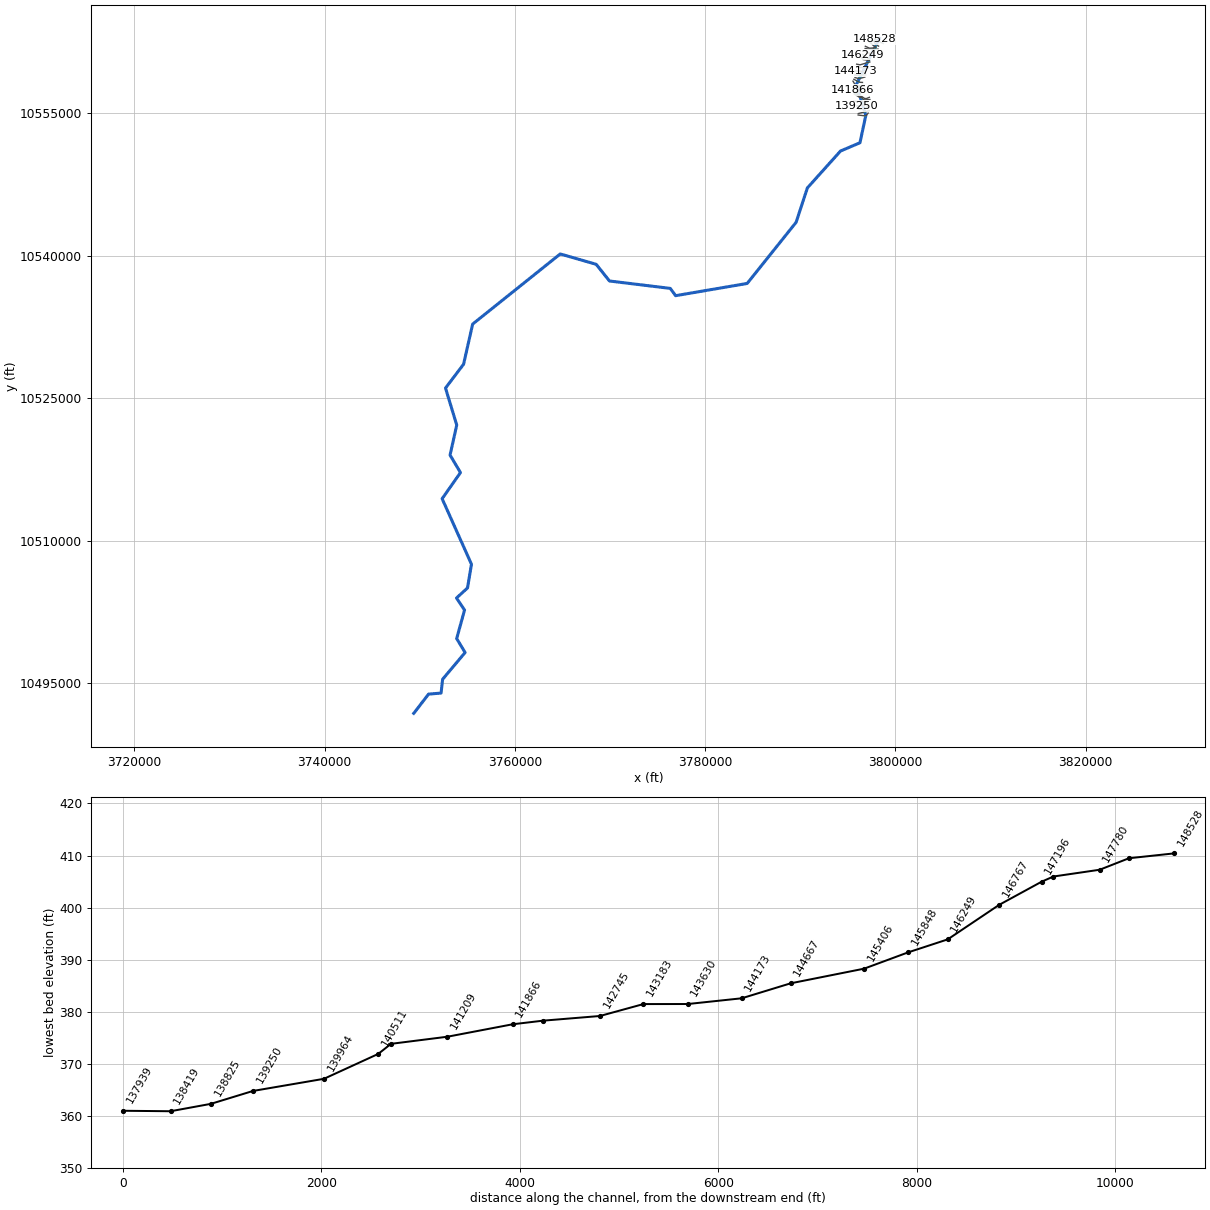
--- BIG ELKHART CREEK.prj (project) ---

Proj Title=BIG ELKHART CREEK Base Level Engineering
Current Plan=p01
Default Exp/Contr=0.3,0.1
English Units
Geom File=g01
Flow File=f01
Plan File=p01
Y Axis Title=Elevation
X Axis Title(PF)=Main Channel Distance
X Axis Title(XS)=Station
BEGIN DESCRIPTION:
BIG ELKHART CREEK
END DESCRIPTION:
DSS Export Rating Curves= 0
DSS Export Rating Curve Sorted= 0
DSS Export Volume Flow Curves= 0
DXF OffsetX= 0
DXF OffsetY= 0
DXF ScaleX= 1
DXF ScaleY= 10

--- BIG ELKHART CREEK.p01 (plan) ---

Plan Title=Multiple Run
Short Identifier=Multiple
Geom File=g01
Flow File=f01
Subcritical Flow
K Sum by GR= 0
Std Step Tol= 0.01
Critical Tol= 0.01
Num of Std Step Trials= 20
Max Error Tol= 0.3
Flow Tol Ratio= 0.001
Split Flow NTrial= 30
Split Flow Tol= 0.02
Split Flow Ratio= 0.02
Log Output Level= 0
Friction Slope Method= 1
Unsteady Friction Slope Method= 2
Unsteady Bridges Friction Slope Method= 1
Parabolic Critical Depth
Global Vel Dist=  1 , 1 , 1
Global Log Level= 0
CheckData=True
Encroach Param= -1, 0, 0, 0
BEGIN DESCRIPTION:
Multiple Run
END DESCRIPTION:

--- BIG ELKHART CREEK.f01 (steady flow) ---

Flow Title=Multiple
Program Version=4.10
Number of Profiles= 7
Profile Names=10-year,25-year,50-year,1pct_min,100-year,1pct_plu,500-year
River Rch & RM=BIG ELKHART CREE,Reach-1         ,148528
     762    1043    1278    1151    1557    2105    2316
River Rch & RM=BIG ELKHART CREE,Reach-1         ,146249
    1126    1573    1954    1781    2409    3257    3674
River Rch & RM=BIG ELKHART CREE,Reach-1         ,144667
    1229    1719    2136    1947    2633    3560    4013
River Rch & RM=BIG ELKHART CREE,Reach-1         ,140511
    1258    1759    2186    1991    2692    3641    4102
River Rch & RM=BIG ELKHART CREE,Reach-1         ,137500
    1778    2526    3173    2918    3946    5337    6131
River Rch & RM=BIG ELKHART CREE,Reach-1         ,136106
    2209    3161    3989    3684    4982    6738    7805
River Rch & RM=BIG ELKHART CREE,Reach-1         ,135641
    2209    3161    3989    3684    4982    6738    7805
River Rch & RM=BIG ELKHART CREE,Reach-1         ,131953
    2525    3623    4579    4233    5725    7743    8987
River Rch & RM=BIG ELKHART CREE,Reach-1         ,131111
    2525    3623    4579    4233    5725    7743    8987
River Rch & RM=BIG ELKHART CREE,Reach-1         ,126332
    2815    4055    5139    4762    6440    8710   10158
River Rch & RM=BIG ELKHART CREE,Reach-1         ,124632
    2866    4121    5217    4827    6528    8828   10265
River Rch & RM=BIG ELKHART CREE,Reach-1         ,120716
    4051    5890    7511    6997    9463   12798   15080
River Rch & RM=BIG ELKHART CREE,Reach-1         ,116578
    4112    5972    7612    7085    9582   12959   15247
River Rch & RM=BIG ELKHART CREE,Reach-1         ,112193
    4125    5988    7630    7100    9602   12985   15266
River Rch & RM=BIG ELKHART CREE,Reach-1         ,111330
    4161    6037    7689    7151    9671   13079   15360
River Rch & RM=BIG ELKHART CREE,Reach-1         ,110575
    4202    6089    7748    7199    9736   13167   15432
River Rch & RM=BIG ELKHART CREE,Reach-1         ,106885
    4497    6526    8311    7728   10451   14134   16589
River Rch & RM=BIG ELKHART CREE,Reach-1         ,105514
    4497    6526    8311    7728   10451   14134   16589
River Rch & RM=BIG ELKHART CREE,Reach-1         ,103344
    4896    7115    9073    8444   11420   15444   18161
River Rch & RM=BIG ELKHART CREE,Reach-1         ,102211
    4896    7115    9073    8444   11420   15444   18161
River Rch & RM=BIG ELKHART CREE,Reach-1         ,98935
    4987    7247    9241    8600   11631   15729   18492
River Rch & RM=BIG ELKHART CREE,Reach-1         ,96231
    5019    7289    9288    8638   11682   15798   18548
River Rch & RM=BIG ELKHART CREE,Reach-1         ,89967
    5057    7337    9345    8686   11747   15886   18629
River Rch & RM=BIG ELKHART CREE,Reach-1         ,85110
    5096    7397    9423    8760   11846   16021   18795
River Rch & RM=BIG ELKHART CREE,Reach-1         ,84703
    7100   10386   13305   12430   16811   22734   26926
River Rch & RM=BIG ELKHART CREE,Reach-1         ,83378
    7100   10386   13305   12430   16811   22734   26926
River Rch & RM=BIG ELKHART CREE,Reach-1         ,83244
    7405   10817   13844   12918   17471   23627   27916
River Rch & RM=BIG ELKHART CREE,Reach-1         ,77144
    7405   10817   13844   12918   17471   23627   27916
River Rch & RM=BIG ELKHART CREE,Reach-1         ,66655
    7481   10920   13968   13027   17618   23826   28120
River Rch & RM=BIG ELKHART CREE,Reach-1         ,63009
    7429   10828   13836   12889   17431   23574   27759
River Rch & RM=BIG ELKHART CREE,Reach-1         ,55052
    7427   10814   13809   12855   17385   23511   27645
River Rch & RM=BIG ELKHART CREE,Reach-1         ,51781
    7454   10838   13825   12856   17387   23514   27588
River Rch & RM=BIG ELKHART CREE,Reach-1         ,50852
    7454   10838   13825   12856   17387   23514   27588
River Rch & RM=BIG ELKHART CREE,Reach-1         ,43918
    7618   11062   14100   13100   17717   23960   28058
River Rch & RM=BIG ELKHART CREE,Reach-1         ,34562
    7637   11082   14117   13107   17726   23972   28036
River Rch & RM=BIG ELKHART CREE,Reach-1         ,33151
    7855   11402   14530   13494   18249   24680   28878
River Rch & RM=BIG ELKHART CREE,Reach-1         ,28830
    7855   11402   14530   13494   18249   24680   28878
River Rch & RM=BIG ELKHART CREE,Reach-1         ,26451
    7838   11369   14480   13440   18177   24582   28731
River Rch & RM=BIG ELKHART CREE,Reach-1         ,21557
   11880   17341   22193   20689   27980   37840   44582
Boundary for River Rch & Prof#=BIG ELKHART CREE,Reach-1         , 1
Up Type= 0
Dn Type= 3
Dn Slope=0.001
Boundary for River Rch & Prof#=BIG ELKHART CREE,Reach-1         , 2
Up Type= 0
Dn Type= 3
Dn Slope=0.001
Boundary for River Rch & Prof#=BIG ELKHART CREE,Reach-1         , 3
Up Type= 0
Dn Type= 3
Dn Slope=0.001
Boundary for River Rch & Prof#=BIG ELKHART CREE,Reach-1         , 4
Up Type= 0
Dn Type= 3
Dn Slope=0.001
Boundary for River Rch & Prof#=BIG ELKHART CREE,Reach-1         , 5
Up Type= 0
Dn Type= 3
Dn Slope=0.001
Boundary for River Rch & Prof#=BIG ELKHART CREE,Reach-1         , 6
Up Type= 0
Dn Type= 3
Dn Slope=0.001
Boundary for River Rch & Prof#=BIG ELKHART CREE,Reach-1         , 7
Up Type= 0
Dn Type= 3
Dn Slope=0.001
DSS Import GetInterval= 0
DSS Import GetPeak= 0
DSS Import FillOption= 0

--- BIG ELKHART CREEK.g01 (geometry) ---

Geom Title=Existing Conditions
Program Version=4.10

River Reach=BIG ELKHART CREE,Reach-1
Reach XY= 30
       3798339.5       10562881.      3795904.25       10558020.
      3796903.75       10554770.        3796288.       10551890.
        3794247.       10551025.      3790758.75       10547137.
      3789576.25       10543521.        3784433.       10537087.
       3776909.5       10535801.      3776348.25       10536567.
      3769957.25       10537345.      3768555.75       10539103.
        3764780.       10540191.      3755574.25       10532813.
       3754616.5       10528582.       3752719.5       10526080.
       3753898.5       10522181.        3753197.       10519027.
       3754290.5       10517185.        3752364.       10514435.
       3755447.5       10507540.      3755029.75       10505041.
       3753871.5       10503984.      3754721.25       10502724.
        3753892.       10499716.      3754778.25       10498251.
        3752414.       10495434.       3752252.5       10493983.
      3750939.25       10493873.      3749376.12     10491846.09

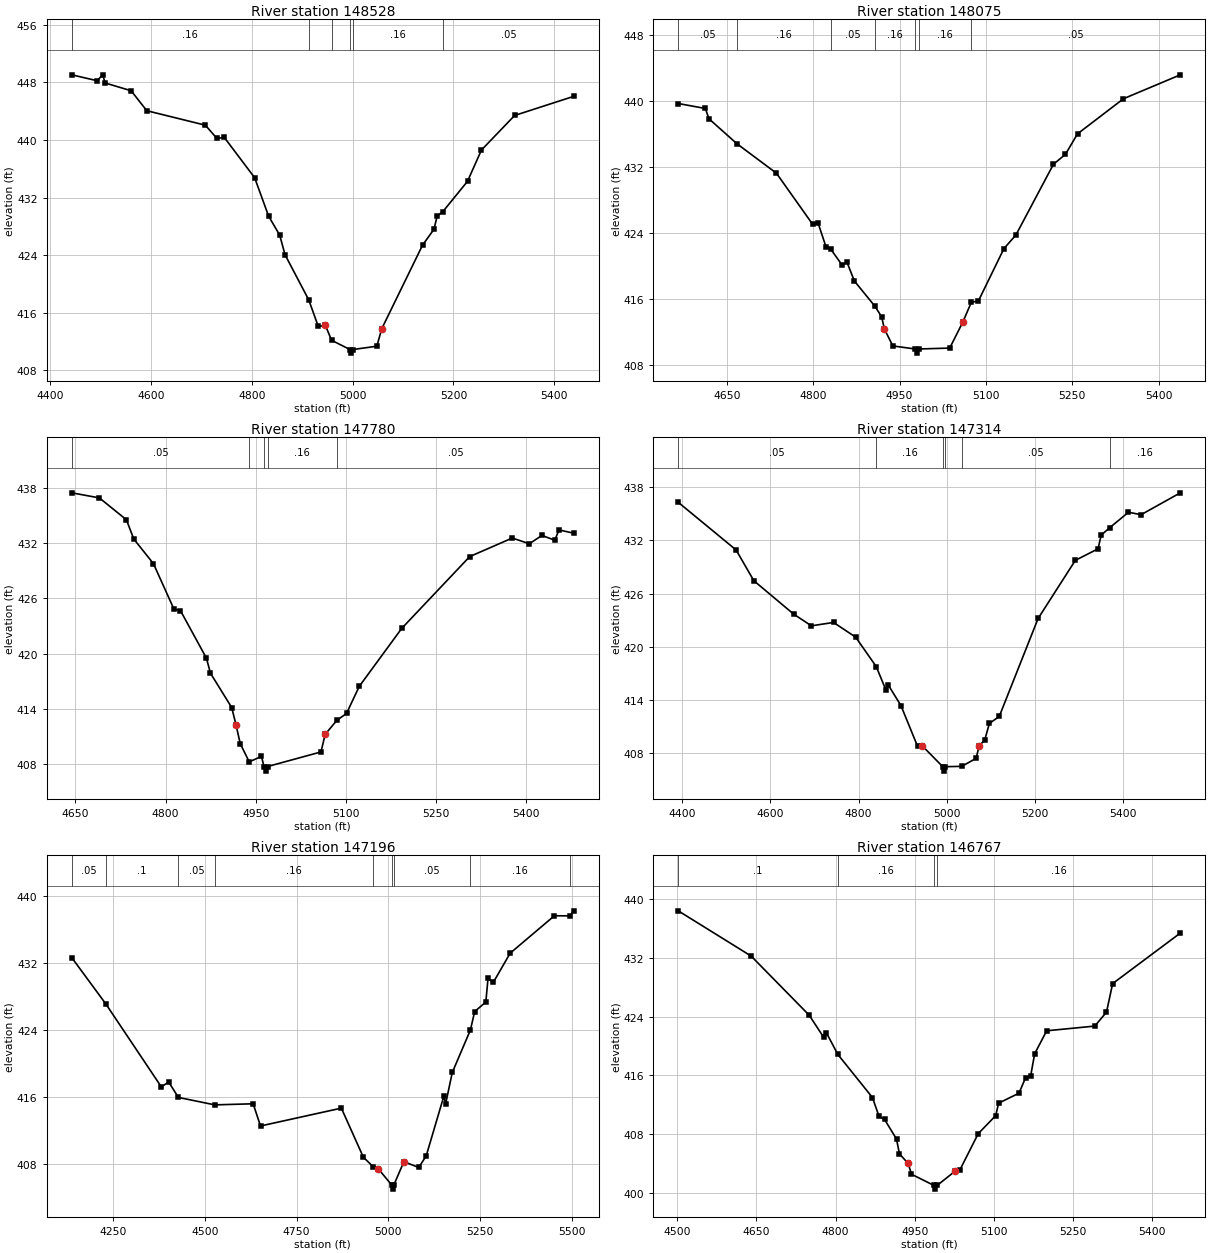
Type RM Length L Ch R = 1 ,148528  ,453,453,453
BEGIN DESCRIPTION:
BIG ELKHART CREEK 198.0
END DESCRIPTION:
XS GIS Cut Line= 2
      3798723.41     10562333.82      3797844.95     10562802.56
#Sta/Elev= 30
    4443  449.03  4493.4  448.21    4504  449.02  4509.6  447.89  4560.7  446.82
  4591.8  444.05    4708  442.04  4730.7  440.21  4745.5  440.34  4805.7  434.75
  4833.3  429.43  4855.4  426.78  4865.9  424.07  4913.1  417.78  4931.8  414.12
    4946  414.25  4958.2   412.2  4994.6  410.91  4997.4  410.41  5000.6  410.91
    5048  411.37  5057.8   413.8  5138.7   425.4  5161.4  427.61  5167.6  429.44
    5179  430.05  5227.8  434.25  5255.4  438.59  5321.3  443.39  5438.7  446.05
#Mann= 6 ,-1 , 0
    4443     .16       0  4913.1     .12       0  4958.2     .16       0
  4994.6     .07       0  5000.6     .16       0    5179     .05       0
Bank Sta=4946,5057.8
XS Rating Curve= 0 ,0
Exp/Cntr=0.3,0.1

Type RM Length L Ch R = 1 ,148075  ,295,295,295
BEGIN DESCRIPTION:
BIG ELKHART CREEK 197.0
END DESCRIPTION:
XS GIS Cut Line= 3
      3798244.24     10562059.52      3797949.12     10562253.95
      3797647.91     10562676.34
#Sta/Elev= 30
  4565.5  439.67  4612.6  439.07  4618.9  437.82  4667.2  434.82  4736.1  431.24
  4799.2  425.04  4808.3  425.24  4822.5  422.27  4830.2  422.08  4850.5   420.1
  4858.4  420.52  4871.5   418.2  4907.2  415.15  4918.9  413.87  4923.6   412.4
  4938.3  410.35  4977.1  409.98  4979.8  409.48  4983.1  409.98  5037.1  410.09
    5060  413.25  5074.6  415.62    5087   415.8  5131.3  422.12  5152.2  423.78
  5217.3  432.32  5238.2  433.53  5259.1     436    5339  440.25  5437.7  443.14
#Mann= 7 ,-1 , 0
  4565.5     .05       0  4667.2     .16       0  4830.2     .05       0
  4907.2     .16       0  4977.1     .07       0  4983.1     .16       0
  5074.6     .05       0
Bank Sta=4923.6,5060
XS Rating Curve= 0 ,0
Exp/Cntr=0.3,0.1

Type RM Length L Ch R = 1 ,147780  ,466,466,466
BEGIN DESCRIPTION:
BIG ELKHART CREEK 196.0
END DESCRIPTION:
XS GIS Cut Line= 3
      3797942.16     10561983.13      3797744.26     10562080.34
      3797300.95     10562506.33
#Sta/Elev= 30
  4643.8  437.44  4689.7  436.89  4734.7  434.52  4746.9  432.44  4779.7  429.76
  4813.8  424.83  4824.6  424.67  4867.8  419.52  4874.5  417.89    4910  414.15
  4916.9  412.32  4924.1  410.25    4939  408.28  4959.4  408.86  4963.6  407.77
  4966.3  407.27  4969.6  407.77  5058.4  409.35  5065.4  411.26  5084.9  412.78
  5100.9  413.52    5122  416.45  5192.7  422.74  5305.9  430.53  5376.7  432.54
    5405  431.92  5426.1  432.82  5447.4   432.3  5454.4  433.42  5479.1  433.06
#Mann= 5 ,-1 , 0
  4643.8     .05       0    4939     .16       0  4963.6     .07       0
  4969.6     .16       0  5084.9     .05       0
Bank Sta=4916.9,5065.4
XS Rating Curve= 0 ,0
Exp/Cntr=0.3,0.1

Type RM Length L Ch R = 1 ,147314  ,118,118,118
BEGIN DESCRIPTION:
Mapping XS 522f206a
END DESCRIPTION:
XS GIS Cut Line= 4
       3797950.3      10561897.8      3797450.32     10561852.66
      3797280.18     10561849.19      3796856.56     10562043.64
#Sta/Elev= 30
  4391.2  436.31  4522.4  430.93  4562.6  427.46  4652.9  423.69  4693.1  422.37
  4743.3  422.75  4793.5  421.09  4840.2  417.76  4861.9  415.14    4867  415.72
  4896.1  413.37  4933.9  408.76  4943.9  408.85  4990.9  406.47  4993.7  405.97
  4996.9  406.47    5034  406.51  5066.5  407.41  5073.6  408.85    5086  409.47
  5096.6  411.35    5119  412.14  5207.1   423.2  5291.5  429.76    5343  431.06
  5350.1  432.61  5369.1  433.43    5412  435.19  5440.5  434.91  5529.5  437.38
#Mann= 6 ,-1 , 0
  4391.2     .05       0  4840.2     .16       0  4990.9     .07       0
  4996.9     .16       0    5034     .05       0  5369.1     .16       0
Bank Sta=4943.9,5073.6
XS Rating Curve= 0 ,0
Exp/Cntr=0.3,0.1

Type RM Length L Ch R = 1 ,147196  ,429,429,429
BEGIN DESCRIPTION:
BIG ELKHART CREEK 195.0
END DESCRIPTION:
XS GIS Cut Line= 4
      3798193.39     10561745.02      3797450.32     10561734.61
      3797301.01     10561734.61       3796833.4     10561814.27
#Sta/Elev= 30
  4138.1  432.62  4230.7   427.1  4381.9  417.19  4401.9  417.77  4428.4  415.93
  4527.3  415.04  4631.9  415.17  4651.9  412.52    4872  414.65    4932  408.78
  4958.4  407.67    4972  407.43    5009  405.48  5011.7  404.98    5015  405.48
  5042.1  408.25  5082.7  407.57    5103  408.95  5150.9  416.07  5155.9  415.17
    5174  418.91  5223.3  423.98  5234.9  426.18  5265.3  427.32  5271.3  430.17
  5285.6  429.66  5331.5  433.15  5451.9  437.62    5494  437.61  5504.9  438.21
#Mann= 9 ,-1 , 0
  4138.1     .05       0  4230.7      .1       0  4428.4     .05       0
  4527.3     .16       0  4958.4     .05       0    5009     .04       0
    5015     .05       0  5223.3     .16       0    5494     .05       0
Bank Sta=4972,5042.1
XS Rating Curve= 0 ,0
Exp/Cntr=0.3,0.1

Type RM Length L Ch R = 1 ,146767  ,518,518,518
BEGIN DESCRIPTION:
BIG ELKHART CREEK 194.0
END DESCRIPTION:
XS GIS Cut Line= 3
       3797657.5     10561281.72      3797299.82     10561299.09
      3796763.07     10561551.88
#Sta/Elev= 30
  4501.8  438.43  4639.9  432.27    4750  424.21  4777.3  421.21  4782.3  421.85
  4804.3  418.86  4869.9  412.99  4882.2  410.44  4892.7  410.02  4915.4  407.34
    4921  405.32  4937.5  404.02  4943.8  402.55  4986.4  401.02  4989.2  400.52
  4992.4  401.02  5025.9  402.94    5035  403.06  5070.2  408.07  5103.3  410.53
  5108.9  412.23  5147.5  413.59    5160   415.7  5169.6  415.93  5177.2  418.96
    5200  422.09  5291.2  422.73  5313.3  424.63    5325  428.52  5453.2   435.4
#Mann= 4 ,-1 , 0
  4501.8      .1       0  4804.3     .16       0  4986.4     .07       0
  4992.4     .16       0
Bank Sta=4937.5,5025.9
XS Rating Curve= 0 ,0
Exp/Cntr=0.3,0.1

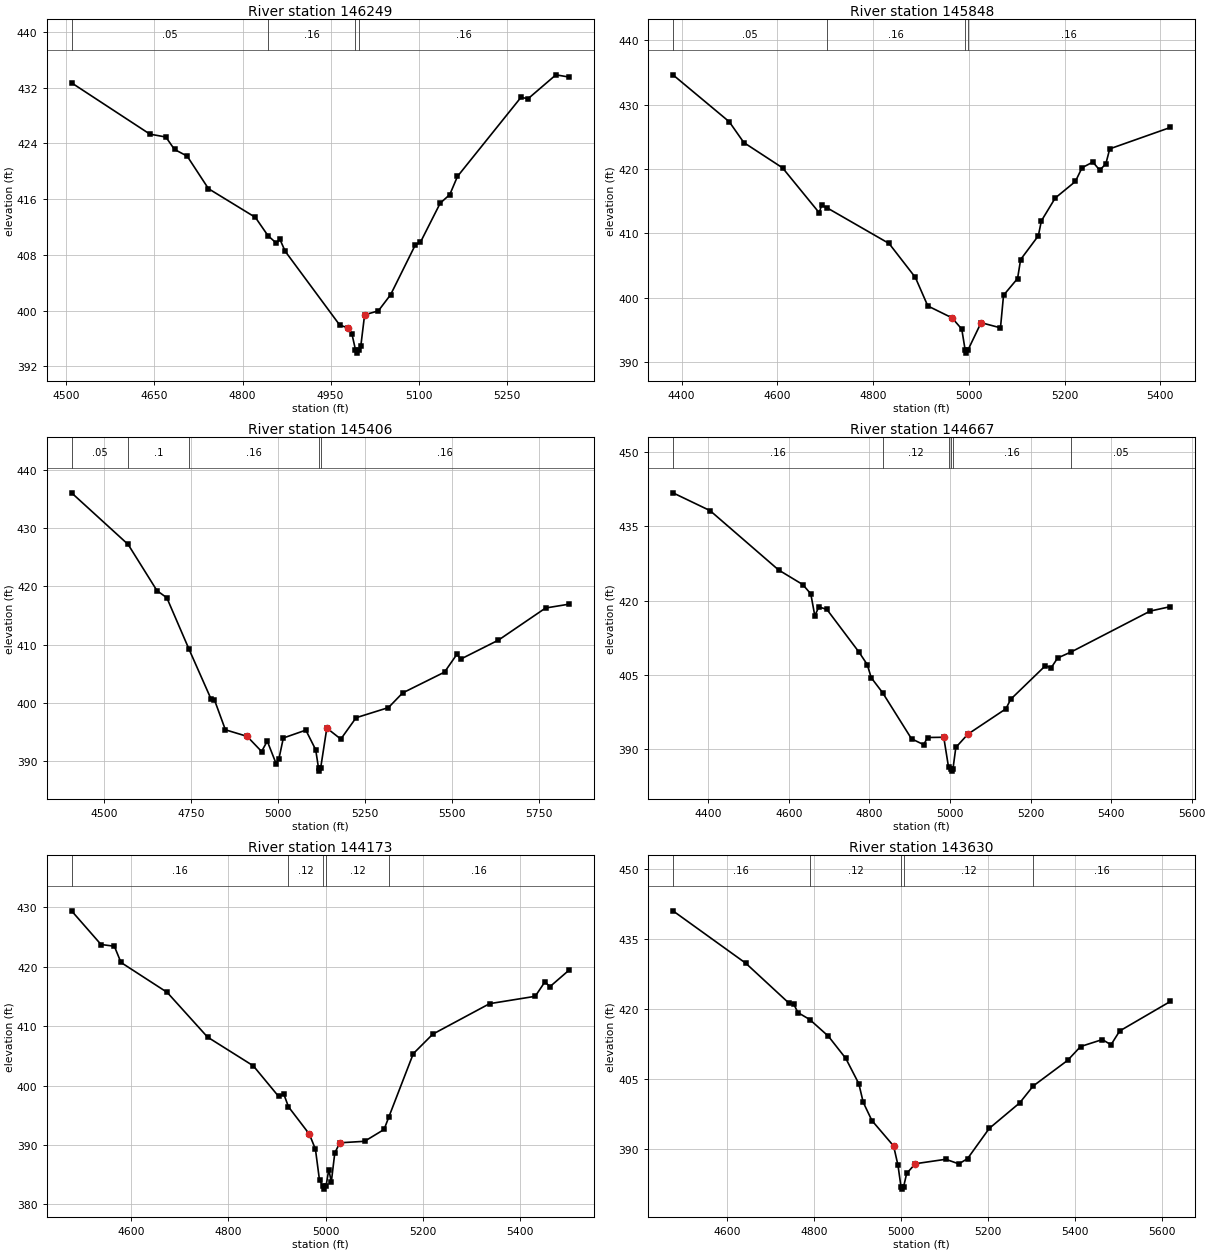
Type RM Length L Ch R = 1 ,146249  ,401,401,401
BEGIN DESCRIPTION:
BIG ELKHART CREEK 193.0
END DESCRIPTION:
XS GIS Cut Line= 3
      3797282.42     10560698.42      3796761.62     10561052.56
       3796581.1     10561174.06
#Sta/Elev= 30
  4508.7  432.71  4642.2  425.34  4669.3  424.93  4684.1  423.14  4705.6  422.19
  4741.9  417.51  4821.8  413.39  4843.4  410.75  4857.7  409.68  4863.7  410.22
  4872.6  408.52  4965.5  397.92  4980.4  397.49  4986.4  396.61  4992.3  394.39
  4995.1  393.89  4998.3  394.39  5001.4  394.88  5007.9  399.39  5031.3  399.96
  5052.2  402.28  5094.2  409.42  5103.1  409.83  5136.7  415.43    5153  416.66
  5166.1  419.27  5274.1  430.61  5286.5  430.44  5333.8  433.86  5356.1  433.54
#Mann= 4 ,-1 , 0
  4508.7     .05       0  4843.4     .16       0  4992.3     .07       0
  4998.3     .16       0
Bank Sta=4980.4,5007.9
XS Rating Curve= 0 ,0
Exp/Cntr=0.3,0.1

Type RM Length L Ch R = 1 ,145848  ,442,442,442
BEGIN DESCRIPTION:
BIG ELKHART CREEK 192.0
END DESCRIPTION:
XS GIS Cut Line= 3
      3797285.89     10560549.09       3796601.9     10560653.25
      3796387.53      10560926.4
#Sta/Elev= 30
  4382.1  434.61  4499.7  427.32  4530.1  424.09    4611  420.16  4687.6  413.18
  4692.6  414.37  4704.2  413.94  4833.5  408.41  4888.4  403.14  4914.4  398.71
    4965  396.86  4985.3  395.12  4992.4  391.88  4995.1  391.38  4998.4  391.88
  5025.7  396.11  5066.2  395.31  5072.6  400.37  5101.9  402.97  5108.3  405.92
  5145.3  409.61  5151.6  411.92  5180.5  415.47  5222.6  418.04  5236.6  420.18
  5259.2  421.06  5273.5   419.8  5286.3  420.78  5294.4  423.11  5421.2  426.44
#Mann= 4 ,-1 , 0
  4382.1     .05       0  4704.2     .16       0  4992.4     .07       0
  4998.4     .16       0
Bank Sta=4965,5025.7
XS Rating Curve= 0 ,0
Exp/Cntr=0.3,0.1

Type RM Length L Ch R = 1 ,145406  ,739,739,739
BEGIN DESCRIPTION:
BIG ELKHART CREEK 191.0
END DESCRIPTION:
XS GIS Cut Line= 3
      3797324.11     10560392.83      3796299.82     10560094.23
      3795943.41     10560163.43
#Sta/Elev= 30
  4406.3  436.05  4568.9  427.19  4651.9  419.25  4680.2  418.03  4743.5  409.26
  4806.8  400.71  4817.2  400.48  4848.5  395.36    4911  394.23  4952.6  391.63
  4968.9  393.41  4994.3  389.56  5002.4  390.37  5015.1  393.95  5079.8   395.3
  5108.1  391.93  5116.3  388.76    5119  388.26  5122.3  388.76  5140.1  395.65
  5180.3  393.76  5224.2  397.43  5317.2  399.17  5358.1  401.69  5478.4  405.26
  5514.2  408.34  5524.4  407.48  5633.5  410.76  5768.9  416.27  5836.3  416.93
#Mann= 5 ,-1 , 0
  4406.3     .05       0  4568.9      .1       0  4743.5     .16       0
  5116.3     .07       0  5122.3     .16       0
Bank Sta=4911,5140.1
XS Rating Curve= 0 ,0
Exp/Cntr=0.3,0.1

Type RM Length L Ch R = 1 ,144667  ,494,494,494
BEGIN DESCRIPTION:
BIG ELKHART CREEK 190.0
END DESCRIPTION:
XS GIS Cut Line= 3
      3797181.76      10559785.2      3796355.37     10559802.56
      3795955.31     10559885.33
#Sta/Elev= 30
  4312.2  441.82  4404.4  438.21  4574.4   426.2  4634.4  423.24  4654.4  421.36
  4664.4  416.91  4674.4  418.72  4694.4   418.2  4774.5  409.51  4794.5  407.04
  4804.5  404.36  4832.5  401.36  4904.5     392  4934.5  390.81  4944.5  392.26
  4984.5  392.31  4996.4  386.24  5001.5  385.95  5004.3  385.45  5007.5  385.95
  5014.5  390.25  5044.5  392.94  5138.8  398.07  5150.8  400.01  5236.6  406.78
  5251.2  406.38  5267.2  408.36  5301.6  409.62  5497.1  417.87  5547.3  418.77
#Mann= 6 ,-1 , 0
  4312.2     .16       0  4832.5     .12       0  4996.4     .16       0
  5001.5     .07       0  5007.5     .16       0  5301.6     .05       0
Bank Sta=4984.5,5044.5
XS Rating Curve= 0 ,0
Exp/Cntr=0.3,0.1

Type RM Length L Ch R = 1 ,144173  ,543,543,543
BEGIN DESCRIPTION:
BIG ELKHART CREEK 189.0
END DESCRIPTION:
XS GIS Cut Line= 3
      3796806.74     10559288.68       3796265.1     10559455.34
      3795810.27     10559424.09
#Sta/Elev= 30
  4477.8  429.42  4538.4  423.75  4565.8  423.46  4579.4  420.73  4674.4  415.69
  4757.3  408.17  4851.5  403.32  4903.3  398.19  4914.2  398.55  4923.7  396.43
  4966.5  391.84  4979.1  389.31  4987.5  384.07  4994.9  383.07  4997.7  382.57
  5000.9  383.07  5006.6  385.86  5011.8  383.78  5018.9  388.65  5029.3  390.37
  5080.1  390.62  5120.2  392.61  5129.9  394.69  5180.3  405.38  5220.4  408.66
  5337.1  413.79  5430.9  415.03  5450.9  417.47    5461  416.64  5500.4  419.43
#Mann= 5 ,-1 , 0
  4477.8     .16       0  4923.7     .12       0  4994.9     .07       0
  5000.9     .12       0  5129.9     .16       0
Bank Sta=4966.5,5029.3
XS Rating Curve= 0 ,0
Exp/Cntr=0.3,0.1

Type RM Length L Ch R = 1 ,143630  ,447,447,447
BEGIN DESCRIPTION:
BIG ELKHART CREEK 188.0
END DESCRIPTION:
XS GIS Cut Line= 2
      3796897.08      10559035.2      3795752.93     10559010.93
#Sta/Elev= 30
  4475.7  440.96  4643.2  429.76  4743.2  421.17  4753.2  421.08  4763.2  419.21
  4790.4  417.72  4833.2  414.16  4873.3  409.41  4903.3     404  4913.3  400.05
  4933.3  396.14  4983.3  390.69  4993.3  386.59  5000.3  381.97    5003  381.47
  5006.3  381.97  5013.3  384.82  5033.3   386.9  5103.3  387.85  5133.3  386.87
  5153.3  387.98  5203.3  394.45  5273.3   399.9  5304.3  403.51  5383.4  408.98
  5413.4  411.95  5463.4  413.44  5483.4  412.33  5503.4  415.28  5620.1   421.6
#Mann= 5 ,-1 , 0
  4475.7     .16       0  4790.4     .12       0  5000.3     .07       0
  5006.3     .12       0  5304.3     .16       0
Bank Sta=4983.3,5033.3
XS Rating Curve= 0 ,0
Exp/Cntr=0.3,0.1

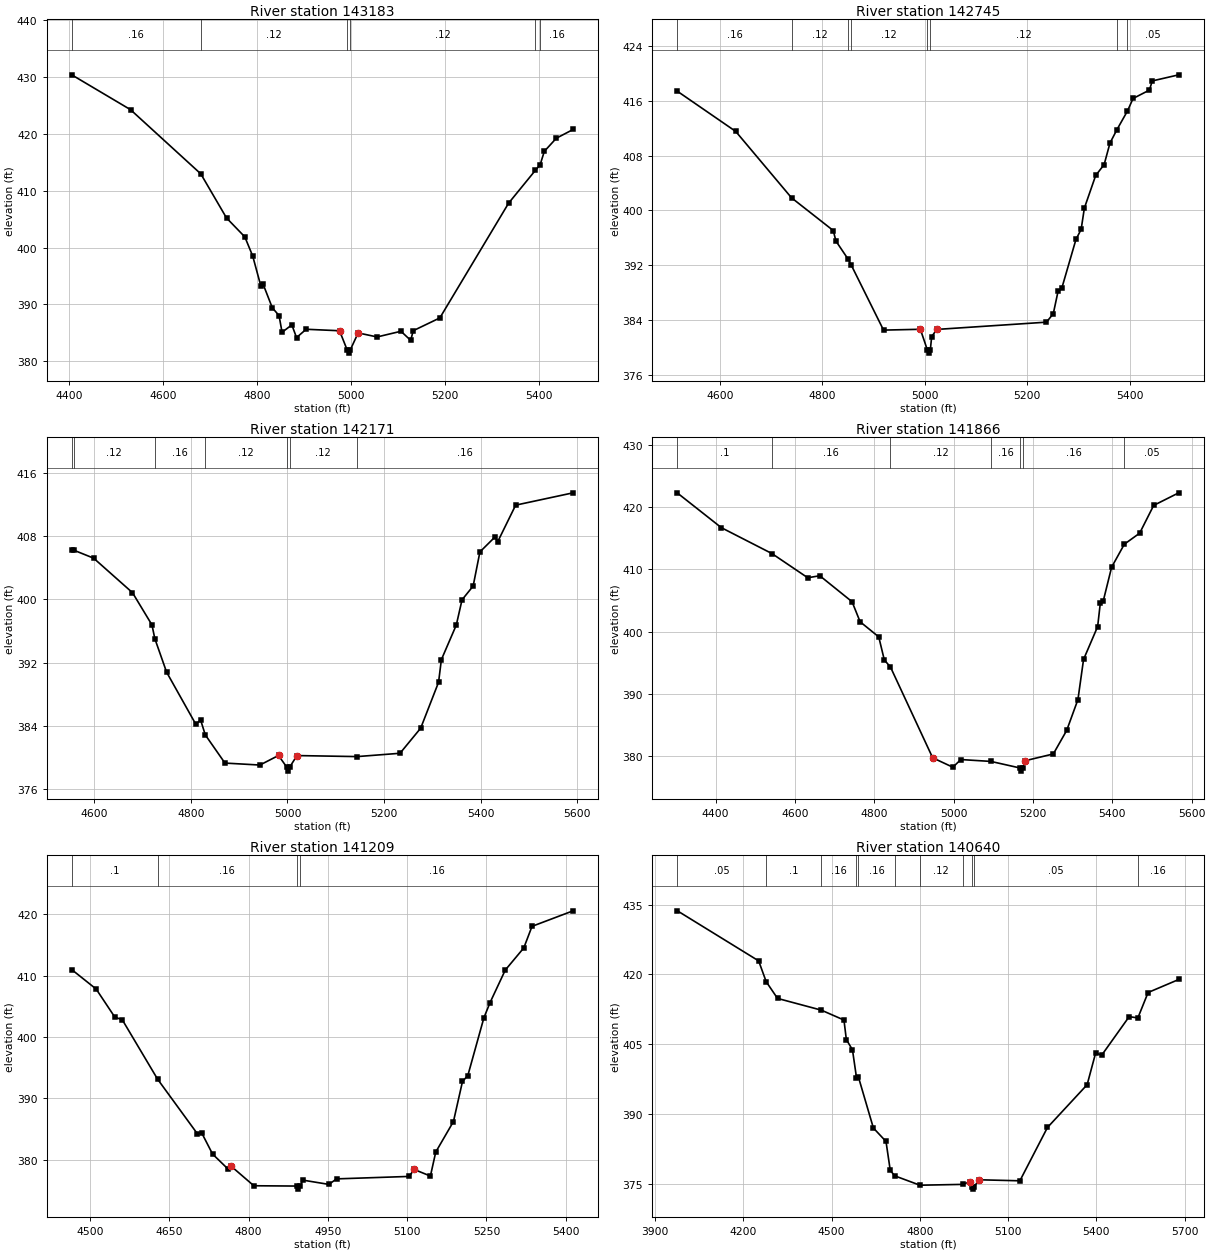
Type RM Length L Ch R = 1 ,143183  ,438,438,438
BEGIN DESCRIPTION:
BIG ELKHART CREEK 187.0
END DESCRIPTION:
XS GIS Cut Line= 4
      3796799.87     10558806.04      3796338.01     10558674.09
       3796140.1     10558653.25      3795765.14     10558750.47
#Sta/Elev= 30
  4405.6  430.33  4530.7  424.21  4680.2  412.94  4734.9   405.2  4773.9  401.87
  4790.7   398.5  4807.7  393.32  4812.9  393.55  4832.3  389.43  4846.7  388.05
  4853.1  385.12  4873.9  386.42  4883.9  384.19  4904.4  385.65  4975.4  385.39
  4991.9  381.96  4994.7  381.46  4997.9  381.96    5015  385.01  5055.3   384.3
  5106.1   385.3  5126.8   383.7  5132.2   385.4  5188.8  387.64  5335.1  407.79
  5392.3  413.58  5402.1  414.51  5411.1  416.89  5436.7   419.2  5472.3  420.73
#Mann= 6 ,-1 , 0
  4405.6     .16       0  4680.2     .12       0  4991.9     .07       0
  4997.9     .12       0  5392.3     .05       0  5402.1     .16       0
Bank Sta=4975.4,5015
XS Rating Curve= 0 ,0
Exp/Cntr=0.3,0.1

Type RM Length L Ch R = 1 ,142745  ,574,574,574
BEGIN DESCRIPTION:
BIG ELKHART CREEK 186.0
END DESCRIPTION:
XS GIS Cut Line= 3
      3796553.29     10558240.06      3796244.26     10558260.89
      3795650.49     10558569.93
#Sta/Elev= 30
  4516.7  417.39  4630.6  411.53  4739.6  401.84  4821.1  397.06  4826.3  395.53
  4849.4  392.96  4856.3  392.01  4919.3  382.53  4991.2  382.65  5004.7  379.67
  5007.5  379.17  5010.7  379.67  5013.3  381.58  5023.3  382.63  5237.5  383.69
  5250.8  384.93  5260.1  388.19  5267.3  388.62  5295.1  395.77  5305.2  397.23
  5311.5  400.34  5333.6   405.1  5350.1  406.69  5361.5  409.83  5375.1  411.79
  5395.7  414.52  5406.6  416.34  5438.5  417.56  5444.1   418.9  5495.8  419.79
#Mann= 8 ,-1 , 0
  4516.7     .16       0  4739.6     .12       0  4849.4     .16       0
  4856.3     .12       0  5004.7     .07       0  5010.7     .12       0
  5375.1     .16       0  5395.7     .05       0
Bank Sta=4991.2,5023.3
XS Rating Curve= 0 ,0
Exp/Cntr=0.3,0.1

Type RM Length L Ch R = 1 ,142171  ,305,305,305
BEGIN DESCRIPTION:
BIG ELKHART CREEK 185.0
END DESCRIPTION:
XS GIS Cut Line= 3
      3796334.53     10557868.53      3795820.65     10557931.03
      3795553.96     10558377.83
#Sta/Elev= 30
  4553.3  406.24  4557.5  406.24  4598.6  405.23  4679.1  400.86  4719.4  396.78
  4725.3  395.05  4749.7   390.8  4810.1  384.21  4820.2  384.73  4829.8  382.86
  4870.5  379.29  4942.9  379.04  4981.4  380.25  4998.5  378.77  5001.2  378.27
  5004.5  378.77  5019.6  380.24  5144.1  380.11    5233  380.53  5275.8  383.71
  5312.8  389.52  5318.6  392.38  5349.5  396.76  5361.4  399.96  5384.4   401.7
  5398.4  406.02  5429.6  407.91  5435.4  407.33  5472.4  411.94  5591.3   413.5
#Mann= 7 ,-1 , 0
  4553.3     .16       0  4557.5     .12       0  4725.3     .16       0
  4829.8     .12       0  4998.5     .07       0  5004.5     .12       0
  5144.1     .16       0
Bank Sta=4981.4,5019.6
XS Rating Curve= 0 ,0
Exp/Cntr=0.3,0.1

Type RM Length L Ch R = 1 ,141866  ,657,657,657
BEGIN DESCRIPTION:
BIG ELKHART CREEK 184.0
END DESCRIPTION:
XS GIS Cut Line= 3
      3796682.93     10557824.88       3795752.4     10557658.22
      3795523.92     10557436.66
#Sta/Elev= 30
  4303.9  422.25  4414.8  416.68  4542.3  412.52  4632.4  408.64  4662.8  408.96
  4744.1  404.79  4764.4  401.57  4811.4  399.14  4825.4  395.44    4841  394.29
  4947.3  379.72  4998.1  378.21  5018.4  379.44    5094  379.14  5167.8  378.08
  5170.5  377.58  5173.8  378.08    5181  379.26  5251.4  380.34  5285.1  384.12
  5313.4  389.07  5327.6  395.52  5363.1   400.8    5370  404.66  5377.2   404.9
  5398.3  410.33  5430.4  414.03    5469   415.8  5504.3  420.26  5567.5  422.28
#Mann= 7 ,-1 , 0
  4303.9      .1       0  4542.3     .16       0    4841     .12       0
    5094     .16       0  5167.8     .07       0  5173.8     .16       0
  5430.4     .05       0
Bank Sta=4947.3,5181
XS Rating Curve= 0 ,0
Exp/Cntr=0.3,0.1

Type RM Length L Ch R = 1 ,141209  ,569,569,569
BEGIN DESCRIPTION:
BIG ELKHART CREEK 183.0
END DESCRIPTION:
XS GIS Cut Line= 3
      3796549.79     10557615.04      3796088.01     10557233.11
      3795742.73     10557181.32
#Sta/Elev= 30
  4465.6  410.97  4511.8   407.8    4547  403.24  4561.3  402.78  4628.1   393.1
  4703.3  384.21  4711.2   384.4    4732  380.91  4760.6  378.52  4767.1  378.93
  4810.1  375.74  4891.8  375.69  4894.5  375.19  4897.8  375.69  4902.6  376.66
  4952.1  375.96  4966.5  376.86  5103.7  377.26  5113.5  378.39  5144.1  377.32
  5154.2  381.23  5187.7  386.21  5204.8  392.74  5214.9   393.7  5245.3  403.12
  5256.8  405.57  5285.7  410.89  5320.8  414.51  5336.3  418.02    5414  420.55
#Mann= 4 ,-1 , 0
  4465.6      .1       0  4628.1     .16       0  4891.8     .07       0
  4897.8     .16       0
Bank Sta=4767.1,5113.5
XS Rating Curve= 0 ,0
Exp/Cntr=0.3,0.1

Type RM Length L Ch R = 1 ,140640  ,129,129,129
BEGIN DESCRIPTION:
BIG ELKHART CREEK 182.0
END DESCRIPTION:
XS GIS Cut Line= 6
      3797276.71     10556675.58      3796964.21     10556540.16
      3796783.65     10556550.58      3796457.26      10556772.8
      3796196.84     10556831.83      3795790.58     10557147.81
#Sta/Elev= 30
    3976  433.65  4252.2  422.89  4277.8  418.42  4316.4  414.82  4465.2   412.3
  4542.2  410.17  4550.3  405.98  4571.1  403.77  4584.8  397.81  4591.2  397.96
  4642.2  386.96  4685.1  384.07  4699.5  377.89  4714.2  376.69  4800.5  374.66
  4945.3  374.84  4971.5  375.45  4978.5  374.32  4981.2  373.82  4984.5  374.32
  5001.5  375.83  5140.2  375.61  5233.9  387.07  5368.8  396.27  5397.7  403.09
  5418.5  402.63  5511.7   410.9  5541.3  410.63    5576  416.09  5680.2  418.89
#Mann= 11 ,-1 , 0
    3976     .05       0  4277.8      .1       0  4465.2     .16       0
  4584.8     .05       0  4591.2     .16       0  4714.2     .05       0
  4800.5     .12       0  4945.3     .05       0  4978.5     .04       0
  4984.5     .05       0  5541.3     .16       0
Bank Sta=4971.5,5001.5
XS Rating Curve= 0 ,0
Exp/Cntr=0.3,0.1

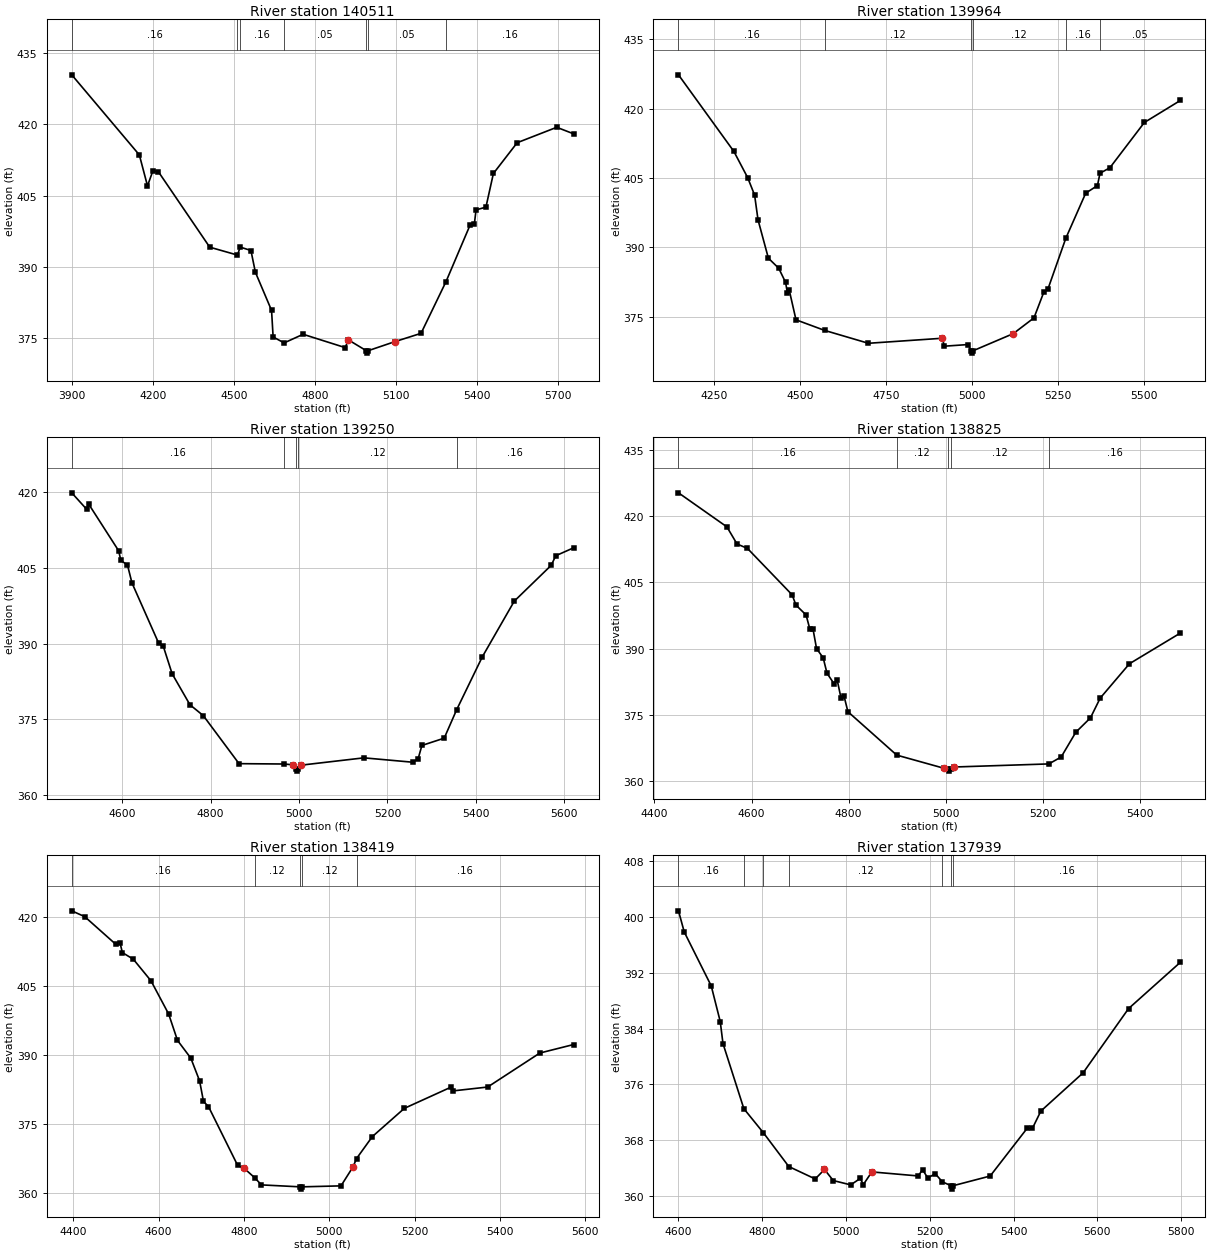
Type RM Length L Ch R = 1 ,140511  ,547,547,547
BEGIN DESCRIPTION:
BIG ELKHART CREEK 181.0
END DESCRIPTION:
XS GIS Cut Line= 6
      3797339.24     10556439.47      3796759.34      10556397.8
      3796603.09     10556481.13      3796509.34     10556651.27
      3796228.09     10556692.94      3795697.35     10557015.54
#Sta/Elev= 30
  3899.6  430.38  4149.9  413.54    4180  407.04    4200  410.19  4220.1  410.03
  4410.5  394.15  4513.2  392.49  4523.3  394.17  4563.1  393.45  4579.4   388.9
  4639.4  380.86  4645.2  375.28    4686  374.03  4756.3  375.84  4912.7  373.03
  4922.8   374.7  4990.6  372.38  4993.3  371.88  4996.6  372.38  5094.7  374.27
  5192.9  376.04  5285.2  386.89  5375.3  398.91  5390.2  398.97  5396.6  401.99
  5433.2  402.57  5460.8  409.64  5548.9  416.11  5695.3  419.35  5757.8  417.98
#Mann= 7 ,-1 , 0
  3899.6     .16       0  4513.2     .05       0  4523.3     .16       0
    4686     .05       0  4990.6     .04       0  4996.6     .05       0
  5285.2     .16       0
Bank Sta=4922.8,5094.7
XS Rating Curve= 0 ,0
Exp/Cntr=0.3,0.1

Type RM Length L Ch R = 1 ,139964  ,714,714,714
BEGIN DESCRIPTION:
BIG ELKHART CREEK 180.0
END DESCRIPTION:
XS GIS Cut Line= 2
      3797060.21     10556174.09      3795605.36     10556271.31
#Sta/Elev= 30
    4147  427.31    4308  410.73    4348  405.07  4368.1  401.31  4378.1  395.94
  4408.2  387.64  4438.2  385.47  4458.3  382.39  4463.4  380.11  4468.4  380.86
  4488.4  374.31  4571.5  372.02  4698.8  369.23  4913.8  370.32  4919.3   368.6
  4989.5  368.96  4996.5   367.6  4999.2   367.1  5002.5   367.6  5119.8  371.32
  5179.9  374.73  5209.1  380.42    5220  380.87  5272.4  391.95  5330.2  401.71
  5364.3  403.35  5371.7  406.02  5400.4   407.2  5500.6     417  5605.1  421.76
#Mann= 6 ,-1 , 0
    4147     .16       0  4571.5     .12       0  4996.5     .07       0
  5002.5     .12       0  5272.4     .16       0  5371.7     .05       0
Bank Sta=4913.8,5119.8
XS Rating Curve= 0 ,0
Exp/Cntr=0.3,0.1

Type RM Length L Ch R = 1 ,139250  ,425,425,425
BEGIN DESCRIPTION:
BIG ELKHART CREEK 179.0
END DESCRIPTION:
XS GIS Cut Line= 2
      3797084.53      10555910.2      3795959.56     10555757.42
#Sta/Elev= 30
  4485.8  419.88  4519.5  416.62  4524.6  417.58  4591.7  408.43    4597  406.48
  4611.9  405.57    4622  402.04  4682.5  390.09  4692.6  389.58  4712.8  384.06
  4753.2  377.91  4783.4  375.76  4864.2  366.25  4965.9  366.18  4985.3  366.03
  4992.4  365.27  4995.1  364.77  4998.4  365.27  5005.4  365.96  5146.7   367.4
  5257.7  366.53  5269.5  367.25  5277.9  369.85  5328.4   371.3  5356.4   376.9
  5414.5  387.39  5486.9  398.43  5570.6  405.54  5580.7  407.42  5621.1  408.99
#Mann= 5 ,-1 , 0
  4485.8     .16       0  4965.9     .12       0  4992.4     .07       0
  4998.4     .12       0  5356.4     .16       0
Bank Sta=4985.3,5005.4
XS Rating Curve= 0 ,0
Exp/Cntr=0.3,0.1

Type RM Length L Ch R = 1 ,138825  ,406,406,406
BEGIN DESCRIPTION:
BIG ELKHART CREEK 178.0
END DESCRIPTION:
XS GIS Cut Line= 3
      3797119.25     10555750.46       3796789.4     10555479.64
      3796185.23     10555431.03
#Sta/Elev= 30
  4449.7  425.21  4549.4  417.51  4570.2  413.64  4591.6  412.65  4683.6  402.15
  4691.5  399.83  4712.3   397.6  4720.2  394.36  4726.7  394.33  4733.9  389.98
  4747.5  387.92  4755.4  384.42  4769.7  382.08  4776.2  382.96  4784.1  378.88
  4790.5  379.23  4798.4  375.73  4898.9  365.91  4996.7  362.92  5003.7  362.79
  5006.4  362.29  5009.7  362.79  5016.7  363.22    5212  363.92  5237.4  365.49
  5267.5  371.08  5297.6  374.33  5317.7   378.8  5377.9  386.57  5482.6   393.5
#Mann= 5 ,-1 , 0
  4449.7     .16       0  4898.9     .12       0  5003.7     .07       0
  5009.7     .12       0    5212     .16       0
Bank Sta=4996.7,5016.7
XS Rating Curve= 0 ,0
Exp/Cntr=0.3,0.1

Type RM Length L Ch R = 1 ,138419  ,480,480,480
BEGIN DESCRIPTION:
BIG ELKHART CREEK 177.0
END DESCRIPTION:
XS GIS Cut Line= 2
      3797248.93     10555265.86      3796113.17     10554962.41
#Sta/Elev= 30
  4396.7  421.44  4427.1  420.17  4499.5  414.18  4509.9  414.41  4515.3  412.35
  4540.9  410.91  4582.3  406.21  4623.7  398.98  4644.4  393.24  4675.6  389.38
  4696.2  384.43  4705.3  379.95  4716.9  378.85  4785.4  366.02  4799.7  365.47
  4825.1  363.36  4841.1  361.79  4931.2  361.37    4934  360.87  4937.2  361.37
  5027.4  361.58  5055.6  365.72  5063.8  367.52  5100.8   372.3  5175.8  378.45
  5285.7  383.09  5290.8  382.26    5371  383.09  5493.2  390.49  5572.3  392.34
#Mann= 5 ,-1 , 0
  4396.7     .16       0  4825.1     .12       0  4931.2     .07       0
  4937.2     .12       0  5063.8     .16       0
Bank Sta=4799.7,5055.6
XS Rating Curve= 0 ,0
Exp/Cntr=0.3,0.1

Type RM Length L Ch R = 1 ,137939  ,439,439,439
BEGIN DESCRIPTION:
BIG ELKHART CREEK 176.0
END DESCRIPTION:
XS GIS Cut Line= 3
      3797149.63     10555010.21      3796899.61     10554710.19
      3796099.58     10554810.19
#Sta/Elev= 30
  4600.9  400.89  4614.6  397.86    4679  390.12  4700.5     385    4707  381.85
  4756.8   372.5  4803.6  369.03    4864   364.2    4927  362.42  4949.1  363.78
    4970  362.19  5011.6  361.57  5034.3  362.49  5041.8  361.62    5062  363.43
  5172.8  362.85  5182.9  363.76  5195.5  362.55  5213.2  363.18  5230.1  362.01
  5250.5  361.46  5253.2  360.96  5256.5  361.46  5344.2  362.84  5432.3  369.68
  5444.9  369.67  5465.1  372.16  5565.9  377.65  5674.2  386.86  5797.7   393.5
#Mann= 7 ,-1 , 0
  4600.9     .16       0  4756.8     .12       0  4803.6     .16       0
    4864     .12       0  5230.1     .16       0  5250.5     .07       0
  5256.5     .16       0
Bank Sta=4949.1,5062
XS Rating Curve= 0 ,0
Exp/Cntr=0.3,0.1