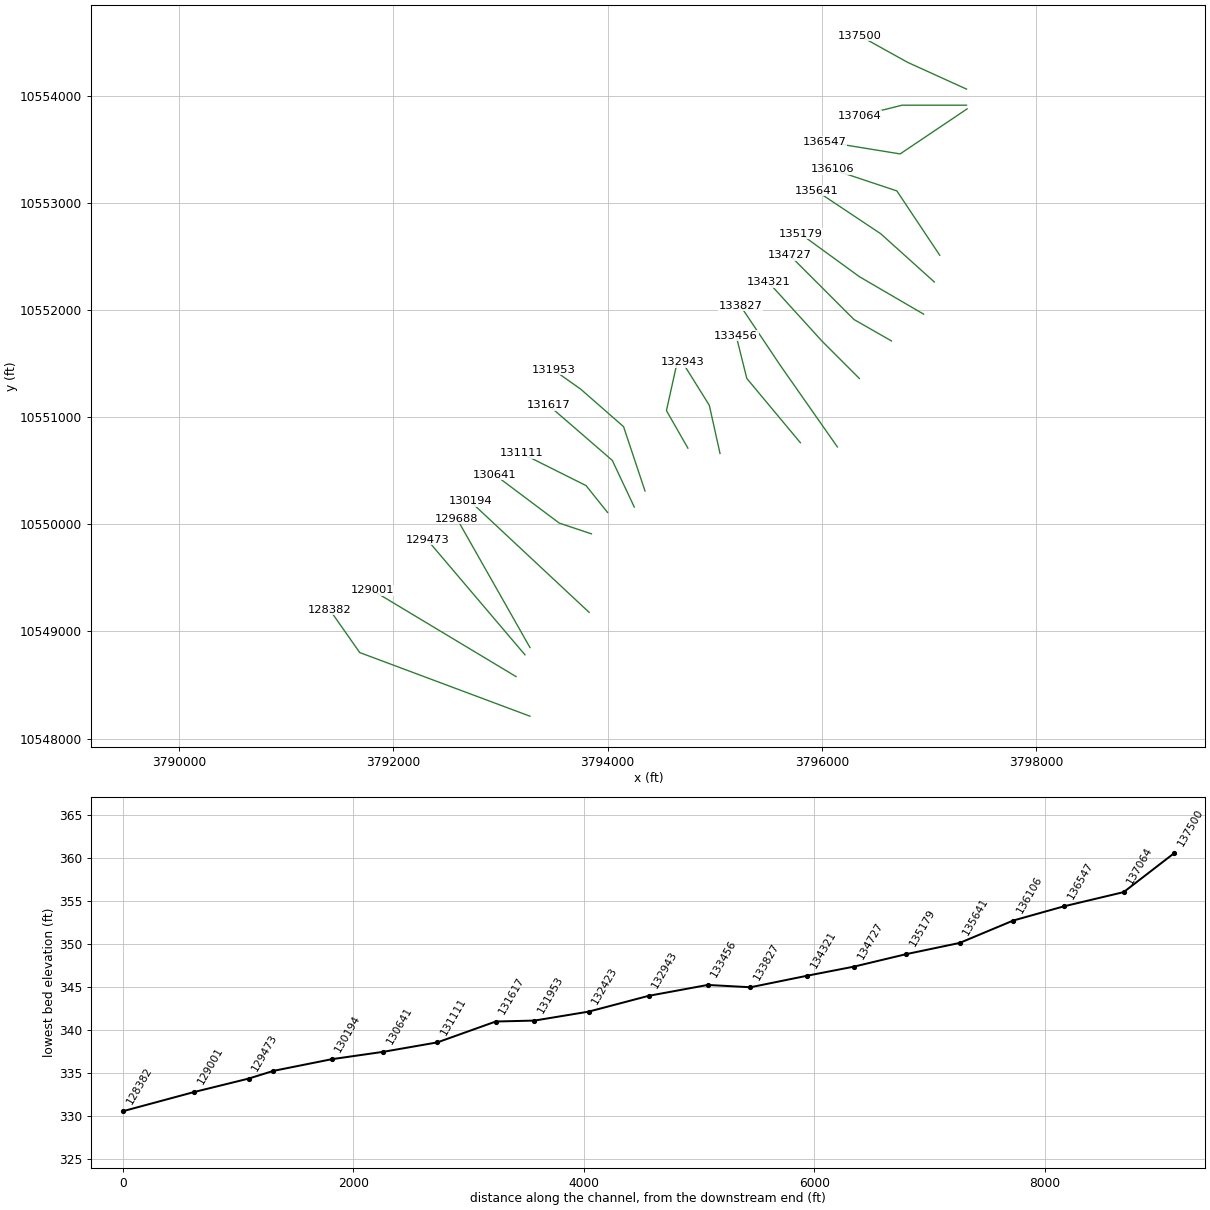
HEC-RAS study BIG ELKHART CREEK.prj: BIG ELKHART CREEK Base Level Engineering

--- BIG ELKHART CREEK.g01 (geometry) --- (continued)

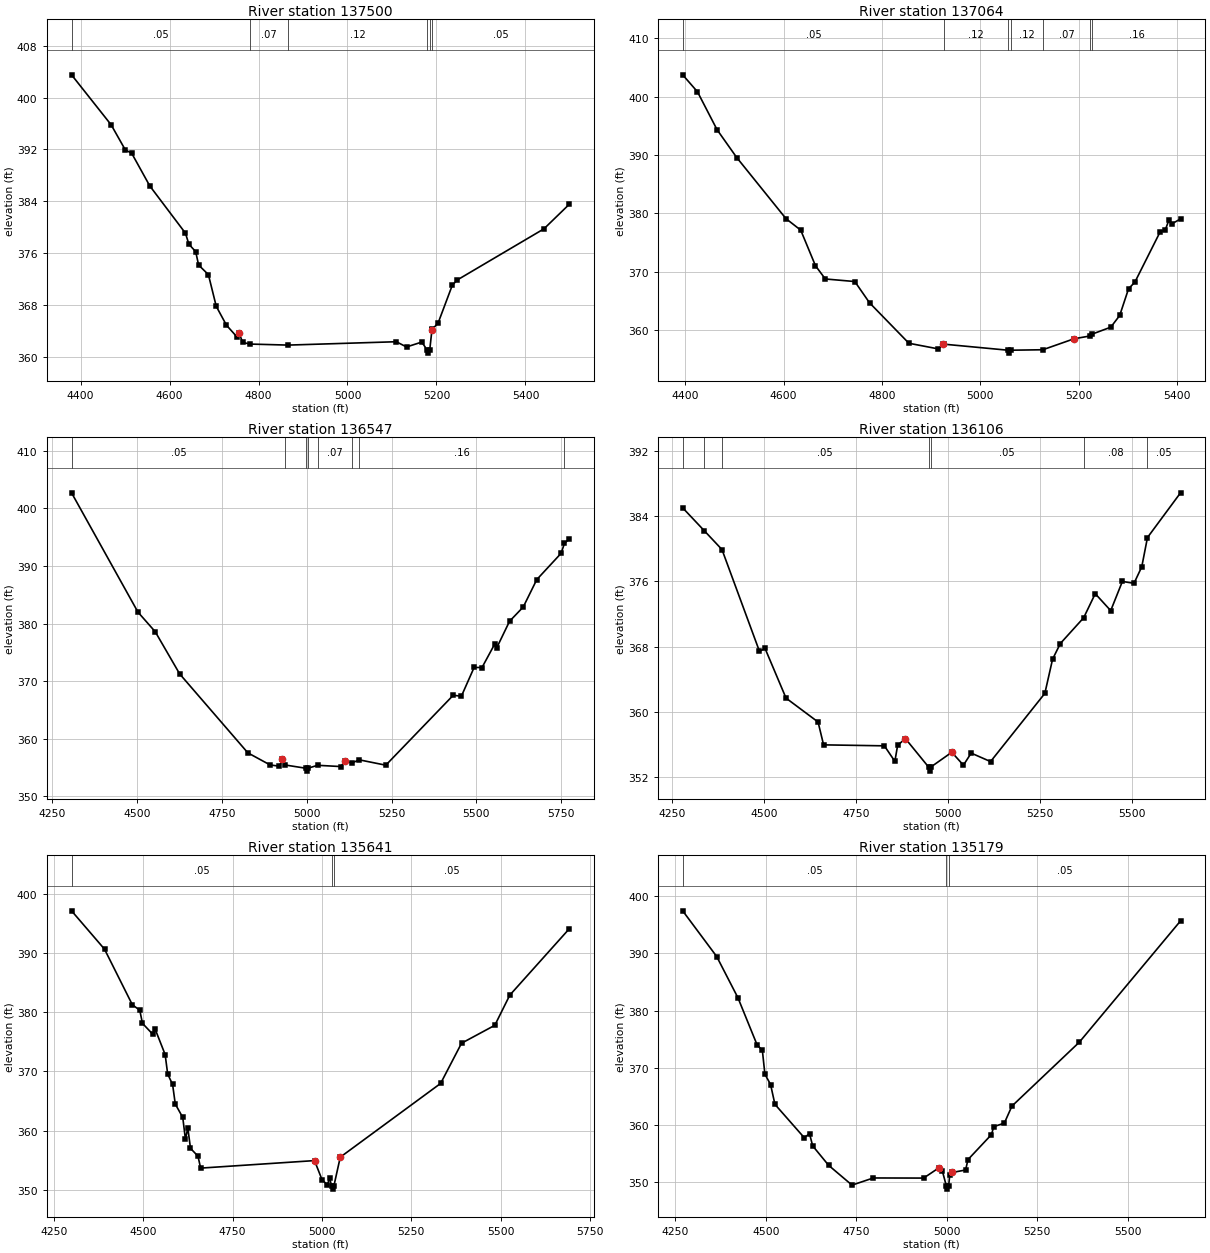
Type RM Length L Ch R = 1 ,137500  ,436,436,436
BEGIN DESCRIPTION:
BIG ELKHART CREEK 175.0
END DESCRIPTION:
XS GIS Cut Line= 3
      3797349.64     10554060.18      3796799.61     10554310.19
      3796349.58     10554560.21
#Sta/Elev= 30
  4379.8  403.52  4468.8   395.8  4500.7  391.92  4514.9  391.42  4555.6  386.37
  4635.8  379.07  4643.5  377.37  4658.8  376.22  4665.4  374.15  4687.4  372.67
    4705  367.78    4728  364.86  4751.1  363.09  4756.6  363.64  4764.3   362.2
  4781.2  361.95  4866.5  361.79  5109.8  362.31  5132.7   361.5    5167  362.26
  5178.9  361.05  5181.6  360.55  5184.9  361.05  5189.9  364.17  5190.4  364.22
  5203.6  365.18  5235.7  371.05  5247.1  371.86  5441.6  379.74  5498.8  383.55
#Mann= 6 ,-1 , 0
  4379.8     .05       0  4781.2     .07       0  4866.5     .12       0
  5178.9     .07       0  5184.9     .12       0  5190.4     .05       0
Bank Sta=4756.6,5189.9
XS Rating Curve= 0 ,0
Exp/Cntr=0.3,0.1

Type RM Length L Ch R = 1 ,137064  ,517,517,517
BEGIN DESCRIPTION:
BIG ELKHART CREEK 174.0
END DESCRIPTION:
XS GIS Cut Line= 3
      3797349.56     10553910.19      3796749.61     10553910.19
      3796349.57     10553810.18
#Sta/Elev= 30
  4394.7  403.74  4424.7  400.84  4464.7  394.32  4504.7  389.55  4604.7  379.09
  4634.7  377.12  4664.7  371.02  4684.7  368.75  4744.7  368.31  4774.7  364.66
  4854.7  357.73  4914.7  356.76  4924.7   357.6  4926.5  357.57  5056.1  356.54
  5058.8  356.04  5062.1  356.54    5127  356.62  5190.5   358.5  5223.6  358.99
    5228  359.32  5265.2  360.49  5283.3  362.49  5301.3  367.07  5314.2  368.21
  5365.7  376.85    5376  377.17  5383.8  378.92  5388.9  378.17    5407  379.05
#Mann= 7 ,-1 , 0
  4394.7     .05       0  4926.5     .12       0  5056.1     .07       0
  5062.1     .12       0    5127     .07       0  5223.6     .12       0
    5228     .16       0
Bank Sta=4924.7,5190.5
XS Rating Curve= 0 ,0
Exp/Cntr=0.3,0.1

Type RM Length L Ch R = 1 ,136547  ,441,441,441
BEGIN DESCRIPTION:
BIG ELKHART CREEK 173.0
END DESCRIPTION:
XS GIS Cut Line= 3
      3797355.34     10553875.45      3796730.37     10553455.34
      3796025.48     10553569.93
#Sta/Elev= 30
    4307  402.68  4502.7  381.98  4553.6  378.58  4625.6  371.26  4826.6  357.56
  4892.3  355.46  4919.7  355.25  4928.4  356.43    4937  355.45  4997.6  354.89
  5000.4  354.39  5003.6  354.89  5032.1   355.4  5101.3  355.18  5111.5  356.14
  5134.2  355.83  5154.9  356.35  5233.1  355.42  5431.8  367.55  5455.9  367.39
  5493.4  372.38  5516.7  372.37  5554.9  376.53    5560  375.78  5597.8  380.39
  5638.3  382.88  5678.1  387.63  5749.7  392.18  5759.7  393.92  5774.2  394.69
#Mann= 8 ,-1 , 0
    4307     .05       0    4937     .12       0  4997.6     .07       0
  5003.6     .12       0  5032.1     .07       0  5134.2     .12       0
  5154.9     .16       0  5759.7     .08       0
Bank Sta=4928.4,5111.5
XS Rating Curve= 0 ,0
Exp/Cntr=0.3,0.1

Type RM Length L Ch R = 1 ,136106  ,465,465,465
BEGIN DESCRIPTION:
BIG ELKHART CREEK 172.0
END DESCRIPTION:
XS GIS Cut Line= 3
      3797099.62     10552510.17      3796699.61     10553110.19
       3796099.6     10553310.19
#Sta/Elev= 30
  4279.1     385  4337.7   382.2  4385.9  379.89  4487.9  367.41    4503  367.77
  4560.1  361.68  4647.2  358.75  4662.2  355.95  4827.5  355.83    4856  353.93
  4863.5  355.89  4884.6  356.72  4947.7  353.23  4950.4  352.73  4953.7  353.23
  5010.8  355.04  5042.4  353.46  5063.5  354.94  5116.2   353.9  5263.8  362.26
  5284.8  366.45  5305.9  368.37  5369.4  371.53  5400.8  374.48  5442.9   372.4
  5474.6  375.98  5506.2  375.75  5527.3  377.77  5542.8  381.36  5632.7  386.84
#Mann= 7 ,-1 , 0
  4279.1     .05       0  4337.7     .08       0  4385.9     .05       0
  4947.7     .03       0  4953.7     .05       0  5369.4     .08       0
  5542.8     .05       0
Bank Sta=4884.6,5010.8
XS Rating Curve= 0 ,0
Exp/Cntr=0.3,0.1

Type RM Length L Ch R = 1 ,135641  ,462,462,462
BEGIN DESCRIPTION:
BIG ELKHART CREEK 171.0
END DESCRIPTION:
XS GIS Cut Line= 3
      3797049.62     10552260.18      3796549.61     10552710.19
      3795949.61     10553110.19
#Sta/Elev= 30
  4298.9  397.14  4391.2  390.66    4469  381.28  4489.9  380.34  4497.4  378.13
  4525.8  376.32  4532.5  377.22  4560.9  372.86    4568  369.57  4581.8   367.8
  4589.3  364.49  4610.2  362.24  4617.7  358.56  4624.4  360.44  4631.9  357.01
  4652.8  355.69  4660.3  353.67  4979.1  354.94  5000.1  351.72  5015.2  350.83
  5021.2  351.99  5027.2  350.62  5029.9  350.12  5033.2  350.62  5051.2  355.52
  5332.2  367.98  5390.7  374.77  5483.9   377.8  5525.9   382.9  5692.7  394.13
#Mann= 3 ,-1 , 0
  4298.9     .05       0  5027.2     .03       0  5033.2     .05       0
Bank Sta=4979.1,5051.2
XS Rating Curve= 0 ,0
Exp/Cntr=0.3,0.1

Type RM Length L Ch R = 1 ,135179  ,452,452,452
BEGIN DESCRIPTION:
BIG ELKHART CREEK 170.0
END DESCRIPTION:
XS GIS Cut Line= 3
      3796949.62     10551960.18      3796349.61     10552310.19
      3795799.62     10552710.18
#Sta/Elev= 30
  4270.8  397.43  4364.7  389.45  4423.4  382.24  4476.3  374.01  4490.8  373.06
  4497.8   368.9  4513.5  367.09  4525.5  363.63  4606.5   357.8    4621  358.51
  4629.7  356.38  4673.9  352.97  4738.4  349.52  4797.2  350.77  4936.1  350.75
    4979  352.57  4987.5  352.06  4999.1  349.32  5001.9  348.82  5005.1  349.32
  5008.3  351.32  5014.9  351.73    5052  352.16  5058.6  353.98  5123.5  358.35
  5129.7  359.73    5159  360.35  5179.9  363.32  5366.1  374.49  5645.5  395.67
#Mann= 3 ,-1 , 0
  4270.8     .05       0  4999.1     .03       0  5005.1     .05       0
Bank Sta=4979,5014.9
XS Rating Curve= 0 ,0
Exp/Cntr=0.3,0.1

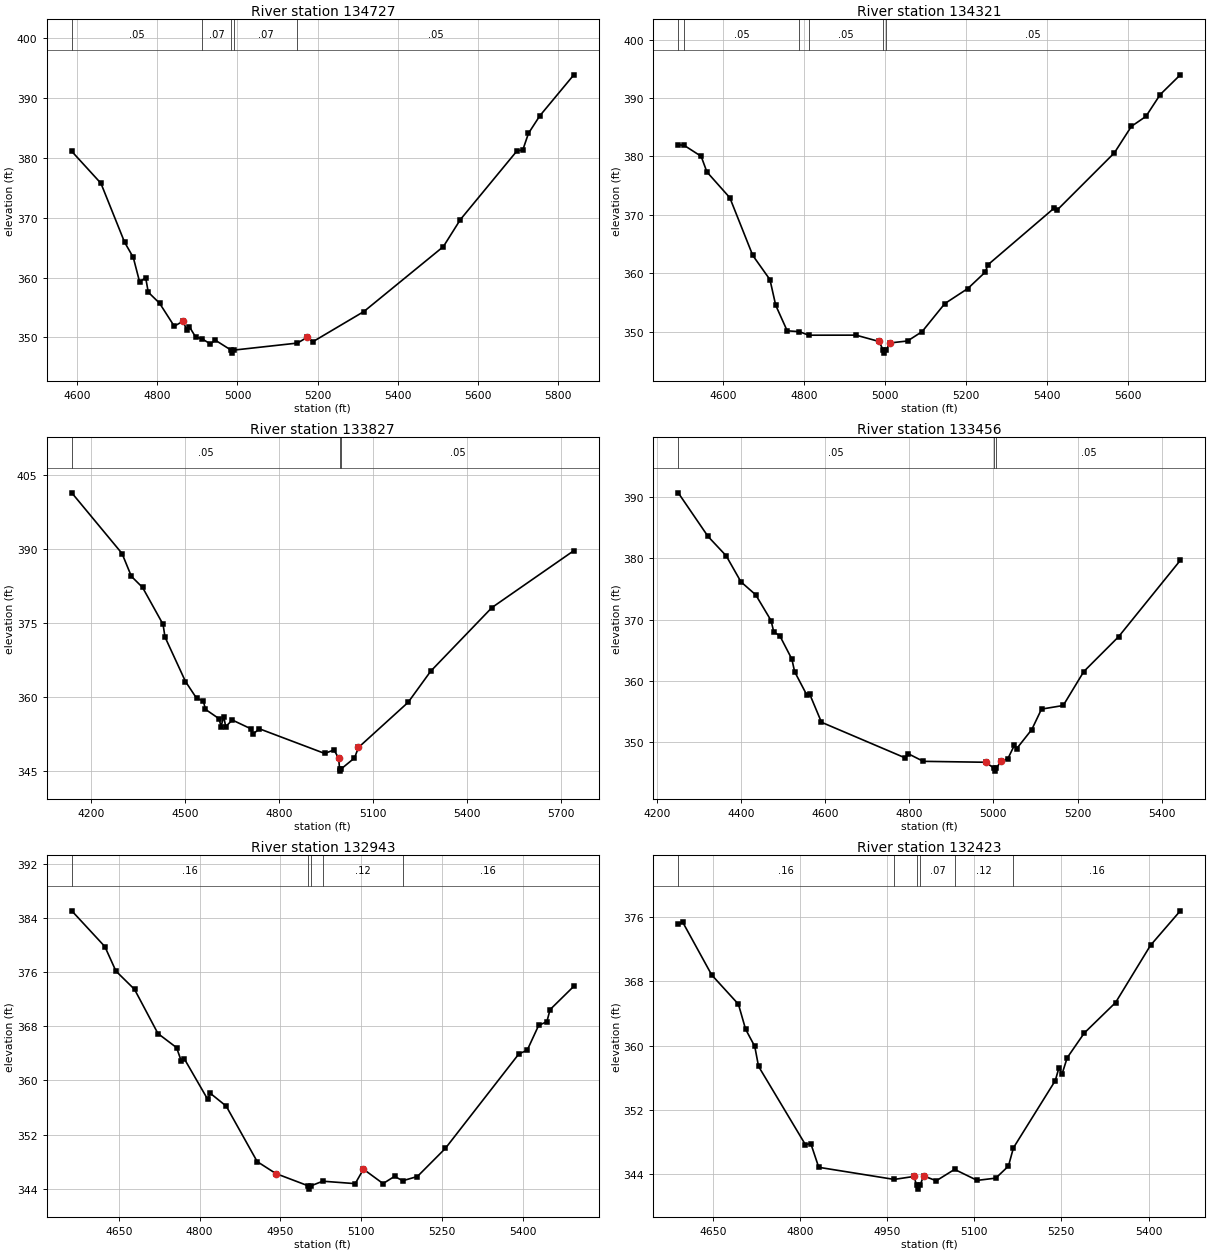
Type RM Length L Ch R = 1 ,134727  ,406,406,406
BEGIN DESCRIPTION:
BIG ELKHART CREEK 169.0
END DESCRIPTION:
XS GIS Cut Line= 3
      3796649.58      10551710.2      3796299.61     10551910.19
      3795699.62     10552510.18
#Sta/Elev= 30
    4587  381.11  4659.7  375.77  4718.7  365.91  4740.3  363.38  4756.1  359.28
  4771.2  359.98  4777.7  357.56  4805.8  355.72  4842.5  351.87  4864.1   352.7
  4874.2  351.17  4879.9  351.81  4895.8  350.06  4911.8  349.76  4932.5  348.91
  4944.7  349.54  4984.2  347.87    4987  347.37  4990.2  347.87  5149.4  349.05
  5173.9  350.01  5188.1  349.28  5315.3  354.33  5513.3  365.18  5555.8  369.71
  5697.2  381.22  5711.3  381.33  5725.5  384.13  5753.8  387.06  5838.6  393.91
#Mann= 5 ,-1 , 0
    4587     .05       0  4911.8     .07       0  4984.2     .07       0
  4990.2     .07       0  5149.4     .05       0
Bank Sta=4864.1,5173.9
XS Rating Curve= 0 ,0
Exp/Cntr=0.3,0.1

Type RM Length L Ch R = 1 ,134321  ,494,494,494
BEGIN DESCRIPTION:
BIG ELKHART CREEK 168.0
END DESCRIPTION:
XS GIS Cut Line= 3
      3796349.57     10551360.22      3795999.61     10551710.19
      3795499.63     10552260.17
#Sta/Elev= 30
  4489.9  381.97  4503.9  381.91  4546.4  380.01  4560.6  377.33  4617.1  372.92
  4673.7  363.04  4716.1  358.89  4730.3   354.5  4758.6  350.13  4788.8  349.99
  4811.2  349.38  4928.3  349.39  4984.8  348.31  4995.7  346.81  4998.4  346.31
  5001.7  346.81  5012.9  348.06  5055.4  348.39  5091.3  349.99  5147.3  354.79
  5204.1  357.37  5246.7  360.16  5254.1  361.46    5417  371.14  5423.7  370.76
  5565.6  380.61  5607.5  385.14  5643.3  386.84  5678.5  390.58  5728.1  393.96
#Mann= 6 ,-1 , 0
  4489.9     .08       0  4503.9     .05       0  4788.8     .07       0
  4811.2     .05       0  4995.7     .03       0  5001.7     .05       0
Bank Sta=4984.8,5012.9
XS Rating Curve= 0 ,0
Exp/Cntr=0.3,0.1

Type RM Length L Ch R = 1 ,133827  ,371,371,371
BEGIN DESCRIPTION:
BIG ELKHART CREEK 167.0
END DESCRIPTION:
XS GIS Cut Line= 3
      3796144.74     10550721.23      3795616.95     10551474.72
      3795238.48     10552040.68
#Sta/Elev= 30
  4139.3  401.46  4299.6  389.14  4329.3  384.51    4365  382.25  4430.4  374.75
  4436.5  372.19  4501.9  363.15  4537.6  359.72  4558.6  359.25  4565.4  357.51
  4609.1  355.59  4615.2  354.01  4623.9  356.05    4630  353.98    4651  355.34
  4710.2  353.56  4716.3  352.42  4737.3  353.56  4945.6  348.55  4975.3  349.26
  4990.1  347.61  4993.2  345.46  4995.9  344.96  4999.2  345.46  5040.7  347.63
  5053.4  349.77  5211.8  358.93  5283.9  365.26    5479  378.17  5740.1  389.72
#Mann= 3 ,-1 , 0
  4139.3     .05       0  4993.2     .03       0  4999.2     .05       0
Bank Sta=4990.1,5053.4
XS Rating Curve= 0 ,0
Exp/Cntr=0.3,0.1

Type RM Length L Ch R = 1 ,133456  ,513,513,513
BEGIN DESCRIPTION:
BIG ELKHART CREEK 166.0
END DESCRIPTION:
XS GIS Cut Line= 3
      3795799.58     10550760.22      3795299.61     10551360.19
      3795199.61     10551760.19
#Sta/Elev= 30
  4250.9  390.73  4321.8  383.59  4364.8  380.44  4399.9  376.18  4435.1  374.05
  4471.5  369.85    4478  367.98  4492.3  367.36    4521  363.54  4527.5  361.49
  4556.1  357.73  4563.3  357.83  4591.3  353.22  4790.4  347.39  4797.6  348.07
  4833.4  346.83  4981.8  346.68  5000.9  345.73  5003.6  345.23  5006.9  345.73
  5018.2  346.87  5034.5  347.29  5049.9  349.47  5055.1  348.89  5091.2  352.03
  5114.3  355.37  5165.9  355.96  5214.8  361.51  5297.3  367.19  5444.2  379.69
#Mann= 3 ,-1 , 0
  4250.9     .05       0  5000.9     .03       0  5006.9     .05       0
Bank Sta=4981.8,5018.2
XS Rating Curve= 0 ,0
Exp/Cntr=0.3,0.1

Type RM Length L Ch R = 1 ,132943  ,520,520,520
BEGIN DESCRIPTION:
BIG ELKHART CREEK 165.0
END DESCRIPTION:
XS GIS Cut Line= 3
      3795049.62     10550660.15      3794949.61     10551110.19
      3794699.61     10551510.18
#Sta/Elev= 30
  4562.4  385.03  4623.9  379.75  4644.4  376.14    4679  373.44  4722.5  366.92
  4757.1  364.84    4766  362.82  4771.2  363.23  4814.7  357.24  4819.8   358.1
  4849.3  356.21  4906.9  348.02  4941.5  346.26  5001.2  344.46    5004  343.96
  5007.2  344.46  5028.6  345.13  5088.9  344.77 5104.27   346.9  5140.7  344.78
    5162  345.84  5177.2   345.2  5204.4  345.82  5256.3  349.96  5393.1  363.93
  5408.4  364.45  5429.7  368.12    5445  368.67  5450.9  370.45  5495.1   373.9
#Mann= 5 ,-1 , 0
  4562.4     .16       0  5001.2     .07       0  5007.2     .16       0
  5028.6     .12       0  5177.2     .16       0
Bank Sta=4941.5,5104.27
XS Rating Curve= 0 ,0
Exp/Cntr=0.3,0.1

Type RM Length L Ch R = 1 ,132423  ,470,470,470
BEGIN DESCRIPTION:
BIG ELKHART CREEK 164.0
END DESCRIPTION:
XS GIS Cut Line= 3
      3794749.59     10550710.22      3794549.61     10551060.19
      3794649.62     10551510.23
#Sta/Elev= 30
  4590.6   375.2  4598.5  375.36  4648.2  368.81  4694.2  365.16  4706.5  362.05
  4722.3  359.91  4728.8  357.42  4809.4  347.67  4818.8  347.79  4832.4  344.84
  4962.2  343.33  4996.2   343.7  5000.9  342.62  5003.7  342.12  5006.9  342.62
  5012.9  343.77  5034.7  343.16  5066.2  344.58  5105.1  343.21  5137.1  343.49
  5158.9  344.99  5167.5  347.27  5239.5  355.64  5245.9  357.26  5251.1  356.45
    5260  358.49  5289.5  361.58  5343.3  365.37  5403.4   372.5  5454.7   376.8
#Mann= 6 ,-1 , 0
  4590.6     .16       0  4962.2     .07       0  5000.9     .07       0
  5006.9     .07       0  5066.2     .12       0  5167.5     .16       0
Bank Sta=4996.2,5012.9
XS Rating Curve= 0 ,0
Exp/Cntr=0.3,0.1

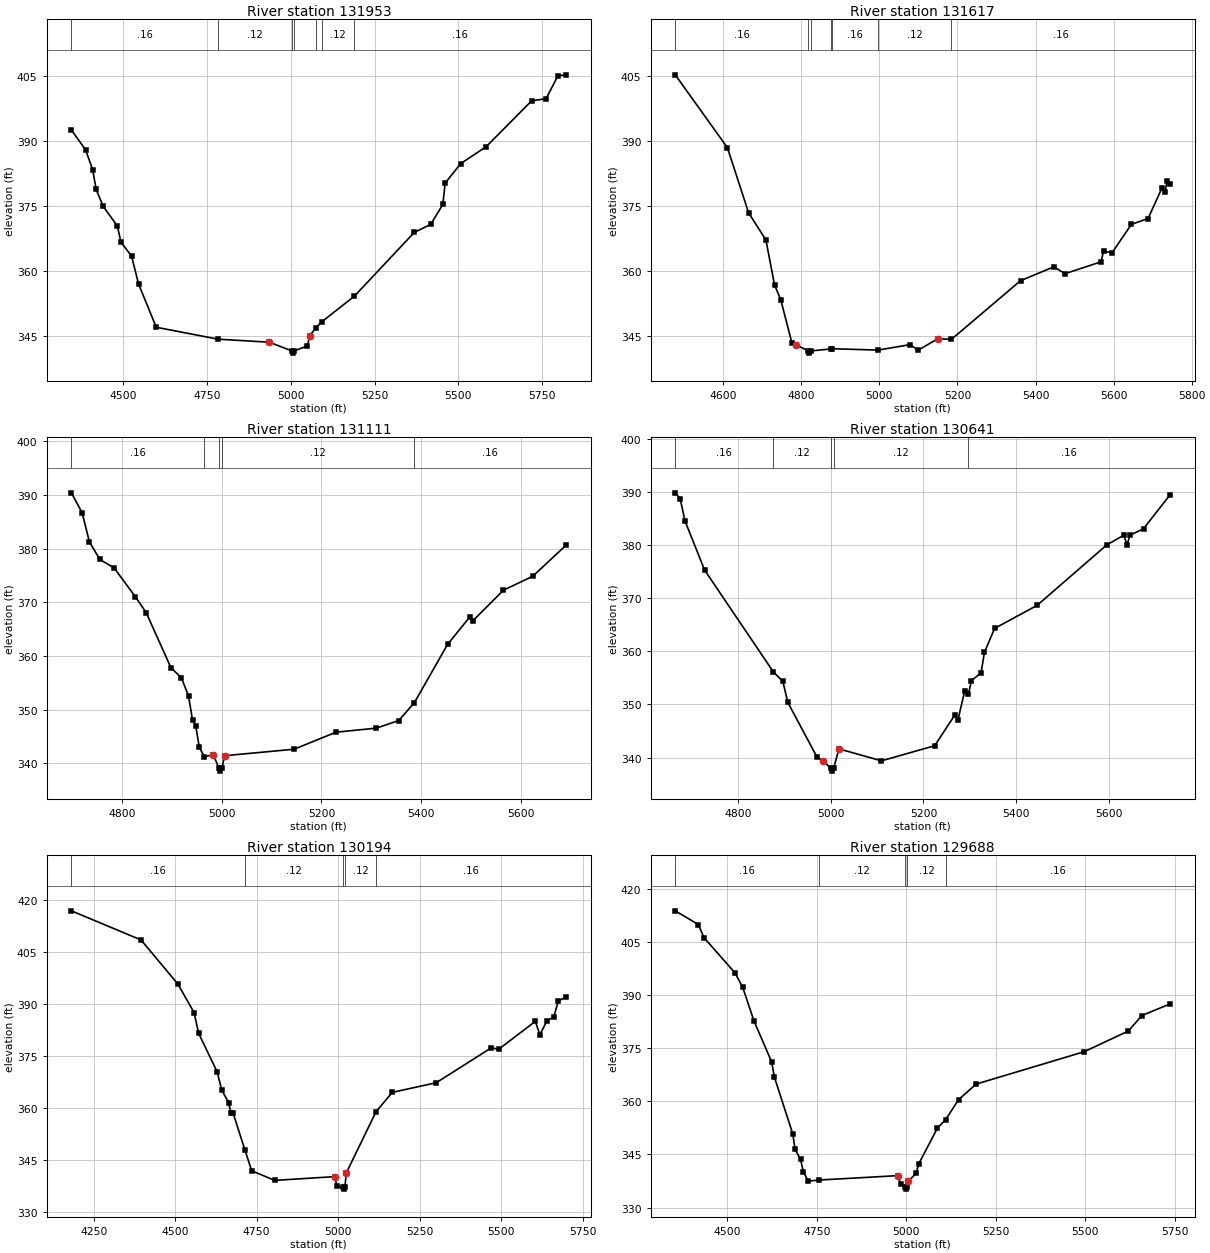
Type RM Length L Ch R = 1 ,131953  ,336,336,336
BEGIN DESCRIPTION:
BIG ELKHART CREEK 163.0
END DESCRIPTION:
XS GIS Cut Line= 4
      3794349.62     10550310.15      3794149.61     10550910.19
      3793749.61     10551260.19      3793495.39     10551440.03
#Sta/Elev= 30
  4346.1   392.6  4388.3  388.01  4409.4  383.45  4419.9  378.87    4441  374.94
  4483.2  370.42  4493.7  366.71  4525.3   363.5  4546.4  357.03  4599.1  347.05
  4783.4   344.3  4936.4   343.6  5003.6  341.58  5006.3  341.08  5009.6  341.58
  5049.3  342.72  5056.9   345.1    5075  346.94  5093.2  348.35    5190  354.24
  5368.2  368.93  5417.6  370.82  5453.6  375.41  5460.3  380.33  5506.8  384.83
  5582.7  388.73  5718.3  399.32  5761.2   399.8  5796.9  405.13  5821.5  405.32
#Mann= 7 ,-1 , 0
  4346.1     .16       0  4783.4     .12       0  5003.6     .07       0
  5009.6     .12       0    5075     .16       0  5093.2     .12       0
    5190     .16       0
Bank Sta=4936.4,5056.9
XS Rating Curve= 0 ,0
Exp/Cntr=0.3,0.1

Type RM Length L Ch R = 1 ,131617  ,506,506,506
BEGIN DESCRIPTION:
BIG ELKHART CREEK 162.0
END DESCRIPTION:
XS GIS Cut Line= 3
      3794249.61     10550160.18      3794044.33     10550595.54
      3793449.62     10551110.18
#Sta/Elev= 30
    4477  405.23  4610.6  388.41    4665  373.35  4709.2  367.12  4731.3  356.74
  4747.3  353.31  4775.6  343.38  4786.6  342.89  4818.1  341.47  4820.9  340.97
  4824.1  341.47  4875.7  341.94  4878.9  341.99    4996  341.67  5078.5  342.93
  5099.4  341.65  5149.7  344.31  5184.5  344.14  5361.5  357.69    5447   360.9
  5475.5  359.31  5567.7  362.05  5574.3   364.5  5596.2  364.17  5645.6   370.7
  5688.3  372.05  5723.4     379  5731.1  378.06  5737.7  380.76  5744.8  380.05
#Mann= 7 ,-1 , 0
    4477     .16       0  4818.1     .07       0  4824.1     .16       0
  4875.7     .12       0  4878.9     .16       0    4996     .12       0
  5184.5     .16       0
Bank Sta=4786.6,5149.7
XS Rating Curve= 0 ,0
Exp/Cntr=0.3,0.1

Type RM Length L Ch R = 1 ,131111  ,470,470,470
BEGIN DESCRIPTION:
BIG ELKHART CREEK 161.0
END DESCRIPTION:
XS GIS Cut Line= 3
      3793999.62     10550110.17      3793799.61     10550360.19
      3793199.61     10550660.19
#Sta/Elev= 30
  4699.2  390.38  4720.8  386.64  4735.2  381.26  4756.1  377.97  4784.9  376.38
  4827.3  371.02  4848.9  368.08  4898.5   357.8  4919.3  355.95  4933.7  352.57
  4941.7  348.09  4948.1     347  4955.3  342.98  4965.5  341.22  4983.4   341.6
  4994.8  339.04  4997.5  338.54  5000.8  339.04  5005.8  341.41  5145.2  342.62
    5229  345.79  5310.1  346.55  5354.8  347.97  5386.2  351.32  5452.6  362.16
  5497.3  367.29  5502.9  366.52  5564.4  372.24  5623.1  374.84  5690.2  380.66
#Mann= 5 ,-1 , 0
  4699.2     .16       0  4965.5     .12       0  4994.8     .07       0
  5000.8     .12       0  5386.2     .16       0
Bank Sta=4983.4,5005.8
XS Rating Curve= 0 ,0
Exp/Cntr=0.3,0.1

Type RM Length L Ch R = 1 ,130641  ,447,447,447
BEGIN DESCRIPTION:
BIG ELKHART CREEK 160.0
END DESCRIPTION:
XS GIS Cut Line= 3
      3793849.58      10549910.2      3793549.61     10550010.19
      3792949.61     10550460.19
#Sta/Elev= 30
  4665.3  389.85  4675.8  388.76  4686.4  384.53  4728.5  375.31  4876.8  356.11
  4897.2  354.33  4907.7   350.4    4971  340.04  4984.6  339.37  5000.4  337.94
  5003.1  337.44  5006.4  337.94    5018  341.63  5109.6  339.38  5224.2  342.22
    5268  348.05  5274.2  347.01  5288.8  352.48    5297  351.96  5303.4  354.45
  5324.2  355.97  5331.5  359.83  5353.4  364.32    5445  368.66    5595  380.04
  5631.5  381.86  5638.8  380.09    5645  381.88  5674.2  383.09  5731.5  389.49
#Mann= 5 ,-1 , 0
  4665.3     .16       0  4876.8     .12       0  5000.4     .07       0
  5006.4     .12       0    5297     .16       0
Bank Sta=4984.6,5018
XS Rating Curve= 0 ,0
Exp/Cntr=0.3,0.1

Type RM Length L Ch R = 1 ,130194  ,506,506,506
BEGIN DESCRIPTION:
BIG ELKHART CREEK 159.0
END DESCRIPTION:
XS GIS Cut Line= 2
      3793828.36      10549177.2      3792718.99     10550213.66
#Sta/Elev= 30
  4181.8  416.95  4395.4  408.54  4508.5   395.8  4558.1  387.57  4572.2  381.57
  4628.9  370.45  4643.1  365.18  4664.1  361.56  4671.4  358.45  4678.2  358.45
  4714.2  347.86  4734.9  341.88  4805.7   339.1  4989.4  340.19  4996.7  337.41
  5014.8  337.08  5017.5  336.58  5020.8  337.08  5025.1  341.25  5116.4  358.94
  5166.3  364.52  5301.1  367.31  5470.6  377.42  5492.1  376.93    5605  385.03
  5619.1  381.15  5640.6  385.18  5661.6  386.31  5675.8  390.96    5700  392.04
#Mann= 5 ,-1 , 0
  4181.8     .16       0  4714.2     .12       0  5014.8     .07       0
  5020.8     .12       0  5116.4     .16       0
Bank Sta=4989.4,5025.1
XS Rating Curve= 0 ,0
Exp/Cntr=0.3,0.1

Type RM Length L Ch R = 1 ,129688  ,215,215,215
BEGIN DESCRIPTION:
BIG ELKHART CREEK 158.0
END DESCRIPTION:
XS GIS Cut Line= 2
      3793276.29     10548849.04      3792594.31     10550051.62
#Sta/Elev= 30
  4354.6  413.76    4419   409.9  4434.9  406.19  4521.4  396.26    4543   392.2
  4574.3  382.74  4623.8  371.14  4631.8  366.77    4683  350.77  4689.3  346.48
  4704.6  343.59  4712.3  340.17  4726.2  337.46  4755.3  337.78  4976.7  339.03
  4984.4  336.54  4996.7  335.72  4999.4  335.22  5002.7  335.72  5006.1  337.57
  5027.7  339.64  5034.2  342.23  5086.9  352.43    5110  354.84    5146  360.46
  5195.1  364.86  5496.5  373.98  5620.5  379.84  5658.1   384.2  5737.1   387.5
#Mann= 5 ,-1 , 0
  4354.6     .16       0  4755.3     .12       0  4996.7     .07       0
  5002.7     .12       0    5110     .16       0
Bank Sta=4976.7,5006.1
XS Rating Curve= 0 ,0
Exp/Cntr=0.3,0.1

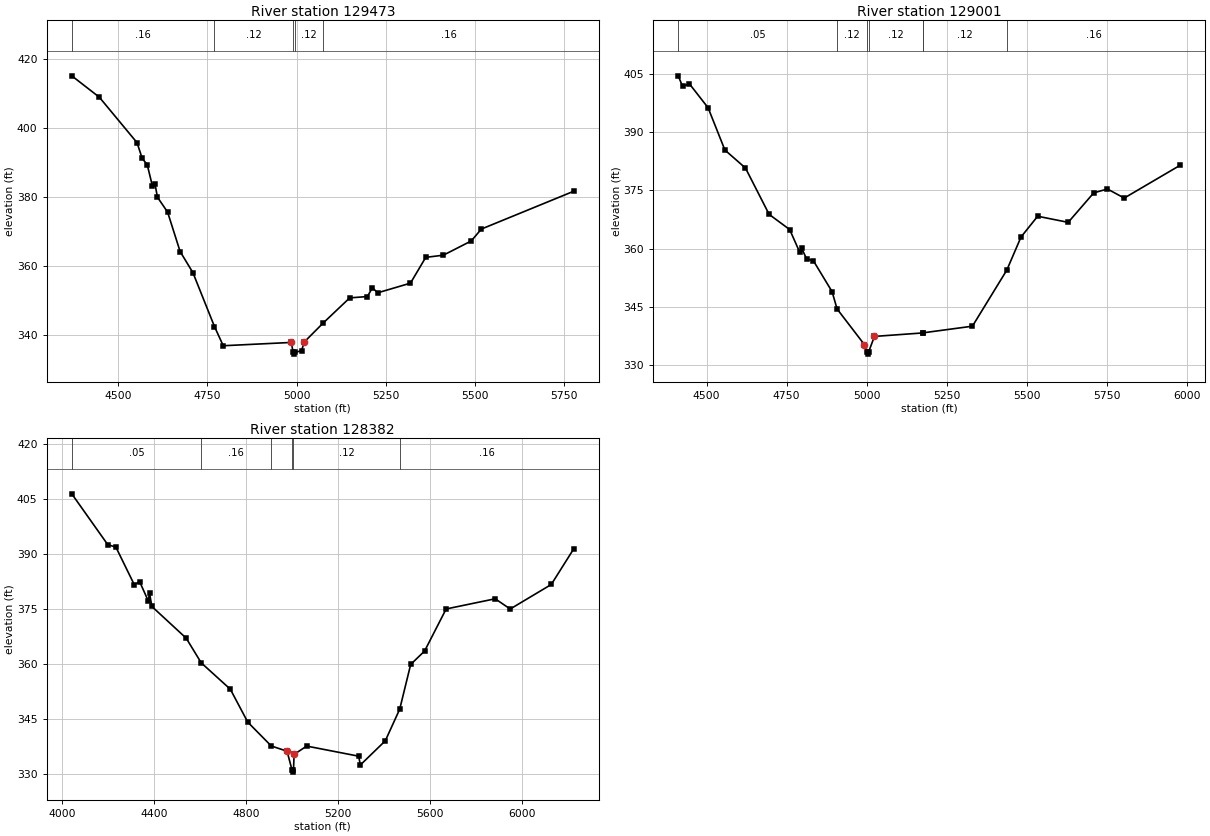
Type RM Length L Ch R = 1 ,129473  ,472,472,472
BEGIN DESCRIPTION:
BIG ELKHART CREEK 157.0
END DESCRIPTION:
XS GIS Cut Line= 2
      3793229.41     10548781.36      3792317.95     10549854.27
#Sta/Elev= 30
  4369.8  415.25    4447  409.04  4552.8  395.81  4567.1  391.29  4581.4  389.39
  4595.7  383.31  4603.4  383.65    4610  379.96  4638.5  375.62  4673.6  364.16
  4709.4  358.03  4769.9  342.35  4794.5  336.76  4985.6  337.72  4990.3  334.82
    4993  334.32  4996.3  334.82  5014.1  335.34  5021.8  337.86  5074.5  343.34
  5149.2  350.68  5198.6  351.06  5212.9  353.65  5227.2  352.14  5319.5  354.96
  5362.3  362.46  5411.7  363.09  5489.7  367.22  5518.3  370.69  5777.6   381.7
#Mann= 5 ,-1 , 0
  4369.8     .16       0  4769.9     .12       0  4990.3     .07       0
  4996.3     .12       0  5074.5     .16       0
Bank Sta=4985.6,5021.8
XS Rating Curve= 0 ,0
Exp/Cntr=0.3,0.1

Type RM Length L Ch R = 1 ,129001  ,619,619,619
BEGIN DESCRIPTION:
BIG ELKHART CREEK 156.0
END DESCRIPTION:
XS GIS Cut Line= 2
      3793146.06     10548578.25      3791803.77     10549384.66
#Sta/Elev= 30
  4411.8  404.59  4425.2  401.88  4446.6  402.53  4504.9  396.35  4557.3  385.44
  4621.5  380.79  4695.3  368.83  4759.4  364.91  4790.5  359.09  4796.3  360.16
  4811.9  357.37  4833.3  356.86  4891.6  348.89  4907.2  344.42  4992.6   335.2
  4999.3  333.26  5002.1  332.76  5005.3  333.26  5023.7  337.33  5174.2  338.23
  5175.8  338.26  5329.3  339.97  5436.6  354.45  5480.9  362.99  5532.8  368.35
    5628  366.77  5707.6  374.38  5750.4  375.38  5802.8  373.04  5977.7  381.53
#Mann= 7 ,-1 , 0
  4411.8     .05       0  4907.2     .12       0  4999.3     .07       0
  5005.3     .12       0  5174.2     .16       0  5175.8     .12       0
  5436.6     .16       0
Bank Sta=4992.6,5023.7
XS Rating Curve= 0 ,0
Exp/Cntr=0.3,0.1

Type RM Length L Ch R = 1 ,128382  ,867,867,867
BEGIN DESCRIPTION:
BIG ELKHART CREEK 155.0
END DESCRIPTION:
XS GIS Cut Line= 3
      3793276.24     10548208.47      3791687.73     10548802.21
      3791406.46     10549203.27
#Sta/Elev= 30
  4041.4  406.49  4197.9  392.63  4233.6  391.93  4313.8  381.65  4336.7  382.54
  4374.4  377.25  4379.8  379.43  4390.1  375.74  4539.6  367.08    4605  360.35
  4731.7  353.15  4807.5  344.17  4909.9  337.66  4978.6  336.23  5000.5  331.02
  5003.3  330.52  5006.5  331.02  5009.3  335.36  5064.1  337.63  5290.5  334.87
  5297.5  332.46  5406.3  339.07  5469.1  347.72  5516.8  359.92  5577.4  363.58
  5671.2  375.06  5884.7  377.84  5950.1  375.05  6128.8  381.74  6227.1  391.52
#Mann= 6 ,-1 , 0
  4041.4     .05       0    4605     .16       0  4909.9     .12       0
  5000.5     .07       0  5006.5     .12       0  5469.1     .16       0
Bank Sta=4978.6,5009.3
XS Rating Curve= 0 ,0
Exp/Cntr=0.3,0.1