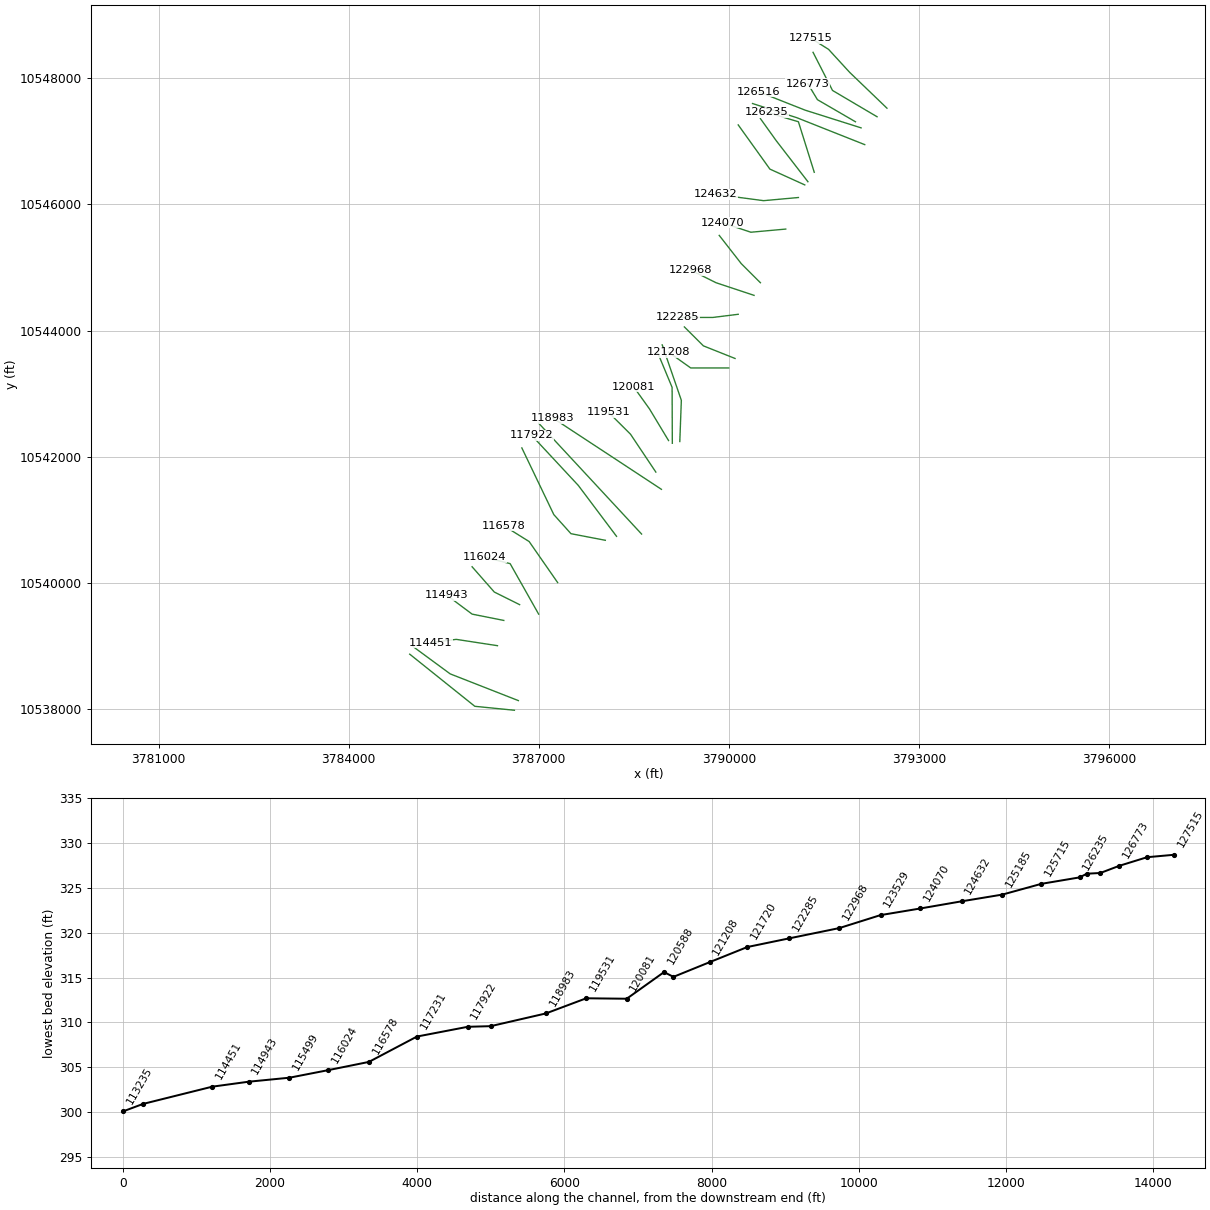
HEC-RAS study BIG ELKHART CREEK.prj: BIG ELKHART CREEK Base Level Engineering

--- BIG ELKHART CREEK.g01 (geometry) --- (continued)

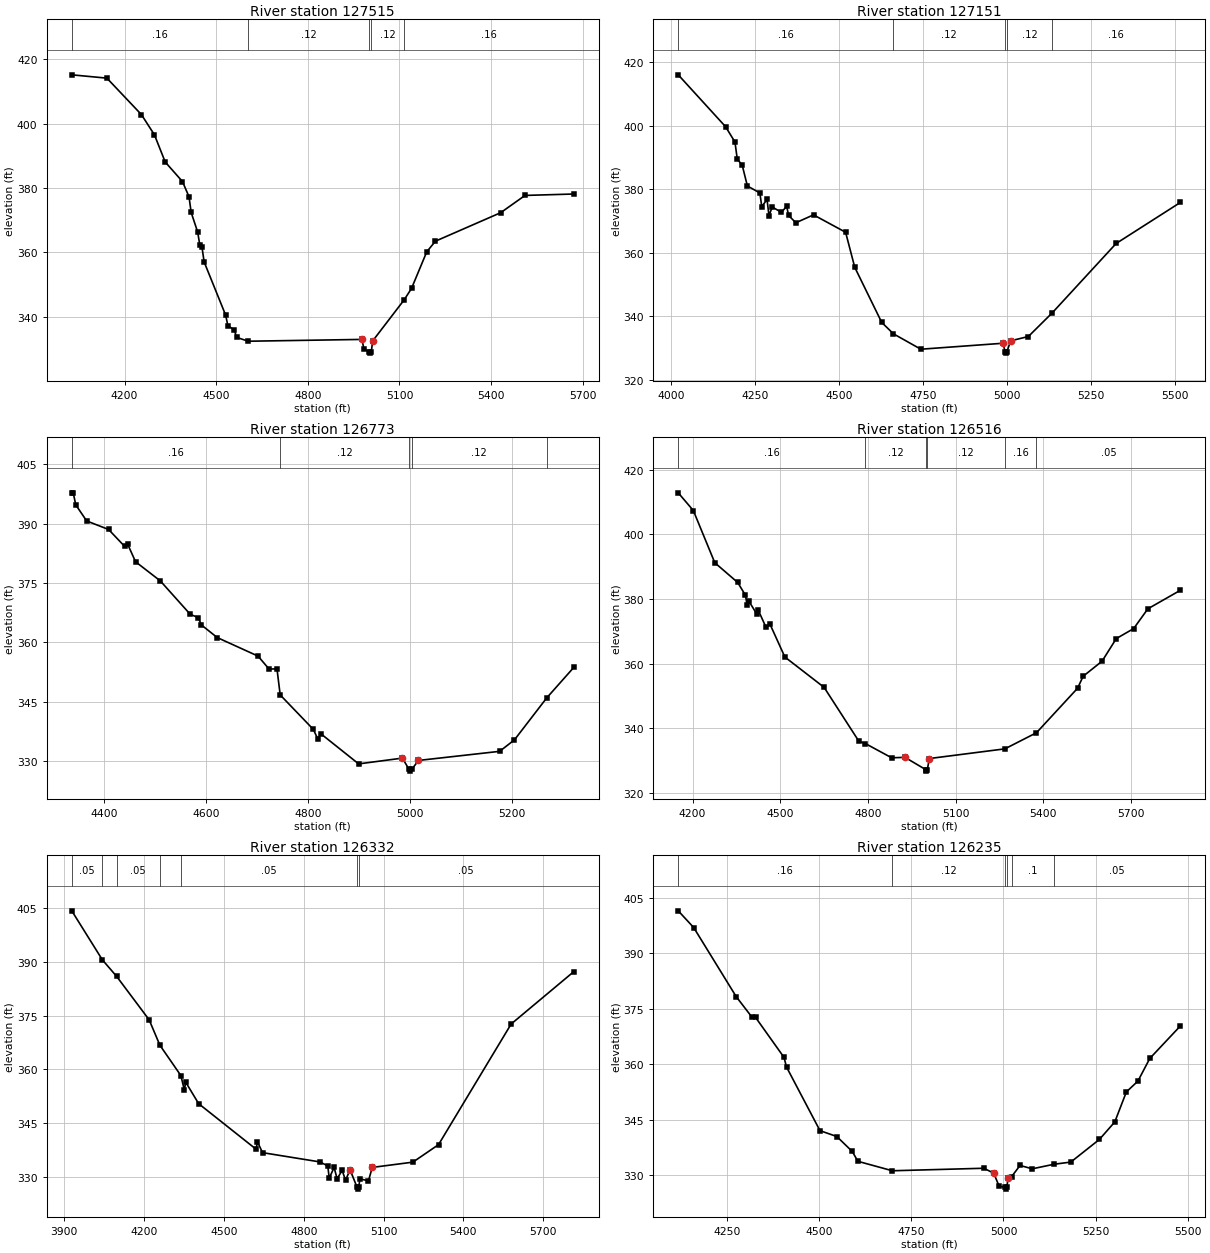
Type RM Length L Ch R = 1 ,127515  ,364,364,364
BEGIN DESCRIPTION:
BIG ELKHART CREEK 154.0
END DESCRIPTION:
XS GIS Cut Line= 4
      3792497.15     10547525.08      3791908.61     10548092.78
      3791575.28     10548457.36      3791294.34     10548634.25
#Sta/Elev= 30
  4027.1   415.2  4142.1  414.17  4255.3  402.82  4297.8  396.54    4333  388.11
  4389.6  382.02    4411  377.29  4417.9  372.46  4439.3  366.33  4446.2  362.35
  4453.4  361.65  4460.4  357.06  4531.1  340.46  4538.1  337.23  4559.4  335.92
  4566.4  333.62  4604.7  332.41  4976.8  332.97  4983.9  329.95  5001.8  329.21
  5004.6  328.71  5007.8  329.21  5012.2   332.5  5115.2  345.26  5139.4  348.82
  5189.2  360.19  5217.6   363.5  5431.4  372.36    5511  377.72  5670.8  378.16
#Mann= 5 ,-1 , 0
  4027.1     .16       0  4604.7     .12       0  5001.8     .07       0
  5007.8     .12       0  5115.2     .16       0
Bank Sta=4976.8,5012.2
XS Rating Curve= 0 ,0
Exp/Cntr=0.3,0.1

Type RM Length L Ch R = 1 ,127151  ,378,378,378
BEGIN DESCRIPTION:
BIG ELKHART CREEK 153.0
END DESCRIPTION:
XS GIS Cut Line= 3
      3792340.88     10547389.67      3791637.78     10547806.32
      3791330.49     10548410.48
#Sta/Elev= 30
  4021.3  416.03  4162.3   399.7  4190.2  394.88  4197.1  389.48  4211.6  387.67
  4227.2  381.04  4264.3  378.87  4270.1  374.53  4285.7  376.82  4291.5  371.75
  4301.3  374.42  4328.6  372.76  4344.2  374.66    4350  371.77  4371.5  369.47
  4424.1  371.96  4519.7  366.48  4546.9  355.46  4627.2  338.11  4662.2  334.51
  4743.8  329.67  4988.8  331.55  4994.2  328.94  4996.9  328.44  5000.2  328.94
  5011.2  332.31  5063.9  333.67  5135.1  341.12  5325.3  362.95  5516.4  375.85
#Mann= 5 ,-1 , 0
  4021.3     .16       0  4662.2     .12       0  4994.2     .07       0
  5000.2     .12       0  5135.1     .16       0
Bank Sta=4988.8,5011.2
XS Rating Curve= 0 ,0
Exp/Cntr=0.3,0.1

Type RM Length L Ch R = 1 ,126773  ,257,257,257
BEGIN DESCRIPTION:
BIG ELKHART CREEK 152.0
END DESCRIPTION:
XS GIS Cut Line= 3
      3791999.59      10547310.2      3791399.61     10547660.19
      3791249.58     10547910.23
#Sta/Elev= 30
  4336.1  397.82    4339  397.82  4343.9  394.79  4365.4  390.71  4408.4  388.56
  4439.9  384.29  4445.6  384.91  4461.4   380.4  4510.1  375.55  4568.9   367.1
  4584.6  366.29  4590.8  364.42  4621.8  361.24    4702  356.55  4723.5   353.3
  4739.2  353.31  4745.5  346.74  4810.7  338.01  4819.4  335.57  4825.2  336.94
  4899.6  329.31  4985.6  330.77  4998.3  327.98  5001.1  327.48  5004.3  327.98
  5017.1  330.18  5176.5  332.48  5205.6  335.38  5269.1     346  5322.3  353.71
#Mann= 5 ,-1 , 0
  4336.1     .16       0  4745.5     .12       0  4998.3     .07       0
  5004.3     .12       0  5269.1     .16       0
Bank Sta=4985.6,5017.1
XS Rating Curve= 0 ,0
Exp/Cntr=0.3,0.1

Type RM Length L Ch R = 1 ,126516  ,184,184,184
BEGIN DESCRIPTION:
Mapping XS e460eb6f
END DESCRIPTION:
XS GIS Cut Line= 3
      3792088.74     10547213.67      3791203.35     10547494.91
      3790470.71     10547785.89
#Sta/Elev= 30
    4151  412.89  4202.6  407.41    4276  391.24  4354.4  385.12  4380.9  381.16
  4386.7  378.03  4391.9  379.44    4419  375.44  4424.2  376.64  4451.2  371.23
  4464.9  372.19  4515.7  362.03    4650  352.62  4769.1   335.9  4790.9  335.23
    4881  330.81  4926.5  330.95    4997  327.18  4999.7  326.68    5003  327.18
    5010  330.58  5268.3  333.58  5376.3  338.57    5517  352.37  5535.9  356.06
  5600.7  360.74  5649.3  367.74  5708.7  370.83  5757.3  376.96  5868.3  382.69
#Mann= 6 ,-1 , 0
    4151     .16       0  4790.9     .12       0    4997     .07       0
    5003     .12       0  5268.3     .16       0  5376.3     .05       0
Bank Sta=4926.5,5010
XS Rating Curve= 0 ,0
Exp/Cntr=0.3,0.1

Type RM Length L Ch R = 1 ,126332  ,97,97,97
BEGIN DESCRIPTION:
Mapping XS 2734fadb
END DESCRIPTION:
XS GIS Cut Line= 3
      3792146.09     10546948.03      3791073.15     10547375.12
      3790375.22     10547599.08
#Sta/Elev= 30
  3927.9  404.18  4043.1   390.5  4096.2  385.94  4218.9  373.79  4259.2  366.72
  4338.2  358.25  4351.1  354.24  4356.4   356.4    4405  350.42  4620.8  337.73
  4626.2  339.78  4645.1  336.77  4860.5  334.19  4890.5  333.08  4895.9  329.65
  4914.3  332.65  4925.6  329.48  4944.5  331.82  4957.4  329.07  4974.1     332
  5000.8   327.1  5003.5   326.6  5006.8   327.1  5011.2  329.46  5043.5  328.92
  5057.7  332.65  5210.5  334.12  5306.9     339    5580  372.63  5815.7  387.24
#Mann= 7 ,-1 , 0
  3927.9     .05       0  4043.1      .1       0  4096.2     .05       0
  4259.2      .1       0  4338.2     .05       0  5000.8     .04       0
  5006.8     .05       0
Bank Sta=4974.1,5057.7
XS Rating Curve= 0 ,0
Exp/Cntr=0.3,0.1

Type RM Length L Ch R = 1 ,126235  ,520,520,520
BEGIN DESCRIPTION:
BIG ELKHART CREEK 151.0
END DESCRIPTION:
XS GIS Cut Line= 3
      3791349.61     10546510.19      3791099.61     10547310.19
      3790599.58      10547460.2
#Sta/Elev= 30
  4118.9  401.52  4160.8  396.99  4276.1  378.27    4318  372.82  4328.4  372.67
  4405.4  361.86  4412.3  359.23  4502.9  342.02  4548.5  340.43  4590.4  336.38
  4605.6  333.72    4699  331.16  4946.6  331.84  4973.6  330.52  4988.4  326.93
  5003.6  326.69  5006.4  326.19  5009.6  326.69  5011.9  329.17  5022.1  329.58
  5044.9   332.6    5078  331.69  5137.3  332.93  5182.4  333.51  5259.8  339.63
  5301.6  344.38  5332.9  352.49  5364.2  355.43  5396.4  361.56  5479.1  370.34
#Mann= 6 ,-1 , 0
  4118.9     .16       0    4699     .12       0  5003.6     .07       0
  5009.6     .12       0  5022.1      .1       0  5137.3     .05       0
Bank Sta=4973.6,5011.9
XS Rating Curve= 0 ,0
Exp/Cntr=0.3,0.1

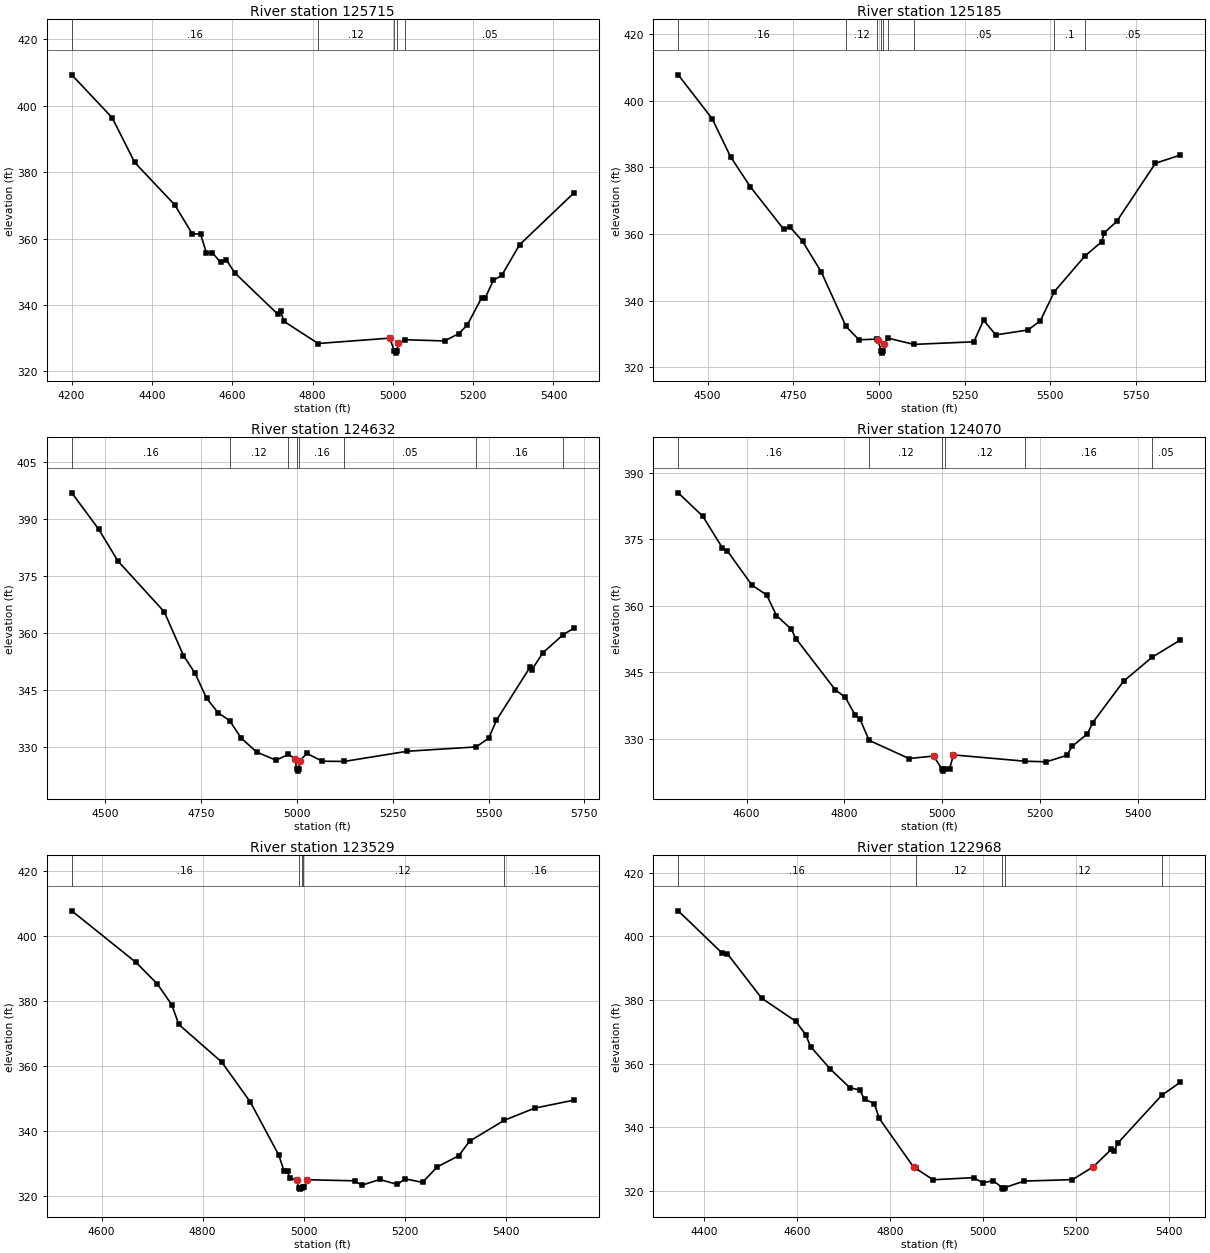
Type RM Length L Ch R = 1 ,125715  ,530,530,530
BEGIN DESCRIPTION:
BIG ELKHART CREEK 150.0
END DESCRIPTION:
XS GIS Cut Line= 3
      3791249.58     10546360.23      3790749.61     10547010.19
      3790499.62     10547360.17
#Sta/Elev= 30
  4200.6  409.32  4301.2  396.39  4357.3  382.92    4457  370.14  4500.5  361.43
  4521.3   361.3  4535.8  355.68  4550.3  355.76  4571.2  352.82  4585.7  353.52
  4606.5  349.65  4714.3  337.11  4720.7  338.11  4728.9  335.04  4814.1  328.37
  4992.5  329.99    5004  325.97  5006.8  325.47    5010  325.97  5013.4  328.56
  5030.4  329.51  5128.8  329.14  5164.4  331.36  5185.3  333.95  5220.9  342.06
  5229.5  341.99  5250.4  347.41  5271.3  348.91  5315.5  358.11  5450.7  373.72
#Mann= 5 ,-1 , 0
  4200.6     .16       0  4814.1     .12       0    5004     .07       0
    5010     .12       0  5030.4     .05       0
Bank Sta=4992.5,5013.4
XS Rating Curve= 0 ,0
Exp/Cntr=0.3,0.1

Type RM Length L Ch R = 1 ,125185  ,553,553,553
BEGIN DESCRIPTION:
BIG ELKHART CREEK 149.0
END DESCRIPTION:
XS GIS Cut Line= 3
      3791199.63     10546310.18      3790649.61     10546560.19
      3790149.61     10547260.18
#Sta/Elev= 30
  4414.5  407.78  4513.4  394.62  4567.2  383.19  4624.3  374.25  4722.1  361.44
  4739.7  362.19    4777  357.86  4831.9  348.57  4903.9  332.27  4941.8  328.27
  4994.5  328.48  4996.7  328.35  5006.9  324.77  5009.6  324.27  5012.9  324.77
  5015.9  327.05  5026.3  328.77  5101.6  326.89  5276.7  327.67    5305  334.16
  5340.6  329.73  5435.3  331.23  5470.9  334.02  5511.8  342.76  5600.4  353.38
  5649.1  357.65  5657.7  360.45  5693.3  363.77  5806.4  381.25  5878.9  383.69
#Mann= 9 ,-1 , 0
  4414.5     .16       0  4903.9     .12       0  4994.5     .16       0
  5006.9     .07       0  5012.9     .16       0  5026.3     .12       0
  5101.6     .05       0  5511.8      .1       0  5600.4     .05       0
Bank Sta=4996.7,5015.9
XS Rating Curve= 0 ,0
Exp/Cntr=0.3,0.1

Type RM Length L Ch R = 1 ,124632  ,562,562,562
BEGIN DESCRIPTION:
BIG ELKHART CREEK 148.0
END DESCRIPTION:
XS GIS Cut Line= 3
      3791099.65     10546110.19      3790549.61     10546060.19
      3789799.65     10546160.18
#Sta/Elev= 30
  4413.5  396.96  4483.8  387.34    4534  378.93  4654.5  365.58  4704.7  354.03
  4734.9  349.34    4765  342.75  4795.1  338.92    4825  336.84  4855.4  332.21
  4895.5  328.56  4945.7   326.4  4978.1  327.92 4996.23  326.77  4999.4  324.02
  5002.1  323.52  5005.4  324.02  5007.4  326.18  5026.3   328.2  5066.7  326.13
  5123.9  326.08  5288.6  328.77  5467.8  329.91  5500.5  332.23  5520.7  336.95
  5607.7  350.87  5612.7  350.22  5641.7  354.76  5694.6  359.53  5722.4  361.24
#Mann= 8 ,-1 , 0
  4413.5     .16       0    4825     .12       0  4978.1     .16       0
  4999.4     .07       0  5005.4     .16       0  5123.9     .05       0
  5467.8     .16       0  5694.6     .05       0
Bank Sta=4996.23,5007.4
XS Rating Curve= 0 ,0
Exp/Cntr=0.3,0.1

Type RM Length L Ch R = 1 ,124070  ,541,541,541
BEGIN DESCRIPTION:
BIG ELKHART CREEK 147.0
END DESCRIPTION:
XS GIS Cut Line= 3
      3790899.57     10545610.18      3790349.61     10545560.19
      3789899.58      10545710.2
#Sta/Elev= 30
  4460.3  385.49  4510.5  380.21  4550.6  373.07  4560.7  372.39  4610.9  364.68
    4641  362.47  4661.1  357.82  4691.2  354.77  4701.2  352.57  4781.6  341.04
  4801.7  339.41  4821.7  335.44  4831.8   334.5  4850.4  329.67  4932.2  325.56
  4982.4  326.12  4999.5  323.22  5002.2  322.72  5005.5  323.22  5015.2  323.31
  5023.1  326.38    5169  324.96  5212.8  324.82    5255  326.28  5265.5   328.3
  5297.1  331.15  5307.7  333.65  5370.9     343  5429.1   348.4  5486.9  352.29
#Mann= 6 ,-1 , 0
  4460.3     .16       0  4850.4     .12       0  4999.5     .07       0
  5005.5     .12       0    5169     .16       0  5429.1     .05       0
Bank Sta=4982.4,5023.1
XS Rating Curve= 0 ,0
Exp/Cntr=0.3,0.1

Type RM Length L Ch R = 1 ,123529  ,561,561,561
BEGIN DESCRIPTION:
BIG ELKHART CREEK 146.0
END DESCRIPTION:
XS GIS Cut Line= 3
      3790499.62     10544760.18      3790199.61     10545060.19
      3789849.59     10545510.22
#Sta/Elev= 30
  4540.9  407.72  4668.2  391.82  4710.6  385.15  4738.9  378.78    4753   372.7
  4837.9  361.12  4894.5  348.83    4951  332.42  4961.6  327.44  4968.3  327.44
  4972.4  325.43  4986.9   324.7  4990.2  322.48    4993  321.98  4996.2  322.48
  4997.9  322.51  5001.4  322.58  5007.7  324.87  5100.9  324.54  5115.4  323.18
  5150.7  324.96    5186  323.41  5200.5  325.16  5235.7  324.05  5264.7  328.84
  5307.2  332.25  5328.9  336.76  5396.9  343.14  5457.4  346.92  5535.3   349.4
#Mann= 5 ,-1 , 0
  4540.9     .16       0  4990.2     .07       0  4996.2     .16       0
  4997.9     .12       0  5396.9     .16       0
Bank Sta=4986.9,5007.7
XS Rating Curve= 0 ,0
Exp/Cntr=0.3,0.1

Type RM Length L Ch R = 1 ,122968  ,683,683,683
BEGIN DESCRIPTION:
BIG ELKHART CREEK 145.0
END DESCRIPTION:
XS GIS Cut Line= 3
      3790399.61     10544560.19      3789799.61     10544760.19
      3789399.58      10544960.2
#Sta/Elev= 30
  4344.5  407.99  4439.4  394.63  4449.9  394.56  4523.7  380.56  4597.5  373.25
  4618.6  369.05  4629.1  365.33  4671.3  358.29  4713.4  352.42  4734.5  351.69
  4745.1  348.78  4766.1  347.43  4776.7  342.76  4850.5  327.47  4855.3  327.05
  4892.6  323.47  4979.8  324.14  4999.3  322.52  5021.7  323.18    5041  321.03
  5043.8  320.53    5047  321.03  5088.8  323.07  5192.2  323.51  5236.9  327.54
    5276  333.05  5281.6  332.48    5290  335.02    5384  349.99  5424.2  354.13
#Mann= 5 ,-1 , 0
  4344.5     .16       0  4855.3     .12       0    5041     .07       0
    5047     .12       0    5384     .16       0
Bank Sta=4850.5,5236.9
XS Rating Curve= 0 ,0
Exp/Cntr=0.3,0.1

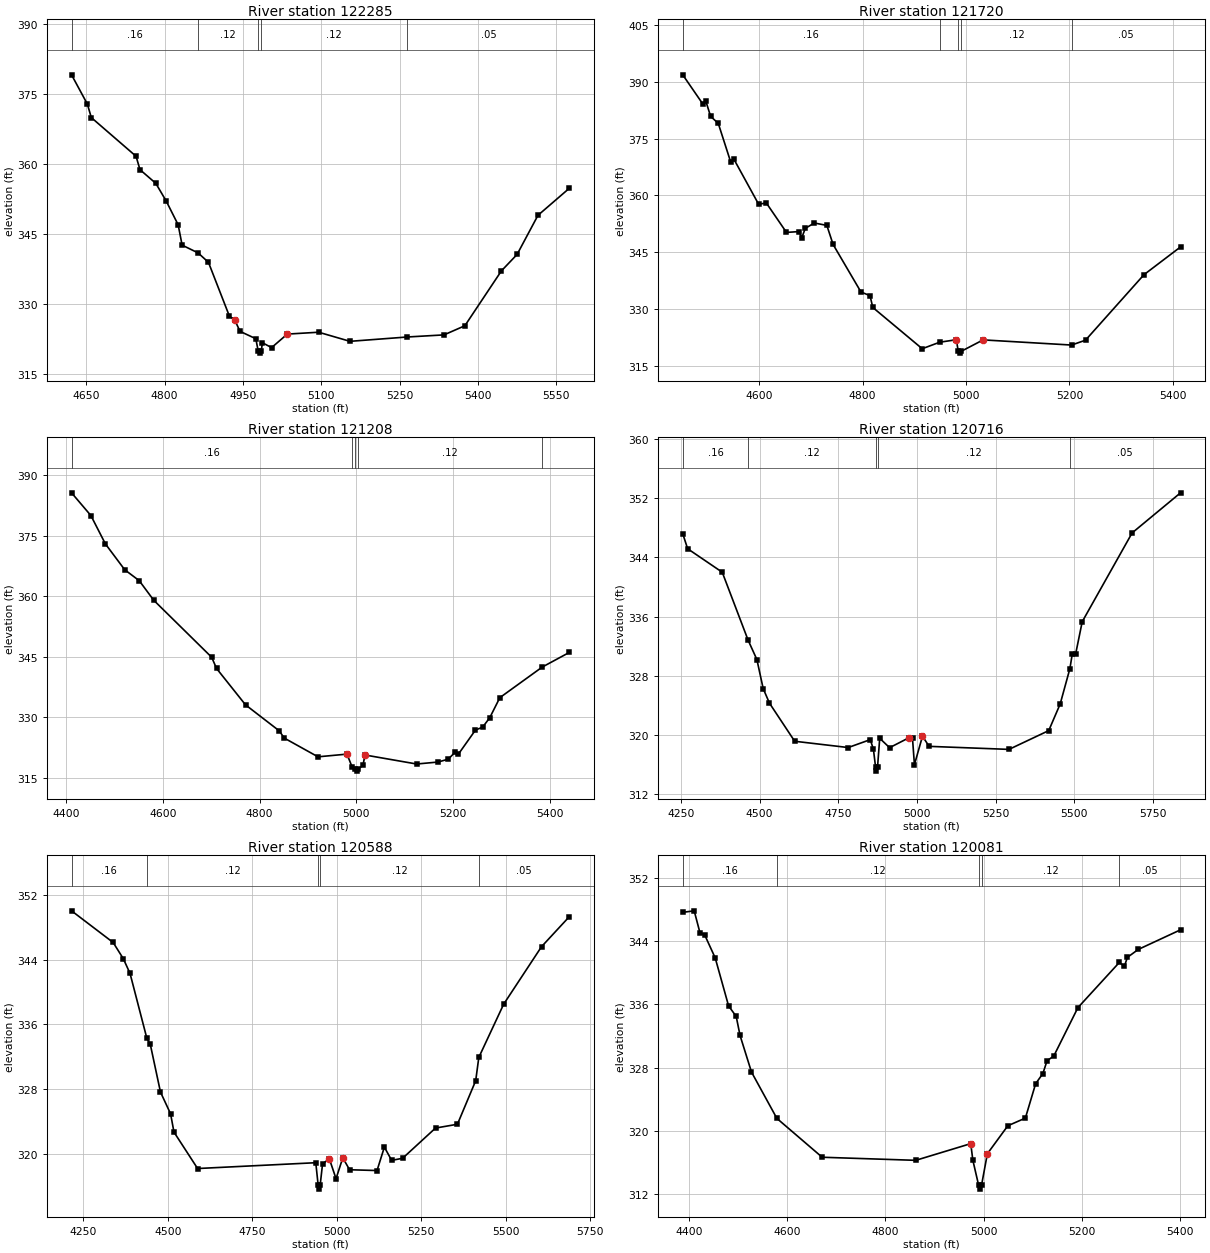
Type RM Length L Ch R = 1 ,122285  ,565,565,565
BEGIN DESCRIPTION:
BIG ELKHART CREEK 144.0
END DESCRIPTION:
XS GIS Cut Line= 3
      3790149.64     10544260.19      3789749.61     10544210.19
      3789199.65     10544210.19
#Sta/Elev= 30
    4622  379.04  4652.3  372.76  4659.8  369.88  4745.5  361.58    4753  358.71
  4783.3  355.78  4803.4  351.95  4826.1  346.89  4833.7  342.53  4864.2  340.87
  4884.1  338.85  4924.4  327.26  4934.4  326.51  4944.5  324.05  4974.8  322.47
  4979.3  319.88  4982.1  319.38  4985.3  319.88  4987.4  321.61    5005  320.56
  5035.1  323.46  5095.1  323.86  5155.1  321.91    5265  322.84  5335.1  323.29
  5375.1  325.25  5445.1  337.02  5475.1  340.54  5515.1  348.93  5575.1  354.72
#Mann= 5 ,-1 , 0
    4622     .16       0  4864.2     .12       0  4979.3     .07       0
  4985.3     .12       0    5265     .05       0
Bank Sta=4934.4,5035.1
XS Rating Curve= 0 ,0
Exp/Cntr=0.3,0.1

Type RM Length L Ch R = 1 ,121720  ,512,512,512
BEGIN DESCRIPTION:
BIG ELKHART CREEK 143.0
END DESCRIPTION:
XS GIS Cut Line= 3
      3790099.65     10543560.17      3789599.61     10543760.19
      3789299.62     10544060.17
#Sta/Elev= 30
  4452.1   391.8  4491.2  384.05  4496.6  384.93    4506  380.85  4520.8     379
    4545  368.74  4550.4  369.71  4598.9  357.67  4613.7  358.02  4652.7  350.25
    4677  350.47  4682.4  348.87  4689.1  351.32  4706.6  352.73  4730.8   352.1
  4742.9  347.07  4796.8  334.54  4814.3  333.57  4819.7  330.46  4915.3  319.58
  4949.1   321.3  4981.2  321.95    4985  318.92  4987.7  318.42    4991  318.92
  5033.1  321.91  5204.1  320.55  5231.1  321.83  5344.2   339.1  5414.9  346.42
#Mann= 5 ,-1 , 0
  4452.1     .16       0  4949.1     .12       0    4985     .07       0
    4991     .12       0  5204.1     .05       0
Bank Sta=4981.2,5033.1
XS Rating Curve= 0 ,0
Exp/Cntr=0.3,0.1

Type RM Length L Ch R = 1 ,121208  ,492,492,492
BEGIN DESCRIPTION:
BIG ELKHART CREEK 142.0
END DESCRIPTION:
XS GIS Cut Line= 3
      3789999.56     10543410.19      3789399.61     10543410.19
      3789049.59     10543660.21
#Sta/Elev= 30
  4410.8  385.59  4450.8  379.97  4480.8  372.96  4520.8  366.56  4550.8  363.86
  4580.8  359.02  4700.8   344.9  4710.8  342.14  4770.8  333.13  4840.8  326.68
  4850.8  324.92  4920.8  320.27  4980.8  320.94  4991.4  317.75  4997.8  317.23
  5000.5  316.73  5003.8  317.23  5013.8  318.17  5018.1  320.72    5125  318.49
  5169.3  318.98  5190.2  319.69  5204.9  321.44  5211.1  320.89  5246.7   326.9
  5261.5  327.61  5276.2  329.94  5297.1  334.91  5384.7  342.47  5440.9   346.1
#Mann= 5 ,-1 , 0
  4410.8     .16       0  4991.4     .12       0  4997.8     .07       0
  5003.8     .12       0  5384.7     .05       0
Bank Sta=4980.8,5018.1
XS Rating Curve= 0 ,0
Exp/Cntr=0.3,0.1

Type RM Length L Ch R = 1 ,120716  ,128,128,128
BEGIN DESCRIPTION:
BIG ELKHART CREEK 141.0
END DESCRIPTION:
XS GIS Cut Line= 3
      3789227.57     10542244.75      3789251.88     10542897.52
      3788949.92     10543775.63
#Sta/Elev= 30
  4256.1   347.2  4271.6  345.17  4381.6  341.99  4463.8   332.8  4491.7  330.18
  4511.7  326.25  4531.7  324.28  4611.8  319.13  4781.9  318.28    4852  319.35
    4862  318.04    4869  315.59  4871.7  315.09    4875  315.59    4882  319.53
  4913.4  318.26  4975.6  319.62  4986.2  319.51  4992.3  315.96  5017.9  319.81
    5039  318.44  5292.8  318.03  5419.1  320.57  5455.6  324.19  5486.4  328.97
  5493.8  330.91  5504.3  330.87  5525.5   335.3  5684.1  347.31  5837.9  352.73
#Mann= 5 ,-1 , 0
  4256.1     .16       0  4463.8     .12       0    4869     .07       0
    4875     .12       0  5486.4     .05       0
Bank Sta=4975.6,5017.9
XS Rating Curve= 0 ,0
Exp/Cntr=0.3,0.1

Type RM Length L Ch R = 1 ,120588  ,507,507,507
BEGIN DESCRIPTION:
Mapping XS 2e7121dc
END DESCRIPTION:
XS GIS Cut Line= 3
      3789109.52     10542216.94      3789106.05     10543102.38
      3788880.83     10543646.36
#Sta/Elev= 30
  4214.8  350.07    4338  346.15    4368  344.15    4388  342.32  4437.8  334.29
    4448  333.54  4478.1  327.64  4508.1  324.94  4518.1  322.68  4588.1  318.17
  4938.1  318.89  4945.1  316.12  4947.8  315.62  4951.1  316.12  4958.1  318.73
  4978.1  319.39  4998.1  316.91  5018.1   319.5  5038.1  318.02  5119.5  317.92
  5141.2  320.82  5162.8  319.18  5195.3  319.44  5292.7  323.18  5357.6  323.65
  5411.7  329.04  5420.9  331.92  5494.5  338.51  5606.6  345.63    5689  349.35
#Mann= 5 ,-1 , 0
  4214.8     .16       0  4437.8     .12       0  4945.1     .07       0
  4951.1     .12       0  5420.9     .05       0
Bank Sta=4978.1,5018.1
XS Rating Curve= 0 ,0
Exp/Cntr=0.3,0.1

Type RM Length L Ch R = 1 ,120081  ,550,550,550
BEGIN DESCRIPTION:
BIG ELKHART CREEK 140.0
END DESCRIPTION:
XS GIS Cut Line= 3
      3789049.61     10542260.19      3788749.61     10542760.19
      3788499.61     10543110.18
#Sta/Elev= 30
  4387.4  347.64  4410.7  347.83  4422.4  345.06  4432.1  344.78  4453.5  341.87
  4480.7  335.81  4496.2  334.48    4504  332.08  4527.3  327.45    4579  321.59
  4671.2  316.68  4861.6  316.29  4973.6   318.4  4977.9   316.3  4989.6  313.15
  4992.4  312.65  4995.6  313.15  5007.4  317.12  5049.1  320.66  5084.8  321.63
  5105.7  325.98  5120.4  327.26    5129  328.89  5142.5  329.46  5191.7  335.59
  5276.1  341.31  5286.3  340.82  5292.5  341.95  5314.6  342.95  5400.6  345.43
#Mann= 5 ,-1 , 0
  4387.4     .16       0    4579     .12       0  4989.6     .07       0
  4995.6     .12       0  5276.1     .05       0
Bank Sta=4973.6,5007.4
XS Rating Curve= 0 ,0
Exp/Cntr=0.3,0.1

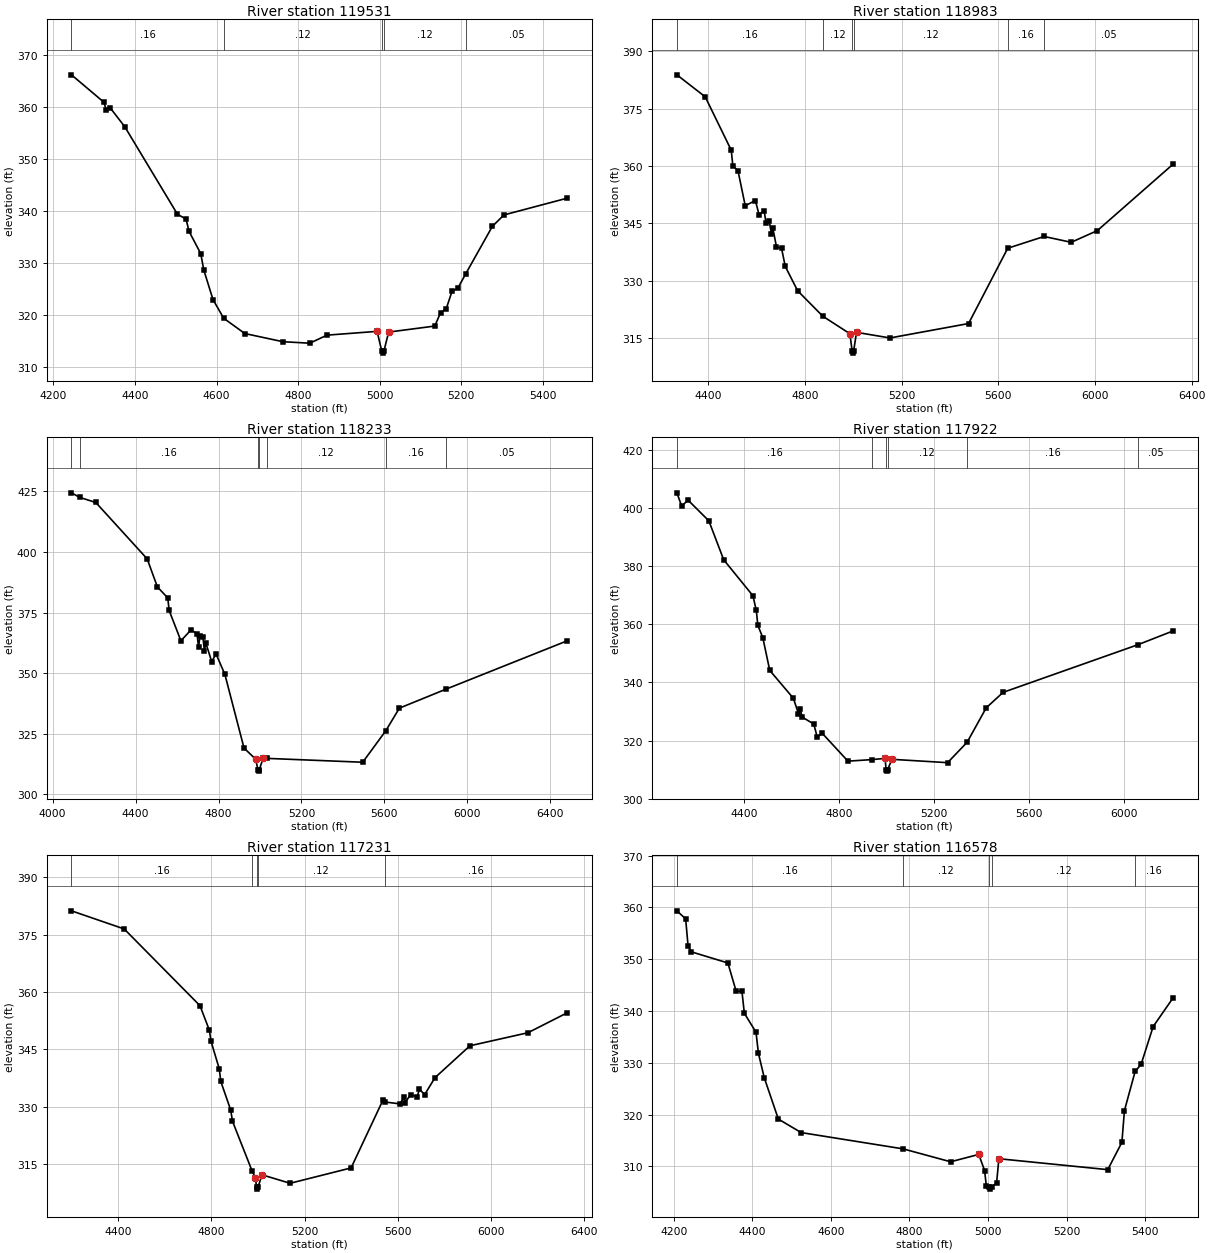
Type RM Length L Ch R = 1 ,119531  ,548,548,548
BEGIN DESCRIPTION:
BIG ELKHART CREEK 139.0
END DESCRIPTION:
XS GIS Cut Line= 3
      3788849.59     10541760.21      3788449.61     10542360.19
      3788099.58     10542710.22
#Sta/Elev= 30
  4244.3  366.27  4323.9  360.99  4329.9  359.41  4338.9  359.95    4375  356.28
  4504.2  339.43  4525.2   338.5  4532.7  336.13  4561.3  331.85  4568.8   328.7
  4591.3  323.01  4617.6  319.41  4669.4  316.47  4762.6   314.9  4828.7  314.61
  4870.7  316.16  4993.7  316.89  5004.8   313.2  5007.6   312.7  5010.8   313.2
    5022  316.75  5135.1  317.91  5149.2  320.46  5163.4  321.29  5177.5  324.61
  5191.7   325.2  5210.9  327.95  5276.5  337.12  5304.8   339.3  5460.4  342.54
#Mann= 5 ,-1 , 0
  4244.3     .16       0  4617.6     .12       0  5004.8     .07       0
  5010.8     .12       0  5210.9     .05       0
Bank Sta=4993.7,5022
XS Rating Curve= 0 ,0
Exp/Cntr=0.3,0.1

Type RM Length L Ch R = 1 ,118983  ,750,750,750
BEGIN DESCRIPTION:
BIG ELKHART CREEK 138.0
END DESCRIPTION:
XS GIS Cut Line= 3
      3788937.41     10541487.26      3788124.89     10542023.73
       3787224.2     10542617.24
#Sta/Elev= 30
  4269.9  383.82  4387.1  378.07  4494.9  364.09  4501.5     360  4522.6  358.77
  4552.7  349.58  4594.8  350.94  4609.9  347.22  4630.9   348.3  4638.7  345.11
    4652   345.7  4661.1  342.09  4667.1  343.66  4682.1  338.77  4703.2   338.4
  4718.2  333.72  4769.4  327.34  4873.8  320.66 4985.79  316.09  4995.2  311.51
    4998  311.01  5001.2  311.51  5013.2  316.45  5151.7  314.98  5476.9  318.75
  5638.9  338.45  5789.5  341.53  5901.5     340  6009.9  343.07  6322.2  360.39
#Mann= 6 ,-1 , 0
  4269.9     .16       0  4873.8     .12       0  4995.2     .07       0
  5001.2     .12       0  5638.9     .16       0  5789.5     .05       0
Bank Sta=4985.79,5013.2
XS Rating Curve= 0 ,0
Exp/Cntr=0.3,0.1

Type RM Length L Ch R = 1 ,118233  ,311,311,311
BEGIN DESCRIPTION:
BIG ELKHART CREEK 137.0
END DESCRIPTION:
XS GIS Cut Line= 2
      3788624.36     10540778.87      3786999.64     10542535.51
#Sta/Elev= 30
  4090.6  424.45  4130.3  422.57  4208.1  420.46  4455.9  397.18  4505.2  385.61
  4555.1  381.09  4561.9   375.9  4618.6  363.39    4668  367.93  4696.3  366.24
  4703.7  360.84  4710.5  365.25  4724.7  364.96    4732  359.36  4738.8  362.45
  4767.2  354.82  4788.2  357.93  4830.7  349.55  4923.1  319.11  4979.2  314.52
  4990.4  310.09  4993.2  309.59  4996.4  310.09    5015  314.86  5031.7  314.86
  5495.8  313.26  5606.3  326.16  5672.7  335.58  5896.7  343.39  6483.4  363.41
#Mann= 7 ,-1 , 0
  4090.6     .05       0  4130.3     .16       0  4990.4     .07       0
  4996.4     .16       0  5031.7     .12       0  5606.3     .16       0
  5896.7     .05       0
Bank Sta=4979.2,5015
XS Rating Curve= 0 ,0
Exp/Cntr=0.3,0.1

Type RM Length L Ch R = 1 ,117922  ,691,691,691
BEGIN DESCRIPTION:
BIG ELKHART CREEK 136.0
END DESCRIPTION:
XS GIS Cut Line= 3
      3788229.07     10540742.45      3787624.89     10541549.77
      3786890.51     10542341.44
#Sta/Elev= 30
  4117.9  405.23  4137.9  400.69    4165  402.71  4252.5   395.6    4315   382.2
    4438  369.85  4452.3  364.77  4458.8  359.64  4479.7  355.42  4508.9  344.16
  4608.4  334.58  4629.7  329.31  4638.1  330.94  4644.3  328.14  4694.3  325.73
  4708.9  321.16  4729.8  322.54  4838.1  312.95  4940.3  313.49  4994.4   313.9
  4998.9  310.02  5001.6  309.52  5004.9  310.02  5023.6  313.58  5257.7  312.43
  5339.9  319.45  5420.4   331.3  5491.3  336.61  6059.2     353  6206.1   357.7
#Mann= 6 ,-1 , 0
  4117.9     .16       0  4940.3     .12       0  4998.9     .07       0
  5004.9     .12       0  5339.9     .16       0  6059.2     .05       0
Bank Sta=4994.4,5023.6
XS Rating Curve= 0 ,0
Exp/Cntr=0.3,0.1

Type RM Length L Ch R = 1 ,117231  ,653,653,653
BEGIN DESCRIPTION:
BIG ELKHART CREEK 135.0
END DESCRIPTION:
XS GIS Cut Line= 4
      3788051.95     10540679.98      3787510.31     10540784.14
      3787239.47     10541086.23      3786734.43     10542143.18
#Sta/Elev= 30
  4199.6  381.27    4426  376.52  4751.2  356.44  4791.3  350.05  4798.8  347.07
  4833.9  339.93  4840.6   336.6  4883.2  329.11  4890.7   326.2  4974.8   313.2
  4989.4  311.36  4993.9  308.93  4996.6  308.43  4999.9  308.93  5017.8  312.17
  5138.1  309.96  5399.8  313.98  5535.9  331.65  5544.5  331.23  5609.5  330.75
  5626.6  332.55  5632.2   331.1  5654.9  333.18  5683.1  332.61  5693.3   334.6
  5715.4  333.15  5759.8   337.6  5909.9  345.95  6158.7  349.36  6328.3  354.61
#Mann= 5 ,-1 , 0
  4199.6     .16       0  4974.8     .12       0  4993.9     .07       0
  4999.9     .12       0  5544.5     .16       0
Bank Sta=4989.4,5017.8
XS Rating Curve= 0 ,0
Exp/Cntr=0.3,0.1

Type RM Length L Ch R = 1 ,116578  ,554,554,554
BEGIN DESCRIPTION:
BIG ELKHART CREEK 134.0
END DESCRIPTION:
XS GIS Cut Line= 3
      3787299.63     10540010.16      3786849.61     10540660.19
      3786449.61     10540910.19
#Sta/Elev= 30
  4208.3  359.34  4230.6  357.79  4236.7  352.62  4244.8  351.43  4338.1  349.27
    4359  343.85  4373.9  343.78    4380  339.55  4409.7   335.9  4415.8  331.83
  4430.6  327.13  4466.5  319.13  4524.6  316.52  4784.3  313.37    4905  310.88
  4976.6   312.3  4991.5  309.18  4995.9  306.18  5003.6   306.1  5006.3   305.6
  5009.6   306.1  5021.9   306.7  5027.8  311.47  5304.9  309.36  5340.9  314.63
  5347.4  320.78  5374.6  328.32  5389.8   329.7  5420.5  336.99  5470.6  342.47
#Mann= 5 ,-1 , 0
  4208.3     .16       0  4784.3     .12       0  5003.6     .07       0
  5009.6     .12       0  5374.6     .16       0
Bank Sta=4976.6,5027.8
XS Rating Curve= 0 ,0
Exp/Cntr=0.3,0.1

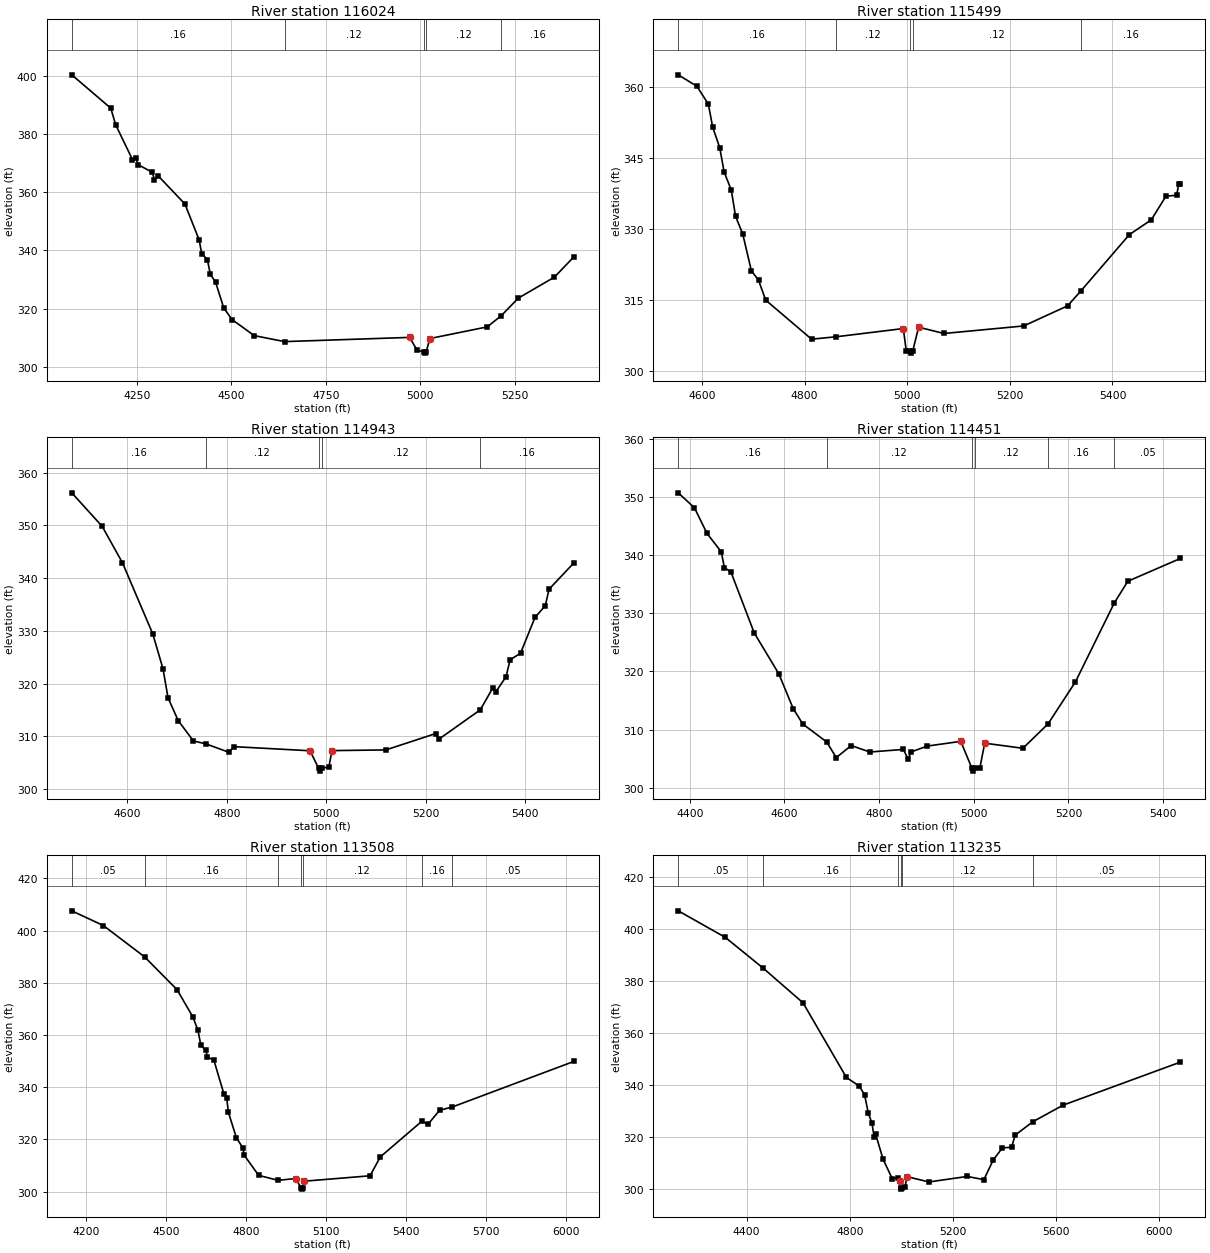
Type RM Length L Ch R = 1 ,116024  ,525,525,525
BEGIN DESCRIPTION:
BIG ELKHART CREEK 133.0
END DESCRIPTION:
XS GIS Cut Line= 3
      3786999.63     10539510.16      3786549.61     10540310.19
      3786149.63     10540410.18
#Sta/Elev= 30
    4077   400.4  4180.3  388.93  4193.4  383.19  4237.7  371.27  4246.9  371.96
  4252.6  369.49  4290.2  366.91    4296  364.34  4306.2  365.62  4376.9  355.95
  4414.5   343.6  4421.2  338.93  4436.2  336.83  4444.2  331.75  4457.9  329.15
  4479.6  320.24  4501.6  316.22  4560.5   310.7  4640.7  308.64    4972  310.09
    4992  305.63    5010  305.18  5012.7  304.68    5016  305.18  5025.8   309.7
  5177.9  313.71  5214.7  317.54  5260.3  323.62  5355.7  330.81  5407.2  337.79
#Mann= 5 ,-1 , 0
    4077     .16       0  4640.7     .12       0    5010     .07       0
    5016     .12       0  5214.7     .16       0
Bank Sta=4972,5025.8
XS Rating Curve= 0 ,0
Exp/Cntr=0.3,0.1

Type RM Length L Ch R = 1 ,115499  ,556,556,556
BEGIN DESCRIPTION:
BIG ELKHART CREEK 132.0
END DESCRIPTION:
XS GIS Cut Line= 3
      3786699.58      10539660.2      3786299.61     10539860.19
       3785949.6      10540260.2
#Sta/Elev= 30
  4553.6   362.5  4589.9   360.1  4612.3  356.33  4620.7   351.5  4634.6   347.1
    4643  342.03    4657  338.22  4665.4  332.65  4679.3  328.97  4696.1  321.23
  4710.1  319.21  4724.1  315.01  4813.5  306.78  4861.6  307.29  4992.4  309.02
    4998  304.34  5004.9  304.34  5007.7  303.84  5010.9  304.34  5022.1  309.31
  5071.5  307.98  5227.1  309.57  5312.6  313.81  5338.9     317  5433.1  328.83
  5475.8  331.94  5504.3  336.92  5525.2  337.11    5529  339.41  5532.3  339.41
#Mann= 5 ,-1 , 0
  4553.6     .16       0  4861.6     .12       0  5004.9     .07       0
  5010.9     .12       0  5338.9     .16       0
Bank Sta=4992.4,5022.1
XS Rating Curve= 0 ,0
Exp/Cntr=0.3,0.1

Type RM Length L Ch R = 1 ,114943  ,492,492,492
BEGIN DESCRIPTION:
BIG ELKHART CREEK 131.0
END DESCRIPTION:
XS GIS Cut Line= 3
      3786449.58     10539410.19      3785949.61     10539510.19
      3785549.59     10539810.21
#Sta/Elev= 30
  4488.2  356.15  4549.4  349.79  4590.1   342.9  4651.3  329.37  4671.7  322.78
  4681.9  317.27  4702.3  312.97  4732.9  309.11  4757.7  308.57  4804.3  306.96
  4814.5  308.03  4967.5  307.25  4984.9  303.89  4987.6  303.39  4990.9  303.89
  5005.4  304.22  5011.6  307.28  5119.9  307.41  5219.9   310.5  5226.2  309.42
  5309.9  315.01  5334.5  319.07  5340.8  318.39  5361.6  321.26  5369.9   324.5
  5390.8  325.73  5419.9  332.52  5440.8  334.77  5448.1  337.87  5498.1  342.86
#Mann= 5 ,-1 , 0
  4488.2     .16       0  4757.7     .12       0  4984.9     .07       0
  4990.9     .12       0  5309.9     .16       0
Bank Sta=4967.5,5011.6
XS Rating Curve= 0 ,0
Exp/Cntr=0.3,0.1

Type RM Length L Ch R = 1 ,114451  ,943,943,943
BEGIN DESCRIPTION:
BIG ELKHART CREEK 130.0
END DESCRIPTION:
XS GIS Cut Line= 3
      3786349.61     10539010.19      3785699.61     10539110.19
      3785299.57     10539060.18
#Sta/Elev= 30
  4375.7  350.71  4409.9  348.14  4436.4  343.74  4466.8  340.54  4473.1  337.86
    4487   337.1  4536.3  326.61  4588.2  319.58  4618.5  313.61  4638.8  310.95
  4689.4  307.85  4709.6  305.17  4741.2  307.24  4780.4  306.13  4851.2  306.57
  4861.4  304.94  4867.7  306.14  4901.8  307.15  4972.6  307.96  4996.2  303.34
    4999  302.84  5002.2  303.34  5013.1  303.43  5023.2  307.65  5103.9  306.77
  5156.8  310.94  5214.8  318.18  5297.2   331.8  5325.6   335.5  5436.5  339.42
#Mann= 6 ,-1 , 0
  4375.7     .16       0  4689.4     .12       0  4996.2     .07       0
  5002.2     .12       0  5156.8     .16       0  5297.2     .05       0
Bank Sta=4972.6,5023.2
XS Rating Curve= 0 ,0
Exp/Cntr=0.3,0.1

Type RM Length L Ch R = 1 ,113508  ,273,273,273
BEGIN DESCRIPTION:
BIG ELKHART CREEK 129.0
END DESCRIPTION:
XS GIS Cut Line= 3
       3786679.9       10538140.      3785603.51     10538563.61
      3785020.15     10538994.18
#Sta/Elev= 30
  4146.4  407.59  4264.7  401.95  4419.4  389.94  4540.9  377.38  4600.5  366.88
  4619.5  361.75  4630.3  356.01  4649.3  354.06  4654.6  351.59    4679  350.36
  4716.3  337.52    4727  335.96  4733.2  330.46    4763   320.7  4787.4  316.75
  4792.8   313.9  4846.9  306.19  4919.8  304.28  4985.1  304.98  5006.5  301.41
  5009.2  300.91  5012.5  301.41  5017.2  303.95  5264.4  306.02  5302.6  313.24
  5457.5  326.84    5482  325.82  5525.1  331.13  5572.8   332.4  6028.2  349.86
#Mann= 7 ,-1 , 0
  4146.4     .05       0  4419.4     .16       0  4919.8     .12       0
  5006.5     .07       0  5012.5     .12       0  5457.5     .16       0
  5572.8     .05       0
Bank Sta=4985.1,5017.2
XS Rating Curve= 0 ,0
Exp/Cntr=0.3,0.1

Type RM Length L Ch R = 1 ,113235  ,477,477,477
BEGIN DESCRIPTION:
BIG ELKHART CREEK 128.0
END DESCRIPTION:
XS GIS Cut Line= 3
      3786617.44     10537987.21       3785992.4     10538049.72
      3784965.22     10538875.63
#Sta/Elev= 30
  4135.1  407.04  4317.3  396.85  4464.2  385.02  4618.8  371.68    4787  342.99
  4836.6  339.68  4857.4  336.34  4871.8  329.32  4886.2  325.34  4894.2  320.17
  4900.6  321.07  4929.4  311.48  4964.6  304.13  4985.6  304.42  4993.4  303.38
  4996.8  300.57  4999.6  300.07  5002.8  300.57  5014.2  301.04  5022.2  304.86
    5107  302.83  5255.8  304.95  5319.8   303.7  5356.6  311.37  5391.8  315.92
    5427  316.16  5441.4  320.85  5510.1     326  5626.6  332.33  6081.3  348.88
#Mann= 6 ,-1 , 0
  4135.1     .05       0  4464.2     .16       0  4985.6     .12       0
  4996.8     .07       0  5002.8     .12       0  5510.1     .05       0
Bank Sta=4993.4,5022.2
XS Rating Curve= 0 ,0
Exp/Cntr=0.3,0.1