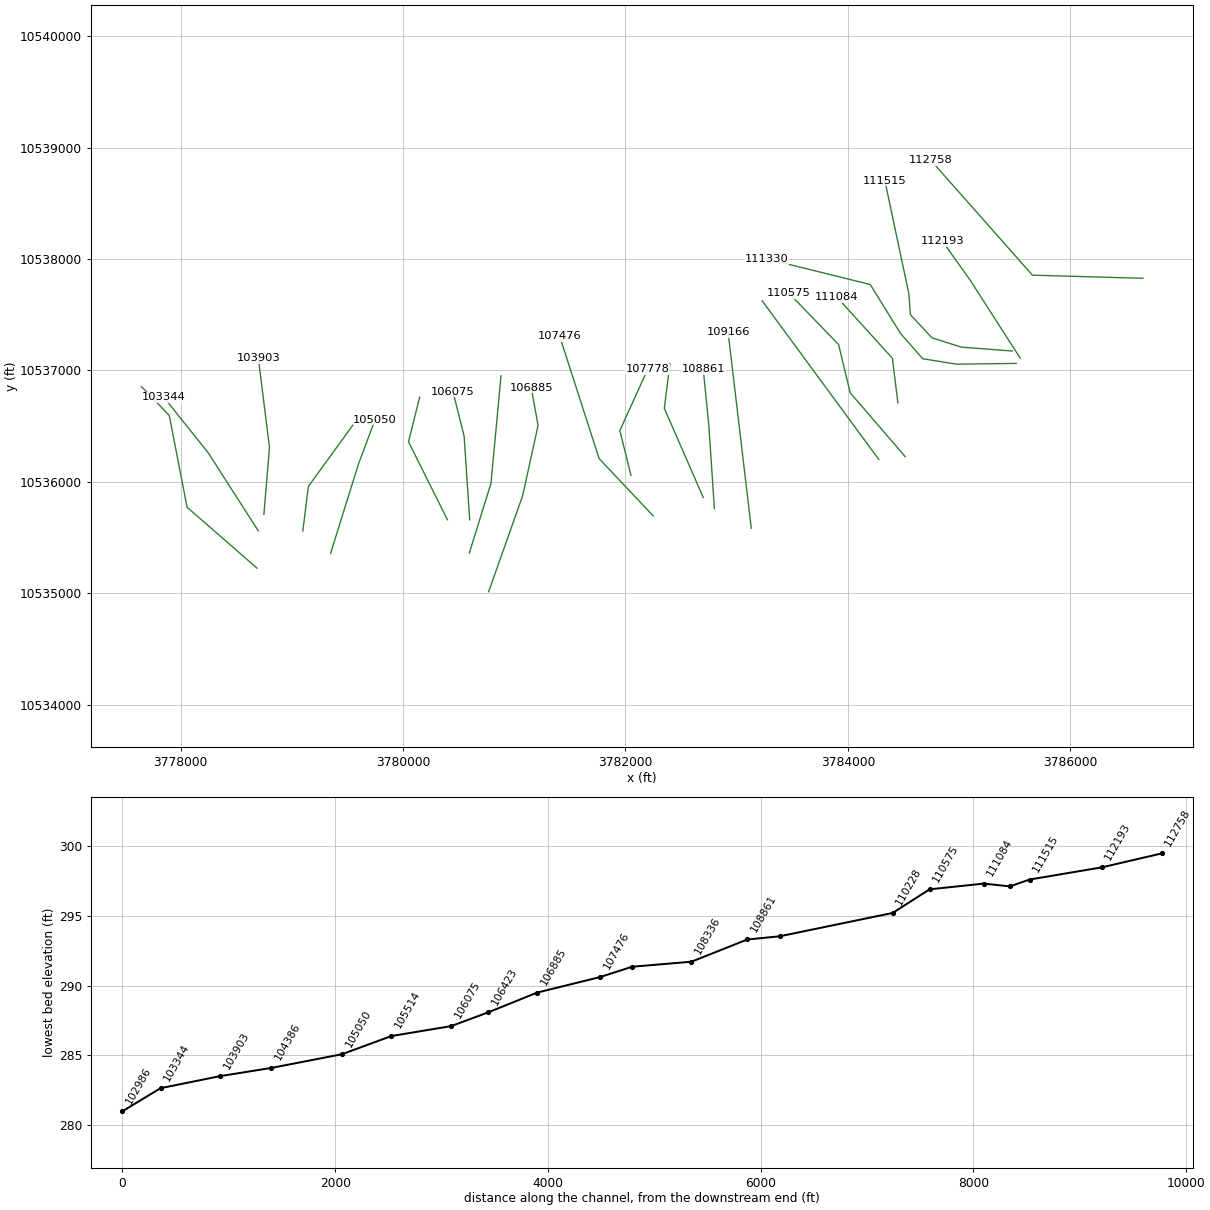
HEC-RAS study BIG ELKHART CREEK.prj: BIG ELKHART CREEK Base Level Engineering

--- BIG ELKHART CREEK.g01 (geometry) --- (continued)

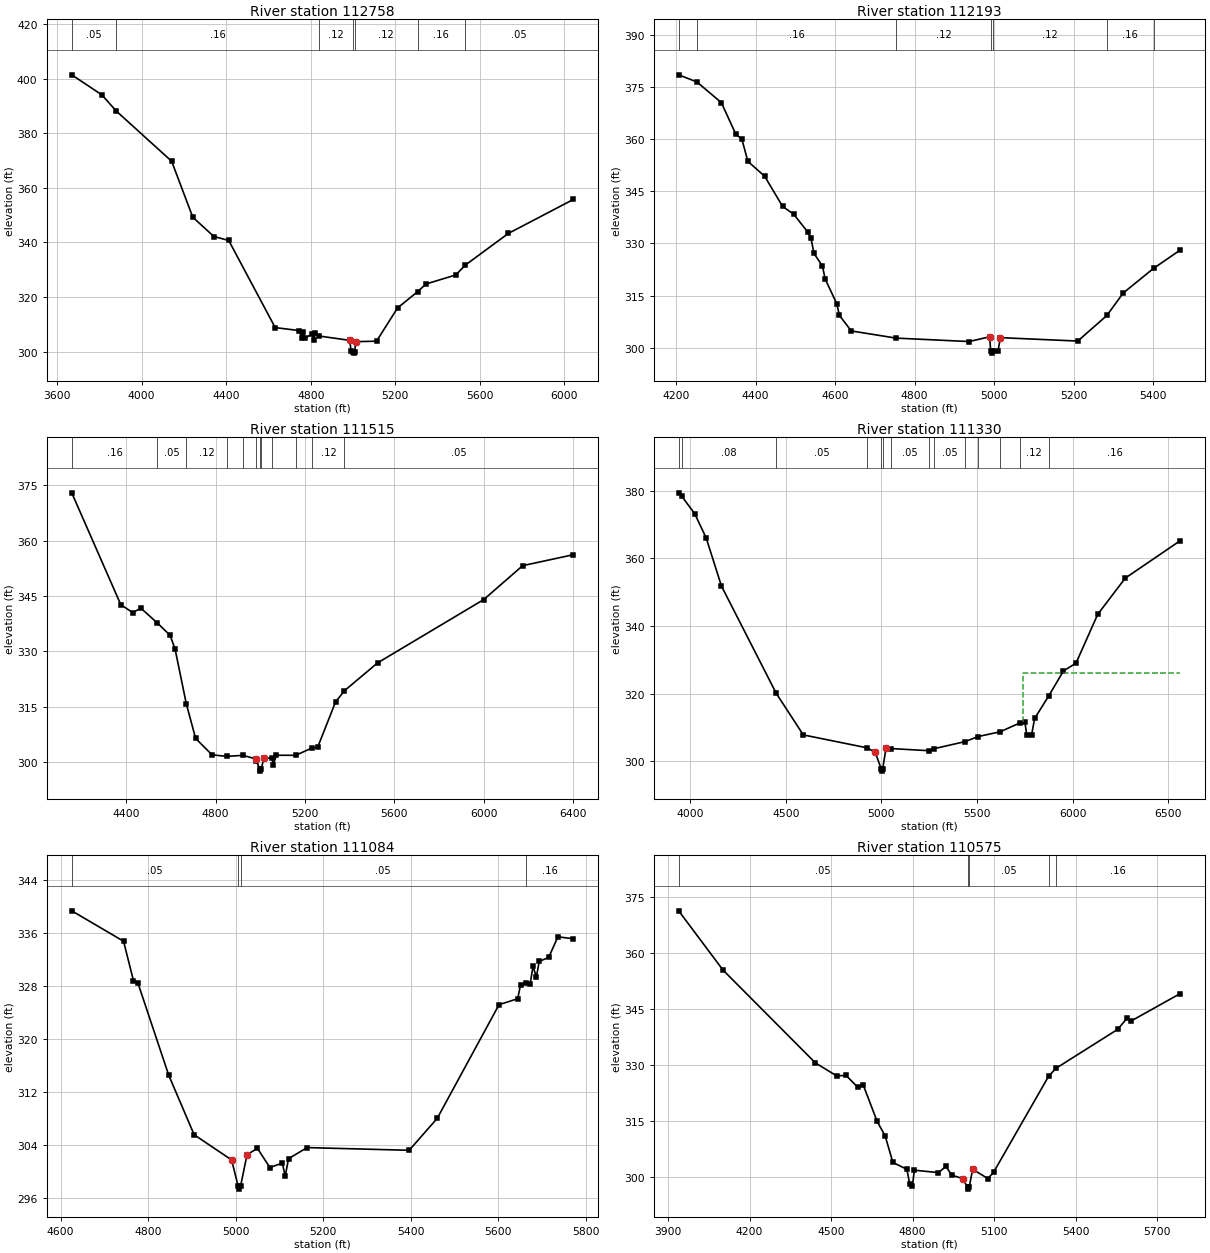
Type RM Length L Ch R = 1 ,112758  ,565,565,565
BEGIN DESCRIPTION:
BIG ELKHART CREEK 127.0
END DESCRIPTION:
XS GIS Cut Line= 3
      3786652.14     10537827.49      3785659.07     10537855.27
      3784743.48     10538888.78
#Sta/Elev= 30
  3669.1  401.42  3811.7  394.07    3880  388.14  4141.8  369.77  4241.9  349.26
  4341.9  342.18  4411.9  340.76    4632  308.81  4743.6  307.75  4757.9  305.17
  4764.5  307.31  4772.1  304.92  4807.2   306.5  4814.7  304.17  4821.4  306.66
  4838.5  305.74  4984.5  304.14  4991.2  300.25  5002.4  299.96  5005.2  299.46
  5008.4  299.96    5013  303.65  5111.6  303.84  5211.2  316.02  5305.8  321.96
  5345.8  324.79  5487.2  328.11  5530.8  331.65  5735.6  343.32  6043.3  355.77
#Mann= 7 ,-1 , 0
  3669.1     .05       0    3880     .16       0  4838.5     .12       0
  5002.4     .07       0  5008.4     .12       0  5305.8     .16       0
  5530.8     .05       0
Bank Sta=4984.5,5013
XS Rating Curve= 0 ,0
Exp/Cntr=0.3,0.1

Type RM Length L Ch R = 1 ,112193  ,678,678,678
BEGIN DESCRIPTION:
BIG ELKHART CREEK 126.0
END DESCRIPTION:
XS GIS Cut Line= 3
      3785549.62     10537110.17      3785099.61     10537810.19
      3784849.61     10538160.18
#Sta/Elev= 30
  4206.3  378.49  4252.1  376.44  4313.6   370.5    4350  361.43  4365.2  360.02
  4380.4  353.61  4422.6  349.32  4467.9  340.63  4495.3  338.46  4531.6  333.21
  4539.2  331.48  4546.8  327.12  4567.9  323.52  4574.9  319.78  4604.2  312.63
  4610.5  309.34  4640.6  304.84  4753.2  302.78  4937.1  301.79  4988.6  303.15
  4991.6  298.96  4994.3  298.46  4997.6  298.96  5009.8  299.05  5015.7  302.91
  5210.5  301.93  5283.8  309.29  5324.8  315.74  5401.2  322.83  5468.6  328.13
#Mann= 7 ,-1 , 0
  4206.3     .05       0  4252.1     .16       0  4753.2     .12       0
  4991.6     .07       0  4997.6     .12       0  5283.8     .16       0
  5401.2     .05       0
Bank Sta=4988.6,5015.7
XS Rating Curve= 0 ,0
Exp/Cntr=0.3,0.1

Type RM Length L Ch R = 1 ,111515  ,185,185,185
BEGIN DESCRIPTION:
BIG ELKHART CREEK 125.0
END DESCRIPTION:
XS GIS Cut Line= 6
      3785478.47     10537174.72      3785020.18     10537209.44
      3784756.29     10537292.77      3784561.85     10537501.11
      3784547.96     10537688.61      3784332.68     10538702.48
#Sta/Elev= 30
  4156.4  372.93  4375.9  342.66  4429.2  340.51  4466.1  341.69  4539.7  337.69
  4596.5  334.37  4618.9  330.66  4669.3  315.81    4711  306.44  4784.4  302.01
  4850.3  301.58  4922.6  301.86  4980.6   300.9  4982.8  300.35  4998.6  298.09
  5001.4  297.59  5004.6  298.09  5015.8  301.01  5052.2   301.2  5058.3  299.31
  5072.5  301.89    5159  301.87  5233.5   303.9    5257     304  5337.2  316.28
  5377.1  319.35    5526  326.91  6001.2  344.05    6175  353.21  6402.2  356.18
#Mann= 12 ,-1 , 0
  4156.4     .16       0  4539.7     .05       0  4669.3     .12       0
  4850.3     .05       0  4922.6     .12       0  4982.8     .16       0
  4998.6     .07       0  5004.6     .16       0  5052.2     .12       0
    5159     .05       0  5233.5     .12       0  5377.1     .05       0
Bank Sta=4980.6,5015.8
XS Rating Curve= 0 ,0
Exp/Cntr=0.3,0.1

Type RM Length L Ch R = 1 ,111330  ,246,246,246
BEGIN DESCRIPTION:
Mapping XS 551e6f8d
END DESCRIPTION:
XS GIS Cut Line= 6
      3785513.21     10537063.61      3784978.51     10537056.66
      3784672.96     10537105.27      3784471.57     10537334.44
      3784200.74     10537771.94       3783270.2      10538001.1
#Sta/Elev= 30
  3940.6  379.37  3956.6  378.35  4024.2  373.22  4084.2  366.05  4164.2   351.8
  4450.8  320.06    4592  307.81  4924.9  303.99  4967.5  302.67  5000.5   297.6
  5003.3   297.1  5006.5   297.6  5024.4  303.93  5047.9  303.78  5251.2  303.13
  5274.8  303.72  5436.7  305.82  5506.3  307.33  5621.1  308.73  5723.9  311.35
  5749.7  311.71    5760  307.82  5785.5  307.91  5801.2  312.69  5874.7  319.31
  5951.5  326.71  6017.5  329.03  6130.8  343.45  6274.9  354.16  6562.7  365.24
#Mann= 14 ,-1 , 0
  3940.6     .05       0  3956.6     .08       0  4450.8     .05       0
  4924.9     .12       0  5000.5     .07       0  5006.5     .12       0
  5047.9     .05       0  5251.2      .1       0  5274.8     .05       0
  5436.7     .16       0  5506.3     .05       0  5621.1     .16       0
  5723.9     .12       0  5874.7     .16       0
#XS Ineff= 2 , 0
       0                  5738.8       0  326.14
Permanent Ineff=
       F       F
Bank Sta=4967.5,5024.4
XS Rating Curve= 0 ,0
Exp/Cntr=0.3,0.1

Type RM Length L Ch R = 1 ,111084  ,509,509,509
BEGIN DESCRIPTION:
BIG ELKHART CREEK 124.0
END DESCRIPTION:
XS GIS Cut Line= 3
      3784449.61     10536710.16      3784399.61     10537110.19
      3783899.64     10537660.15
#Sta/Elev= 30
  4625.6   339.3    4744  334.71  4766.7  328.75  4776.8  328.41  4847.3  314.48
  4905.3  305.51    4991   301.7  5005.6   297.8  5008.3   297.3  5011.6   297.8
  5026.2  302.51    5050  303.45  5078.4  300.56  5106.8  301.23  5113.5  299.25
    5121   301.9  5163.6  303.57  5396.7  303.16  5460.9  307.99  5602.1  325.14
  5644.7  326.03  5651.4  328.18  5663.3  328.42  5673.1  328.22  5679.8  330.97
  5687.2  329.28    5694  331.67  5715.6  332.27  5736.6  335.38    5772  335.08
#Mann= 4 ,-1 , 0
  4625.6     .05       0  5005.6     .03       0  5011.6     .05       0
  5663.3     .16       0
Bank Sta=4991,5026.2
XS Rating Curve= 0 ,0
Exp/Cntr=0.3,0.1

Type RM Length L Ch R = 1 ,110575  ,347,347,347
BEGIN DESCRIPTION:
BIG ELKHART CREEK 123.0
END DESCRIPTION:
XS GIS Cut Line= 4
      3784515.51     10536226.85      3784020.72     10536799.77
      3783916.56     10537232.06      3783468.82     10537695.41
#Sta/Elev= 30
  3939.1  371.27  4102.1  355.44  4442.2  330.63  4520.1  327.17  4555.2  327.27
    4598  324.12  4618.8  324.61  4669.2  315.02  4698.9   311.1  4727.4  304.01
  4778.8  302.19  4789.1   298.3  4799.4  297.68  4806.1  301.95    4895  301.31
  4922.8  302.97  4943.4  300.63  4984.5  299.71  5002.1  297.39  5004.9  296.89
  5008.1  297.39  5020.8  302.18  5077.1  299.72  5097.7  301.38  5300.7  327.09
  5327.4  329.18  5554.6  339.59  5589.9  342.65    5604  341.83  5785.1  349.17
#Mann= 5 ,-1 , 0
  3939.1     .05       0  5002.1     .03       0  5008.1     .05       0
  5300.7     .12       0  5327.4     .16       0
Bank Sta=4984.5,5020.8
XS Rating Curve= 0 ,0
Exp/Cntr=0.3,0.1

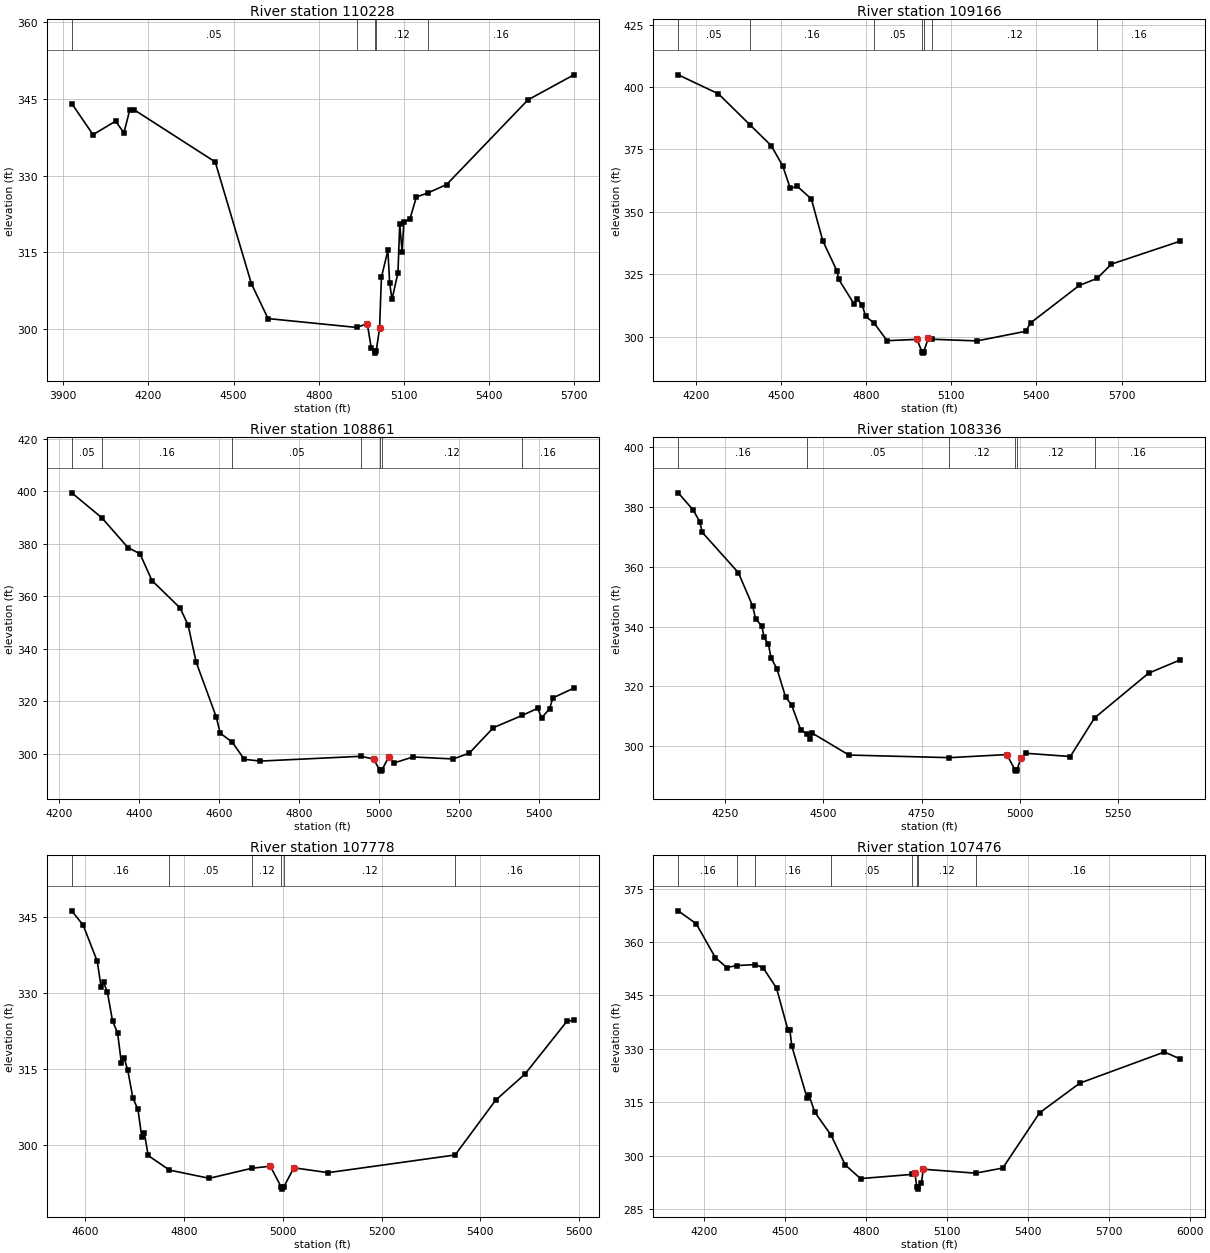
Type RM Length L Ch R = 1 ,110228  ,1062,1062,1062
BEGIN DESCRIPTION:
BIG ELKHART CREEK 122.0
END DESCRIPTION:
XS GIS Cut Line= 2
      3784277.14     10536202.48      3783228.84     10537625.67
#Sta/Elev= 30
  3930.4  344.11  4005.2     338  4084.6  340.66  4113.9  338.37  4134.7  342.87
  4149.4   342.9  4435.5  332.66  4562.9  308.78  4621.4  301.97  4933.7  300.23
  4970.8  300.98  4984.8  296.15  4996.4   295.7  4999.2   295.2  5002.4   295.7
  5014.1  300.09  5020.5  310.04  5043.3  315.34  5049.5  308.94  5057.8  305.73
  5078.8  310.96    5085  320.52  5093.5  315.06  5099.7  320.95  5120.5   321.4
  5143.6   325.8  5182.8  326.56  5250.1  328.23  5536.2  344.81    5698  349.73
#Mann= 5 ,-1 , 0
  3930.4     .05       0  4933.7     .12       0  4996.4     .07       0
  5002.4     .12       0  5182.8     .16       0
Bank Sta=4970.8,5014.1
XS Rating Curve= 0 ,0
Exp/Cntr=0.3,0.1

Type RM Length L Ch R = 1 ,109166  ,305,305,305
BEGIN DESCRIPTION:
BIG ELKHART CREEK 121.0
END DESCRIPTION:
XS GIS Cut Line= 2
       3783131.3     10535584.41      3782922.96      10537341.4
#Sta/Elev= 30
  4137.8  404.87  4279.5  397.27  4391.1  384.81  4465.9  376.49  4506.1  368.41
  4532.8  359.42  4556.5  360.32  4606.8  355.24  4647.1   338.5  4697.5  326.32
  4703.3  323.06  4757.9  313.11    4768  315.21  4786.1  312.81  4798.2  308.19
  4827.2  305.67  4873.8  298.52  4979.4  299.02  4996.6  294.03  4999.3  293.53
  5002.6  294.03  5019.7  299.68  5032.3  299.08  5190.9  298.42  5362.1  302.27
  5380.4   305.7  5550.9   320.6  5613.9  323.43  5664.2  329.13  5907.1  338.34
#Mann= 7 ,-1 , 0
  4137.8     .05       0  4391.1     .16       0  4827.2     .05       0
  4996.6     .03       0  5002.6     .05       0  5032.3     .12       0
  5613.9     .16       0
Bank Sta=4979.4,5019.7
XS Rating Curve= 0 ,0
Exp/Cntr=0.3,0.1

Type RM Length L Ch R = 1 ,108861  ,525,525,525
BEGIN DESCRIPTION:
BIG ELKHART CREEK 120.0
END DESCRIPTION:
XS GIS Cut Line= 3
      3782799.61     10535760.22      3782749.61     10536510.19
      3782699.61     10537010.17
#Sta/Elev= 30
    4232  399.43  4307.4  389.87  4372.3  378.55  4402.3  376.19  4432.4  365.96
  4502.6  355.53  4522.6  348.96  4542.7  334.86  4592.8  313.99  4602.8  307.78
  4632.9  304.34  4662.9  297.81    4703  297.13  4954.8  298.96  4986.1  297.88
  5000.7   293.8  5003.5   293.3  5006.7   293.8  5023.8  298.68  5036.4  296.39
  5084.1   298.7  5184.6  297.94  5224.8  300.14  5285.1  309.87  5357.8  314.59
  5395.7  317.26  5405.7  313.57  5425.8  317.17  5433.4   321.2  5486.1  324.96
#Mann= 7 ,-1 , 0
    4232     .05       0  4307.4     .16       0  4632.9     .05       0
  4954.8     .12       0  5000.7     .07       0  5006.7     .12       0
  5357.8     .16       0
Bank Sta=4986.1,5023.8
XS Rating Curve= 0 ,0
Exp/Cntr=0.3,0.1

Type RM Length L Ch R = 1 ,108336  ,558,558,558
BEGIN DESCRIPTION:
BIG ELKHART CREEK 119.0
END DESCRIPTION:
XS GIS Cut Line= 3
      3782699.63     10535860.15      3782349.61     10536660.19
      3782399.61     10537060.22
#Sta/Elev= 30
  4131.1  384.66    4169  378.93  4185.7  375.02  4192.3  371.44    4284  357.99
  4320.2  346.89  4327.6  342.66  4343.6  340.16  4349.4  336.35  4360.4  334.07
    4367  329.58  4382.2  325.85    4404  316.44  4419.2  313.86  4442.6  305.43
  4458.4  304.15    4466  302.31  4471.5  304.43    4565  297.08  4820.6  296.21
  4966.5  297.24  4986.9  292.21  4989.7  291.71  4992.9  292.21  5001.6  295.97
  5014.4  297.68  5127.8  296.59  5189.6  309.49  5326.8  324.42  5407.5  328.88
#Mann= 6 ,-1 , 0
  4131.1     .16       0  4458.4     .05       0  4820.6     .12       0
  4986.9     .07       0  4992.9     .12       0  5189.6     .16       0
Bank Sta=4966.5,5001.6
XS Rating Curve= 0 ,0
Exp/Cntr=0.3,0.1

Type RM Length L Ch R = 1 ,107778  ,302,302,302
BEGIN DESCRIPTION:
BIG ELKHART CREEK 118.0
END DESCRIPTION:
XS GIS Cut Line= 3
      3782049.62     10536060.15      3781949.61     10536460.19
      3782199.61     10537010.19
#Sta/Elev= 30
  4572.7  346.13  4595.9  343.28  4624.3  336.19    4632  331.16  4637.2  332.07
  4644.9  330.08  4655.2  324.47  4665.5  322.08  4673.2  316.11  4678.4  317.25
  4686.1  314.74  4696.4  309.29  4706.7  307.04  4714.5  301.53  4719.6  302.41
  4727.4  297.97  4770.4   295.1  4851.1  293.48  4937.9  295.47  4974.7  295.86
  4996.3  291.85  4999.1  291.35  5002.3  291.85  5022.4  295.55  5091.6  294.59
  5348.8  298.07    5431  308.87  5490.3     314  5574.9  324.35  5589.2  324.59
#Mann= 6 ,-1 , 0
  4572.7     .16       0  4770.4     .05       0  4937.9     .12       0
  4996.3     .07       0  5002.3     .12       0  5348.8     .16       0
Bank Sta=4974.7,5022.4
XS Rating Curve= 0 ,0
Exp/Cntr=0.3,0.1

Type RM Length L Ch R = 1 ,107476  ,591,591,591
BEGIN DESCRIPTION:
BIG ELKHART CREEK 117.0
END DESCRIPTION:
XS GIS Cut Line= 3
      3782249.34     10535695.56      3781763.24     10536209.44
      3781409.29     10537305.96
#Sta/Elev= 30
  4105.5  368.76  4172.2  365.12    4243  355.61  4285.5  352.84  4322.3  353.39
  4390.6  353.66  4419.8  352.78  4469.5  347.02  4511.6  335.36  4518.9   335.4
  4525.8  330.87  4582.4  316.29  4589.7  317.04  4610.7  312.29  4671.7  305.75
    4724  297.41  4780.6  293.57  4972.3  294.75  4981.8  295.23  4989.3  291.11
    4992  290.61  4995.3  291.11  5005.9  292.29  5013.3   296.2  5206.7  295.09
  5307.5  296.53  5444.1  312.06  5593.1  320.38  5906.5  329.12  5965.1  327.14
#Mann= 8 ,-1 , 0
  4105.5     .16       0  4322.3     .05       0  4390.6     .16       0
  4671.7     .05       0  4972.3     .12       0  4989.3     .07       0
  4995.3     .12       0  5206.7     .16       0
Bank Sta=4981.8,5013.3
XS Rating Curve= 0 ,0
Exp/Cntr=0.3,0.1

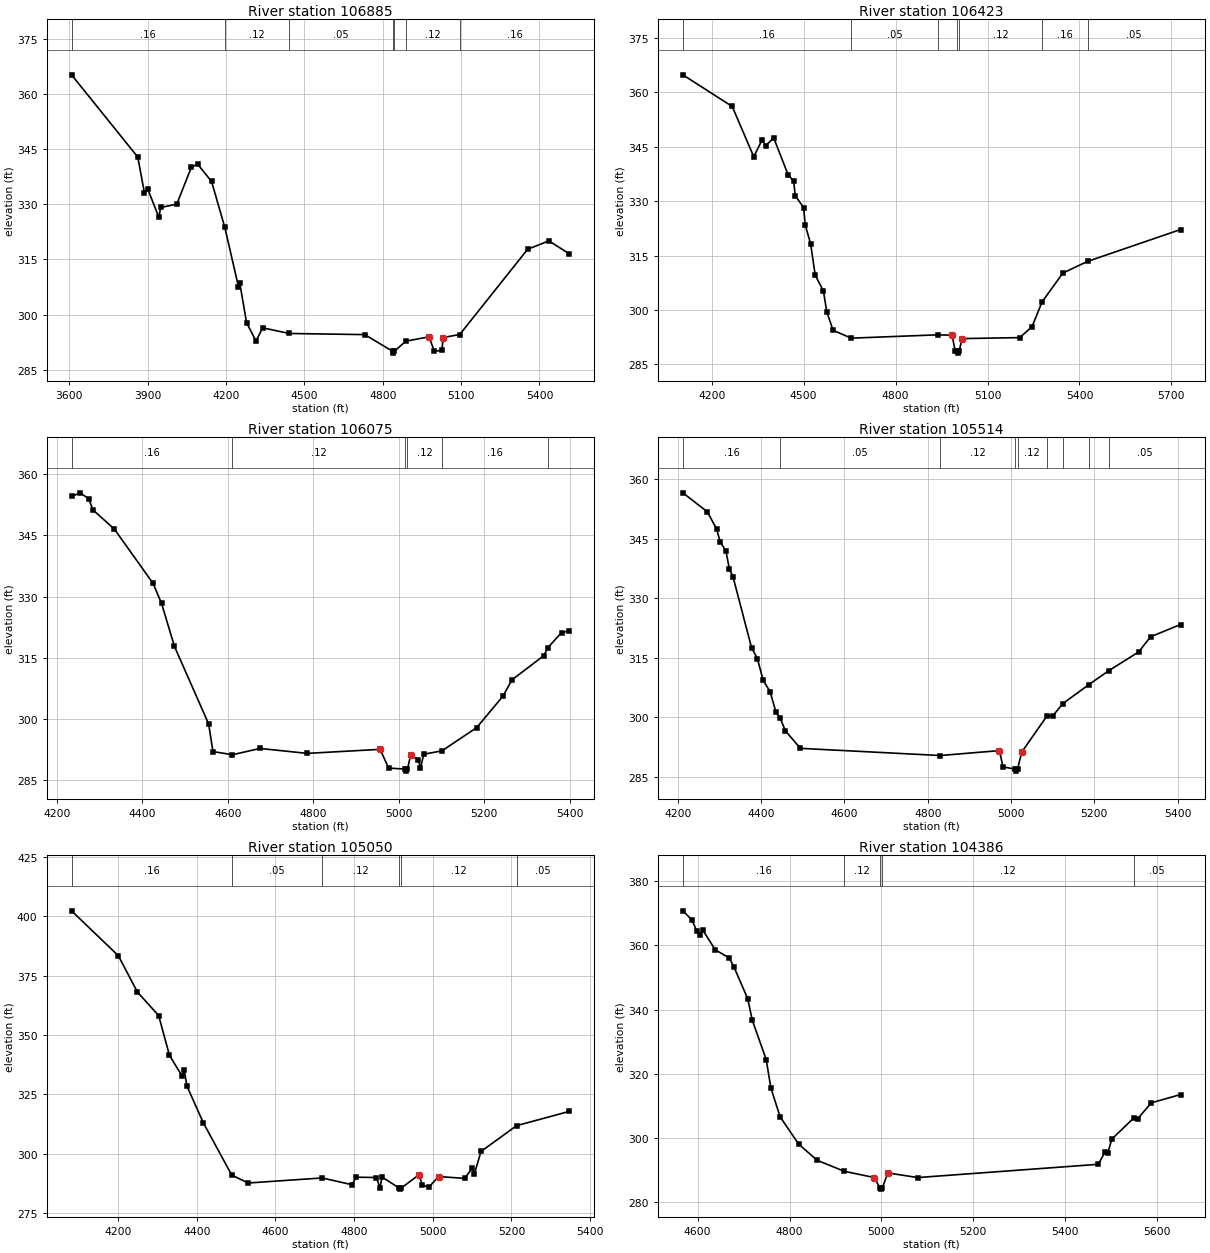
Type RM Length L Ch R = 1 ,106885  ,462,462,462
BEGIN DESCRIPTION:
Mapping XS 6a5f2b03
END DESCRIPTION:
XS GIS Cut Line= 4
      3780770.19     10535015.02      3781075.74     10535876.11
      3781214.62     10536508.05      3781152.41     10536846.76
#Sta/Elev= 30
  3608.7  365.27  3862.3  342.88  3887.9  333.03  3900.7  334.11  3943.1  326.47
  3949.6  329.15  4011.4  330.06  4067.8  340.17  4091.7  340.91  4144.7  336.24
  4195.4  323.73  4247.7  307.59    4253  308.48  4278.6   297.8  4314.8  292.78
  4340.3   296.4  4441.4  294.85  4731.3  294.54    4838     290  4840.8   289.5
    4844     290  4888.6  292.76  4977.1  293.93  4997.6     290  5026.4  290.26
  5031.5  293.75  5094.8  294.57  5354.6  317.78  5435.9  320.06  5513.8  316.56
#Mann= 7 ,-1 , 0
  3608.7     .16       0  4195.4     .12       0  4441.4     .05       0
    4838     .07       0    4844     .05       0  4888.6     .12       0
  5094.8     .16       0
#XS Ineff= 1 ,-1
    3857  4091.7  340.91
Permanent Ineff=
       F
Bank Sta=4977.1,5031.5
XS Rating Curve= 0 ,0
Exp/Cntr=0.3,0.1

Type RM Length L Ch R = 1 ,106423  ,348,348,348
BEGIN DESCRIPTION:
BIG ELKHART CREEK 116.0
END DESCRIPTION:
XS GIS Cut Line= 3
      3780596.57     10535362.21      3780791.01     10535987.22
      3780881.29     10536952.45
#Sta/Elev= 30
  4105.8  364.87  4266.8  356.14  4337.1  342.28  4364.4  346.91    4376  345.33
  4402.2  347.48  4449.3  337.26  4467.2  335.57  4472.5  331.52  4499.8  328.24
    4505  323.45  4522.6  318.29  4537.6  309.61  4564.5  305.21  4575.3  299.52
  4595.9  294.39  4655.2  292.21  4937.4  293.13  4984.3  293.02  4994.3  288.76
  5001.4  288.58  5004.1  288.08  5007.4  288.58  5016.6  292.09  5205.3  292.36
  5245.4  295.41    5278  302.23  5345.9  310.18  5426.4  313.39  5729.8  322.18
#Mann= 7 ,-1 , 0
  4105.8     .16       0  4655.2     .05       0  4937.4     .12       0
  5001.4     .07       0  5007.4     .12       0    5278     .16       0
  5426.4     .05       0
Bank Sta=4984.3,5016.6
XS Rating Curve= 0 ,0
Exp/Cntr=0.3,0.1

Type RM Length L Ch R = 1 ,106075  ,561,561,561
BEGIN DESCRIPTION:
BIG ELKHART CREEK 115.0
END DESCRIPTION:
XS GIS Cut Line= 3
      3780599.61     10535660.22      3780549.61     10536410.19
      3780449.62     10536810.14
#Sta/Elev= 30
  4234.7  354.59  4254.7  355.48  4274.8  354.02  4284.8  351.28  4334.9  346.56
  4425.1  333.27  4445.1  328.34  4475.2  317.78  4555.4  298.67  4565.4  291.91
  4610.9  291.13  4675.6  292.67  4785.9  291.46  4956.3  292.45  4976.3  287.85
  5014.3   287.6    5017   287.1  5020.3   287.6  5027.6  290.95  5045.6  289.94
  5050.8  287.87  5058.5  291.26  5100.9  292.08  5182.2  297.79    5244  305.57
  5264.6  309.52  5339.4  315.49  5348.1  317.37  5380.6  321.14  5398.6  321.56
#Mann= 6 ,-1 , 0
  4234.7     .16       0  4610.9     .12       0  5014.3     .07       0
  5020.3     .12       0  5100.9     .16       0  5348.1     .05       0
Bank Sta=4956.3,5027.6
XS Rating Curve= 0 ,0
Exp/Cntr=0.3,0.1

Type RM Length L Ch R = 1 ,105514  ,464,464,464
BEGIN DESCRIPTION:
BIG ELKHART CREEK 114.0
END DESCRIPTION:
XS GIS Cut Line= 3
       3780399.6     10535660.21      3780049.61     10536360.19
      3780149.61     10536760.18
#Sta/Elev= 30
  4212.1  356.63  4270.8  351.84  4293.1  347.51  4301.5  344.32  4315.5  341.92
  4323.9  337.32  4332.3  335.51    4377  317.55    4391  314.79  4404.9  309.31
  4421.7  306.41  4435.7   301.2  4445.6  299.84    4458  296.59  4494.4  292.14
  4829.8  290.33  4972.3  291.57  4980.7  287.46  5009.7  286.89  5012.5  286.39
  5015.7  286.89  5025.6  291.17  5086.3   300.3  5100.4  300.35  5124.5  303.44
  5186.7  308.21  5234.4  311.72  5306.5  316.47  5334.9  320.29    5407  323.39
#Mann= 9 ,-1 , 0
  4212.1     .16       0  4445.6     .05       0  4829.8     .12       0
  5009.7     .07       0  5015.7     .12       0  5086.3     .16       0
  5124.5     .12       0  5186.7     .16       0  5234.4     .05       0
Bank Sta=4972.3,5025.6
XS Rating Curve= 0 ,0
Exp/Cntr=0.3,0.1

Type RM Length L Ch R = 1 ,105050  ,664,664,664
BEGIN DESCRIPTION:
BIG ELKHART CREEK 113.0
END DESCRIPTION:
XS GIS Cut Line= 3
       3779349.6     10535360.17      3779599.61     10536160.19
      3779749.62     10536560.22
#Sta/Elev= 30
  4081.6  402.39  4200.5  383.47  4249.2  368.14  4303.2  358.23  4330.4  341.55
  4362.9  332.68  4368.2  335.12    4375  328.51  4416.9  312.96  4488.9  291.01
  4530.6  287.67  4718.8   289.8    4794  286.97  4806.1  290.11  4856.9  289.99
  4865.8  285.63  4871.1  290.19  4914.1  285.59  4916.9  285.09  4920.1  285.59
  4965.2  291.16  4973.2  286.83  4990.1  285.92    5015   290.4  5080.9  289.62
  5100.4  293.85  5105.8  291.43  5122.7  300.97  5213.2  311.84    5347  317.84
#Mann= 6 ,-1 , 0
  4081.6     .16       0  4488.9     .05       0  4718.8     .12       0
  4914.1     .07       0  4920.1     .12       0  5213.2     .05       0
Bank Sta=4965.2,5015
XS Rating Curve= 0 ,0
Exp/Cntr=0.3,0.1

Type RM Length L Ch R = 1 ,104386  ,483,483,483
BEGIN DESCRIPTION:
BIG ELKHART CREEK 112.0
END DESCRIPTION:
XS GIS Cut Line= 3
       3779099.6     10535560.14      3779149.61     10535960.19
      3779549.59     10536510.16
#Sta/Elev= 30
  4567.9  370.76  4588.1  367.85  4598.2  364.37  4605.7  363.28  4610.8  364.86
  4638.5  358.62  4668.7   356.1  4678.8  353.37    4709  343.42  4719.1  336.65
  4749.3  324.46  4759.4  315.63  4779.6  306.61  4819.9  298.12  4860.2  293.08
  4919.2  289.67  4984.6  287.71  4996.3  284.61    4999  284.11  5002.3  284.61
    5014  289.16  5078.9  287.71  5472.2  291.84  5486.9  295.74  5493.1  295.51
  5501.6   299.7  5549.9  306.34    5558  306.04  5587.4  310.97  5651.1  313.56
#Mann= 5 ,-1 , 0
  4567.9     .16       0  4919.2     .12       0  4996.3     .07       0
  5002.3     .12       0  5549.9     .05       0
Bank Sta=4984.6,5014
XS Rating Curve= 0 ,0
Exp/Cntr=0.3,0.1

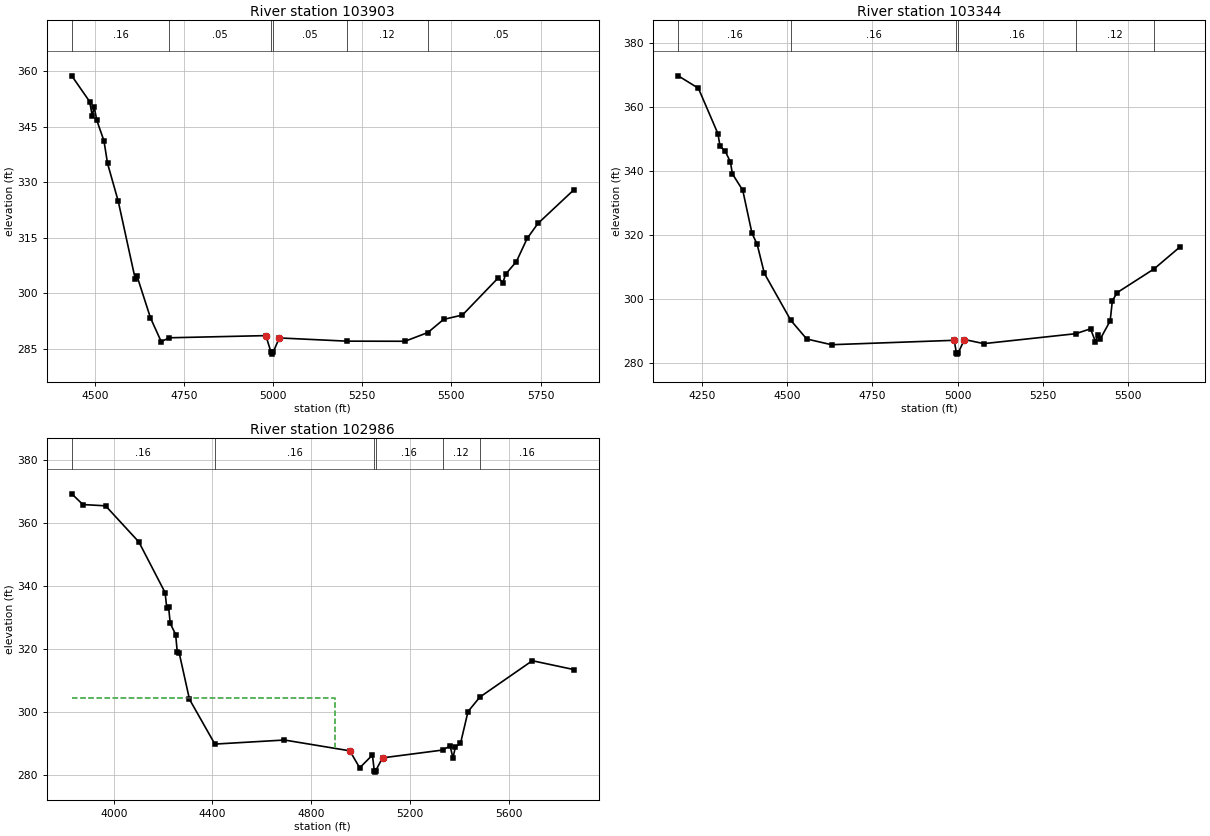
Type RM Length L Ch R = 1 ,103903  ,559,559,559
BEGIN DESCRIPTION:
BIG ELKHART CREEK 111.0
END DESCRIPTION:
XS GIS Cut Line= 3
      3778749.61      10535710.2      3778799.61     10536310.19
      3778699.61     10537110.19
#Sta/Elev= 30
  4435.1  358.81  4485.3  351.83  4492.8  347.88  4497.8  350.47  4505.3  346.77
  4525.4  341.22  4535.4  335.13  4565.5  324.86  4613.2   303.8  4618.2   304.6
  4655.9  293.32    4686  286.89  4708.2  287.94  4979.5  288.53    4994  284.02
  4996.8  283.52    5000  284.02  5017.1   287.9  5206.6  287.03  5369.7     287
  5434.1  289.37  5478.1  292.92    5531   294.1  5631.8   304.2  5644.4   302.8
  5651.9  305.14  5682.2  308.54  5712.4  314.81  5742.6  318.86  5843.4  327.97
#Mann= 6 ,-1 , 0
  4435.1     .16       0  4708.2     .05       0    4994     .03       0
    5000     .05       0  5206.6     .12       0  5434.1     .05       0
Bank Sta=4979.5,5017.1
XS Rating Curve= 0 ,0
Exp/Cntr=0.3,0.1

Type RM Length L Ch R = 1 ,103344  ,358,358,358
BEGIN DESCRIPTION:
BIG ELKHART CREEK 110.0
END DESCRIPTION:
XS GIS Cut Line= 3
      3778699.62     10535560.17      3778249.61     10536260.19
      3777849.61     10536760.19
#Sta/Elev= 30
  4180.5  369.84  4239.6  365.95  4297.1  351.67    4303  347.78  4318.2  346.24
  4333.4  342.88  4339.4  339.13  4369.7  333.99  4396.8  320.51    4412  317.05
  4433.1  307.95  4510.7  293.24  4557.3   287.4    4630  285.61  4989.9  286.99
  4996.1  283.16  4998.9  282.66  5002.1  283.16  5019.9  287.24  5076.7  285.95
  5346.3  289.06  5389.7  290.59  5404.1  286.54  5410.5  288.64  5418.5  287.44
  5447.3  293.09  5453.7  299.38  5468.1  301.95  5576.2  309.37    5653  316.33
#Mann= 6 ,-1 , 0
  4180.5     .16       0  4510.7     .16       0  4996.1     .03       0
  5002.1     .16       0  5346.3     .12       0  5576.2     .16       0
Bank Sta=4989.9,5019.9
XS Rating Curve= 0 ,0
Exp/Cntr=0.3,0.1

Type RM Length L Ch R = 1 ,102986  ,775,775,775
BEGIN DESCRIPTION:
BIG ELKHART CREEK 109.0
END DESCRIPTION:
XS GIS Cut Line= 4
      3778688.38     10535225.68      3778059.01     10535772.58
      3777898.42     10536597.23      3777647.88     10536856.41
#Sta/Elev= 30
  3830.1  369.34    3875  365.94  3967.1  365.53  4101.9  354.07  4208.3  337.98
  4214.9  333.16  4222.5  333.31  4229.1  328.22    4251  324.69  4257.6  319.11
  4265.3  318.86    4307  304.13  4409.9  289.91    4692   291.2  4956.9  287.77
  4996.7  282.37  5048.3  286.43  5055.8  281.51  5058.5  281.01  5061.8  281.51
  5089.3  285.54  5333.1  288.02  5363.2  289.34  5374.6  285.48  5384.8  289.06
  5405.2   290.1  5435.7  300.24  5483.6  304.82  5696.2  316.37  5864.5  313.56
#Mann= 6 ,-1 , 0
  3830.1     .16       0  4409.9     .16       0  5055.8     .07       0
  5061.8     .16       0  5333.1     .12       0  5483.6     .16       0
#XS Ineff= 2 , 0
         4897.73  304.53
Permanent Ineff=
       F       F
Bank Sta=4956.9,5089.3
XS Rating Curve= 0 ,0
Exp/Cntr=0.3,0.1