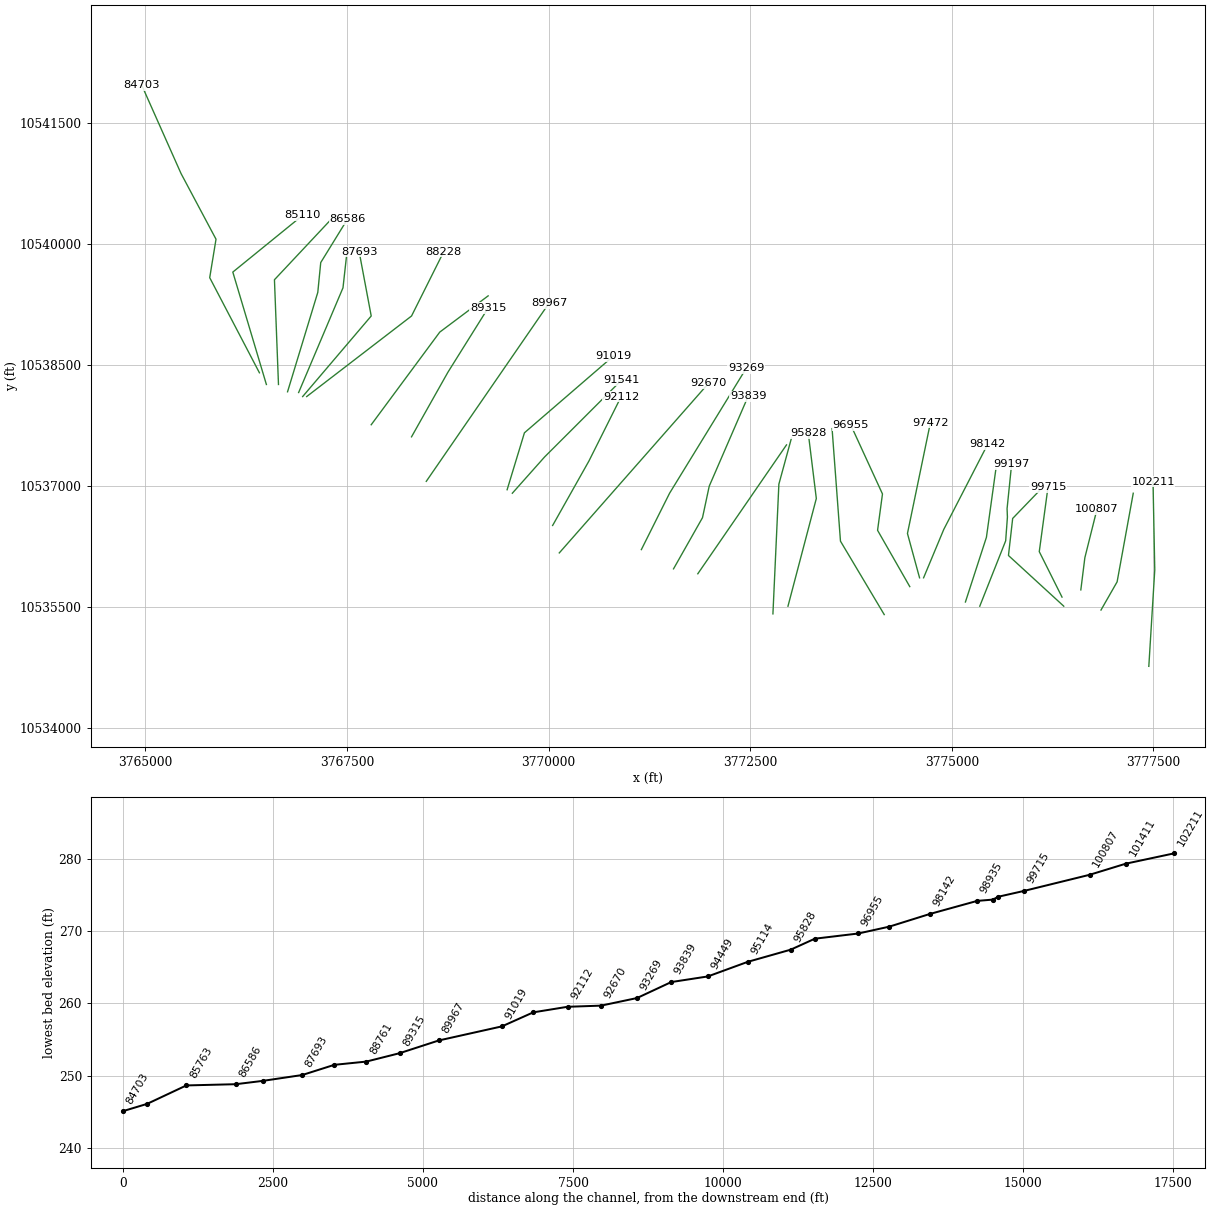
HEC-RAS study BIG ELKHART CREEK.prj: BIG ELKHART CREEK Base Level Engineering

--- BIG ELKHART CREEK.g01 (geometry) --- (continued)

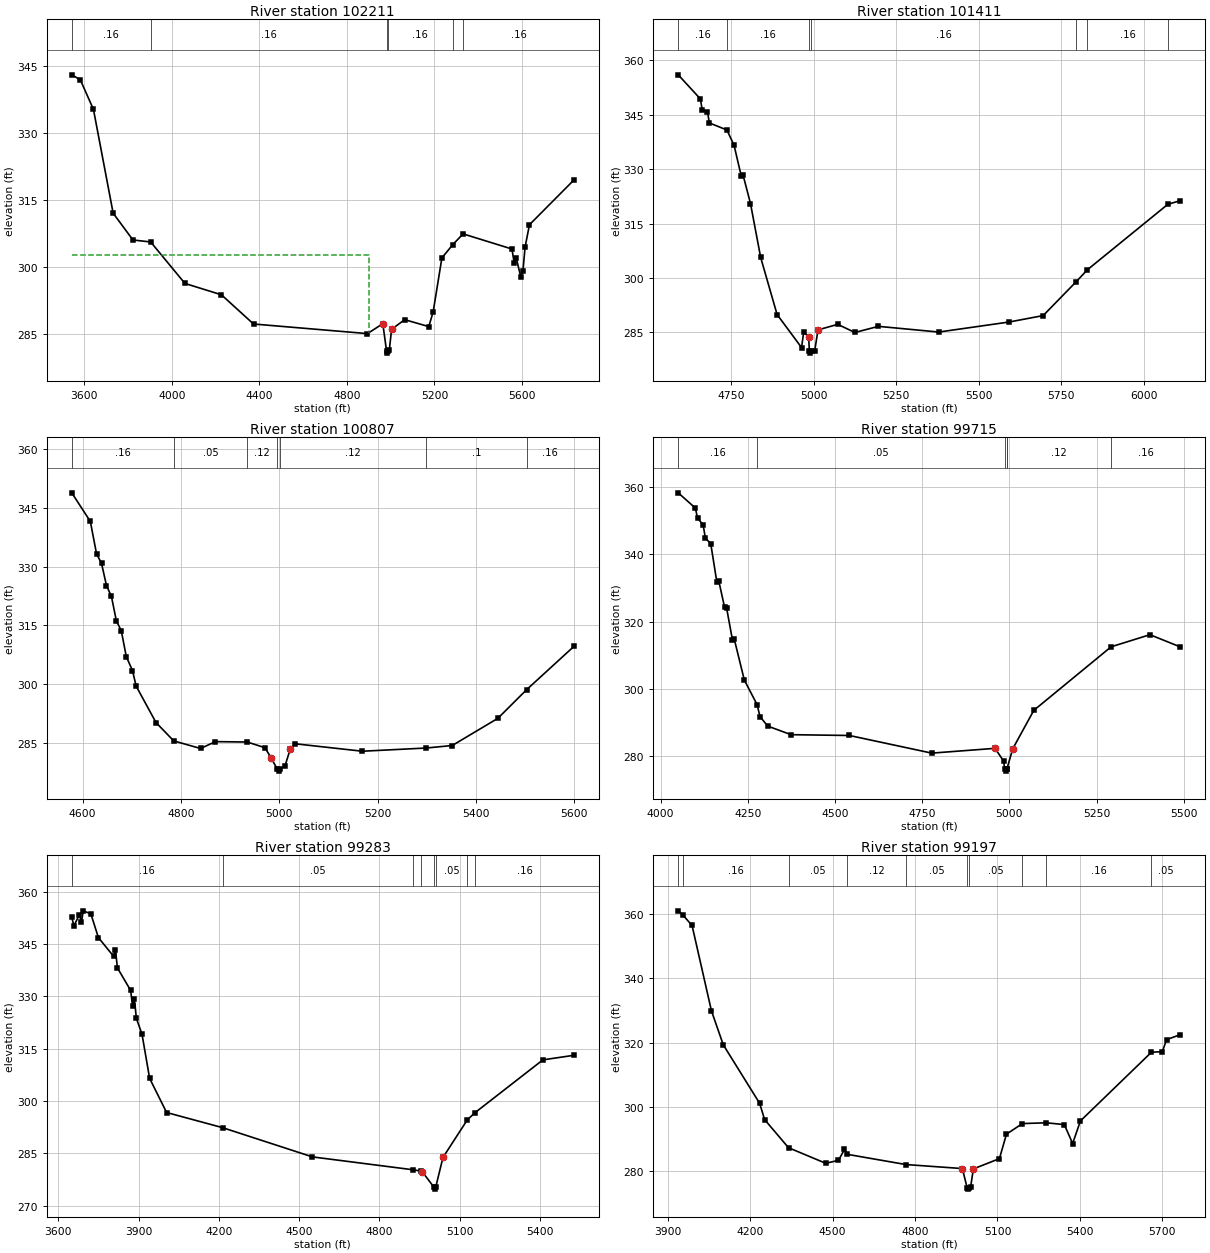
Type RM Length L Ch R = 1 ,102211  ,800,800,800
BEGIN DESCRIPTION:
BIG ELKHART CREEK 108.0
END DESCRIPTION:
XS GIS Cut Line= 3
      3777442.69     10534761.24      3777516.48     10535959.21
      3777494.78     10537052.96
#Sta/Elev= 30
    3543  343.04    3582  341.93  3642.1  335.29  3732.1  312.06  3822.5  306.06
  3903.6  305.62  4060.1  296.33  4226.6   293.8  4373.5  287.25  4894.2   285.1
  4964.3  287.32  4981.3  281.23    4984  280.73  4987.3  281.23  4994.3   281.5
  5004.3  286.06  5064.3  288.22  5174.3  286.67  5194.3  289.96  5234.3  302.06
  5284.3  305.03    5331  307.43  5554.4  304.04  5564.4  300.96  5574.4  301.92
  5594.4  297.88  5604.4  299.05  5614.4  304.48  5634.4  309.48  5837.2  319.48
#Mann= 6 ,-1 , 0
    3543     .16       0  3903.6     .16       0  4981.3     .07       0
  4987.3     .16       0  5284.3     .05       0    5331     .16       0
#XS Ineff= 2 , 0
         4900.57   302.6
Permanent Ineff=
       F       F
Bank Sta=4964.3,5004.3
XS Rating Curve= 0 ,0
Exp/Cntr=0.3,0.1

Type RM Length L Ch R = 1 ,101411  ,604,604,604
BEGIN DESCRIPTION:
BIG ELKHART CREEK 107.0
END DESCRIPTION:
XS GIS Cut Line= 3
       3776849.6     10535460.17      3777049.61     10535810.19
      3777249.62     10536910.22
#Sta/Elev= 30
  4589.1  356.02  4656.1  349.39  4661.8  346.39  4677.7  345.81  4683.4  342.76
  4736.7  340.81  4758.3  336.57  4779.9  328.17  4785.6  328.37    4808  320.55
  4838.9  305.67  4888.6  289.95  4962.7  280.85  4969.2  285.05  4984.3  283.83
  4986.4  279.81  4989.1  279.31  4992.4  279.81  5002.4  279.86  5012.6  285.72
  5072.3  287.24  5124.4     285  5195.5  286.69  5378.5  285.12  5591.9  287.89
  5694.8  289.66  5795.2  299.03  5828.7  302.28  6072.9  320.36  6110.3  321.32
#Mann= 7 ,-1 , 0
  4589.1     .16       0  4736.7     .16       0  4986.4     .07       0
  4992.4     .16       0  5795.2      .1       0  5828.7     .16       0
  6072.9     .05       0
Bank Sta=4984.3,5012.6
XS Rating Curve= 0 ,0
Exp/Cntr=0.3,0.1

Type RM Length L Ch R = 1 ,100807  ,1092,1092,1092
BEGIN DESCRIPTION:
BIG ELKHART CREEK 106.0
END DESCRIPTION:
XS GIS Cut Line= 3
       3776599.6     10535710.16      3776649.61     10536110.19
      3776799.61     10536710.18
#Sta/Elev= 30
  4577.9  348.81  4615.7   341.5  4628.3  333.23  4638.4  330.82  4648.5  325.15
  4658.6  322.36  4668.6  316.16  4678.7  313.58  4688.8  307.02  4701.4  303.45
  4708.9  299.47  4749.3  290.17  4785.4  285.48    4840  283.55  4870.2   285.3
    4935   285.2    4971  283.75  4983.6  281.13  4996.1  278.27  4998.8  277.77
  5002.1  278.27    5012   279.2  5022.3  283.32  5032.6  284.75  5169.2  282.85
  5299.2  283.67  5352.1  284.31  5444.9  291.25  5503.4  298.56  5599.5  309.59
#Mann= 7 ,-1 , 0
  4577.9     .16       0  4785.4     .05       0    4935     .12       0
  4996.1     .07       0  5002.1     .12       0  5299.2      .1       0
  5503.4     .16       0
Bank Sta=4983.6,5022.3
XS Rating Curve= 0 ,0
Exp/Cntr=0.3,0.1

Type RM Length L Ch R = 1 ,99715   ,432,432,432
BEGIN DESCRIPTION:
BIG ELKHART CREEK 105.0
END DESCRIPTION:
XS GIS Cut Line= 3
       3776366.3     10535620.67      3776084.18      10536184.9
      3776192.51     10536986.48
#Sta/Elev= 30
  4050.4  358.24  4099.5  353.71  4105.8  350.71  4121.9  348.72  4128.1   344.8
  4143.6  343.15    4161  331.79  4166.6  332.08  4183.4  324.18    4189  324.08
  4205.8  314.53  4211.3  314.66  4239.9   302.6  4276.7  295.27  4284.7  291.76
    4307  288.92  4374.1  286.37  4541.2  286.13  4777.4  280.89    4959  282.31
  4983.7  278.46  4986.3  276.04    4989  275.54  4992.3  276.04  4993.1  276.26
  5009.5  282.16    5070   293.6  5291.6  312.48    5403  316.08  5490.1  312.45
#Mann= 6 ,-1 , 0
  4050.4     .16       0  4276.7     .05       0  4986.3     .07       0
  4992.3     .05       0  4993.1     .12       0  5291.6     .16       0
Bank Sta=4959,5009.5
XS Rating Curve= 0 ,0
Exp/Cntr=0.3,0.1

Type RM Length L Ch R = 1 ,99283   ,86,86,86
BEGIN DESCRIPTION:
Mapping XS bd7ba50b
END DESCRIPTION:
XS GIS Cut Line= 4
        3776388.     10535507.82      3775702.24     10536137.16
      3775754.32     10536597.23      3776088.52     10536944.45
#Sta/Elev= 30
  3650.6  352.81  3658.3  350.18  3679.3  353.45  3686.7  351.26  3693.5  354.53
  3721.9  353.66  3750.2  346.83  3806.9  341.49  3813.7  343.41  3821.1  338.17
  3870.5  331.72  3877.9  327.11  3884.6  329.23    3892  323.68    3913  319.16
  3941.4   306.5  4004.9   296.7  4213.8  292.36  4549.9  283.97  4925.5  280.28
  4954.7  279.91  4959.9  279.74  5004.1  275.23  5006.9  274.73  5010.1  275.23
  5037.3   283.8  5128.4  294.61  5157.7  296.69  5410.8   311.8  5526.3   313.1
#Mann= 8 ,-1 , 0
  3650.6     .16       0  4213.8     .05       0  4925.5     .12       0
  4954.7     .05       0  5004.1     .04       0  5010.1     .05       0
  5128.4     .12       0  5157.7     .16       0
Bank Sta=4959.9,5037.3
XS Rating Curve= 0 ,0
Exp/Cntr=0.3,0.1

Type RM Length L Ch R = 1 ,99197   ,262,262,262
BEGIN DESCRIPTION:
Mapping XS 1851ac44
END DESCRIPTION:
XS GIS Cut Line= 5
      3775346.35     10535507.86      3775667.52     10536319.45
      3775689.22     10536614.59      3775684.88     10536718.76
       3775741.3     10537269.96
#Sta/Elev= 30
  3938.3  361.09  3954.4  359.86  3988.6  356.52  4059.1  329.93  4102.1  319.34
  4234.5  301.09  4252.7  296.01  4339.6  287.25  4475.1  282.39  4521.5  283.32
  4543.1   286.7  4553.9  285.18    4767     282  4972.3  280.75  4989.4  274.84
  4992.1  274.34  4995.4  274.84  5002.4  275.06  5012.4  280.65  5107.1  283.84
  5132.7  291.47  5190.7  294.77  5278.2  295.02  5343.4  294.44  5373.6  288.55
  5401.9   295.6  5660.4  317.02    5700  317.18  5715.4  320.93  5765.4   322.5
#Mann= 10 ,-1 , 0
  3938.3     .05       0  3954.4     .16       0  4339.6     .05       0
  4553.9     .12       0    4767     .05       0  4989.4     .04       0
  4995.4     .05       0  5190.7     .12       0  5278.2     .16       0
  5660.4     .05       0
Bank Sta=4972.3,5012.4
XS Rating Curve= 0 ,0
Exp/Cntr=0.3,0.1

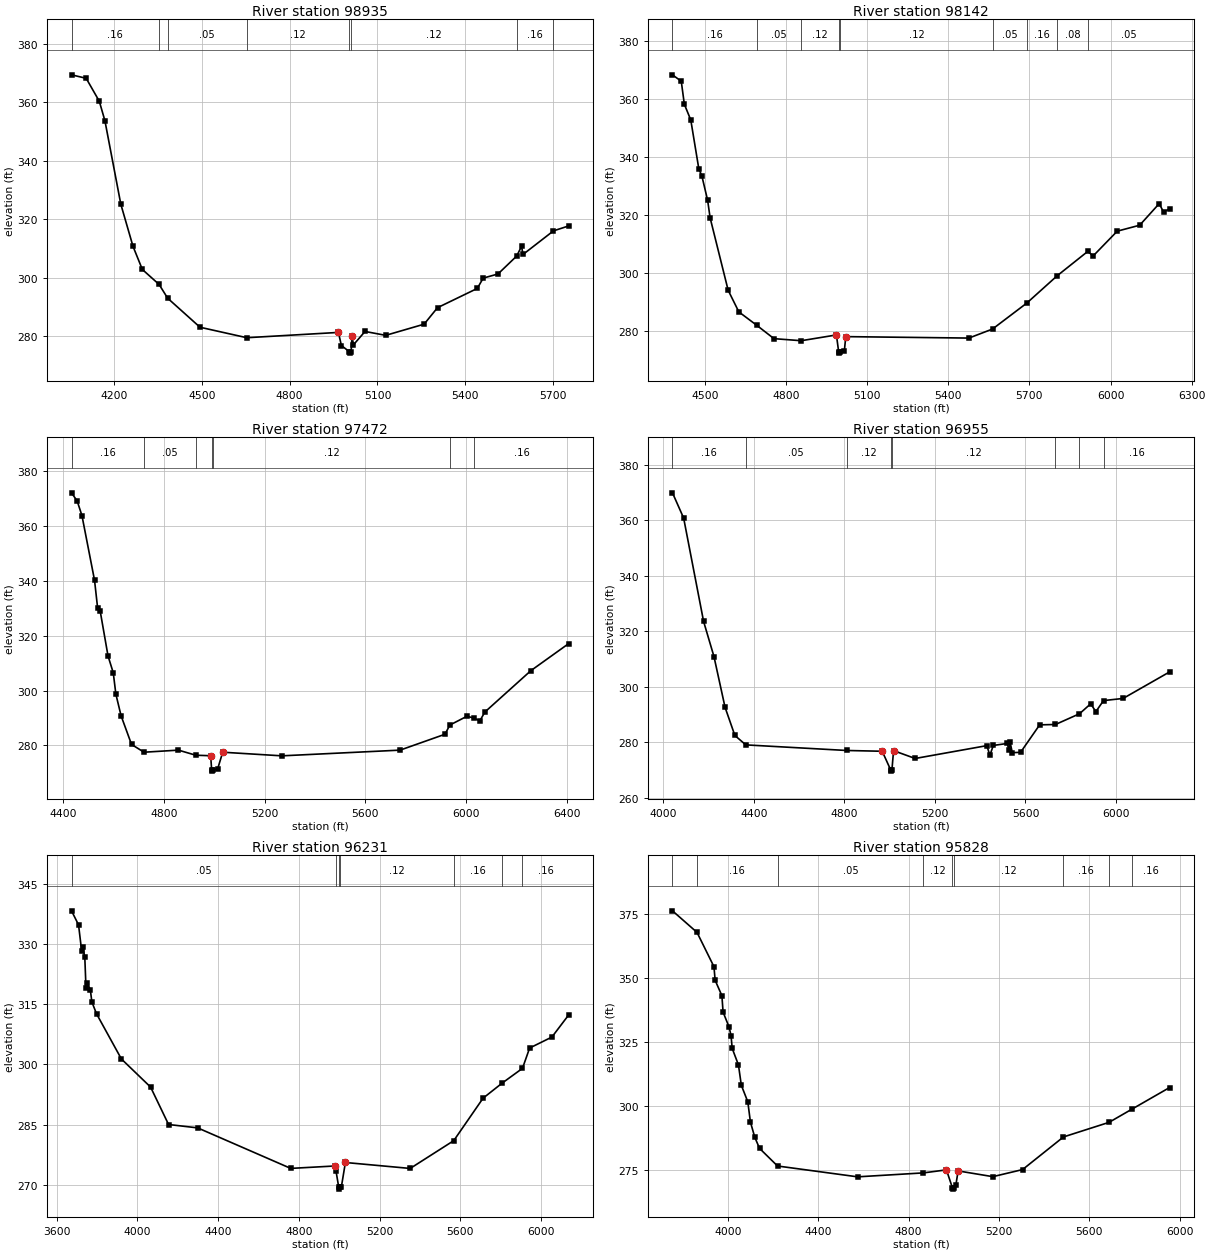
Type RM Length L Ch R = 1 ,98935   ,793,793,793
BEGIN DESCRIPTION:
BIG ELKHART CREEK 104.0
END DESCRIPTION:
XS GIS Cut Line= 3
      3775168.38     10535559.87       3775428.8     10536362.85
      3775545.99     10537209.22
#Sta/Elev= 30
  4054.6  369.32  4104.7  368.13  4149.5  360.29  4168.7  353.63  4223.1  325.06
  4264.6   310.7  4296.6  302.77  4353.9  297.64  4383.2  292.93  4493.7  283.01
  4653.6  279.43  4966.7  281.24  4976.8  276.75  5004.1  274.66  5006.9  274.16
  5010.1  274.66  5013.1     280  5018.1  277.01  5057.6  281.57  5128.3  280.24
  5259.5  284.06  5305.3   289.7  5441.2  296.28  5461.4  299.81  5511.9  301.22
  5575.7  307.34  5592.4  310.65  5597.5   307.9  5701.6  315.97  5753.2  317.64
#Mann= 8 ,-1 , 0
  4054.6     .16       0  4353.9     .08       0  4383.2     .05       0
  4653.6     .12       0  5004.1     .07       0  5010.1     .12       0
  5575.7     .16       0  5701.6     .05       0
Bank Sta=4966.7,5013.1
XS Rating Curve= 0 ,0
Exp/Cntr=0.3,0.1

Type RM Length L Ch R = 1 ,98142   ,670,670,670
BEGIN DESCRIPTION:
BIG ELKHART CREEK 103.0
END DESCRIPTION:
XS GIS Cut Line= 3
      3774649.59     10535860.15      3774899.61     10536460.19
      3775443.56     10537516.41
#Sta/Elev= 30
  4380.1  368.29  4412.6  366.07    4424  358.14  4447.8  352.72  4477.6  335.83
  4488.5  333.53  4510.1  325.03  4519.3  318.99    4586  294.01  4625.5  286.56
  4691.4  281.96  4755.5  277.33  4856.1  276.62  4986.3  278.61  4994.6  272.84
  4997.4  272.34  5000.6  272.84  5015.5  272.94  5020.9  278.03  5476.2  277.53
  5563.7  280.65  5690.3  289.59  5802.9  299.03  5915.4  307.38  5936.1  305.88
  6024.8  314.39  6107.8  316.44  6179.9  323.88  6196.5  320.91  6218.2  322.14
#Mann= 9 ,-1 , 0
  4380.1     .16       0  4691.4     .05       0  4856.1     .12       0
  4994.6     .07       0  5000.6     .12       0  5563.7     .05       0
  5690.3     .16       0  5802.9     .08       0  5915.4     .05       0
Bank Sta=4986.3,5020.9
XS Rating Curve= 0 ,0
Exp/Cntr=0.3,0.1

Type RM Length L Ch R = 1 ,97472   ,517,517,517
BEGIN DESCRIPTION:
BIG ELKHART CREEK 102.0
END DESCRIPTION:
XS GIS Cut Line= 3
       3774599.6     10535860.22      3774449.61     10536410.19
      3774734.22      10537785.8
#Sta/Elev= 30
  4433.2  372.15  4455.6  369.18  4474.6  363.86  4524.7  340.22  4536.8  330.19
  4547.2  328.95  4578.3  312.59    4599  306.51  4609.4  298.69  4630.1   290.8
  4671.6  280.34  4721.3   277.5  4858.1  278.26    4927   276.4    4986  276.22
  4989.9   271.1  4992.6   270.6  4995.9   271.1  5013.5  271.34  5033.9   277.5
  5268.8  276.18  5738.5  278.26  5916.8  284.05  5936.4  287.42    6004  290.61
  6033.1  289.94  6055.1  288.91  6075.5  292.17    6258  307.25    6408  317.11
#Mann= 7 ,-1 , 0
  4433.2     .16       0  4721.3     .05       0    4927     .12       0
  4989.9     .07       0  4995.9     .12       0  5936.4     .05       0
  6033.1     .16       0
Bank Sta=4986,5033.9
XS Rating Curve= 0 ,0
Exp/Cntr=0.3,0.1

Type RM Length L Ch R = 1 ,96955   ,724,724,724
BEGIN DESCRIPTION:
BIG ELKHART CREEK 101.0
END DESCRIPTION:
XS GIS Cut Line= 4
       3774478.3     10535750.84      3774078.98     10536449.66
      3774139.74     10536901.05      3773749.12     10537751.72
#Sta/Elev= 30
  4040.3  369.96  4089.7  360.85  4177.8   323.6  4223.6  310.96  4272.6  292.66
    4316   282.5  4364.3  279.11  4810.1  277.09  4967.1  276.81  5004.1  270.15
  5006.9  269.65  5010.1  270.15  5017.2  277.03  5112.7  274.21  5429.5  278.84
  5442.7  275.35    5458  278.91  5519.8  279.62  5526.9  277.14  5532.4     280
  5541.8  276.31  5578.4  276.42  5662.8  286.33  5732.7  286.46  5838.8  290.33
  5888.2  293.91  5911.2   291.1  5944.9  295.07  6031.6  295.85  6236.7   305.4
#Mann= 8 ,-1 , 0
  4040.3     .16       0  4364.3     .05       0  4810.1     .12       0
  5004.1     .07       0  5010.1     .12       0  5732.7     .16       0
  5838.8     .05       0  5944.9     .16       0
Bank Sta=4967.1,5017.2
XS Rating Curve= 0 ,0
Exp/Cntr=0.3,0.1

Type RM Length L Ch R = 1 ,96231   ,403,403,403
BEGIN DESCRIPTION:
BIG ELKHART CREEK 100.0
END DESCRIPTION:
XS GIS Cut Line= 3
      3774161.44     10535403.66      3773618.91     10536315.11
      3773514.74     10537712.63
#Sta/Elev= 30
  3674.2  338.22    3709  334.73  3724.6  328.15  3730.4  329.09    3740  326.64
    3746  318.89  3751.8  320.32  3767.4  318.56  3774.9  315.55  3798.2  312.57
  3921.3  301.33  4065.8  294.34  4154.9  285.02    4299  284.18  4760.1  274.09
  4980.7   274.7  4984.3  273.43  4997.7  269.43  5000.5  268.93  5003.7  269.43
  5010.7  269.45  5030.8  275.56  5351.7  274.08  5567.5     281  5712.7  291.57
  5808.1  295.36  5907.9     299  5943.3  304.06  6053.6  306.79  6136.3  312.27
#Mann= 7 ,-1 , 0
  3674.2     .05       0  4984.3     .12       0  4997.7     .07       0
  5003.7     .12       0  5567.5     .16       0  5808.1     .05       0
  5907.9     .16       0
Bank Sta=4980.7,5030.8
XS Rating Curve= 0 ,0
Exp/Cntr=0.3,0.1

Type RM Length L Ch R = 1 ,95828   ,714,714,714
BEGIN DESCRIPTION:
BIG ELKHART CREEK 99.0
END DESCRIPTION:
XS GIS Cut Line= 3
      3772967.87     10535507.85      3773319.43     10536844.62
      3773219.67     10537655.68
#Sta/Elev= 30
  3755.1  376.09  3863.6  367.68  3938.7  354.26  3943.8  348.98  3973.8  342.95
    3979  336.54  4005.7  330.67  4014.2  327.37  4019.3  322.38    4047  315.92
  4059.7  307.98  4088.4  301.51    4100   293.6  4119.4  287.63  4140.4  283.32
    4220  276.44  4574.4  272.21  4865.4  273.75  4967.3  274.93  4993.8  267.91
  4996.5  267.41  4999.8  267.91  5008.7  268.84    5019  274.52  5172.5  272.28
  5304.1  275.04  5485.1  287.79  5686.6  293.48  5789.3   298.7  5954.5  307.07
#Mann= 9 ,-1 , 0
  3755.1      .1       0  3863.6     .16       0    4220     .05       0
  4865.4     .12       0  4993.8     .07       0  4999.8     .12       0
  5485.1     .16       0  5686.6     .05       0  5789.3     .16       0
Bank Sta=4967.3,5019
XS Rating Curve= 0 ,0
Exp/Cntr=0.3,0.1

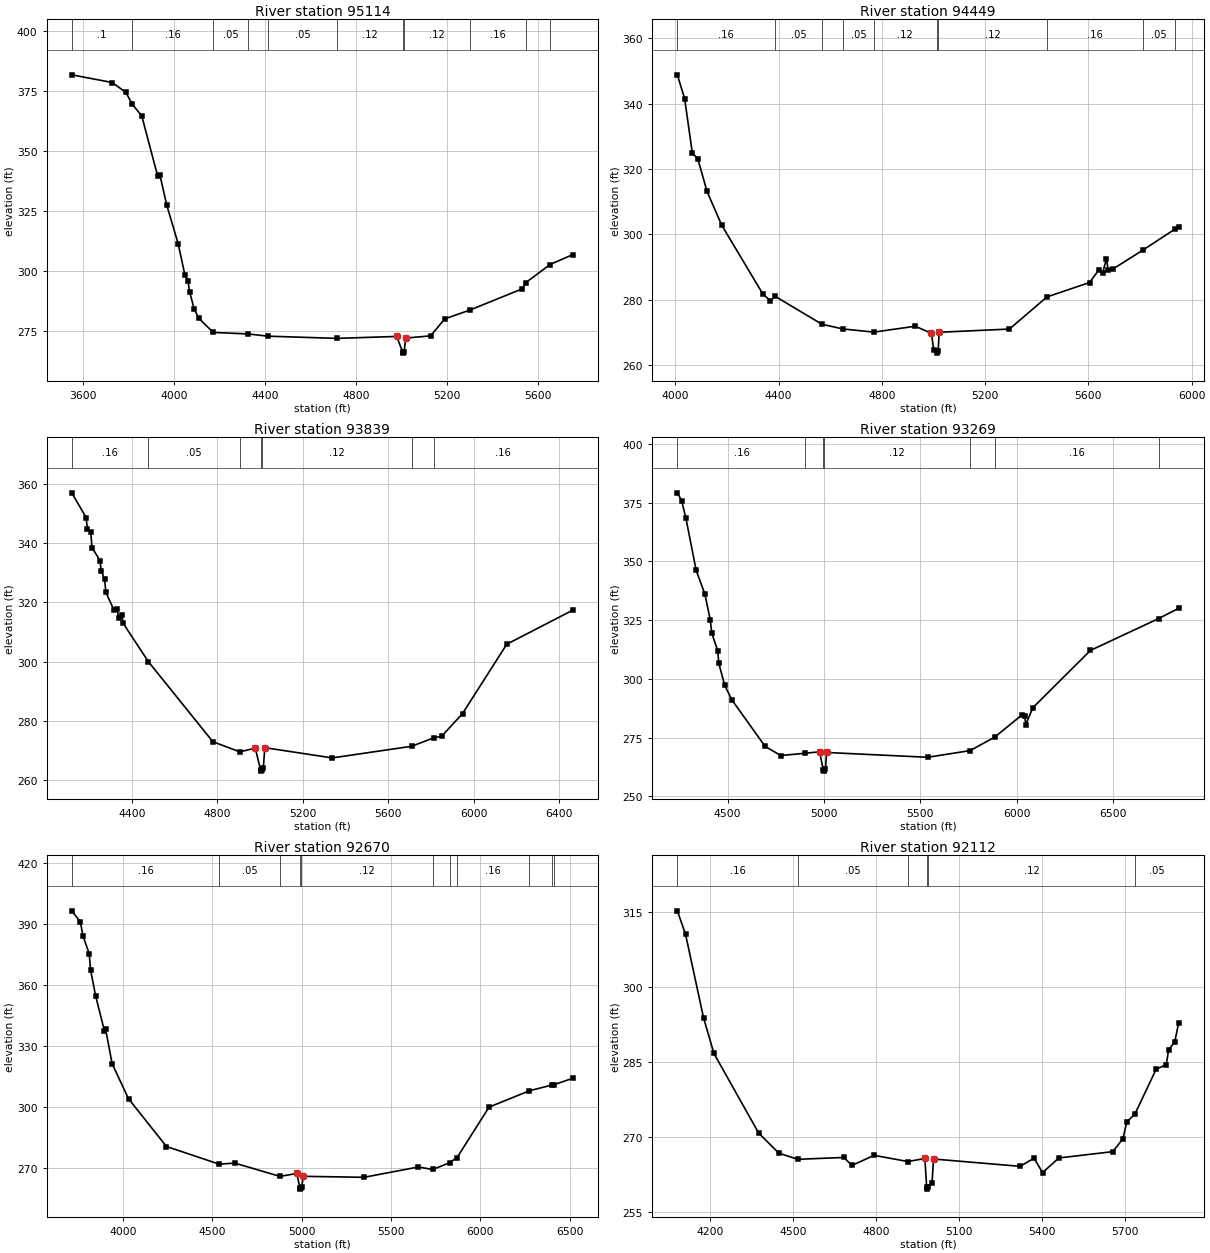
Type RM Length L Ch R = 1 ,95114   ,665,665,665
BEGIN DESCRIPTION:
BIG ELKHART CREEK 98.0
END DESCRIPTION:
XS GIS Cut Line= 3
      3772781.24     10535412.37      3772855.02     10537022.58
      3773011.23     10537595.36
#Sta/Elev= 30
    3550  381.79    3728  378.59  3788.1  374.47  3817.2  369.43  3858.1  364.66
  3928.2  339.52  3938.2  339.85  3968.3  327.38  4018.3  311.35  4048.3  298.18
    4062   295.7  4068.4  291.35  4088.4  284.27  4108.4  280.33  4172.7  274.35
  4325.3  273.74  4412.4   272.8  4717.3  271.88  4979.3  272.69  5006.3  266.23
  5009.1  265.73  5012.3  266.23  5019.4  272.01  5129.5  272.94  5190.5  279.99
  5300.2  283.64  5532.6  292.55  5547.2  295.07  5654.4  302.68  5755.6  306.86
#Mann= 11 ,-1 , 0
    3550      .1       0  3817.2     .16       0  4172.7     .05       0
  4325.3     .08       0  4412.4     .05       0  4717.3     .12       0
  5006.3     .07       0  5012.3     .12       0  5300.2     .16       0
  5547.2     .05       0  5654.4     .16       0
Bank Sta=4979.3,5019.4
XS Rating Curve= 0 ,0
Exp/Cntr=0.3,0.1

Type RM Length L Ch R = 1 ,94449   ,610,610,610
BEGIN DESCRIPTION:
BIG ELKHART CREEK 97.0
END DESCRIPTION:
XS GIS Cut Line= 3
      3771849.64     10535910.23      3772399.61     10536710.19
      3772949.61     10537510.19
#Sta/Elev= 30
    4008   348.8  4036.4  341.47  4066.1  324.88  4087.1  323.17    4123  313.14
  4179.8  302.84  4338.1  281.93  4367.9  279.71  4386.9  281.07  4568.2  272.54
  4649.2   271.1  4769.2  270.13  4929.4  271.93  4992.3  269.76  5001.1  264.57
  5012.2  264.21  5014.9  263.71  5018.2  264.21  5022.1  270.09  5294.3  271.07
  5439.7   280.9  5604.6   285.3  5640.4  289.12  5655.3  288.18  5670.2  292.62
  5676.3  289.27  5697.2  289.53  5810.7  295.18  5935.7  301.65  5949.6  302.33
#Mann= 10 ,-1 , 0
    4008     .16       0  4386.9     .05       0  4568.2     .08       0
  4649.2     .05       0  4769.2     .12       0  5012.2     .07       0
  5018.2     .12       0  5439.7     .16       0  5810.7     .05       0
  5935.7     .16       0
Bank Sta=4992.3,5022.1
XS Rating Curve= 0 ,0
Exp/Cntr=0.3,0.1

Type RM Length L Ch R = 1 ,93839   ,570,570,570
BEGIN DESCRIPTION:
BIG ELKHART CREEK 96.0
END DESCRIPTION:
XS GIS Cut Line= 4
      3771548.61     10535971.39      3771907.97     10536606.78
       3771991.3      10536997.4      3772474.71     10538114.95
#Sta/Elev= 30
  4117.9  357.06  4185.4   348.7  4191.1  344.95    4207  343.83  4212.8  338.55
  4250.3  334.16    4256  330.68  4271.9  327.81  4277.7  323.38  4315.2  317.49
  4331.1  317.91  4336.9  314.82  4352.8  315.87  4358.5  312.95  4476.4  299.99
  4778.6  272.88  4904.9  269.44  4977.4  270.72  5001.7  263.43  5004.5  262.93
  5007.7  263.43    5015  264.07  5021.8  270.86  5337.5   267.4  5709.3  271.33
  5812.2  274.18  5849.6  274.71  5947.6  282.39  6154.6  305.85  6464.9  317.41
#Mann= 7 ,-1 , 0
  4117.9     .16       0  4476.4     .05       0  4904.9     .12       0
  5001.7     .07       0  5007.7     .12       0  5709.3     .05       0
  5812.2     .16       0
Bank Sta=4977.4,5021.8
XS Rating Curve= 0 ,0
Exp/Cntr=0.3,0.1

Type RM Length L Ch R = 1 ,93269   ,599,599,599
BEGIN DESCRIPTION:
BIG ELKHART CREEK 95.0
END DESCRIPTION:
XS GIS Cut Line= 3
      3771149.61      10536210.2      3771499.61     10536910.19
      3772449.62     10538460.21
#Sta/Elev= 30
    4239  379.15  4261.3  375.83  4283.7  368.28  4336.8  346.11  4381.5  336.18
  4409.5  325.23  4417.9  319.44  4448.6   311.9  4454.2  306.53    4485  297.23
  4521.3  291.12  4694.6  271.23  4775.6  267.36  4903.8  268.34  4976.9  268.95
  4996.2  261.22    4999  260.72  5002.2  261.22  5007.6  261.48  5013.2  268.66
  5537.7  266.61  5757.8  269.45  5885.9  275.22  6025.3  284.53  6040.8  284.21
  6046.6  280.53  6083.4   287.7  6382.2  312.09  6735.3  325.62  6839.6  329.99
#Mann= 7 ,-1 , 0
    4239     .16       0  4903.8     .12       0  4996.2     .07       0
  5002.2     .12       0  5757.8     .05       0  5885.9     .16       0
  6735.3     .05       0
Bank Sta=4976.9,5013.2
XS Rating Curve= 0 ,0
Exp/Cntr=0.3,0.1

Type RM Length L Ch R = 1 ,92670   ,558,558,558
BEGIN DESCRIPTION:
BIG ELKHART CREEK 94.0
END DESCRIPTION:
XS GIS Cut Line= 2
      3770131.95      10536169.3      3771985.36     10538277.81
#Sta/Elev= 30
  3712.2  396.38  3760.8  390.87  3775.1  384.05  3810.2  375.33  3817.7  367.32
  3846.2  354.54  3895.6   337.3  3902.2  338.21  3938.2  321.33  4030.3  304.05
  4242.8  280.61  4537.5  271.96  4625.2  272.45  4878.3  265.93  4972.5  267.35
  4990.4  260.17  4993.1  259.67  4996.4  260.17  5000.9  260.52  5007.6  265.97
  5348.2  265.47  5652.8  270.53    5735  269.32  5828.2  272.66  5870.1  275.16
  6049.4  299.97  6275.7     308  6402.2  310.82  6410.9  310.94  6519.5  314.15
#Mann= 11 ,-1 , 0
  3712.2     .16       0  4537.5     .05       0  4878.3     .12       0
  4990.4     .07       0  4996.4     .12       0    5735     .08       0
  5828.2     .05       0  5870.1     .16       0  6275.7     .05       0
  6402.2     .16       0  6410.9     .05       0
Bank Sta=4972.5,5007.6
XS Rating Curve= 0 ,0
Exp/Cntr=0.3,0.1

Type RM Length L Ch R = 1 ,92112   ,571,571,571
BEGIN DESCRIPTION:
BIG ELKHART CREEK 93.0
END DESCRIPTION:
XS GIS Cut Line= 3
      3770049.59     10536510.15      3770499.61     10537310.19
      3770899.59     10538110.15
#Sta/Elev= 30
  4082.3  315.32    4112  310.61    4177  293.88  4214.6  286.72  4376.5  270.74
  4449.5  266.72  4517.5  265.49  4684.4  265.86  4713.4  264.25  4793.7  266.29
  4915.9  265.04  4977.3  265.66  4983.5  260.01  4986.3  259.51  4989.5  260.01
    5003  260.72  5008.6  265.55  5321.7  264.08    5372  265.72  5402.7  262.82
  5461.4  265.76  5657.1  267.03  5693.4  269.65  5707.4  273.03  5736.3  274.53
  5813.6  283.58  5849.9  284.46  5858.3  287.41  5880.7   289.1  5894.6  292.79
#Mann= 6 ,-1 , 0
  4082.3     .16       0  4517.5     .05       0  4915.9     .12       0
  4983.5     .07       0  4989.5     .12       0  5736.3     .05       0
Bank Sta=4977.3,5008.6
XS Rating Curve= 0 ,0
Exp/Cntr=0.3,0.1

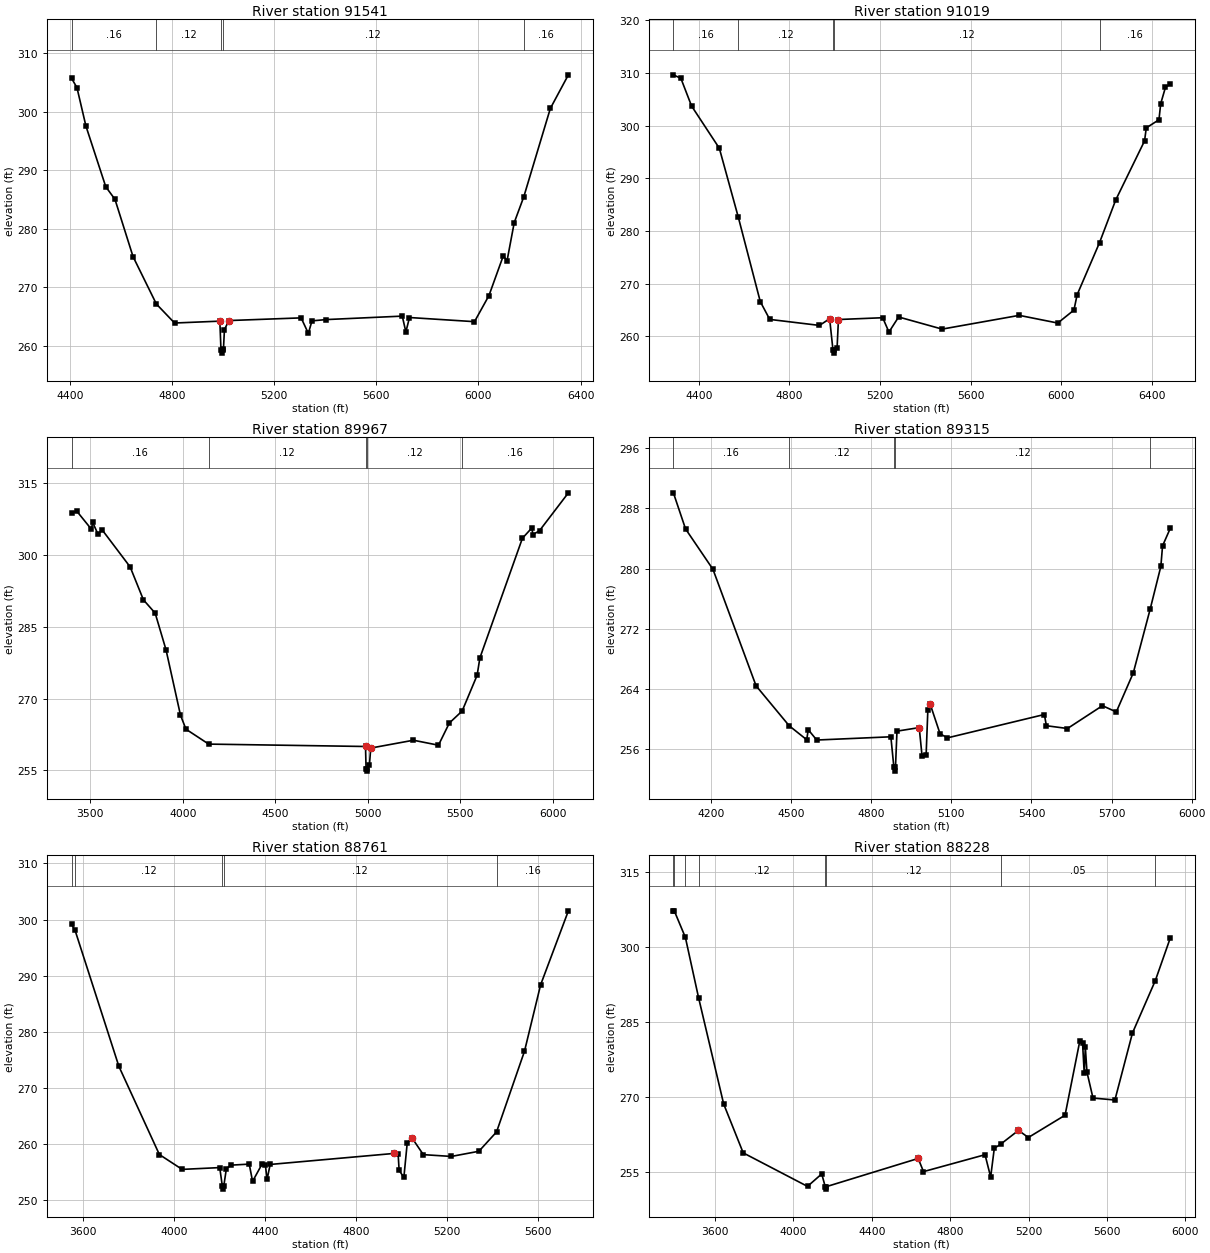
Type RM Length L Ch R = 1 ,91541   ,522,522,522
BEGIN DESCRIPTION:
BIG ELKHART CREEK 92.0
END DESCRIPTION:
XS GIS Cut Line= 3
      3769549.59     10536910.17      3769949.61     10537360.19
       3770899.6     10538310.18
#Sta/Elev= 30
  4406.7  305.76    4428  304.15  4463.2  297.57  4540.9  287.19  4576.9  285.04
  4647.6  275.25    4739  267.14  4810.2  263.89  4987.5  264.21    4992  259.24
  4994.8  258.74    4998  259.24  5001.7  259.47  5005.5  262.76  5022.9  264.31
  5305.8  264.77  5334.1  262.12  5348.2  264.26  5404.8  264.48  5701.8  265.07
  5715.9  262.37  5730.1  264.83  5984.6  264.12  6041.2  268.58  6097.7  275.42
  6111.9  274.48  6140.2  281.06  6177.5  285.46  6281.6  300.59  6352.3  306.34
#Mann= 5 ,-1 , 0
  4406.7     .16       0    4739     .12       0    4992     .07       0
    4998     .12       0  6177.5     .16       0
Bank Sta=4987.5,5022.9
XS Rating Curve= 0 ,0
Exp/Cntr=0.3,0.1

Type RM Length L Ch R = 1 ,91019   ,1052,1052,1052
BEGIN DESCRIPTION:
BIG ELKHART CREEK 91.0
END DESCRIPTION:
XS GIS Cut Line= 3
      3769485.03     10536953.46      3769699.61     10537660.19
      3770799.58     10538610.17
#Sta/Elev= 30
  4287.9  309.63    4321  308.96  4368.1  303.71  4490.6  295.69  4574.6  282.55
  4671.2  266.58    4713   263.2  4932.4  262.06  4977.2  263.33  4992.1   257.3
  4994.9   256.8  4998.1   257.3    5010  257.76    5016  263.18  5211.3  263.52
  5238.8   260.8  5281.5  263.66  5473.5  261.36  5813.5  263.97  5983.6  262.51
  6054.9  264.97  6069.1  267.89  6167.7  277.76  6239.1  285.86  6366.4  297.08
  6374.1  299.56    6430   301.1  6437.7  304.16  6458.5  307.23  6479.9  307.92
#Mann= 5 ,-1 , 0
  4287.9     .16       0  4574.6     .12       0  4992.1     .07       0
  4998.1     .12       0  6167.7     .16       0
Bank Sta=4977.2,5016
XS Rating Curve= 0 ,0
Exp/Cntr=0.3,0.1

Type RM Length L Ch R = 1 ,89967   ,652,652,652
BEGIN DESCRIPTION:
BIG ELKHART CREEK 90.0
END DESCRIPTION:
XS GIS Cut Line= 2
      3768482.44     10537057.67      3770005.24     10539270.28
#Sta/Elev= 30
  3398.4  308.76  3425.8  309.25  3506.3   305.4  3512.4  306.88  3542.2  304.32
  3563.2  305.33  3715.4  297.54  3787.1  290.66  3850.6  287.88  3909.5  280.18
  3987.3  266.58    4017  263.62  4139.9   260.5  4987.7     260  4990.7  255.35
  4993.5  254.85  4996.7  255.35  5008.6  256.04    5016  259.67  5246.7  261.31
    5382  260.27  5440.9  264.91    5510  267.41    5591  274.89  5605.9  278.51
  5835.9  303.54  5886.6  305.68  5892.7  304.28  5928.5  305.13  6084.4  313.03
#Mann= 5 ,-1 , 0
  3398.4     .16       0  4139.9     .12       0  4990.7     .07       0
  4996.7     .12       0    5510     .16       0
Bank Sta=4987.7,5016
XS Rating Curve= 0 ,0
Exp/Cntr=0.3,0.1

Type RM Length L Ch R = 1 ,89315   ,554,554,554
BEGIN DESCRIPTION:
BIG ELKHART CREEK 89.0
END DESCRIPTION:
XS GIS Cut Line= 3
      3768299.63     10537610.23      3768749.61     10538410.19
      3769249.59     10539210.16
#Sta/Elev= 30
  4058.7  290.05  4104.2  285.26  4206.9  279.89  4368.4  264.42  4492.5  259.11
  4558.1  257.26  4563.8  258.59  4595.7  257.22  4873.3  257.65  4884.6  253.59
  4887.4  253.09  4890.6  253.59  4896.2   258.4  4979.5  258.87  4990.1  255.12
  5005.4  255.27  5011.9  261.25  5020.8  261.96  5057.3  258.08  5084.4   257.5
  5448.2  260.61  5455.9  259.12  5534.9  258.75  5665.8  261.78  5717.7  260.95
  5781.4  266.14  5844.5  274.59  5884.6  280.28    5891  283.01  5919.9  285.33
#Mann= 5 ,-1 , 0
  4058.7     .16       0  4492.5     .12       0  4884.6     .07       0
  4890.6     .12       0  5844.5     .16       0
Bank Sta=4979.5,5020.8
XS Rating Curve= 0 ,0
Exp/Cntr=0.3,0.1

Type RM Length L Ch R = 1 ,88761   ,533,533,533
BEGIN DESCRIPTION:
BIG ELKHART CREEK 88.0
END DESCRIPTION:
XS GIS Cut Line= 3
      3767799.59     10537760.17      3768649.61     10538910.19
      3769249.64     10539360.21
#Sta/Elev= 30
  3551.5  299.15  3567.1  298.08  3759.3  273.83    3937   258.1  4036.9  255.45
  4201.8  255.77  4213.4  252.43  4216.2  251.93  4219.4  252.43  4231.1   255.6
  4251.9  256.21  4331.3  256.39  4345.9  253.32  4387.6   256.4  4402.2  256.19
  4409.5  253.65  4423.1  256.33    4968   258.3  4984.7  258.12  4988.9  255.29
  5009.7  254.01  5024.3  260.09  5045.1  261.08  5095.1  258.08    5218  257.76
  5338.9  258.68  5416.4  262.13  5538.9  276.51  5609.7  288.36  5731.6  301.56
#Mann= 5 ,-1 , 0
  3551.5     .16       0  3567.1     .12       0  4213.4     .07       0
  4219.4     .12       0  5416.4     .16       0
Bank Sta=4968,5045.1
XS Rating Curve= 0 ,0
Exp/Cntr=0.3,0.1

Type RM Length L Ch R = 1 ,88228   ,535,535,535
BEGIN DESCRIPTION:
BIG ELKHART CREEK 87.0
END DESCRIPTION:
XS GIS Cut Line= 3
      3766999.61     10538110.19      3768299.61     10539110.19
      3768699.63     10539910.23
#Sta/Elev= 30
  3387.8  307.26  3392.3  307.28    3449  301.95  3516.1  289.89  3644.2  268.56
  3743.9  258.75  4071.9  252.03  4144.5  254.53  4162.3  251.98    4165  251.48
  4168.3  251.98  4636.5  257.63  4663.6  254.99  4977.5  258.38  5006.2  253.91
  5024.8  259.68  5056.6  260.47  5148.1  263.26  5198.4  261.83  5385.7   266.3
  5461.2  281.23  5475.1  280.68  5483.5  274.74  5489.1  279.97  5497.5  274.93
  5528.2  269.74    5640  269.35  5729.5  282.78  5846.1  293.29  5922.4  301.83
#Mann= 8 ,-1 , 0
  3387.8     .16       0  3392.3     .12       0    3449     .16       0
  3516.1     .12       0  4162.3     .07       0  4168.3     .12       0
  5056.6     .05       0  5846.1     .16       0
#XS Ineff= 1 ,-1
  5461.2  5721.1  281.23
Permanent Ineff=
       F
Bank Sta=4636.5,5148.1
XS Rating Curve= 0 ,0
Exp/Cntr=0.3,0.1

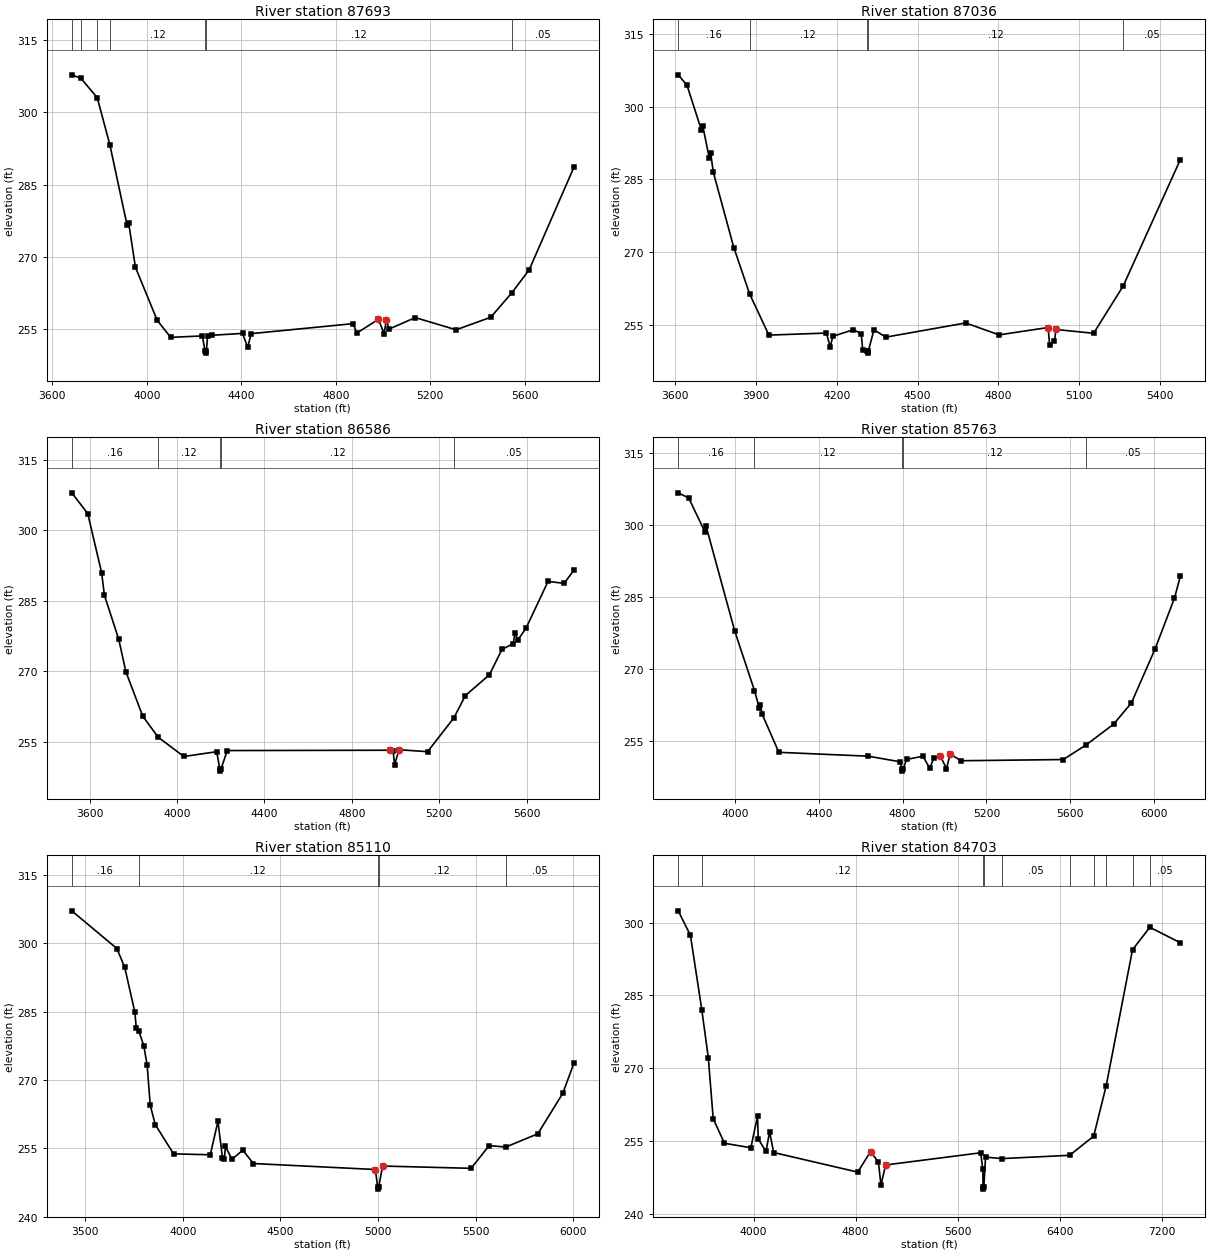
Type RM Length L Ch R = 1 ,87693   ,657,657,657
BEGIN DESCRIPTION:
BIG ELKHART CREEK 86.0
END DESCRIPTION:
XS GIS Cut Line= 3
      3766949.61     10538110.19      3767799.61     10539110.19
      3767649.61      10539910.2
#Sta/Elev= 30
    3682   307.8  3720.3   307.1  3789.9  303.06  3843.5  293.25  3916.5  276.55
  3923.1  277.03  3951.6  267.88  4043.9  256.87    4101  253.34    4235  253.64
  4246.2  250.57    4249  250.07  4252.2  250.57    4257  253.52  4277.8  253.78
  4405.2  254.16  4427.2  251.26  4441.5  254.11  4874.2  256.19  4888.5  254.21
  4980.7  257.08  5004.6  254.13  5014.8  256.98  5025.8  255.06  5136.9  257.44
  5309.8  254.91  5456.5  257.51  5545.7  262.58  5619.3  267.35  5808.4   288.6
#Mann= 7 ,-1 , 0
    3682     .16       0  3720.3     .12       0  3789.9     .16       0
  3843.5     .12       0  4246.2     .07       0  4252.2     .12       0
  5545.7     .05       0
Bank Sta=4980.7,5014.8
XS Rating Curve= 0 ,0
Exp/Cntr=0.3,0.1

Type RM Length L Ch R = 1 ,87036   ,450,450,450
BEGIN DESCRIPTION:
BIG ELKHART CREEK 85.0
END DESCRIPTION:
XS GIS Cut Line= 3
      3766899.61     10538160.18      3767449.61     10539460.19
      3767499.61     10539910.15
#Sta/Elev= 30
  3611.3  306.54  3643.9  304.39  3696.9  295.24  3702.4  296.04  3726.1  289.51
  3731.5  290.48  3741.6  286.48  3817.6     271  3876.4  261.44  3947.9  252.97
  4161.4  253.39  4175.9   250.5  4185.1  252.72  4261.6  254.07  4290.7  253.29
  4296.1     250  4311.4  249.76  4314.1  249.26  4317.4  249.76  4338.1  254.06
  4382.2  252.55  4678.6  255.47  4802.5  253.02  4984.6  254.53  4990.3  251.02
  5008.3  251.66  5013.7  254.13  5153.7  253.34  5263.6  263.09  5475.6  289.08
#Mann= 5 ,-1 , 0
  3611.3     .16       0  3876.4     .12       0  4311.4     .07       0
  4317.4     .12       0  5263.6     .05       0
Bank Sta=4984.6,5013.7
XS Rating Curve= 0 ,0
Exp/Cntr=0.3,0.1

Type RM Length L Ch R = 1 ,86586   ,823,823,823
BEGIN DESCRIPTION:
BIG ELKHART CREEK 84.0
END DESCRIPTION:
XS GIS Cut Line= 4
      3766762.15     10538169.32      3767137.14     10539403.65
      3767173.59     10539773.44      3767506.91     10540315.08
#Sta/Elev= 30
  3518.3  307.94  3591.4  303.54  3655.1  290.92  3667.6  286.19  3733.3   276.8
  3766.2  269.88  3843.2  260.47  3914.2  255.99  4031.3  251.91  4181.6  252.93
  4195.5   249.3  4198.3   248.8  4201.5   249.3  4229.9  253.17  4975.7  253.24
  4988.6  253.13  4995.8  250.18  5015.9  253.35  5146.5  252.93  5267.3  260.14
  5319.1  264.84  5429.2  269.26  5487.2  274.67  5539.3  275.91  5545.2   278.1
  5560.6  276.73  5597.3  279.19  5697.8  289.12  5771.2   288.7  5815.9  291.47
#Mann= 5 ,-1 , 0
  3518.3     .16       0  3914.2     .12       0  4195.5     .07       0
  4201.5     .12       0  5267.3     .05       0
Bank Sta=4975.7,5015.9
XS Rating Curve= 0 ,0
Exp/Cntr=0.3,0.1

Type RM Length L Ch R = 1 ,85763   ,653,653,653
BEGIN DESCRIPTION:
BIG ELKHART CREEK 83.0
END DESCRIPTION:
XS GIS Cut Line= 3
      3766649.61     10538260.16      3766599.61     10539560.19
      3767349.62      10540360.2
#Sta/Elev= 30
  3728.3  306.77  3778.4  305.69  3855.9  298.58  3860.9  299.84  3998.5  277.84
  4092.3  265.47  4116.1  261.74  4121.1  262.48  4128.6  260.57  4208.7  252.56
  4636.5  251.75  4789.1  250.57  4796.1  249.13  4798.9  248.63  4802.1  249.13
  4819.1  251.07  4896.7  251.75  4929.2  249.23  4949.2   251.4  4979.3  251.86
  5009.3  249.15  5026.8  252.19  5078.9   250.8  5566.8  251.05  5675.4  254.08
  5807.6  258.45  5892.6  262.89  6005.5  274.17  6097.8  284.74  6125.9  289.33
#Mann= 5 ,-1 , 0
  3728.3     .16       0  4092.3     .12       0  4796.1     .07       0
  4802.1     .12       0  5675.4     .05       0
Bank Sta=4979.3,5026.8
XS Rating Curve= 0 ,0
Exp/Cntr=0.3,0.1

Type RM Length L Ch R = 1 ,85110   ,407,407,407
BEGIN DESCRIPTION:
BIG ELKHART CREEK 82.0
END DESCRIPTION:
XS GIS Cut Line= 3
      3766499.62     10538260.15      3766083.32     10539655.39
      3766949.61     10540360.19
#Sta/Elev= 30
  3430.8  307.08  3661.9  298.82  3702.2  294.69  3754.3  284.83  3761.3  281.36
  3773.4  280.84  3799.7  277.54    3817  273.29  3832.8   264.5  3858.7  260.21
  3952.6  253.81  4140.5  253.61  4179.9  260.93  4203.1  252.98    4213  252.72
  4218.2  255.47  4251.4  252.62  4307.4  254.62  4361.2  251.69  4986.6  250.38
    4998  246.58  5000.7  246.08    5004  246.58  5023.3  251.14  5477.1  250.64
  5569.8  255.63  5654.7   255.3    5819  258.21  5946.9  267.08  6003.6  273.63
#Mann= 5 ,-1 , 0
  3430.8     .16       0  3773.4     .12       0    4998     .07       0
    5004     .12       0  5654.7     .05       0
Bank Sta=4986.6,5023.3
XS Rating Curve= 0 ,0
Exp/Cntr=0.3,0.1

Type RM Length L Ch R = 1 ,84703   ,444,444,444
BEGIN DESCRIPTION:
Mapping XS ab4668e6
END DESCRIPTION:
XS GIS Cut Line= 5
      3766413.19     10538405.36      3765796.86     10539585.94
      3765874.98     10540063.37      3765440.96     10540879.35
      3764954.84      10541973.1
#Sta/Elev= 30
  3409.7  302.42  3505.4  297.36  3594.3  282.04  3645.4  272.17  3683.9  259.57
  3772.2  254.51  3979.2  253.59  4031.6   260.1  4037.2  255.39  4097.9  252.82
  4125.8  256.84  4158.5   252.6  4816.7  248.57  4918.2  252.81  4979.6  250.57
  4999.1  245.92  5035.9  250.04    5781  252.55  5797.3  249.22    5800  245.56
  5802.7  245.06    5806  245.56  5819.3  251.66  5946.5  251.35  6478.5  252.03
  6667.3  255.98  6765.1  266.36  6971.6   294.4  7107.5  299.03  7346.4  295.84
#Mann= 10 ,-1 , 0
  3409.7     .16       0  3594.3     .12       0    5800     .07       0
    5806     .12       0  5946.5     .05       0  6478.5     .12       0
  6667.3     .16       0  6765.1     .05       0  6971.6     .16       0
  7107.5     .05       0
Bank Sta=4918.2,5035.9
XS Rating Curve= 0 ,0
Exp/Cntr=0.3,0.1