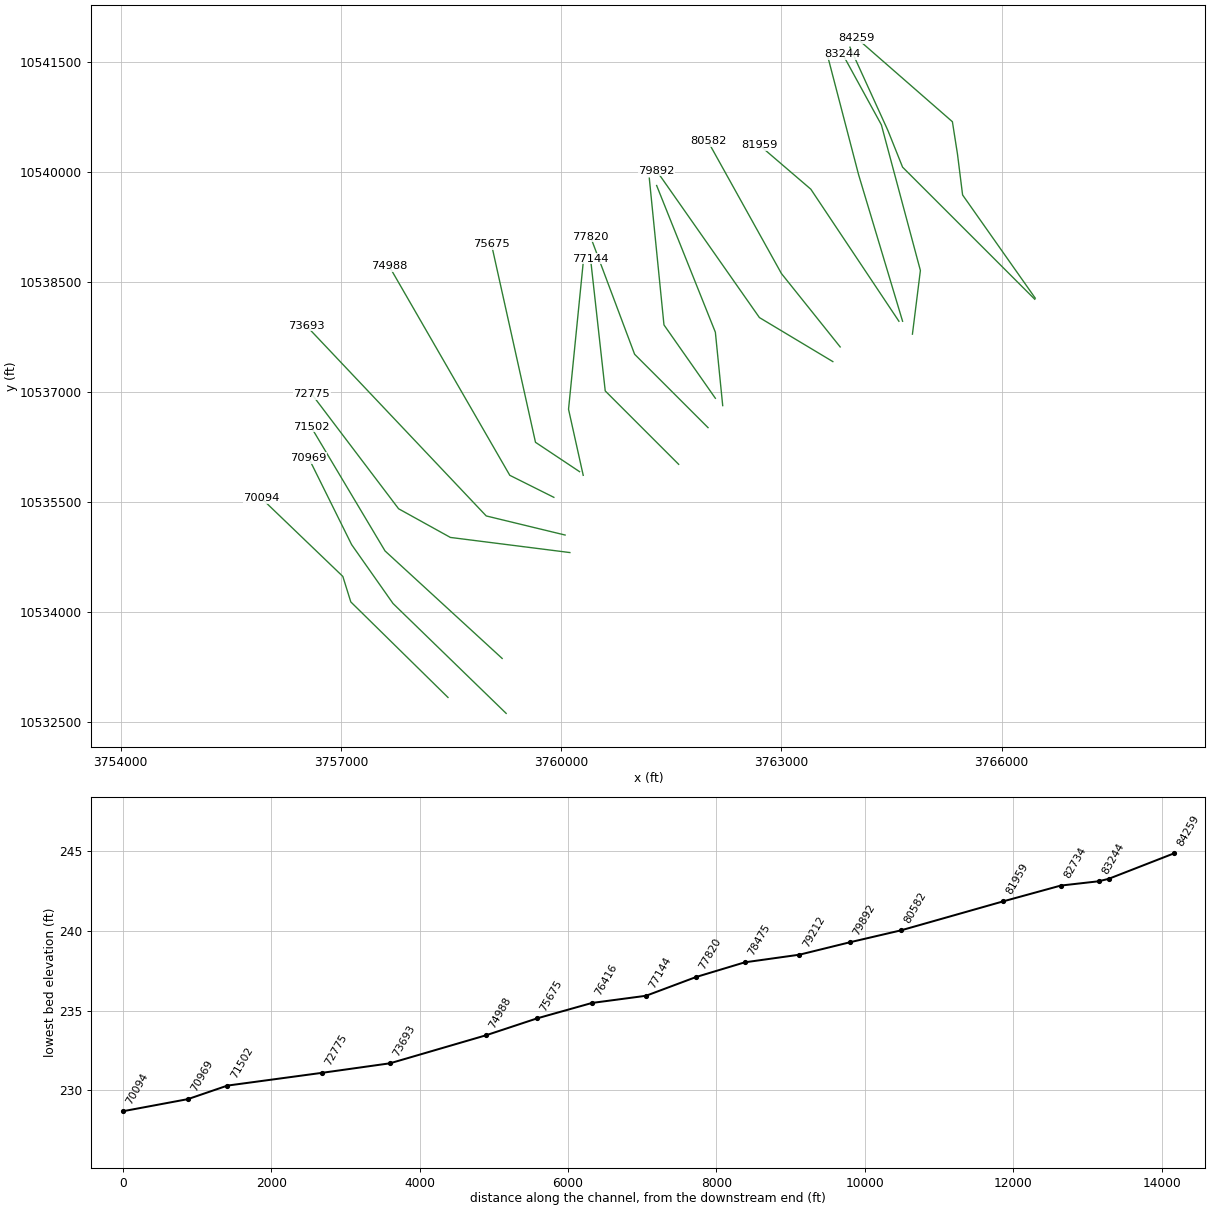
HEC-RAS study BIG ELKHART CREEK.prj: BIG ELKHART CREEK Base Level Engineering

--- BIG ELKHART CREEK.g01 (geometry) --- (continued)

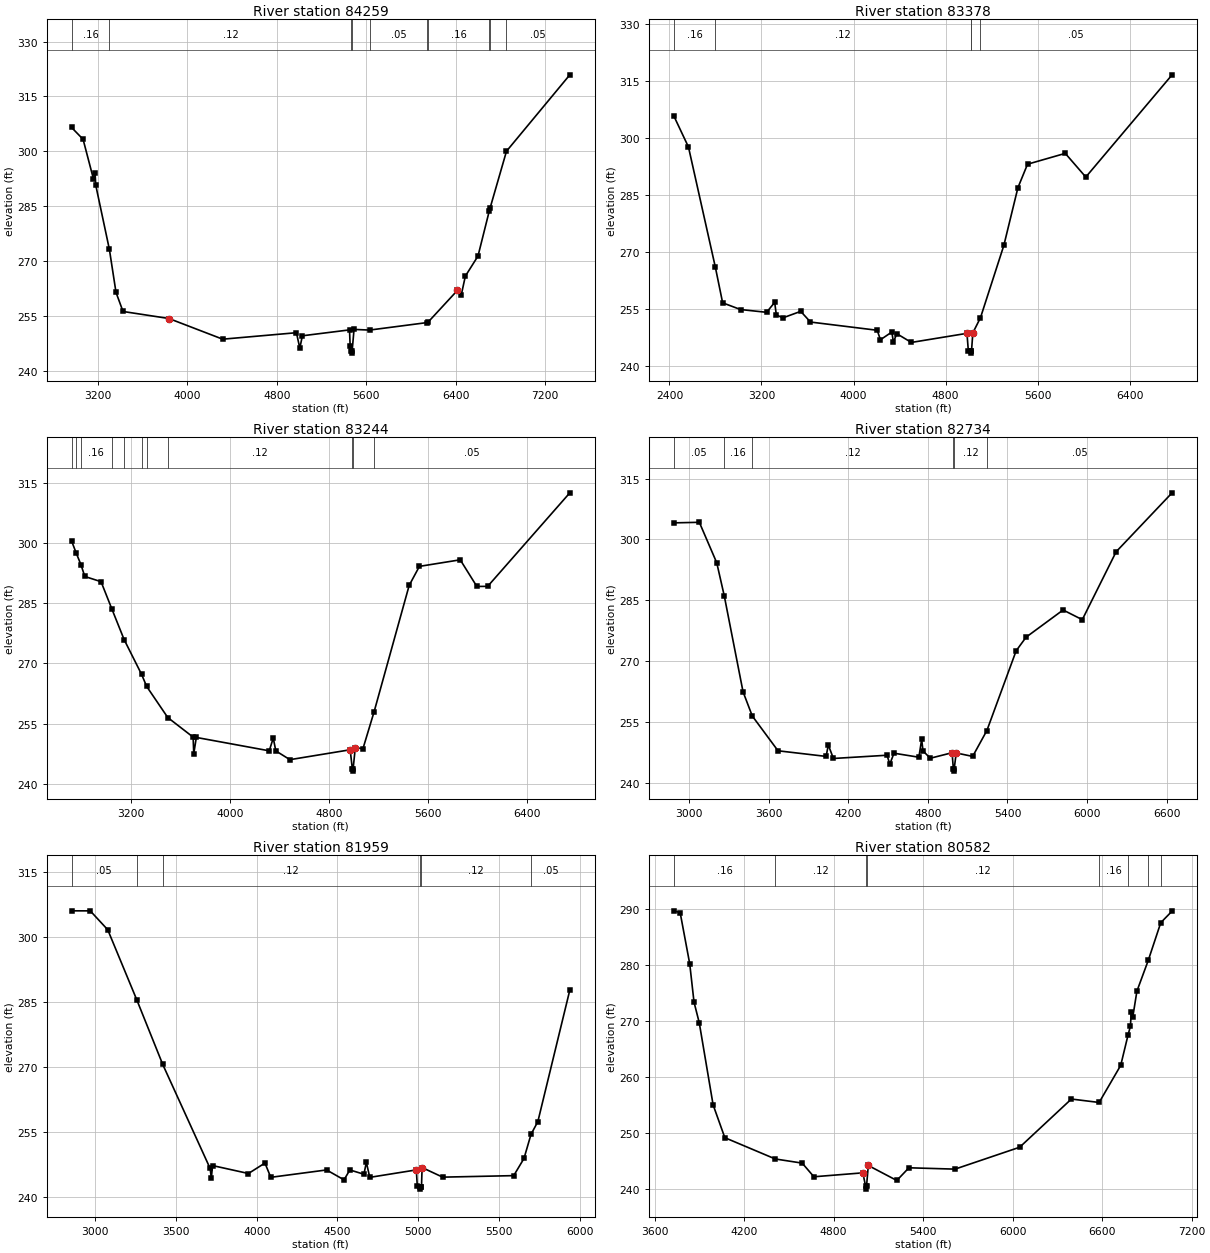
Type RM Length L Ch R = 1 ,84259   ,881,881,881
BEGIN DESCRIPTION:
Mapping XS fd1955f5
END DESCRIPTION:
XS GIS Cut Line= 5
       3766456.6     10538275.15        3765467.     10539681.43
      3765397.55     10540236.99      3765328.11     10540679.69
      3764026.94     10541816.05
#Sta/Elev= 30
    2966  306.53  3068.8   303.3  3161.1  292.52  3175.9     294  3182.1  290.77
  3304.2   273.2  3363.2  261.47    3426  256.25  3836.3  254.33  4317.2  248.68
  4976.6  250.45  5006.8  246.22  5029.7  249.61  5451.1  251.22  5457.1  246.74
  5468.4  245.37  5471.1  244.87  5474.4  245.37  5491.6  251.35  5630.5  251.17
  6145.3  253.22  6154.1  253.35  6415.8  262.01  6450.9  260.84    6487  265.91
    6600   271.4  6701.5   283.8  6708.8  284.59  6854.8  300.05  7421.1  320.92
#Mann= 10 ,-1 , 0
    2966     .16       0  3304.2     .12       0  5468.4     .07       0
  5474.4     .12       0  5630.5     .05       0  6145.3     .12       0
  6154.1     .16       0  6701.5     .05       0  6708.8     .16       0
  6854.8     .05       0
Bank Sta=3836.3,6415.8
XS Rating Curve= 0 ,0
Exp/Cntr=0.3,0.1

Type RM Length L Ch R = 1 ,83378   ,134,134,134
BEGIN DESCRIPTION:
BIG ELKHART CREEK 81.0
END DESCRIPTION:
XS GIS Cut Line= 4
      3766449.61     10538260.19      3764649.61     10540060.19
      3764449.61     10540560.19      3763932.51     10541695.25
#Sta/Elev= 30
    2438  305.84  2565.3  297.64  2799.1  265.92  2862.3  256.54  3017.8  254.77
  3244.1  254.04  3314.8  256.66    3329  253.36  3385.5  252.57  3541.1  254.29
  3625.9  251.47  4205.8   249.3  4234.1   246.8    4333  248.83  4347.2  246.13
  4375.5  248.41  4502.8  246.09  4986.3  248.49  4998.4  243.79  5019.6  243.77
  5022.4  243.27  5025.6  243.77  5037.4  248.62  5103.9  252.63  5306.7  271.67
  5429.2  286.91  5512.7  293.11  5840.8  295.97  6019.3  289.72  6769.4  316.69
#Mann= 5 ,-1 , 0
    2438     .16       0  2799.1     .12       0  5019.6     .07       0
  5025.6     .12       0  5103.9     .05       0
Bank Sta=4986.3,5037.4
XS Rating Curve= 0 ,0
Exp/Cntr=0.3,0.1

Type RM Length L Ch R = 1 ,83244   ,510,510,510
BEGIN DESCRIPTION:
Mapping XS 5d3bbbcf
END DESCRIPTION:
XS GIS Cut Line= 4
      3764783.68     10537784.11      3764892.19     10538652.12
       3764360.5      10540637.8      3763835.52     10541596.36
#Sta/Elev= 30
  2719.5  300.58    2756  297.62  2794.7  294.69  2826.4  291.71  2957.4  290.41
  3043.5   283.7    3144  275.94  3284.7  267.28  3325.8  264.26  3496.2   256.5
  3700.9  251.61  3706.1  247.45  3726.8  251.53  4315.6  248.19    4348  251.38
  4368.7  248.17  4482.6  245.98  4969.1  248.45  4986.8  243.62  4989.6  243.12
  4992.8  243.62  5010.4  248.95  5072.6  248.75  5162.8  257.99  5445.6  289.49
  5528.1  294.23  5857.8  295.87  5992.1  289.22  6079.4  289.24  6742.8  312.59
#Mann= 11 ,-1 , 0
  2719.5     .16       0    2756     .05       0  2794.7     .16       0
  3043.5     .12       0    3144     .16       0  3284.7     .12       0
  3325.8     .16       0  3496.2     .12       0  4986.8     .07       0
  4992.8     .12       0  5162.8     .05       0
Bank Sta=4969.1,5010.4
XS Rating Curve= 0 ,0
Exp/Cntr=0.3,0.1

Type RM Length L Ch R = 1 ,82734   ,775,775,775
BEGIN DESCRIPTION:
BIG ELKHART CREEK 80.0
END DESCRIPTION:
XS GIS Cut Line= 3
       3764649.6      10537960.2      3764049.61     10539960.19
      3763628.79     10541575.53
#Sta/Elev= 30
  2883.9  304.09  3076.2  304.23  3207.5  294.24  3264.2  286.09  3405.9  262.41
  3475.5  256.45  3669.5  247.87  4032.3  246.48  4048.8  249.31  4087.1  245.97
  4491.7  246.77  4512.6  244.56  4543.9  247.27  4731.8  246.28  4752.7  250.67
  4763.1  247.82    4818  246.03  4982.3  247.39  4991.8  243.35  4994.5  242.85
  4997.8  243.35  5013.3  247.33  5137.3  246.48  5244.7  252.87  5465.3  272.53
  5540.3  275.89  5819.3   282.6    5964  280.21  6219.3  296.96  6641.2   311.5
#Mann= 6 ,-1 , 0
  2883.9     .05       0  3264.2     .16       0  3475.5     .12       0
  4991.8     .07       0  4997.8     .12       0  5244.7     .05       0
Bank Sta=4982.3,5013.3
XS Rating Curve= 0 ,0
Exp/Cntr=0.3,0.1

Type RM Length L Ch R = 1 ,81959   ,1377,1377,1377
BEGIN DESCRIPTION:
BIG ELKHART CREEK 79.0
END DESCRIPTION:
XS GIS Cut Line= 3
      3764599.63     10537960.16      3763399.61     10539760.19
      3762699.62     10540360.18
#Sta/Elev= 30
  2853.5  305.99  2969.2  305.98  3077.4  301.63  3258.7  285.35    3418  270.59
  3711.4  246.63  3718.9   244.4  3726.4  247.29  3948.7  245.46  4050.9  247.87
  4086.9  244.58  4432.5  246.28  4540.6     244  4576.7  246.28  4663.8  245.29
  4678.8  248.04  4699.9  244.57  4988.3  246.29  4994.3  242.49  5010.9  242.36
  5013.6  241.86  5016.9  242.36  5020.2  242.36    5024  246.83  5151.3  244.62
  5591.4  244.97  5655.1  248.94  5698.4  254.48  5740.7  257.41  5938.8  287.74
#Mann= 6 ,-1 , 0
  2853.5     .05       0  3258.7     .16       0    3418     .12       0
  5010.9     .07       0  5016.9     .12       0  5698.4     .05       0
Bank Sta=4988.3,5024
XS Rating Curve= 0 ,0
Exp/Cntr=0.3,0.1

Type RM Length L Ch R = 1 ,80582   ,690,690,690
BEGIN DESCRIPTION:
BIG ELKHART CREEK 78.0
END DESCRIPTION:
XS GIS Cut Line= 3
      3763799.62     10537610.18      3762999.61     10538610.19
      3761999.59     10540410.22
#Sta/Elev= 30
  3728.6  289.59    3771  289.27  3835.1  280.16  3863.9  273.34  3899.1  269.65
  3991.9  255.04  4070.4   249.2  4408.5  245.41    4589  244.67  4667.5  242.24
  4995.6  242.94  5014.2  240.54    5017  240.04  5020.2  240.54  5032.1  244.25
  5223.2  241.58  5304.4  243.84  5613.2   243.6  6046.8   247.5  6393.4  256.08
  6579.4  255.47    6724  262.07  6773.9  267.55  6789.2  269.04    6795  271.65
  6805.3  270.74  6832.7  275.29    6909  280.79  6992.6  287.48  7068.4  289.54
#Mann= 8 ,-1 , 0
  3728.6     .16       0  4408.5     .12       0  5014.2     .07       0
  5020.2     .12       0  6579.4     .16       0  6773.9     .05       0
    6909     .16       0  6992.6     .05       0
Bank Sta=4995.6,5032.1
XS Rating Curve= 0 ,0
Exp/Cntr=0.3,0.1

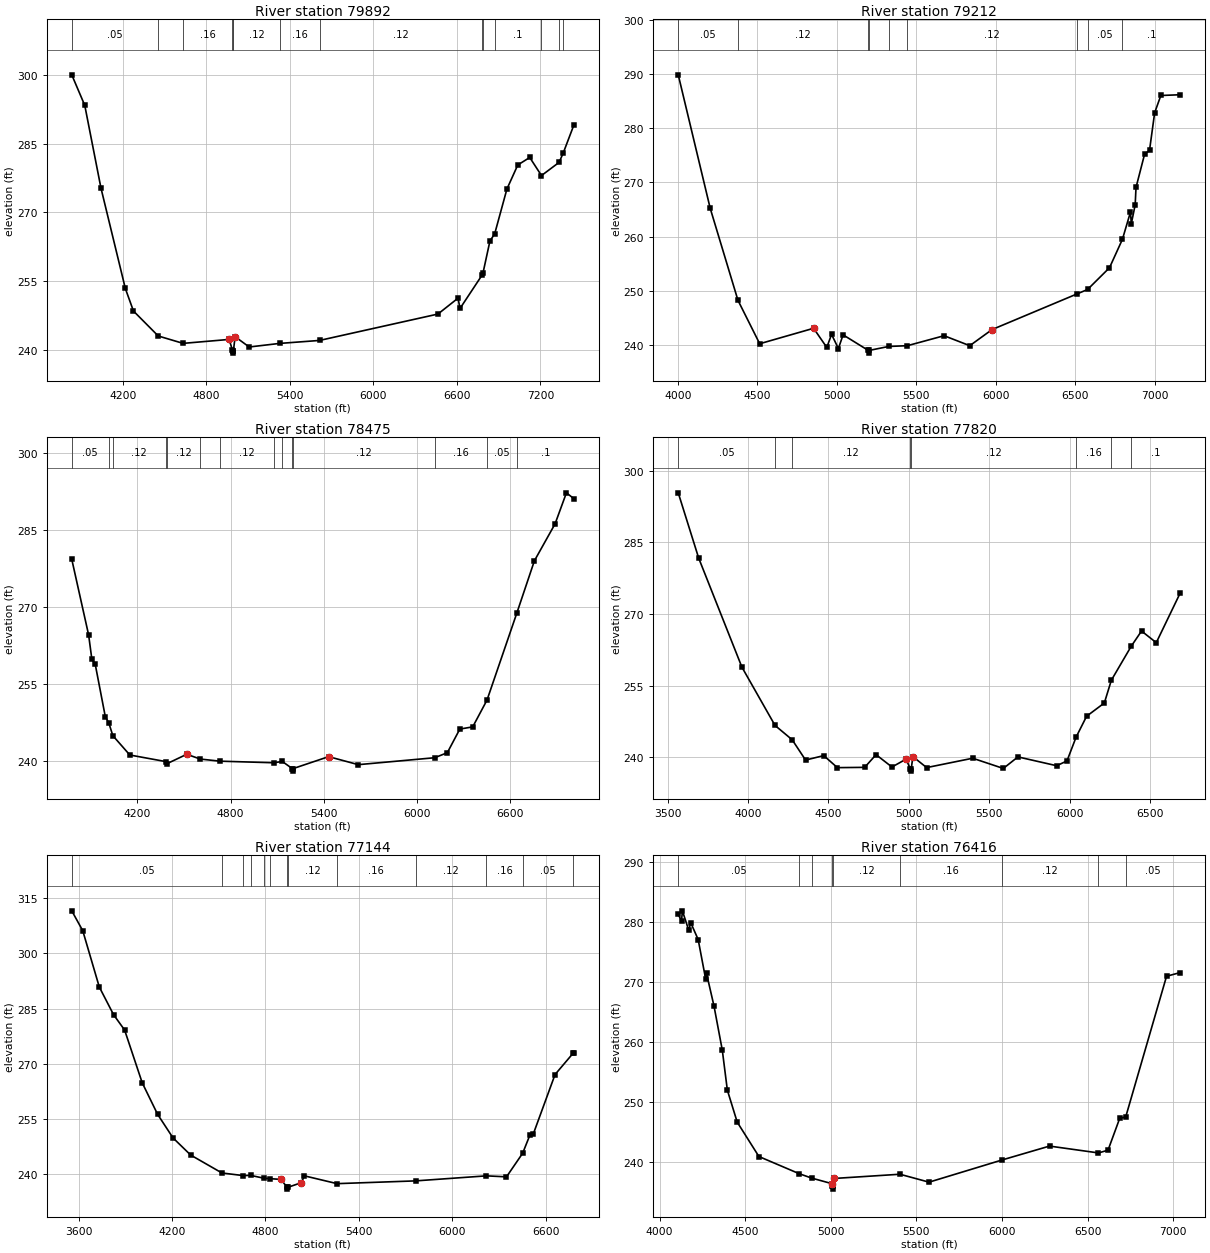
Type RM Length L Ch R = 1 ,79892   ,680,680,680
BEGIN DESCRIPTION:
BIG ELKHART CREEK 77.0
END DESCRIPTION:
XS GIS Cut Line= 3
      3763699.62     10537410.18      3762699.61     10538010.19
      3761299.61     10540010.18
#Sta/Elev= 30
  3833.1  300.04  3926.4  293.38    4043   275.3    4218   253.4  4276.3  248.48
  4454.5  243.03  4633.1  241.42  4964.3  242.28  4986.9  239.98  4988.5  239.79
  4991.3  239.29  4994.5  239.79  5006.7  242.88  5107.8  240.63  5326.7  241.41
  5613.3  242.06  6464.1  247.82  6608.4  251.29  6622.8  249.04  6783.5  256.43
  6787.3  256.71  6837.7  263.77  6871.7  265.32  6959.8  275.12  7037.8  280.36
  7123.7     282    7208  278.05  7334.6  280.93  7365.2  283.04  7440.6  289.07
#Mann= 14 ,-1 , 0
  3833.1     .05       0  4454.5     .12       0  4633.1     .16       0
  4986.9     .12       0  4988.5     .07       0  4994.5     .12       0
  5326.7     .16       0  5613.3     .12       0  6783.5     .16       0
  6787.3     .05       0  6871.7      .1       0    7208     .16       0
  7334.6     .05       0  7365.2     .16       0
Bank Sta=4964.3,5006.7
XS Rating Curve= 0 ,0
Exp/Cntr=0.3,0.1

Type RM Length L Ch R = 1 ,79212   ,737,737,737
BEGIN DESCRIPTION:
BIG ELKHART CREEK 76.0
END DESCRIPTION:
XS GIS Cut Line= 3
      3762199.61     10536810.22      3762099.61     10537810.19
      3761299.62     10539810.17
#Sta/Elev= 30
  4002.6  289.81  4203.6  265.22  4378.4  248.24  4515.1  240.24  4854.3  243.09
  4937.2  239.56  4967.4  241.96  5010.2  239.36  5039.9  241.88  5198.4  239.01
  5201.2  238.51  5204.4  239.01  5326.5  239.74  5444.4  239.88  5675.3  241.72
  5836.9  239.88  5976.9  242.85  6512.2  249.43    6578  250.24    6716  254.25
  6797.4  259.49  6847.9  264.51  6853.3  262.37  6877.6  265.84  6882.9  269.05
  6936.8  275.18  6967.8  275.88  7000.1  282.81  7039.1     286  7161.6  286.14
#Mann= 9 ,-1 , 0
  4002.6     .05       0  4378.4     .12       0  5198.4     .07       0
  5204.4     .12       0  5326.5     .16       0  5444.4     .12       0
  6512.2     .16       0    6578     .05       0  6797.4      .1       0
Bank Sta=4854.3,5976.9
XS Rating Curve= 0 ,0
Exp/Cntr=0.3,0.1

Type RM Length L Ch R = 1 ,78475   ,655,655,655
BEGIN DESCRIPTION:
BIG ELKHART CREEK 75.0
END DESCRIPTION:
XS GIS Cut Line= 3
      3762099.58     10536910.23      3761399.61     10537910.19
      3761199.61     10539910.21
#Sta/Elev= 30
  3777.7  279.29  3886.2  264.55  3907.1  259.79  3928.1  258.93  3993.4  248.65
    4016  247.42  4041.9  244.94  4151.3  241.17  4380.8   239.9  4391.7   239.5
  4517.5  241.31    4605  240.38  4730.4  239.97  5077.5  239.66  5132.4  239.91
  5196.3  238.53  5199.1  238.03  5202.3  238.53  5430.5  240.85  5621.4  239.29
  6112.8  240.64  6194.2  241.62  6274.6  246.22  6357.6  246.65  6449.7  251.88
    6642  268.87  6754.5     279  6887.7  286.21  6960.5  292.24  7008.3  291.11
#Mann= 14 ,-1 , 0
  3777.7     .05       0    4016     .16       0  4041.9     .12       0
  4380.8     .16       0  4391.7     .12       0    4605     .16       0
  4730.4     .12       0  5077.5     .16       0  5132.4     .12       0
  5196.3     .07       0  5202.3     .12       0  6112.8     .16       0
  6449.7     .05       0    6642      .1       0
Bank Sta=4517.5,5430.5
XS Rating Curve= 0 ,0
Exp/Cntr=0.3,0.1

Type RM Length L Ch R = 1 ,77820   ,676,676,676
BEGIN DESCRIPTION:
BIG ELKHART CREEK 74.0
END DESCRIPTION:
XS GIS Cut Line= 3
      3761999.61     10536510.18      3760999.61     10537510.19
      3760399.62     10539110.17
#Sta/Elev= 30
  3565.5  295.39  3692.8  281.71  3961.5  258.89  4167.5  246.68  4274.2  243.68
  4357.5  239.43  4470.6  240.36  4555.5  237.84  4725.2   237.9  4795.9  240.56
  4894.9  237.97  4982.4  239.62  5008.8  237.61  5011.5  237.11  5014.8  237.61
  5025.1  240.15  5110.6  237.85  5397.1  239.81  5587.6  237.67  5678.4  240.09
  5919.6  238.24  5983.6  239.25  6040.3  244.23  6105.6   248.6  6215.9  251.38
  6259.6  256.15  6382.9  263.25  6447.3  266.45    6539  264.01  6688.5  274.46
#Mann= 8 ,-1 , 0
  3565.5     .05       0  4167.5     .16       0  4274.2     .12       0
  5008.8     .07       0  5014.8     .12       0  6040.3     .16       0
  6259.6     .05       0  6382.9      .1       0
Bank Sta=4982.4,5025.1
XS Rating Curve= 0 ,0
Exp/Cntr=0.3,0.1

Type RM Length L Ch R = 1 ,77144   ,728,728,728
BEGIN DESCRIPTION:
BIG ELKHART CREEK 73.0
END DESCRIPTION:
XS GIS Cut Line= 3
      3761599.61     10536010.19      3760599.61     10537010.19
      3760399.61      10538810.2
#Sta/Elev= 30
  3555.7  311.59  3626.4  306.17  3732.5  290.88  3824.4  283.34  3895.1  279.19
  4008.2  264.84  4107.2  256.26  4206.2  249.85  4319.4   245.2  4520.4  240.32
  4657.1  239.61  4704.5  239.67  4790.7  238.89  4827.8  238.78 4899.96  238.57
  4938.6  236.43  4941.4  235.93  4944.6  236.43 5030.16  237.68  5050.4  239.54
  5260.1  237.42    5764  238.17  6219.3  239.54  6348.3  239.27  6452.2  245.69
  6499.3  250.69  6519.4  250.79  6660.3  267.09  6777.2  272.92    6781   272.9
#Mann= 13 ,-1 , 0
  3555.7     .05       0  4520.4     .16       0  4657.1     .12       0
  4704.5     .16       0  4790.7     .05       0  4827.8     .12       0
  4938.6     .07       0  4944.6     .12       0  5260.1     .16       0
    5764     .12       0  6219.3     .16       0  6452.2     .05       0
  6777.2      .1       0
Bank Sta=4899.96,5030.16
XS Rating Curve= 0 ,0
Exp/Cntr=0.3,0.1

Type RM Length L Ch R = 1 ,76416   ,741,741,741
BEGIN DESCRIPTION:
BIG ELKHART CREEK 72.0
END DESCRIPTION:
XS GIS Cut Line= 3
      3760299.61     10535860.19      3760099.61     10536760.19
      3760299.61     10538760.16
#Sta/Elev= 30
  4109.1  281.23  4128.3  280.18  4133.4  281.84  4170.6  278.59  4182.1  279.86
  4225.6  277.05  4269.2  270.48  4274.3   271.4  4317.8     266  4366.5  258.61
  4395.9  251.97  4453.5  246.64  4580.3  240.91  4815.6  238.05  4888.1  237.32
  5006.7  236.39  5008.8  235.98  5011.6  235.48  5014.8  235.98  5020.8  237.26
  5403.7  237.96  5573.7  236.64  6000.4  240.34  6277.2  242.65  6563.2  241.51
  6618.9  241.97  6686.8  247.25  6722.2  247.51  6960.6  270.94    7041  271.56
#Mann= 9 ,-1 , 0
  4109.1     .05       0  4815.6     .07       0  4888.1     .12       0
  5008.8     .07       0  5014.8     .12       0  5403.7     .16       0
  6000.4     .12       0  6563.2     .16       0  6722.2     .05       0
Bank Sta=5006.7,5020.8
XS Rating Curve= 0 ,0
Exp/Cntr=0.3,0.1

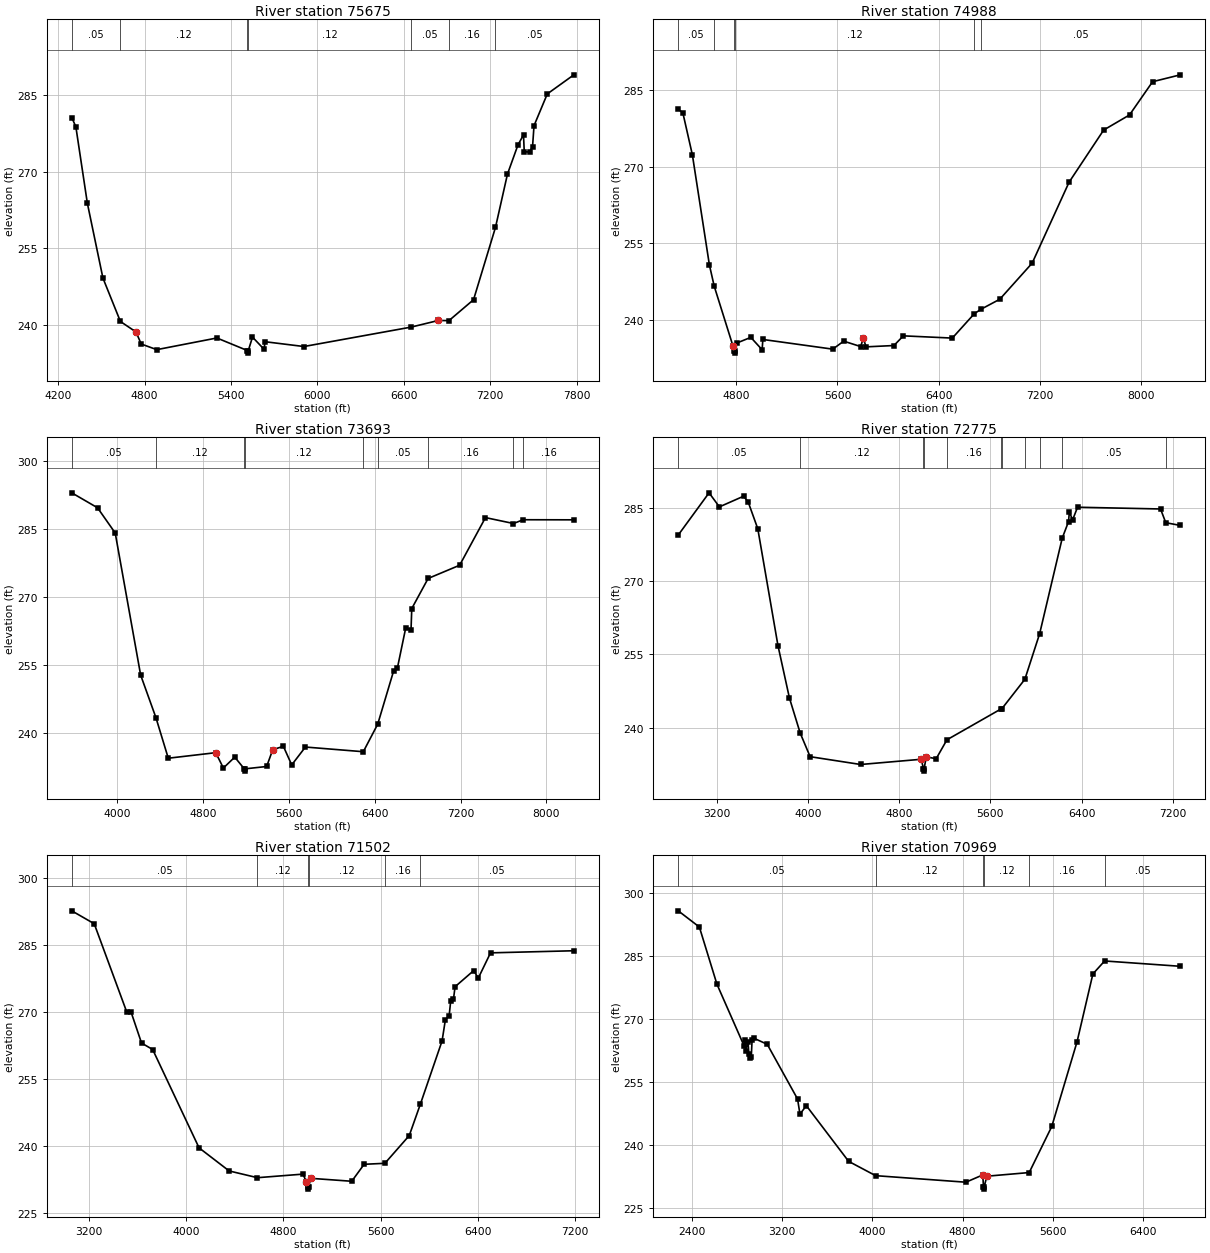
Type RM Length L Ch R = 1 ,75675   ,687,687,687
BEGIN DESCRIPTION:
BIG ELKHART CREEK 71.0
END DESCRIPTION:
XS GIS Cut Line= 3
       3760249.6      10535910.2      3759649.61     10536310.19
       3759049.6     10539010.23
#Sta/Elev= 30
  4294.1  280.56  4322.6  278.73  4402.3  263.81  4510.4  249.19  4631.8   240.7
  4740.3  238.64  4776.3  236.29  4884.5  235.19    5302  237.47  5514.2  235.01
  5516.9  234.51  5520.2  235.01  5549.2  237.64  5629.8  235.26  5636.2  236.74
  5906.4   235.8  6651.6   239.6  6839.9  240.89  6913.6  240.86  7084.5  244.95
  7236.9  259.09  7320.1   269.5  7393.1  275.21  7431.5  277.17  7436.6  273.87
  7473.7  273.81  7494.2  274.83  7504.5  278.96  7596.7  285.17  7781.1   288.9
#Mann= 7 ,-1 , 0
  4294.1     .05       0  4631.8     .12       0  5514.2     .07       0
  5520.2     .12       0  6651.6     .05       0  6913.6     .16       0
  7236.9     .05       0
Bank Sta=4740.3,6839.9
XS Rating Curve= 0 ,0
Exp/Cntr=0.3,0.1

Type RM Length L Ch R = 1 ,74988   ,1295,1295,1295
BEGIN DESCRIPTION:
BIG ELKHART CREEK 70.0
END DESCRIPTION:
XS GIS Cut Line= 3
      3759899.64     10535560.17      3759299.61     10535860.19
      3757654.79     10538713.73
#Sta/Elev= 30
  4342.6  281.29    4379  280.59  4454.4  272.32  4588.6  250.75  4626.9  246.56
  4775.9  234.76  4786.8  233.95  4789.6  233.45  4792.8  233.95  4803.8  235.42
  4915.6  236.54  5005.1  234.11  5010.7  236.13  5562.9  234.23  5649.1   235.8
  5782.7  234.74  5804.3  236.33  5825.8  234.68  6045.6  234.94  6120.3  236.84
  6506.7   236.4  6681.3   241.2  6737.2  242.11  6881.6  244.02  7137.2   251.1
    7429  266.99  7701.9  277.21  7905.9  280.17  8088.3  286.69  8307.1  288.04
#Mann= 6 ,-1 , 0
  4342.6     .05       0  4626.9     .12       0  4786.8     .07       0
  4792.8     .12       0  6681.3     .16       0  6737.2     .05       0
Bank Sta=4775.9,5804.3
XS Rating Curve= 0 ,0
Exp/Cntr=0.3,0.1

Type RM Length L Ch R = 1 ,73693   ,918,918,918
BEGIN DESCRIPTION:
BIG ELKHART CREEK 69.0
END DESCRIPTION:
XS GIS Cut Line= 3
      3760052.77     10535046.22      3758978.56     10535306.63
      3756526.29     10537899.96
#Sta/Elev= 30
  3580.2  292.92  3820.1  289.63  3984.7  284.08  4221.4  252.83  4363.7  243.46
  4478.7  234.53  4920.8  235.75  4991.6  232.37  5097.6  234.77  5186.4  232.19
  5189.2  231.69  5192.4  232.19  5394.6  232.71  5451.2  236.41  5550.3  237.15
    5628  233.06  5755.4  236.99  6294.5  235.96  6428.8  242.03  6575.9  253.67
  6611.4  254.32  6689.1  263.17  6738.8   262.8  6745.7  267.46  6897.9  274.08
  7191.5  276.99  7431.8  287.47  7692.6  286.17  7783.3     287  8254.7  286.98
#Mann= 9 ,-1 , 0
  3580.2     .05       0  4363.7     .12       0  5186.4     .07       0
  5192.4     .12       0  6294.5     .16       0  6428.8     .05       0
  6897.9     .16       0  7692.6     .05       0  7783.3     .16       0
Bank Sta=4920.8,5451.2
XS Rating Curve= 0 ,0
Exp/Cntr=0.3,0.1

Type RM Length L Ch R = 1 ,72775   ,1273,1273,1273
BEGIN DESCRIPTION:
BIG ELKHART CREEK 68.0
END DESCRIPTION:
XS GIS Cut Line= 4
      3760117.92      10534807.5      3758490.28     10535013.66
      3757784.98     10535404.29      3756602.29     10536966.75
#Sta/Elev= 30
    2860  279.47  3130.5  288.12  3221.2  285.24  3432.9  287.42  3473.2  286.29
  3558.3  280.75  3735.3  256.81    3836  246.07    3930  238.91  4017.5  234.05
    4461  232.45    4993  233.52    5012  231.59  5014.7  231.09    5018  231.59
  5036.7  234.02  5123.7  233.63  5218.2  237.51  5695.9  243.87  5700.5  243.88
  5902.2  249.91  6032.3  259.29  6230.1  278.83  6285.7  282.24  6292.6  284.24
  6321.1  282.57  6364.7  285.17    7093  284.81  7138.8     282  7266.5  281.44
#Mann= 11 ,-1 , 0
    2860     .05       0    3930     .12       0    5012     .07       0
    5018     .12       0  5218.2     .16       0  5695.9     .12       0
  5700.5     .16       0  5902.2     .05       0  6032.3     .16       0
  6230.1     .05       0  7138.8     .16       0
Bank Sta=4993,5036.7
XS Rating Curve= 0 ,0
Exp/Cntr=0.3,0.1

Type RM Length L Ch R = 1 ,71502   ,533,533,533
BEGIN DESCRIPTION:
BIG ELKHART CREEK 67.0
END DESCRIPTION:
XS GIS Cut Line= 3
      3759195.56     10533364.37      3757600.52      10534829.2
       3756591.4     10536521.92
#Sta/Elev= 30
  3055.8   292.6  3240.8  289.71  3510.2  269.84  3545.4  269.85  3630.5     263
  3722.3  261.55  4104.6  239.53  4352.5  234.36  4585.6  232.85    4961  233.65
  4989.4  231.84  5000.6  230.79  5003.3  230.29  5006.6  230.79  5024.5  232.71
  5362.3  232.05  5464.3  235.85  5635.4  236.07  5836.1  242.28  5927.5   249.3
  6106.6  263.48  6133.9  268.24    6165  269.15  6177.2  272.32  6200.5  272.87
  6213.7  275.61  6367.5  279.23  6404.5  277.52  6505.7  283.19  7192.1  283.66
#Mann= 6 ,-1 , 0
  3055.8     .05       0  4585.6     .12       0  5000.6     .07       0
  5006.6     .12       0  5635.4     .16       0  5927.5     .05       0
Bank Sta=4989.4,5024.5
XS Rating Curve= 0 ,0
Exp/Cntr=0.3,0.1

Type RM Length L Ch R = 1 ,70969   ,875,875,875
BEGIN DESCRIPTION:
BIG ELKHART CREEK 66.0
END DESCRIPTION:
XS GIS Cut Line= 4
      3759249.85     10532615.63      3757709.03     10534113.06
      3757144.79     10534916.01      3756559.73     10536096.97
#Sta/Elev= 30
  2280.7  295.77  2467.9  291.91  2623.6  278.28    2864  263.59    2871  265.06
  2878.2  262.45  2899.3  264.52  2906.5  261.55  2920.6  260.72  2927.6  260.86
  2934.8  264.94  2948.9  265.43  3069.1  263.96  3337.8  250.92    3359  247.32
  3415.6  249.33  3790.3  236.06  4029.3  232.65  4829.1  231.09    4979  232.83
  4984.7  229.94  4987.5  229.44  4990.7  229.94  5014.7  232.52  5389.9  233.39
  5589.8  244.37    5814  264.58  5954.1  280.73  6058.1  283.82  6728.6  282.55
#Mann= 6 ,-1 , 0
  2280.7     .05       0  4029.3     .12       0  4984.7     .07       0
  4990.7     .12       0  5389.9     .16       0  6058.1     .05       0
Bank Sta=4979,5014.7
XS Rating Curve= 0 ,0
Exp/Cntr=0.3,0.1

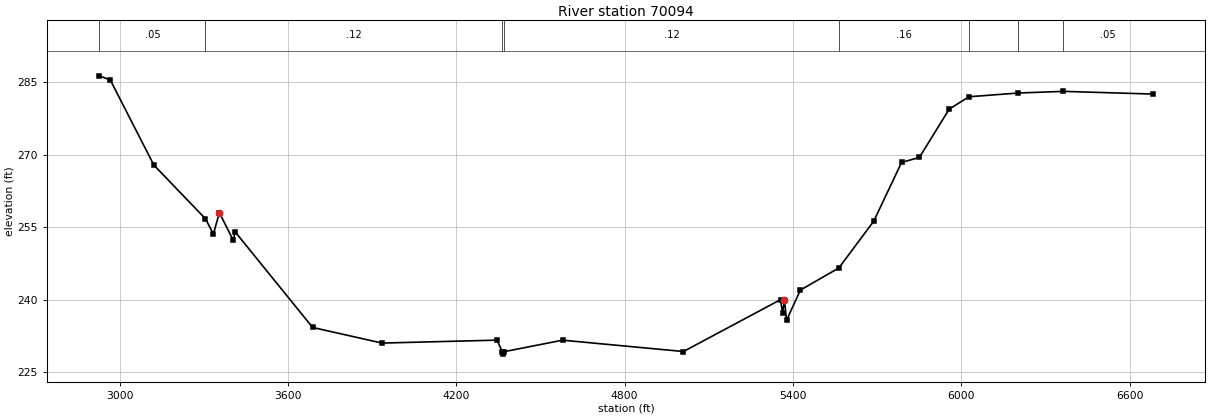
Type RM Length L Ch R = 1 ,70094   ,1938,1938,1938
BEGIN DESCRIPTION:
BIG ELKHART CREEK 65.0
END DESCRIPTION:
XS GIS Cut Line= 4
      3758457.71     10532832.69      3757133.94     10534134.76
      3757025.43     10534481.98      3755918.75     10535545.26
#Sta/Elev= 30
  2927.4  286.36  2966.8  285.51  3122.2  267.86  3306.2  256.73  3334.4  253.57
  3355.7     258  3405.1  252.28  3412.2     254    3688  234.21  3935.4  230.97
  4345.6  231.58  4363.9  229.18  4366.6  228.68  4369.9  229.18    4579  231.57
  5009.9  229.22  5355.9  239.97  5363.1  237.23  5370.1  239.84  5377.3  235.69
  5426.7  241.95    5564  246.55  5688.3  256.24  5787.4  268.42  5850.9  269.44
  5957.2  279.46  6027.4  282.02  6204.1   282.8  6364.6  283.14  6682.7  282.58
#Mann= 8 ,-1 , 0
  2927.4     .05       0  3306.2     .12       0  4363.9     .07       0
  4369.9     .12       0    5564     .16       0  6027.4     .12       0
  6204.1     .16       0  6364.6     .05       0
Bank Sta=3355.7,5370.1
XS Rating Curve= 0 ,0
Exp/Cntr=0.3,0.1