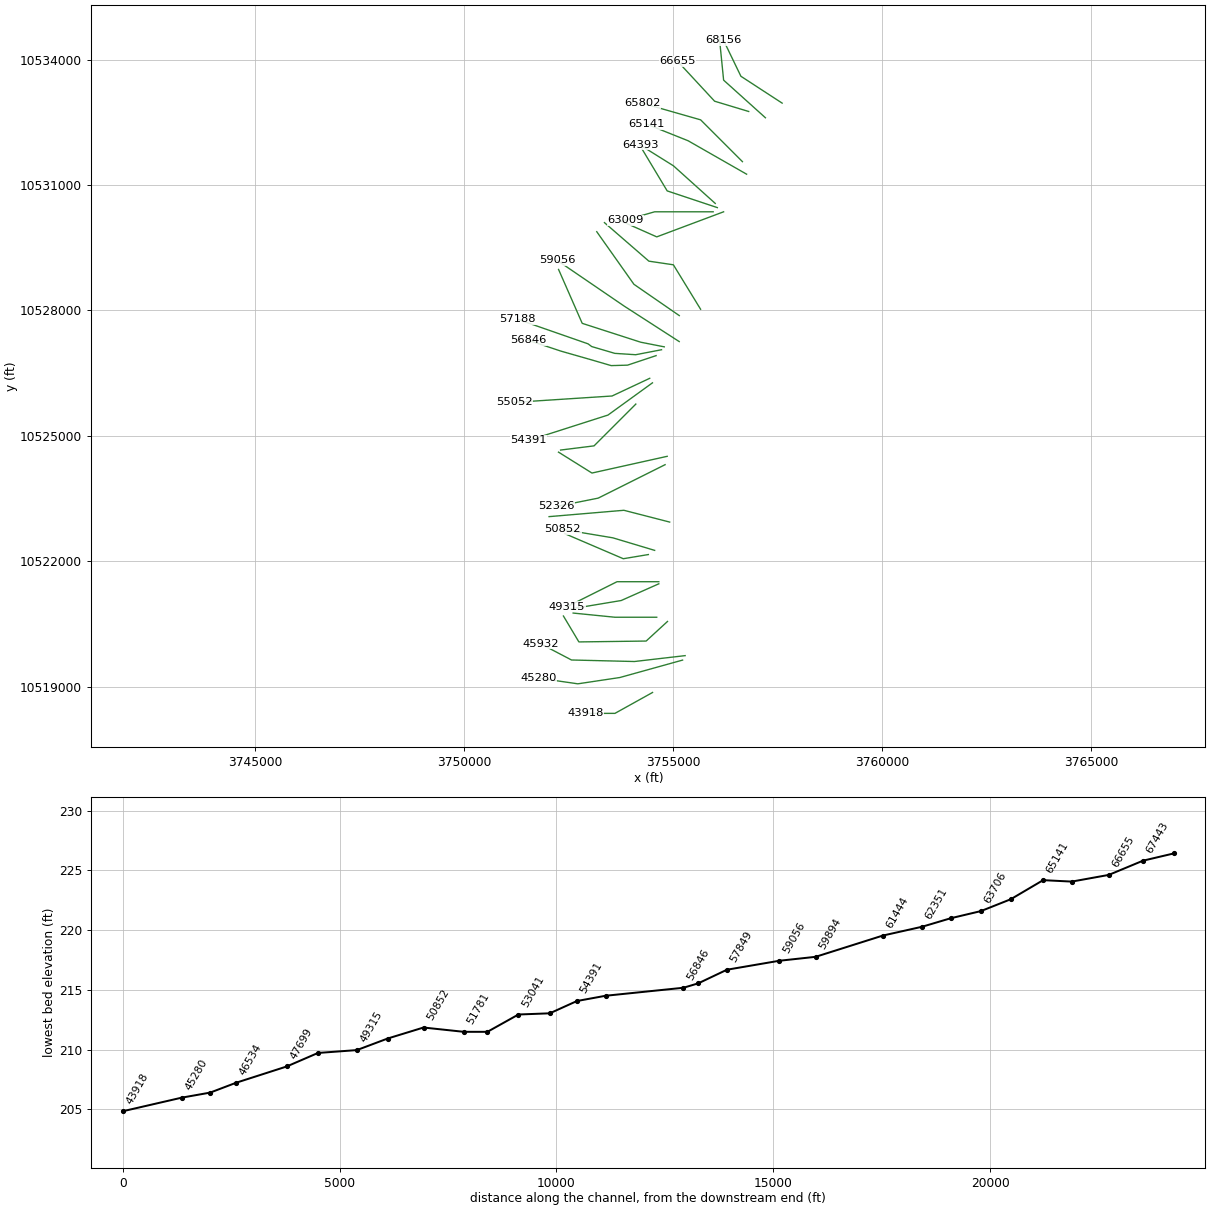
HEC-RAS study BIG ELKHART CREEK.prj: BIG ELKHART CREEK Base Level Engineering

--- BIG ELKHART CREEK.g01 (geometry) --- (continued)

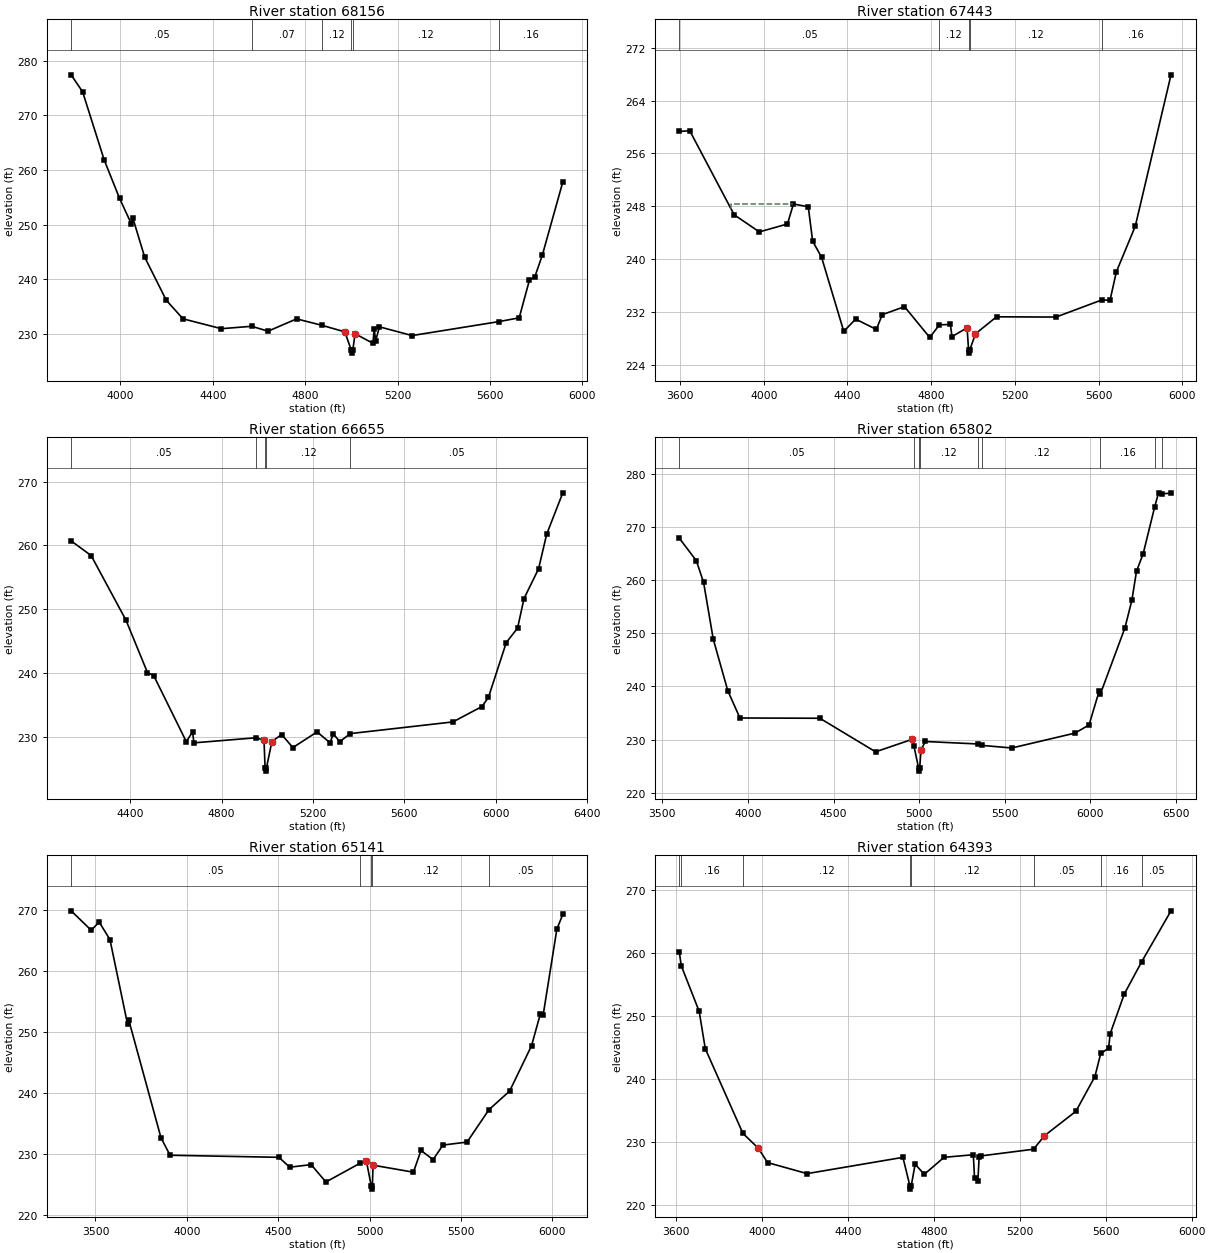
Type RM Length L Ch R = 1 ,68156   ,713,713,713
BEGIN DESCRIPTION:
BIG ELKHART CREEK 64.0
END DESCRIPTION:
XS GIS Cut Line= 3
      3757599.64     10532960.17      3756613.11     10533603.07
       3756199.6     10534460.21
#Sta/Elev= 30
  3786.6  277.45  3836.4  274.33  3929.9  261.83  3996.4   254.8  4047.7   250.1
  4053.7  251.22  4105.1  244.03  4198.6  236.13    4271  232.72    4437  230.91
  4568.9  231.35  4639.2  230.45    4763  232.71  4873.3  231.52    4972  230.33
  5000.2  226.93    5003  226.43  5006.2  226.93  5016.4  229.98  5093.7  228.23
  5099.2  230.85  5105.3  228.69  5121.8  231.25  5263.1  229.65  5638.1   232.2
    5727   232.9  5771.6  239.86  5794.2  240.37  5826.9  244.35  5915.8   257.8
#Mann= 6 ,-1 , 0
  3786.6     .05       0  4568.9     .07       0  4873.3     .12       0
  5000.2     .07       0  5006.2     .12       0  5638.1     .16       0
Bank Sta=4972,5016.4
XS Rating Curve= 0 ,0
Exp/Cntr=0.3,0.1

Type RM Length L Ch R = 1 ,67443   ,788,788,788
BEGIN DESCRIPTION:
BIG ELKHART CREEK 63.0
END DESCRIPTION:
XS GIS Cut Line= 3
      3757199.63     10532610.17      3756199.61     10533510.19
      3756099.61      10534510.2
#Sta/Elev= 30
  3596.2  259.32  3645.9  259.43  3858.2  246.73  3978.5  244.14  4113.1  245.34
  4141.5  248.36  4212.5  247.94  4233.4  242.74    4276  240.31  4382.2  229.11
    4439  230.96    4538   229.4    4566  231.63  4672.5  232.84  4793.2  228.19
  4839.6   230.1  4891.9  230.15  4899.4  228.32  4971.7  229.64  4978.8  226.32
  4981.5  225.82  4984.8  226.32  5011.9  228.74  5112.4  231.31  5396.4  231.27
  5614.3  233.84  5655.1  233.82  5685.3  238.11  5775.7     245  5946.6  267.88
#Mann= 5 ,-1 , 0
  3596.2     .05       0  4839.6     .12       0  4978.8     .07       0
  4984.8     .12       0  5614.3     .16       0
#XS Ineff= 1 ,-1
    3844  4141.5  248.36
Permanent Ineff=
       F
Bank Sta=4971.7,5011.9
XS Rating Curve= 0 ,0
Exp/Cntr=0.3,0.1

Type RM Length L Ch R = 1 ,66655   ,853,853,853
BEGIN DESCRIPTION:
BIG ELKHART CREEK 62.0
END DESCRIPTION:
XS GIS Cut Line= 3
      3756799.62     10532760.18      3755983.77     10533006.29
      3755099.61     10533960.18
#Sta/Elev= 30
  4141.4   260.7  4229.1   258.4  4381.6  248.28  4475.7  240.07  4503.4  239.57
  4645.7  229.25  4673.5   230.8  4678.7  229.06  4952.7  229.86    4986  229.44
  4990.6  225.13  4993.3  224.63  4996.6  225.13  5020.5  229.27  5063.1  230.36
  5112.4  228.32  5218.4  230.78  5275.1  229.07  5289.3  230.48  5317.6  229.24
  5363.9  230.51  5813.1  232.34  5940.2  234.75  5968.5  236.17  6046.7  244.77
  6096.1  247.03  6124.4  251.67  6187.9  256.31  6223.6  261.74  6294.2  268.23
#Mann= 5 ,-1 , 0
  4141.4     .05       0  4952.7     .12       0  4990.6     .07       0
  4996.6     .12       0  5363.9     .05       0
Bank Sta=4986,5020.5
XS Rating Curve= 0 ,0
Exp/Cntr=0.3,0.1

Type RM Length L Ch R = 1 ,65802   ,661,661,661
BEGIN DESCRIPTION:
BIG ELKHART CREEK 61.0
END DESCRIPTION:
XS GIS Cut Line= 3
      3756649.64     10531560.16      3755649.61     10532560.19
      3754249.58      10532960.2
#Sta/Elev= 30
  3599.8  267.85  3698.8  263.64  3741.3  259.55  3797.8  248.87  3882.7  239.18
  3953.4  234.06  4420.1  234.01  4745.4   227.7  4957.5  230.03  4969.6  228.74
  4996.9  224.57  4999.7  224.07  5002.9  224.57  5010.5   228.1  5036.2  229.64
  5345.5  229.17  5369.4   228.9  5540.6  228.42  5909.8  231.22  5991.7  232.76
  6050.2  239.06  6057.8  238.58    6201     251  6241.3  256.16  6268.6  261.64
  6307.6  264.95  6374.9  273.77  6397.3  276.39  6416.7  276.21  6470.1  276.32
#Mann= 9 ,-1 , 0
  3599.8     .05       0  4969.6     .12       0  4996.9     .07       0
  5002.9     .12       0  5345.5     .16       0  5369.4     .12       0
  6057.8     .16       0  6374.9     .05       0  6416.7     .16       0
Bank Sta=4957.5,5010.5
XS Rating Curve= 0 ,0
Exp/Cntr=0.3,0.1

Type RM Length L Ch R = 1 ,65141   ,748,748,748
BEGIN DESCRIPTION:
BIG ELKHART CREEK 60.0
END DESCRIPTION:
XS GIS Cut Line= 3
      3756749.61     10531260.19      3755349.61     10532060.19
       3754349.6     10532460.19
#Sta/Elev= 30
    3367  269.86  3477.1  266.67  3520.3  268.03  3579.4  265.14  3675.8  251.24
  3681.6  252.01  3858.7   232.6  3908.3  229.75  4503.6  229.41  4562.7  227.79
    4680  228.21  4760.6  225.36  4948.8  228.46  4982.1  228.82  5008.8  224.69
  5011.5  224.19  5014.8  224.69  5018.5  228.12  5239.3  226.97    5281  230.54
    5347  229.03  5400.8  231.42  5532.8  231.91  5652.3  237.22  5765.7  240.28
  5885.5  247.72    5934  252.97  5948.8   252.7  6024.2  266.87  6056.5  269.26
#Mann= 5 ,-1 , 0
    3367     .05       0  4948.8     .12       0  5008.8     .07       0
  5014.8     .12       0  5652.3     .05       0
Bank Sta=4982.1,5018.5
XS Rating Curve= 0 ,0
Exp/Cntr=0.3,0.1

Type RM Length L Ch R = 1 ,64393   ,687,687,687
BEGIN DESCRIPTION:
BIG ELKHART CREEK 59.0
END DESCRIPTION:
XS GIS Cut Line= 3
      3755999.61     10530560.19      3754999.61     10531460.19
      3754199.58     10531960.21
#Sta/Elev= 30
  3615.1  260.19  3623.6  258.06  3707.4  250.79  3735.8  244.87  3910.9  231.44
  3983.2  229.06  4025.8   226.8  4209.7  225.05  4655.9  227.63  4688.4  223.09
  4691.1  222.59  4694.4  223.09  4712.7  226.54  4755.3  224.94  4847.2  227.63
  4983.5  228.05  4989.4  224.29  5004.7  223.82  5010.6  227.63  5019.4  227.86
  5263.8  228.92  5314.8  231.06  5461.1  234.94  5549.5  240.44  5576.8  244.12
  5613.2  244.94  5620.8  247.26  5686.3  253.54  5767.6  258.68  5903.9  266.74
#Mann= 8 ,-1 , 0
  3615.1     .05       0  3623.6     .16       0  3910.9     .12       0
  4688.4     .07       0  4694.4     .12       0  5263.8     .05       0
  5576.8     .16       0  5767.6     .05       0
Bank Sta=3983.2,5314.8
XS Rating Curve= 0 ,0
Exp/Cntr=0.3,0.1

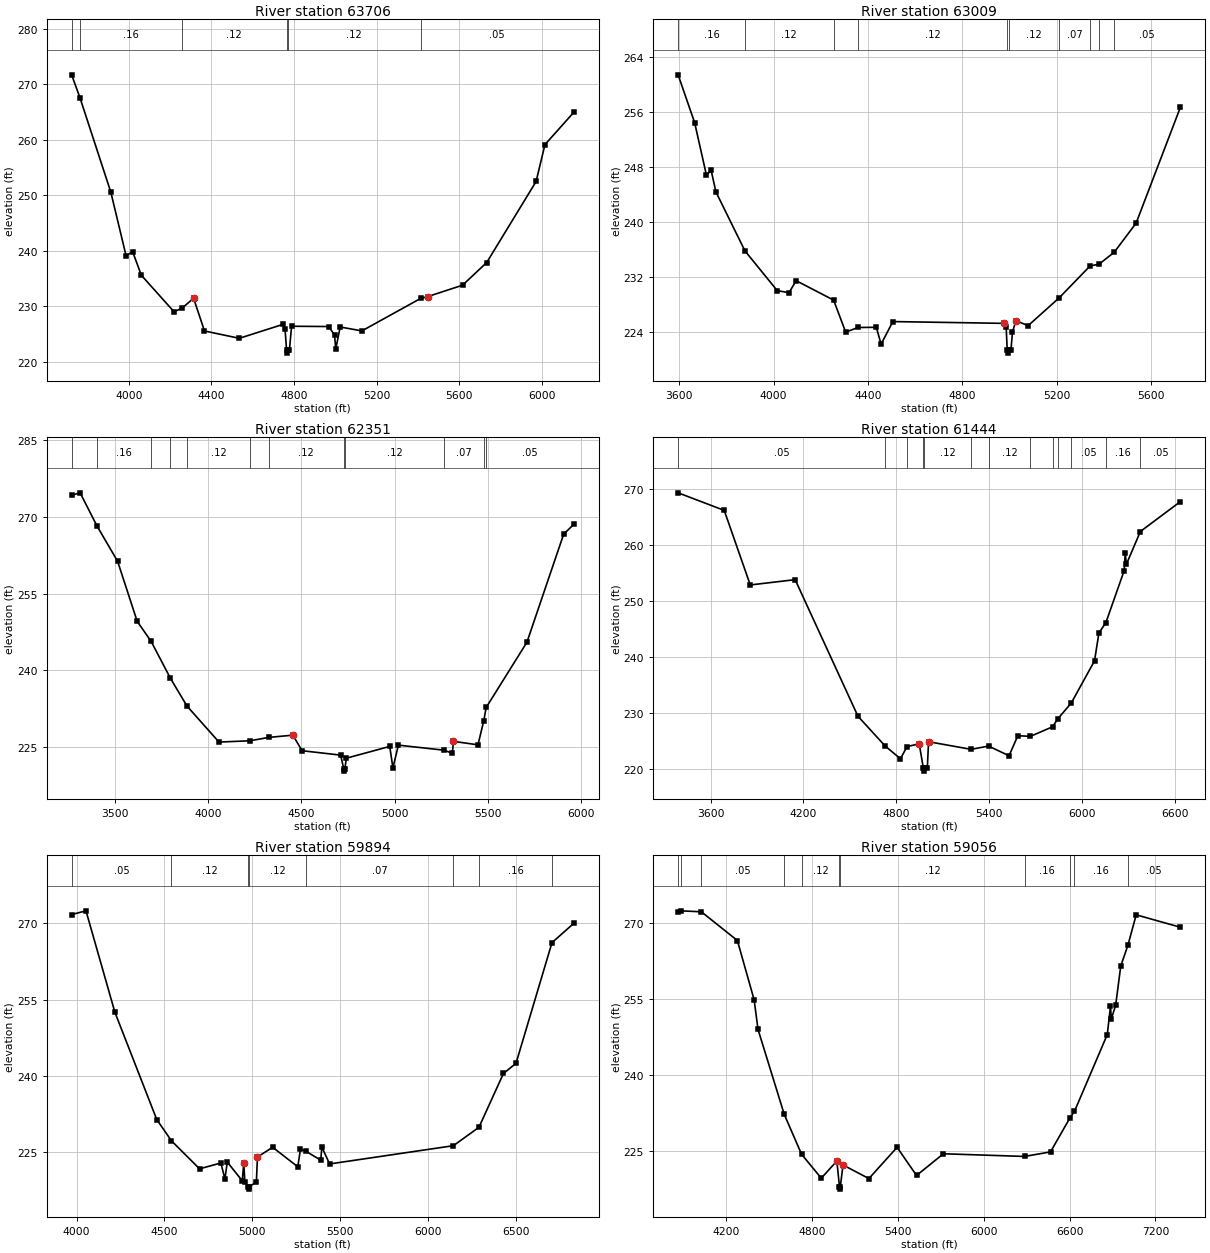
Type RM Length L Ch R = 1 ,63706   ,697,697,697
BEGIN DESCRIPTION:
BIG ELKHART CREEK 58.0
END DESCRIPTION:
XS GIS Cut Line= 3
      3756049.63     10530460.18      3754849.61     10530860.19
      3754249.62     10531860.17
#Sta/Elev= 30
  3723.1  271.72    3763  267.63  3912.9  250.57  3986.6  239.13  4018.3  239.87
  4060.4  235.63  4218.5  229.06    4256  229.65  4313.4  231.48  4366.1  225.59
  4534.8  224.27  4745.6  226.77  4756.1  225.96  4763.7   222.1  4766.4   221.6
  4769.7   222.1  4777.2  222.12  4787.8  226.44  4966.9  226.39  4995.8  224.88
  5001.6  222.33    5023  226.31    5128   225.6    5412  231.44  5446.7  231.78
  5615.8  233.84  5732.4  237.92  5971.5  252.51  6014.3  259.15  6154.2  264.98
#Mann= 6 ,-1 , 0
  3723.1     .05       0    3763     .16       0    4256     .12       0
  4763.7     .07       0  4769.7     .12       0    5412     .05       0
Bank Sta=4313.4,5446.7
XS Rating Curve= 0 ,0
Exp/Cntr=0.3,0.1

Type RM Length L Ch R = 1 ,63009   ,658,658,658
BEGIN DESCRIPTION:
BIG ELKHART CREEK 57.0
END DESCRIPTION:
XS GIS Cut Line= 3
      3755949.57     10530360.19      3754549.61     10530360.19
      3753849.58     10530160.18
#Sta/Elev= 30
  3595.7  261.39  3665.7  254.45  3715.7  246.83  3735.7  247.53  3755.7  244.41
  3878.9  235.84  4015.7  230.07  4065.7  229.77  4095.7  231.52  4254.7  228.69
  4305.7  224.05    4358  224.72  4435.7  224.75  4455.7   222.3  4505.7  225.58
  4975.7  225.32  4985.7  224.83  4990.2   221.5  4992.9     221  4996.2   221.5
  5006.1  221.52  5012.6  224.04  5026.9  225.71  5078.9  224.99  5210.3  229.02
  5341.9  233.67  5378.7  233.89  5443.6  235.64  5536.5  239.87  5723.7  256.65
#Mann= 10 ,-1 , 0
  3595.7     .16       0  3878.9     .12       0  4254.7     .07       0
    4358     .12       0  4990.2     .07       0  4996.2     .12       0
  5210.3     .07       0  5341.9     .12       0  5378.7     .16       0
  5443.6     .05       0
Bank Sta=4975.7,5026.9
XS Rating Curve= 0 ,0
Exp/Cntr=0.3,0.1

Type RM Length L Ch R = 1 ,62351   ,907,907,907
BEGIN DESCRIPTION:
BIG ELKHART CREEK 56.0
END DESCRIPTION:
XS GIS Cut Line= 3
      3756199.63      10530360.2      3754599.61     10529760.19
      3753699.62     10530160.19
#Sta/Elev= 30
  3267.7  274.22  3313.1  274.69  3404.1  268.18  3514.3   261.3  3619.3  249.56
  3693.7  245.67  3797.8  238.42  3886.4  233.01    4058  225.97  4224.6  226.22
  4324.2  226.88  4454.1  227.32  4503.9  224.28  4710.4  223.42    4727  220.79
  4729.7  220.29    4733  220.79  4741.6  222.82  4973.9  225.12  4990.9  220.92
  5020.3  225.37  5265.9  224.38  5309.6  223.76  5315.8  226.11  5447.1  225.43
  5477.9  230.07  5491.3  232.74  5709.7  245.48  5906.7   266.6  5961.4  268.54
#Mann= 12 ,-1 , 0
  3267.7     .05       0  3404.1     .16       0  3693.7     .12       0
  3797.8     .16       0  3886.4     .12       0  4224.6     .16       0
  4324.2     .12       0    4727     .07       0    4733     .12       0
  5265.9     .07       0  5477.9     .12       0  5491.3     .05       0
Bank Sta=4454.1,5315.8
XS Rating Curve= 0 ,0
Exp/Cntr=0.3,0.1

Type RM Length L Ch R = 1 ,61444   ,1550,1550,1550
BEGIN DESCRIPTION:
BIG ELKHART CREEK 55.0
END DESCRIPTION:
XS GIS Cut Line= 4
      3755649.01     10528028.83      3754997.94     10529092.23
      3754412.01     10529179.04      3753348.67     10530101.32
#Sta/Elev= 30
  3389.7  269.33  3687.8  266.19  3856.1  252.85  4146.3   253.8  4552.6  229.36
    4728  224.05    4827  221.76  4870.1  223.95  4948.3  224.43  4975.6  220.05
  4978.4  219.55  4981.6  220.05  5000.9  220.13  5008.9  224.81  5283.5  223.45
  5396.9  224.03  5529.1   222.3  5586.1  225.88  5667.3  225.77  5810.6  227.48
  5845.4  228.94  5931.6  231.73  6081.8  239.27  6110.3  244.26  6155.4  246.12
  6273.7  255.43  6280.3  258.54  6287.9  256.55  6378.2  262.41  6636.5  267.75
#Mann= 13 ,-1 , 0
  3389.7     .05       0    4728     .16       0  4870.1     .12       0
  4975.6     .07       0  4981.6     .12       0  5283.5     .07       0
  5396.9     .12       0  5667.3     .07       0  5810.6     .12       0
  5845.4     .16       0  5931.6     .05       0  6155.4     .16       0
  6378.2     .05       0
Bank Sta=4948.3,5008.9
XS Rating Curve= 0 ,0
Exp/Cntr=0.3,0.1

Type RM Length L Ch R = 1 ,59894   ,838,838,838
BEGIN DESCRIPTION:
BIG ELKHART CREEK 54.0
END DESCRIPTION:
XS GIS Cut Line= 3
      3755139.02     10527876.94      3754053.93     10528625.65
      3753164.37     10529884.06
#Sta/Elev= 30
  3972.2  271.75  4053.8  272.48  4218.1  252.57  4456.8  231.45  4540.5  227.27
  4700.5  221.76  4821.9  222.91  4844.8  219.76  4858.4  223.09  4943.5  219.41
  4952.3  222.85  4958.4   219.2  4976.9  218.27  4979.6  217.77  4982.9  218.27
    5024  219.13  5030.1  224.08  5116.6     226  5259.9  222.16  5274.8  225.59
  5307.1  225.19  5390.6  223.46  5396.7  226.04  5441.1  222.72  6145.9  226.31
  6291.4  229.93  6430.8  240.51  6502.2  242.49  6707.2  266.23  6831.6  270.03
#Mann= 8 ,-1 , 0
  3972.2     .05       0  4540.5     .12       0  4976.9     .07       0
  4982.9     .12       0  5307.1     .07       0  6145.9     .12       0
  6291.4     .16       0  6707.2     .05       0
Bank Sta=4952.3,5030.1
XS Rating Curve= 0 ,0
Exp/Cntr=0.3,0.1

Type RM Length L Ch R = 1 ,59056   ,1207,1207,1207
BEGIN DESCRIPTION:
BIG ELKHART CREEK 53.0
END DESCRIPTION:
XS GIS Cut Line= 3
      3755137.39     10527255.43      3753824.48     10528101.77
      3752218.55     10529197.71
#Sta/Elev= 30
  3867.2  272.27  3884.4  272.45  4029.4  272.26    4281  266.58    4398  254.85
  4425.1  249.01  4608.1  232.22  4728.8  224.35  4866.7   219.6  4975.6     223
  4993.7  217.94  4996.4  217.44  4999.7  217.94  5018.6  222.21  5199.3  219.53
    5396   225.7    5532  220.14  5719.4  224.43  6286.3   223.9  6467.3   224.8
  6604.2  231.58  6634.3  232.79  6863.7     248    6886  253.62    6892  251.11
  6921.9  253.74  6957.8  261.55  7007.9  265.66  7065.5  271.66  7373.5  269.21
#Mann= 11 ,-1 , 0
  3867.2     .05       0  3884.4     .08       0  4029.4     .05       0
  4608.1     .16       0  4728.8     .12       0  4993.7     .07       0
  4999.7     .12       0  6286.3     .16       0  6604.2     .12       0
  6634.3     .16       0  7007.9     .05       0
Bank Sta=4975.6,5018.6
XS Rating Curve= 0 ,0
Exp/Cntr=0.3,0.1

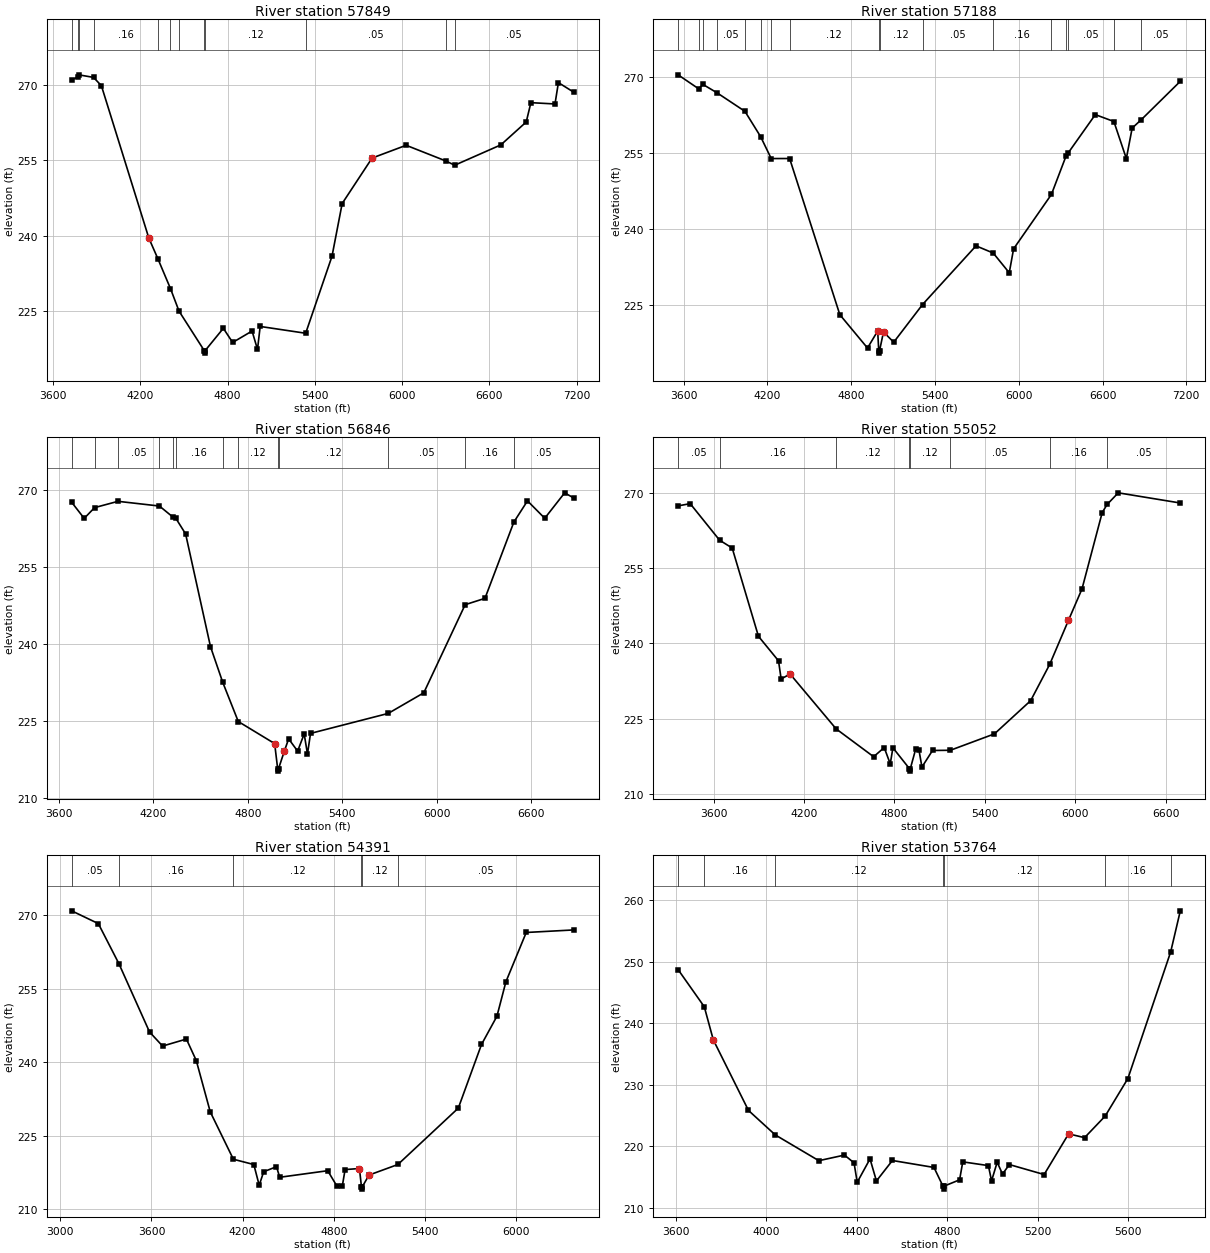
Type RM Length L Ch R = 1 ,57849   ,661,661,661
BEGIN DESCRIPTION:
BIG ELKHART CREEK 52.0
END DESCRIPTION:
XS GIS Cut Line= 4
      3754780.26     10527129.04      3754216.56     10527240.14
       3752816.7     10527691.54      3752251.14     10528980.65
#Sta/Elev= 30
  3728.3  270.93  3769.6  271.58  3777.2  271.99  3878.7  271.48  3932.8  269.83
    4259  239.55  4321.7  235.41  4407.9  229.51  4466.5  225.04  4640.1  217.19
  4642.9  216.69  4646.1  217.19  4771.3  221.62  4835.4  218.81  4968.9  221.08
  5006.2  217.42  5024.6  221.99  5337.5  220.64  5518.5  235.94  5588.4  246.42
    5794  255.45  6028.3  257.99    6299   254.9  6362.2  254.03  6679.5  258.07
    6854  262.62  6886.1  266.46  7051.8   266.2  7075.2  270.44  7181.4  268.53
#Mann= 12 ,-1 , 0
  3728.3     .05       0  3769.6     .08       0  3777.2     .05       0
  3878.7     .16       0  4321.7     .12       0  4407.9     .16       0
  4466.5     .12       0  4640.1     .07       0  4646.1     .12       0
  5337.5     .05       0    6299     .16       0  6362.2     .05       0
Bank Sta=4259,5794
XS Rating Curve= 0 ,0
Exp/Cntr=0.3,0.1

Type RM Length L Ch R = 1 ,57188   ,342,342,342
BEGIN DESCRIPTION:
BIG ELKHART CREEK 51.0
END DESCRIPTION:
XS GIS Cut Line= 6
      3754714.23      10527060.1      3754095.74     10526940.75
      3753596.61      10526973.3      3753043.23     10527136.06
      3752956.42     10527201.16      3751274.58      10527787.1
#Sta/Elev= 30
  3560.5  270.52  3706.6  267.78  3739.1  268.61  3839.1  266.97    4039  263.31
  4151.1  258.32  4227.3  253.98  4359.1  253.99  4718.7  223.14  4916.8  216.56
  4989.7  219.92  4997.2  216.05  4999.9  215.55  5003.2  216.05  5031.4  219.74
  5104.4   217.7    5311  225.15  5693.8  236.74  5817.1  235.32  5931.9  231.42
    5963  236.15  6233.8  246.89  6337.7  254.41  6355.2  255.14  6548.2  262.66
  6681.2   261.3  6770.4  253.98  6812.1     260  6877.9  261.67  7156.9  269.24
#Mann= 17 ,-1 , 0
  3560.5     .08       0  3706.6     .05       0  3739.1     .08       0
  3839.1     .05       0    4039     .16       0  4151.1     .12       0
  4227.3     .16       0  4359.1     .12       0  4997.2     .07       0
  5003.2     .12       0    5311     .05       0  5817.1     .16       0
  6233.8     .05       0  6337.7     .16       0  6355.2     .05       0
  6681.2     .16       0  6877.9     .05       0
Bank Sta=4989.7,5031.4
XS Rating Curve= 0 ,0
Exp/Cntr=0.3,0.1

Type RM Length L Ch R = 1 ,56846   ,1794,1794,1794
BEGIN DESCRIPTION:
BIG ELKHART CREEK 50.0
END DESCRIPTION:
XS GIS Cut Line= 6
      3754584.02     10526919.04      3753900.43     10526691.18
      3753509.81     10526680.33      3753064.93     10526810.54
      3752305.38     10527027.55      3751524.35      10527287.9
#Sta/Elev= 30
  3681.2   267.7  3760.8  264.55  3826.8  266.65  3975.5  267.88  4238.4  266.96
  4326.3  264.75  4341.3  264.63  4404.7  261.51  4562.6  239.49  4640.2  232.54
    4739  224.87  4969.9  220.56  4988.9  215.68  4991.6  215.18  4994.9  215.68
  5032.4  219.17  5058.7  221.48  5115.8  219.09  5157.4  222.45  5178.3  218.52
  5197.7  222.55  5690.7  226.45  5916.8  230.48  6179.3  247.69  6305.1  248.93
  6488.6  263.83    6575  267.97  6684.6  264.57  6811.1  269.54  6869.3  268.52
#Mann= 13 ,-1 , 0
  3681.2     .05       0  3826.8     .08       0  3975.5     .05       0
  4238.4      .1       0  4326.3     .05       0  4341.3     .16       0
  4640.2     .05       0    4739     .12       0  4988.9     .07       0
  4994.9     .12       0  5690.7     .05       0  6179.3     .16       0
  6488.6     .05       0
Bank Sta=4969.9,5032.4
XS Rating Curve= 0 ,0
Exp/Cntr=0.3,0.1

Type RM Length L Ch R = 1 ,55052   ,661,661,661
BEGIN DESCRIPTION:
BIG ELKHART CREEK 49.0
END DESCRIPTION:
XS GIS Cut Line= 3
      3754432.16     10526376.53      3753531.51     10525953.33
      3751198.57     10525801.42
#Sta/Elev= 30
    3365  267.42  3445.2  267.86  3640.3  260.57  3723.9  259.01  3898.2   241.4
  4031.4  236.51  4048.7  232.89  4108.1  233.88  4413.6  222.94  4662.7  217.38
  4732.8  219.21  4772.9  215.96  4790.6  219.16  4900.2  215.01  4902.9  214.51
  4906.2  215.01  4942.7  219.01  4963.3  218.73  4983.3  215.33  5053.5  218.63
  5171.9  218.67  5464.4  221.94  5704.9  228.57  5831.5  235.82  5955.4  244.57
  6045.6  250.86  6179.6  266.08  6212.2   267.7  6286.1  270.02    6698  267.99
#Mann= 8 ,-1 , 0
    3365     .05       0  3640.3     .16       0  4413.6     .12       0
  4900.2     .07       0  4906.2     .12       0  5171.9     .05       0
  5831.5     .16       0  6212.2     .05       0
Bank Sta=4108.1,5955.4
XS Rating Curve= 0 ,0
Exp/Cntr=0.3,0.1

Type RM Length L Ch R = 1 ,54391   ,627,627,627
BEGIN DESCRIPTION:
BIG ELKHART CREEK 48.0
END DESCRIPTION:
XS GIS Cut Line= 3
      3754497.21       10526268.      3753433.85      10525497.6
      3751535.01     10524889.97
#Sta/Elev= 30
  3074.5  270.89  3250.2  268.28  3385.8  260.09  3587.3  246.16  3673.2  243.28
  3830.1  244.71  3895.1  240.32  3987.1  229.85  4139.4  220.17    4274  219.09
  4309.5  214.86  4338.9  217.62  4423.3  218.65  4444.6  216.49  4760.6  217.83
  4819.7  214.76  4857.1  214.77    4875  218.06  4969.5  218.28  4982.7  214.57
  4985.5  214.07  4988.7  214.57  5032.5  216.94  5222.8   219.1  5620.5  230.61
  5773.2   243.6  5874.9  249.37  5933.9   256.4  6067.8  266.47  6381.3  266.99
#Mann= 6 ,-1 , 0
  3074.5     .05       0  3385.8     .16       0  4139.4     .12       0
  4982.7     .07       0  4988.7     .12       0  5222.8     .05       0
Bank Sta=4969.5,5032.5
XS Rating Curve= 0 ,0
Exp/Cntr=0.3,0.1

Type RM Length L Ch R = 1 ,53764   ,723,723,723
BEGIN DESCRIPTION:
BIG ELKHART CREEK 47.0
END DESCRIPTION:
XS GIS Cut Line= 3
      3754099.59     10525760.17      3753099.61     10524760.19
      3752299.63     10524660.19
#Sta/Elev= 30
  3610.5  248.69  3726.2  242.66    3766  237.29  3921.6  225.82  4039.9  221.85
  4232.7  217.66  4345.9  218.57  4388.3  217.31  4402.4  214.16    4459  217.95
  4487.3  214.37    4558  217.69  4741.8  216.56  4781.3  213.54    4784  213.04
  4787.3  213.54    4855  214.55  4869.1  217.47  4982.3  216.86  4996.4  214.38
  5021.2  217.41  5044.8  215.49  5075.1  217.03  5228.8  215.41  5337.1  222.02
  5407.6   221.4  5498.6   224.9  5599.1     231  5788.4  251.58  5830.9  258.24
#Mann= 7 ,-1 , 0
  3610.5     .05       0  3726.2     .16       0  4039.9     .12       0
  4781.3     .07       0  4787.3     .12       0  5498.6     .16       0
  5788.4     .05       0
Bank Sta=3766,5337.1
XS Rating Curve= 0 ,0
Exp/Cntr=0.3,0.1

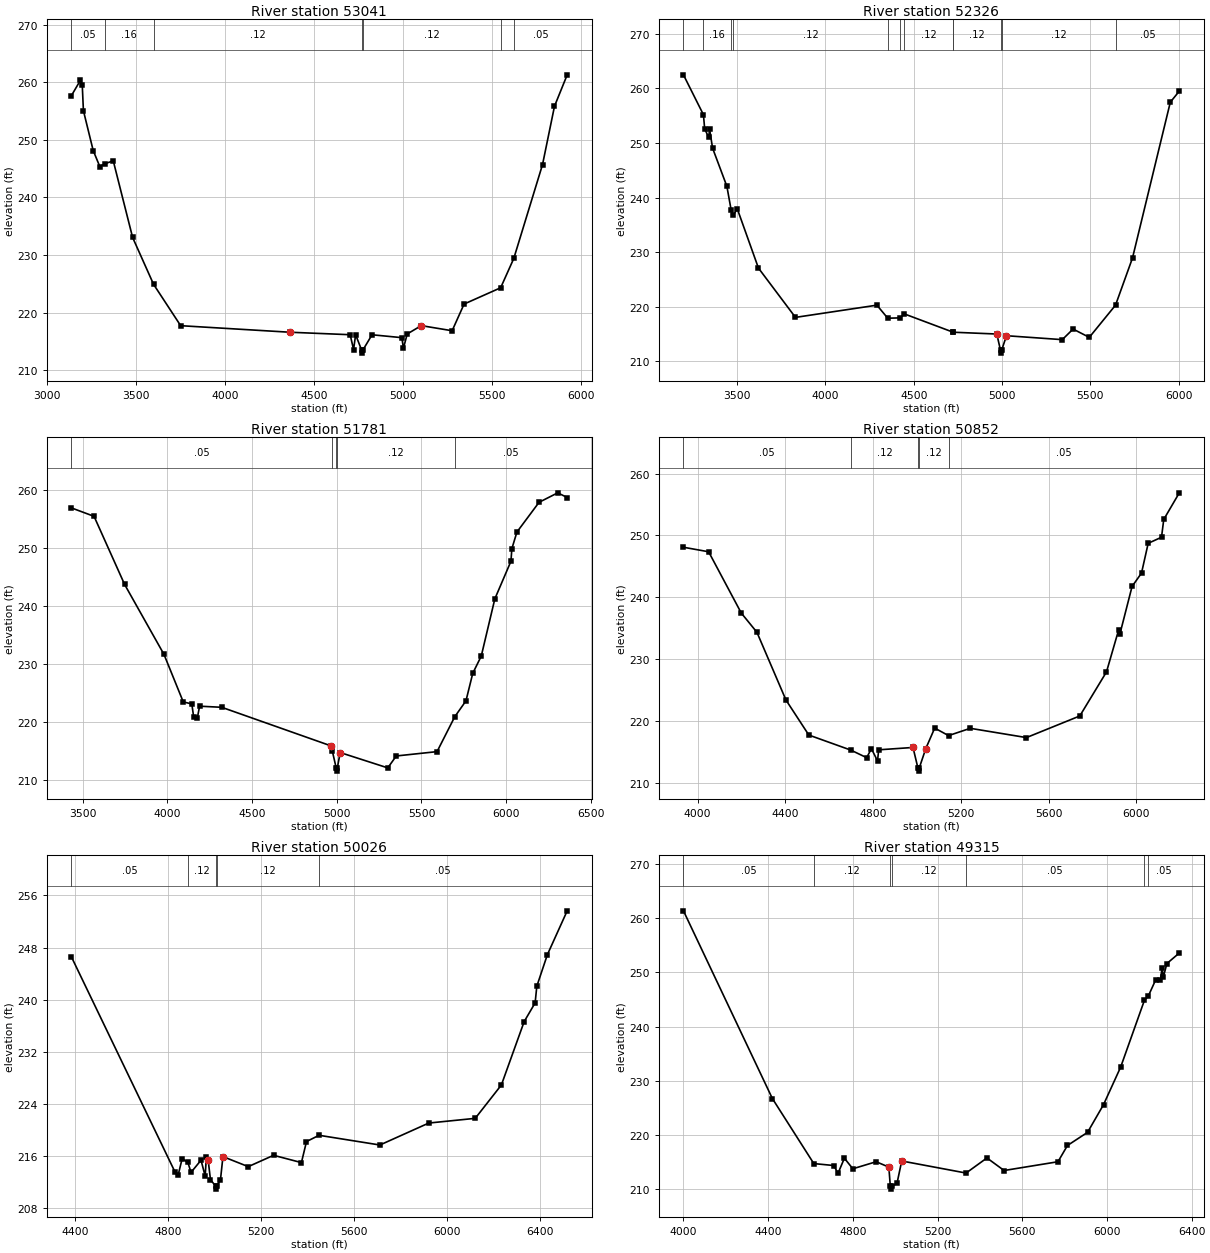
Type RM Length L Ch R = 1 ,53041   ,715,715,715
BEGIN DESCRIPTION:
BIG ELKHART CREEK 46.0
END DESCRIPTION:
XS GIS Cut Line= 3
      3754849.59     10524510.19      3753049.61     10524110.19
       3752249.6     10524610.19
#Sta/Elev= 30
  3135.7  257.67  3186.9  260.37  3197.1  259.54  3203.6  255.08  3258.6  248.15
  3295.7  245.37  3325.8  245.87  3371.3  246.37  3480.1  233.05  3597.9   224.9
  3750.3  217.71    4365  216.57    4703  216.14  4722.2  213.57  4733.7  216.13
  4767.9  213.44  4770.6  212.94  4773.9  213.44  4825.9  216.13  4993.2  215.63
  5002.6  213.81  5023.8  216.27  5102.8  217.72  5276.2  216.83  5343.4  221.47
    5549   224.3  5622.8   229.4  5784.4  245.72  5851.6  255.85    5923  261.31
#Mann= 7 ,-1 , 0
  3135.7     .05       0  3325.8     .16       0  3597.9     .12       0
  4767.9     .07       0  4773.9     .12       0    5549     .16       0
  5622.8     .05       0
Bank Sta=4365,5102.8
XS Rating Curve= 0 ,0
Exp/Cntr=0.3,0.1

Type RM Length L Ch R = 1 ,52326   ,545,545,545
BEGIN DESCRIPTION:
BIG ELKHART CREEK 45.0
END DESCRIPTION:
XS GIS Cut Line= 3
      3754799.65     10524310.21      3753199.61     10523510.19
      3752199.61     10523310.19
#Sta/Elev= 30
  3195.6  262.49  3308.8  255.18  3315.8   252.6  3338.2  251.04  3343.8  252.49
  3360.6  249.06  3441.6  242.06    3466  237.68  3477.8  236.73  3500.3  237.96
  3620.5  227.07  3830.1  218.04  4291.3  220.28  4352.9  217.89  4422.7  217.95
  4447.4  218.67    4722  215.34  4723.6  215.32  4970.5  214.99  4991.7  211.99
  4994.4  211.49  4997.7  211.99  5025.3  214.68  5341.4  213.96  5402.6   215.9
  5494.4  214.38    5643  220.28  5739.2  228.93  5953.3  257.47  6004.3  259.51
#Mann= 12 ,-1 , 0
  3195.6     .05       0  3308.8     .16       0    3466     .05       0
  3477.8     .12       0  4352.9     .05       0  4422.7     .07       0
  4447.4     .12       0    4722     .07       0  4723.6     .12       0
  4991.7     .07       0  4997.7     .12       0    5643     .05       0
Bank Sta=4970.5,5025.3
XS Rating Curve= 0 ,0
Exp/Cntr=0.3,0.1

Type RM Length L Ch R = 1 ,51781   ,929,929,929
BEGIN DESCRIPTION:
BIG ELKHART CREEK 44.0
END DESCRIPTION:
XS GIS Cut Line= 3
      3754909.52     10522936.85      3753813.63     10523218.96
      3752023.98     10523067.11
#Sta/Elev= 30
  3432.7  256.98  3566.8  255.52  3747.2  243.75  3979.9  231.65  4093.5  223.45
    4144   223.1  4155.4  220.77  4176.1  220.59  4189.9  222.71  4320.6  222.52
  4964.3  215.87    4974  214.91  4996.9  211.99  4999.6  211.49  5002.9  211.99
    5020   214.7    5301  212.05  5351.2  214.11    5592  214.86  5696.6  220.89
  5762.6  223.63  5802.8  228.39    5853  231.37  5933.2  241.26  6028.4  247.77
  6033.6  249.92  6063.7  252.81  6194.2  257.94  6304.6  259.58  6360.4  258.77
#Mann= 5 ,-1 , 0
  3432.7     .05       0    4974     .12       0  4996.9     .07       0
  5002.9     .12       0  5696.6     .05       0
Bank Sta=4964.3,5020
XS Rating Curve= 0 ,0
Exp/Cntr=0.3,0.1

Type RM Length L Ch R = 1 ,50852   ,826,826,826
BEGIN DESCRIPTION:
BIG ELKHART CREEK 43.0
END DESCRIPTION:
XS GIS Cut Line= 3
      3754549.58      10522260.2      3753549.61     10522560.19
      3752349.66     10522760.18
#Sta/Elev= 30
  3935.1  248.09  4049.9  247.36  4198.7  237.44    4270  234.33  4402.3  223.37
  4506.7  217.69  4698.4  215.25  4770.3  214.03    4792  215.48  4819.9   213.5
  4825.1   215.3  4981.6  215.68    5004  212.35  5006.7  211.85    5010  212.35
  5039.9   215.5  5080.5  218.82  5143.6   217.6  5242.7  218.78  5498.7  217.28
    5742  220.78  5863.6  227.91  5919.4  234.75  5924.5  234.01  5980.2  241.74
  6023.3  243.91  6053.7  248.73  6114.5  249.71  6124.7  252.59  6195.6   256.9
#Mann= 5 ,-1 , 0
  3935.1     .05       0  4698.4     .12       0    5004     .07       0
    5010     .12       0  5143.6     .05       0
Bank Sta=4981.6,5039.9
XS Rating Curve= 0 ,0
Exp/Cntr=0.3,0.1

Type RM Length L Ch R = 1 ,50026   ,711,711,711
BEGIN DESCRIPTION:
BIG ELKHART CREEK 42.0
END DESCRIPTION:
XS GIS Cut Line= 3
      3754399.56     10522160.18      3753799.61     10522060.19
      3752399.59      10522660.2
#Sta/Elev= 30
  4384.1  246.59  4830.1  213.53  4842.8  213.03  4860.5  215.61    4885  215.03
  4898.6   213.5  4941.6  215.37  4959.4  212.92  4964.4  215.81  4972.1  215.42
  4982.2  212.37  5003.8  211.43  5006.6  210.93  5009.8  211.43    5025  212.32
  5035.8  215.92  5144.6  214.38  5253.4  216.12  5373.1     215  5394.9  218.23
    5449  219.19  5710.4   217.7  5920.7  221.07  6120.2  221.79  6232.6  226.91
  6330.5  236.63  6377.7  239.51  6384.9  242.06  6430.3   246.9  6515.5  253.63
#Mann= 5 ,-1 , 0
  4384.1     .05       0    4885     .12       0  5003.8     .07       0
  5009.8     .12       0    5449     .05       0
Bank Sta=4972.1,5035.8
XS Rating Curve= 0 ,0
Exp/Cntr=0.3,0.1

Type RM Length L Ch R = 1 ,49315   ,897,897,897
BEGIN DESCRIPTION:
BIG ELKHART CREEK 41.0
END DESCRIPTION:
XS GIS Cut Line= 3
      3754649.63     10521510.19      3753649.61     10521510.19
      3752449.58     10520910.17
#Sta/Elev= 30
  4000.1  261.37  4420.1  226.69  4615.7  214.68  4710.1  214.32  4730.1  212.88
  4760.1  215.67  4800.1  213.72  4910.1  215.02  4970.1  214.03  4977.1  210.46
  4979.9  209.96  4983.1  210.46  5008.5     211  5030.9  215.16  5334.8  212.93
  5433.4  215.72  5514.4   213.4  5768.8  215.02  5813.5  218.02  5908.5  220.45
    5984  225.57  6065.1  232.53    6177  244.84  6194.6  245.56    6230   248.6
  6252.3  248.58  6260.7  250.87  6266.3  249.11  6283.1  251.63  6341.8  253.58
#Mann= 7 ,-1 , 0
  4000.1     .05       0  4615.7     .12       0  4977.1     .07       0
  4983.1     .12       0  5334.8     .05       0    6177     .16       0
  6194.6     .05       0
Bank Sta=4970.1,5030.9
XS Rating Curve= 0 ,0
Exp/Cntr=0.3,0.1

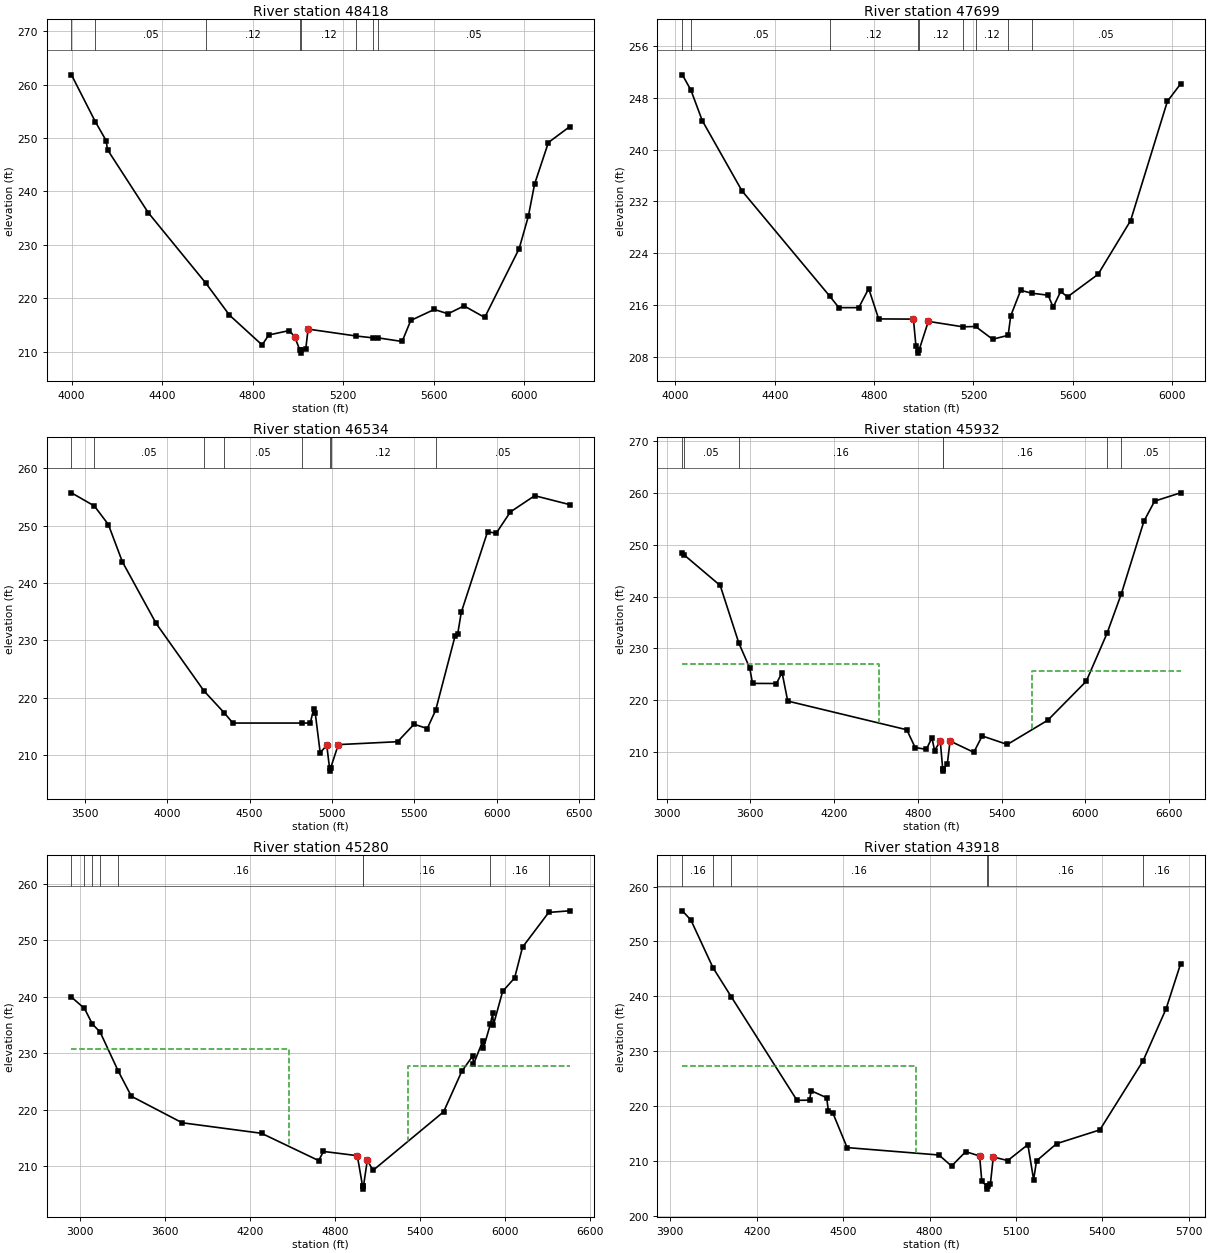
Type RM Length L Ch R = 1 ,48418   ,719,719,719
BEGIN DESCRIPTION:
BIG ELKHART CREEK 40.0
END DESCRIPTION:
XS GIS Cut Line= 3
      3754649.61     10521460.19      3753749.61     10521060.19
      3752549.65      10520860.2
#Sta/Elev= 30
  3999.7  261.85    4105  253.09  4152.9  249.53  4159.1  247.82  4338.9  236.04
  4594.5  222.78    4698  216.84  4842.3  211.25  4871.7  213.12  4962.7  213.95
  4987.1  212.71  5009.5  210.22  5012.2  209.72  5015.5  210.22  5035.3  210.54
  5045.4  214.22  5259.2  212.92  5332.7  212.58    5353  212.59  5461.1   211.9
  5499.1  215.84    5603   217.9  5663.8  217.09  5734.8  218.57    5826   216.4
  5978.1  229.28  6018.7  235.33  6046.5   241.4  6107.4  249.17  6201.1  252.13
#Mann= 8 ,-1 , 0
  3999.7     .16       0    4105     .05       0  4594.5     .12       0
  5009.5     .07       0  5015.5     .12       0  5259.2     .05       0
  5332.7     .16       0    5353     .05       0
Bank Sta=4987.1,5045.4
XS Rating Curve= 0 ,0
Exp/Cntr=0.3,0.1

Type RM Length L Ch R = 1 ,47699   ,1165,1165,1165
BEGIN DESCRIPTION:
BIG ELKHART CREEK 39.0
END DESCRIPTION:
XS GIS Cut Line= 3
      3754599.58     10520660.19      3753599.61     10520660.19
      3752599.57     10520760.19
#Sta/Elev= 30
  4028.3  251.54  4062.6  249.19  4108.3  244.48  4268.3  233.63  4621.9  217.36
  4658.3  215.61  4738.3  215.61  4778.3  218.55  4818.3  213.87  4958.3  213.84
  4968.3  209.74  4975.3  209.09    4978  208.59  4981.3  209.09  5018.3  213.49
  5157.4  212.65  5208.6   212.7    5277  210.73  5339.6  211.34  5349.9  214.34
  5390.1  218.29  5433.8  217.84  5500.6  217.53  5520.7  215.67  5550.9  218.11
  5578.5  217.27  5701.6  220.76  5832.3  229.03  5980.5  247.45  6033.3  250.12
#Mann= 9 ,-1 , 0
  4028.3     .16       0  4062.6     .05       0  4621.9     .12       0
  4975.3     .07       0  4981.3     .12       0  5157.4     .16       0
  5208.6     .12       0  5339.6     .16       0  5433.8     .05       0
Bank Sta=4958.3,5018.3
XS Rating Curve= 0 ,0
Exp/Cntr=0.3,0.1

Type RM Length L Ch R = 1 ,46534   ,602,602,602
BEGIN DESCRIPTION:
BIG ELKHART CREEK 38.0
END DESCRIPTION:
XS GIS Cut Line= 4
      3754857.05     10520559.27       3754346.6      10520090.5
      3752737.23     10520069.66      3752367.43     10520689.47
#Sta/Elev= 30
  3418.5  255.74  3557.5  253.45  3642.7  250.21  3727.3  243.74  3932.5  232.98
  4223.1  221.21  4344.8  217.43  4398.6  215.61  4820.7  215.61  4868.6  215.61
  4888.6  218.03  4898.6  217.36  4928.6  210.45  4968.6  211.72  4985.6  207.73
  4988.4  207.23  4991.6  207.73  5038.6  211.85  5398.6  212.36  5498.7  215.41
  5578.7  214.65  5629.6  217.84  5748.2  230.85  5763.8  231.19  5785.2  234.92
  5944.8  248.95  5997.4   248.7    6083   252.4  6230.9  255.24  6442.8  253.69
#Mann= 8 ,-1 , 0
  3418.5     .16       0  3557.5     .05       0  4223.1     .16       0
  4344.8     .05       0  4820.7     .12       0  4985.6     .07       0
  4991.6     .12       0  5629.6     .05       0
Bank Sta=4968.6,5038.6
XS Rating Curve= 0 ,0
Exp/Cntr=0.3,0.1

Type RM Length L Ch R = 1 ,45932   ,652,652,652
BEGIN DESCRIPTION:
BIG ELKHART CREEK 37.0
END DESCRIPTION:
XS GIS Cut Line= 4
      3755278.94     10519741.54      3754065.35     10519600.91
      3752560.15     10519637.37      3751815.33     10520028.01
#Sta/Elev= 30
  3112.7   248.3  3122.2  248.07  3383.8  242.12  3517.6  231.01  3595.2  226.25
  3615.4  223.28  3786.5  223.26  3826.8  225.37  3867.5  219.88  4720.3  214.36
  4780.3  210.94  4860.3  210.59  4900.3  212.81  4919.7  210.36  4960.3  212.19
  4977.3   206.9  4980.1   206.4  4983.3   206.9  5010.3   207.7  5030.4  212.19
  5200.4  210.02  5260.4  213.17  5440.5  211.53  5730.6   216.2    6006   223.7
  6154.7  232.91    6257   240.5  6419.4  254.51  6495.6  258.35  6681.1  259.95
#Mann= 7 ,-1 , 0
  3112.7     .16       0  3122.2     .05       0  3517.6     .16       0
  4977.3     .07       0  4983.3     .16       0  6154.7     .16       0
    6257     .05       0
#XS Ineff= 2 , 0
         4518.18  226.98 5620.45          225.58
Permanent Ineff=
       F       F
Bank Sta=4960.3,5030.4
XS Rating Curve= 0 ,0
Exp/Cntr=0.3,0.1

Type RM Length L Ch R = 1 ,45280   ,1362,1362,1362
BEGIN DESCRIPTION:
Mapping XS 123afe6c
END DESCRIPTION:
XS GIS Cut Line= 4
      3755217.89     10519634.98      3753717.85      10519218.3
      3752712.65     10519067.26       3751775.1     10519202.68
#Sta/Elev= 30
  2937.7  239.96  3029.7  237.96  3085.1  235.21  3140.4  233.77    3268  226.89
  3361.4  222.41  3720.5  217.72    4281  215.86  4684.9  211.03  4718.8  212.65
  4957.9   211.9  4995.4  206.48  4998.1  205.98  5001.4  206.48  5028.7  211.08
  5069.2   209.3  5568.1  219.67    5696  226.81    5774  229.56  5779.1  228.09
  5844.4  232.16  5849.4  230.93    5898  235.13  5914.7  237.08  5919.8  235.03
  5985.1  240.97  6069.8  243.36  6125.7   248.8  6310.8  254.95  6458.3  255.23
#Mann= 9 ,-1 , 0
  2937.7     .16       0  3029.7     .05       0  3085.1     .16       0
  3140.4     .05       0    3268     .16       0  4995.4     .07       0
  5001.4     .16       0    5898     .16       0  6310.8     .05       0
#XS Ineff= 2 , 0
         4475.41  230.79 5313.64          227.78
Permanent Ineff=
       F       F
Bank Sta=4957.9,5028.7
XS Rating Curve= 0 ,0
Exp/Cntr=0.3,0.1

Type RM Length L Ch R = 1 ,43918   ,667,667,667
BEGIN DESCRIPTION:
BIG ELKHART CREEK 36.0
END DESCRIPTION:
XS GIS Cut Line= 3
       3754499.6     10518860.18      3753599.61     10518360.19
      3752899.56     10518360.19
#Sta/Elev= 30
  3941.8  255.57  3971.5  253.88  4048.1  245.21  4112.2  239.85  4339.9  221.02
  4383.4  221.06  4389.1  222.77  4442.8   221.5  4448.6  219.17  4464.6  218.68
  4513.8  212.41  4832.9  211.06  4876.4  209.04  4925.6  211.67  4973.9  210.88
  4981.4  206.33  4998.4  205.34  5001.1  204.84  5004.4  205.34  5011.4  205.82
  5021.4  210.71  5071.4  210.04  5141.4  212.95  5161.4  206.55  5171.4  209.99
  5241.4  213.13  5391.4  215.64  5541.4  228.22  5621.4  237.72  5671.4  245.86
#Mann= 6 ,-1 , 0
  3941.8     .16       0  4048.1     .05       0  4112.2     .16       0
  4998.4     .07       0  5004.4     .16       0  5541.4     .16       0
#XS Ineff= 2 , 0
          4751.4  227.33
Permanent Ineff=
       F       F
Bank Sta=4973.9,5021.4
XS Rating Curve= 0 ,0
Exp/Cntr=0.3,0.1