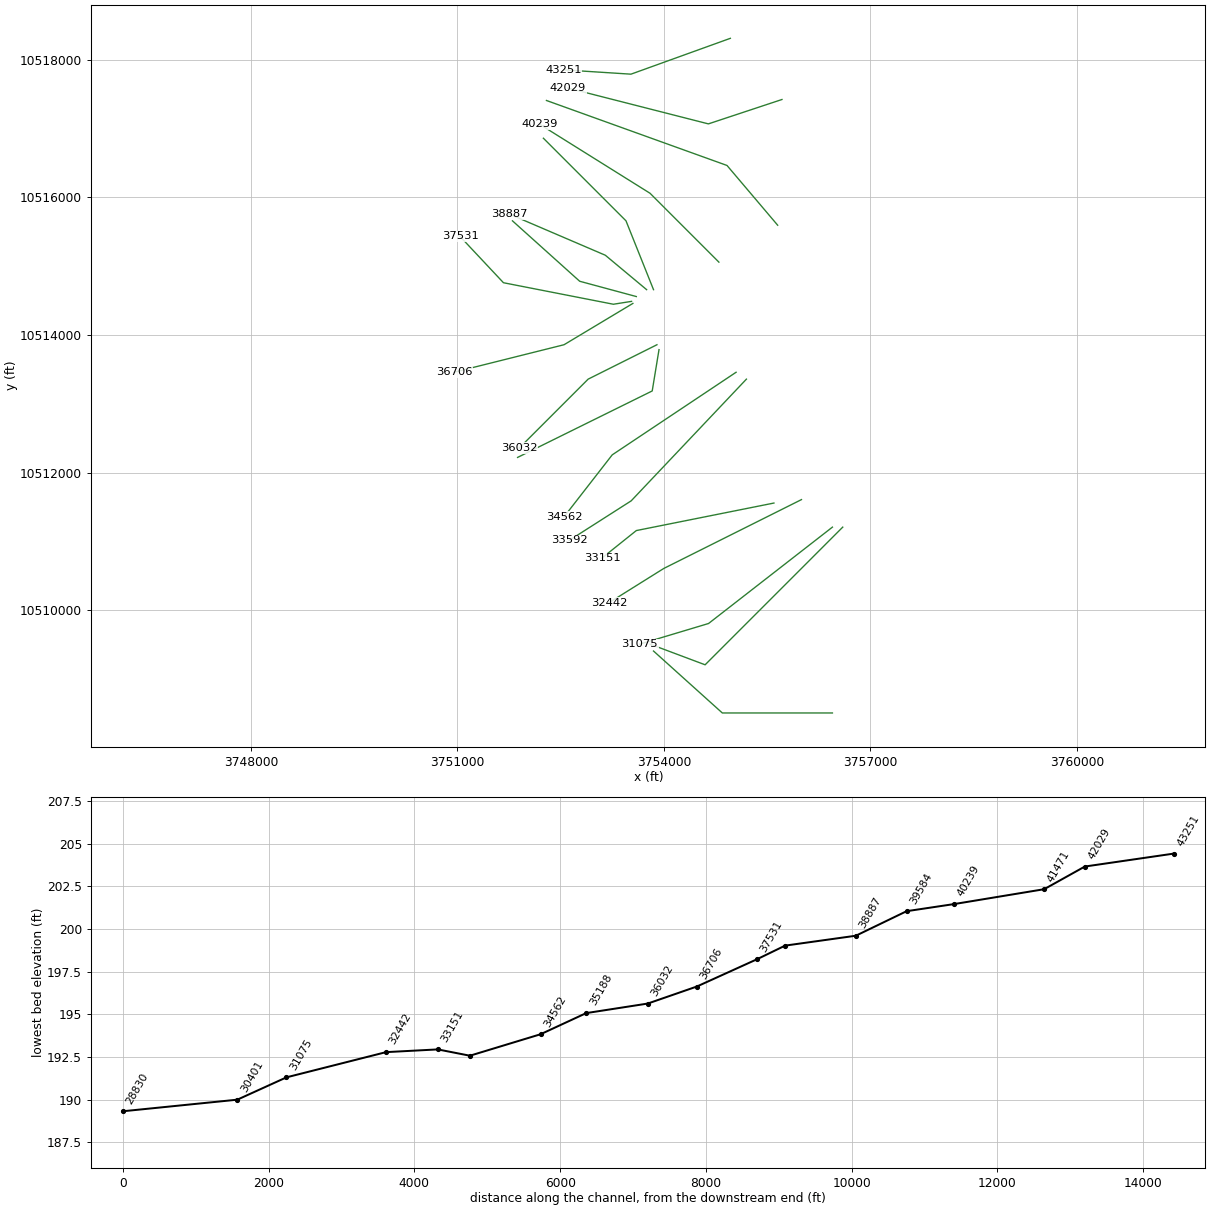
HEC-RAS study BIG ELKHART CREEK.prj: BIG ELKHART CREEK Base Level Engineering

--- BIG ELKHART CREEK.g01 (geometry) --- (continued)

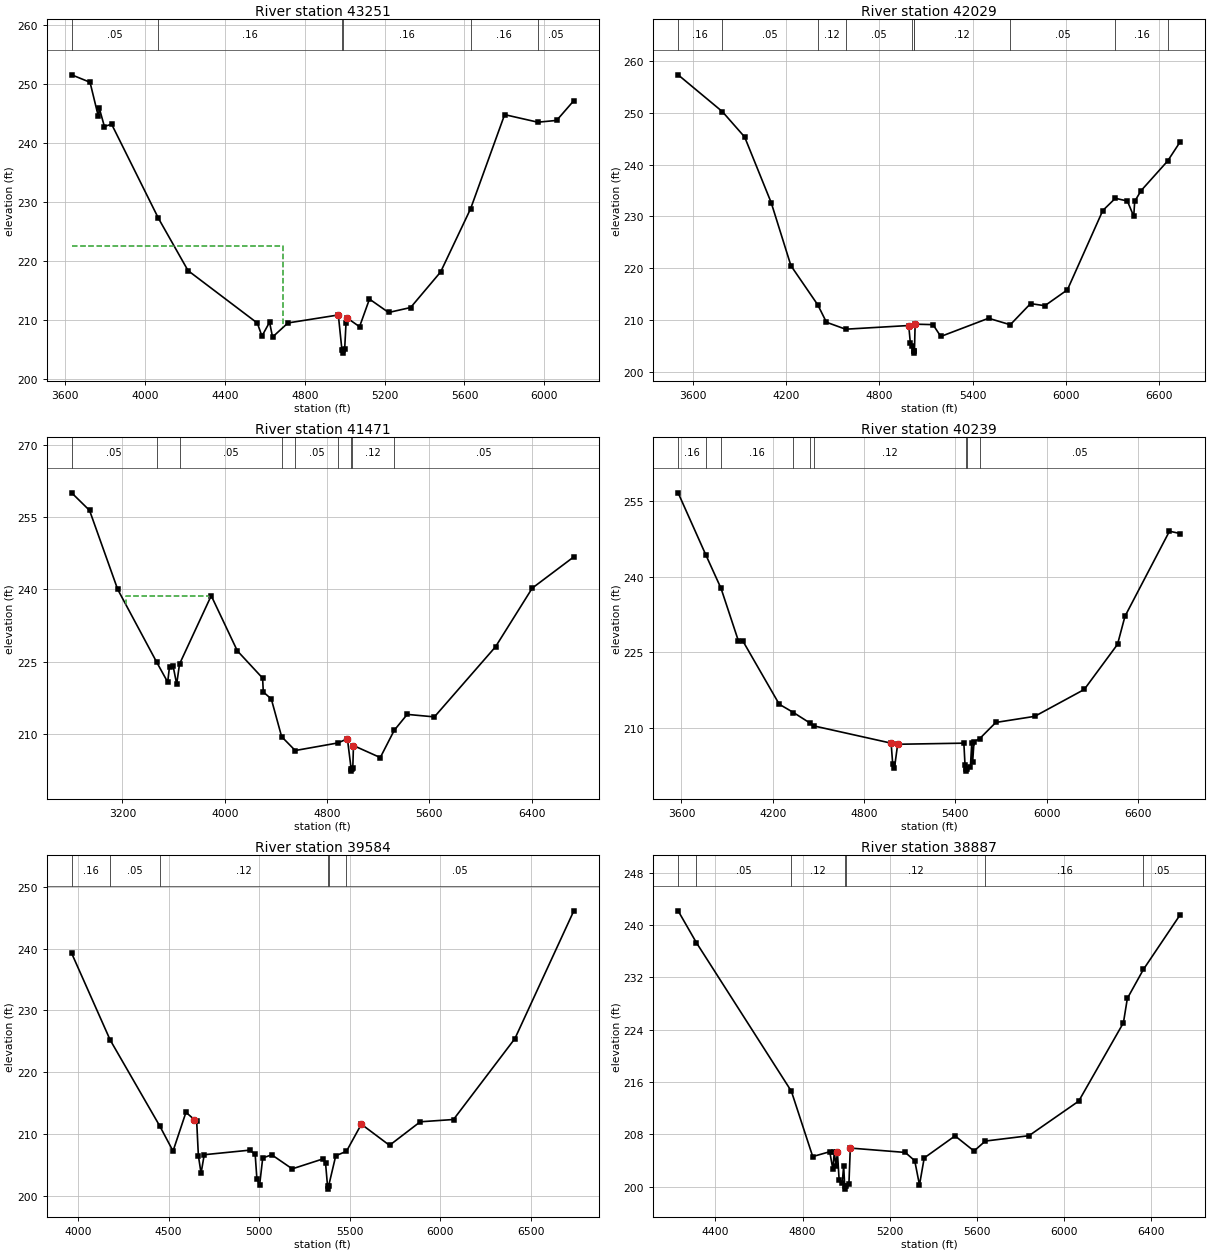
Type RM Length L Ch R = 1 ,43251   ,1222,1222,1222
BEGIN DESCRIPTION:
BIG ELKHART CREEK 35.0
END DESCRIPTION:
XS GIS Cut Line= 3
      3754966.29     10518311.85      3753521.82     10517791.01
      3752543.61     10517853.45
#Sta/Elev= 30
  3632.3  251.55  3724.4  250.29  3765.8  244.54  3771.1  245.86  3796.4   242.8
  3832.4   243.2  4067.3  227.24  4215.4   218.4  4562.4  209.52  4585.5  207.31
  4623.8  209.67  4638.6  207.15  4715.8  209.54  4968.2  210.89  4986.4  204.93
  4989.2  204.43  4992.4  204.93  5000.1   205.2  5006.7   209.5    5012  210.39
  5074.5   208.9  5124.2  213.58  5220.1  211.31  5330.3  212.15  5480.6  218.17
    5631  228.89  5801.3  244.81  5967.6  243.53  6061.8  243.83    6148  247.18
#Mann= 6 ,-1 , 0
  3632.3     .05       0  4067.3     .16       0  4986.4     .07       0
  4992.4     .16       0    5631     .16       0  5967.6     .05       0
#XS Ineff= 2 , 0
         4691.48  222.53
Permanent Ineff=
       F       F
Bank Sta=4968.2,5012
XS Rating Curve= 0 ,0
Exp/Cntr=0.3,0.1

Type RM Length L Ch R = 1 ,42029   ,558,558,558
BEGIN DESCRIPTION:
BIG ELKHART CREEK 34.0
END DESCRIPTION:
XS GIS Cut Line= 3
      3755716.25     10517422.95      3754646.82     10517068.79
      3752605.16     10517589.62
#Sta/Elev= 30
  3503.3   257.3  3788.2  250.21  3931.7  245.32    4103  232.64  4229.8  220.51
  4402.6  212.97  4458.4  209.62  4581.9  208.28  4988.2  208.99  4998.5  205.65
  5011.3  205.05  5019.1  204.17  5021.8  203.67  5025.1  204.17  5029.5  209.25
  5144.7  209.16  5194.6  206.88  5502.2  210.39  5642.1  209.14  5772.5  213.21
  5864.8  212.81  6009.9  215.87  6237.8  231.15  6318.6  233.51  6396.1  232.98
    6437  230.04  6443.3  232.92  6484.6  234.99  6655.5   240.7  6736.9  244.43
#Mann= 10 ,-1 , 0
  3503.3     .16       0  3788.2     .05       0  4402.6     .12       0
  4581.9     .05       0  5011.3     .12       0  5019.1     .03       0
  5025.1     .12       0  5642.1     .05       0  6318.6     .16       0
  6655.5     .05       0
Bank Sta=4988.2,5029.5
XS Rating Curve= 0 ,0
Exp/Cntr=0.3,0.1

Type RM Length L Ch R = 1 ,41471   ,1232,1232,1232
BEGIN DESCRIPTION:
BIG ELKHART CREEK 33.0
END DESCRIPTION:
XS GIS Cut Line= 3
      3755653.75     10515596.58      3754917.65     10516464.62
      3752293.64      10517408.7
#Sta/Elev= 30
  2802.4  260.02  2942.5  256.37  3162.2  240.02  3466.8  224.95  3553.3  220.79
  3567.6  223.99    3595  224.22  3623.6  220.38  3645.9  224.53  3893.8   238.7
  4097.9  227.27  4295.6  221.62  4300.9  218.74  4363.5   217.3  4444.2  209.49
  4550.7  206.61  4883.5  208.18  4958.7  209.04  4987.6  202.84  4990.3  202.34
  4993.6  202.84  5000.7  202.96  5006.1  207.64  5215.7  205.15  5324.8   210.8
  5426.3   214.1  5638.9  213.58  6117.1  228.12    6404  240.27  6729.2  246.75
#Mann= 9 ,-1 , 0
  2802.4     .05       0  3466.8     .16       0  3645.9     .05       0
  4444.2     .07       0  4550.7     .05       0  4883.5     .12       0
  4987.6     .07       0  4993.6     .12       0  5324.8     .05       0
#XS Ineff= 1 ,-1
  3226.7  3879.5  238.57
Permanent Ineff=
       F
Bank Sta=4958.7,5006.1
XS Rating Curve= 0 ,0
Exp/Cntr=0.3,0.1

Type RM Length L Ch R = 1 ,40239   ,655,655,655
BEGIN DESCRIPTION:
BIG ELKHART CREEK 32.0
END DESCRIPTION:
XS GIS Cut Line= 3
      3754799.62     10515060.17      3753799.61     10516060.19
      3752199.64     10517060.17
#Sta/Elev= 30
  3577.8  256.59  3760.5  244.26    3860  237.66  3973.8  227.29  4002.1  227.31
  4242.5  214.72  4335.8  213.08  4446.8  210.95  4469.2  210.43  4977.9  207.01
  4988.5   202.8  4999.7  202.05  5020.9  206.79  5456.1  207.01  5463.7  202.63
  5468.4  201.97  5471.1  201.47  5474.4  201.97  5499.1  202.36    5508  207.03
  5513.9   203.3  5522.7  207.29  5560.6  207.92    5666  211.11  5921.9  212.32
  6247.3  217.64  6466.1  226.58    6515  232.13  6807.5  248.99  6878.8  248.52
#Mann= 9 ,-1 , 0
  3577.8     .16       0  3760.5     .05       0    3860     .16       0
  4335.8     .12       0  4446.8     .16       0  4469.2     .12       0
  5468.4     .07       0  5474.4     .12       0  5560.6     .05       0
Bank Sta=4977.9,5020.9
XS Rating Curve= 0 ,0
Exp/Cntr=0.3,0.1

Type RM Length L Ch R = 1 ,39584   ,697,697,697
BEGIN DESCRIPTION:
BIG ELKHART CREEK 31.0
END DESCRIPTION:
XS GIS Cut Line= 3
      3753849.61     10514660.18      3753449.61     10515660.19
      3752249.61     10516860.19
#Sta/Elev= 30
  3964.2  239.23    4177  225.19  4452.4  211.19  4524.3  207.21  4595.6  213.48
  4642.7  212.29  4654.9  212.01  4664.3  206.45  4679.1  203.62  4696.6  206.62
  4948.3  207.36    4978  206.67  4987.4  202.75  5002.2  201.64  5019.7  206.09
  5069.5  206.61  5182.7  204.33  5352.4  205.94  5366.5  205.34  5377.7  201.55
  5380.4  201.05  5383.7  201.55  5423.1  206.45  5482.4  207.18  5564.5  211.56
  5720.1  208.14  5889.8  211.95  6073.6  212.32    6413  225.43  6738.3   246.1
#Mann= 6 ,-1 , 0
  3964.2     .16       0    4177     .05       0  4452.4     .12       0
  5377.7     .07       0  5383.7     .12       0  5482.4     .05       0
Bank Sta=4642.7,5564.5
XS Rating Curve= 0 ,0
Exp/Cntr=0.3,0.1

Type RM Length L Ch R = 1 ,38887   ,970,970,970
BEGIN DESCRIPTION:
BIG ELKHART CREEK 30.0
END DESCRIPTION:
XS GIS Cut Line= 3
      3753749.58     10514660.22      3753149.61     10515160.19
      3751749.64     10515760.17
#Sta/Elev= 30
    4229  242.17  4312.9   237.3  4748.6  214.58  4846.6  204.59  4924.7  205.33
    4939  202.65  4945.5  205.28  4953.4  203.19  4959.9  205.23  4967.7  201.04
    4982  200.58  4988.5   203.2  4993.3  200.11  4996.1  199.61  4999.3  200.11
  5012.7  200.43    5019  205.89  5271.1  205.22  5314.6  203.96  5336.4  200.24
  5358.1  204.38  5499.6  207.75  5586.6  205.44  5638.5  206.96  5838.7  207.78
  6067.1  213.07    6272  225.04  6290.2  228.78  6363.9  233.21  6533.1   241.6
#Mann= 7 ,-1 , 0
    4229     .16       0  4312.9     .05       0  4748.6     .12       0
  4993.3     .07       0  4999.3     .12       0  5638.5     .16       0
  6363.9     .05       0
Bank Sta=4959.9,5019
XS Rating Curve= 0 ,0
Exp/Cntr=0.3,0.1

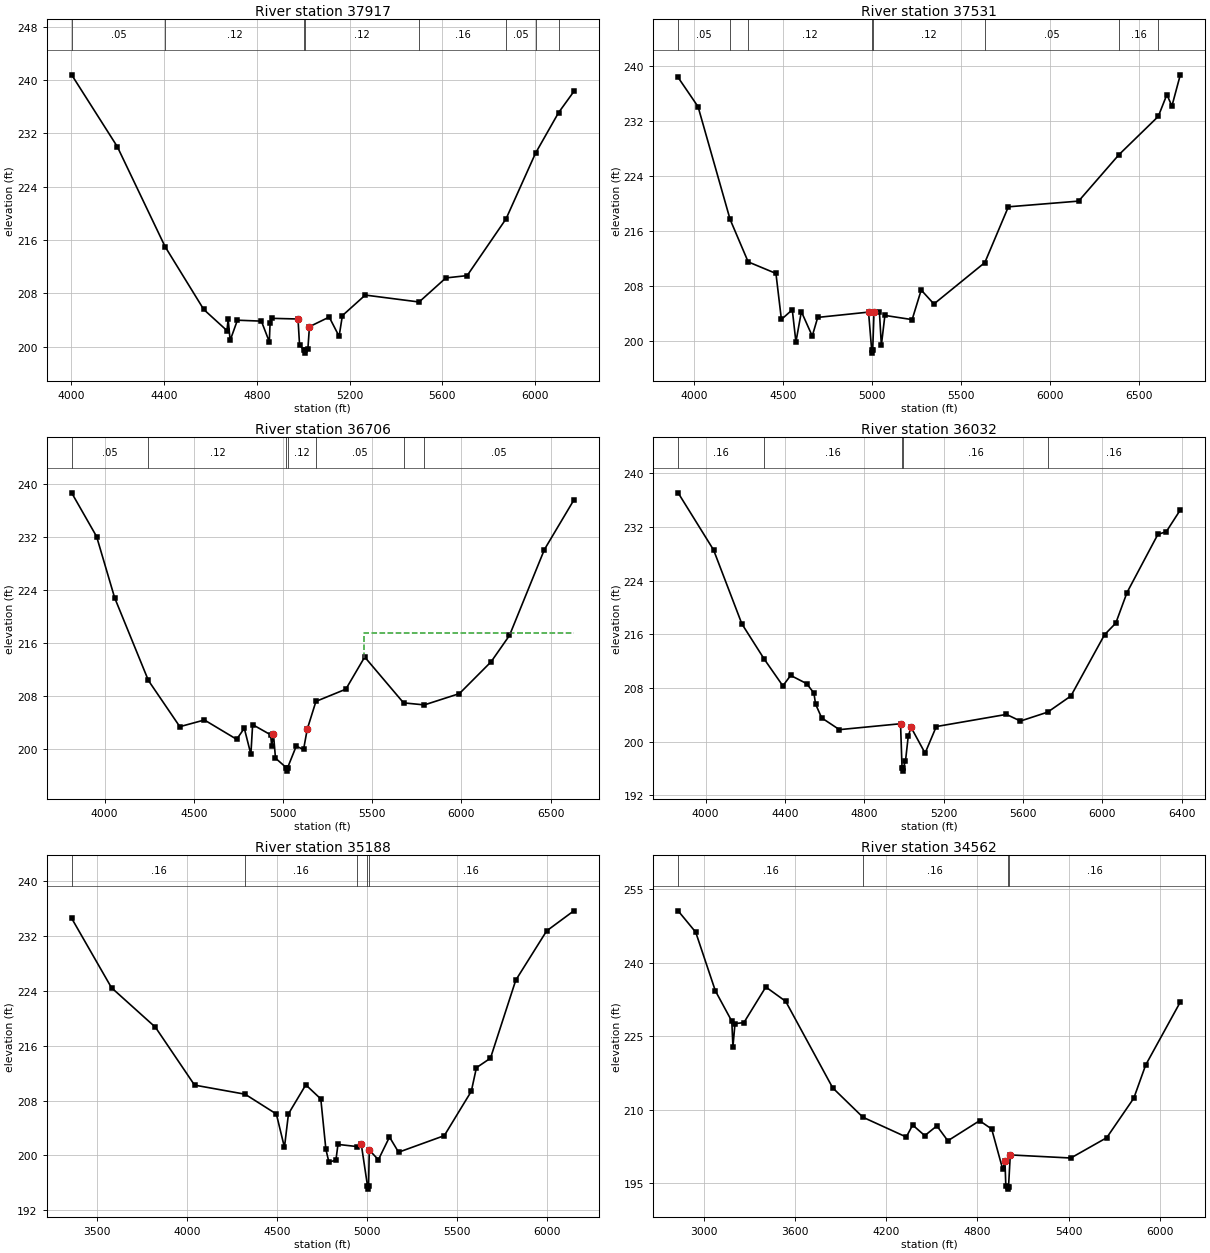
Type RM Length L Ch R = 1 ,37917   ,386,386,386
BEGIN DESCRIPTION:
BIG ELKHART CREEK 29.0
END DESCRIPTION:
XS GIS Cut Line= 3
      3753599.62     10514560.19      3752776.59     10514782.33
      3751799.62     10515660.17
#Sta/Elev= 30
  4000.9  240.78  4197.7  230.01  4403.8  215.01  4570.6  205.58  4670.7  202.41
  4675.9  204.09  4684.5  200.93  4715.8  203.97  4819.2  203.83  4853.4  200.73
  4856.8  203.59  4863.6  204.25  4977.2  204.15  4983.9  200.22  5002.6  199.53
  5005.4  199.03  5008.6  199.53  5019.8  199.69  5026.5     203  5111.7  204.44
  5154.4  201.55  5168.6  204.66  5267.2  207.74  5499.4   206.7  5614.8  210.31
  5706.7  210.66  5874.5  219.18  6001.5  229.02  6100.8   235.1  6166.8  238.28
#Mann= 8 ,-1 , 0
  4000.9     .05       0  4403.8     .12       0  5002.6     .07       0
  5008.6     .12       0  5499.4     .16       0  5874.5     .05       0
  6001.5     .16       0  6100.8     .05       0
Bank Sta=4977.2,5026.5
XS Rating Curve= 0 ,0
Exp/Cntr=0.3,0.1

Type RM Length L Ch R = 1 ,37531   ,825,825,825
BEGIN DESCRIPTION:
BIG ELKHART CREEK 28.0
END DESCRIPTION:
XS GIS Cut Line= 4
      3753530.13     10514490.04      3753266.22     10514448.37
        3751669.     10514760.87      3751037.07     10515434.46
#Sta/Elev= 30
  3912.2  238.29  4024.1  234.04  4203.8  217.67  4305.3  211.49  4461.2  209.81
  4491.8  203.13  4552.9  204.53  4573.3  199.85  4603.9  204.26    4665  200.71
  4695.6  203.42  4980.9  204.19  4998.3  198.73    5001  198.23  5004.3  198.73
  5011.5  204.16    5042  204.19  5052.8  199.36  5072.6  203.71  5225.5   203.1
  5276.4   207.4  5347.7  205.37  5633.5  211.39  5765.5  219.49  6159.8  220.32
  6386.3  227.07  6606.9  232.63  6655.1  235.79  6683.4  234.13  6730.5  238.67
#Mann= 8 ,-1 , 0
  3912.2     .05       0  4203.8     .07       0  4305.3     .12       0
  4998.3     .07       0  5004.3     .12       0  5633.5     .05       0
  6386.3     .16       0  6606.9     .05       0
Bank Sta=4980.9,5011.5
XS Rating Curve= 0 ,0
Exp/Cntr=0.3,0.1

Type RM Length L Ch R = 1 ,36706   ,674,674,674
BEGIN DESCRIPTION:
BIG ELKHART CREEK 27.0
END DESCRIPTION:
XS GIS Cut Line= 3
      3753549.59     10514460.18      3752549.61     10513860.19
      3750949.62     10513460.19
#Sta/Elev= 30
  3815.3   238.7  3955.2  232.09  4056.3  222.84  4245.6  210.33  4421.7  203.35
  4559.7  204.36  4740.5  201.44  4783.2  203.11  4820.1  199.17  4829.9  203.66
  4930.9  202.12  4936.8  200.38  4946.5  202.27  4958.1  198.59  5019.7  197.13
  5022.4  196.63  5025.7  197.13  5074.2  200.39  5115.5  199.91  5136.1  202.97
  5184.8  207.17  5352.5  209.02  5458.2  213.88    5676  206.95  5792.8  206.64
  5989.1  208.35  6166.9  213.16  6269.9  217.14  6465.8  230.13  6630.7  237.61
#Mann= 7 ,-1 , 0
  3815.3     .05       0  4245.6     .12       0  5019.7     .07       0
  5025.7     .12       0  5184.8     .05       0    5676     .12       0
  5792.8     .05       0
#XS Ineff= 2 , 0
                         5456.42          217.48
Permanent Ineff=
       F       F
Bank Sta=4946.5,5136.1
XS Rating Curve= 0 ,0
Exp/Cntr=0.3,0.1

Type RM Length L Ch R = 1 ,36032   ,844,844,844
BEGIN DESCRIPTION:
BIG ELKHART CREEK 26.0
END DESCRIPTION:
XS GIS Cut Line= 3
      3753899.57     10513860.17      3752899.61     10513360.19
      3751899.61     10512360.19
#Sta/Elev= 30
  3861.7  237.09  4040.5  228.58  4183.1  217.57  4296.3   212.3  4389.9  208.33
  4429.1  209.89  4510.1  208.66  4546.5  207.25  4554.8  205.61  4585.6  203.56
    4675  201.81  4983.2  202.69  4990.8  196.13  4993.6  195.63  4996.8  196.13
    5008  197.08  5022.1  200.84  5036.3  202.15    5107  198.31  5163.5  202.27
  5517.1  204.08  5587.8  203.09  5725.3  204.42  5842.4  206.83  6012.1  215.96
  6068.6  217.68  6125.2  222.24  6280.8   230.9  6323.2   231.3  6393.9  234.54
#Mann= 5 ,-1 , 0
  3861.7     .16       0  4296.3     .16       0  4990.8     .07       0
  4996.8     .16       0  5725.3     .16       0
Bank Sta=4983.2,5036.3
XS Rating Curve= 0 ,0
Exp/Cntr=0.3,0.1

Type RM Length L Ch R = 1 ,35188   ,626,626,626
BEGIN DESCRIPTION:
BIG ELKHART CREEK 25.0
END DESCRIPTION:
XS GIS Cut Line= 3
      3753929.42     10513788.67      3753830.75     10513188.64
      3751874.23     10512222.85
#Sta/Elev= 30
    3358  234.62  3579.4  224.48  3823.4  218.71  4040.8  210.26  4321.7  208.93
  4495.3  206.04  4540.2  201.17  4562.6  206.07  4658.8   210.3  4742.2  208.24
  4770.3  200.91  4787.1  199.02  4826.1   199.3  4837.6   201.6    4942  201.29
  4966.7  201.69  5001.5  195.57  5004.2  195.07  5007.5  195.57  5011.6  200.77
  5062.1  199.36  5123.8  202.68  5174.3  200.46  5428.3  202.88  5578.4  209.36
  5606.7   212.8  5684.8  214.19  5825.3  225.58    5997  232.78    6148  235.71
#Mann= 5 ,-1 , 0
    3358     .16       0  4321.7     .16       0    4942     .05       0
  5001.5     .03       0  5007.5     .16       0
Bank Sta=4966.7,5011.6
XS Rating Curve= 0 ,0
Exp/Cntr=0.3,0.1

Type RM Length L Ch R = 1 ,34562   ,970,970,970
BEGIN DESCRIPTION:
BIG ELKHART CREEK 24.0
END DESCRIPTION:
XS GIS Cut Line= 3
      3755049.62      10513460.2      3753249.61     10512260.19
      3752549.62     10511360.21
#Sta/Elev= 30
  2831.3  250.54    2947  246.19  3076.2  234.24  3184.4  228.05  3191.9  222.83
  3205.4  227.56    3264  227.76  3408.2  235.02  3538.9   232.1  3848.4  214.46
    4047  208.48  4332.1  204.45  4374.2   206.9  4453.8  204.73  4533.4  206.72
  4605.5  203.68  4814.4  207.77    4894  206.08  4966.1  197.93  4981.1  199.55
  4987.1   194.5  4998.9  194.33  5001.6  193.83  5004.9  194.33  5016.4   200.8
  5414.5  200.17  5650.7  204.31    5829  212.37  5906.8  219.11  6134.8  231.96
#Mann= 4 ,-1 , 0
  2831.3     .16       0    4047     .16       0  4998.9     .07       0
  5004.9     .16       0
Bank Sta=4981.1,5016.4
XS Rating Curve= 0 ,0
Exp/Cntr=0.3,0.1

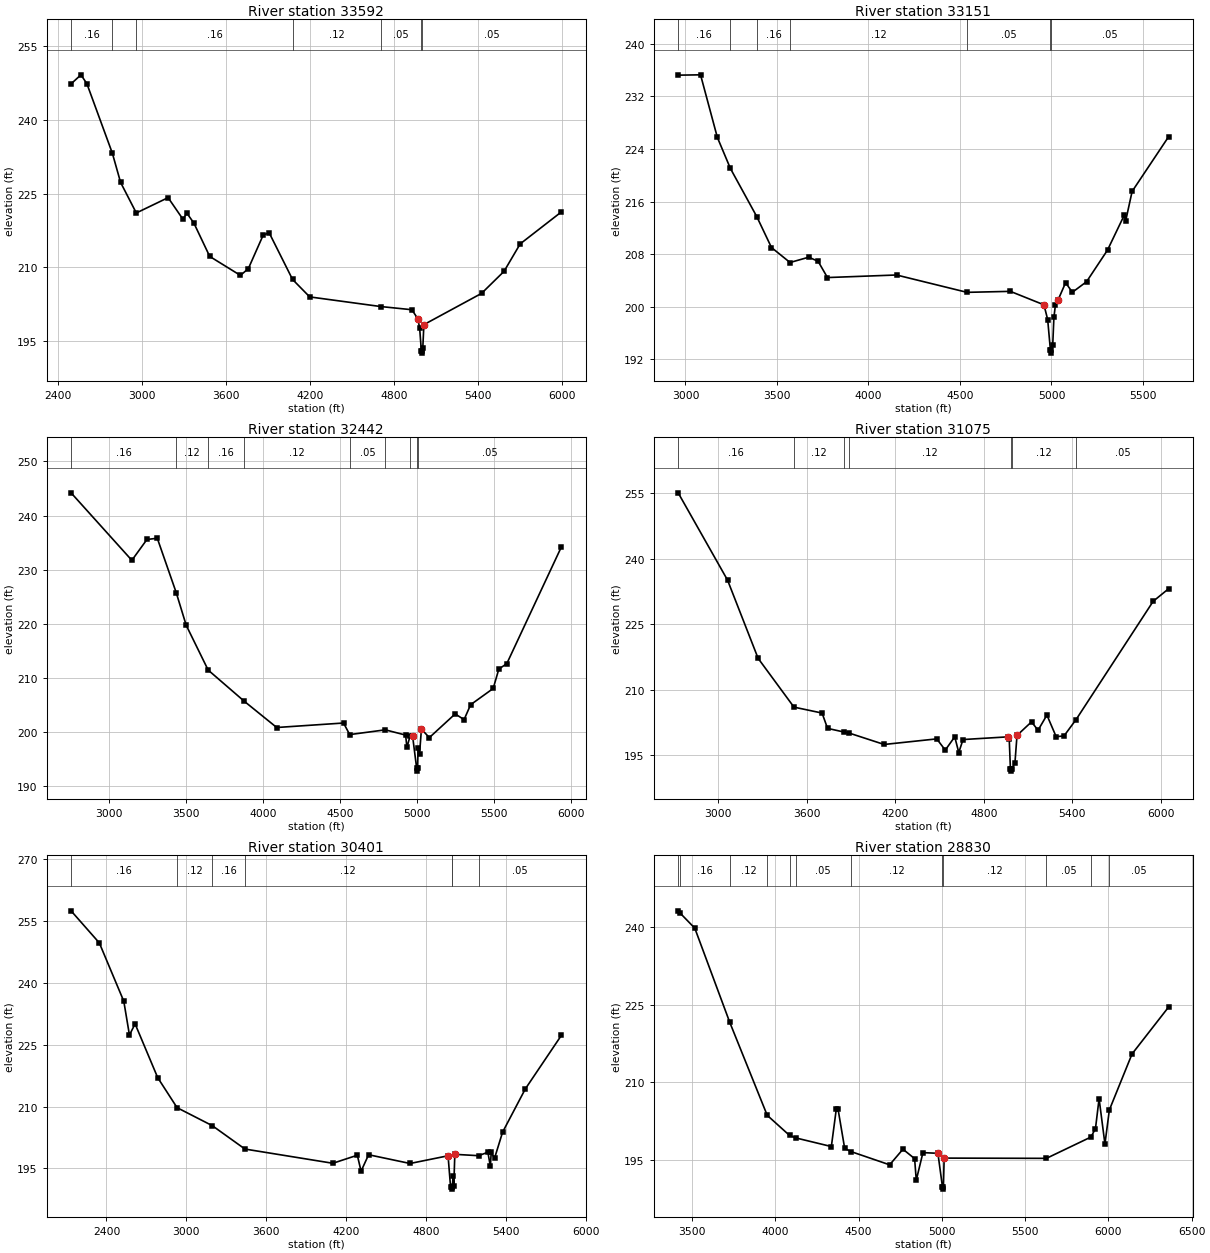
Type RM Length L Ch R = 1 ,33592   ,441,441,441
BEGIN DESCRIPTION:
BIG ELKHART CREEK 23.0
END DESCRIPTION:
XS GIS Cut Line= 3
      3755199.64     10513360.22      3753525.29     10511592.22
      3752624.66     10511017.12
#Sta/Elev= 30
  2492.5  247.36  2563.1   249.2  2605.6  247.39  2787.7  233.23  2846.3  227.31
  2958.6  221.09  3185.7  224.21  3291.7  219.82    3320  221.04  3369.8  219.04
    3483  212.25  3702.3  208.39  3758.9  209.76  3864.9  216.58  3907.4  217.08
  4074.9  207.56  4197.4  204.01  4704.5  202.05  4927.5   201.4  4969.8  199.55
  4982.7  197.69  4994.9  193.07  4997.7  192.57  5000.9  193.07  5005.4   193.7
  5013.1  198.37  5425.2  204.73  5585.9  209.22    5701   214.8  5996.1  221.32
#Mann= 7 ,-1 , 0
  2492.5     .16       0  2787.7     .12       0  2958.6     .16       0
  4074.9     .12       0  4704.5     .05       0  4994.9     .03       0
  5000.9     .05       0
Bank Sta=4969.8,5013.1
XS Rating Curve= 0 ,0
Exp/Cntr=0.3,0.1

Type RM Length L Ch R = 1 ,33151   ,709,709,709
BEGIN DESCRIPTION:
BIG ELKHART CREEK 22.0
END DESCRIPTION:
XS GIS Cut Line= 3
      3755599.57     10511560.18      3753599.61     10511160.19
       3753099.6     10510760.18
#Sta/Elev= 30
  2960.2  235.24  3082.5  235.29  3174.3  225.77  3245.7  221.04  3389.5  213.73
  3470.1  209.01  3571.6  206.73    3674  207.54    3725  206.91    3776  204.44
  4153.3  204.83  4538.7  202.19  4775.4  202.34    4959  200.29  4979.4  198.05
  4994.2  193.44    4997  192.94  5000.2  193.44    5007  194.19  5013.4  198.37
  5021.4   200.2  5035.8  201.01  5077.4  203.66  5114.2   202.2  5191.9  203.81
  5306.3  208.62  5397.6  213.92  5405.6  213.06  5440.8  217.55  5640.1  225.87
#Mann= 7 ,-1 , 0
  2960.2     .16       0  3245.7     .12       0  3389.5     .16       0
  3571.6     .12       0  4538.7     .05       0  4994.2     .03       0
  5000.2     .05       0
Bank Sta=4959,5035.8
XS Rating Curve= 0 ,0
Exp/Cntr=0.3,0.1

Type RM Length L Ch R = 1 ,32442   ,1367,1367,1367
BEGIN DESCRIPTION:
BIG ELKHART CREEK 21.0
END DESCRIPTION:
XS GIS Cut Line= 3
       3755999.6     10511610.19      3753999.61     10510610.19
      3753199.58     10510110.17
#Sta/Elev= 30
  2756.9   244.2    3151  231.73  3248.8  235.58  3315.9  235.81  3438.5  225.77
  3503.2  219.74  3645.8  211.45    3881  205.66  4090.2  200.84  4523.4  201.67
  4563.3  199.53  4794.1  200.41  4925.9  199.44  4934.3  197.15    4955   199.3
  4970.6  199.36  4997.6  193.28  5000.4  192.78  5003.6  193.28  5006.5  197.04
    5016  195.89  5028.3  200.55  5079.6  198.97  5247.1  203.35  5304.9   202.3
  5347.3  205.05  5493.6  208.05  5530.1  211.63    5582  212.65  5936.4  234.25
#Mann= 9 ,-1 , 0
  2756.9     .16       0  3438.5     .12       0  3645.8     .16       0
    3881     .12       0  4563.3     .05       0  4794.1     .12       0
    4955     .05       0  4997.6     .03       0  5003.6     .05       0
Bank Sta=4970.6,5028.3
XS Rating Curve= 0 ,0
Exp/Cntr=0.3,0.1

Type RM Length L Ch R = 1 ,31075   ,674,674,674
BEGIN DESCRIPTION:
BIG ELKHART CREEK 20.0
END DESCRIPTION:
XS GIS Cut Line= 3
       3756449.6     10511210.18      3754649.61     10509810.19
      3753649.58     10509510.18
#Sta/Elev= 30
  2727.6  255.09  3062.4  235.08  3269.6  217.15  3512.6  205.97  3703.1  204.61
  3740.2   201.1  3854.2  200.24    3887  200.02  4123.8  197.41  4480.4  198.69
  4538.3  196.12  4602.5  199.17  4629.7  195.56  4658.6  198.54  4965.4  199.16
  4971.7  198.71  4979.9  191.81  4983.2   191.8    4986   191.3  4989.2   191.8
  5010.5  193.18  5024.5  199.49  5122.8  202.59  5167.1  200.67  5227.2  204.15
  5289.8   199.2  5342.9  199.36  5425.2  203.13  5947.6  230.23    6052   233.1
#Mann= 7 ,-1 , 0
  2727.6     .16       0  3512.6     .12       0  3854.2     .16       0
    3887     .12       0  4983.2     .07       0  4989.2     .12       0
  5425.2     .05       0
Bank Sta=4965.4,5024.5
XS Rating Curve= 0 ,0
Exp/Cntr=0.3,0.1

Type RM Length L Ch R = 1 ,30401   ,1571,1571,1571
BEGIN DESCRIPTION:
BIG ELKHART CREEK 19.0
END DESCRIPTION:
XS GIS Cut Line= 3
      3756599.63     10511210.21      3754599.61     10509210.19
      3753799.57      10509510.2
#Sta/Elev= 30
  2134.3  257.49  2346.5  249.71  2530.3  235.56  2572.7  227.37  2615.2  230.07
  2784.9  217.03  2930.4  209.75    3195  205.38  3440.2  199.71  4100.1  196.26
  4283.9  198.21  4312.2  194.35  4368.8  198.33  4679.9  196.21  4965.4  198.08
  4984.1  190.56  4991.8  190.49  4994.6  189.99  4997.8  190.49  5002.8  193.11
  5008.2  190.67  5016.2  198.43  5194.8   198.1  5264.5  198.94  5283.2  195.48
  5289.4  198.92  5314.3  197.46  5374.8   203.8  5545.7   214.3  5817.2  227.32
#Mann= 7 ,-1 , 0
  2134.3     .16       0  2930.4     .12       0    3195     .16       0
  3440.2     .12       0  4991.8     .07       0  4997.8     .12       0
  5194.8     .05       0
Bank Sta=4965.4,5016.2
XS Rating Curve= 0 ,0
Exp/Cntr=0.3,0.1

Type RM Length L Ch R = 1 ,28830   ,2123,2123,2123
BEGIN DESCRIPTION:
BIG ELKHART CREEK 18.0
END DESCRIPTION:
XS GIS Cut Line= 3
      3756449.56     10508510.19      3754849.61     10508510.19
      3753849.62     10509410.18
#Sta/Elev= 30
  3416.1  243.22  3429.4  242.73  3516.1  239.85  3725.7  221.64  3950.9  203.61
  4085.1  199.71  4121.2  199.24  4336.1  197.56  4366.1  204.89  4376.1  204.85
  4416.1  197.21  4454.4  196.58  4686.1  194.02  4766.1  197.04  4836.1  195.22
  4846.1  191.05  4886.1  196.38  4976.1  196.25  5003.1  189.81  5005.8  189.31
  5009.1  189.81  5013.6  195.32  5627.6  195.27    5895   199.4  5922.3  201.03
    5944  206.84  5979.1  198.05  6005.8  204.66    6142   215.5  6361.4  224.58
#Mann= 12 ,-1 , 0
  3416.1      .1       0  3429.4     .16       0  3725.7     .12       0
  3950.9     .05       0  4085.1     .08       0  4121.2     .05       0
  4454.4     .12       0  5003.1     .07       0  5009.1     .12       0
  5627.6     .05       0    5895     .16       0  6005.8     .05       0
Bank Sta=4976.1,5013.6
XS Rating Curve= 0 ,0
Exp/Cntr=0.3,0.1