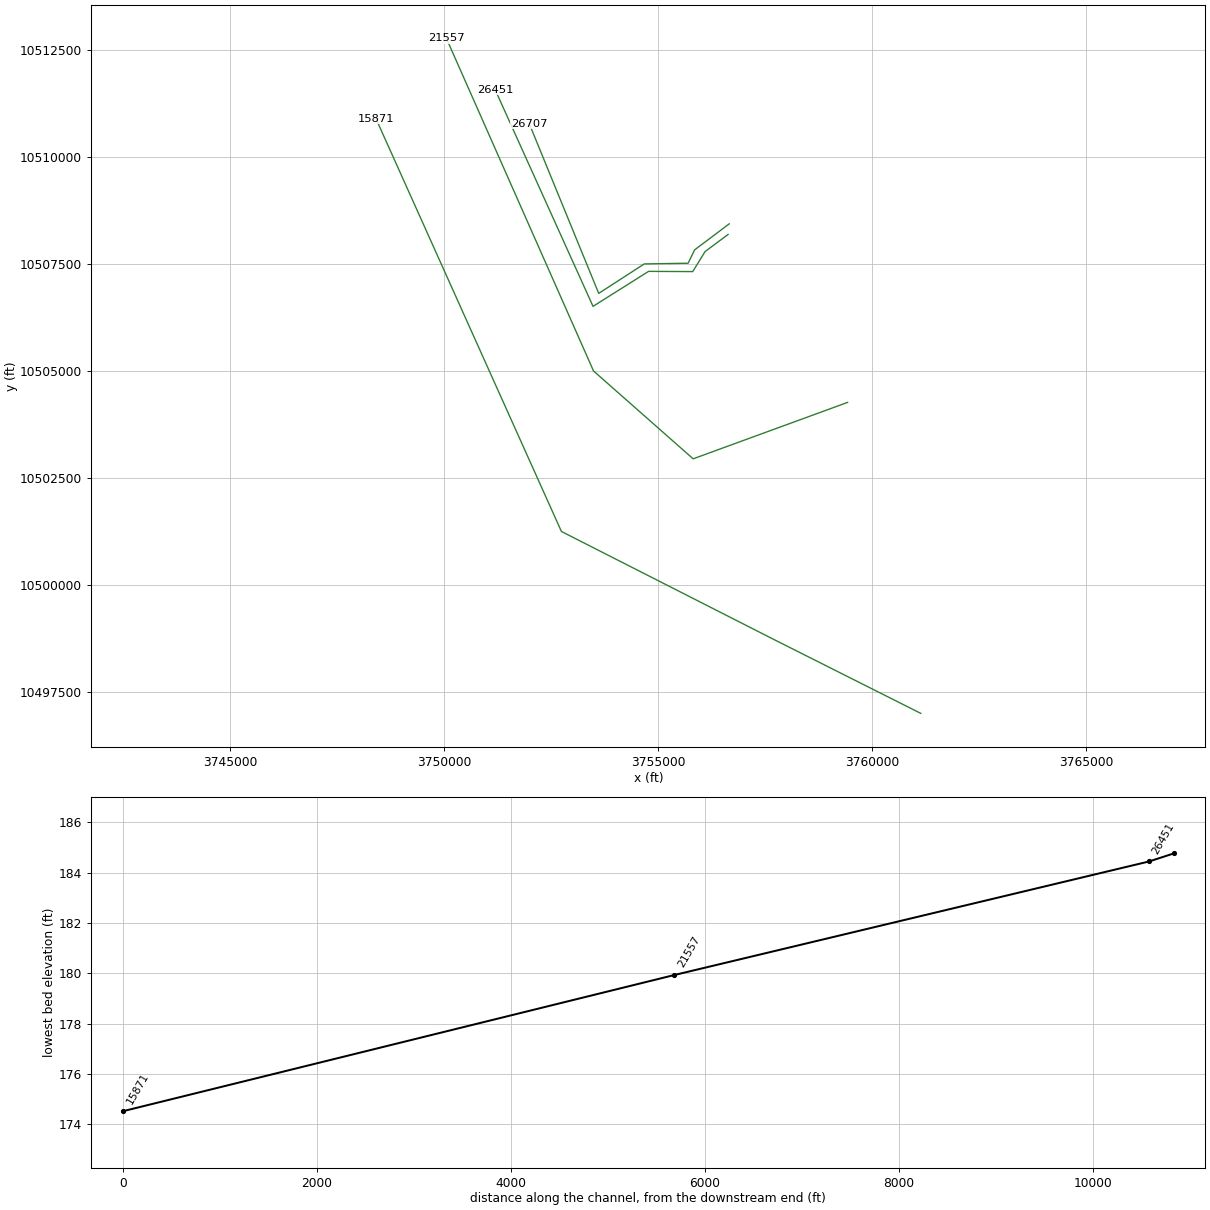
HEC-RAS study BIG ELKHART CREEK.prj: BIG ELKHART CREEK Base Level Engineering

--- BIG ELKHART CREEK.g01 (geometry) --- (continued)

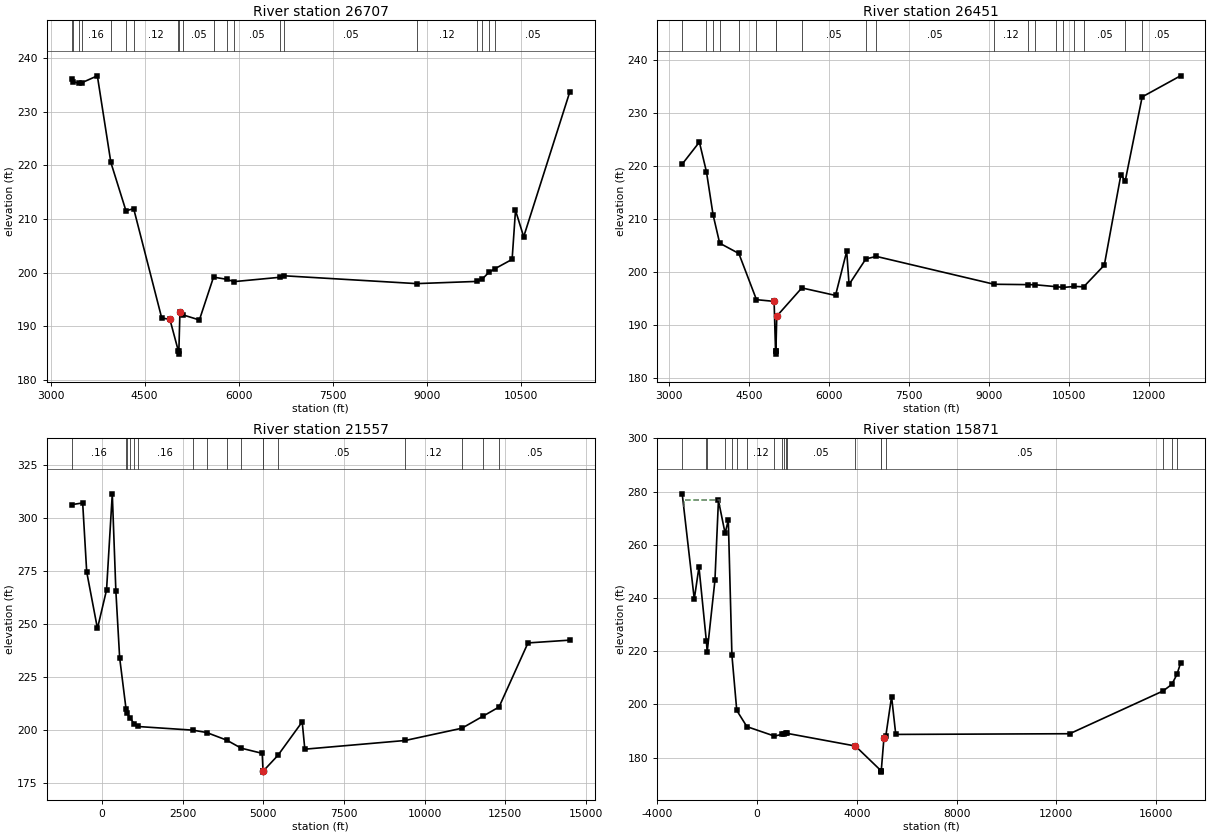
Type RM Length L Ch R = 1 ,26707   ,256,256,256
BEGIN DESCRIPTION:
Mapping XS f84fa1ef
END DESCRIPTION:
XS GIS Cut Line= 6
      3756657.17     10508438.65      3755848.88     10507830.44
      3755696.82     10507518.32      3754672.43     10507502.31
      3753608.02     10506814.04      3751984.01     10510782.05
#Sta/Elev= 30
  3335.7  236.22  3360.2  235.67  3450.2  235.33  3496.7  235.44  3746.3  236.74
  3961.5  220.56    4202  211.53  4324.9  211.93  4771.7   191.5  4901.7  191.26
  5038.7  185.26  5041.5  184.76  5044.7  185.26  5061.7  192.58  5113.3  192.08
  5371.7  191.14  5596.9  199.14  5806.8  198.74  5921.6   198.3  6660.6  199.12
  6725.8  199.39    8831  197.93  9789.3  198.34  9877.2  198.77  9981.6  200.02
   10086  200.75 10353.7  202.46 10407.6  211.62 10537.9  206.68   11274  233.79
#Mann= 20 ,-1 , 0
  3335.7     .05       0  3360.2     .16       0  3450.2     .05       0
  3496.7     .16       0  3961.5     .12       0    4202     .05       0
  4324.9     .12       0  5038.7     .07       0  5044.7     .12       0
  5113.3     .05       0  5596.9     .08       0  5806.8     .05       0
  5921.6     .05       0  6660.6     .08       0  6725.8     .05       0
    8831     .12       0  9789.3     .12       0  9877.2     .16       0
  9981.6     .05       0   10086     .05       0
Bank Sta=4901.7,5061.7
XS Rating Curve= 0 ,0
Exp/Cntr=0.3,0.1

Type RM Length L Ch R = 1 ,26451   ,4894,4894,4894
BEGIN DESCRIPTION:
BIG ELKHART CREEK 17.0
END DESCRIPTION:
XS GIS Cut Line= 6
       3756629.7     10508190.23       3756092.5       10507790.
      3755804.09     10507322.82      3754772.84     10507328.02
      3753475.16     10506510.53      3751186.24     10511576.54
#Sta/Elev= 30
  3249.2  220.31  3571.5  224.47  3704.6  218.83    3828  210.75  3951.7  205.39
  4311.3  203.44  4641.8  194.72  4972.6   194.4  4999.6  184.94  5002.4  184.44
  5005.6  184.94  5022.6  191.61  5492.3  196.94  6123.8  195.52  6333.3  203.84
  6377.8  197.59  6692.4  202.41  6888.5  202.89  9098.3  197.63  9727.8  197.56
  9862.7  197.54 10255.9  197.18 10391.8  197.03 10603.4  197.22 10777.5  197.15
 11163.7  201.24 11475.2  218.33 11555.9  217.13 11873.3     233 12592.2  236.98
#Mann= 20 ,-1 , 0
  3249.2     .12       0  3704.6     .12       0    3828     .16       0
  3951.7     .12       0  4311.3     .05       0  4641.8     .12       0
  4999.6     .07       0  5005.6     .12       0  5492.3     .05       0
  6692.4     .05       0  6888.5     .05       0  9098.3     .12       0
  9727.8     .16       0  9862.7     .05       0 10255.9     .05       0
 10391.8     .16       0 10603.4     .12       0 10777.5     .05       0
 11555.9     .05       0 11873.3     .05       0
Bank Sta=4972.6,5022.6
XS Rating Curve= 0 ,0
Exp/Cntr=0.3,0.1

Type RM Length L Ch R = 1 ,21557   ,5686,5686,5686
BEGIN DESCRIPTION:
BIG ELKHART CREEK 16.0
END DESCRIPTION:
XS GIS Cut Line= 4
      3759422.57     10504266.86      3755814.33     10502948.76
      3753486.41     10505001.64      3750048.93     10512772.44
#Sta/Elev= 30
  -938.6  306.42  -594.8  307.23  -469.9  274.62    -137  247.86   144.9  266.08
   322.8  311.54   434.3  265.41   551.2  233.99   750.1  209.66   779.8  207.69
   883.6  205.38   999.2   202.8  1109.2  201.51  2819.6  199.78  3245.3  198.67
  3868.9  195.06    4318  191.25  4968.9  188.81  4994.4  180.43  4997.1  179.93
  5000.4  180.43  5453.7  187.82  6208.1   203.7  6289.4  190.78  9402.4   194.9
 11156.6  200.69 11821.4  206.48 12308.7  210.73   13205  241.03 14503.8  242.35
#Mann= 17 ,-1 , 0
  -938.6     .16       0   750.1     .05       0   779.8     .08       0
   883.6     .16       0   999.2     .05       0  1109.2     .16       0
  2819.6     .05       0  3245.3     .16       0  3868.9     .05       0
    4318     .12       0  4994.4     .07       0  5000.4     .12       0
  5453.7     .05       0  9402.4     .12       0 11156.6     .05       0
 11821.4     .07       0 12308.7     .05       0
Bank Sta=4994.4,5000.4
XS Rating Curve= 0 ,0
Exp/Cntr=0.3,0.1

Type RM Length L Ch R = 1 ,15871   ,0,0,0
BEGIN DESCRIPTION:
BIG ELKHART CREEK 15.0
END DESCRIPTION:
XS GIS Cut Line= 4
      3761132.22     10497001.65      3757694.75     10498730.81
      3752736.41     10501251.64      3748403.09     10510897.46
#Sta/Elev= 30
 -3003.5  279.17 -2519.2  239.57 -2331.3  251.64 -2033.6  223.72 -2001.2  219.77
 -1690.9  246.61 -1550.1   276.7 -1283.7  264.37 -1153.9  269.26 -1009.3  218.48
  -815.3  197.72  -409.1  191.63   697.9  188.07   981.5  188.69  1062.4  188.87
  1175.5  189.11  1182.8  189.13  3941.3  184.34  4973.6  175.02  4976.3  174.52
  4979.6  175.02  5087.8  187.35  5164.5  188.22  5393.5  202.92  5561.8   188.7
 12537.5  188.96 16277.9  205.02 16630.3  207.48 16838.3  211.25 16981.2  215.46
#Mann= 19 ,-1 , 0
 -3003.5     .16       0 -2033.6     .12       0 -2001.2     .16       0
 -1283.7     .12       0 -1009.3     .16       0  -815.3     .05       0
  -409.1     .12       0   697.9     .05       0   981.5     .16       0
  1062.4     .12       0  1175.5     .16       0  1182.8     .05       0
  3941.3     .12       0  4973.6     .07       0  4979.6     .12       0
  5164.5     .05       0 16277.9     .07       0 16630.3     .05       0
 16838.3     .12       0
#XS Ineff= 1 ,-1
   -2944 -1505.4     277
Permanent Ineff=
       F
Bank Sta=3941.3,5087.8
XS Rating Curve= 0 ,0
Exp/Cntr=0.3,0.1

Chan Stop Cuts=-1
Use User Specified Reach Order=0
Composite Channel Slope=5