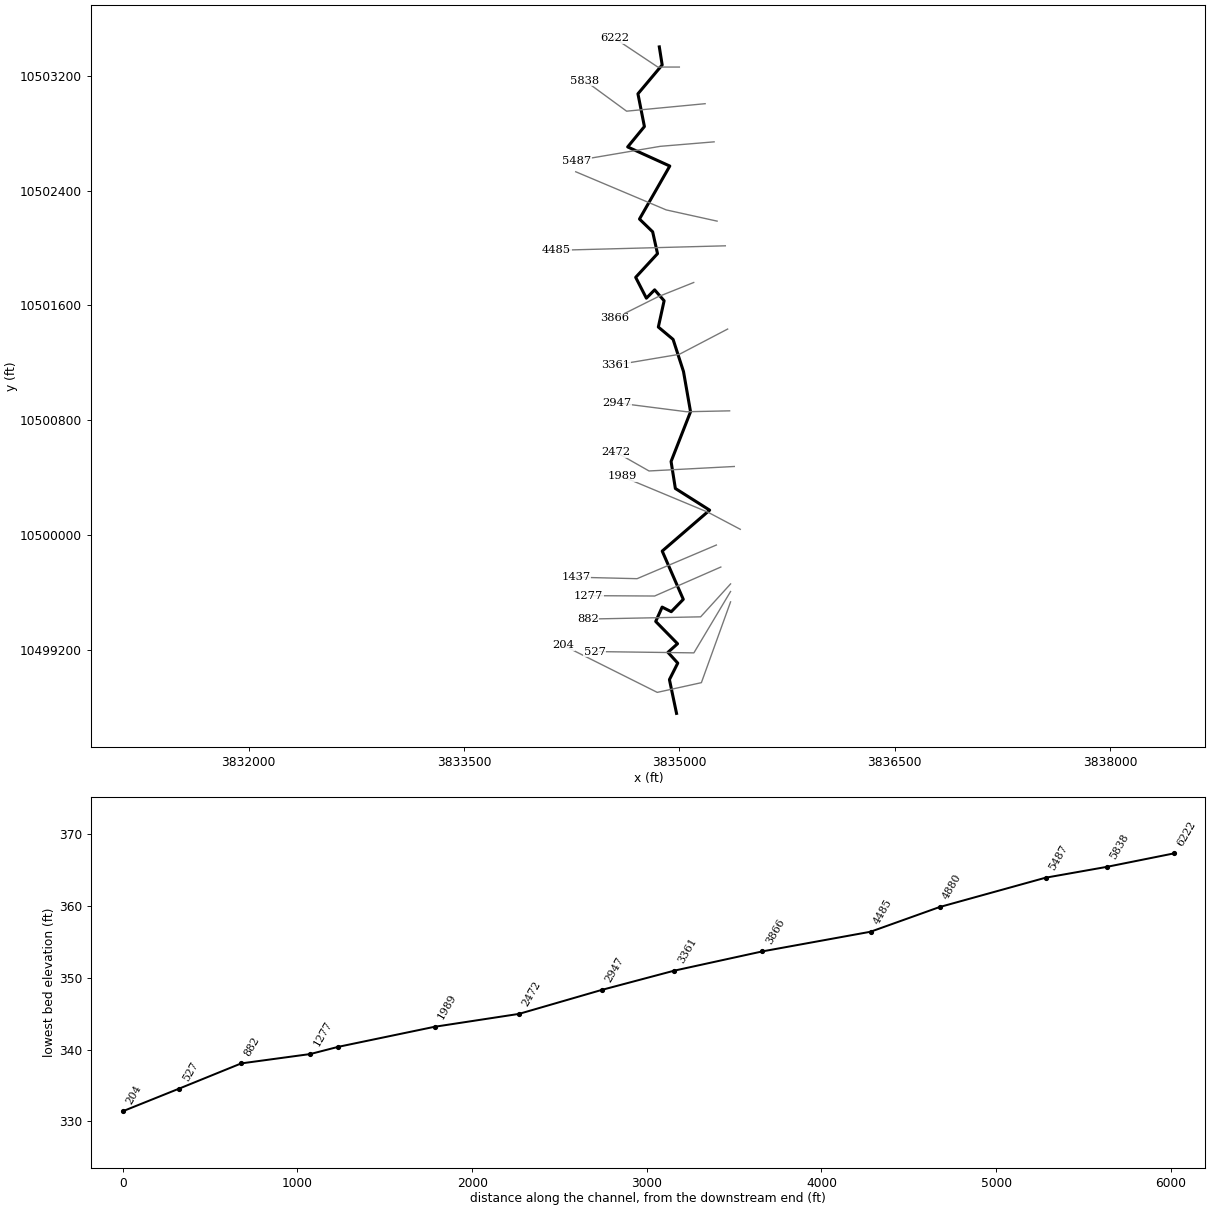
--- BLACK LICK BRANCH.prj (project) ---

Proj Title=BLACK LICK BRANCH Base Level Engineering
Current Plan=p01
Default Exp/Contr=0.3,0.1
English Units
Geom File=g01
Flow File=f01
Plan File=p01
Y Axis Title=Elevation
X Axis Title(PF)=Main Channel Distance
X Axis Title(XS)=Station
BEGIN DESCRIPTION:
BLACK LICK BRANCH
END DESCRIPTION:
DSS File=dss
DSS Export Rating Curves= 0
DSS Export Rating Curve Sorted= 0
DSS Export Volume Flow Curves= 0
DXF OffsetX= 0
DXF OffsetY= 0
DXF ScaleX= 1
DXF ScaleY= 10

--- BLACK LICK BRANCH.p01 (plan) ---

Plan Title=Multiple Run
Program Version=4.10
Short Identifier=Multiple Run
Geom File=g01
Flow File=f01
Subcritical Flow
K Sum by GR= 0
Std Step Tol= 0.01
Critical Tol= 0.01
Num of Std Step Trials= 20
Max Error Tol= 0.3
Flow Tol Ratio= 0.001
Split Flow NTrial= 30
Split Flow Tol= 0.02
Split Flow Ratio= 0.02
Log Output Level= 0
Friction Slope Method= 1
Unsteady Friction Slope Method= 2
Unsteady Bridges Friction Slope Method= 1
Parabolic Critical Depth
Global Vel Dist= 1 , 1 , 1
Global Log Level= 0
CheckData=True
Encroach Param=-1 ,0,0, 0
BEGIN DESCRIPTION:
Multiple Run
END DESCRIPTION:
Computation Interval=1HOUR
Output Interval=1HOUR
Run HTab= 0
Run UNet= 0
Run PostProcess= 0
Run WQNet= 0
UNET Theta= 1
UNET Theta Warmup= 1
UNET ZTol= 0.02
UNET ZSATol= 0.05
UNET MxIter= 20
UNET MaxInSteps= 0
UNET DtIC= 0
UNET DtMin= 0
UNET MaxCRTS= 20
UNET WFStab= 2
UNET SFStab= 1
UNET WFX= 1
UNET SFX= 1
UNET DSS MLevel= 4
UNET DZMax Abort= 100
UNET Convert EG Bridges= 0
UNET Use Existing IB Tables=-1
UNET Froude Reduction=False
UNET Froude Limit= 1
UNET Froude Power= 10
UNET Time Slicing=0,0, 5
UNET Junction Losses=0
Instantaneous Interval=1HOUR
DSS File=dss
Write IC File= 0
Write IC File at Sim End=0
Echo Input=False
Echo Parameters=False
Echo Output=False
Write Detailed= 0
WQ AD Non Conservative
WQ ULTIMATE=-1
WQ Max Comp Step=1HOUR
WQ Output Interval=15MIN
WQ Output Selected Increments= 0
WQ Output face flow=0
WQ Output face velocity=0
WQ Output face area=0
WQ Output face dispersion=0
WQ Output cell volume=0
WQ Output cell surface area=0
WQ Output cell continuity=0
WQ Output cumulative cell continuity=0
WQ Output face conc=0
WQ Output face dconc_dx=0
WQ Output face courant=0
WQ Output face peclet=0
WQ Output face adv mass=0
WQ Output face disp mass=0
WQ Output cell mass=0
WQ Output cell source sink temp=0
WQ Output cell source sink nsm=0
WQ Output MaxMinRange=-1
WQ Daily Max Min Mean=-1
WQ Daily Range=0
WQ Daily Time=0
WQ Create Restart=0
WQ Fixed Restart=0
WQ System Summary=0
WQ Use Fixed Temperature=0
Sorting and Armoring Iterations= 10
XS Update Threshold= 0.02
Hydraulics Update Threshold= 0.02
Energy Slope Method= 1
Volume Change Method= 0
XS Weighting Method= 0
Number of US Weighted Cross Sections= 1
Number of DS Weighted Cross Sections= 1
Upstream XS Weight=0.25
Main XS Weight=0.5
Downstream XS Weight=0.25
Number of DS XS's Weighted with US Boundary= 1
Upstream Boundary Weight= 1
Weight of XSs Associated with US Boundary= 0
Number of US XS's Weighted with DS Boundary= 1
Downstream Boundary Weight= 0.5
Weight of XSs Associated with DS Boundary= 0.5
Sediment Output Level= 4
Mass or Volume Output= 0
Output Increment Type= 1
Profile and TS Output Increment= 10
XS Output Flag= 0
XS Output Increment= 10
Disregard all LS=0
Disregard all Conn=0
Disregard all Breaches=0
Disregard all Pumps=0

--- BLACK LICK BRANCH.f01 (steady flow) ---

Flow Title=Multiple
Program Version=4.10
Number of Profiles= 7
Profile Names=10-year,25-year,50-year,1pct_min,100-year,1pct_plu,500-year
River Rch & RM=BLACK LICK BRANC,Reach-1         ,6222
     392     513     610     533     721     975    1011
Boundary for River Rch & Prof#=BLACK LICK BRANC,Reach-1         , 1
Up Type= 0
Dn Type= 3
Dn Slope=0.006
Boundary for River Rch & Prof#=BLACK LICK BRANC,Reach-1         , 2
Up Type= 0
Dn Type= 3
Dn Slope=0.006
Boundary for River Rch & Prof#=BLACK LICK BRANC,Reach-1         , 3
Up Type= 0
Dn Type= 3
Dn Slope=0.006
Boundary for River Rch & Prof#=BLACK LICK BRANC,Reach-1         , 4
Up Type= 0
Dn Type= 3
Dn Slope=0.006
Boundary for River Rch & Prof#=BLACK LICK BRANC,Reach-1         , 5
Up Type= 0
Dn Type= 3
Dn Slope=0.006
Boundary for River Rch & Prof#=BLACK LICK BRANC,Reach-1         , 6
Up Type= 0
Dn Type= 3
Dn Slope=0.006
Boundary for River Rch & Prof#=BLACK LICK BRANC,Reach-1         , 7
Up Type= 0
Dn Type= 3
Dn Slope=0.006
DSS Import GetInterval= 0
DSS Import GetPeak= 0
DSS Import FillOption= 0

--- BLACK LICK BRANCH.g01 (geometry) ---

Geom Title=Existing Conditions
Program Version=4.10

River Reach=BLACK LICK BRANC,Reach-1
Reach XY= 30
      3834860.06     10503400.61        3834880.       10503275.
      3834711.25       10503074.      3834756.25       10502846.
      3834639.75       10502704.        3834933.       10502571.
        3834722.       10502202.      3834813.75       10502113.
       3834847.5       10501961.       3834695.5       10501796.
        3834770.       10501651.       3834827.5       10501709.
       3834893.5       10501633.      3834853.25       10501450.
        3834956.       10501364.       3835028.5       10501140.
       3835077.5       10500860.        3834942.       10500514.
      3834971.75       10500326.       3835210.5       10500175.
      3834880.25       10499890.        3835027.       10499554.
      3834943.25       10499468.      3834879.75       10499500.
        3834835.       10499400.        3834987.       10499245.
      3834920.25       10499185.       3834988.5       10499110.
       3834930.5       10498995.        3834980.       10498760.

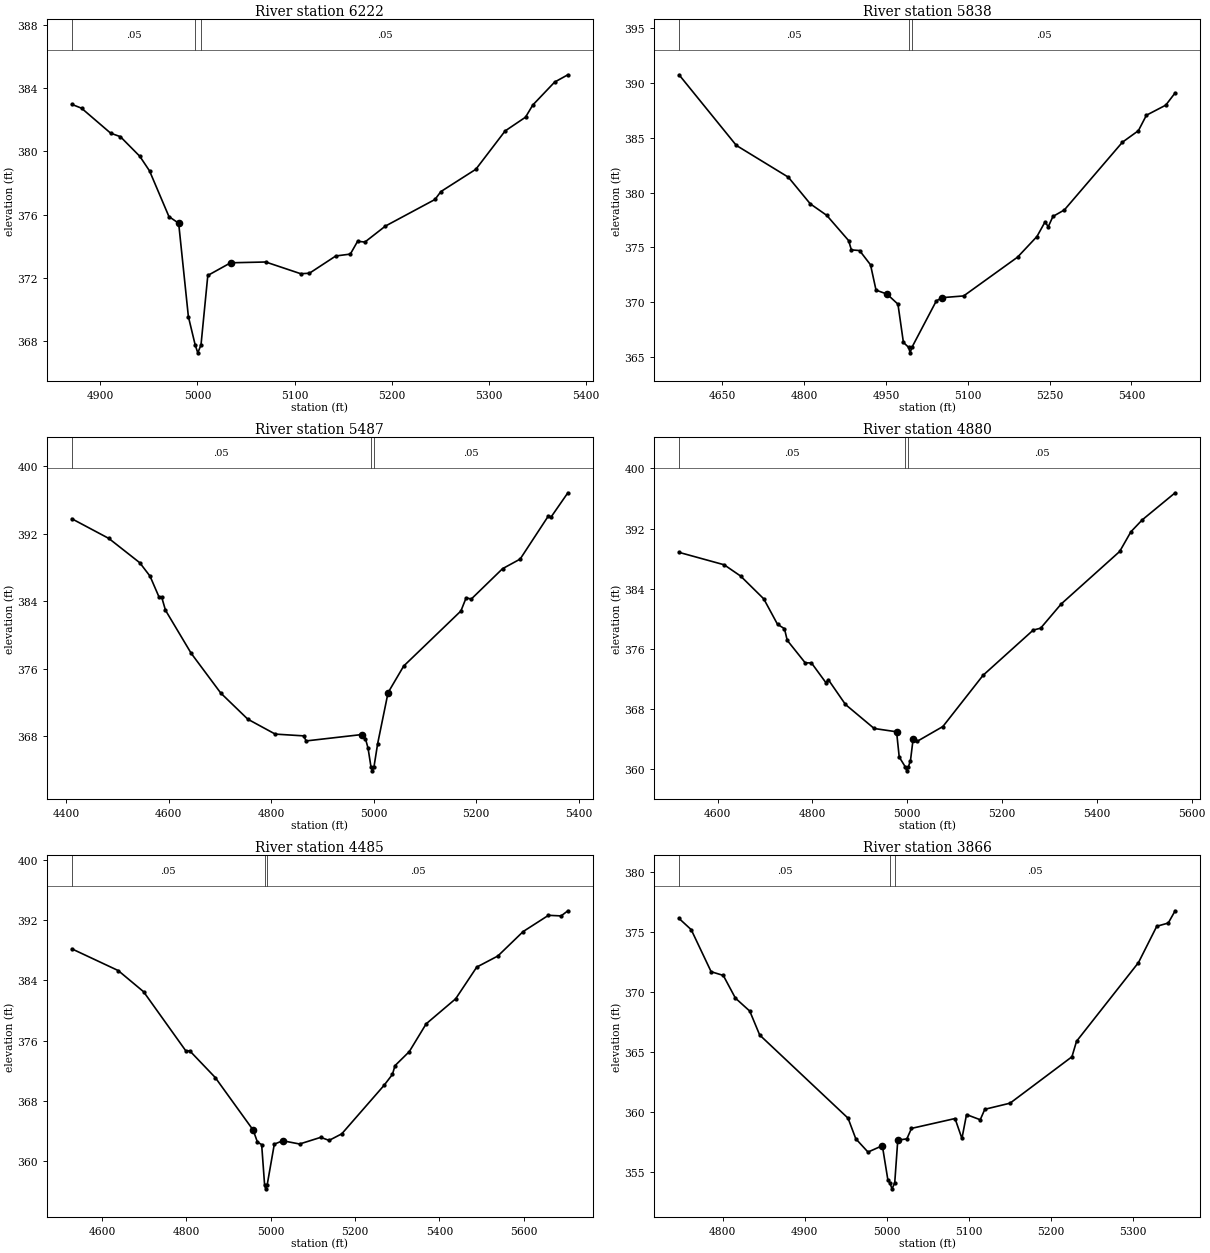
Type RM Length L Ch R = 1 ,6222    ,384,384,384
BEGIN DESCRIPTION:
BLACK LICK BRANCH 12.0
END DESCRIPTION:
XS GIS Cut Line= 3
      3834999.61     10503260.19      3834849.61     10503260.19
      3834549.57     10503460.21
#Sta/Elev= 30
  4870.7  382.96  4880.7  382.72  4910.7  381.14  4920.7  380.92  4940.7  379.68
  4950.7  378.76  4970.7  375.87  4980.7  375.45  4990.7  369.55  4997.7  367.76
  5000.4  367.26  5003.7  367.76  5010.7  372.15  5034.2  372.95  5070.3     373
  5106.3  372.26  5115.3  372.29  5142.4  373.38  5157.4   373.5  5164.9  374.31
  5172.4  374.26  5193.5  375.27  5244.5  376.95  5250.6  377.45  5286.6  378.86
  5316.7  381.28  5337.7  382.15  5345.2  382.92  5367.7  384.37  5381.3  384.83
#Mann= 3 ,-1 , 0
  4870.7     .05       0  4997.7     .03       0  5003.7     .05       0
Bank Sta=4980.7,5034.2
XS Rating Curve= 0 ,0
Exp/Cntr=0.3,0.1

Type RM Length L Ch R = 1 ,5838    ,351,351,351
BEGIN DESCRIPTION:
BLACK LICK BRANCH 11.0
END DESCRIPTION:
XS GIS Cut Line= 3
      3835179.15     10503005.15      3834632.23     10502953.06
      3834341.52     10503165.91
#Sta/Elev= 30
  4570.5  390.75  4675.5  384.31  4770.9  381.41  4811.1  378.98  4841.3  377.93
  4881.4  375.63  4886.5  374.78  4901.5  374.72  4921.6  373.42  4931.7  371.11
  4951.8  370.75  4971.9  369.83  4981.9  366.34  4991.5  365.89  4994.2  365.39
  4997.5  365.89  5042.2  370.12  5052.2  370.42  5092.4  370.58  5191.3  374.12
  5226.8     376  5241.4  377.31  5247.6   376.9  5256.1  377.83    5277  378.42
  5383.5   384.6  5412.8  385.65  5427.5  387.06    5463  387.98  5480.2   389.1
#Mann= 3 ,-1 , 0
  4570.5     .05       0  4991.5     .03       0  4997.5     .05       0
Bank Sta=4951.8,5052.2
XS Rating Curve= 0 ,0
Exp/Cntr=0.3,0.1

Type RM Length L Ch R = 1 ,5487    ,607,607,607
BEGIN DESCRIPTION:
BLACK LICK BRANCH 10.0
END DESCRIPTION:
XS GIS Cut Line= 3
      3835241.65     10502739.52      3834866.61     10502708.27
      3834283.98     10502609.43
#Sta/Elev= 30
  4411.3   393.8  4483.6  391.46  4543.8  388.58  4563.9  386.98  4581.4  384.51
  4586.4  384.53    4594  382.94  4644.1  377.83  4701.8  373.11  4754.5  370.01
    4808  368.24  4863.3  368.03  4868.3  367.43  4977.3  368.19  4983.9   367.7
    4989  366.56  4994.6  364.38  4997.4  363.88  5000.6  364.38  5007.7  367.11
    5028  373.16  5058.5  376.32    5170  382.85  5180.2  384.41  5190.3  384.27
  5251.2  387.87  5285.5  389.01  5340.8  394.15  5345.8     394  5378.6  396.88
#Mann= 3 ,-1 , 0
  4411.3     .05       0  4994.6     .03       0  5000.6     .05       0
Bank Sta=4977.3,5028
XS Rating Curve= 0 ,0
Exp/Cntr=0.3,0.1

Type RM Length L Ch R = 1 ,4880    ,395,395,395
BEGIN DESCRIPTION:
BLACK LICK BRANCH 9.0
END DESCRIPTION:
XS GIS Cut Line= 3
      3835262.44     10502187.44      3834908.28     10502265.56
      3834278.04      10502531.2
#Sta/Elev= 30
  4518.6  388.84  4613.7  387.19  4648.5  385.69  4697.3  382.66  4726.3  379.28
    4741  378.69  4746.8  377.15  4784.7  374.16    4798  374.14  4828.4  371.52
  4833.5  371.92  4869.7  368.62  4930.2  365.43  4977.5  364.99  4983.1  361.63
  4996.2   360.3  4998.9   359.8  5002.2   360.3  5006.8  361.15  5012.3  363.98
  5020.9  363.72  5075.2  365.69    5160   372.5  5265.8  378.51  5281.4  378.76
  5324.8  381.98  5448.2  388.96  5471.9  391.58  5495.6  393.15  5565.2  396.76
#Mann= 3 ,-1 , 0
  4518.6     .05       0  4996.2     .03       0  5002.2     .05       0
Bank Sta=4977.5,5012.3
XS Rating Curve= 0 ,0
Exp/Cntr=0.3,0.1

Type RM Length L Ch R = 1 ,4485    ,619,619,619
BEGIN DESCRIPTION:
BLACK LICK BRANCH 8.0
END DESCRIPTION:
XS GIS Cut Line= 2
       3835319.7     10502015.56      3834143.62     10501984.34
#Sta/Elev= 30
  4528.2  388.17  4638.3  385.29  4698.4  382.49  4798.4  374.67  4808.4  374.63
  4868.4  371.12  4958.4  364.15  4968.4  362.57  4978.5  362.23  4985.5  356.87
  4988.2  356.37  4991.5  356.87  5008.5  362.29  5028.5  362.74  5068.5  362.31
  5118.5  363.19  5138.5  362.79  5168.5  363.66  5268.6  370.07  5288.6  371.53
  5294.7  372.69  5328.6  374.55  5368.6  378.23  5438.6  381.55  5488.6  385.75
  5538.7  387.22  5598.7  390.46  5658.7  392.61  5688.7  392.53  5704.7  393.21
#Mann= 3 ,-1 , 0
  4528.2     .05       0  4985.5     .03       0  4991.5     .05       0
Bank Sta=4958.4,5028.5
XS Rating Curve= 0 ,0
Exp/Cntr=0.3,0.1

Type RM Length L Ch R = 1 ,3866    ,505,505,505
BEGIN DESCRIPTION:
BLACK LICK BRANCH 7.0
END DESCRIPTION:
XS GIS Cut Line= 3
      3835099.64      10501760.2      3834849.61     10501660.19
      3834549.62     10501510.19
#Sta/Elev= 30
  4746.8  376.14  4761.6  375.21  4785.9  371.71  4800.7   371.4  4815.5  369.51
    4833  368.43  4845.1  366.44  4952.8  359.52  4962.2  357.81  4977.1   356.7
  4994.6  357.23  5001.3   354.4  5003.7  354.14  5006.4  353.64  5009.7  354.14
  5013.4  357.69  5024.5   357.8  5030.1  358.67  5083.2  359.49  5091.6  357.83
  5097.2  359.82  5113.9  359.39  5119.5  360.26  5150.3  360.77  5225.7  364.63
  5231.3  365.92  5306.8  372.47  5329.1  375.49  5343.1  375.76  5351.5  376.78
#Mann= 3 ,-1 , 0
  4746.8     .05       0  5003.7     .03       0  5009.7     .05       0
Bank Sta=4994.6,5013.4
XS Rating Curve= 0 ,0
Exp/Cntr=0.3,0.1

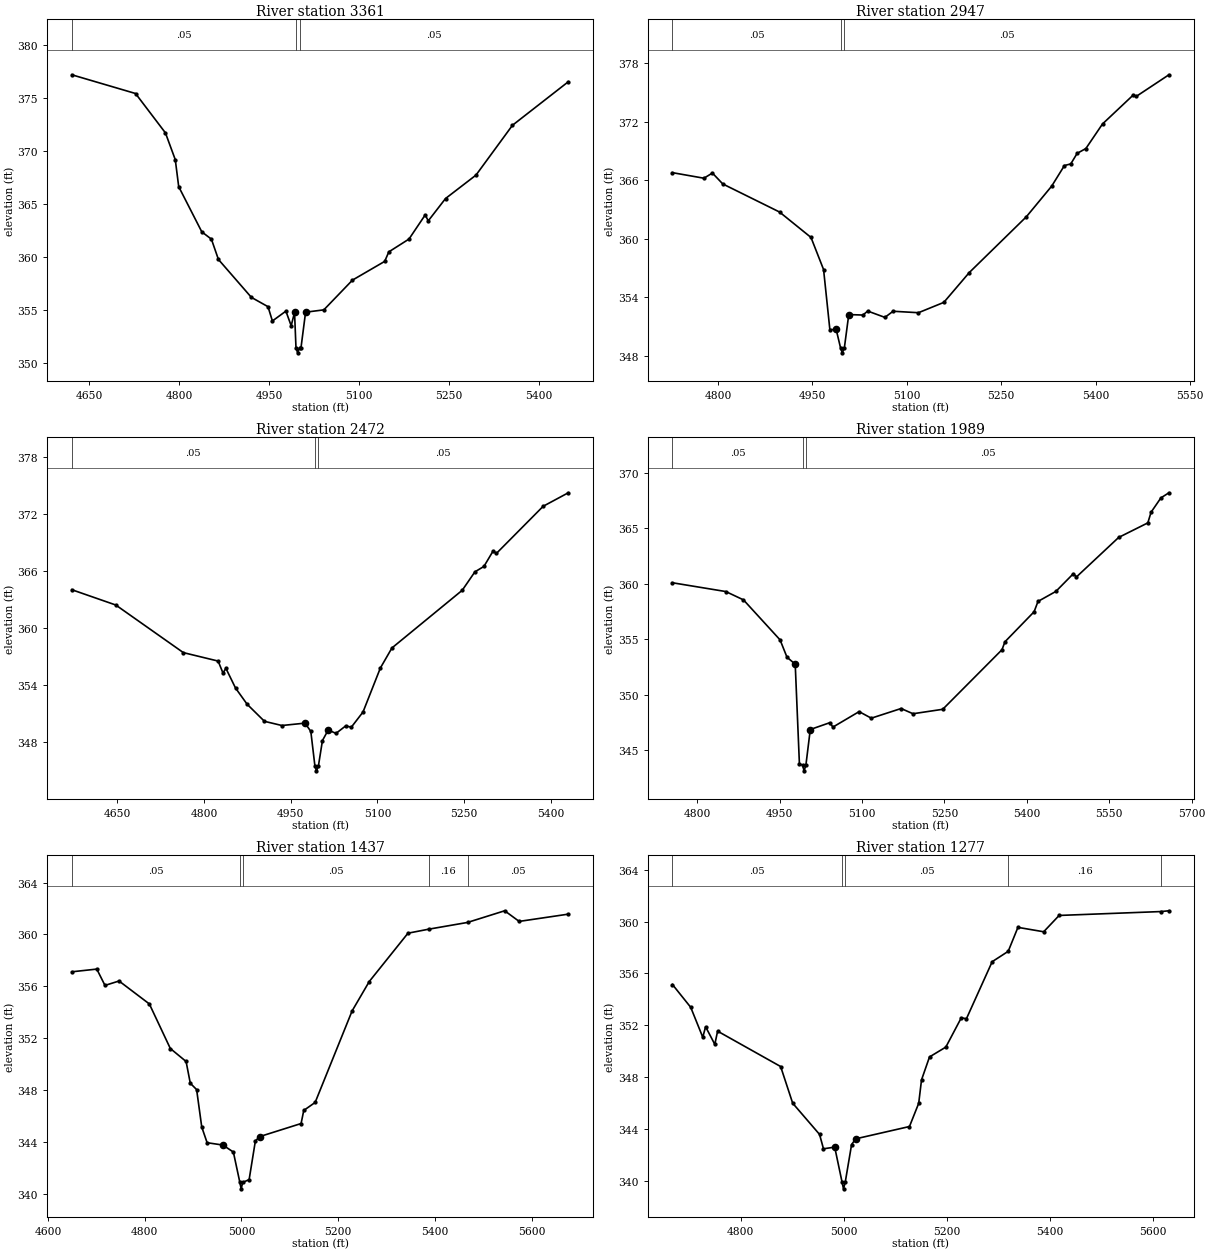
Type RM Length L Ch R = 1 ,3361    ,414,414,414
BEGIN DESCRIPTION:
BLACK LICK BRANCH 6.0
END DESCRIPTION:
XS GIS Cut Line= 3
      3835335.75     10501435.94      3834999.61     10501260.19
      3834557.92     10501185.93
#Sta/Elev= 30
  4621.4  377.23  4727.6  375.46  4777.4  371.74  4793.8  369.21  4799.5  366.66
    4838  362.39    4854   361.7  4865.7  359.78  4920.6   356.2  4948.3  355.32
  4955.6  353.97  4978.1   354.9  4986.9  353.52  4992.5  354.78  4994.9  351.46
  4997.6  350.96  5000.9  351.46  5003.3  351.46  5010.9   354.8  5041.3  355.02
    5089  357.83  5142.7   359.6  5149.6   360.5  5183.2  361.71  5210.2  363.99
  5215.3  363.43  5244.1  365.54  5294.8  367.75  5355.6  372.46  5448.6  376.57
#Mann= 3 ,-1 , 0
  4621.4     .05       0  4994.9     .03       0  5000.9     .05       0
Bank Sta=4992.5,5010.9
XS Rating Curve= 0 ,0
Exp/Cntr=0.3,0.1

Type RM Length L Ch R = 1 ,2947    ,475,475,475
BEGIN DESCRIPTION:
BLACK LICK BRANCH 5.0
END DESCRIPTION:
XS GIS Cut Line= 3
      3835349.64     10500866.49      3835049.61     10500860.19
      3834564.94     10500922.04
#Sta/Elev= 30
  4727.6  366.79  4777.6  366.22  4791.1  366.75  4807.6  365.63  4897.7  362.75
  4947.7  360.14  4967.7  356.84  4977.7  350.67  4987.7  350.69  4994.7  348.79
  4997.4  348.29  5000.7  348.79  5007.7  352.22  5030.2  352.17  5037.8  352.58
  5065.1  351.93  5078.1  352.56  5118.4  352.41  5158.7  353.47  5199.1  356.53
  5289.8  362.26  5330.1  365.41  5350.3  367.52  5360.4  367.69  5370.5  368.77
  5384.4  369.27  5410.8  371.79  5459.1  374.73  5464.2  374.61  5516.3  376.84
#Mann= 3 ,-1 , 0
  4727.6     .05       0  4994.7     .03       0  5000.7     .05       0
Bank Sta=4987.7,5007.7
XS Rating Curve= 0 ,0
Exp/Cntr=0.3,0.1

Type RM Length L Ch R = 1 ,2472    ,483,483,483
BEGIN DESCRIPTION:
BLACK LICK BRANCH 4.0
END DESCRIPTION:
XS GIS Cut Line= 3
      3835382.19      10500479.1      3834788.48     10500447.85
      3834559.32     10500578.06
#Sta/Elev= 30
  4571.7  364.01  4647.7   362.4  4764.5  357.39  4824.6   356.5    4833  355.24
    4838  355.74  4854.7  353.66  4874.7  351.96  4904.7  350.16  4934.8  349.72
  4974.8  349.97  4984.8   349.1  4991.9  345.45  4994.6  344.95  4997.9  345.45
  5004.9  348.14  5014.9  349.25  5028.3  348.89  5044.9  349.67  5054.9  349.55
    5075  351.14    5105  355.77    5125  357.88  5246.5  363.95  5268.4  365.89
    5284  366.46  5299.9  368.09  5305.6  367.83  5386.4  372.79  5429.8  374.21
#Mann= 3 ,-1 , 0
  4571.7     .05       0  4991.9     .03       0  4997.9     .05       0
Bank Sta=4974.8,5014.9
XS Rating Curve= 0 ,0
Exp/Cntr=0.3,0.1

Type RM Length L Ch R = 1 ,1989    ,552,552,552
BEGIN DESCRIPTION:
BLACK LICK BRANCH 3.0
END DESCRIPTION:
XS GIS Cut Line= 3
       3835423.9      10500041.6      3835199.61     10500160.19
      3834599.62     10500410.18
#Sta/Elev= 30
  4754.9  360.09    4852   359.3  4884.2  358.55  4950.8  354.95  4963.4  353.39
  4978.4  352.76    4986  343.82  4991.8  343.66  4994.5  343.16  4997.8  343.66
  5005.8  346.88  5041.1  347.49  5047.1   347.1  5094.7  348.49  5116.9   347.9
  5171.1  348.77  5192.8   348.3  5246.9   348.7  5354.7  354.06  5360.2  354.78
  5413.2  357.48  5420.3  358.41  5452.8  359.31  5484.7  360.91  5490.2  360.61
  5567.1  364.17  5620.2  365.48  5626.1  366.44    5644  367.73  5658.6  368.19
#Mann= 3 ,-1 , 0
  4754.9     .05       0  4991.8     .03       0  4997.8     .05       0
Bank Sta=4978.4,5005.8
XS Rating Curve= 0 ,0
Exp/Cntr=0.3,0.1

Type RM Length L Ch R = 1 ,1437    ,160,160,160
BEGIN DESCRIPTION:
BLACK LICK BRANCH 2.0
END DESCRIPTION:
XS GIS Cut Line= 3
      3835257.24     10499932.23      3834705.15     10499697.85
      3834278.06     10499708.27
#Sta/Elev= 30
  4649.1  357.12  4700.8  357.33  4717.7  356.07  4746.8  356.41  4809.5  354.64
  4852.9   351.2  4885.5   350.2  4894.2  348.52  4907.3  348.03  4917.9  345.14
    4929  343.93  4961.6  343.75  4983.3  343.21  4996.7  340.87  4999.4  340.37
  5002.7  340.87  5015.9  341.08  5028.8  344.06  5037.6   344.4  5123.4  345.41
  5128.9  346.42  5152.5  347.04  5228.9   354.1  5264.4  356.37  5344.5   360.1
  5387.4  360.41  5467.7  360.93  5544.5  361.83  5574.5  361.01  5676.1  361.57
#Mann= 5 ,-1 , 0
  4649.1     .05       0  4996.7     .03       0  5002.7     .05       0
  5387.4     .16       0  5467.7     .05       0
Bank Sta=4961.6,5037.6
XS Rating Curve= 0 ,0
Exp/Cntr=0.3,0.1

Type RM Length L Ch R = 1 ,1277    ,395,395,395
BEGIN DESCRIPTION:
Mapping XS 0783c02f
END DESCRIPTION:
XS GIS Cut Line= 3
      3835288.29     10499778.94      3834827.38     10499577.13
      3834366.45     10499579.73
#Sta/Elev= 30
  4667.1  355.14  4702.6  353.38    4726  351.07  4731.5  351.88  4749.4  350.52
  4754.8  351.54  4877.2  348.81  4900.6  345.98  4952.8  343.57  4960.4  342.46
  4982.2  342.59  4996.6  339.87  4999.3  339.37  5002.6  339.87    5015  342.79
    5023  343.23  5127.4  344.18  5145.3  345.97  5150.8  347.78  5166.3  349.55
    5198  350.31    5228  352.57    5238   352.5    5288   356.9  5319.1   357.7
    5338  359.55    5388  359.21    5418  360.47  5615.7  360.77  5631.2  360.83
#Mann= 5 ,-1 , 0
  4667.1     .05       0  4996.6     .03       0  5002.6     .05       0
  5319.1     .16       0  5615.7     .05       0
Bank Sta=4982.2,5023
XS Rating Curve= 0 ,0
Exp/Cntr=0.3,0.1

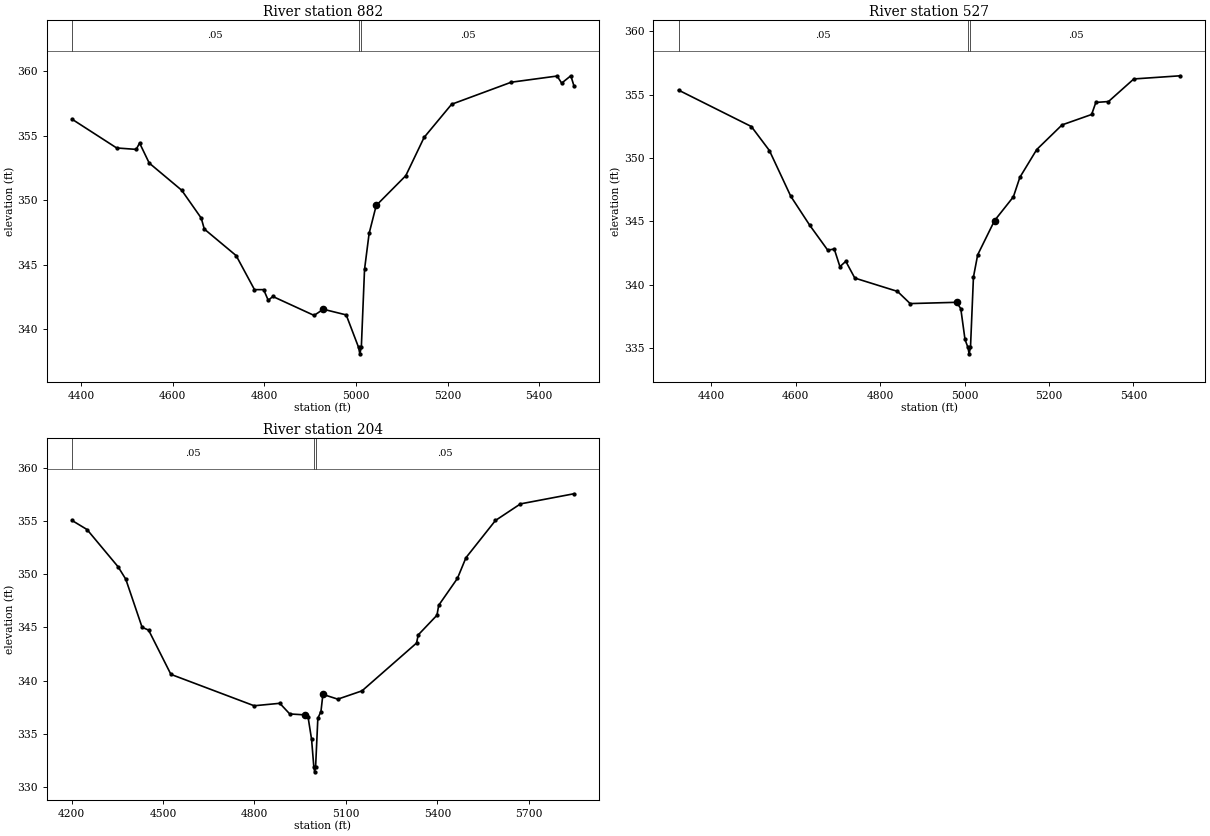
Type RM Length L Ch R = 1 ,882     ,355,355,355
BEGIN DESCRIPTION:
Mapping XS 96f197bf
END DESCRIPTION:
XS GIS Cut Line= 3
      3835356.22     10499661.43      3835147.86     10499432.23
      3834362.97     10499416.63
#Sta/Elev= 30
  4380.8  356.27  4478.1  354.04  4520.7  353.93  4528.1  354.42  4549.1  352.87
    4620  350.76  4662.6   348.6  4669.3  347.75  4738.8  345.69  4778.8  343.05
  4798.8  343.05  4808.8  342.22  4818.8  342.52  4908.9  341.05  4928.9  341.53
  4978.9  341.09  5005.9  338.57  5008.6  338.07  5011.9  338.57  5018.9  344.62
  5028.9  347.41  5044.4  349.58  5108.9  351.89  5148.9  354.86  5208.9  357.43
  5338.9  359.14    5439  359.62    5449  359.07    5469  359.64  5475.6  358.88
#Mann= 3 ,-1 , 0
  4380.8     .05       0  5005.9     .03       0  5011.9     .05       0
Bank Sta=4928.9,5044.4
XS Rating Curve= 0 ,0
Exp/Cntr=0.3,0.1

Type RM Length L Ch R = 1 ,527     ,323,323,323
BEGIN DESCRIPTION:
Mapping XS a2425958
END DESCRIPTION:
XS GIS Cut Line= 3
      3835356.05     10499608.41      3835100.82     10499181.29
      3834409.45     10499190.41
#Sta/Elev= 30
  4322.2  355.35  4494.8  352.48  4537.5  350.59  4588.1  346.99  4632.9  344.71
  4675.7  342.74  4691.2  342.83  4704.6  341.44  4718.5  341.86  4739.9  340.54
    4841  339.49    4871  338.53    4981  338.63    4991  338.13    5001   335.7
    5008  335.07  5010.7  334.57    5014  335.07    5021  340.62    5031  342.37
    5071  345.07  5115.6  346.94    5131  348.48    5171  350.67    5231  352.61
    5301  353.43    5311  354.38    5341  354.45    5401  356.23  5511.2  356.48
#Mann= 3 ,-1 , 0
  4322.2     .05       0    5008     .03       0    5014     .05       0
Bank Sta=4981,5071
XS Rating Curve= 0 ,0
Exp/Cntr=0.3,0.1

Type RM Length L Ch R = 1 ,204     ,0,0,0
BEGIN DESCRIPTION:
BLACK LICK BRANCH 1.0
END DESCRIPTION:
XS GIS Cut Line= 4
      3835356.18     10499536.36      3835153.07     10498973.89
      3834845.78     10498906.19      3834189.51     10499234.32
#Sta/Elev= 30
  4201.5  355.04  4250.6  354.19  4352.5  350.69  4377.8  349.52  4431.3     345
  4452.6  344.74  4525.8  340.58  4798.8  337.63  4883.1  337.86  4915.7  336.86
  4966.9  336.77  4975.7  336.59  4987.4  334.46  4994.6  331.92  4997.4  331.42
  5000.6  331.92  5007.9  336.45  5018.1  337.09  5024.5   338.7  5073.4  338.25
  5152.8  339.03  5331.7  343.52  5337.3  344.29  5398.8  346.14  5404.4  347.07
  5465.9   349.6  5493.8  351.54  5590.6  355.04  5672.7   356.6  5847.9  357.55
#Mann= 3 ,-1 , 0
  4201.5     .05       0  4994.6     .03       0  5000.6     .05       0
Bank Sta=4966.9,5024.5
XS Rating Curve= 0 ,0
Exp/Cntr=0.3,0.1

Chan Stop Cuts=-1
Use User Specified Reach Order=0
Composite Channel Slope=5