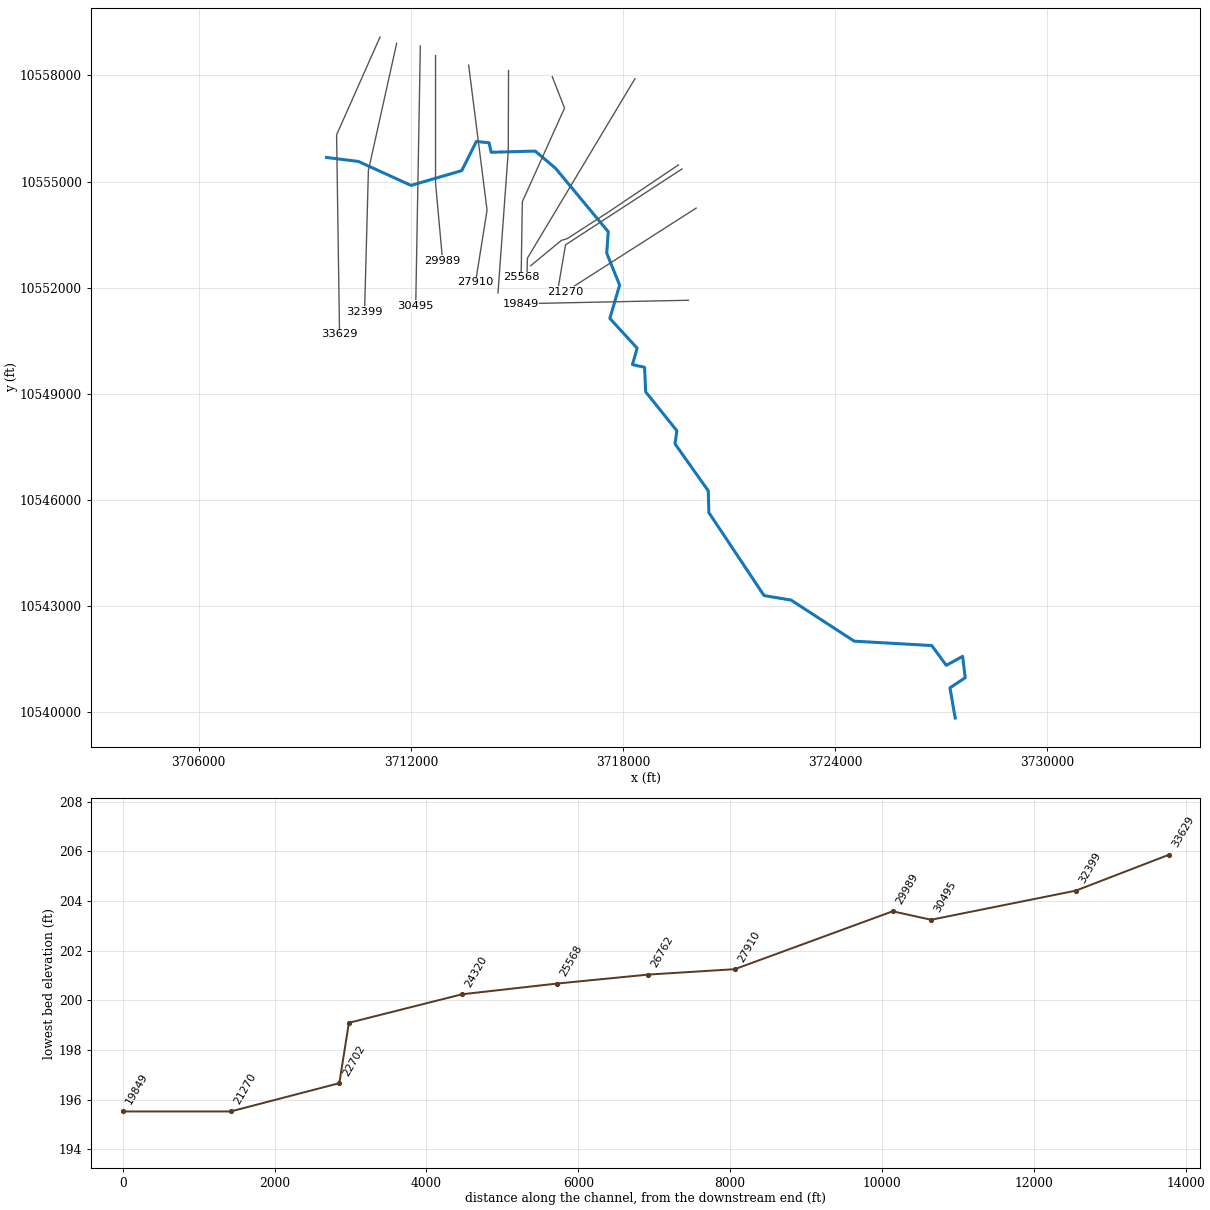
--- BOONS CREEK.prj (project) ---

Proj Title=BOONS CREEK Base Level Engineering
Current Plan=p01
Default Exp/Contr=0.3,0.1
English Units
Geom File=g01
Flow File=f01
Plan File=p01
Y Axis Title=Elevation
X Axis Title(PF)=Main Channel Distance
X Axis Title(XS)=Station
BEGIN DESCRIPTION:
BOONS CREEK
END DESCRIPTION:
DSS Export Rating Curves= 0
DSS Export Rating Curve Sorted= 0
DSS Export Volume Flow Curves= 0
DXF OffsetX= 0
DXF OffsetY= 0
DXF ScaleX= 1
DXF ScaleY= 10

--- BOONS CREEK.p01 (plan) ---

Plan Title=Multiple Run
Short Identifier=Multiple
Geom File=g01
Flow File=f01
Subcritical Flow
K Sum by GR= 0
Std Step Tol= 0.01
Critical Tol= 0.01
Num of Std Step Trials= 20
Max Error Tol= 0.3
Flow Tol Ratio= 0.001
Split Flow NTrial= 30
Split Flow Tol= 0.02
Split Flow Ratio= 0.02
Log Output Level= 0
Friction Slope Method= 1
Unsteady Friction Slope Method= 2
Unsteady Bridges Friction Slope Method= 1
Parabolic Critical Depth
Global Vel Dist=  1 , 1 , 1
Global Log Level= 0
CheckData=True
Encroach Param= -1, 0, 0, 0
BEGIN DESCRIPTION:
Multiple Run
END DESCRIPTION:

--- BOONS CREEK.f01 (steady flow) ---

Flow Title=Multiple
Program Version=4.10
Number of Profiles= 7
Profile Names=10-year,25-year,50-year,1pct_min,100-year,1pct_plu,500-year
River Rch & RM=BOONS CREEK,Reach-1         ,33629
    2985    4303    5452    5046    6824    9229   10746
River Rch & RM=BOONS CREEK,Reach-1         ,27910
    3034    4368    5531    5115    6917    9354   10874
River Rch & RM=BOONS CREEK,Reach-1         ,25568
    2988    4286    5412    4990    6749    9127   10549
Boundary for River Rch & Prof#=BOONS CREEK,Reach-1         , 1
Up Type= 0
Dn Type= 3
Dn Slope=0.00023
Boundary for River Rch & Prof#=BOONS CREEK,Reach-1         , 2
Up Type= 0
Dn Type= 3
Dn Slope=0.00023
Boundary for River Rch & Prof#=BOONS CREEK,Reach-1         , 3
Up Type= 0
Dn Type= 3
Dn Slope=0.00023
Boundary for River Rch & Prof#=BOONS CREEK,Reach-1         , 4
Up Type= 0
Dn Type= 3
Dn Slope=0.00023
Boundary for River Rch & Prof#=BOONS CREEK,Reach-1         , 5
Up Type= 0
Dn Type= 3
Dn Slope=0.00023
Boundary for River Rch & Prof#=BOONS CREEK,Reach-1         , 6
Up Type= 0
Dn Type= 3
Dn Slope=0.00023
Boundary for River Rch & Prof#=BOONS CREEK,Reach-1         , 7
Up Type= 0
Dn Type= 3
Dn Slope=0.00023
DSS Import GetInterval= 0
DSS Import GetPeak= 0
DSS Import FillOption= 0

--- BOONS CREEK.g01 (geometry) ---

Geom Title=Existing Conditions
Program Version=4.10

River Reach=BOONS CREEK     ,Reach-1
Reach XY= 30
        3709615.       10555681.        3710518.       10555567.
        3712005.       10554890.       3713439.5       10555307.
      3713853.75       10556132.      3714213.25       10556096.
        3714274.       10555827.      3715519.25       10555861.
      3716093.75       10555375.        3717586.       10553579.
      3717542.75       10552971.       3717908.5       10552069.
      3717630.75       10551128.       3718404.5       10550283.
       3718270.5       10549821.      3718614.25       10549743.
      3718644.75       10549048.      3719527.75       10547949.
      3719474.75       10547578.        3720416.       10546249.
      3720432.75       10545632.       3721993.5       10543286.
      3722762.25       10543155.       3724546.5       10541994.
        3726739.       10541871.      3727149.75       10541311.
      3727612.25       10541565.      3727686.25       10540961.
       3727254.5       10540674.      3727402.67     10539820.82

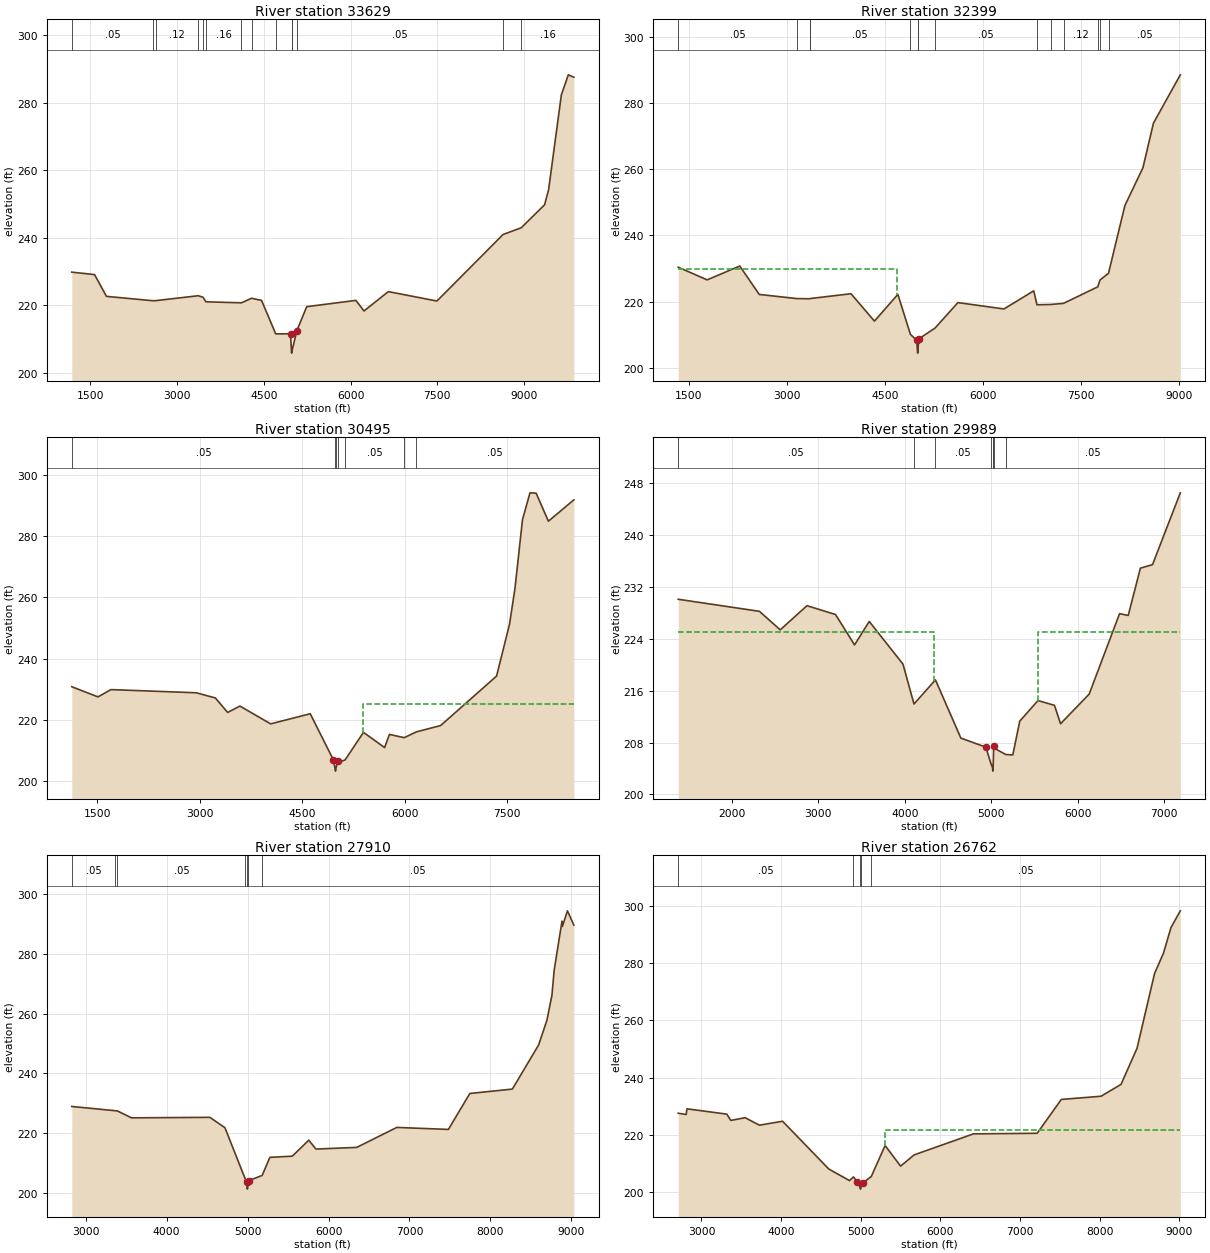
Type RM Length L Ch R = 1 ,33629   ,1230,1230,1230
BEGIN DESCRIPTION:
BOONS CREEK 34.0
END DESCRIPTION:
XS GIS Cut Line= 3
      3711129.18     10559090.17      3709899.99     10556319.29
      3709983.32     10550674.29
#Sta/Elev= 30
  1182.1  229.84  1575.9  229.11  1781.8  222.67  2586.7  221.37  2636.8  221.41
  3368.4  222.86  3451.5   222.4  3500.7  221.06  4115.3  220.76  4289.2  222.11
  4462.5  221.47  4706.4  211.57  4962.6  211.59  4979.6  206.37  4982.3  205.87
  4985.6  206.37  5072.6  212.53  5072.7  212.54  5242.6  219.62  6092.7  221.48
  6232.7  218.35  6652.8  224.08  7492.8  221.29  8635.8  240.98  8949.4  242.97
    9353  249.77  9423.1  254.25  9643.1   282.3  9763.1  288.24    9859  287.54
#Mann= 14 ,-1 , 0
  1182.1     .05       0  2586.7     .16       0  2636.8     .12       0
  3368.4     .16       0  3451.5     .12       0  3500.7     .16       0
  4115.3     .05       0  4289.2     .16       0  4706.4     .12       0
  4979.6     .07       0  4985.6     .12       0  5072.7     .05       0
  8635.8     .08       0  8949.4     .16       0
Bank Sta=4962.6,5072.6
XS Rating Curve= 0 ,0
Exp/Cntr=0.3,0.1

Type RM Length L Ch R = 1 ,32399   ,1904,1904,1904
BEGIN DESCRIPTION:
BOONS CREEK 33.0
END DESCRIPTION:
XS GIS Cut Line= 3
      3711599.61     10558910.18      3710799.61     10555310.19
      3710691.66     10551319.26
#Sta/Elev= 30
    1337  230.41  1778.8  226.57  2278.2  230.76  2576.5  222.17  3147.5  220.92
  3348.3  220.86  3351.5  220.92  3979.9  222.38  4338.5   214.1    4697  222.19
  4888.6   210.1  4983.8  208.31  4997.5  204.92  5000.2  204.42  5003.5  204.92
  5014.6   208.7  5265.7     212    5615   219.7  6319.8  217.78  6775.4  223.26
  6824.4  219.04  7034.7  219.13  7231.2  219.47  7755.4  224.48  7788.4  226.53
  7918.8  228.56  8169.7  249.06  8446.1  260.51  8606.1  273.96  9017.2  288.58
#Mann= 14 ,-1 , 0
    1337     .05       0  3147.5     .16       0  3348.3     .12       0
  3351.5     .05       0  4888.6     .12       0  4997.5     .07       0
  5003.5     .12       0  5265.7     .05       0  6824.4     .12       0
  7034.7     .07       0  7231.2     .12       0  7755.4     .08       0
  7788.4     .12       0  7918.8     .05       0
#XS Ineff= 2 , 0
       0  4686.8     230               0
Permanent Ineff=
       F       F
Bank Sta=4983.8,5014.6
XS Rating Curve= 0 ,0
Exp/Cntr=0.3,0.1

Type RM Length L Ch R = 1 ,30495   ,506,506,506
BEGIN DESCRIPTION:
BOONS CREEK 30.0
END DESCRIPTION:
XS GIS Cut Line= 2
      3712269.13     10558834.42      3712138.92     10551477.67
#Sta/Elev= 30
  1123.8   230.8  1508.1  227.48  1698.1  229.86  2948.3  228.82  3228.4  227.13
  3408.4   222.4  3588.4  224.48  4038.5  218.67  4618.6  221.98  4958.6   206.9
  4985.6  203.75  4988.4  203.25  4991.6  203.75  5018.6  206.56  5027.6  206.06
  5130.2  206.93  5398.7   215.9  5708.7  210.94  5778.8  215.23  5995.6  214.17
  6175.1  216.07  6528.9  218.12    7349  234.26    7539  251.19    7619  262.88
  7729.1  285.32  7839.1  294.08  7929.1  293.96  8109.1  284.82  8481.7  291.79
#Mann= 7 ,-1 , 0
  1123.8     .05       0  4985.6     .03       0  4991.6     .05       0
  5027.6     .12       0  5130.2     .05       0  5995.6     .12       0
  6175.1     .05       0
#XS Ineff= 2 , 0
       0                  5389.7       0     225
Permanent Ineff=
       F       F
Bank Sta=4958.6,5018.6
XS Rating Curve= 0 ,0
Exp/Cntr=0.3,0.1

Type RM Length L Ch R = 1 ,29989   ,2079,2079,2079
BEGIN DESCRIPTION:
BOONS CREEK 29.0
END DESCRIPTION:
XS GIS Cut Line= 3
      3712699.61     10558560.22      3712699.61     10554960.19
      3712899.61     10552760.19
#Sta/Elev= 30
  1379.7  230.07  2319.7  228.21  2559.7  225.36  2869.7  229.08  3199.7  227.72
  3419.7  223.04  3589.7  226.65  3979.7  220.09  4107.5  213.93  4355.8  217.65
  4649.7  208.68  4939.7  207.28  4993.8   204.9  5016.9  204.09  5019.6  203.59
  5022.9  204.09  5029.9  207.49  5036.6  207.13  5168.6  206.15  5250.8  206.09
  5331.2  211.29    5542  214.46  5732.8  213.73  5803.1  210.89  6134.5  215.46
  6485.9  227.85  6586.3  227.58  6726.9  234.86  6867.5  235.41  7188.8  246.47
#Mann= 8 ,-1 , 0
  1379.7     .05       0  4107.5     .08       0  4355.8     .05       0
  4993.8     .12       0  5016.9     .07       0  5022.9     .12       0
  5036.6     .07       0  5168.6     .05       0
#XS Ineff= 2 , 0
       0  4339.7     225    5542       0     225
Permanent Ineff=
       F       F
Bank Sta=4939.7,5029.9
XS Rating Curve= 0 ,0
Exp/Cntr=0.3,0.1

Type RM Length L Ch R = 1 ,27910   ,1148,1148,1148
BEGIN DESCRIPTION:
BOONS CREEK 26.0
END DESCRIPTION:
XS GIS Cut Line= 3
      3713636.31     10558291.88      3714157.15      10554190.3
      3713831.62     10552150.33
#Sta/Elev= 30
  2829.4  228.95  3364.5  227.53    3394  227.44    3567  225.14  4534.7  225.31
  4721.1  221.83  4971.6  204.67  4988.3  203.77  4995.4  201.76  4998.1  201.26
  5001.4  201.76  5018.5  204.13  5180.6  205.85  5276.2   211.9  5552.8   212.3
  5756.2  217.65  5845.1  214.68  6349.1  215.24  6843.1  221.93  7480.5  221.26
  7745.2   233.3  8270.3  234.77  8594.4  249.53  8697.1  257.83  8759.2   266.2
  8786.8  274.59  8883.4  291.03  8888.5  289.26  8950.6  294.49  9029.7  289.72
#Mann= 7 ,-1 , 0
  2829.4     .05       0  3364.5     .08       0    3394     .05       0
  4971.6     .12       0  4995.4     .07       0  5001.4     .12       0
  5180.6     .05       0
Bank Sta=4988.3,5018.5
XS Rating Curve= 0 ,0
Exp/Cntr=0.3,0.1

Type RM Length L Ch R = 1 ,26762   ,1194,1194,1194
BEGIN DESCRIPTION:
BOONS CREEK 23.0
END DESCRIPTION:
XS GIS Cut Line= 3
      3714764.79     10558139.93      3714756.83     10555848.86
      3714466.19     10551848.18
#Sta/Elev= 30
  2708.5  227.56  2808.2   227.1  2818.2  229.09  3318.2  227.24  3368.2  225.04
  3548.2  225.99  3728.2  223.38  4018.2  224.76  4598.2  208.07  4858.3  204.02
  4907.3   205.3  4958.3  203.63  4993.4  201.54  4996.2  201.04  4999.4  201.54
  5026.8  203.21  5131.9  205.47  5305.2  216.27  5499.6  209.08    5670     213
  6413.7  220.34  7214.1  220.55  7517.2  232.37  8016.2  233.49  8266.8  237.63
  8467.4  250.23  8687.9   276.4  8798.2  283.38  8894.1  292.43  9010.8  298.26
#Mann= 5 ,-1 , 0
  2708.5     .05       0  4907.3     .12       0  4993.4     .07       0
  4999.4     .12       0  5131.9     .05       0
#XS Ineff= 2 , 0
       0                  5305.2       0  221.73
Permanent Ineff=
       F       F
Bank Sta=4958.3,5026.8
XS Rating Curve= 0 ,0
Exp/Cntr=0.3,0.1

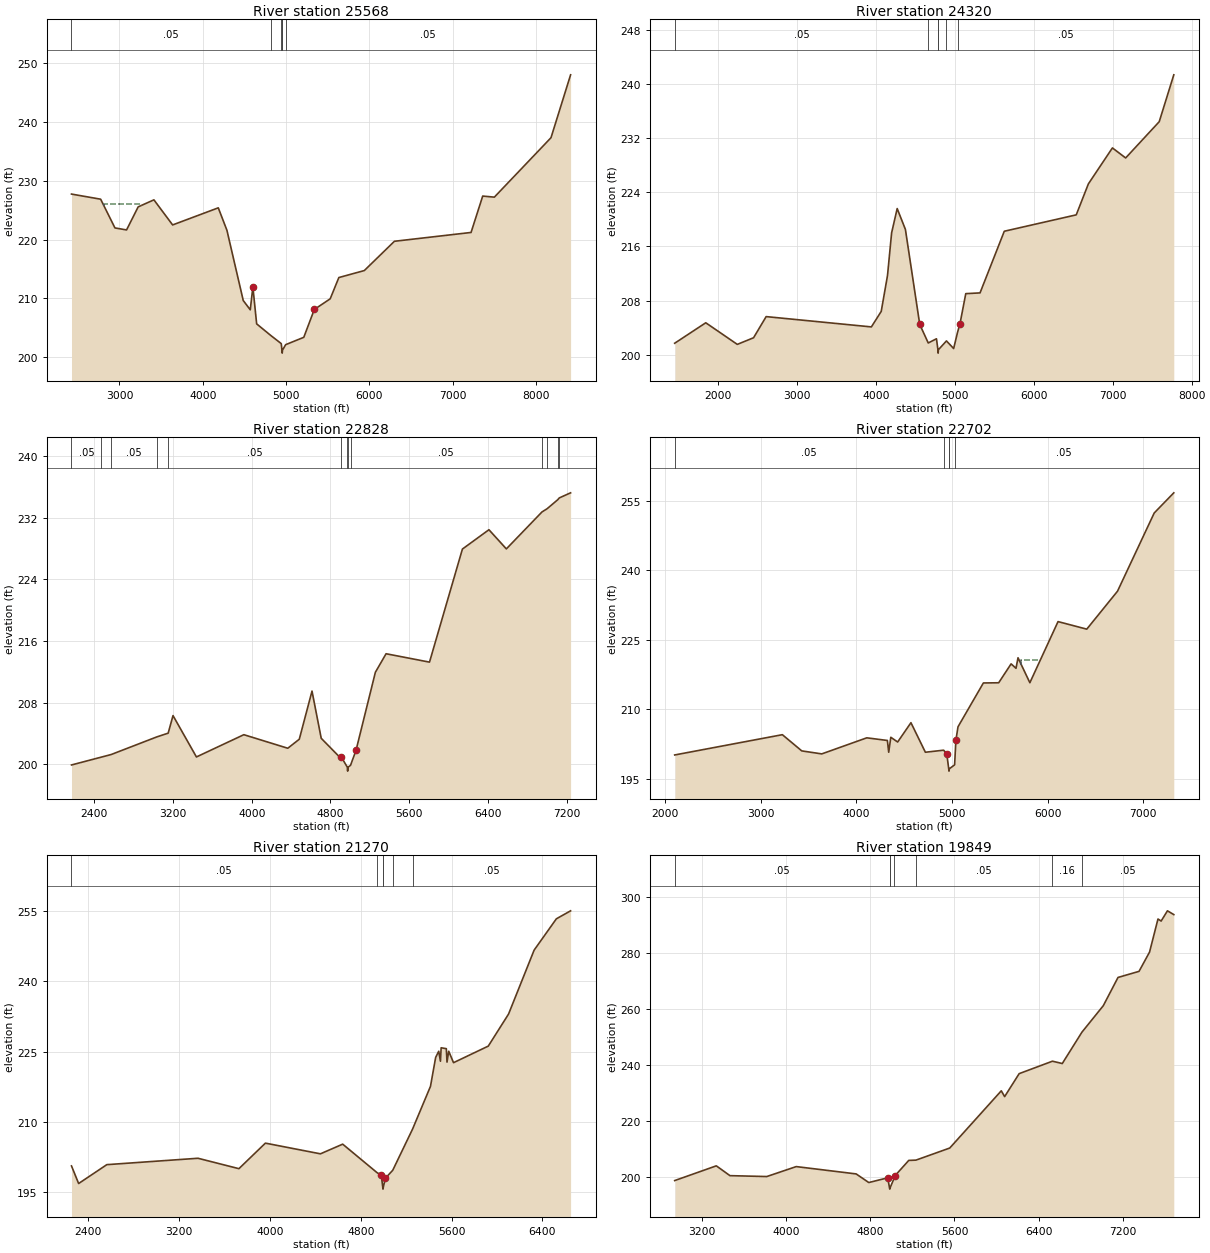
Type RM Length L Ch R = 1 ,25568   ,1248,1248,1248
BEGIN DESCRIPTION:
BOONS CREEK 20.0
END DESCRIPTION:
XS GIS Cut Line= 4
      3716001.76     10557966.36      3716348.99     10557076.59
      3715155.41     10554429.02      3715120.99      10552294.8
#Sta/Elev= 30
  2423.7  227.74  2773.8  226.87  2945.6  221.98  3085.1  221.64  3224.3  225.56
  3413.5  226.76  3638.2  222.49  4186.6   225.4  4290.3  221.58  4486.3  209.63
  4570.5  208.05    4602  211.93  4647.3  205.66  4815.6   203.7  4942.6   202.3
  4951.4  201.18  4954.2  200.68  4957.4  201.18  4995.5  202.12  5213.3  203.37
  5339.9  208.11  5530.5  209.92  5634.5  213.54  5940.3  214.73  6301.8  219.71
    7222  221.21    7362   227.4    7502  227.22  8182.1  237.33  8417.5  248.03
#Mann= 6 ,-1 , 0
  2423.7     .05       0  4815.6     .07       0  4942.6     .12       0
  4951.4     .03       0  4957.4     .12       0  4995.5     .05       0
#XS Ineff= 1 ,-1
    2814  3254.1  225.97
Permanent Ineff=
       F
Bank Sta=4602,5339.9
XS Rating Curve= 0 ,0
Exp/Cntr=0.3,0.1

Type RM Length L Ch R = 1 ,24320   ,1492,1492,1492
BEGIN DESCRIPTION:
Mapping XS b1e326b8
END DESCRIPTION:
XS GIS Cut Line= 3
      3718340.94     10557908.09      3715298.72     10552830.43
      3715287.78     10552425.55
#Sta/Elev= 30
  1449.4  201.71  1843.3  204.73  2242.8  201.54  2448.9  202.52  2608.3  205.64
  3941.7  204.12  4066.5  206.41  4146.2  211.72  4198.1     218  4268.7  221.59
    4373  218.51  4554.5  204.49  4662.2  201.75  4766.5  202.37  4784.9  200.75
  4787.6  200.25  4790.9  200.75  4892.9  202.05  4984.2  200.93  5033.6  203.33
  5063.9  204.55  5137.8  209.03  5318.6  209.14  5625.8  218.24  6537.7  220.66
  6691.3  225.23  6995.9  230.54  7163.8  229.06    7589  234.41  7773.7  241.33
#Mann= 6 ,-1 , 0
  1449.4     .05       0  4662.2     .07       0  4784.9     .07       0
  4790.9     .07       0  4892.9     .12       0  5033.6     .05       0
Bank Sta=4554.5,5063.9
XS Rating Curve= 0 ,0
Exp/Cntr=0.3,0.1

Type RM Length L Ch R = 1 ,22828   ,126,126,126
BEGIN DESCRIPTION:
BOONS CREEK 19.0
END DESCRIPTION:
XS GIS Cut Line= 5
      3719573.41     10555469.71      3717588.83     10554134.43
      3716425.64     10553383.56       3716258.1     10553333.21
      3715393.21     10552617.38
#Sta/Elev= 30
  2167.5   199.9  2471.2  200.92  2569.7  201.25  3034.3  203.54  3150.5  204.03
  3199.6  206.31  3437.6  200.94  3919.7  203.83  4366.4  202.07  4483.3  203.24
  4612.7  209.49  4706.4  203.36  4905.6  200.77    4909  200.97  4972.1   199.6
  4974.9   199.1  4978.1   199.6  5004.1  199.85  5060.2   201.8  5256.8  211.93
  5365.7  214.34  5807.1  213.25  6141.8  227.93  6411.4  230.44  6588.5  227.95
  6950.9  232.75  7002.3  233.16  7112.3  234.35  7126.7  234.57  7241.6  235.23
#Mann= 13 ,-1 , 0
  2167.5     .05       0  2471.2      .1       0  2569.7     .05       0
  3034.3      .1       0  3150.5     .05       0  4905.6     .08       0
  4972.1     .07       0  4978.1     .08       0  5004.1     .05       0
  6950.9     .08       0  7002.3     .05       0  7112.3     .08       0
  7126.7     .05       0
Bank Sta=4909,5060.2
XS Rating Curve= 0 ,0
Exp/Cntr=0.3,0.1

Type RM Length L Ch R = 1 ,22702   ,1432,1432,1432
BEGIN DESCRIPTION:
BOONS CREEK 18.0
END DESCRIPTION:
XS GIS Cut Line= 3
      3719672.76     10555355.07      3716377.65     10553207.52
      3716160.62     10551940.32
#Sta/Elev= 30
  2101.1  200.16  3226.9  204.54  3429.8  201.04    3639  200.39  4109.8  203.86
    4325  203.29  4339.1  200.75  4360.8  203.98  4432.6  202.96  4571.5  207.13
  4722.4  200.75    4913  201.19  4945.7  200.45  4966.6  197.17  4969.3  196.67
  4972.6  197.17  5028.1  198.03  5041.2  203.29  5063.5  206.24  5328.9  215.71
  5488.9  215.75  5618.7  219.83    5670  218.88  5691.1  221.15  5814.9  215.76
  6109.6  228.96  6409.9  227.33  6731.6  235.53  7115.3  252.42  7319.9  256.77
#Mann= 5 ,-1 , 0
  2101.1     .05       0    4913     .08       0  4966.6     .07       0
  4972.6     .08       0  5028.1     .05       0
#XS Ineff= 1 ,-1
  5727.4 5923.98  220.67
Permanent Ineff=
       F
Bank Sta=4945.7,5041.2
XS Rating Curve= 0 ,0
Exp/Cntr=0.3,0.1

Type RM Length L Ch R = 1 ,21270   ,1421,1421,1421
BEGIN DESCRIPTION:
BOONS CREEK 16.0
END DESCRIPTION:
XS GIS Cut Line= 2
      3720071.65     10554246.37      3716368.92     10551877.78
#Sta/Elev= 30
  2252.6   200.5  2315.4  196.73  2563.7  200.77  3366.6  202.14    3727  199.91
  3960.3  205.38  4444.9  203.09  4641.1  205.16  4943.6  199.06  4981.1  198.52
  4993.3  196.03    4996  195.53  4999.3  196.03  5017.4  197.87    5082  199.58
  5256.2  208.38  5414.1  217.54  5459.7  223.73  5486.8  225.06    5502  222.92
    5508   225.8  5553.6  225.61  5559.6  222.73  5574.8  225.06  5617.1  222.61
  5923.2  226.16  6101.7  233.02  6326.8  246.71  6522.8  253.42  6648.1  255.13
#Mann= 6 ,-1 , 0
  2252.6     .05       0  4943.6     .07       0  4993.3     .07       0
  4999.3     .07       0    5082     .12       0  5256.2     .05       0
Bank Sta=4981.1,5017.4
XS Rating Curve= 0 ,0
Exp/Cntr=0.3,0.1

Type RM Length L Ch R = 1 ,19849   ,0,0,0
BEGIN DESCRIPTION:
Mapping XS 73e05359
END DESCRIPTION:
XS GIS Cut Line= 2
      3719855.29     10551640.01       3715109.2     10551541.85
#Sta/Elev= 30
  2938.9  198.59  3334.7  203.86  3464.7  200.35  3814.8  200.03  4094.8  203.59
  4664.9  200.97    4785  197.89    4965  199.57    4982  196.03  4984.8  195.53
    4988  196.03  5025.6  199.39    5035  200.35  5165.1   205.8  5233.4   205.9
  5555.1  210.23  6045.2   230.7  6077.1  228.62  6215.3  236.84  6531.8  241.29
  6625.4  240.46    6812  251.66  7015.5  261.15  7155.5  271.25  7355.5  273.43
  7455.5  280.33  7535.6  292.16  7565.6  291.42  7625.6  295.08    7686  293.74
#Mann= 7 ,-1 , 0
  2938.9     .05       0    4982     .03       0    4988     .05       0
  5025.6     .12       0  5233.4     .05       0  6531.8     .16       0
    6812     .05       0
Bank Sta=4965,5035
XS Rating Curve= 0 ,0
Exp/Cntr=0.3,0.1

Chan Stop Cuts=-1
Use User Specified Reach Order=0
Composite Channel Slope=5