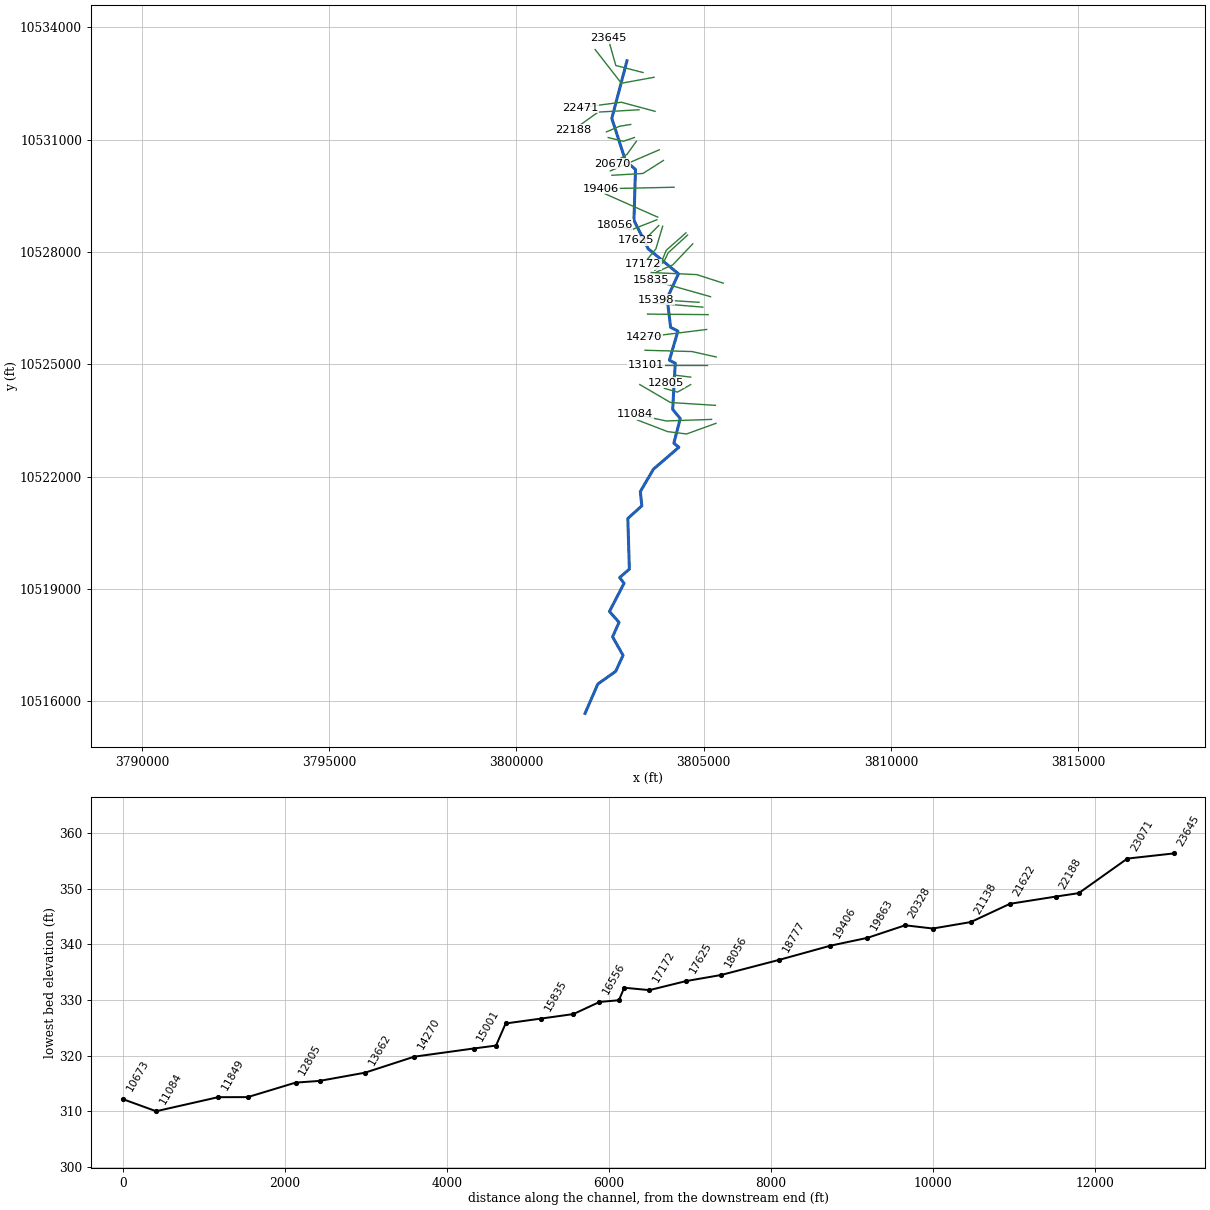
--- CANEY CREEK.prj (project) ---

Proj Title=CANEY CREEK Base Level Engineering
Current Plan=p01
Default Exp/Contr=0.3,0.1
English Units
Geom File=g01
Flow File=f01
Plan File=p01
Y Axis Title=Elevation
X Axis Title(PF)=Main Channel Distance
X Axis Title(XS)=Station
BEGIN DESCRIPTION:
CANEY CREEK
END DESCRIPTION:
DSS Export Rating Curves= 0
DSS Export Rating Curve Sorted= 0
DSS Export Volume Flow Curves= 0
DXF OffsetX= 0
DXF OffsetY= 0
DXF ScaleX= 1
DXF ScaleY= 10

--- CANEY CREEK.p01 (plan) ---

Plan Title=Multiple Run
Short Identifier=Multiple
Geom File=g01
Flow File=f01
Subcritical Flow
K Sum by GR= 0
Std Step Tol= 0.01
Critical Tol= 0.01
Num of Std Step Trials= 20
Max Error Tol= 0.3
Flow Tol Ratio= 0.001
Split Flow NTrial= 30
Split Flow Tol= 0.02
Split Flow Ratio= 0.02
Log Output Level= 0
Friction Slope Method= 1
Unsteady Friction Slope Method= 2
Unsteady Bridges Friction Slope Method= 1
Parabolic Critical Depth
Global Vel Dist=  1 , 1 , 1
Global Log Level= 0
CheckData=True
Encroach Param= -1, 0, 0, 0
BEGIN DESCRIPTION:
Multiple Run
END DESCRIPTION:

--- CANEY CREEK.f01 (steady flow) ---

Flow Title=Multiple
Program Version=4.10
Number of Profiles= 7
Profile Names=10-year,25-year,50-year,1pct_min,100-year,1pct_plu,500-year
River Rch & RM=CANEY CREEK,Reach-1         ,23645
     785    1074    1316    1184    1601    2166    2379
River Rch & RM=CANEY CREEK,Reach-1         ,22471
    1535    2169    2715    2490    3368    4554    5203
River Rch & RM=CANEY CREEK,Reach-1         ,21622
    1535    2169    2715    2490    3368    4554    5203
River Rch & RM=CANEY CREEK,Reach-1         ,15835
    1684    2380    2977    2728    3689    4989    5688
River Rch & RM=CANEY CREEK,Reach-1         ,7665
    1909    2704    3388    3107    4202    5683    6490
Boundary for River Rch & Prof#=CANEY CREEK,Reach-1         , 1
Up Type= 0
Dn Type= 3
Dn Slope=0.0028
Boundary for River Rch & Prof#=CANEY CREEK,Reach-1         , 2
Up Type= 0
Dn Type= 3
Dn Slope=0.0028
Boundary for River Rch & Prof#=CANEY CREEK,Reach-1         , 3
Up Type= 0
Dn Type= 3
Dn Slope=0.0028
Boundary for River Rch & Prof#=CANEY CREEK,Reach-1         , 4
Up Type= 0
Dn Type= 3
Dn Slope=0.0028
Boundary for River Rch & Prof#=CANEY CREEK,Reach-1         , 5
Up Type= 0
Dn Type= 3
Dn Slope=0.0028
Boundary for River Rch & Prof#=CANEY CREEK,Reach-1         , 6
Up Type= 0
Dn Type= 3
Dn Slope=0.0028
Boundary for River Rch & Prof#=CANEY CREEK,Reach-1         , 7
Up Type= 0
Dn Type= 3
Dn Slope=0.0028
DSS Import GetInterval= 0
DSS Import GetPeak= 0
DSS Import FillOption= 0

--- CANEY CREEK.g01 (geometry) ---

Geom Title=Existing Conditions
Program Version=4.10

River Reach=CANEY CREEK     ,Reach-1
Reach XY= 30
       3802949.5       10533111.       3802544.5       10531572.
      3802913.25       10530431.       3803176.5       10530209.
       3803135.5       10528848.       3803515.5       10528089.
      3804324.25       10527420.      3804021.25       10526765.
      3804114.25       10525991.        3804309.       10525890.
       3804081.5       10525110.       3804238.5       10525031.
       3804169.5       10523801.      3804370.75       10523552.
       3804200.5       10522895.        3804335.       10522787.
        3803656.       10522201.       3803305.5       10521603.
      3803345.75       10521222.      3802971.75       10520884.
      3803013.25       10519531.       3802753.5       10519307.
      3802871.75       10519153.      3802481.25       10518400.
      3802737.75       10518110.      3802565.25       10517722.
        3802844.       10517229.        3802648.       10516801.
      3802171.75       10516463.        3801830.       10515678.

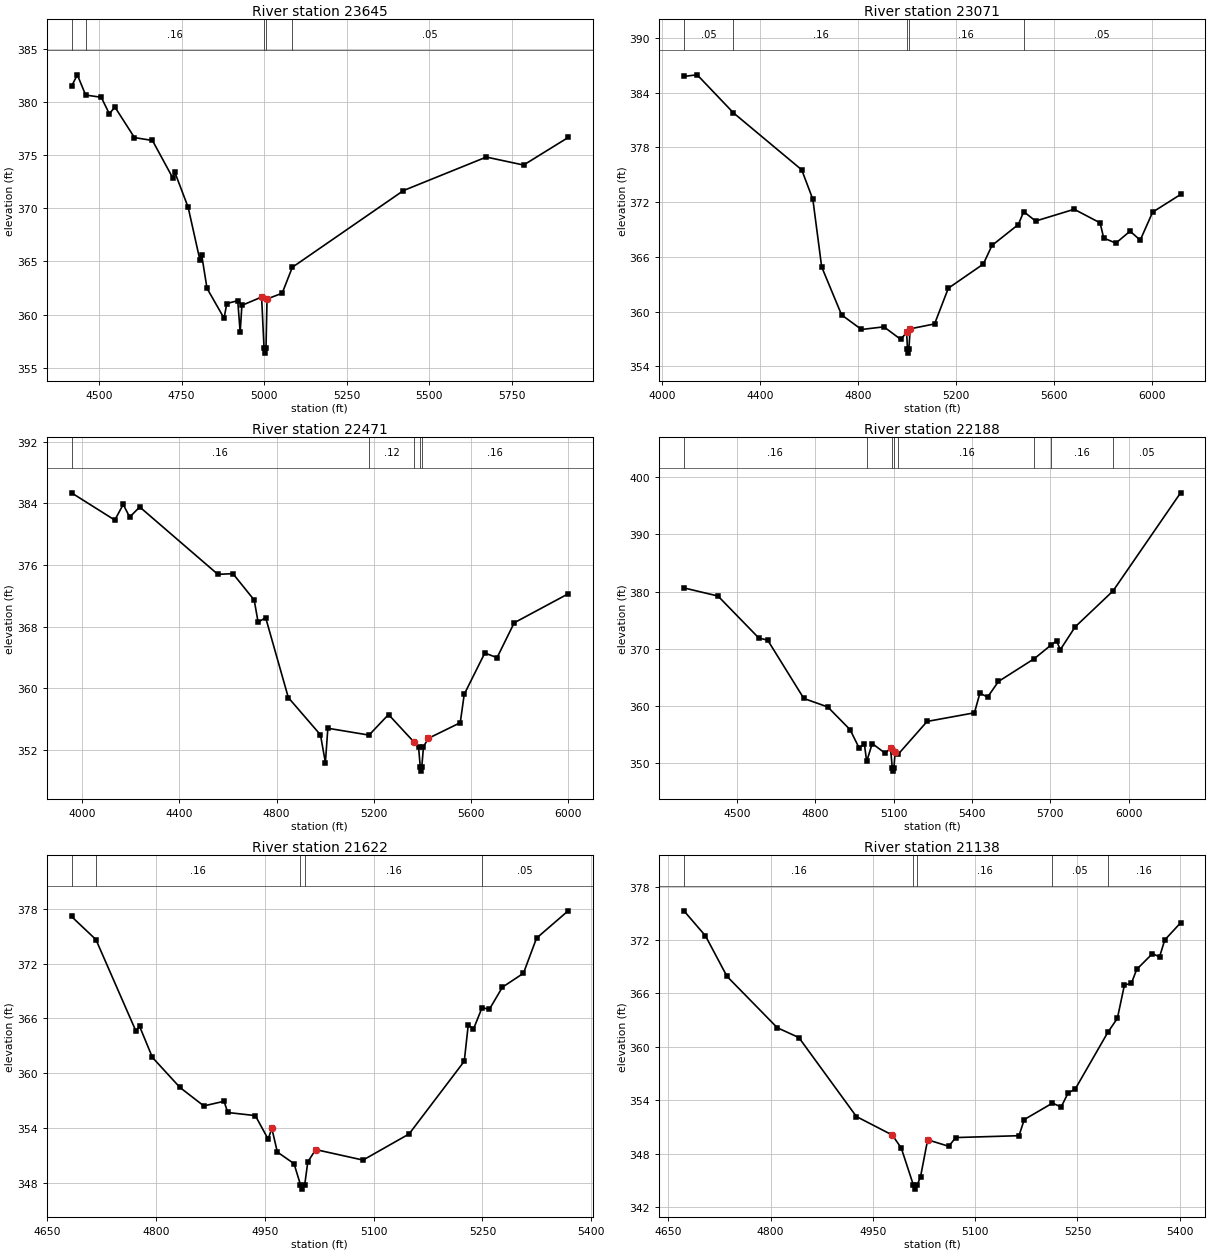
Type RM Length L Ch R = 1 ,23645   ,574,574,574
BEGIN DESCRIPTION:
CANEY CREEK 44.0
END DESCRIPTION:
XS GIS Cut Line= 3
      3803376.79     10532796.88      3802651.13     10532984.37
      3802446.28     10533710.02
#Sta/Elev= 30
    4417  381.46  4434.7  382.54  4459.8  380.64    4507  380.43  4531.5  378.88
  4548.4  379.51  4607.6  376.64    4662  376.37  4723.9  372.83  4729.6   373.4
  4770.2  370.08  4805.7  365.13  4810.9  365.64  4827.2  362.47  4878.9  359.66
    4887  361.04  4920.2  361.31  4927.6  358.35  4932.8  360.87  4992.5  361.65
  4999.8  356.88  5002.6  356.38  5005.8  356.88  5008.9  361.47  5054.7  362.01
  5085.5  364.45  5421.9  371.66  5672.7  374.81  5785.6  374.06  5920.5  376.65
#Mann= 5 ,-1 , 0
    4417     .05       0  4459.8     .16       0  4999.8     .07       0
  5005.8     .16       0  5085.5     .05       0
Bank Sta=4992.5,5008.9
XS Rating Curve= 0 ,0
Exp/Cntr=0.3,0.1

Type RM Length L Ch R = 1 ,23071   ,600,600,600
BEGIN DESCRIPTION:
CANEY CREEK 43.0
END DESCRIPTION:
XS GIS Cut Line= 3
       3803672.8     10532669.73      3802799.61     10532510.19
      3802099.62     10533410.17
#Sta/Elev= 30
  4089.7  385.77  4143.8  385.94    4292  381.77  4570.7  375.53  4616.1   372.3
  4652.1   364.9  4733.4  359.64  4814.7  358.04  4906.2  358.33  4974.8  356.96
  4999.1  357.71  5002.4  355.95  5005.2  355.45  5008.4  355.95  5013.5  358.11
  5113.1  358.65  5169.2  362.56  5312.2  365.21  5347.5  367.25  5455.1  369.54
  5477.1  370.95  5525.7  369.92  5683.2  371.21    5789  369.72  5803.5  368.06
  5853.3   367.5  5911.2  368.81  5952.8  367.83  6003.5   370.9  6117.5  372.83
#Mann= 5 ,-1 , 0
  4089.7     .05       0    4292     .16       0  5002.4     .07       0
  5008.4     .16       0  5477.1     .05       0
Bank Sta=4999.1,5013.5
XS Rating Curve= 0 ,0
Exp/Cntr=0.3,0.1

Type RM Length L Ch R = 1 ,22471   ,283,283,283
BEGIN DESCRIPTION:
CANEY CREEK 42.0
END DESCRIPTION:
XS GIS Cut Line= 3
      3803700.55     10531760.02      3802797.81     10532003.07
      3801699.65     10531860.19
#Sta/Elev= 30
  3956.9  385.38  4134.9  381.84  4169.6  383.87  4196.1  382.23  4237.5  383.54
  4558.7  374.79  4620.7  374.88  4708.2  371.45  4724.2  368.58  4755.3  369.16
  4848.5  358.78  4980.7  353.94  5000.9  350.34    5011   354.8  5180.3  353.91
  5260.5  356.58  5363.9  353.05  5365.1  352.97  5384.1  352.31  5391.2  349.73
  5393.9  349.23  5397.2  349.73  5404.3  352.42  5424.4  353.49  5555.5  355.52
  5571.8  359.21  5656.4  364.57  5706.8  363.97  5777.4   368.5  5999.2  372.26
#Mann= 5 ,-1 , 0
  3956.9     .16       0  5180.3     .12       0  5365.1     .16       0
  5391.2     .07       0  5397.2     .16       0
Bank Sta=5363.9,5424.4
XS Rating Curve= 0 ,0
Exp/Cntr=0.3,0.1

Type RM Length L Ch R = 1 ,22188   ,566,566,566
BEGIN DESCRIPTION:
CANEY CREEK 41.0
END DESCRIPTION:
XS GIS Cut Line= 3
      3803270.04     10531801.68      3802179.75     10531739.18
      3801520.02     10531266.95
#Sta/Elev= 30
  4296.2  380.65  4426.8  379.23  4583.2  371.89  4617.2  371.52  4755.7  361.32
  4847.5  359.83  4933.2  355.85  4967.7  352.65  4987.8  353.33  4996.7   350.3
  5017.8  353.44  5067.9  351.72  5087.9  352.64  5094.9  349.11  5097.7  348.61
  5100.9  349.11  5105.7  352.01  5118.1   351.6  5228.2   357.3  5409.6  358.81
  5430.5  362.25    5460  361.56  5501.7  364.29  5639.4  368.29    5704  370.69
  5724.1  371.39  5738.8  369.85  5795.4  373.83  5940.7  380.12  6199.6  397.28
#Mann= 8 ,-1 , 0
  4296.2     .16       0  4996.7     .12       0  5094.9     .07       0
  5100.9     .12       0  5118.1     .16       0  5639.4     .05       0
    5704     .16       0  5940.7     .05       0
Bank Sta=5087.9,5105.7
XS Rating Curve= 0 ,0
Exp/Cntr=0.3,0.1

Type RM Length L Ch R = 1 ,21622   ,484,484,484
BEGIN DESCRIPTION:
CANEY CREEK 40.0
END DESCRIPTION:
XS GIS Cut Line= 3
      3803049.65     10531410.19      3802749.61     10531360.19
      3802399.58     10531210.17
#Sta/Elev= 30
  4683.3  377.16    4717  374.63    4772  364.64  4777.1  365.15  4794.9  361.73
  4832.9  358.44  4865.8  356.42  4893.7  356.93  4898.8   355.7  4936.8  355.36
  4954.5  352.79  4959.6  353.96  4967.2  351.37  4990.2   350.1    4999  347.81
  5001.7  347.31    5005  347.81  5009.2  350.29  5020.1  351.64  5085.4  350.49
  5148.9  353.35    5225  361.31  5230.5   365.3  5237.7  364.83  5249.6  367.19
  5259.5  366.98  5277.6  369.42  5306.6  370.94  5324.7  374.79  5368.3  377.78
#Mann= 5 ,-1 , 0
  4683.3     .05       0    4717     .16       0    4999     .07       0
    5005     .16       0  5249.6     .05       0
Bank Sta=4959.6,5020.1
XS Rating Curve= 0 ,0
Exp/Cntr=0.3,0.1

Type RM Length L Ch R = 1 ,21138   ,468,468,468
BEGIN DESCRIPTION:
CANEY CREEK 39.0
END DESCRIPTION:
XS GIS Cut Line= 3
       3803149.6     10531060.19      3802849.61     10530960.19
      3802449.64     10531060.18
#Sta/Elev= 30
  4672.8  375.27  4704.4  372.46    4736  367.91  4809.8  362.14  4841.4  361.04
  4925.8  352.17  4978.5  350.09  4991.6  348.63  5009.2  344.52    5012  344.02
  5015.2  344.52  5019.9  345.42  5030.3  349.56  5061.2  348.83  5071.5  349.81
  5164.3  350.02    5172  351.83  5213.4  353.68  5226.1  353.24  5236.4  354.83
  5246.7  355.25  5294.7  361.64  5308.6   363.2  5318.9  366.93  5329.2  367.14
  5336.9  368.69  5360.1  370.47  5370.4  370.09  5378.1     372  5401.3  373.92
#Mann= 5 ,-1 , 0
  4672.8     .16       0  5009.2     .07       0  5015.2     .16       0
  5213.4     .05       0  5294.7     .16       0
Bank Sta=4978.5,5030.3
XS Rating Curve= 0 ,0
Exp/Cntr=0.3,0.1

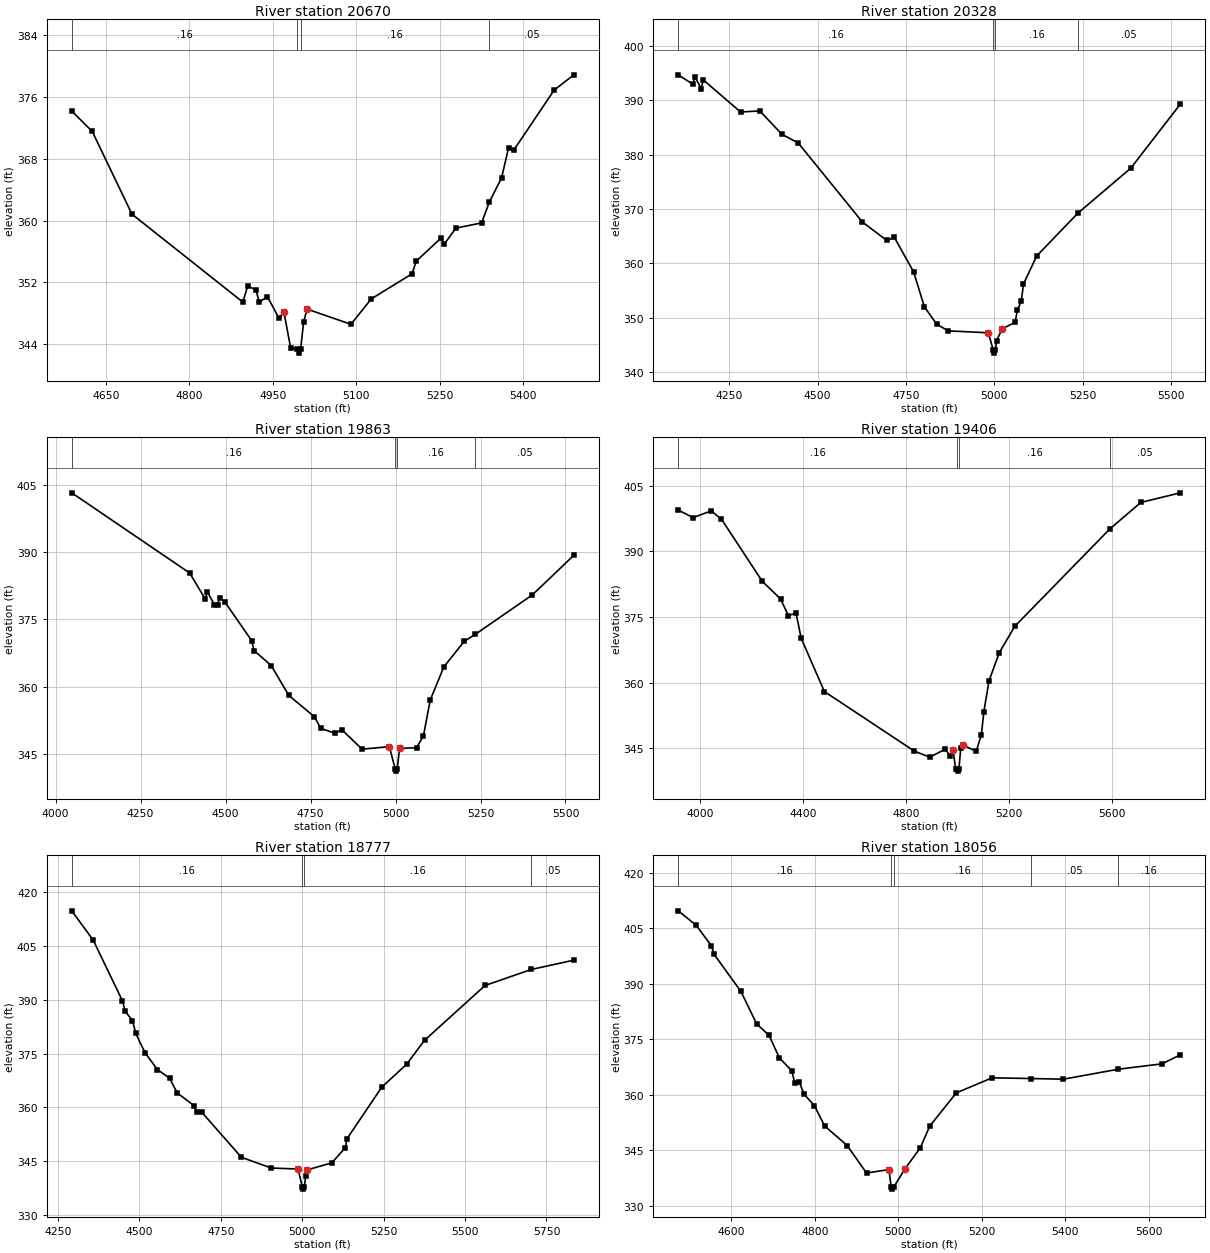
Type RM Length L Ch R = 1 ,20670   ,342,342,342
BEGIN DESCRIPTION:
CANEY CREEK 38.0
END DESCRIPTION:
XS GIS Cut Line= 3
       3803199.6     10530960.17      3802949.61     10530610.19
       3802549.6     10530360.18
#Sta/Elev= 30
    4589  374.15  4625.8  371.51  4697.1  360.82  4896.2  349.46  4904.8  351.49
  4919.6  351.08  4925.7  349.46  4940.4  350.16  4961.3  347.36  4969.9   348.2
  4982.2  343.52    4994  343.36  4996.7  342.86    5000  343.36  5005.6  346.94
  5011.7  348.55  5090.4  346.59    5127  349.87  5200.1  353.11  5207.8  354.76
    5252  357.71  5257.9  356.94  5279.1  359.02  5325.1  359.69  5338.9  362.37
  5361.1  365.53  5373.5  369.38  5382.9   369.1  5455.4  376.85  5490.8  378.83
#Mann= 4 ,-1 , 0
    4589     .16       0    4994     .07       0    5000     .16       0
  5338.9     .05       0
Bank Sta=4969.9,5011.7
XS Rating Curve= 0 ,0
Exp/Cntr=0.3,0.1

Type RM Length L Ch R = 1 ,20328   ,465,465,465
BEGIN DESCRIPTION:
CANEY CREEK 37.0
END DESCRIPTION:
XS GIS Cut Line= 2
      3803811.66     10530732.22      3802506.18     10530169.75
#Sta/Elev= 30
  4105.4  394.71  4147.1  392.96  4152.5  394.33  4170.6  392.18  4176.1  393.78
  4281.9  387.86  4336.3  388.06  4398.7  383.77  4445.2  382.15  4626.7   367.6
  4695.6  364.21  4717.4  364.75  4771.8  358.41  4802.3  351.97  4837.2  348.77
  4869.8  347.54  4983.3  347.19  4997.5  343.94  5000.3  343.44  5003.5  343.94
  5006.8  345.75  5022.3  347.88  5059.3  349.14  5065.8  351.42  5076.7  353.01
  5082.8  356.16  5120.3  361.34  5236.3  369.19  5386.9  377.53  5526.9  389.31
#Mann= 4 ,-1 , 0
  4105.4     .16       0  4997.5     .07       0  5003.5     .16       0
  5236.3     .05       0
Bank Sta=4983.3,5022.3
XS Rating Curve= 0 ,0
Exp/Cntr=0.3,0.1

Type RM Length L Ch R = 1 ,19863   ,457,457,457
BEGIN DESCRIPTION:
CANEY CREEK 36.0
END DESCRIPTION:
XS GIS Cut Line= 3
      3803922.84     10530447.53       3803374.2     10530100.29
      3802547.82     10530051.68
#Sta/Elev= 30
  4047.5  403.22  4394.5  385.34  4440.3  379.53  4446.2  381.15  4467.4  378.28
  4476.7  378.28  4482.6  379.87  4497.9   378.9  4576.7  370.27  4583.9  368.06
  4634.3  364.71  4686.1  358.05  4761.5  353.29  4780.1  350.71  4821.6  349.63
  4841.6  350.42  4901.7  346.08  4981.9  346.63  4998.9  341.68  5001.7  341.18
  5004.9  341.68  5011.9  346.25    5062   346.4  5082.1  349.05  5102.1  357.02
  5142.2  364.43  5202.3  370.13    5234  371.64  5402.6  380.47  5524.6   389.3
#Mann= 4 ,-1 , 0
  4047.5     .16       0  4998.9     .07       0  5004.9     .16       0
    5234     .05       0
Bank Sta=4981.9,5011.9
XS Rating Curve= 0 ,0
Exp/Cntr=0.3,0.1

Type RM Length L Ch R = 1 ,19406   ,629,629,629
BEGIN DESCRIPTION:
CANEY CREEK 35.0
END DESCRIPTION:
XS GIS Cut Line= 2
      3804207.52     10529732.23      3802256.16     10529690.57
#Sta/Elev= 30
  3914.3  399.43  3972.2  397.72  4042.2  399.25  4082.2  397.37  4240.8  383.17
  4312.3  379.11  4342.3  375.34  4372.3  375.87  4392.3  370.13  4482.3  357.97
  4832.4  344.33  4892.4  342.96  4952.4  344.79  4972.5  343.17  4982.5  344.64
  4992.5  340.35  4999.5  340.27  5002.2  339.77  5005.5  340.27  5012.5  344.96
  5022.5  345.68  5072.5   344.3  5092.5  348.02  5102.5  353.39  5122.5  360.42
  5162.5  366.86  5222.5  372.86  5592.2  395.13  5712.6  401.18  5866.1  403.38
#Mann= 4 ,-1 , 0
  3914.3     .16       0  4999.5     .07       0  5005.5     .16       0
  5592.2     .05       0
Bank Sta=4982.5,5022.5
XS Rating Curve= 0 ,0
Exp/Cntr=0.3,0.1

Type RM Length L Ch R = 1 ,18777   ,721,721,721
BEGIN DESCRIPTION:
CANEY CREEK 34.0
END DESCRIPTION:
XS GIS Cut Line= 2
      3803770.07     10528933.61      3802360.31     10529558.62
#Sta/Elev= 30
    4292  414.84  4358.1  406.63  4447.5  389.77  4456.6  386.77  4478.5   384.2
  4488.6  380.64  4517.4  375.21    4555  370.57  4592.6  368.15  4615.9  364.05
  4667.9   360.5  4675.4   358.6  4691.2  358.69  4813.1   346.1  4905.1  343.11
  4986.9  342.84  5000.5  337.73  5003.3  337.23  5006.5  337.73  5010.2  340.98
  5015.7  342.61    5091  344.57    5132  348.77  5137.5  351.31  5244.2  365.66
  5320.7  372.08  5375.4  378.72  5561.4  394.02  5703.2  398.48  5834.1  401.08
#Mann= 4 ,-1 , 0
    4292     .16       0  5000.5     .07       0  5006.5     .16       0
  5703.2     .05       0
Bank Sta=4986.9,5015.7
XS Rating Curve= 0 ,0
Exp/Cntr=0.3,0.1

Type RM Length L Ch R = 1 ,18056   ,431,431,431
BEGIN DESCRIPTION:
CANEY CREEK 33.0
END DESCRIPTION:
XS GIS Cut Line= 3
      3803749.21     10528864.18       3803061.7     10528593.34
       3802617.4     10528725.24
#Sta/Elev= 30
  4473.1  409.65  4515.7  405.79  4552.7   400.2  4558.7  397.95  4623.1  387.89
  4661.1  379.09  4690.8  375.99  4715.2  369.96    4745  366.44  4752.1  363.17
  4762.9  363.44  4774.7  360.08  4799.1  357.06  4823.5  351.58  4877.7  346.26
  4924.1  338.83  4977.8  339.78    4983  334.99  4985.7  334.49    4989  334.99
  5015.7   339.9  5053.1   345.7  5075.3  351.49    5139  360.47  5224.7  364.55
  5318.3  364.36  5395.5  364.18  5526.7  366.87  5631.5  368.32  5675.5  370.75
#Mann= 5 ,-1 , 0
  4473.1     .16       0    4983     .07       0    4989     .16       0
  5318.3     .05       0  5526.7     .16       0
Bank Sta=4977.8,5015.7
XS Rating Curve= 0 ,0
Exp/Cntr=0.3,0.1

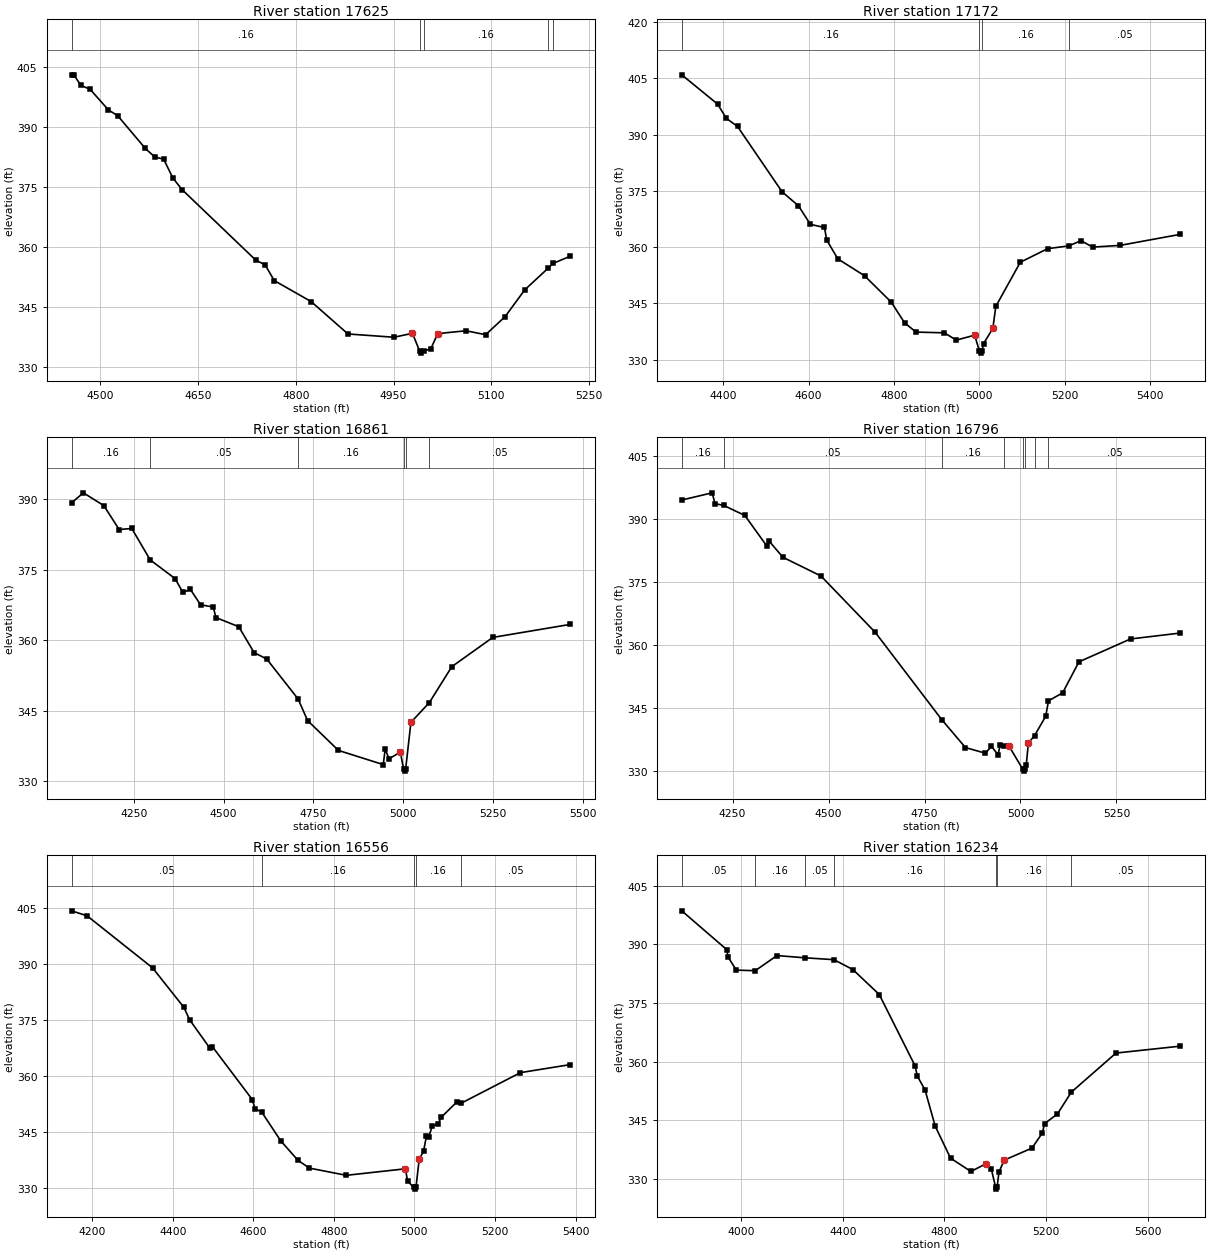
Type RM Length L Ch R = 1 ,17625   ,453,453,453
BEGIN DESCRIPTION:
CANEY CREEK 32.0
END DESCRIPTION:
XS GIS Cut Line= 3
      3803799.61     10528710.19      3803399.61     10528310.19
      3803199.59     10528310.19
#Sta/Elev= 30
  4455.7  402.99  4459.2  402.99  4469.8  400.35    4484  399.39  4512.3   394.2
  4526.4  392.78  4568.8   384.6    4583  382.49  4597.1  381.88  4611.3  377.16
  4625.4  374.27  4738.5  356.64  4752.7   355.5  4766.8  351.54  4823.4   346.3
    4880  338.19  4950.7  337.37    4979  338.36  4990.1   333.9  4992.8   333.4
  4996.1   333.9  5007.2  334.48  5017.8  338.28  5061.4  338.99  5091.4  338.01
  5121.4  342.55  5151.4  349.22  5187.6  354.68  5194.7  355.82  5221.4  357.64
#Mann= 5 ,-1 , 0
  4455.7     .16       0  4990.1     .07       0  4996.1     .16       0
  5187.6     .05       0  5194.7     .16       0
Bank Sta=4979,5017.8
XS Rating Curve= 0 ,0
Exp/Cntr=0.3,0.1

Type RM Length L Ch R = 1 ,17172   ,311,311,311
BEGIN DESCRIPTION:
CANEY CREEK 31.0
END DESCRIPTION:
XS GIS Cut Line= 3
      3803901.96     10528690.53      3803721.42      10528086.4
      3803381.13     10527669.73
#Sta/Elev= 30
  4302.8  405.95  4386.7  398.15  4407.5  394.33  4433.4  392.19    4538  374.75
  4576.3  371.03  4604.2  366.09  4637.1  365.26  4642.6  361.87  4668.5  356.89
  4731.1  352.39  4793.7  345.35    4825  339.82  4851.7  337.38    4918  337.18
    4946  335.24    4989  336.55  5000.4  332.27  5003.1  331.77  5006.4  332.27
  5009.8  334.31  5031.7  338.35  5038.6  344.23    5096  355.99  5159.9  359.61
  5209.6  360.36  5238.2  361.75  5265.4  360.03  5329.3  360.48  5471.3  363.44
#Mann= 4 ,-1 , 0
  4302.8     .16       0  5000.4     .07       0  5006.4     .16       0
  5209.6     .05       0
Bank Sta=4989,5031.7
XS Rating Curve= 0 ,0
Exp/Cntr=0.3,0.1

Type RM Length L Ch R = 1 ,16861   ,65,65,65
BEGIN DESCRIPTION:
Mapping XS 9b09b764
END DESCRIPTION:
XS GIS Cut Line= 4
      3804523.37      10528513.2      3803998.35      10528048.6
      3803871.27     10527742.35      3803575.99     10527544.81
#Sta/Elev= 30
  4076.9  389.26  4109.7  391.37  4166.6  388.65  4209.2  383.57  4244.4  383.79
  4295.7   377.1  4364.8  373.14  4386.6  370.19  4407.5  370.83  4435.9  367.56
    4471   367.1  4478.6  364.85  4542.1   362.9  4584.8   357.4  4619.9  356.04
  4707.2  347.54  4733.7  342.94  4819.6   336.6  4944.2  333.59  4949.6  336.88
  4960.3  334.83  4991.9  336.24  5000.6   332.7  5003.4   332.2  5006.6   332.7
  5021.2  342.57  5072.5  346.77    5135  354.41  5249.1  360.63  5464.8   363.4
#Mann= 6 ,-1 , 0
  4076.9     .16       0  4295.7     .05       0  4707.2     .16       0
  5000.6     .07       0  5006.6     .16       0  5072.5     .05       0
Bank Sta=4991.9,5021.2
XS Rating Curve= 0 ,0
Exp/Cntr=0.3,0.1

Type RM Length L Ch R = 1 ,16796   ,240,240,240
BEGIN DESCRIPTION:
CANEY CREEK 30.0
END DESCRIPTION:
XS GIS Cut Line= 4
      3804567.12     10528454.87      3804050.44     10527981.94
      3803940.02     10527752.77      3803694.37     10527511.28
#Sta/Elev= 30
  4117.5  394.42  4196.7  396.13  4204.1  393.56  4227.1  393.12  4281.8  390.75
  4338.5  383.56  4345.3  384.63  4381.1   380.8  4480.2  376.35  4621.5  362.96
  4794.7  342.21  4856.6  335.55  4908.7  334.21  4924.4  335.87  4941.5  333.83
  4947.1  336.19  4956.8  335.88  4969.7  335.96  5005.6  330.45  5008.3  329.95
  5011.6  330.45  5014.9  331.31  5020.5  336.63  5036.6   338.4  5065.7  342.99
  5072.9  346.66  5109.8  348.57  5152.3  355.94  5286.6  361.38  5416.8  362.79
#Mann= 8 ,-1 , 0
  4117.5     .16       0  4227.1     .05       0  4794.7     .16       0
  4956.8     .05       0  5005.6     .03       0  5011.6     .05       0
  5036.6     .16       0  5072.9     .05       0
Bank Sta=4969.7,5020.5
XS Rating Curve= 0 ,0
Exp/Cntr=0.3,0.1

Type RM Length L Ch R = 1 ,16556   ,322,322,322
BEGIN DESCRIPTION:
Mapping XS e60f63ce
END DESCRIPTION:
XS GIS Cut Line= 3
       3804704.6     10528219.43      3804171.27     10527659.02
      3803746.31     10527471.54
#Sta/Elev= 30
  4148.9  404.24  4187.4   402.9    4350  388.94  4427.7  378.36  4441.8  375.05
  4491.5  367.53  4498.4  367.83  4597.5  353.64  4604.4  351.17  4620.8  350.31
  4668.3  342.56  4710.8  337.37  4739.1  335.28  4830.9  333.34  4977.5  335.09
    4983  331.82  4997.8  330.14  5000.6  329.64  5003.8  330.14  5011.8  337.59
  5022.7  339.82  5029.6  343.77  5035.1  343.58  5044.6  346.58  5058.4  347.02
  5066.4  348.88  5105.1  352.99  5114.9  352.61  5263.2  360.87    5387  363.02
#Mann= 5 ,-1 , 0
  4148.9     .05       0  4620.8     .16       0  4997.8     .07       0
  5003.8     .16       0  5114.9     .05       0
Bank Sta=4977.5,5011.8
XS Rating Curve= 0 ,0
Exp/Cntr=0.3,0.1

Type RM Length L Ch R = 1 ,16234   ,399,399,399
BEGIN DESCRIPTION:
CANEY CREEK 29.0
END DESCRIPTION:
XS GIS Cut Line= 3
      3805520.06     10527169.72       3804811.7      10527398.9
      3803596.38     10527454.46
#Sta/Elev= 30
    3767  398.57    3944  388.65  3949.3  386.76  3981.3  383.42  4055.9  383.27
  4141.4  387.14  4250.5  386.57  4365.5  386.09  4440.1  383.55  4543.6  377.19
  4683.8  359.04  4693.8  356.29  4723.8  352.77  4763.9  343.49  4823.9  335.38
    4904  331.97  4964.1  333.97  4984.1  332.62  5001.1  327.96  5003.9  327.46
  5007.1  327.96  5014.1  331.71  5034.1  334.84  5144.3  337.95  5184.3  341.75
  5194.3  344.22  5244.4  346.68  5298.8  352.24  5474.6  362.23  5728.1     364
#Mann= 7 ,-1 , 0
    3767     .05       0  4055.9     .16       0  4250.5     .05       0
  4365.5     .16       0  5001.1     .07       0  5007.1     .16       0
  5298.8     .05       0
Bank Sta=4964.1,5034.1
XS Rating Curve= 0 ,0
Exp/Cntr=0.3,0.1

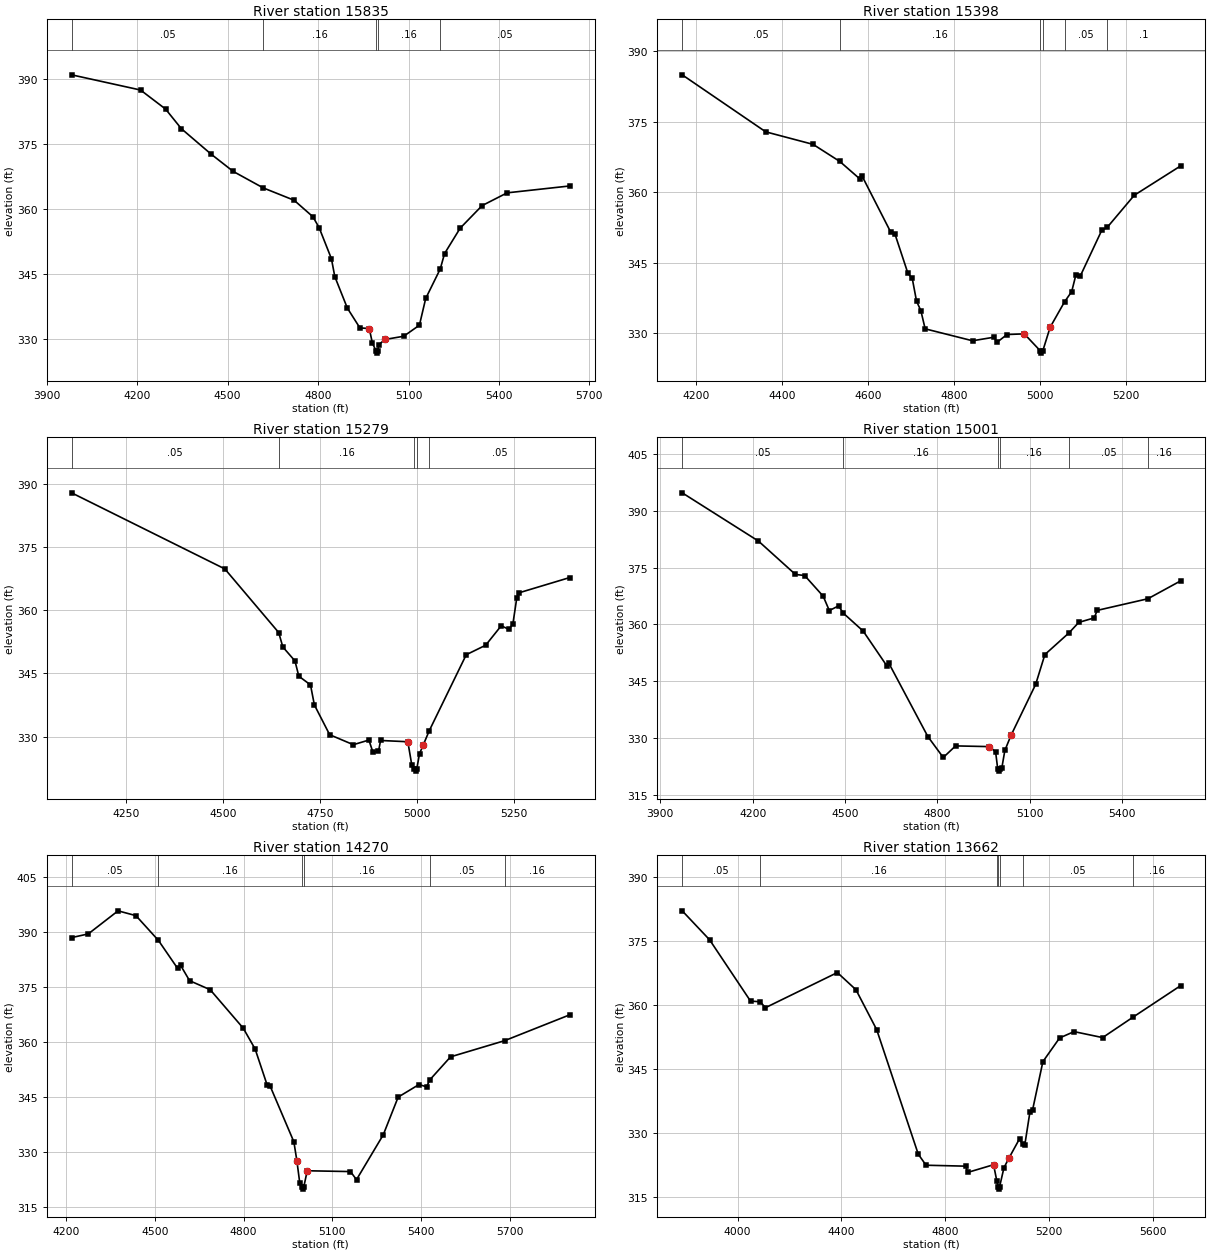
Type RM Length L Ch R = 1 ,15835   ,437,437,437
BEGIN DESCRIPTION:
CANEY CREEK 28.0
END DESCRIPTION:
XS GIS Cut Line= 2
      3805179.73     10526808.63      3803589.45     10527260.02
#Sta/Elev= 30
  3982.2  390.89    4211  387.38  4294.1  382.98  4346.2  378.47  4445.3  372.57
  4518.3   368.6  4617.7   364.8  4720.4  361.94  4782.7  358.14  4803.5  355.61
  4844.2  348.45  4855.5  344.31  4897.1  337.04  4938.7  332.48  4969.9  332.32
  4980.2  328.95  4992.4  327.15  4995.2  326.65  4998.4  327.15    5001  328.57
  5021.8   329.8  5084.2  330.55  5136.2   333.1    5157  339.26  5205.3  346.08
  5219.6  349.63  5271.3  355.49  5344.1   360.7  5427.2  363.65  5635.3  365.24
#Mann= 5 ,-1 , 0
  3982.2     .05       0  4617.7     .16       0  4992.4     .07       0
  4998.4     .16       0  5205.3     .05       0
Bank Sta=4969.9,5021.8
XS Rating Curve= 0 ,0
Exp/Cntr=0.3,0.1

Type RM Length L Ch R = 1 ,15398   ,119,119,119
BEGIN DESCRIPTION:
CANEY CREEK 27.0
END DESCRIPTION:
XS GIS Cut Line= 2
      3804873.32     10526659.02      3803717.11     10526731.94
#Sta/Elev= 30
  4167.7  384.99  4361.8  372.86    4472  370.19  4534.2  366.55  4580.3  362.87
  4585.3  363.55  4652.4  351.53  4662.4  351.08  4692.4  342.77  4702.5  341.68
  4712.5  336.82  4722.5  334.82  4732.5  330.94  4842.7   328.4  4892.8  329.16
  4899.5  328.07  4922.9  329.73    4963  329.87  5000.1  326.27  5002.8  325.77
  5006.1  326.27  5023.1  331.27  5056.5  336.67  5073.2  338.86  5083.2   342.5
  5093.2  342.17  5143.3  351.94  5155.8  352.53  5218.7  359.36  5326.2  365.59
#Mann= 6 ,-1 , 0
  4167.7     .05       0  4534.2     .16       0  5000.1     .07       0
  5006.1     .16       0  5056.5     .05       0  5155.8      .1       0
Bank Sta=4963,5023.1
XS Rating Curve= 0 ,0
Exp/Cntr=0.3,0.1

Type RM Length L Ch R = 1 ,15279   ,278,278,278
BEGIN DESCRIPTION:
Mapping XS a3856494
END DESCRIPTION:
XS GIS Cut Line= 2
       3804973.3     10526529.86       3803693.4       10526636.
#Sta/Elev= 30
  4109.8  387.81  4504.8  369.76  4643.6  354.67  4654.3  351.24  4685.5  347.94
  4695.5  344.31  4725.6  342.25  4735.6  337.49    4775  330.43    4836  328.06
  4876.1  329.16  4886.2  326.36  4900.8  326.45  4906.2  329.06  4976.5  328.76
  4986.5  323.33  4993.5  322.29  4996.3  321.79  4999.5  322.29  5006.6  325.93
  5016.4  328.04  5031.6  331.36    5127   349.4  5177.1  351.66  5217.3  356.28
  5237.4  355.39  5247.4  356.81  5257.4  362.95  5262.9  364.09  5394.1  367.72
#Mann= 5 ,-1 , 0
  4109.8     .05       0  4643.6     .16       0  4993.5     .07       0
  4999.5     .16       0  5031.6     .05       0
Bank Sta=4976.5,5016.4
XS Rating Curve= 0 ,0
Exp/Cntr=0.3,0.1

Type RM Length L Ch R = 1 ,15001   ,731,731,731
BEGIN DESCRIPTION:
CANEY CREEK 26.0
END DESCRIPTION:
XS GIS Cut Line= 2
      3805117.24     10526329.46       3803499.2     10526343.34
#Sta/Elev= 30
  3971.3  394.72  4218.9  381.98  4338.9  373.18  4368.9  372.89    4429  367.44
    4449  363.64    4479  364.88  4494.5  362.95    4559  358.22  4636.6  348.95
  4641.6  349.85    4769  330.38    4819  324.86    4859  327.92    4969  327.73
    4989  326.32    4996  321.76  4998.7  321.26    5002  321.76    5009  322.01
    5019  326.72    5039   330.7    5119  344.15    5149  352.03  5227.5  357.77
    5259  360.52    5309   361.7    5319  363.69  5483.5  366.76  5589.4  371.46
#Mann= 6 ,-1 , 0
  3971.3     .05       0  4494.5     .16       0    4996     .07       0
    5002     .16       0  5227.5     .05       0  5483.5     .16       0
Bank Sta=4969,5039
XS Rating Curve= 0 ,0
Exp/Cntr=0.3,0.1

Type RM Length L Ch R = 1 ,14270   ,608,608,608
BEGIN DESCRIPTION:
CANEY CREEK 25.0
END DESCRIPTION:
XS GIS Cut Line= 2
      3805075.63     10525933.63      3803403.34     10525725.46
#Sta/Elev= 30
  4218.3  388.56  4274.8  389.57  4375.5  395.88    4436  394.56  4512.1  387.78
  4577.1  380.12  4587.1  380.96  4617.4  376.78  4687.1  374.31  4798.8   363.8
  4839.1  358.09  4879.4  348.33  4889.5  348.02  4970.1  332.72  4980.2  327.58
  4990.2  321.36  4997.3  320.29  5000.1  319.79  5003.3  320.29  5015.3  324.81
  5161.5  324.59  5181.9  322.38  5272.4  334.64  5322.8  344.95  5393.3  348.39
  5419.2  347.75    5429  349.59    5500  355.96  5682.9  360.38  5903.5  367.46
#Mann= 6 ,-1 , 0
  4218.3     .05       0  4512.1     .16       0  4997.3     .07       0
  5003.3     .16       0    5429     .05       0  5682.9     .16       0
Bank Sta=4980.2,5015.3
XS Rating Curve= 0 ,0
Exp/Cntr=0.3,0.1

Type RM Length L Ch R = 1 ,13662   ,561,561,561
BEGIN DESCRIPTION:
CANEY CREEK 24.0
END DESCRIPTION:
XS GIS Cut Line= 3
      3805332.51     10525197.51       3804686.7     10525343.34
      3803429.75     10525378.07
#Sta/Elev= 30
  3786.8     382  3892.3  375.22  4049.9  360.89    4087  360.73  4107.6  359.35
  4384.4  367.56    4456  363.55    4536   354.2  4696.1  325.08  4726.1   322.5
  4879.5  322.28  4886.1  320.81  4986.2  322.62  4998.8  318.79  5003.2  317.41
  5005.9  316.91  5009.2  317.41  5026.2  321.92  5046.2  324.26  5086.2  328.68
  5097.8   327.4  5106.2  327.14  5126.2  334.93  5136.2  335.36  5176.2  346.73
  5240.6  352.27  5296.3  353.75  5406.3  352.35  5522.1  357.08  5706.3  364.48
#Mann= 7 ,-1 , 0
  3786.8     .05       0    4087     .16       0  4998.8     .12       0
  5003.2     .07       0  5009.2     .12       0  5097.8     .05       0
  5522.1     .16       0
Bank Sta=4986.2,5046.2
XS Rating Curve= 0 ,0
Exp/Cntr=0.3,0.1

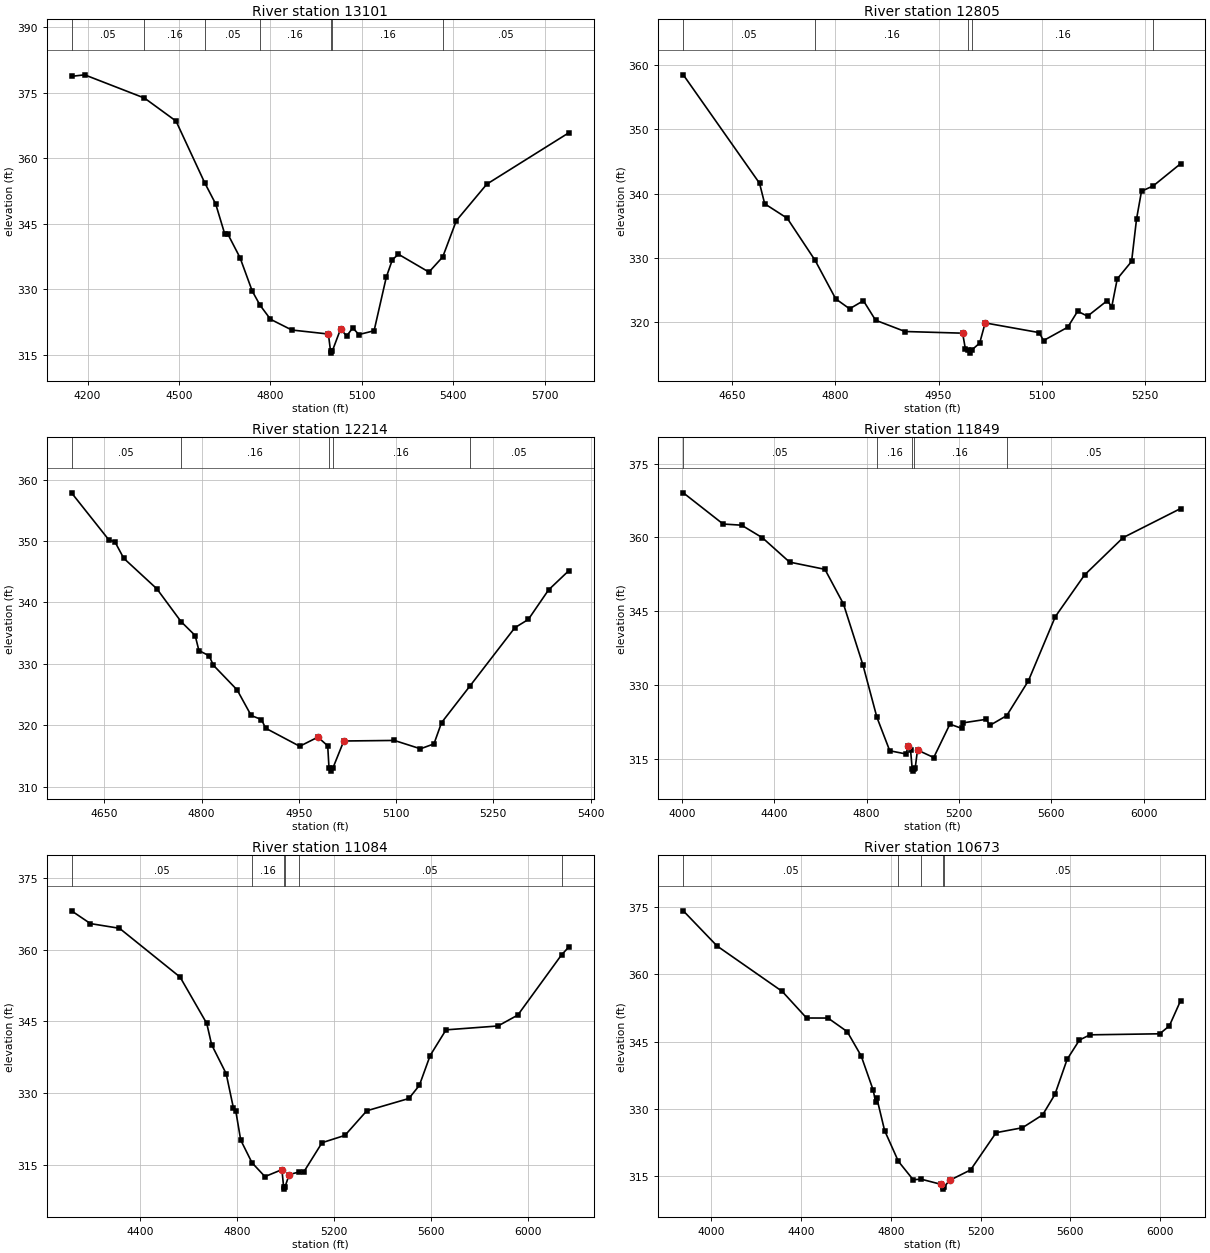
Type RM Length L Ch R = 1 ,13101   ,296,296,296
BEGIN DESCRIPTION:
CANEY CREEK 23.0
END DESCRIPTION:
XS GIS Cut Line= 2
      3805082.57     10524989.18      3803450.57     10524989.18
#Sta/Elev= 30
  4147.3  378.78  4190.3  379.13  4386.7  373.81  4490.3  368.54  4584.5   354.4
  4620.3   349.6  4650.3  342.67  4660.3  342.68  4700.3  337.28  4740.3  329.65
  4765.8  326.42  4800.3  323.18  4870.3  320.72  4990.3   319.8  4997.3  315.93
    5000  315.43  5003.3  315.93  5030.3  320.94  5050.3  319.36  5070.3   321.2
  5090.3  319.68  5140.3  320.55  5180.3   332.8  5200.3  336.82  5220.3  338.06
  5320.3  333.98  5365.6  337.45  5410.3  345.76  5510.3  354.11  5779.3  365.86
#Mann= 7 ,-1 , 0
  4147.3     .05       0  4386.7     .16       0  4584.5     .05       0
  4765.8     .16       0  4997.3     .07       0  5003.3     .16       0
  5365.6     .05       0
Bank Sta=4990.3,5030.3
XS Rating Curve= 0 ,0
Exp/Cntr=0.3,0.1

Type RM Length L Ch R = 1 ,12805   ,591,591,591
BEGIN DESCRIPTION:
CANEY CREEK 22.0
END DESCRIPTION:
XS GIS Cut Line= 3
      3804649.62     10524660.19      3804249.61     10524710.19
       3803999.6     10524510.18
#Sta/Elev= 30
  4578.7   358.5  4689.6   341.6  4697.1   338.4  4729.9  336.14  4770.5  329.57
  4800.4  323.58  4820.6  322.03  4840.7  323.29  4858.4  320.25  4901.2  318.49
    4985  318.23    4989  315.78  4992.4  315.62  4995.2  315.12  4998.4  315.62
  5009.8  316.68  5017.8  319.83  5096.3  318.32  5102.7  317.08  5137.9  319.16
  5152.3  321.65  5166.7  320.88  5195.5  323.31  5201.9  322.33  5209.9  326.69
  5230.8  329.42    5238  336.04  5245.2  340.36  5262.3  341.19    5302  344.64
#Mann= 5 ,-1 , 0
  4578.7     .05       0  4770.5     .16       0  4992.4     .07       0
  4998.4     .16       0  5262.3     .05       0
Bank Sta=4985,5017.8
XS Rating Curve= 0 ,0
Exp/Cntr=0.3,0.1

Type RM Length L Ch R = 1 ,12214   ,365,365,365
BEGIN DESCRIPTION:
CANEY CREEK 21.0
END DESCRIPTION:
XS GIS Cut Line= 3
      3804649.59     10524460.18      3804299.61     10524260.19
       3803949.6     10524360.19
#Sta/Elev= 30
  4599.4  357.86    4657  350.19  4666.3  349.88    4680  347.19  4731.1  342.21
  4768.4  336.87  4790.1  334.61  4795.9  332.16  4811.7   331.3  4818.2  329.77
  4854.9  325.74  4876.5  321.58  4892.4  320.91  4898.8  319.51  4951.4  316.56
  4979.5  318.05  4994.6  316.63  4996.6  313.01  4999.4  312.51  5002.6  313.01
  5019.4  317.42  5097.4  317.51  5137.7  316.15  5158.5  316.95  5170.2  320.41
  5213.8  326.35  5283.3  335.88  5304.1  337.23  5335.3  342.04  5366.5  345.17
#Mann= 5 ,-1 , 0
  4599.4     .05       0  4768.4     .16       0  4996.6     .07       0
  5002.6     .16       0  5213.8     .05       0
Bank Sta=4979.5,5019.4
XS Rating Curve= 0 ,0
Exp/Cntr=0.3,0.1

Type RM Length L Ch R = 1 ,11849   ,765,765,765
BEGIN DESCRIPTION:
CANEY CREEK 20.0
END DESCRIPTION:
XS GIS Cut Line= 3
      3805311.68     10523905.84      3804110.31     10523982.23
      3803290.83     10524461.42
#Sta/Elev= 30
    4006  369.06  4178.4  362.72  4258.6  362.48  4348.8  359.92  4466.2  354.98
  4619.3  353.51  4699.5  346.47  4784.1  334.03  4844.3  323.44  4899.9  316.64
    4970  315.99    4980  317.56  4990.1  316.75  4997.1     313  4999.8   312.5
  5003.1     313  5010.1  313.13  5020.1  316.79  5090.3  315.26  5160.4  322.05
  5212.7  321.17    5216   322.3  5317.7  323.03  5333.4   321.8  5406.4  323.78
  5500.2  330.85  5616.9   343.9  5743.5  352.37  5910.2  359.95  6159.1  365.86
#Mann= 5 ,-1 , 0
    4006     .05       0  4844.3     .16       0  4997.1     .07       0
  5003.1     .16       0  5406.4     .05       0
Bank Sta=4980,5020.1
XS Rating Curve= 0 ,0
Exp/Cntr=0.3,0.1

Type RM Length L Ch R = 1 ,11084   ,411,411,411
BEGIN DESCRIPTION:
CANEY CREEK 19.0
END DESCRIPTION:
XS GIS Cut Line= 3
      3805207.52     10523530.84       3803999.2     10523489.18
      3803173.66     10523662.61
#Sta/Elev= 30
  4115.9  368.12  4193.9  365.45  4313.9  364.47  4564.1  354.27  4674.1  344.59
  4694.2  340.15  4754.2   334.1  4784.2  326.91  4794.2  326.22  4814.2  320.23
  4860.9  315.48  4914.3  312.59  4984.3  314.04  4991.3  310.47  4994.1  309.97
  4997.3  310.47  5014.3     313    5053  313.53  5074.4  313.54    5150  319.67
  5244.5   321.2  5334.7  326.34  5508.5  328.91  5551.6  331.64  5596.3  337.89
  5661.7  343.25  5876.3  344.06  5958.1  346.34  6138.5  358.91  6168.5  360.56
#Mann= 6 ,-1 , 0
  4115.9     .05       0  4860.9     .16       0  4991.3     .07       0
  4997.3     .16       0    5053     .05       0  6138.5     .16       0
Bank Sta=4984.3,5014.3
XS Rating Curve= 0 ,0
Exp/Cntr=0.3,0.1

Type RM Length L Ch R = 1 ,10673   ,586,586,586
BEGIN DESCRIPTION:
CANEY CREEK 18.0
END DESCRIPTION:
XS GIS Cut Line= 4
      3805325.61     10523426.69      3804540.86     10523141.96
      3804033.92     10523204.46      3803223.01     10523516.34
#Sta/Elev= 30
  3876.1  374.16  4026.6  366.32  4316.8   356.2    4425  350.28  4520.5  350.27
  4605.9  347.25  4668.2  341.84  4722.2  334.14  4732.3  331.51  4737.3  332.56
  4772.6   325.2  4833.8  318.35  4899.7  314.25  4935.9  314.36  5024.5  313.21
  5031.6  312.65  5034.3  312.15  5037.6  312.65    5062   314.1  5155.5  316.43
  5269.2  324.73  5386.3  325.83  5476.3   328.7  5530.9  333.24  5585.5  341.08
  5640.2  345.37    5687  346.53  5997.7  346.76  6040.6  348.52  6090.5  354.12
#Mann= 5 ,-1 , 0
  3876.1     .05       0  4833.8     .16       0  4935.9     .05       0
  5031.6     .03       0  5037.6     .05       0
Bank Sta=5024.5,5062
XS Rating Curve= 0 ,0
Exp/Cntr=0.3,0.1