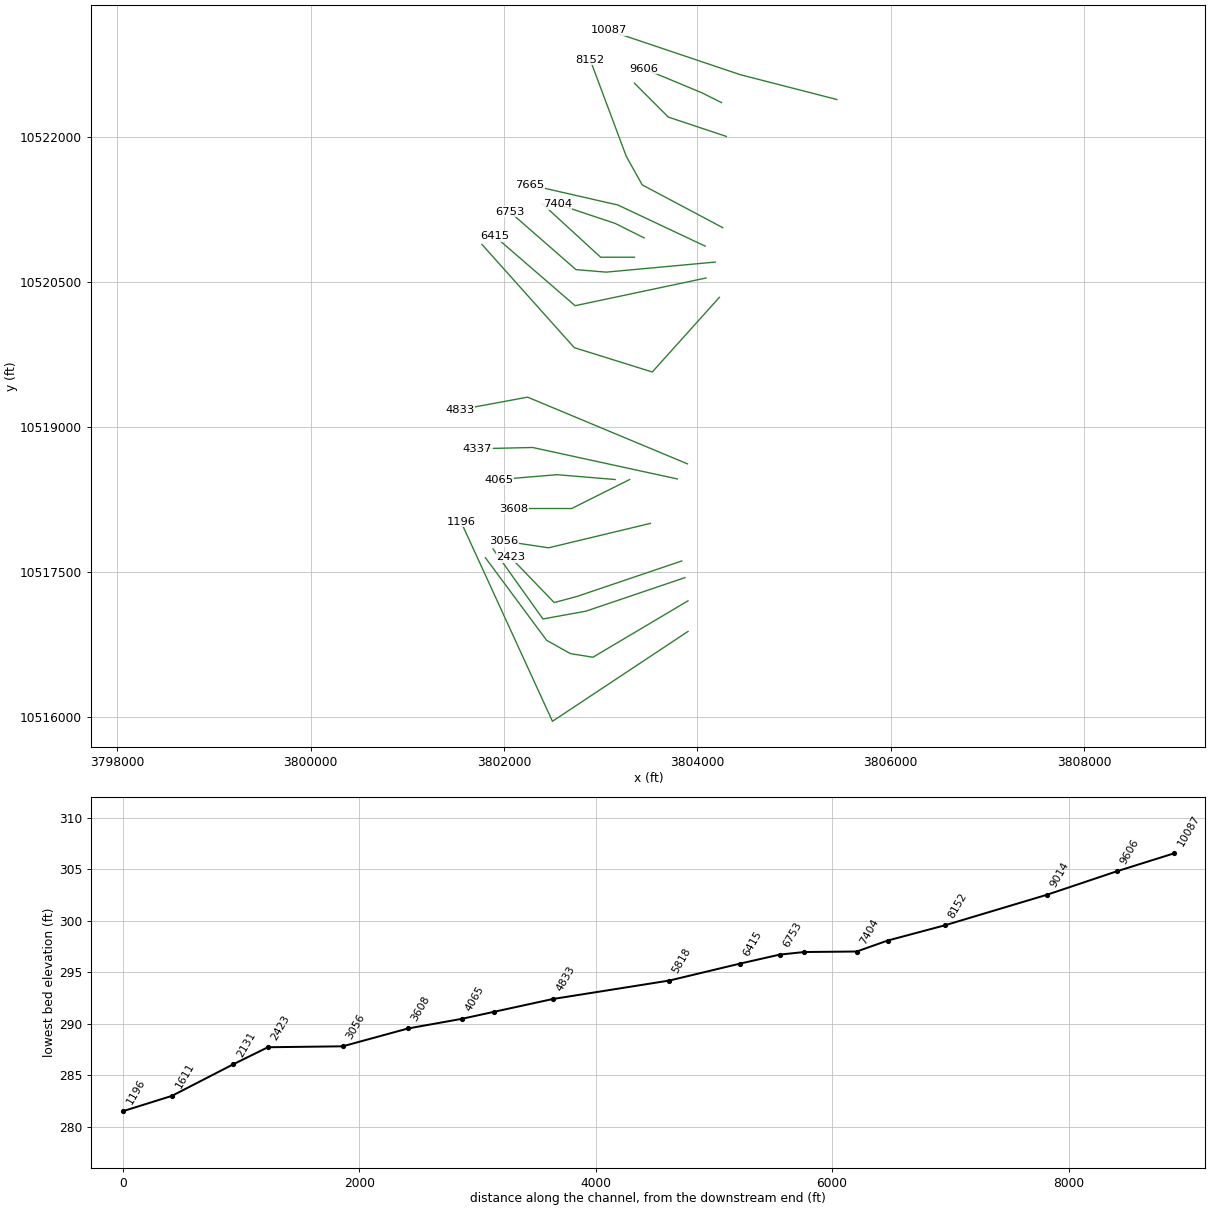
HEC-RAS study CANEY CREEK.prj: CANEY CREEK Base Level Engineering

--- CANEY CREEK.g01 (geometry) --- (continued)

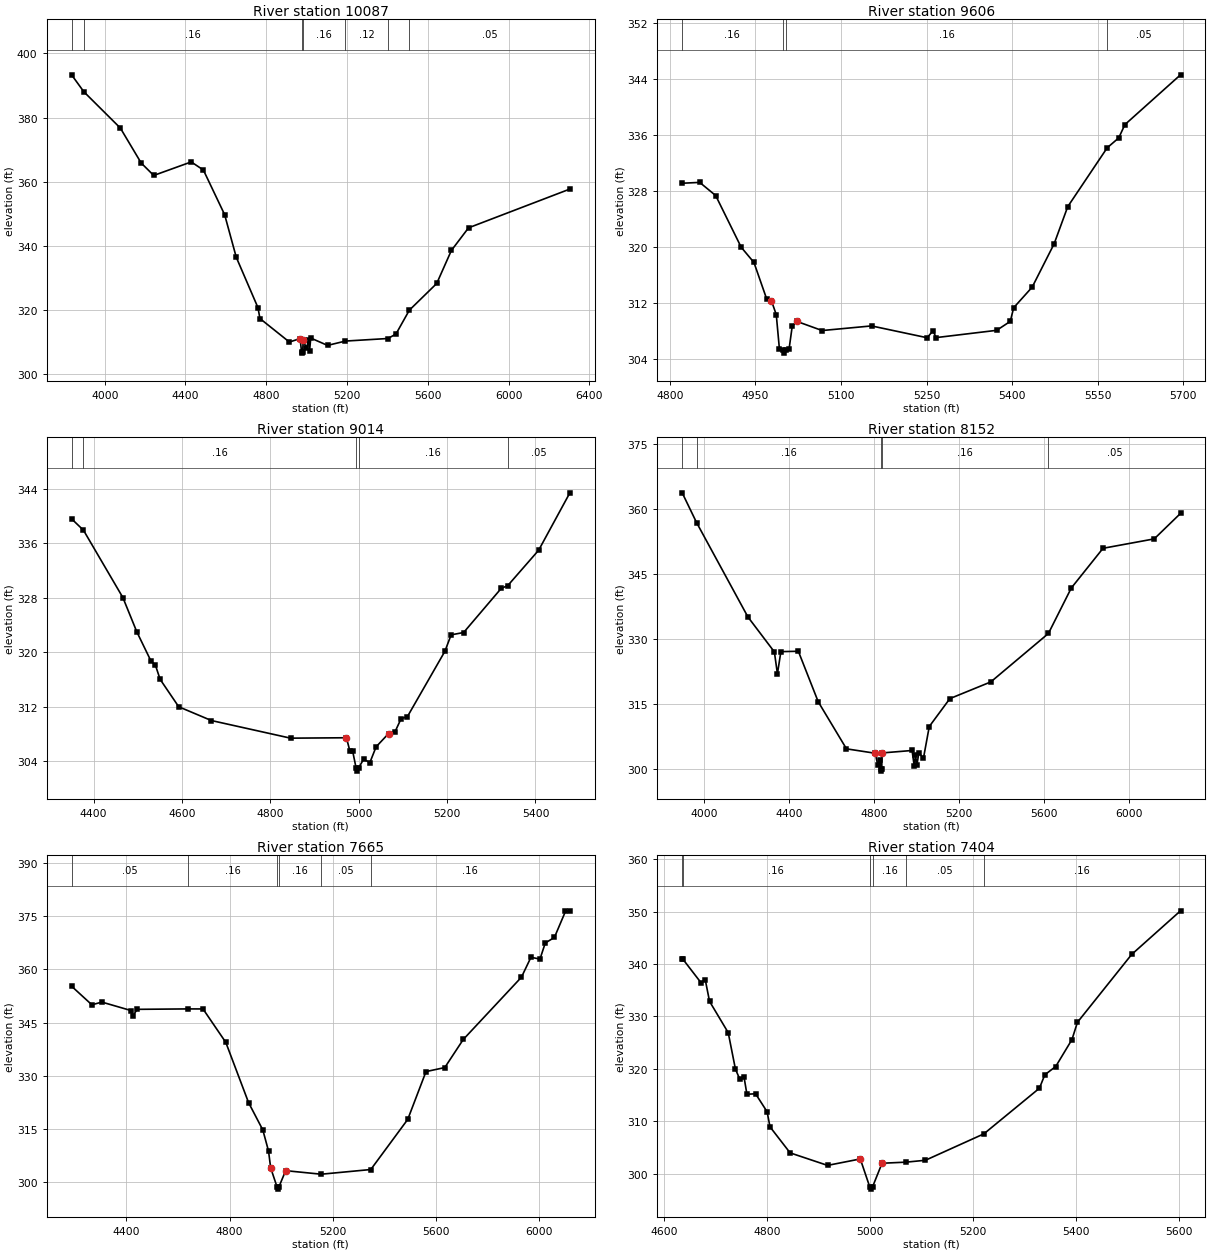
Type RM Length L Ch R = 1 ,10087   ,481,481,481
BEGIN DESCRIPTION:
CANEY CREEK 17.0
END DESCRIPTION:
XS GIS Cut Line= 3
      3805443.61     10522391.96      3804443.64      10522648.9
      3803083.53      10523106.9
#Sta/Elev= 30
    3836  393.31  3896.6  388.04  4077.6  376.71  4180.8  365.81  4242.8  361.94
  4428.6  366.16  4488.7  363.63  4593.8  349.74  4651.6  336.42    4759  320.72
  4768.7  317.34  4914.6  310.01  4967.7  311.08  4974.6  307.05  4977.3  306.55
  4980.6  307.05  4982.8  310.55  4999.3  308.03    5009  310.63  5014.3  307.14
  5020.4  311.25  5103.5  308.96  5192.1  310.31  5402.8  311.11  5442.5  312.52
  5508.5  319.93  5644.2  328.27  5716.8  338.56  5801.7  345.61  6303.6   357.7
#Mann= 7 ,-1 , 0
    3836     .05       0  3896.6     .16       0  4974.6     .07       0
  4980.6     .16       0  5192.1     .12       0  5402.8     .16       0
  5508.5     .05       0
Bank Sta=4967.7,4982.8
XS Rating Curve= 0 ,0
Exp/Cntr=0.3,0.1

Type RM Length L Ch R = 1 ,9606    ,592,592,592
BEGIN DESCRIPTION:
CANEY CREEK 16.0
END DESCRIPTION:
XS GIS Cut Line= 3
      3804249.61     10522360.19      3804049.61     10522460.19
      3803449.62     10522710.18
#Sta/Elev= 30
  4821.5  329.11  4852.2  329.23  4880.2  327.35  4924.9  319.96  4947.3  317.78
  4969.6  312.56    4978  312.29  4986.4  310.33    4992  305.35  4997.4  305.32
  5000.1  304.82  5003.4  305.32  5008.8  305.37  5014.4  308.67  5022.7  309.35
  5066.8  308.05  5153.4  308.71  5250.9  307.02  5261.2  308.01  5266.7  307.04
  5372.8  308.08  5396.7  309.36  5402.6  311.31  5435.1  314.26  5473.6  320.46
  5497.4  325.76  5566.6  334.18  5586.8  335.59  5597.6  337.49  5695.1  344.61
#Mann= 4 ,-1 , 0
  4821.5     .16       0  4997.4     .07       0  5003.4     .16       0
  5566.6     .05       0
Bank Sta=4978,5022.7
XS Rating Curve= 0 ,0
Exp/Cntr=0.3,0.1

Type RM Length L Ch R = 1 ,9014    ,862,862,862
BEGIN DESCRIPTION:
CANEY CREEK 15.0
END DESCRIPTION:
XS GIS Cut Line= 3
      3804299.61     10522010.19      3803699.61     10522210.19
      3803349.63     10522560.17
#Sta/Elev= 30
  4350.4  339.58  4377.3  337.91  4466.4  328.03    4498  322.99  4529.6  318.76
  4540.1  318.09  4550.7  316.02  4592.8  311.99  4666.6  309.97  4845.8  307.38
  4972.3  307.44  4980.2  305.45  4986.4  305.45    4994  303.04  4996.7  302.54
    5000  303.04  5011.1  304.28  5025.3   303.8  5039.4  306.11  5067.7  308.06
  5081.9  308.28    5096  310.25  5110.1  310.53    5195  320.13  5209.1  322.55
  5237.4  322.89  5322.3  329.36  5337.4  329.79  5407.1  334.97  5477.8   343.4
#Mann= 5 ,-1 , 0
  4350.4      .1       0  4377.3     .16       0    4994     .07       0
    5000     .16       0  5337.4     .05       0
Bank Sta=4972.3,5067.7
XS Rating Curve= 0 ,0
Exp/Cntr=0.3,0.1

Type RM Length L Ch R = 1 ,8152    ,487,487,487
BEGIN DESCRIPTION:
CANEY CREEK 14.0
END DESCRIPTION:
XS GIS Cut Line= 4
      3804263.08     10521065.93      3803429.75     10521508.64
      3803264.82     10521803.78      3802891.55     10522802.05
#Sta/Elev= 30
  3895.4  363.75  3963.1  356.89  4205.1  335.12  4329.6  327.07    4344  322.01
  4360.3  327.13  4442.6  327.22  4536.2  315.57  4669.3  304.72    4805   303.7
  4816.5     301  4826.9  302.25  4829.6  300.08  4832.4  299.58  4835.6  300.08
  4836.3  303.77  4978.3  304.34  4988.5  300.76  4994.3  303.31  5001.2  301.01
  5010.2  303.81  5031.9  302.55  5059.4  309.87  5156.4   316.3  5349.2  320.15
  5620.6  331.32  5728.5  341.81  5877.9  350.96  6119.1  353.13  6242.9     359
#Mann= 5 ,-1 , 0
  3895.4     .05       0  3963.1     .16       0  4829.6     .07       0
  4835.6     .16       0  5620.6     .05       0
Bank Sta=4805,4836.3
XS Rating Curve= 0 ,0
Exp/Cntr=0.3,0.1

Type RM Length L Ch R = 1 ,7665    ,261,261,261
BEGIN DESCRIPTION:
CANEY CREEK 13.0
END DESCRIPTION:
XS GIS Cut Line= 3
      3804080.76     10520874.97      3803178.01      10521300.3
      3802266.55     10521508.64
#Sta/Elev= 30
    4187  355.23  4265.7     350  4304.6  350.76  4418.5  348.36    4424  346.76
  4441.3  348.72    4638  348.84  4696.8  348.83  4785.2  339.42  4873.6  322.44
  4928.9  314.74    4951   308.8  4959.2   304.1  4984.5  298.59  4987.2  298.09
  4990.5  298.59  5017.4  303.29  5155.4  302.29  5347.6  303.61    5491  317.73
  5561.8  331.19  5634.6  332.32  5706.4  340.24  5932.1  357.78  5968.9  363.38
  6003.9  362.87  6024.4   367.4  6059.9  368.97  6102.9  376.33  6119.9  376.46
#Mann= 6 ,-1 , 0
    4187     .05       0    4638     .16       0  4984.5     .07       0
  4990.5     .16       0  5155.4     .05       0  5347.6     .16       0
Bank Sta=4959.2,5017.4
XS Rating Curve= 0 ,0
Exp/Cntr=0.3,0.1

Type RM Length L Ch R = 1 ,7404    ,444,444,444
BEGIN DESCRIPTION:
CANEY CREEK 12.0
END DESCRIPTION:
XS GIS Cut Line= 3
      3803449.58      10520960.2      3803149.61     10521110.19
      3802549.64     10521310.18
#Sta/Elev= 30
  4635.7     341  4636.4     341    4672  336.46  4680.4  337.03  4688.8  332.87
  4725.1  326.89  4739.1  319.93  4747.5  318.03  4755.9  318.35  4761.4  315.14
  4778.2  315.23  4800.6   311.8  4806.2  308.92  4845.3  303.95    4918  301.56
  4981.6  302.79  4999.7  297.53  5002.4  297.03  5005.7  297.53  5023.8  301.97
  5070.7  302.18  5108.1  302.54  5221.6  307.58  5329.5  316.29    5340  318.86
  5361.1  320.43  5392.7  325.58  5403.3  328.87  5508.7  341.83  5603.5  350.15
#Mann= 6 ,-1 , 0
  4635.7     .05       0  4636.4     .16       0  4999.7     .07       0
  5005.7     .16       0  5070.7     .05       0  5221.6     .16       0
Bank Sta=4981.6,5023.8
XS Rating Curve= 0 ,0
Exp/Cntr=0.3,0.1

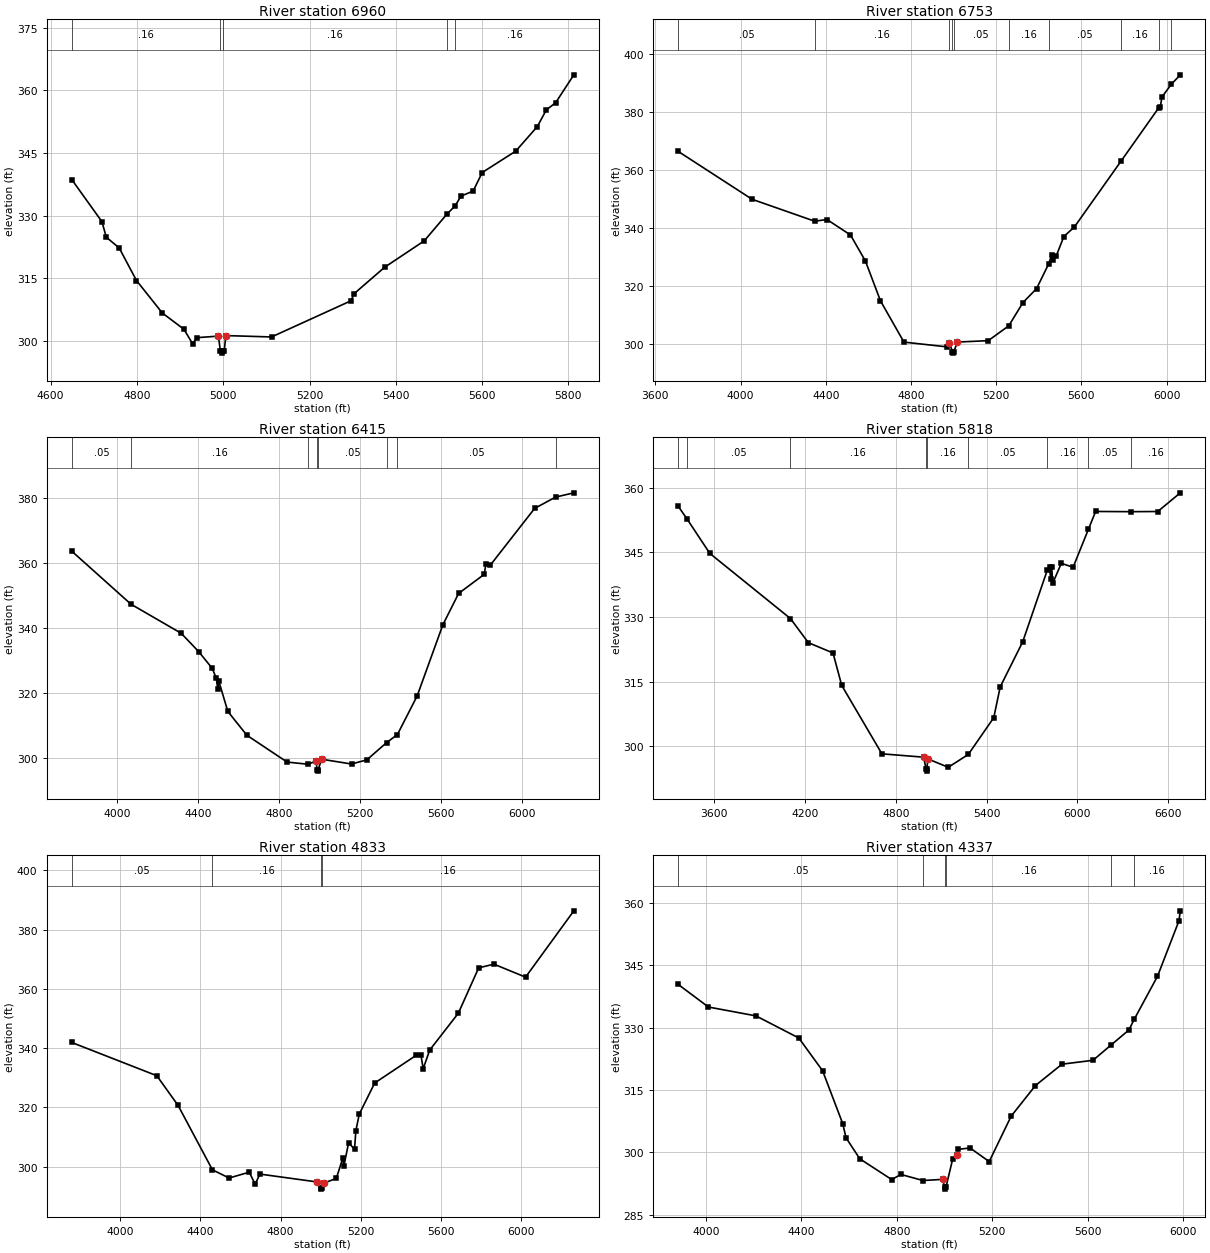
Type RM Length L Ch R = 1 ,6960    ,207,207,207
BEGIN DESCRIPTION:
CANEY CREEK 11.0
END DESCRIPTION:
XS GIS Cut Line= 3
      3803349.59     10520760.19      3802999.61     10520760.19
      3802399.62     10521310.17
#Sta/Elev= 30
  4648.9  338.63  4718.9  328.51  4728.9   324.8  4758.9  322.21  4798.9   314.4
  4858.9   306.6  4908.9  302.71  4928.9  299.24  4938.9  300.69  4988.9  301.06
  4993.4  297.48  4996.1  296.98  4999.4  297.48  5002.3  297.48    5006  301.19
    5112  300.86  5296.4  309.55  5303.2  311.22  5374.1  317.58    5466  323.92
  5518.5  330.32  5537.8  332.34  5551.1  334.65  5579.4  335.87  5600.4  340.32
  5678.1  345.45    5728  351.33    5749  355.34  5770.6  357.07  5812.8  363.76
#Mann= 5 ,-1 , 0
  4648.9     .16       0  4993.4     .07       0  4999.4     .16       0
  5518.5     .05       0  5537.8     .16       0
Bank Sta=4988.9,5006
XS Rating Curve= 0 ,0
Exp/Cntr=0.3,0.1

Type RM Length L Ch R = 1 ,6753    ,338,338,338
BEGIN DESCRIPTION:
CANEY CREEK 10.0
END DESCRIPTION:
XS GIS Cut Line= 4
      3804184.96     10520710.02      3803056.49     10520605.86
      3802743.99      10520631.9      3802058.19     10521230.89
#Sta/Elev= 30
  3707.2  366.48    4054  349.93  4347.8  342.35  4405.5  342.94    4516  337.58
  4586.3  328.55  4656.6  314.83    4767  300.54  4967.8  298.91  4979.2   300.4
  4994.9  297.23  4997.6  296.73  5000.9  297.23    5018  300.56  5162.8  301.04
  5258.9  306.16    5326  314.23  5389.6  319.04  5445.9  327.49  5460.8  330.64
  5467.5  328.87  5481.7  330.27  5517.8  337.05  5567.2  340.35  5785.6  363.05
  5963.9  381.63  5970.6  381.81  5978.2  385.28  6022.1  389.68  6064.6  392.97
#Mann= 10 ,-1 , 0
  3707.2     .05       0  4347.8     .16       0  4979.2     .05       0
  4994.9     .03       0  5000.9     .05       0  5258.9     .16       0
  5445.9     .05       0  5785.6     .16       0  5963.9     .05       0
  6022.1     .16       0
Bank Sta=4979.2,5018
XS Rating Curve= 0 ,0
Exp/Cntr=0.3,0.1

Type RM Length L Ch R = 1 ,6415    ,597,597,597
BEGIN DESCRIPTION:
CANEY CREEK 9.0
END DESCRIPTION:
XS GIS Cut Line= 3
      3804089.43     10520545.09      3802735.31     10520258.64
      3801903.26     10520978.01
#Sta/Elev= 30
  3774.7  363.56  4067.5  347.24  4316.2  338.28  4402.7  332.63  4469.6  327.49
    4490  324.38    4497  321.12  4502.2  323.56  4546.8  314.22  4641.1  306.89
  4839.9  298.64  4943.7  297.97    4984  298.96  4987.8  296.35  4990.6  295.85
  4993.8  296.35  5011.3  299.51  5158.8  298.04  5234.5  299.32  5332.2  304.62
  5385.8  307.11  5483.4  318.98  5610.7   340.9  5688.6  350.55  5815.8  356.45
  5823.5  359.74  5844.3  359.16  6064.8  376.73  6168.2   380.2  6258.7  381.52
#Mann= 8 ,-1 , 0
  3774.7     .05       0  4067.5     .16       0  4943.7     .05       0
  4987.8     .03       0  4993.8     .05       0  5332.2     .16       0
  5385.8     .05       0  6168.2     .16       0
Bank Sta=4984,5011.3
XS Rating Curve= 0 ,0
Exp/Cntr=0.3,0.1

Type RM Length L Ch R = 1 ,5818    ,985,985,985
BEGIN DESCRIPTION:
CANEY CREEK 8.0
END DESCRIPTION:
XS GIS Cut Line= 4
      3804228.33     10520345.41      3803533.92     10519572.87
      3802726.63     10519824.61      3801771.76     10520892.33
#Sta/Elev= 30
  3362.5  355.73  3420.8  352.78    3571  344.79  4103.8  329.65    4222  324.05
    4385  321.66  4442.5  314.12  4707.8  298.23  4983.6  297.45  4999.8  294.71
  5002.6  294.21  5005.8  294.71  5010.9  297.06  5146.2   295.1  5278.6  298.08
  5446.9  306.63  5489.5  313.78  5638.3  324.26  5800.2  340.87  5815.5  341.74
  5822.3  338.92  5829.8  341.54  5836.5  337.87  5893.3  342.49    5971  341.56
  6072.3   350.4  6119.8  354.53  6352.9  354.48  6530.3  354.52  6679.3  358.86
#Mann= 9 ,-1 , 0
  3362.5     .08       0  3420.8     .05       0  4103.8     .16       0
  4999.8     .07       0  5005.8     .16       0  5278.6     .05       0
  5800.2     .16       0  6072.3     .05       0  6352.9     .16       0
Bank Sta=4983.6,5010.9
XS Rating Curve= 0 ,0
Exp/Cntr=0.3,0.1

Type RM Length L Ch R = 1 ,4833    ,496,496,496
BEGIN DESCRIPTION:
CANEY CREEK 7.0
END DESCRIPTION:
XS GIS Cut Line= 3
      3803897.63     10518622.35      3802243.99     10519312.46
      3801542.78      10519182.6
#Sta/Elev= 30
  3758.4  341.93  4182.7  330.71  4288.9  320.67  4460.1  298.94  4543.3  296.17
    4644  298.14  4673.2  294.07    4697   297.5  4980.7  294.86  4999.4  292.92
  5002.1  292.42  5005.4  292.92  5015.4  294.45  5078.2  296.03  5110.6  302.87
  5116.1  300.27  5139.9  308.14  5169.1  305.83  5175.8  312.14  5192.9  317.76
  5269.8  328.25  5476.6  337.59  5500.4  337.76  5511.7  333.05  5544.2  339.37
  5686.9  351.79  5788.6  367.13  5864.8  368.37  6022.5  363.99  6263.4  386.38
#Mann= 4 ,-1 , 0
  3758.4     .05       0  4460.1     .16       0  4999.4     .07       0
  5005.4     .16       0
Bank Sta=4980.7,5015.4
XS Rating Curve= 0 ,0
Exp/Cntr=0.3,0.1

Type RM Length L Ch R = 1 ,4337    ,272,272,272
BEGIN DESCRIPTION:
CANEY CREEK 6.0
END DESCRIPTION:
XS GIS Cut Line= 3
      3803793.46      10518466.1      3802296.07     10518791.62
      3801723.89     10518778.62
#Sta/Elev= 30
  3883.5  340.43  4010.2     335  4209.3  332.87  4388.9  327.55  4488.6  319.67
  4573.1  306.93  4586.9  303.53  4644.7  298.47  4778.2  293.49  4817.1  294.71
  4909.5  293.25  4992.7  293.53  4999.9  291.68  5002.7  291.18  5005.9  291.68
  5033.6  298.32  5052.5  299.28  5057.6  300.75  5106.7  301.09  5187.1  297.81
  5279.2  308.75    5381  316.11  5492.3  321.25  5622.4  322.18    5697  325.82
  5772.4  329.46  5795.8  332.13  5892.5  342.39  5982.5  355.74  5988.2  358.15
#Mann= 6 ,-1 , 0
  3883.5     .05       0  4909.5     .16       0  4999.9     .07       0
  5005.9     .16       0    5697     .05       0  5795.8     .16       0
Bank Sta=4992.7,5052.5
XS Rating Curve= 0 ,0
Exp/Cntr=0.3,0.1

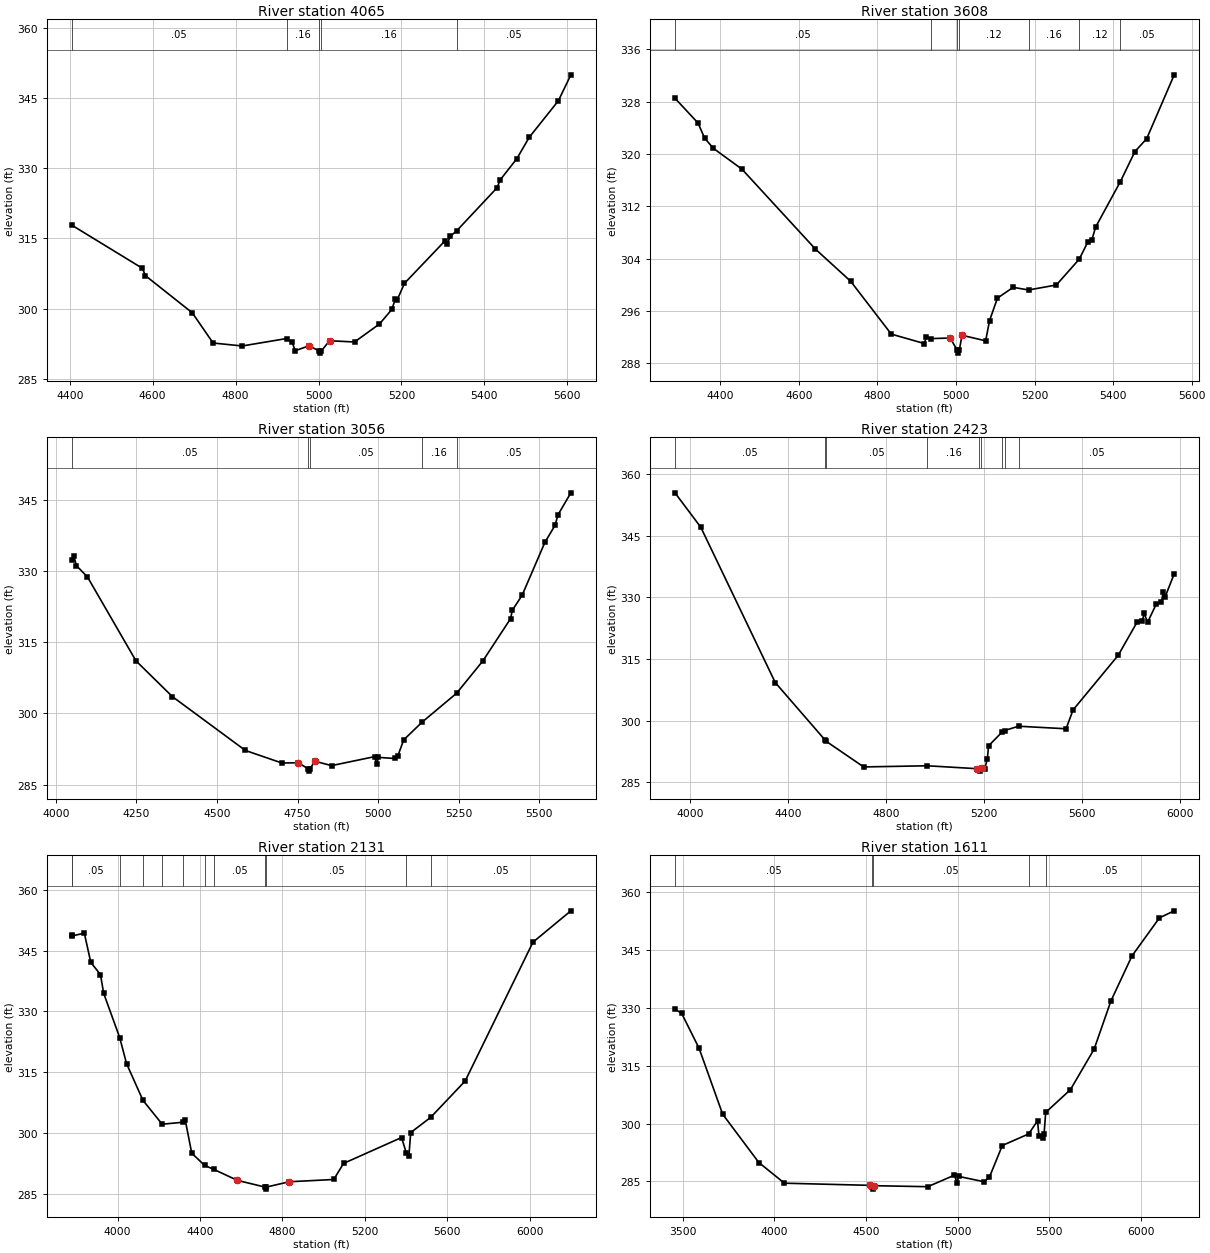
Type RM Length L Ch R = 1 ,4065    ,457,457,457
BEGIN DESCRIPTION:
CANEY CREEK 5.0
END DESCRIPTION:
XS GIS Cut Line= 3
      3803149.59     10518460.19      3802549.61     10518510.19
      3801949.65     10518460.19
#Sta/Elev= 30
  4404.5  317.87  4575.1  308.63  4582.6  307.05  4695.5  299.12  4745.7  292.66
  4815.9  292.03  4923.1  293.62  4936.3  292.82  4943.8  291.01  4976.5  292.06
  5001.1     291  5003.8   290.5  5007.1     291  5026.6  293.15  5086.8  292.88
    5147  296.73  5177.1  299.86  5184.7  301.98  5189.7  301.88  5207.3  305.42
  5305.1   314.5  5310.1  313.74  5317.6  315.46    5333  316.62  5430.5  325.83
  5438.1  327.52  5478.2  332.04  5508.3  336.63  5578.5  344.43  5608.6  349.97
#Mann= 5 ,-1 , 0
  4404.5     .05       0  4923.1     .16       0  5001.1     .07       0
  5007.1     .16       0    5333     .05       0
Bank Sta=4976.5,5026.6
XS Rating Curve= 0 ,0
Exp/Cntr=0.3,0.1

Type RM Length L Ch R = 1 ,3608    ,552,552,552
BEGIN DESCRIPTION:
CANEY CREEK 4.0
END DESCRIPTION:
XS GIS Cut Line= 3
      3803299.58     10518460.18      3802699.61     10518160.19
       3802099.6     10518160.19
#Sta/Elev= 30
  4284.8  328.54  4343.5  324.75  4360.2  322.44  4382.6  320.88  4455.3  317.69
  4642.5  305.46    4732  300.55  4835.4  292.47  4919.3  291.03  4924.8  291.99
  4935.9  291.78  4985.6  291.87  5002.6  290.06  5005.3  289.56  5008.6  290.06
  5015.6  292.29  5075.6  291.44  5085.6  294.54  5105.6  297.97  5145.6  299.62
  5184.9  299.22  5255.6  299.98  5313.7  303.92  5335.6  306.54  5345.6  306.81
  5355.6  308.84  5418.6  315.79  5455.6  320.39  5485.6  322.36  5555.6  332.12
#Mann= 7 ,-1 , 0
  4284.8     .05       0  4935.9     .12       0  5002.6     .07       0
  5008.6     .12       0  5184.9     .16       0  5313.7     .12       0
  5418.6     .05       0
Bank Sta=4985.6,5015.6
XS Rating Curve= 0 ,0
Exp/Cntr=0.3,0.1

Type RM Length L Ch R = 1 ,3056    ,633,633,633
BEGIN DESCRIPTION:
CANEY CREEK 3.0
END DESCRIPTION:
XS GIS Cut Line= 3
      3803513.77     10518006.35      3802461.03     10517753.58
      3801999.89     10517823.03
#Sta/Elev= 30
  4048.9  332.25  4056.1  333.08  4063.5  331.12  4098.1   328.7  4248.6  311.04
  4361.7  303.51    4588  292.18  4701.3  289.54  4752.5  289.59  4782.3  288.33
    4785  287.83  4788.3  288.33  4803.9  289.91  4855.3  288.99    4989  290.88
  4995.2  289.28  5000.3  290.73  5050.7  290.49    5061  291.02  5079.2  294.41
  5136.3  298.14  5243.5  304.24  5325.1  311.06    5411  319.95  5416.2   321.7
  5446.5  324.83  5517.3  335.99    5549   339.6  5557.7  341.77  5597.9  346.42
#Mann= 5 ,-1 , 0
  4048.9     .05       0  4782.3     .07       0  4788.3     .05       0
  5136.3     .16       0  5243.5     .05       0
Bank Sta=4752.5,4803.9
XS Rating Curve= 0 ,0
Exp/Cntr=0.3,0.1

Type RM Length L Ch R = 1 ,2423    ,292,292,292
BEGIN DESCRIPTION:
Mapping XS 75a64311
END DESCRIPTION:
XS GIS Cut Line= 4
      3803838.79     10517617.46      3802755.47      10517250.8
      3802519.36     10517186.91      3802069.34      10517653.6
#Sta/Elev= 30
  3939.2  355.42  4044.5  347.05  4348.3  309.28  4551.1  295.33  4557.1  294.95
    4709  288.76  4969.2  289.04  5171.8  288.33  5181.2  288.24  5183.9  287.74
  5187.2  288.24  5192.6  288.58  5202.9  288.29  5213.3  290.68  5218.8  293.92
  5275.2  297.33  5283.6  297.61  5340.7  298.66  5534.7  298.04    5563  302.61
    5747  315.88  5824.7     324    5846   324.3    5853  326.15  5867.1  323.93
  5902.4  328.34  5923.7  328.84  5930.7  331.23  5937.9  329.98  5975.8  335.74
#Mann= 9 ,-1 , 0
  3939.2     .05       0  4551.1     .08       0  4557.1     .05       0
  4969.2     .16       0  5181.2     .07       0  5187.2     .16       0
  5275.2     .05       0  5283.6     .08       0  5340.7     .05       0
Bank Sta=5171.8,5192.6
XS Rating Curve= 0 ,0
Exp/Cntr=0.3,0.1

Type RM Length L Ch R = 1 ,2131    ,520,520,520
BEGIN DESCRIPTION:
CANEY CREEK 2.0
END DESCRIPTION:
XS GIS Cut Line= 4
      3803872.09     10517445.23      3802847.14     10517098.03
      3802402.69     10517017.47      3801886.04     10517742.46
#Sta/Elev= 30
  3776.4  348.71  3778.2  348.59    3838  349.29  3869.4  342.08  3916.3  339.06
  3932.2  334.41    4010  323.48    4043  317.08  4122.9     308  4216.1  302.12
  4319.1  302.61  4328.1  303.13  4359.7  294.95  4422.2  291.96  4467.6  290.94
  4581.4  288.25  4715.7  286.59  4718.5  286.09  4721.7  286.59  4832.9  287.91
  5049.2  288.47  5096.8  292.44  5378.5  298.83    5402  294.92  5414.2  294.37
  5422.8  300.05  5519.2  303.78  5687.1  312.77  6016.5  347.06  6200.5   354.8
#Mann= 12 ,-1 , 0
  3776.4     .08       0  3778.2     .05       0    4010     .08       0
  4122.9     .05       0  4216.1     .16       0  4319.1     .05       0
  4422.2     .08       0  4467.6     .05       0  4715.7     .03       0
  4721.7     .05       0    5402     .08       0  5519.2     .05       0
Bank Sta=4581.4,4832.9
XS Rating Curve= 0 ,0
Exp/Cntr=0.3,0.1

Type RM Length L Ch R = 1 ,1611    ,415,415,415
BEGIN DESCRIPTION:
Mapping XS da52ba76
END DESCRIPTION:
XS GIS Cut Line= 5
      3803903.29     10517204.99      3802919.92     10516621.64
      3802686.58     10516659.14      3802440.75     10516796.64
      3801807.44     10517650.77
#Sta/Elev= 30
  3457.6  329.66  3493.7  328.63  3589.2  319.54  3717.8  302.45  3915.3  289.92
  4054.9  284.56  4520.7     284  4533.3  283.52  4536.1  283.02  4539.3  283.52
  4543.2  283.91  4837.3  283.65  4982.8  286.64  4996.5  284.69  5005.7  286.32
  5144.1  284.94  5173.2  286.06  5244.2  294.33  5388.2  297.34  5436.2  300.73
  5444.6  296.67  5465.4  296.38    5472  297.25  5480.9  302.91  5615.7   308.8
  5745.1  319.31  5836.8   331.8  5951.6  343.47  6101.9  353.37  6182.3  355.18
#Mann= 5 ,-1 , 0
  3457.6     .05       0  4533.3     .03       0  4539.3     .05       0
  5388.2     .08       0  5480.9     .05       0
Bank Sta=4520.7,4543.2
XS Rating Curve= 0 ,0
Exp/Cntr=0.3,0.1

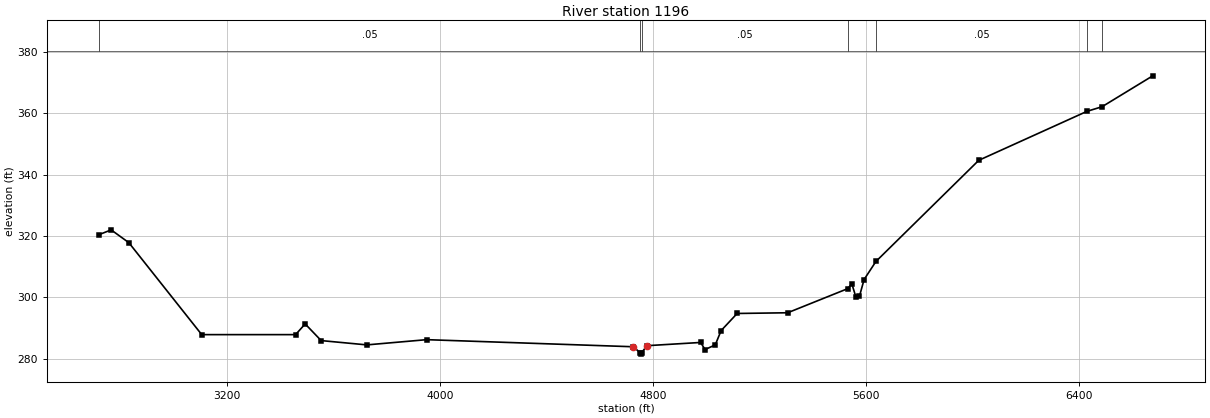
Type RM Length L Ch R = 1 ,1196    ,0,0,0
BEGIN DESCRIPTION:
CANEY CREEK 1.0
END DESCRIPTION:
XS GIS Cut Line= 3
      3803903.46     10516888.47      3802500.87     10515958.62
      3801554.26     10518022.57
#Sta/Elev= 30
  2722.3  320.48  2766.7  321.99  2832.9  317.84  3106.6  287.88  3458.8  287.88
  3494.8  291.37  3554.8  285.94  3726.2  284.54  3950.7  286.24  4725.9  283.93
  4751.7  282.03  4754.4  281.53  4757.7  282.03  4777.7  284.28  4978.9  285.33
  4995.6  283.02  5033.9  284.54  5055.9   289.2  5116.1  294.77  5305.6     295
  5530.9  302.85  5546.5  304.42    5562  300.04    5575  300.36  5592.5  305.83
  5636.9  311.71  6022.9  344.65  6428.8  360.59  6485.6   362.1  6675.8  372.16
#Mann= 7 ,-1 , 0
  2722.3     .05       0  4751.7     .03       0  4757.7     .05       0
  5530.9     .08       0  5636.9     .05       0  6428.8      .1       0
  6485.6     .05       0
Bank Sta=4725.9,4777.7
XS Rating Curve= 0 ,0
Exp/Cntr=0.3,0.1

Chan Stop Cuts=-1
Use User Specified Reach Order=0
Composite Channel Slope=5