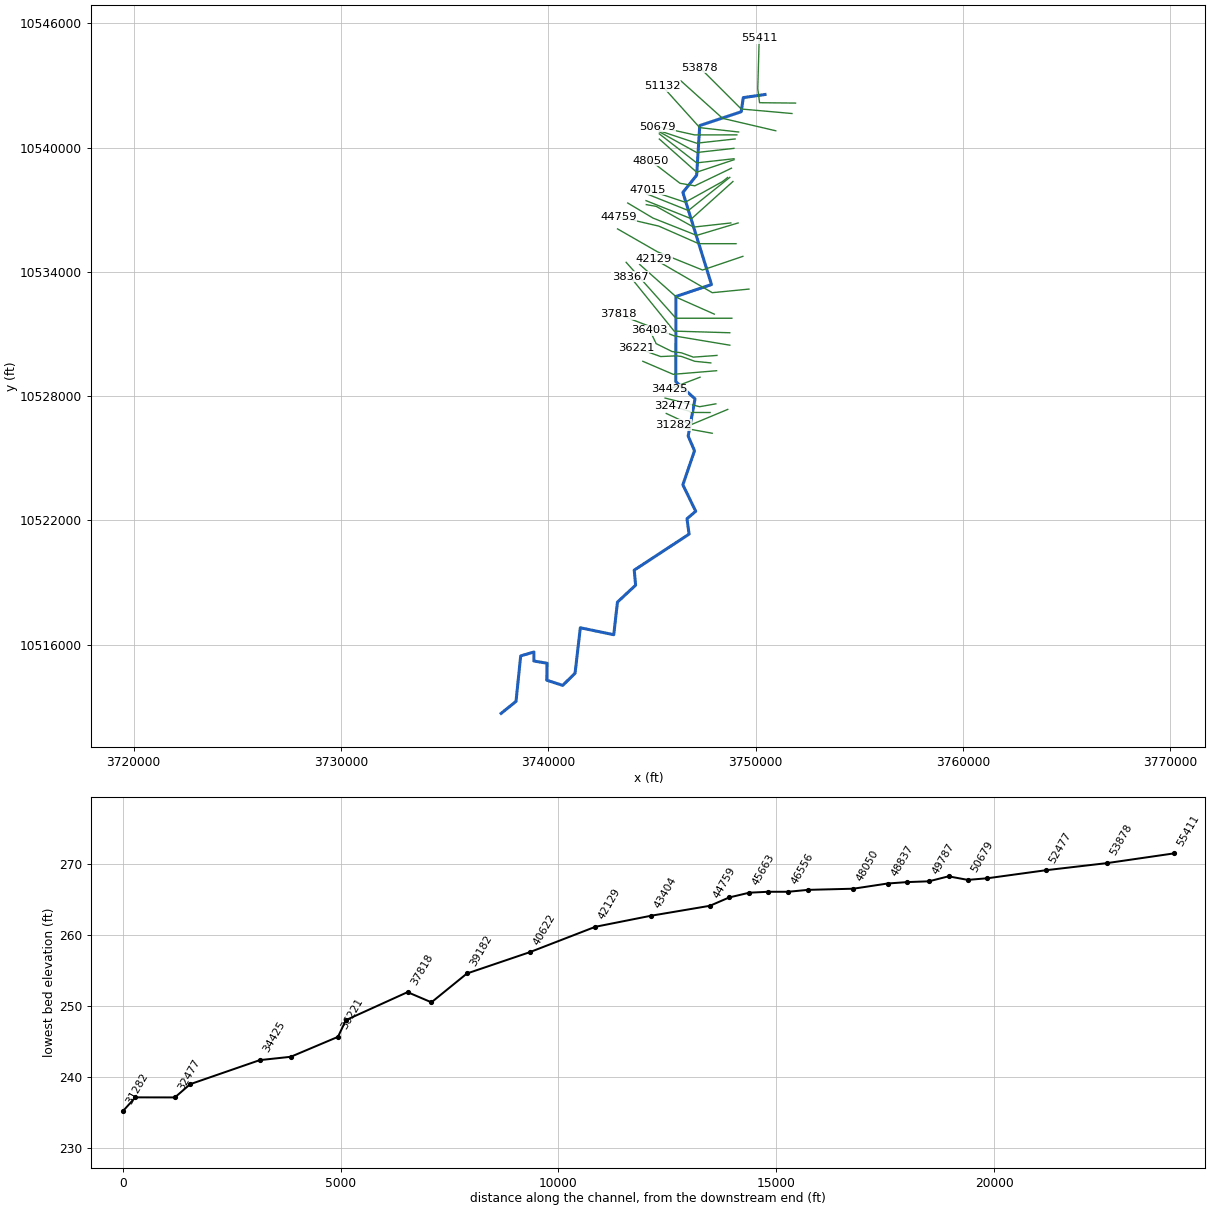
--- CEDAR BRANCH.prj (project) ---

Proj Title=CEDAR BRANCH Base Level Engineering
Current Plan=p01
Default Exp/Contr=0.3,0.1
English Units
Geom File=g01
Flow File=f01
Flow File=f02
Plan File=p01
Y Axis Title=Elevation
X Axis Title(PF)=Main Channel Distance
X Axis Title(XS)=Station
BEGIN DESCRIPTION:
CEDAR BRANCH
END DESCRIPTION:
DSS Export Rating Curves= 0
DSS Export Rating Curve Sorted= 0
DSS Export Volume Flow Curves= 0
DXF OffsetX= 0
DXF OffsetY= 0
DXF ScaleX= 1
DXF ScaleY= 10

--- CEDAR BRANCH.p01 (plan) ---

Plan Title=Multiple Run
Short Identifier=Multiple
Geom File=g01
Flow File=f01
Subcritical Flow
K Sum by GR= 0
Std Step Tol= 0.01
Critical Tol= 0.01
Num of Std Step Trials= 20
Max Error Tol= 0.3
Flow Tol Ratio= 0.001
Split Flow NTrial= 30
Split Flow Tol= 0.02
Split Flow Ratio= 0.02
Log Output Level= 0
Friction Slope Method= 1
Unsteady Friction Slope Method= 2
Unsteady Bridges Friction Slope Method= 1
Parabolic Critical Depth
Global Vel Dist=  1 , 1 , 1
Global Log Level= 0
CheckData=True
Encroach Param= -1, 0, 0, 0
BEGIN DESCRIPTION:
Multiple Run
END DESCRIPTION:

--- CEDAR BRANCH.f01 (steady flow) ---

Flow Title=Multiple
Program Version=4.10
Number of Profiles= 7
Profile Names=10-year,25-year,50-year,1pct_min,100-year,1pct_plu,500-year
River Rch & RM=CEDAR BRANCH,Reach-1         ,55411
     947    1318    1633    1485    2009    2716    3052
River Rch & RM=CEDAR BRANCH,Reach-1         ,51132
    1101    1539    1911    1740    2353    3183    3586
River Rch & RM=CEDAR BRANCH,Reach-1         ,46556
    1315    1848    2303    2104    2845    3848    4362
River Rch & RM=CEDAR BRANCH,Reach-1         ,43404
    1545    2183    2730    2501    3382    4574    5215
River Rch & RM=CEDAR BRANCH,Reach-1         ,39182
    1707    2416    3026    2774    3751    5073    5793
River Rch & RM=CEDAR BRANCH,Reach-1         ,34425
    1809    2564    3215    2949    3989    5394    6169
River Rch & RM=CEDAR BRANCH,Reach-1         ,30421
    1936    2739    3427    3137    4243    5738    6532
River Rch & RM=CEDAR BRANCH,Reach-1         ,15874
    2258    3204    4017    3681    4978    6732    7683
Boundary for River Rch & Prof#=CEDAR BRANCH,Reach-1         , 1
Up Type= 0
Dn Type= 3
Dn Slope=0.001
Boundary for River Rch & Prof#=CEDAR BRANCH,Reach-1         , 2
Up Type= 0
Dn Type= 3
Dn Slope=0.001
Boundary for River Rch & Prof#=CEDAR BRANCH,Reach-1         , 3
Up Type= 0
Dn Type= 3
Dn Slope=0.001
Boundary for River Rch & Prof#=CEDAR BRANCH,Reach-1         , 4
Up Type= 0
Dn Type= 3
Dn Slope=0.001
Boundary for River Rch & Prof#=CEDAR BRANCH,Reach-1         , 5
Up Type= 0
Dn Type= 3
Dn Slope=0.001
Boundary for River Rch & Prof#=CEDAR BRANCH,Reach-1         , 6
Up Type= 0
Dn Type= 3
Dn Slope=0.001
Boundary for River Rch & Prof#=CEDAR BRANCH,Reach-1         , 7
Up Type= 0
Dn Type= 3
Dn Slope=0.001
DSS Import GetInterval= 0
DSS Import GetPeak= 0
DSS Import FillOption= 0

--- CEDAR BRANCH.f02 (steady flow) ---

Flow Title=old Multiple
Program Version=4.10
Number of Profiles= 7
Profile Names=10-year,25-year,50-year,1pct_min,100-year,1pct_plu,500-year
River Rch & RM=CEDAR BRANCH,Reach-1         ,39414
     947    1318    1633    1485    2009    2716    3052
River Rch & RM=CEDAR BRANCH,Reach-1         ,35135
    1101    1539    1911    1740    2353    3183    3586
River Rch & RM=CEDAR BRANCH,Reach-1         ,30559
    1315    1848    2303    2104    2845    3848    4362
River Rch & RM=CEDAR BRANCH,Reach-1         ,27407
    1545    2183    2730    2501    3382    4574    5215
River Rch & RM=CEDAR BRANCH,Reach-1         ,23185
    1707    2416    3026    2774    3751    5073    5793
River Rch & RM=CEDAR BRANCH,Reach-1         ,18428
    1809    2564    3215    2949    3989    5394    6169
River Rch & RM=CEDAR BRANCH,Reach-1         ,14424
    1936    2739    3427    3137    4243    5738    6532
River Rch & RM=CEDAR BRANCH,Reach-1         ,135
    2258    3204    4017    3681    4978    6732    7683
Boundary for River Rch & Prof#=CEDAR BRANCH,Reach-1         , 1
Up Type= 0
Dn Type= 1
Dn Known WS=213.52
Boundary for River Rch & Prof#=CEDAR BRANCH,Reach-1         , 2
Up Type= 0
Dn Type= 1
Dn Known WS=214.69
Boundary for River Rch & Prof#=CEDAR BRANCH,Reach-1         , 3
Up Type= 0
Dn Type= 1
Dn Known WS=215.58
Boundary for River Rch & Prof#=CEDAR BRANCH,Reach-1         , 4
Up Type= 0
Dn Type= 1
Dn Known WS=215.24
Boundary for River Rch & Prof#=CEDAR BRANCH,Reach-1         , 5
Up Type= 0
Dn Type= 1
Dn Known WS=216.45
Boundary for River Rch & Prof#=CEDAR BRANCH,Reach-1         , 6
Up Type= 0
Dn Type= 1
Dn Known WS=217.86
Boundary for River Rch & Prof#=CEDAR BRANCH,Reach-1         , 7
Up Type= 0
Dn Type= 1
Dn Known WS=218.53
DSS Import GetInterval= 0
DSS Import GetPeak= 0
DSS Import FillOption= 0

--- CEDAR BRANCH.g01 (geometry) ---

Geom Title=Existing Conditions
Program Version=4.10

River Reach=CEDAR BRANCH    ,Reach-1
Reach XY= 30
      3750449.61     10542560.19      3749399.61     10542410.19
      3749299.61     10541727.59      3747299.61     10541060.19
      3747149.61     10538660.19      3746485.55     10537834.59
       3747865.8     10533387.43      3746149.61     10532810.19
       3746144.5       10528701.      3747072.75       10527870.
        3746741.       10526077.        3747047.       10525365.
        3746485.       10523720.       3747105.5       10522445.
        3746684.       10522083.      3746785.75       10521341.
        3744140.       10519603.      3744205.75       10518875.
      3743330.25       10518060.      3743152.75       10516485.
      3741539.75       10516821.       3741285.5       10514627.
        3740692.       10514040.      3739919.75       10514290.
      3739936.75       10515109.      3739298.25       10515216.
        3739301.       10515650.       3738663.5       10515462.
       3738437.5       10513267.      3737720.91     10512688.74

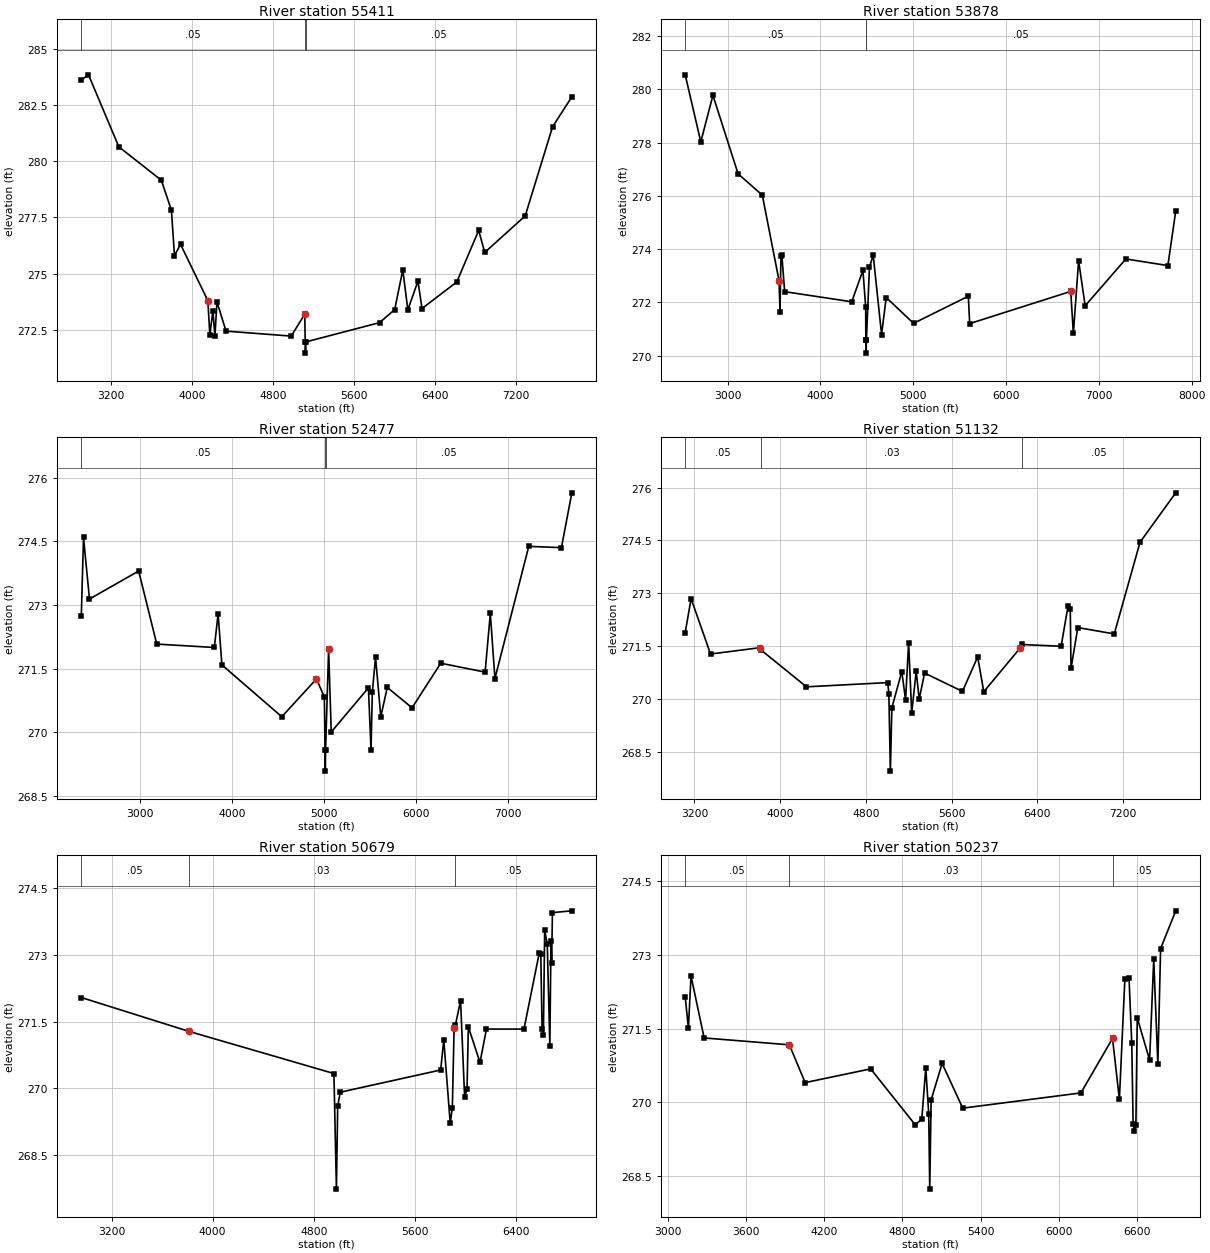
Type RM Length L Ch R = 1 ,55411   ,1533,1533,1533
BEGIN DESCRIPTION:
CEDAR BRANCH 61.0
END DESCRIPTION:
XS GIS Cut Line= 4
      3751920.62     10542146.09      3750184.52     10542163.45
      3750097.71     10542840.53      3750167.16     10545271.13
#Sta/Elev= 30
  2903.2  283.63  2974.2  283.86  3274.2  280.65  3694.3  279.16  3794.3  277.82
  3824.3   275.8  3884.3   276.3  4154.3  273.79  4174.3  272.27  4204.3  273.33
  4224.3   272.2  4244.3  273.74  4334.3  272.43  4978.9  272.21  5112.8  273.19
    5117  271.95  5119.8  271.45    5123  271.95  5851.9  272.81  6001.9  273.39
    6082  275.16    6132  273.38    6232  274.66  6272.1  273.44  6615.5  274.62
  6832.3  276.92  6892.3  275.94  7292.5  277.57  7562.6  281.54  7753.6  282.88
#Mann= 3 ,-1 , 0
  2903.2     .05       0    5117     .03       0    5123     .05       0
Bank Sta=4154.3,5112.8
XS Rating Curve= 0 ,0
Exp/Cntr=0.3,0.1

Type RM Length L Ch R = 1 ,53878   ,1401,1401,1401
BEGIN DESCRIPTION:
CEDAR BRANCH 60.0
END DESCRIPTION:
XS GIS Cut Line= 3
      3751747.06     10541642.61      3749299.61     10541860.19
      3747299.63     10543860.17
#Sta/Elev= 30
  2542.9  280.55    2711  278.03  2841.5  279.78  3112.6  276.83  3373.6  276.03
  3554.3  272.81  3564.4  271.65  3574.4  273.75  3583.9  273.78  3614.6   272.4
  4337.4  272.02  4457.9   273.2  4487.4  271.84  4489.4  270.59  4492.2  270.09
  4495.4  270.59  4528.1  273.31  4568.3  273.78  4658.7  270.79  4708.9  272.18
  5003.5  271.21    5594  272.23  5608.1   271.2  6697.1  272.41  6725.3  270.83
  6781.9  273.56  6852.6  271.87    7291  273.63  7743.6  273.38  7828.4  275.43
#Mann= 3 ,-1 , 0
  2542.9     .05       0  4489.4     .03       0  4495.4     .05       0
Bank Sta=3554.3,6697.1
XS Rating Curve= 0 ,0
Exp/Cntr=0.3,0.1

Type RM Length L Ch R = 1 ,52477   ,1345,1345,1345
BEGIN DESCRIPTION:
CEDAR BRANCH 59.0
END DESCRIPTION:
XS GIS Cut Line= 3
      3750965.79     10540809.28      3748399.61     10541410.19
      3746399.63     10543210.17
#Sta/Elev= 30
  2364.4  272.75  2388.2  274.59  2452.9  273.14    2987   273.8  3183.5  272.08
  3808.6     272  3849.7  272.79  3890.8  271.59  4541.2  270.37  4917.8  271.26
  5003.4  270.83  5010.8  269.59  5013.6  269.09  5016.8  269.59  5049.7  271.96
  5078.1  270.01  5481.7  271.05  5510.1  269.59  5524.3  270.95  5559.4  271.77
  5616.3  270.37  5686.5  271.06  5955.6  270.58  6267.3  271.63    6749  271.42
  6805.4   272.8  6855.5  271.27  7223.2  274.38  7577.5  274.35  7690.7  275.64
#Mann= 3 ,-1 , 0
  2364.4     .05       0  5010.8     .03       0  5016.8     .05       0
Bank Sta=4917.8,5049.7
XS Rating Curve= 0 ,0
Exp/Cntr=0.3,0.1

Type RM Length L Ch R = 1 ,51132   ,453,453,453
BEGIN DESCRIPTION:
CEDAR BRANCH 58.0
END DESCRIPTION:
XS GIS Cut Line= 3
      3749174.33     10540749.68      3747299.61     10540960.19
      3745499.63     10542960.17
#Sta/Elev= 30
  3113.5  271.89  3168.6  272.85  3349.7  271.28  3812.6  271.46  3822.6  271.39
  4245.3  270.35  5003.4  270.47  5013.8  270.16  5027.8  267.96  5042.2  269.76
  5134.5  270.78    5170  269.98  5198.4   271.6  5226.8  269.61  5269.1  270.79
  5297.1     270  5347.2  270.74  5700.7  270.22  5842.7   271.2  5899.5  270.21
  6238.9  271.45  6253.1  271.55  6621.5   271.5  6685.1  272.63  6706.7  272.55
  6713.5  270.87    6777  272.03  7117.1  271.85  7357.7  274.45  7690.7  275.85
#Mann= 3 ,-1 , 0
  3113.5     .05       0  3822.6     .03       0  6253.1     .05       0
Bank Sta=3812.6,6238.9
XS Rating Curve= 0 ,0
Exp/Cntr=0.3,0.1

Type RM Length L Ch R = 1 ,50679   ,442,442,442
BEGIN DESCRIPTION:
CEDAR BRANCH 57.0
END DESCRIPTION:
XS GIS Cut Line= 3
      3749089.71     10540611.87      3747049.61     10540610.19
      3745249.62     10541010.19
#Sta/Elev= 30
  2959.9  272.04    3810  271.28    4960  270.33  4979.8  267.73    4990   269.6
  5010.2  269.91  5805.4  270.41  5829.8  271.09    5881  269.21  5897.6  269.56
  5911.7  271.35    5922  271.42  5962.9  271.97  5994.9   269.8  6014.1  269.98
  6024.4  271.38  6116.6  270.58  6167.8  271.33  6464.9  271.33  6586.5  273.05
  6598.1  273.01  6608.3  271.34  6618.5   271.2  6628.8  273.55  6649.3  273.24
  6669.8  270.96  6678.7  273.32  6683.8  272.81  6690.2  273.95  6843.9  273.99
#Mann= 3 ,-1 , 0
  2959.9     .05       0    3810     .03       0    5922     .05       0
Bank Sta=3810,5911.7
XS Rating Curve= 0 ,0
Exp/Cntr=0.3,0.1

Type RM Length L Ch R = 1 ,50237   ,450,450,450
BEGIN DESCRIPTION:
CEDAR BRANCH 56.0
END DESCRIPTION:
XS GIS Cut Line= 3
        3749004.     10540414.39      3747149.61     10540210.19
      3745349.58      10540810.2
#Sta/Elev= 30
  3134.4  272.15  3158.9  271.51  3179.1  272.57  3279.7  271.31  3933.6  271.17
  4054.3   270.4  4557.3  270.68  4899.4  269.54  4949.5  269.66  4979.9   270.7
  5002.6  269.76  5010.3  268.23  5021.1  270.05  5105.4  270.79  5263.5  269.88
    6170  270.19  6412.5   271.3  6465.2  270.06  6507.4  272.52    6539  272.54
  6560.1   271.2  6570.6  269.55  6581.1  269.41  6591.7  269.53  6602.2  271.72
  6697.1  270.86  6728.7  272.91  6760.3  270.78  6781.4  273.13  6897.4   273.9
#Mann= 3 , 0 , 0
  3134.4     .05       0  3933.6     .03       0  6412.5     .05       0
Bank Sta=3933.6,6412.5
XS Rating Curve= 0 ,0
Exp/Cntr=0.3,0.1

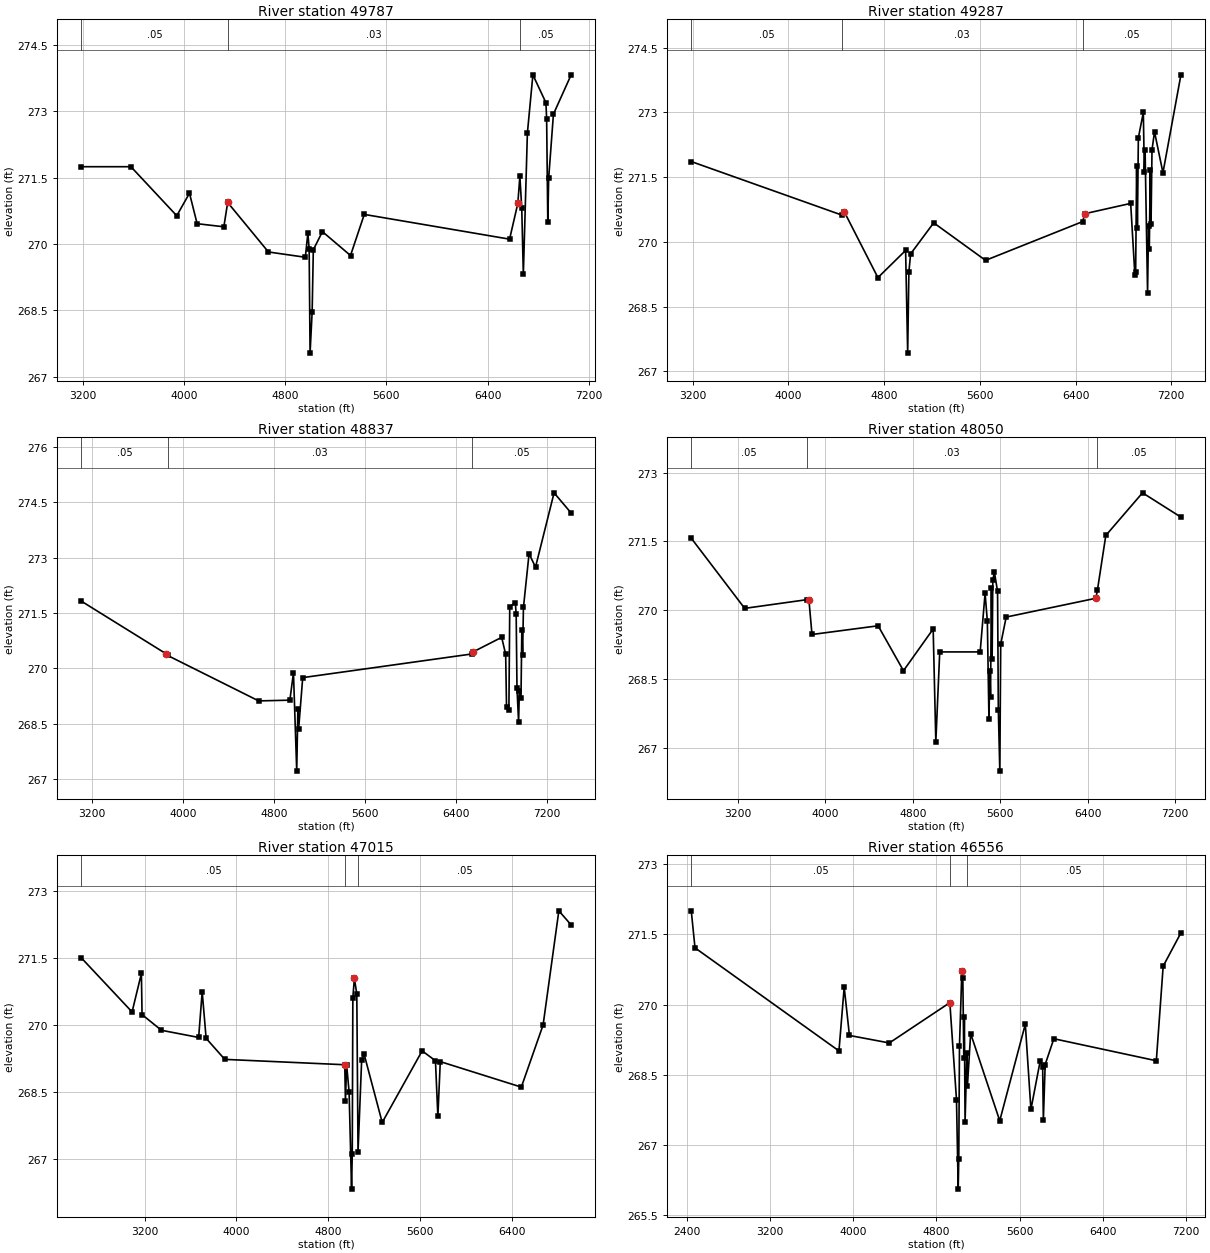
Type RM Length L Ch R = 1 ,49787   ,500,500,500
BEGIN DESCRIPTION:
CEDAR BRANCH 55.0
END DESCRIPTION:
XS GIS Cut Line= 3
      3748949.63     10539960.19      3747149.61     10539760.19
      3745349.63     10540760.18
#Sta/Elev= 30
  3188.9  271.75  3581.3  271.75  3943.5  270.64  4044.2  271.15  4104.5  270.46
  4315.8  270.39    4346  270.94    4668  269.82  4959.8   269.7  4979.9  270.25
  4989.9  269.89  4997.2  267.53  5013.7  268.47  5022.9  269.87  5094.9  270.28
  5316.9  269.74  5425.6  270.67  6574.1  270.11  6639.3  270.92  6655.3  271.53
  6670.2  270.82  6682.8  269.31  6714.8  272.51  6758.3  273.83  6861.2   273.2
  6866.9  272.84  6876.1   270.5    6883  271.49  6920.7  272.94  7059.1  273.82
#Mann= 3 ,-1 , 0
  3188.9     .05       0    4346     .03       0  6655.3     .05       0
Bank Sta=4346,6639.3
XS Rating Curve= 0 ,0
Exp/Cntr=0.3,0.1

Type RM Length L Ch R = 1 ,49287   ,450,450,450
BEGIN DESCRIPTION:
CEDAR BRANCH 54.0
END DESCRIPTION:
XS GIS Cut Line= 3
      3748949.63     10539460.19      3747149.61     10539260.19
      3745349.57     10540660.22
#Sta/Elev= 30
  3188.9  271.86  4446.6  270.62  4466.7   270.7  4748.5  269.17  4979.9   269.8
  4997.2  267.42  5007.2   269.3  5021.7  269.72  5214.5  270.44  5647.9  269.57
  6460.5  270.47    6475  270.65  6860.5  270.89  6895.8  269.22  6902.1  269.31
  6910.2  271.75  6916.6  270.33  6924.7  272.41  6966.3     273  6974.5  271.62
  6980.8  272.13  7001.6  268.82  7009.8  270.37  7016.1  269.84  7024.3  271.67
  7030.6  270.41  7038.7  272.13  7059.6  272.55  7130.1   271.6  7280.4  273.87
#Mann= 3 ,-1 , 0
  3188.9     .05       0  4446.6     .03       0  6460.5     .05       0
Bank Sta=4466.7,6475
XS Rating Curve= 0 ,0
Exp/Cntr=0.3,0.1

Type RM Length L Ch R = 1 ,48837   ,787,787,787
BEGIN DESCRIPTION:
CEDAR BRANCH 53.0
END DESCRIPTION:
XS GIS Cut Line= 3
      3748949.64      10539410.2      3747149.61     10538810.19
      3745349.62     10540410.18
#Sta/Elev= 30
  3102.6  271.82    3851  270.39  3861.6  270.35  4662.7  269.12  4936.8  269.14
  4968.4  269.88  4997.1  267.22  5007.1   268.9  5013.8  268.36  5049.8  269.75
  6537.4  270.39  6544.1  270.44  6799.1  270.84  6834.3  270.38  6841.8  268.96
  6862.7  268.88  6870.2  271.67  6919.5  271.78  6926.7  271.46  6933.8  269.47
    6948  268.55  6954.7  269.38  6968.9  269.19  6976.4  271.04  6983.1  270.37
  6990.6  271.65    7040   273.1  7096.8  272.74  7259.9  274.75  7408.3  274.21
#Mann= 3 ,-1 , 0
  3102.6     .05       0  3861.6     .03       0  6537.4     .05       0
Bank Sta=3851,6544.1
XS Rating Curve= 0 ,0
Exp/Cntr=0.3,0.1

Type RM Length L Ch R = 1 ,48050   ,1035,1035,1035
BEGIN DESCRIPTION:
CEDAR BRANCH 52.0
END DESCRIPTION:
XS GIS Cut Line= 4
      3748830.32     10539003.71      3747059.52     10538153.03
      3746347.71     10538274.56      3744924.34     10539368.13
#Sta/Elev= 30
  2771.8  271.57  3260.7  270.04  3831.4  270.23  3848.5  270.23  3876.7  269.47
    4482  269.66    4714  268.68  4985.8  269.59  5010.1  267.13  5045.9  269.09
  5415.9  269.09  5460.9  270.37  5481.7  269.76  5496.2  267.63  5504.4  268.68
  5510.7   268.1    5519  270.48  5525.3  268.93  5531.7  270.66  5546.1  270.83
  5575.1  270.41  5582.2  267.83  5595.7  266.49  5604.1  269.26    5654  269.85
  6474.2  270.26  6488.7  270.43  6565.8  271.63  6901.9  272.56  7253.4  272.03
#Mann= 3 ,-1 , 0
  2771.8     .05       0  3831.4     .03       0  6488.7     .05       0
Bank Sta=3848.5,6474.2
XS Rating Curve= 0 ,0
Exp/Cntr=0.3,0.1

Type RM Length L Ch R = 1 ,47015   ,459,459,459
BEGIN DESCRIPTION:
CEDAR BRANCH 51.0
END DESCRIPTION:
XS GIS Cut Line= 4
      3748642.47     10538552.66      3748399.61     10538360.19
      3746599.61     10537360.19      3744799.59      10537960.2
#Sta/Elev= 30
  2648.2   271.5  3090.8  270.29    3172  271.15  3177.7  270.23    3347  269.88
  3670.8  269.72  3701.7  270.74    3736   269.7  3898.4  269.23    4944  269.11
  4949.7   268.3    4960  269.11  4981.7   268.5  5003.2  266.33  5009.2  267.12
  5014.4  270.61  5027.8  271.04  5048.8  270.69  5059.4  267.16    5091  269.21
  5112.1  269.35  5270.2  267.82    5618  269.42    5734   269.2  5755.1  267.96
  5776.2  269.18  6482.4  268.61  6672.1     270  6809.2  272.55  6914.6  272.24
#Mann= 3 ,-1 , 0
  2648.2     .05       0  4949.7     .04       0  5059.4     .05       0
Bank Sta=4944,5027.8
XS Rating Curve= 0 ,0
Exp/Cntr=0.3,0.1

Type RM Length L Ch R = 1 ,46556   ,462,462,462
BEGIN DESCRIPTION:
CEDAR BRANCH 50.0
END DESCRIPTION:
XS GIS Cut Line= 3
      3748749.57     10538560.16      3746749.61     10536960.19
      3744749.58      10537760.2
#Sta/Elev= 30
  2438.8     272  2474.8  271.21    3861  269.01  3911.5  270.37  3961.9  269.34
  4346.1  269.18  4928.8  270.04  4992.8  267.97  5009.2  266.06  5014.8   266.7
  5021.5  269.11  5044.4  270.71  5053.9  270.56  5063.3  268.85  5068.7  269.73
  5075.4  267.49  5092.9  268.97  5098.3  268.27  5129.2  269.38  5409.3  267.52
  5655.6  269.58  5709.5  267.76  5798.4  268.79  5822.6  268.67  5829.3  267.53
  5846.8  268.72  5930.3  269.27  6917.1   268.8  6983.1  270.82  7154.1  271.53
#Mann= 3 ,-1 , 0
  2438.8     .05       0  4928.8     .04       0  5098.3     .05       0
Bank Sta=4928.8,5044.4
XS Rating Curve= 0 ,0
Exp/Cntr=0.3,0.1

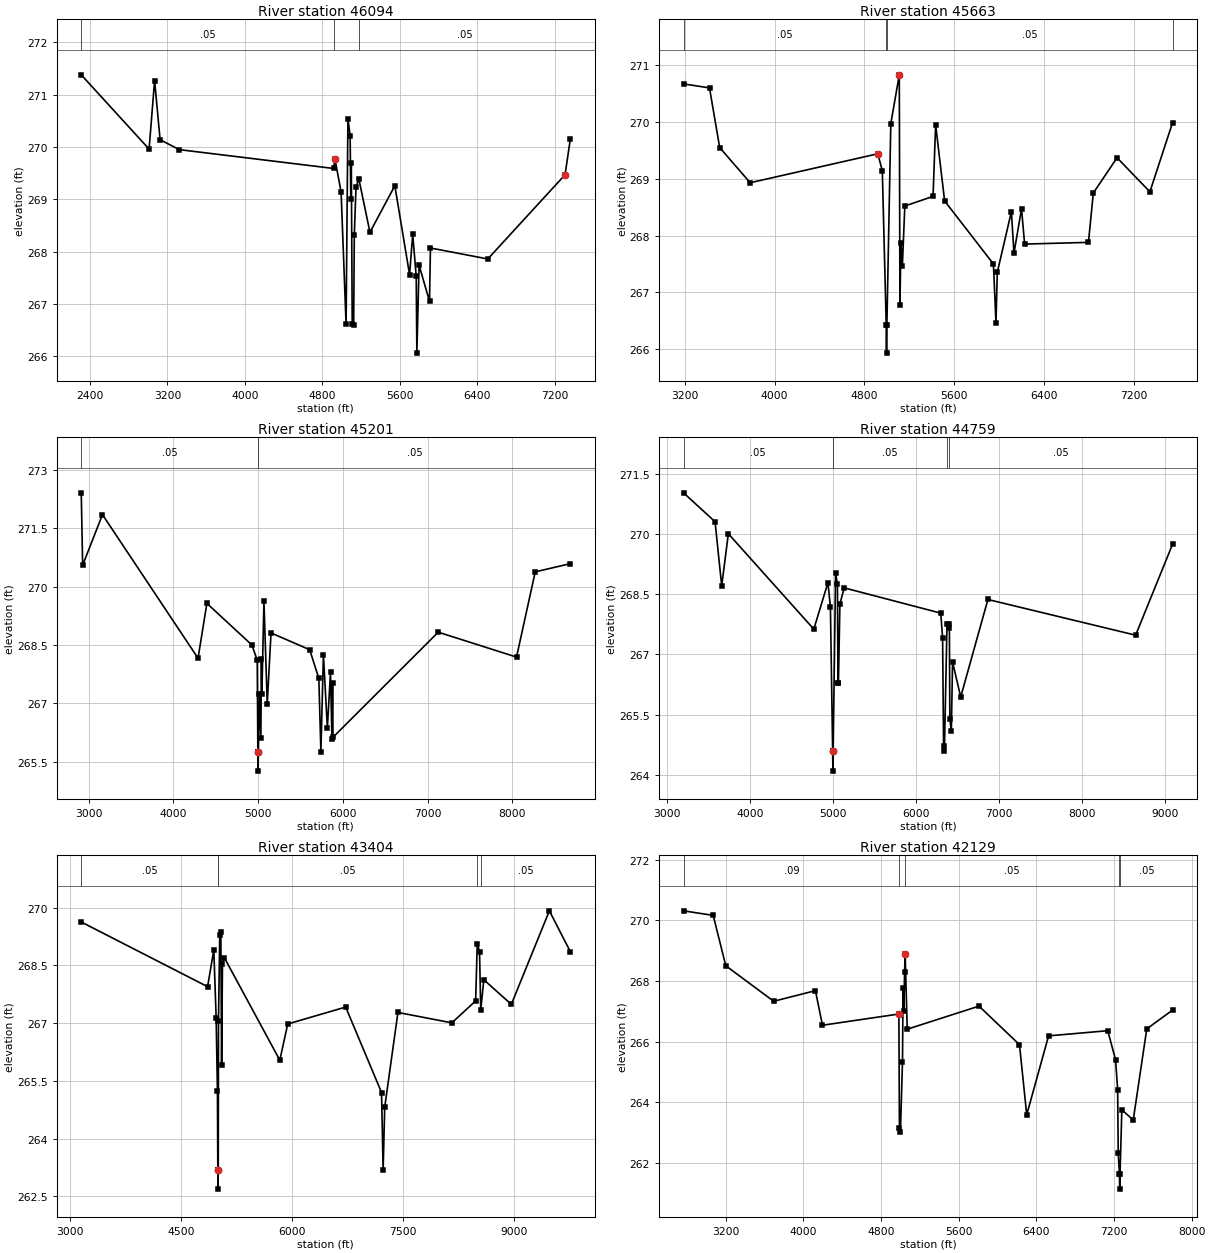
Type RM Length L Ch R = 1 ,46094   ,431,431,431
BEGIN DESCRIPTION:
CEDAR BRANCH 49.0
END DESCRIPTION:
XS GIS Cut Line= 3
      3748899.59     10538360.17      3746899.61     10536560.19
      3744708.59     10537437.13
#Sta/Elev= 30
  2309.3  271.38    3010  269.96  3066.8  271.27  3123.6  270.14  3321.7  269.95
  4915.2  269.59  4929.4  269.77  4992.9  269.14  5044.4  266.61  5063.3  270.54
  5086.2  270.22  5092.9     269  5098.3  269.69  5107.7  266.62  5122.5  266.59
  5129.3  268.32  5146.7  269.23  5176.3  269.39  5290.8  268.37  5547.8  269.26
  5700.1  267.56  5732.4  268.33  5768.6  267.53  5775.3  266.06  5798.2  267.74
  5905.9  267.05  5915.6  268.07    6508  267.86  7305.7  269.47    7360  270.15
#Mann= 3 ,-1 , 0
  2309.3     .05       0  4915.2     .04       0  5176.3     .05       0
Bank Sta=4929.4,7305.7
XS Rating Curve= 0 ,0
Exp/Cntr=0.3,0.1

Type RM Length L Ch R = 1 ,45663   ,462,462,462
BEGIN DESCRIPTION:
CEDAR BRANCH 48.0
END DESCRIPTION:
XS GIS Cut Line= 4
      3748799.63     10536360.19      3746999.61     10536160.19
      3745199.61     10537160.19      3744720.57     10537245.46
#Sta/Elev= 30
  3188.9  270.67  3420.3   270.6  3510.9  269.55  3782.6  268.93  4919.5  269.44
  4959.8  269.14  4994.5  266.43  4997.2  265.93  5000.5  266.43  5035.5  269.97
    5111  270.83  5116.7  266.78  5125.8  267.87  5138.4  267.46  5160.2  268.52
  5411.8  268.69  5434.7  269.95  5514.8  268.61  5949.5   267.5  5972.4  266.46
  5983.8  267.35  6109.6  268.42  6132.5  267.69    6200  268.47  6227.5  267.85
    6796  267.88  6839.5  268.75  7051.1  269.37  7343.5  268.77  7545.7  269.99
#Mann= 4 ,-1 , 0
  3188.9     .05       0  4994.5     .04       0  5000.5     .05       0
  7545.7     .05       0
Bank Sta=4919.5,5111
XS Rating Curve= 0 ,0
Exp/Cntr=0.3,0.1

Type RM Length L Ch R = 1 ,45201   ,442,442,442
BEGIN DESCRIPTION:
CEDAR BRANCH 47.0
END DESCRIPTION:
XS GIS Cut Line= 4
      3749149.65      10536360.2      3747149.61     10535760.19
      3745047.34      10536594.7      3743824.02     10537323.49
#Sta/Elev= 30
  2911.9  272.41  2928.5  270.55  3162.5  271.85  4290.9  268.16  4395.3  269.57
  4926.9   268.5  4989.6  268.11    4997  265.76  4999.8  265.26    5003  265.76
  5014.8  267.24  5032.3  266.11  5039.2  268.14  5044.5  267.24  5068.8  269.63
  5107.6  266.99  5152.5  268.81  5608.9  268.38  5716.9  267.64  5741.2  265.76
  5770.9  268.25  5817.7  266.37  5854.6   267.8  5871.5  266.09  5878.9  267.52
  5884.2  266.13  7126.3  268.83  8050.7  268.19  8271.9  270.38  8685.8  270.59
#Mann= 3 ,-1 , 0
  2911.9     .05       0    4997     .04       0    5003     .05       0
Bank Sta=4997,5003
XS Rating Curve= 0 ,0
Exp/Cntr=0.3,0.1

Type RM Length L Ch R = 1 ,44759   ,1355,1355,1355
BEGIN DESCRIPTION:
CEDAR BRANCH 46.0
END DESCRIPTION:
XS GIS Cut Line= 4
      3749049.61     10535360.19      3747249.61     10535360.19
      3745318.17     10536209.28      3743385.84     10536657.21
#Sta/Elev= 30
    3200  271.03    3580  270.31    3660  268.71    3740  270.01    4770  267.63
    4940  268.79    4970  268.19    4997  264.59  4999.8  264.09    5003  264.59
  5032.3  269.03  5054.6  268.76  5061.1  266.29  5066.6  266.28  5084.4  268.26
  5136.6  268.66  6299.5  268.03  6321.8  267.42  6333.8  264.71  6343.6  264.59
  6375.3  267.77  6399.1  267.76  6403.8  267.66  6409.3  265.38  6427.2  265.09
  6441.9  266.81  6540.2  265.94  6867.9  268.37  8648.1  267.48  9093.4  269.75
#Mann= 5 ,-1 , 0
    3200     .05       0    4997     .04       0    5003     .05       0
  6375.3     .08       0  6399.1     .05       0
Bank Sta=4997,5003
XS Rating Curve= 0 ,0
Exp/Cntr=0.3,0.1

Type RM Length L Ch R = 1 ,43404   ,1275,1275,1275
BEGIN DESCRIPTION:
CEDAR BRANCH 45.0
END DESCRIPTION:
XS GIS Cut Line= 4
      3749378.77     10534747.91      3747434.29     10534088.17
      3745266.09     10534964.49      3743334.19     10536073.64
#Sta/Elev= 30
  3148.5  269.63  4858.3  267.95  4942.8   268.9  4974.5  267.14  4991.8  265.24
    4997  263.19  4999.8  262.69    5003  263.19  5006.2  267.07  5023.2   269.3
  5037.8  269.38  5048.4  265.92  5059.9  268.54    5086   268.7  5836.1  266.04
  5943.4  266.98  6727.7  267.42  7213.1   265.2  7234.6  263.19  7256.2  264.82
  7434.9  267.28  8164.6  267.01  8486.8  267.58  8508.5  269.07  8539.6  268.86
  8555.5  267.34  8597.2  268.13  8969.9  267.49  9484.7  269.92  9768.1  268.86
#Mann= 5 ,-1 , 0
  3148.5     .05       0    4997     .04       0    5003     .05       0
  8508.5     .08       0  8555.5     .05       0
Bank Sta=4997,5003
XS Rating Curve= 0 ,0
Exp/Cntr=0.3,0.1

Type RM Length L Ch R = 1 ,42129   ,1507,1507,1507
BEGIN DESCRIPTION:
CEDAR BRANCH 44.0
END DESCRIPTION:
XS GIS Cut Line= 3
       3749673.9     10533168.04      3747903.04     10532994.42
      3745084.49     10534628.65
#Sta/Elev= 30
  2766.2  270.31  3071.9  270.16  3201.4   268.5  3694.9  267.33  4124.8  267.68
  4197.3  266.54  4984.3  266.91  4990.1  263.14  5000.1  263.01  5021.6  265.34
  5027.4  267.77    5035     267  5043.1  268.29  5048.9  268.89  5070.4  266.41
  5809.5  267.17  6226.6   265.9  6301.1  263.59  6526.4  266.19  7135.9  266.36
  7216.2   265.4  7237.8  264.42  7243.6  262.33  7256.3  261.64  7259.1  261.14
  7262.3  261.64  7280.8  263.75  7398.4  263.42  7537.6  266.42  7803.6  267.04
#Mann= 5 ,-1 , 0
  2766.2     .09       0  4990.1     .07       0  5043.1     .05       0
  7256.3     .07       0  7262.3     .05       0
Bank Sta=4984.3,5048.9
XS Rating Curve= 0 ,0
Exp/Cntr=0.3,0.1

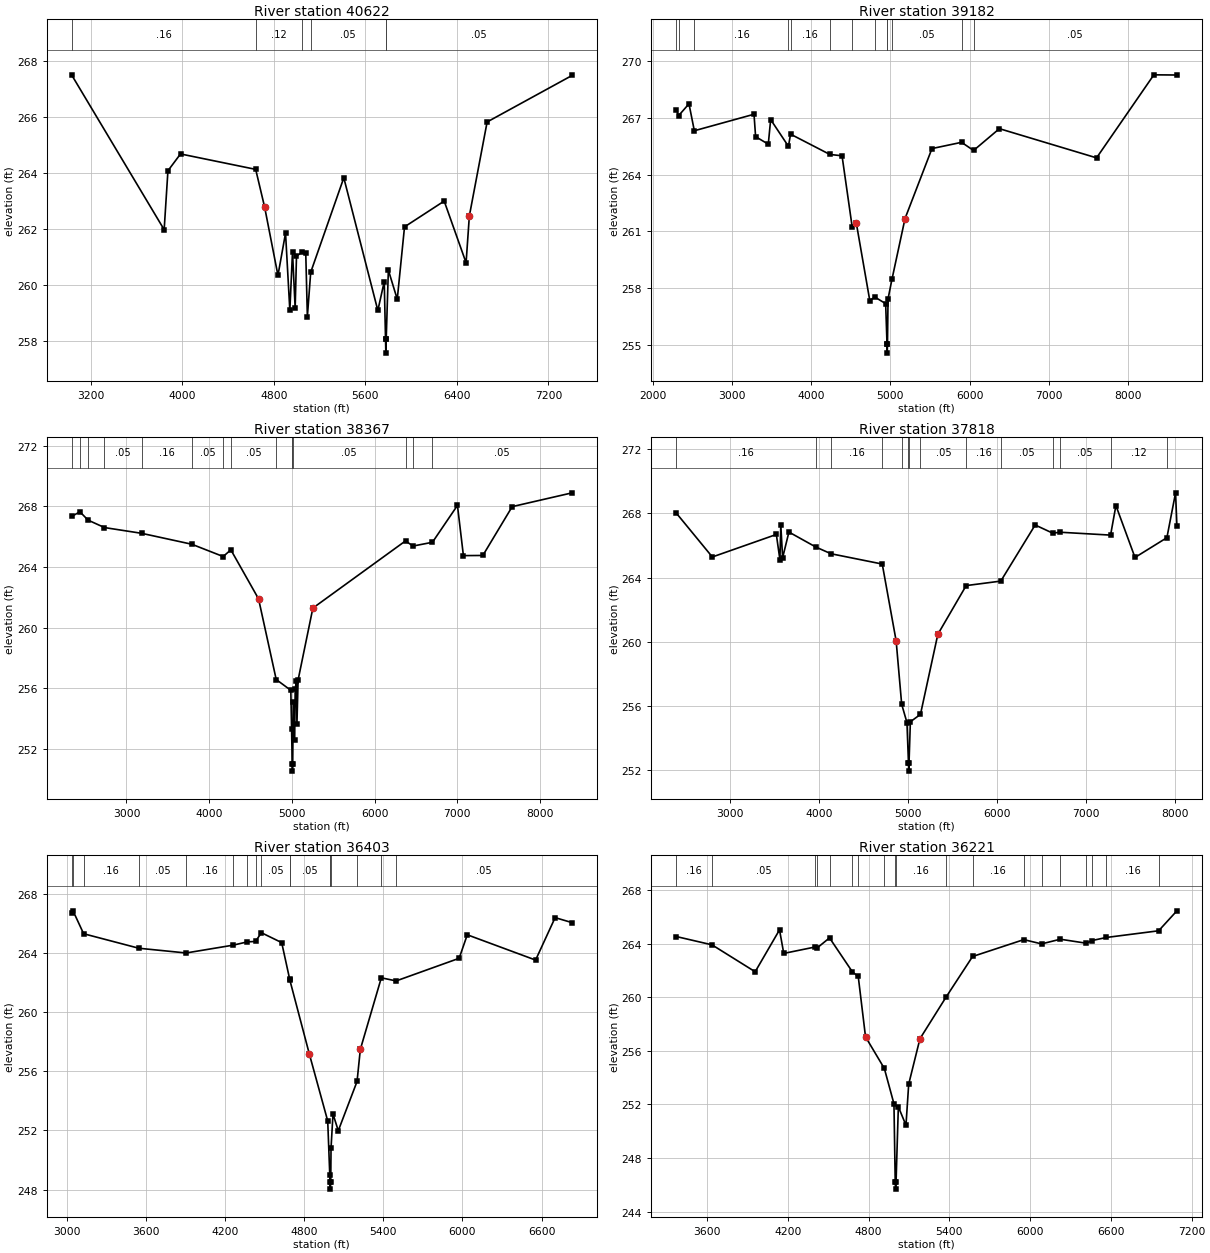
Type RM Length L Ch R = 1 ,40622   ,1440,1440,1440
BEGIN DESCRIPTION:
CEDAR BRANCH 42.0
END DESCRIPTION:
XS GIS Cut Line= 3
      3747999.64     10531960.18      3746199.61     10532760.19
      3744399.62     10534360.18
#Sta/Elev= 30
  3030.2  267.49    3840  261.97  3872.9  264.07    3983  264.67  4640.4  264.12
  4718.9  262.77  4835.2  260.34  4901.5  261.85  4939.1  259.09  4962.4  261.18
  4985.6  259.17  4997.3  261.03    5047  261.17  5078.2  261.15  5092.4  258.87
  5121.5  260.45    5411  263.82  5708.7  259.09  5764.7  260.12  5775.9  258.07
  5778.7  257.57  5781.9  258.07  5800.7  260.53  5878.5  259.49    5942  262.07
    6289  262.99  6480.5  260.79    6509  262.46  6664.5  265.81  7408.3  267.47
#Mann= 6 ,-1 , 0
  3030.2     .16       0  4640.4     .12       0    5047     .16       0
  5121.5     .05       0  5775.9     .07       0  5781.9     .05       0
Bank Sta=4718.9,6509
XS Rating Curve= 0 ,0
Exp/Cntr=0.3,0.1

Type RM Length L Ch R = 1 ,39182   ,815,815,815
BEGIN DESCRIPTION:
CEDAR BRANCH 41.0
END DESCRIPTION:
XS GIS Cut Line= 3
      3748849.61     10531760.19      3746149.61     10531760.19
      3743749.59      10534460.2
#Sta/Elev= 30
    2300  267.42  2329.6  267.11    2460  267.73  2527.4  266.31    3280  267.18
    3300     266    3460   265.6    3490   266.9  3713.9  265.49    3741  266.13
  4236.3  265.06    4390  264.99  4518.8  261.21    4570  261.44    4740  257.35
  4803.2  257.54    4940  257.19    4957  255.08  4959.7  254.58    4963  255.08
    4970  257.44  5019.3  258.47  5184.4  261.68  5523.9  265.37  5897.1   265.7
  6048.7  265.27  6374.3  266.42  7599.4  264.88  8321.9  269.26  8612.5  269.25
#Mann= 13 ,-1 , 0
    2300     .12       0  2329.6     .07       0  2527.4     .16       0
  3713.9     .05       0    3741     .16       0  4236.3     .05       0
  4518.8     .16       0  4803.2     .12       0    4957     .07       0
    4963     .12       0  5019.3     .05       0  5897.1     .16       0
  6048.7     .05       0
Bank Sta=4570,5184.4
XS Rating Curve= 0 ,0
Exp/Cntr=0.3,0.1

Type RM Length L Ch R = 1 ,38367   ,549,549,549
BEGIN DESCRIPTION:
CEDAR BRANCH 40.0
END DESCRIPTION:
XS GIS Cut Line= 3
      3748749.58     10531060.19      3746064.97     10531139.55
      3743949.64     10533760.15
#Sta/Elev= 30
  2336.4  267.32    2437  267.63    2536  267.08  2734.1  266.59    3184  266.21
  3790.3  265.49  4169.4  264.68  4262.7  265.12  4597.4  261.89    4811  256.57
  4987.5  255.86  4997.1  253.31  5004.5  251.03  5007.3  250.53  5010.5  251.03
  5017.4  255.11  5034.1  252.56  5040.5  255.92  5054.9  256.46  5061.6  253.61
  5075.7  256.54  5254.3  261.28  6374.7  265.71  6464.9  265.37  6700.3  265.62
  7002.7  268.05  7074.7  264.74  7309.7  264.75  7664.8  267.97    8390  268.88
#Mann= 15 ,-1 , 0
  2336.4     .16       0    2437     .05       0    2536     .16       0
  2734.1     .05       0    3184     .16       0  3790.3     .05       0
  4169.4     .16       0  4262.7     .05       0    4811     .12       0
  4997.1     .05       0  5004.5     .03       0  5010.5     .05       0
  6374.7     .07       0  6464.9     .16       0  6700.3     .05       0
Bank Sta=4597.4,5254.3
XS Rating Curve= 0 ,0
Exp/Cntr=0.3,0.1

Type RM Length L Ch R = 1 ,37818   ,1415,1415,1415
BEGIN DESCRIPTION:
CEDAR BRANCH 39.0
END DESCRIPTION:
XS GIS Cut Line= 3
      3748749.58     10530460.19      3746083.39     10530906.12
      3743349.58      10531960.2
#Sta/Elev= 30
  2391.3  268.01  2796.8  265.28  3517.2  266.68  3557.2  265.11  3567.4  267.26
  3587.7  265.23  3658.6  266.83  3964.3  265.89    4133  265.48  4708.9  264.84
  4865.2  260.06  4927.5  256.12  4986.8  254.98  5004.1  252.46  5006.9  251.96
  5010.1  252.46  5025.3  255.03  5138.9  255.49  5334.4  260.47  5653.2   263.5
  6042.8  263.78  6429.5  267.27  6628.1  266.76    6707  266.82  7278.2  266.64
  7338.3  268.48  7552.9  265.25  7911.9  266.48  8009.5  269.27  8024.5  267.23
#Mann= 14 ,-1 , 0
  2391.3     .16       0  3964.3     .05       0    4133     .16       0
  4708.9     .05       0  4927.5     .16       0  5004.1     .07       0
  5010.1     .16       0  5138.9     .05       0  5653.2     .16       0
  6042.8     .05       0  6628.1     .08       0    6707     .05       0
  7278.2     .12       0  7911.9     .05       0
Bank Sta=4865.2,5334.4
XS Rating Curve= 0 ,0
Exp/Cntr=0.3,0.1

Type RM Length L Ch R = 1 ,36403   ,182,182,182
BEGIN DESCRIPTION:
CEDAR BRANCH 38.0
END DESCRIPTION:
XS GIS Cut Line= 6
      3748131.25     10529966.69      3746992.39     10529883.36
        3746416.     10530091.69      3745964.61     10530154.19
      3745193.78     10530536.13      3744888.24     10531188.89
#Sta/Elev= 30
  3037.1  266.68  3048.1  266.85  3128.5   265.3    3547  264.32  3905.2     264
  4262.8  264.53  4369.4  264.75  4431.3  264.78    4476  265.37  4629.8   264.7
  4689.3  262.27  4692.1  262.15  4838.4   257.2  4978.7  252.64  4994.3  248.99
  4995.7  248.53  4998.5  248.03  5001.7  248.53  5003.8   250.8  5018.7  253.11
  5058.8  251.98    5201  255.31  5225.9  257.48    5385  262.32  5497.4  262.11
  5974.9  263.64  6036.6  265.23  6554.4  263.52  6702.4  266.39  6831.7  266.05
#Mann= 17 ,-1 , 0
  3037.1     .16       0  3048.1     .12       0  3128.5     .16       0
    3547     .05       0  3905.2     .16       0  4262.8      .1       0
  4369.4     .05       0  4431.3     .16       0    4476     .05       0
  4689.3     .08       0  4692.1     .05       0  4994.3     .16       0
  4995.7     .07       0  5001.7     .16       0    5201     .05       0
    5385     .16       0  5497.4     .05       0
Bank Sta=4838.4,5225.9
XS Rating Curve= 0 ,0
Exp/Cntr=0.3,0.1

Type RM Length L Ch R = 1 ,36221   ,1083,1083,1083
BEGIN DESCRIPTION:
CEDAR BRANCH 37.0
END DESCRIPTION:
XS GIS Cut Line= 6
      3747832.66     10529605.58      3747061.83     10529681.97
      3746409.06     10529918.08        3746166.     10529945.86
        3745416.     10529911.13      3744235.42     10530334.76
#Sta/Elev= 30
  3371.5  264.54  3636.8  263.92  3957.4  261.91  4138.3  265.04  4169.7  263.28
  4403.1  263.76  4419.1   263.7  4509.7  264.44  4679.8   261.9    4723  261.56
  4777.1  257.05  4916.9  254.69  4988.3  252.05  4997.8  246.18  5000.5  245.68
  5003.8  246.18  5020.9  251.83  5077.6  250.45  5097.8  253.52  5181.4  256.91
  5375.5  260.02  5572.3  263.05  5952.9  264.31  6084.7  263.99  6223.8  264.34
  6417.5  264.04  6459.2  264.24  6565.7  264.47  6954.4  264.97    7090  266.46
#Mann= 19 ,-1 , 0
  3371.5     .16       0  3636.8     .05       0  4403.1     .16       0
  4419.1     .08       0  4509.7     .05       0  4679.8     .08       0
    4723     .05       0  4916.9     .16       0  4997.8     .07       0
  5003.8     .16       0  5375.5     .12       0  5572.3     .16       0
  5952.9     .12       0  6084.7     .16       0  6223.8     .12       0
  6417.5     .16       0  6459.2     .12       0  6565.7     .16       0
  6954.4     .05       0
Bank Sta=4777.1,5181.4
XS Rating Curve= 0 ,0
Exp/Cntr=0.3,0.1

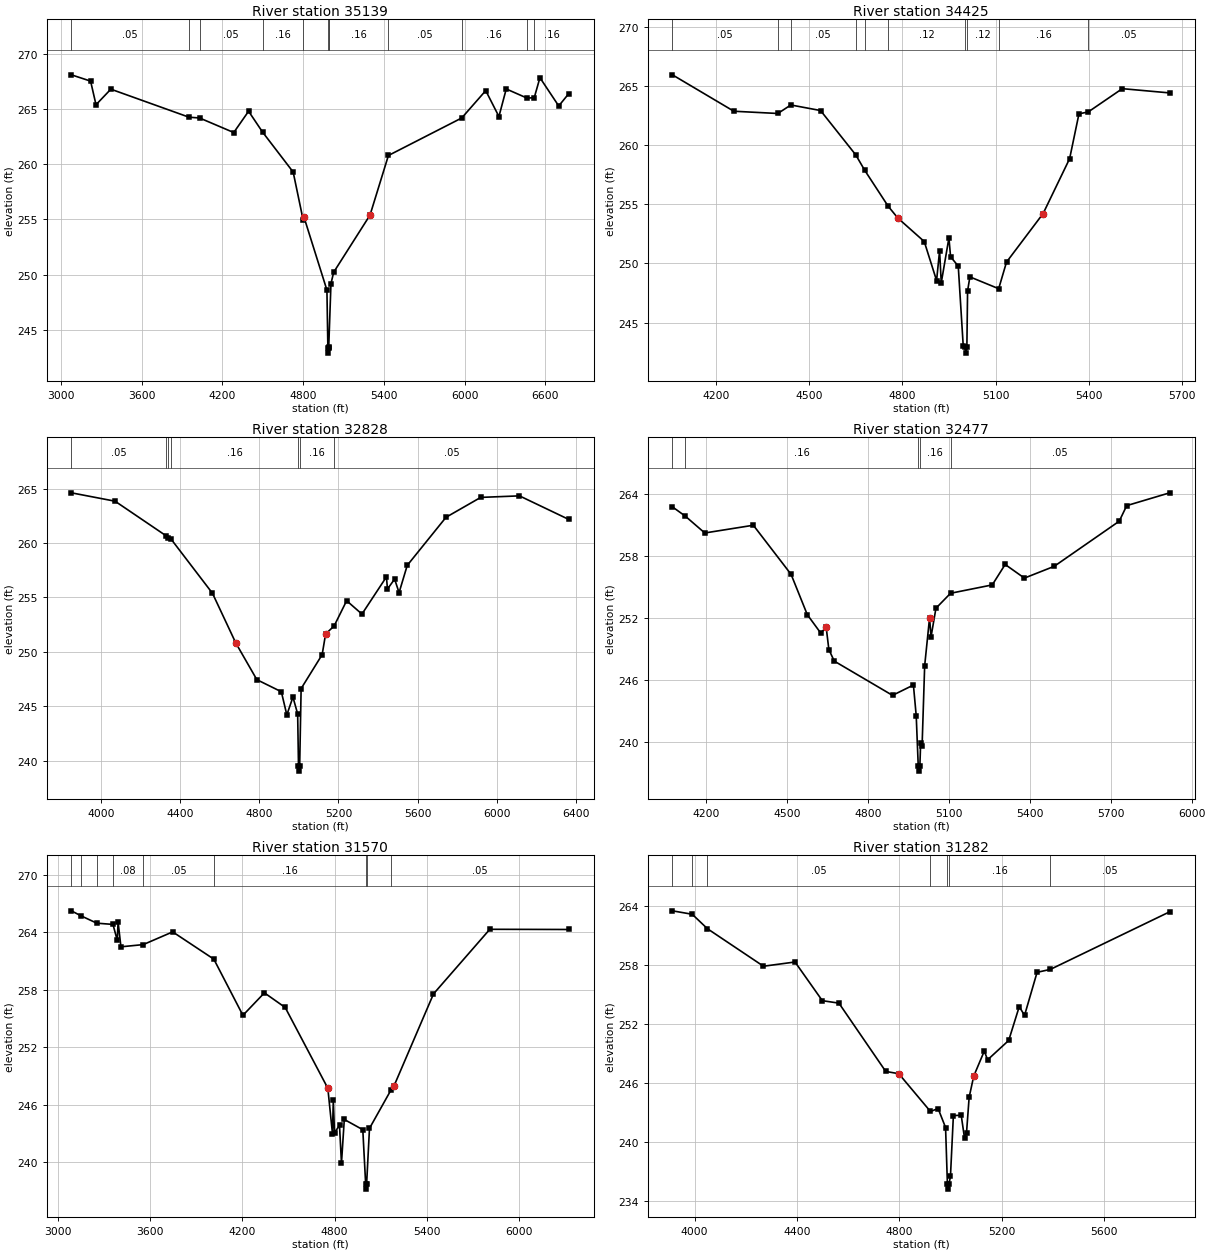
Type RM Length L Ch R = 1 ,35139   ,713,713,713
BEGIN DESCRIPTION:
CEDAR BRANCH 35.0
END DESCRIPTION:
XS GIS Cut Line= 3
      3748111.76     10529227.54      3746017.56     10529053.93
      3744553.63     10529682.88
#Sta/Elev= 30
    3078   268.1  3220.6  267.53  3260.8  265.39  3371.1   266.8    3952  264.26
  4030.2  264.19  4284.3  262.87  4394.6   264.8  4498.5  262.91  4725.8  259.29
  4799.5  254.98  4806.1  255.21  4976.6  248.59  4983.7  243.38  4986.4  242.88
  4989.7  243.38    4990  243.42  5006.7  249.18  5026.8  250.21  5296.9  255.39
  5433.5  260.79  5978.3  264.19  6156.7  266.67  6254.7  264.32  6309.1  266.82
  6461.9     266    6517  266.02  6559.4  267.84    6699  265.28  6772.7  266.38
#Mann= 12 ,-1 , 0
    3078     .05       0    3952     .16       0  4030.2     .05       0
  4498.5     .16       0  4799.5     .12       0  4983.7     .07       0
  4989.7     .12       0    4990     .16       0  5433.5     .05       0
  5978.3     .16       0  6461.9     .12       0    6517     .16       0
Bank Sta=4806.1,5296.9
XS Rating Curve= 0 ,0
Exp/Cntr=0.3,0.1

Type RM Length L Ch R = 1 ,34425   ,1597,1597,1597
BEGIN DESCRIPTION:
CEDAR BRANCH 34.0
END DESCRIPTION:
XS GIS Cut Line= 2
      3747312.79     10528914.57      3745819.74     10528341.66
#Sta/Elev= 30
  4060.9  265.95  4258.5  262.87  4399.8  262.68  4441.8   263.4  4537.3  262.93
  4650.5  259.18  4679.5  257.87  4754.9  254.83  4786.1  253.83  4870.8  251.85
  4910.5  248.55  4920.2  251.08  4925.5  248.35  4950.2  252.16  4955.5  250.56
  4980.2  249.77  4996.2  243.02  5001.9  242.91  5004.6  242.41  5007.9  242.91
  5010.2  247.67  5017.6  248.86  5110.2  247.86  5135.4  250.11  5253.2  254.22
  5338.4  258.86  5368.4  262.65  5398.2  262.81  5507.8  264.78  5660.1  264.42
#Mann= 10 ,-1 , 0
  4060.9     .05       0  4399.8     .16       0  4441.8     .05       0
  4650.5     .16       0  4679.5     .05       0  4754.9     .12       0
  5001.9     .07       0  5007.9     .12       0  5110.2     .16       0
  5398.2     .05       0
Bank Sta=4786.1,5253.2
XS Rating Curve= 0 ,0
Exp/Cntr=0.3,0.1

Type RM Length L Ch R = 1 ,32828   ,351,351,351
BEGIN DESCRIPTION:
CEDAR BRANCH 33.0
END DESCRIPTION:
XS GIS Cut Line= 3
      3748076.68     10527629.84       3747295.4     10527490.95
      3745628.73     10527907.62
#Sta/Elev= 30
  3851.2  264.62  4071.7  263.85  4329.5  260.67  4337.5  260.49  4354.4  260.37
  4563.8  255.38  4681.6  250.81  4787.9  247.44  4911.6  246.33  4939.3   244.2
  4970.2  245.84    4994  244.29  4998.2  239.53  5000.9  239.03  5004.2  239.53
  5011.5  246.62  5117.7  249.74  5135.2  251.64  5178.3  252.38  5241.4   254.7
  5318.7  253.47  5442.4  256.89  5447.6  255.77  5483.7  256.69  5506.2  255.44
  5547.5  257.95  5743.3  262.37  5918.6   264.2  6114.4  264.34  6362.7  262.18
#Mann= 7 ,-1 , 0
  3851.2     .05       0  4329.5     .16       0  4337.5     .05       0
  4354.4     .16       0  4998.2     .07       0  5004.2     .16       0
  5178.3     .05       0
Bank Sta=4681.6,5135.2
XS Rating Curve= 0 ,0
Exp/Cntr=0.3,0.1

Type RM Length L Ch R = 1 ,32477   ,907,907,907
BEGIN DESCRIPTION:
CEDAR BRANCH 32.0
END DESCRIPTION:
XS GIS Cut Line= 3
      3747799.56     10527210.19      3746989.84     10527213.17
      3745999.65     10527510.18
#Sta/Elev= 30
  4074.9  262.77  4122.7  261.87  4194.9  260.24  4374.9  260.99  4514.9  256.23
  4574.9  252.33  4624.9  250.54  4644.9  251.12  4654.9  248.95  4674.9  247.83
  4890.9  244.51  4968.4  245.51  4978.8  242.53  4986.3  237.67    4989  237.17
  4992.3  237.67  4995.3  239.94  5000.5  239.57  5010.1  247.38  5028.3  252.03
  5033.6  250.16  5051.9  252.95  5106.1   254.4  5260.7  255.21  5308.5  257.19
  5379.9  255.87  5490.4  257.01  5731.4  261.38  5759.2  262.89  5918.4  264.13
#Mann= 5 ,-1 , 0
  4074.9     .05       0  4122.7     .16       0  4986.3     .07       0
  4992.3     .16       0  5106.1     .05       0
Bank Sta=4644.9,5028.3
XS Rating Curve= 0 ,0
Exp/Cntr=0.3,0.1

Type RM Length L Ch R = 1 ,31570   ,288,288,288
BEGIN DESCRIPTION:
CEDAR BRANCH 31.0
END DESCRIPTION:
XS GIS Cut Line= 3
       3748649.6     10527360.18      3746864.84     10526615.95
      3745684.48     10527164.47
#Sta/Elev= 30
  3088.1  266.26  3147.7  265.76  3253.2  264.97  3358.6  264.84  3386.5  263.17
  3391.9   265.1  3410.3   262.5  3555.3  262.73  3747.1  264.06  4014.8  261.21
  4204.1  255.34  4343.9  257.69  4479.2  256.16  4756.6  247.72  4786.8  242.97
  4792.2  246.48    4800  243.07  4832.5  243.84  4845.3  239.89  4863.7  244.46
  4984.1  243.39  5002.8  237.68  5005.6  237.18  5008.8  237.68  5027.6  243.53
  5165.8  247.49  5186.8  247.95  5444.1  257.58  5810.5  264.33  6323.4  264.31
#Mann= 9 ,-1 , 0
  3088.1     .05       0  3147.7     .08       0  3253.2     .05       0
  3358.6     .08       0  3555.3     .05       0  4014.8     .16       0
  5002.8     .07       0  5008.8     .16       0  5165.8     .05       0
Bank Sta=4756.6,5186.8
XS Rating Curve= 0 ,0
Exp/Cntr=0.3,0.1

Type RM Length L Ch R = 1 ,31282   ,720,720,720
BEGIN DESCRIPTION:
CEDAR BRANCH 30.0
END DESCRIPTION:
XS GIS Cut Line= 3
      3747899.61     10526210.19      3746799.61     10526410.19
      3745999.57      10526610.2
#Sta/Elev= 30
  3913.5  263.51  3990.9  263.16  4050.4  261.69  4269.2  257.88  4392.5  258.31
  4499.2  254.38    4564  254.13  4746.9  247.19  4797.8  246.96  4921.7  243.12
  4951.5  243.42  4980.7  241.49  4987.9  235.73  4990.6  235.23  4993.9  235.73
  4999.8  236.52  5011.2   242.7  5041.8  242.74  5054.7  240.42  5062.5  240.94
  5072.8  244.56  5090.8  246.72    5132  249.26  5144.9  248.37  5227.4  250.34
  5268.6  253.78  5289.2  252.88  5338.2  257.26  5390.2  257.56  5856.2  263.41
#Mann= 7 ,-1 , 0
  3913.5     .05       0  3990.9     .16       0  4050.4     .05       0
  4921.7     .16       0  4987.9     .07       0  4993.9     .16       0
  5390.2     .05       0
Bank Sta=4797.8,5090.8
XS Rating Curve= 0 ,0
Exp/Cntr=0.3,0.1