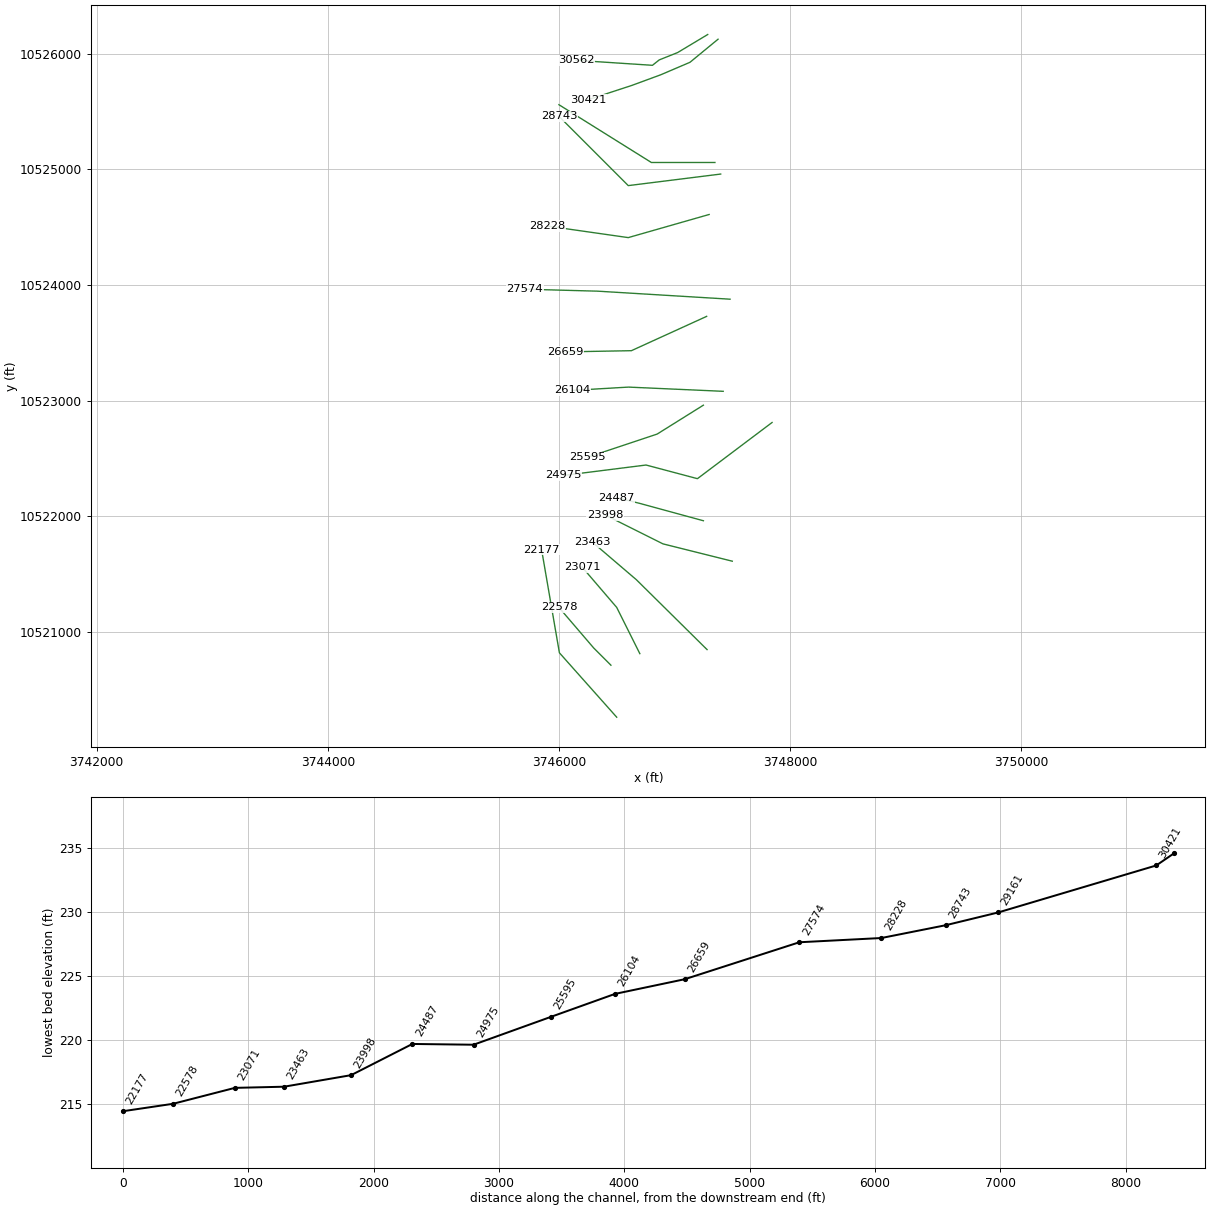
HEC-RAS study CEDAR BRANCH.prj: CEDAR BRANCH Base Level Engineering

--- CEDAR BRANCH.g01 (geometry) --- (continued)

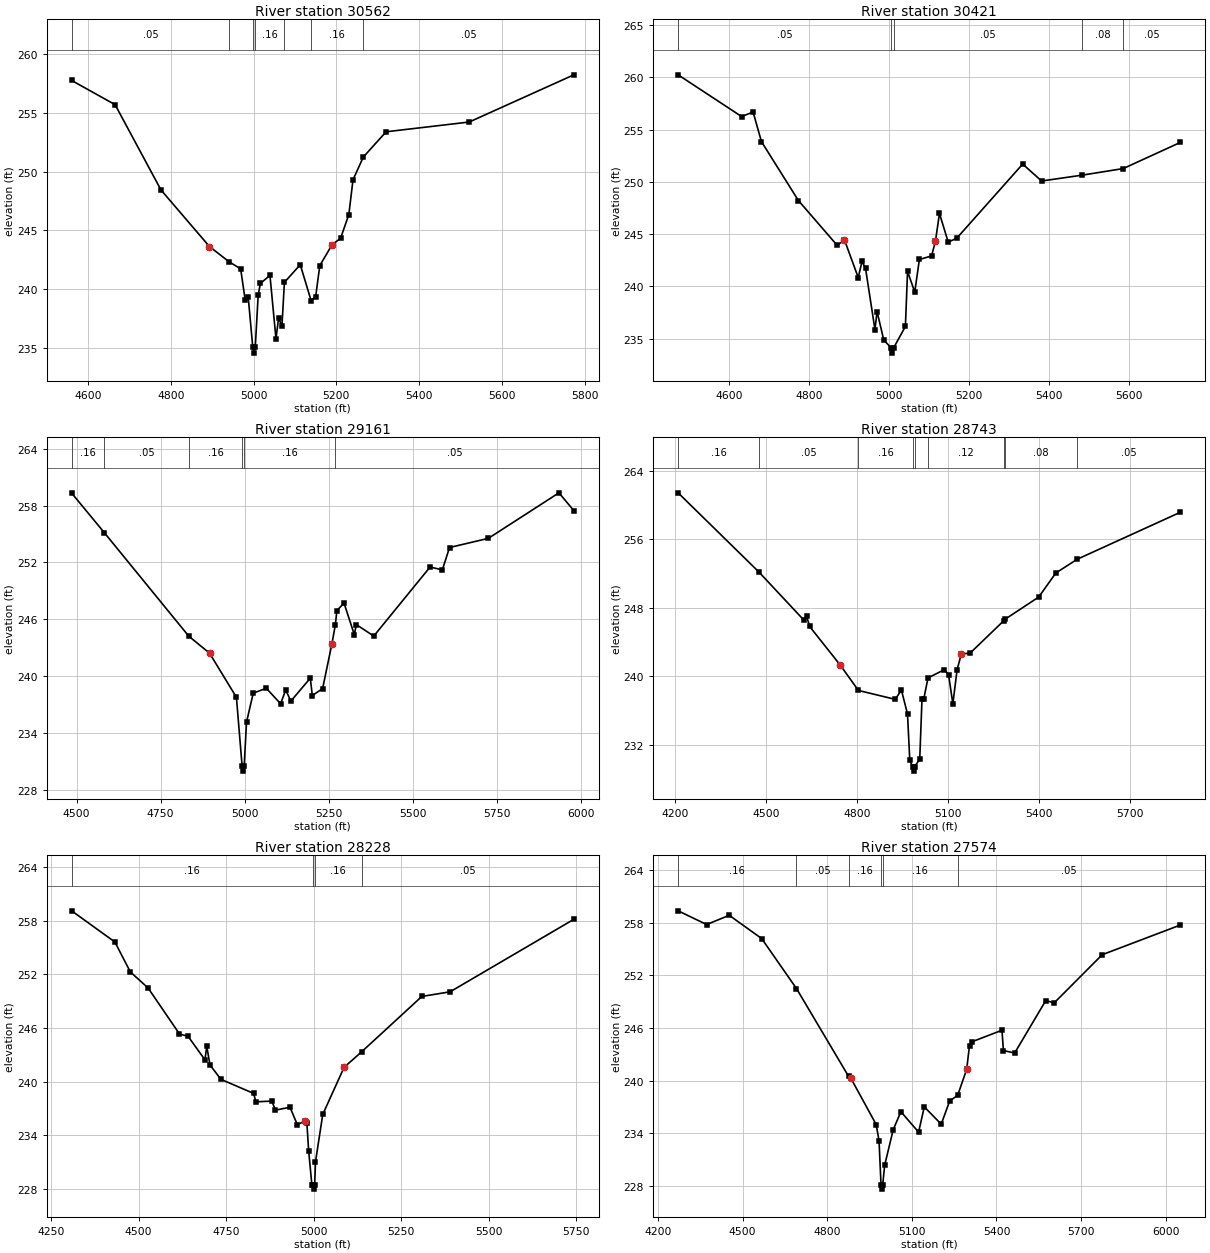
Type RM Length L Ch R = 1 ,30562   ,141,141,141
BEGIN DESCRIPTION:
CEDAR BRANCH 28.0
END DESCRIPTION:
XS GIS Cut Line= 5
      3747287.09     10526167.64      3747026.68      10526011.4
      3746867.82     10525948.03       3746808.8     10525901.15
      3746147.31     10525944.56
#Sta/Elev= 30
  4560.6  257.77  4665.5  255.71  4776.3  248.45  4893.4  243.63  4941.6  242.31
  4968.8  241.73  4979.6  239.11    4987  239.35  4998.1  235.05  5000.8  234.55
  5004.1  235.05  5011.2  239.51  5016.6  240.49  5039.6  241.17  5054.1  235.78
  5060.5  237.54  5068.5  236.84  5074.5  240.58  5112.8  242.08    5139  239.02
    5150  239.36    5160  242.01    5190   243.8  5210.1  244.32  5230.1  246.35
  5240.2  249.31  5265.1  251.25  5320.2   253.4  5520.8  254.23  5773.6  258.25
#Mann= 7 ,-1 , 0
  4560.6     .05       0  4941.6     .16       0  4998.1     .07       0
  5004.1     .16       0  5074.5     .05       0    5139     .16       0
  5265.1     .05       0
Bank Sta=4893.4,5190
XS Rating Curve= 0 ,0
Exp/Cntr=0.3,0.1

Type RM Length L Ch R = 1 ,30421   ,1261,1261,1261
BEGIN DESCRIPTION:
CEDAR BRANCH 27.0
END DESCRIPTION:
XS GIS Cut Line= 5
       3747376.5     10526126.84      3747133.45     10525927.19
      3746881.71     10525819.55      3746631.71     10525727.54
      3746249.76     10525602.54
#Sta/Elev= 30
  4472.6  260.24  4631.5  256.25  4660.2  256.68  4681.1  253.85  4773.6  248.21
  4870.7  243.92  4888.9  244.44  4923.3  240.84  4932.7  242.38  4941.5  241.74
  4965.1  235.87  4970.5  237.58  4987.1  234.87  5005.8  234.11  5008.6  233.61
  5011.8  234.11  5041.3  236.16  5046.7  241.43  5064.7  239.45  5076.3  242.57
  5106.8  242.91  5116.4   244.3  5126.6  246.98  5148.4  244.23  5169.7   244.6
  5334.8   251.7  5382.1  250.08  5483.6  250.64  5586.4  251.27  5729.2  253.77
#Mann= 5 ,-1 , 0
  4472.6     .05       0  5005.8     .04       0  5011.8     .05       0
  5483.6     .08       0  5586.4     .05       0
Bank Sta=4888.9,5116.4
XS Rating Curve= 0 ,0
Exp/Cntr=0.3,0.1

Type RM Length L Ch R = 1 ,29161   ,417,417,417
BEGIN DESCRIPTION:
CEDAR BRANCH 26.0
END DESCRIPTION:
XS GIS Cut Line= 3
      3747349.57     10525060.19      3746799.61     10525060.19
      3745999.58     10525560.21
#Sta/Elev= 30
  4485.4  259.33  4582.3  255.16  4833.7  244.21  4895.4  242.42  4975.4  237.75
  4992.4  230.45  4995.1  229.95  4998.4  230.45  5005.4  235.12  5025.4  238.19
  5064.3  238.71  5106.7  237.07    5122  238.52  5137.4  237.35  5195.1  239.78
    5201  237.94  5231.7  238.67  5259.4  243.41  5269.5   245.4  5274.2  246.92
  5295.4  247.71    5326  244.37  5331.9  245.44  5383.8  244.22  5551.3  251.52
  5587.8  251.22  5609.1  253.58  5724.6  254.55  5934.5  259.36  5978.8  257.48
#Mann= 6 ,-1 , 0
  4485.4     .16       0  4582.3     .05       0  4833.7     .16       0
  4992.4     .07       0  4998.4     .16       0  5269.5     .05       0
Bank Sta=4895.4,5259.4
XS Rating Curve= 0 ,0
Exp/Cntr=0.3,0.1

Type RM Length L Ch R = 1 ,28743   ,515,515,515
BEGIN DESCRIPTION:
CEDAR BRANCH 25.0
END DESCRIPTION:
XS GIS Cut Line= 3
      3747399.64     10524960.19      3746599.61     10524860.19
       3745999.6      10525460.2
#Sta/Elev= 30
  4211.2  261.42    4477   252.2  4624.4  246.62  4634.5  247.04  4644.6  245.83
  4745.4  241.33  4805.2  238.37  4926.8  237.33  4946.9  238.43  4967.1  235.62
  4974.6   230.2  4984.2  229.46    4987  228.96  4990.2  229.46  5007.4  230.36
  5014.9  237.43    5021  237.43  5034.6  239.83  5088.2  240.79  5102.3  240.23
  5116.5  236.81  5130.6  240.81  5144.7  242.64    5173  242.71  5284.5  246.51
  5287.9  246.66  5399.3  249.26  5455.9  252.07  5526.1  253.67    5866  259.15
#Mann= 9 ,-1 , 0
  4211.2     .16       0    4477     .05       0  4805.2     .16       0
  4984.2     .07       0  4990.2     .16       0  5034.6     .12       0
  5284.5     .16       0  5287.9     .08       0  5526.1     .05       0
Bank Sta=4745.4,5144.7
XS Rating Curve= 0 ,0
Exp/Cntr=0.3,0.1

Type RM Length L Ch R = 1 ,28228   ,654,654,654
BEGIN DESCRIPTION:
CEDAR BRANCH 24.0
END DESCRIPTION:
XS GIS Cut Line= 3
      3747299.59     10524610.18      3746599.61     10524410.19
      3745899.61     10524510.19
#Sta/Elev= 30
  4308.5  259.13    4432  255.64  4476.2  252.29  4526.9  250.49  4616.6  245.34
  4641.3  245.07  4689.4  242.44  4694.6  243.96  4703.7  241.88  4734.9  240.26
  4828.5  238.68    4835  237.74  4880.5  237.82  4890.9  236.81  4932.5  237.13
  4953.3  235.19  4974.1  235.55  4980.6  235.42  4985.8  232.25  4994.9  228.46
    4997  228.46  4999.8  227.96    5003  228.46  5005.3  231.02  5026.1  236.33
    5087   241.6  5137.5  243.35  5309.2  249.54    5390  250.06  5743.6  258.18
#Mann= 4 ,-1 , 0
  4308.5     .16       0    4997     .07       0    5003     .16       0
  5137.5     .05       0
Bank Sta=4974.1,5087
XS Rating Curve= 0 ,0
Exp/Cntr=0.3,0.1

Type RM Length L Ch R = 1 ,27574   ,915,915,915
BEGIN DESCRIPTION:
CEDAR BRANCH 23.0
END DESCRIPTION:
XS GIS Cut Line= 3
      3747480.49     10523877.28      3746334.69     10523946.73
      3745702.83     10523964.04
#Sta/Elev= 30
  4271.7  259.33  4372.8  257.77  4452.9  258.82  4567.9  256.17  4691.2  250.48
  4875.8  240.48  4883.7  240.28  4973.9  234.98  4983.9  233.12  4990.9  228.13
  4993.7  227.63  4996.9  228.13  5003.9  230.36    5034  234.39  5061.3  236.45
  5124.1  234.12  5144.2     237  5204.3  235.03  5234.3  237.68  5262.4   238.3
  5294.5  241.27  5304.5  243.99  5314.5  244.43  5419.6  245.73  5424.7  243.41
  5464.7  243.14  5574.7   249.1  5604.8  248.85  5774.8  254.33  6051.7  257.71
#Mann= 6 ,-1 , 0
  4271.7     .16       0  4691.2     .05       0  4875.8     .16       0
  4990.9     .07       0  4996.9     .16       0  5262.4     .05       0
Bank Sta=4883.7,5294.5
XS Rating Curve= 0 ,0
Exp/Cntr=0.3,0.1

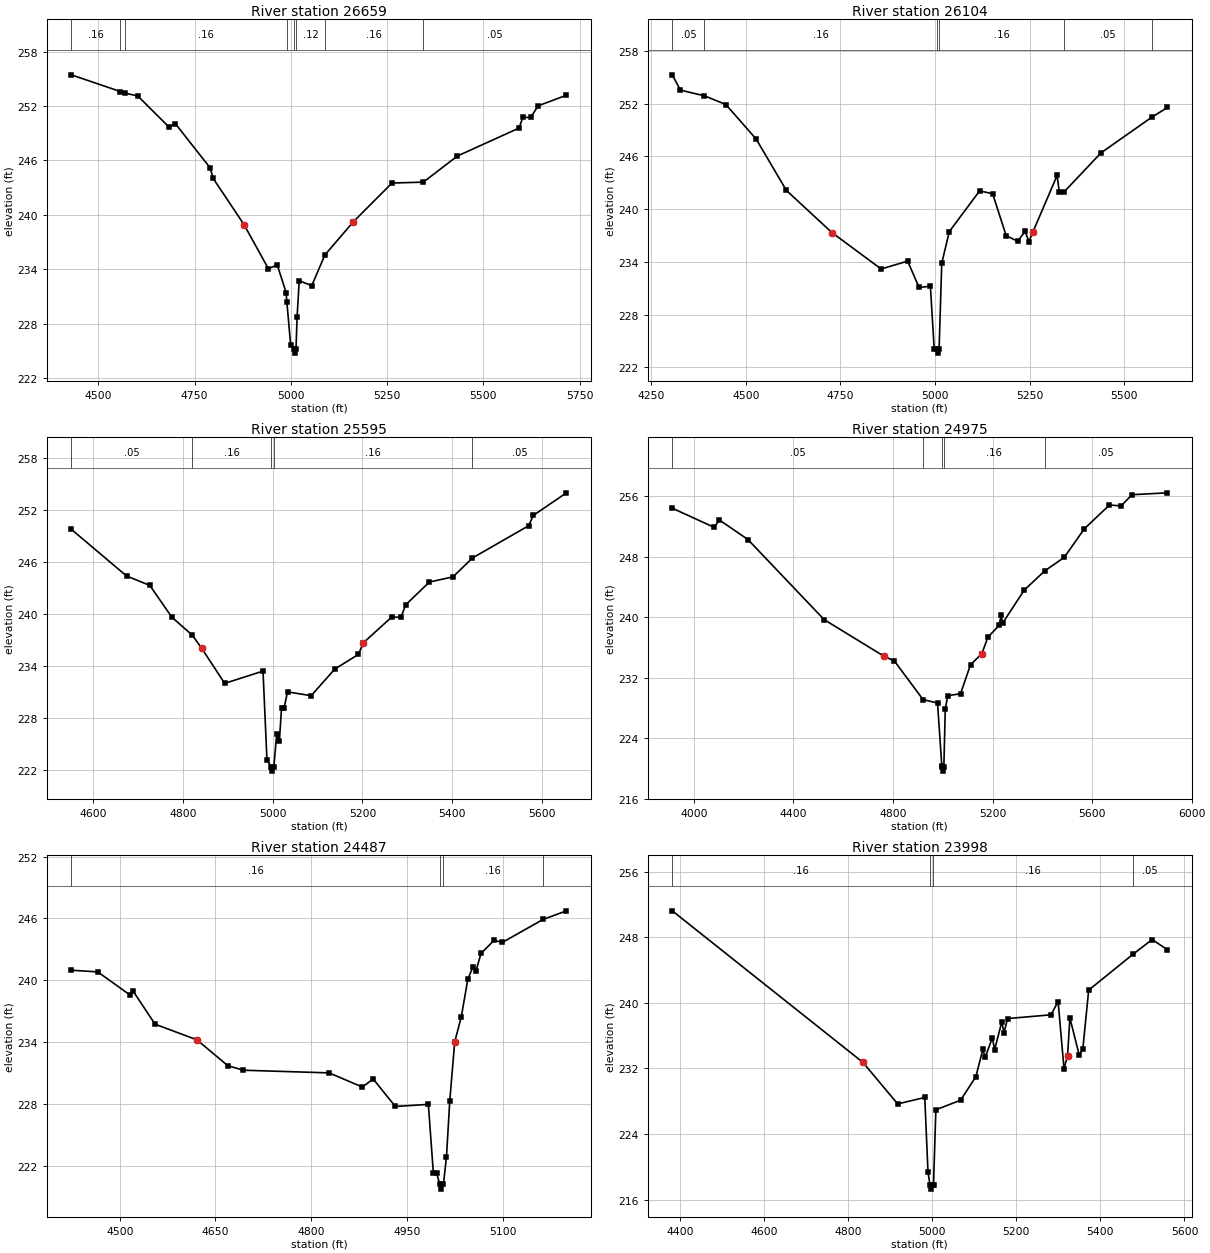
Type RM Length L Ch R = 1 ,26659   ,555,555,555
BEGIN DESCRIPTION:
CEDAR BRANCH 21.0
END DESCRIPTION:
XS GIS Cut Line= 3
      3747277.85     10523728.63      3746626.79     10523431.75
      3746056.44     10523421.33
#Sta/Elev= 30
  4429.7  255.43  4557.1  253.59  4570.2   253.4  4602.4   253.1  4682.5  249.71
  4700.1  250.04  4790.5  245.16  4797.7  244.04  4878.4  238.91  4941.5  234.06
  4964.5  234.48  4987.6  231.43  4989.6  230.36  4999.3  225.69  5007.3  225.25
    5010  224.75  5013.3  225.25  5016.1  228.74  5021.6  232.73  5054.2  232.19
  5088.3  235.57  5162.4  239.24  5262.5   243.5    5344   243.6  5432.5  246.48
  5592.5  249.56  5602.5  250.74  5622.5  250.73  5642.5  252.02  5715.7  253.18
#Mann= 8 ,-1 , 0
  4429.7     .16       0  4557.1     .05       0  4570.2     .16       0
  4989.6     .12       0  5007.3     .07       0  5013.3     .12       0
  5088.3     .16       0    5344     .05       0
Bank Sta=4878.4,5162.4
XS Rating Curve= 0 ,0
Exp/Cntr=0.3,0.1

Type RM Length L Ch R = 1 ,26104   ,509,509,509
BEGIN DESCRIPTION:
CEDAR BRANCH 20.0
END DESCRIPTION:
XS GIS Cut Line= 3
      3747421.03     10523080.19      3746600.75     10523116.65
      3746114.19     10523088.03
#Sta/Elev= 30
  4305.5   255.3  4326.9  253.56  4390.5  252.91  4447.1  251.92  4527.1  247.99
  4607.2  242.13  4727.3  237.34  4857.5  233.19  4927.5  234.09  4957.6  231.09
  4987.6  231.23  4997.6  224.13  5004.6  224.11  5007.4  223.61  5010.6  224.11
  5017.6  233.85  5037.6  237.45  5117.7  242.09  5152.1  241.76  5187.8  236.99
  5217.9  236.35  5237.9  237.46  5247.9  236.32    5258  237.36  5322.4  243.84
  5328.1  242.01  5340.5  241.95  5438.3  246.41  5572.2  250.46    5614  251.58
#Mann= 6 ,-1 , 0
  4305.5     .05       0  4390.5     .16       0  5004.6     .07       0
  5010.6     .16       0  5340.5     .05       0  5572.2     .16       0
Bank Sta=4727.3,5258
XS Rating Curve= 0 ,0
Exp/Cntr=0.3,0.1

Type RM Length L Ch R = 1 ,25595   ,620,620,620
BEGIN DESCRIPTION:
CEDAR BRANCH 19.0
END DESCRIPTION:
XS GIS Cut Line= 3
      3747249.61     10522960.19      3746849.61     10522710.19
      3746249.57     10522510.17
#Sta/Elev= 30
  4550.8  249.75    4674  244.36  4725.9  243.27  4774.9  239.61  4820.9  237.51
  4841.5  236.02  4892.8  231.96  4978.3  233.38  4987.1  223.13  4996.5  222.33
  4999.3  221.83  5002.5  222.33  5008.9  226.15  5014.8  225.31  5019.6  229.09
  5025.1  229.09    5033  230.98  5085.7  230.54  5138.5  233.62  5191.2  235.31
  5201.7  236.63  5264.9   239.6    5286   239.6  5296.6  241.04  5349.3  243.66
    5402  244.26  5445.4  246.44  5570.6  250.16  5581.2  251.36    5655  253.96
#Mann= 5 ,-1 , 0
  4550.8     .05       0  4820.9     .16       0  4996.5     .07       0
  5002.5     .16       0  5445.4     .05       0
Bank Sta=4841.5,5201.7
XS Rating Curve= 0 ,0
Exp/Cntr=0.3,0.1

Type RM Length L Ch R = 1 ,24975   ,488,488,488
BEGIN DESCRIPTION:
CEDAR BRANCH 18.0
END DESCRIPTION:
XS GIS Cut Line= 4
      3747844.02     10522810.41      3747198.18     10522324.28
      3746753.73     10522442.34      3746038.42     10522352.06
#Sta/Elev= 30
  3913.5   254.4  4081.7  251.87  4102.8  252.84  4217.3  250.26  4523.4  239.68
  4765.6   234.8  4805.8  234.21    4921   229.1    4979  228.65  4996.3  220.38
  4998.5  220.15  5001.2  219.65  5004.5  220.15  5010.1  227.86  5020.4  229.62
  5071.5  229.88  5111.6  233.72    5157  235.16  5181.3  237.34  5226.2   238.9
    5235  240.32  5240.1  239.18    5327  243.56  5410.3  246.13  5488.2   247.9
  5568.9  251.68  5669.7  254.82  5716.5   254.7  5760.4  256.18  5902.7  256.43
#Mann= 5 ,-1 , 0
  3913.5     .05       0    4921     .16       0  4998.5     .07       0
  5004.5     .16       0  5410.3     .05       0
Bank Sta=4765.6,5157
XS Rating Curve= 0 ,0
Exp/Cntr=0.3,0.1

Type RM Length L Ch R = 1 ,24487   ,489,489,489
BEGIN DESCRIPTION:
CEDAR BRANCH 17.0
END DESCRIPTION:
XS GIS Cut Line= 3
      3747249.59     10521960.19      3746699.61     10522110.19
      3746499.63     10522160.18
#Sta/Elev= 30
    4424  240.97  4465.4  240.81  4515.5  238.59  4520.7  238.96  4555.3  235.73
  4620.9  234.21  4669.3   231.7  4693.5  231.26  4828.2     231  4880.1  229.63
  4897.3   230.4  4931.9  227.74  4983.7  227.94  4991.5  221.31  4996.6  221.31
  5001.4  220.21  5004.1  219.71  5007.4  220.21  5012.1  222.86  5017.3  228.31
    5025  234.01  5035.3  236.44  5045.6   240.1  5053.3  241.25  5058.5  240.93
  5066.2   242.6  5086.8  243.88  5099.7  243.67  5163.3   245.9  5200.2  246.74
#Mann= 4 ,-1 , 0
    4424     .16       0  5001.4     .07       0  5007.4     .16       0
  5163.3     .05       0
Bank Sta=4620.9,5025
XS Rating Curve= 0 ,0
Exp/Cntr=0.3,0.1

Type RM Length L Ch R = 1 ,23998   ,535,535,535
BEGIN DESCRIPTION:
CEDAR BRANCH 16.0
END DESCRIPTION:
XS GIS Cut Line= 3
      3747499.59     10521610.19      3746899.61     10521760.19
      3746399.58      10522010.2
#Sta/Elev= 30
    4382  251.22  4835.5  232.73    4918  227.67  4982.4  228.46  4990.1  219.36
  4994.9  217.78  4997.6  217.28  5000.9  217.78  5003.2  217.78  5008.8  226.96
  5067.5  228.12  5103.9  230.99  5120.6  234.32  5126.2  233.37    5143  235.71
  5148.6   234.3  5165.4  237.65  5170.9  236.38  5179.3  238.08  5282.7  238.54
  5299.5  240.16  5313.5  231.99  5321.9   233.5  5327.5  238.16  5349.8  233.61
  5358.2  234.33  5372.2  241.55  5477.5  245.92  5523.1  247.72  5559.5  246.47
#Mann= 4 ,-1 , 0
    4382     .16       0  4994.9     .07       0  5000.9     .16       0
  5477.5     .05       0
Bank Sta=4835.5,5321.9
XS Rating Curve= 0 ,0
Exp/Cntr=0.3,0.1

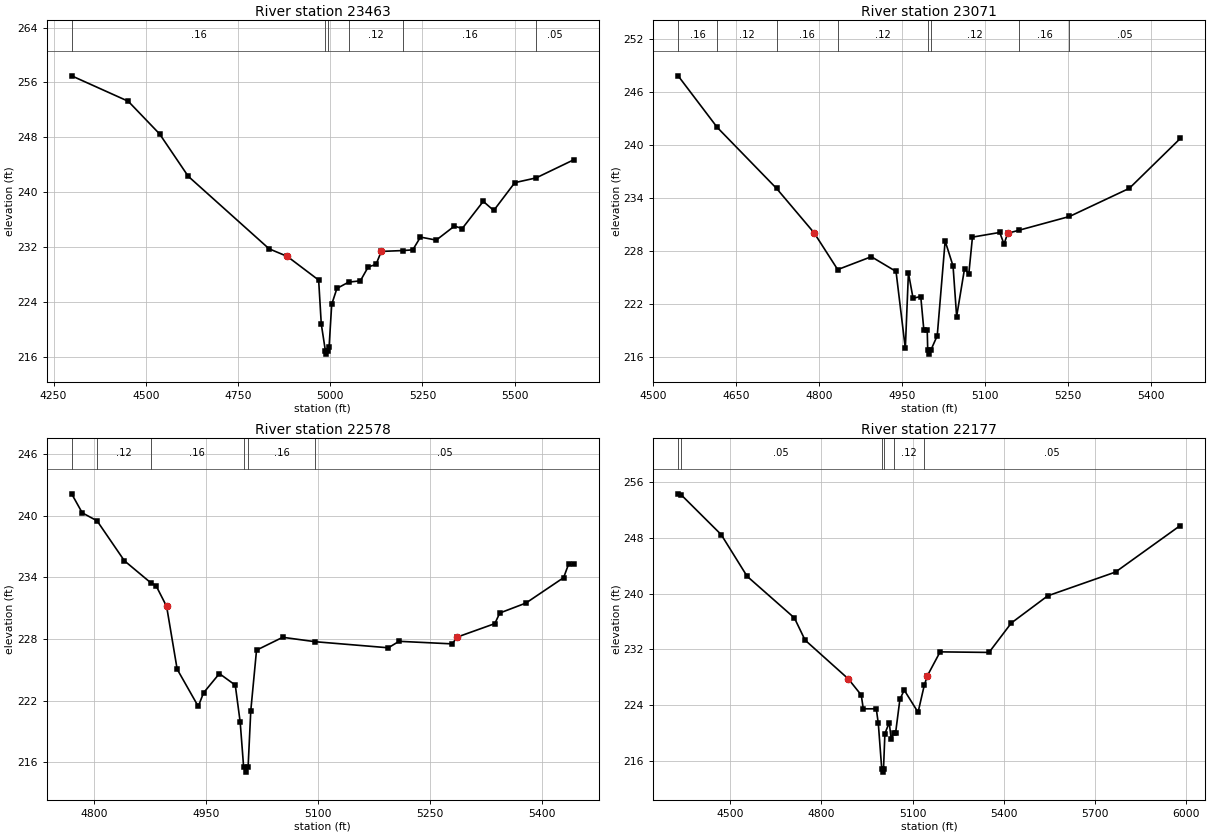
Type RM Length L Ch R = 1 ,23463   ,392,392,392
BEGIN DESCRIPTION:
CEDAR BRANCH 15.0
END DESCRIPTION:
XS GIS Cut Line= 3
      3747281.49     10520845.13       3746670.4     10521449.28
       3746288.7     10521775.46
#Sta/Elev= 30
  4299.1  256.97  4452.5  253.26  4537.4   248.5  4615.1  242.32  4834.4  231.74
  4883.8  230.63  4968.7  227.18  4975.8  220.78  4986.9  216.88  4989.7  216.38
  4992.9  216.88    4997  217.43  5004.1  223.64  5018.2  225.96  5049.9  226.88
  5081.8  227.07  5103.1   229.1  5124.3  229.46  5138.4  231.36  5198.7  231.49
  5223.9  231.59  5244.7  233.45  5287.5  233.01  5336.9  235.06  5357.8  234.69
  5414.9  238.66  5443.4  237.33  5500.5  241.39  5558.1  242.08  5660.5  244.73
#Mann= 6 ,-1 , 0
  4299.1     .16       0  4986.9     .07       0  4992.9     .16       0
  5049.9     .12       0  5198.7     .16       0  5558.1     .05       0
Bank Sta=4883.8,5138.4
XS Rating Curve= 0 ,0
Exp/Cntr=0.3,0.1

Type RM Length L Ch R = 1 ,23071   ,493,493,493
BEGIN DESCRIPTION:
CEDAR BRANCH 14.0
END DESCRIPTION:
XS GIS Cut Line= 3
      3746699.61     10520810.18      3746499.61     10521210.19
      3746199.61     10521560.19
#Sta/Elev= 30
  4545.3  247.83  4616.1  241.98  4723.3  235.07  4791.3  230.03  4833.9  225.87
  4894.7  227.33  4939.4  225.66  4956.2  216.93  4961.8  225.49  4970.2  222.62
  4984.1  222.82  4989.7  219.02  4995.8  219.02  4996.7  216.79  4999.4  216.29
  5002.7  216.79  5013.9  218.37  5028.2  229.11  5042.5  226.28    5049  220.55
  5063.3  225.98    5071  225.38  5077.6  229.55    5127  230.08  5134.7  228.75
  5141.2  229.98  5162.3  230.34  5253.1  231.89  5361.3  235.08  5453.5  240.73
#Mann= 8 ,-1 , 0
  4545.3     .16       0  4616.1     .12       0  4723.3     .16       0
  4833.9     .12       0  4996.7     .07       0  5002.7     .12       0
  5162.3     .16       0  5253.1     .05       0
Bank Sta=4791.3,5141.2
XS Rating Curve= 0 ,0
Exp/Cntr=0.3,0.1

Type RM Length L Ch R = 1 ,22578   ,401,401,401
BEGIN DESCRIPTION:
CEDAR BRANCH 13.0
END DESCRIPTION:
XS GIS Cut Line= 3
      3746449.62     10520710.18      3746299.61     10520860.19
      3745999.62     10521210.17
#Sta/Elev= 30
    4770  242.11  4784.2  240.26    4804  239.49  4840.7   235.6  4875.9  233.47
  4883.1  233.18  4897.3  231.16  4911.4  225.06  4939.7  221.44  4946.8  222.76
    4968  224.63  4989.3  223.51  4995.9  219.91  5000.5  215.55  5003.3  215.05
  5006.5  215.55  5010.1  221.03  5017.8  226.91  5052.9  228.16  5096.5  227.73
  5194.5  227.14  5208.8  227.77  5280.1  227.52  5286.7  228.18  5337.2  229.49
  5343.8  230.52  5378.9  231.49  5429.4  233.96    5436  235.26  5443.1  235.24
#Mann= 6 ,-1 , 0
    4770     .16       0    4804     .12       0  4875.9     .16       0
  5000.5     .07       0  5006.5     .16       0  5096.5     .05       0
Bank Sta=4897.3,5286.7
XS Rating Curve= 0 ,0
Exp/Cntr=0.3,0.1

Type RM Length L Ch R = 1 ,22177   ,716,716,716
BEGIN DESCRIPTION:
CEDAR BRANCH 12.0
END DESCRIPTION:
XS GIS Cut Line= 3
      3746499.59     10520260.21      3746003.73     10520817.34
      3745849.61     10521710.19
#Sta/Elev= 30
  4328.4  254.25  4337.5  254.15  4470.1  248.42  4555.4  242.46  4710.9  236.51
    4746  233.34  4888.2   227.8  4930.8  225.49  4937.5  223.52  4980.2  223.52
  4986.9  221.44  4998.1  214.97  5000.8  214.47  5004.1  214.97  5008.6  219.98
  5022.8  221.54  5029.5  219.18  5037.2  220.09  5043.7  220.05  5057.9  224.86
  5072.1   226.2  5117.7  223.02    5138  226.86  5148.2  228.24  5190.2  231.66
  5351.1  231.58  5424.5  235.79  5544.2  239.67  5767.2  243.07  5980.3  249.72
#Mann= 6 ,-1 , 0
  4328.4     .16       0  4337.5     .05       0  4998.1     .03       0
  5004.1     .05       0  5037.2     .12       0    5138     .05       0
Bank Sta=4888.2,5148.2
XS Rating Curve= 0 ,0
Exp/Cntr=0.3,0.1