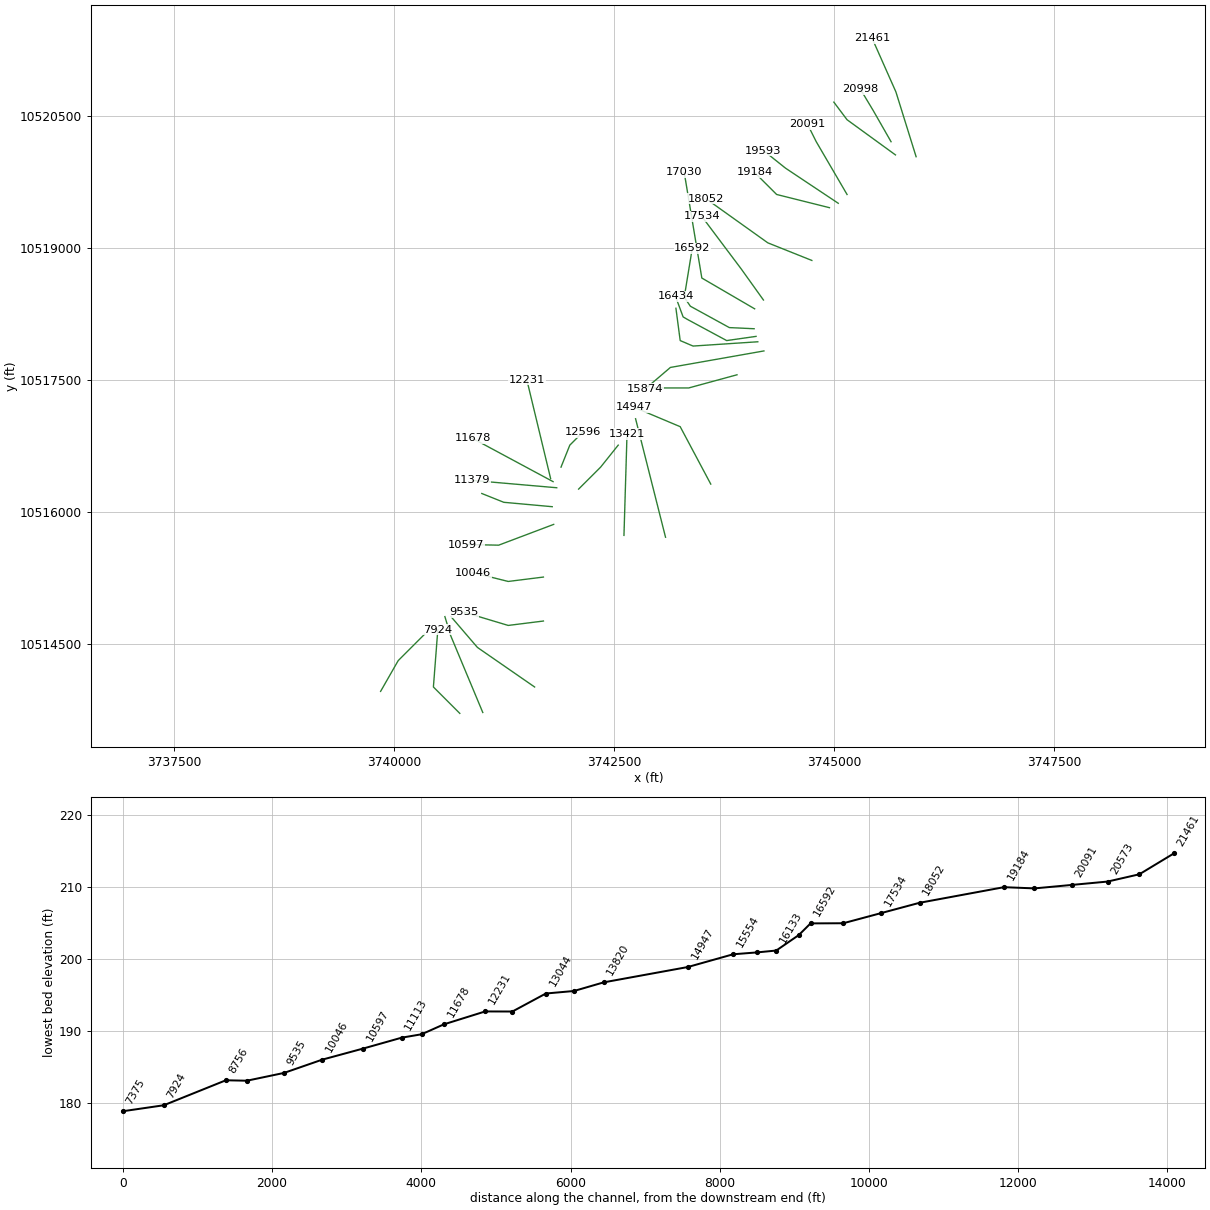
HEC-RAS study CEDAR BRANCH.prj: CEDAR BRANCH Base Level Engineering

--- CEDAR BRANCH.g01 (geometry) --- (continued)

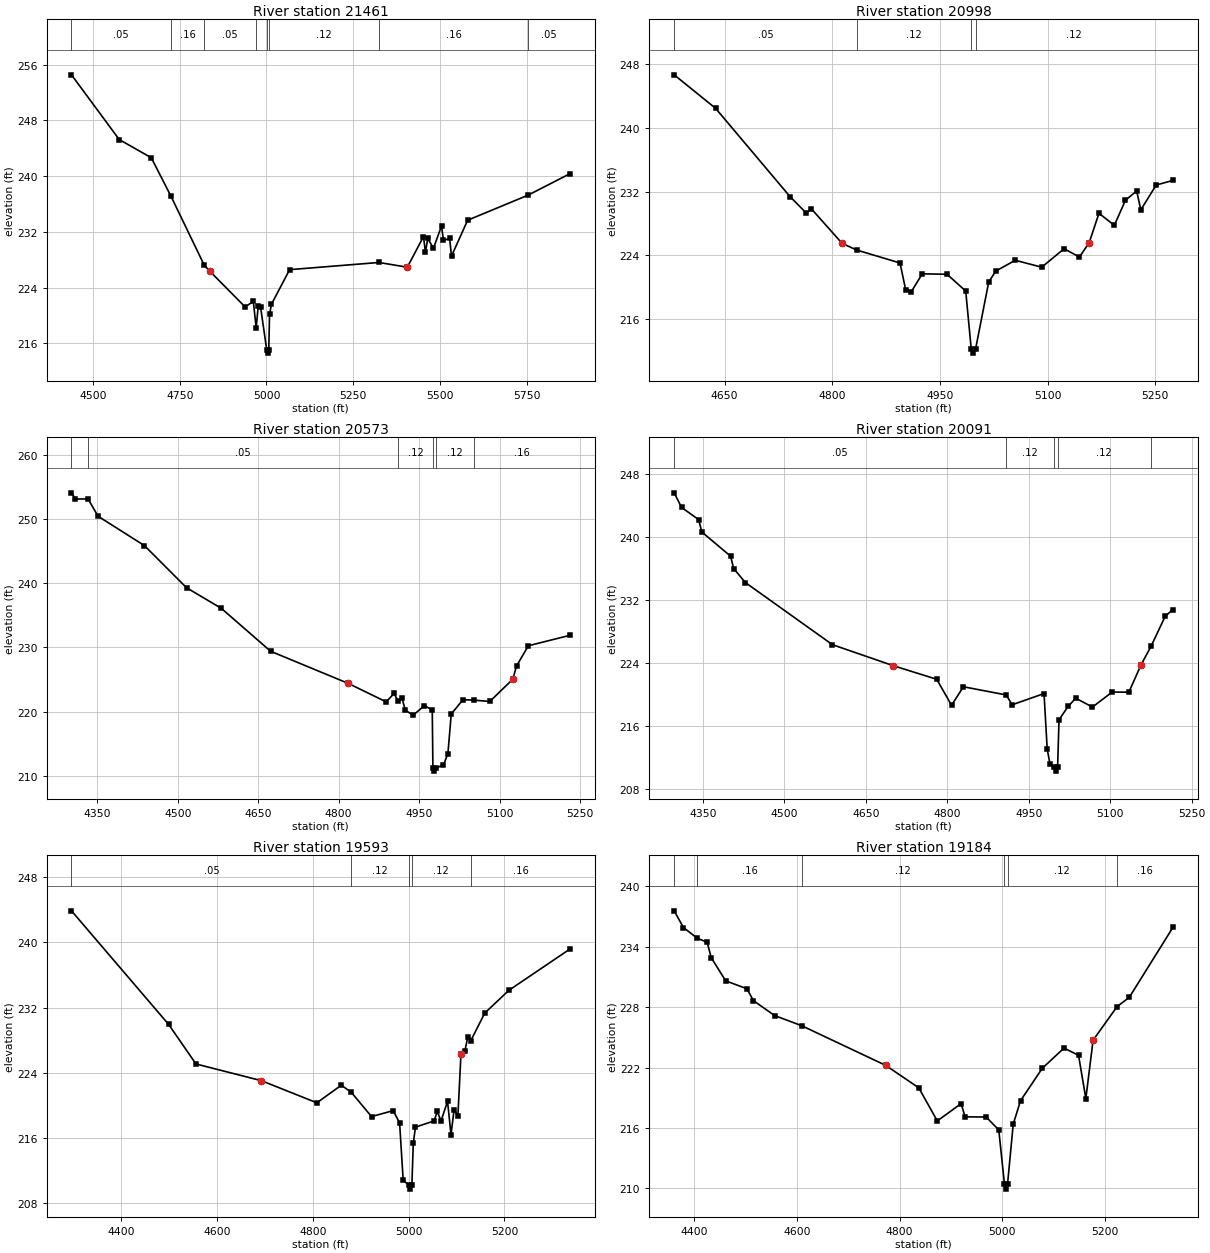
Type RM Length L Ch R = 1 ,21461   ,463,463,463
BEGIN DESCRIPTION:
CEDAR BRANCH 11.0
END DESCRIPTION:
XS GIS Cut Line= 3
      3745934.27     10520039.61      3745705.12     10520775.67
      3745434.79     10521385.64
#Sta/Elev= 30
  4437.7  254.52  4575.4  245.24  4667.8  242.63  4724.9  237.08  4820.3  227.24
  4835.7   226.4  4938.5  221.23    4962  222.03  4970.2  218.26  4976.3  221.39
  4982.9  221.23  5000.6  215.11  5003.3  214.61  5006.6  215.11  5008.8  220.16
  5014.3  221.62  5066.7  226.58  5324.3  227.61  5406.1  226.93  5452.7  231.33
  5458.2  229.08  5465.1  231.05  5481.4  229.64  5504.7  232.86  5510.2  230.78
    5528  231.05  5533.5  228.53    5580  233.67    5754  237.26  5875.8  240.36
#Mann= 8 ,-1 , 0
  4437.7     .05       0  4724.9     .16       0  4820.3     .05       0
  4970.2     .12       0  5000.6     .07       0  5006.6     .12       0
  5324.3     .16       0    5754     .05       0
Bank Sta=4835.7,5406.1
XS Rating Curve= 0 ,0
Exp/Cntr=0.3,0.1

Type RM Length L Ch R = 1 ,20998   ,425,425,425
BEGIN DESCRIPTION:
CEDAR BRANCH 10.0
END DESCRIPTION:
XS GIS Cut Line= 3
      3745649.62     10520210.16      3745449.61     10520560.19
      3745299.61      10520810.2
#Sta/Elev= 30
  4579.8  246.69  4637.4  242.49  4741.1  231.39  4764.1  229.29  4770.6  229.88
  4813.8   225.5  4834.4  224.66  4894.4  223.04  4902.3  219.65  4910.2  219.44
  4925.4  221.68  4959.9  221.62  4985.9  219.51  4993.6  212.21  4996.3  211.71
  4999.6  212.21  5017.9  220.64  5027.6  222.01  5054.9  223.38  5091.8  222.51
  5122.9  224.83  5144.3  223.79  5157.9   225.6  5171.5  229.29  5192.9  227.77
  5208.4  230.93    5224  232.09  5229.8  229.72  5251.2  232.84  5274.5  233.42
#Mann= 4 ,-1 , 0
  4579.8     .05       0  4834.4     .12       0  4993.6     .07       0
  4999.6     .12       0
Bank Sta=4813.8,5157.9
XS Rating Curve= 0 ,0
Exp/Cntr=0.3,0.1

Type RM Length L Ch R = 1 ,20573   ,482,482,482
BEGIN DESCRIPTION:
CEDAR BRANCH 9.0
END DESCRIPTION:
XS GIS Cut Line= 3
      3745699.65     10520060.16      3745149.61     10520460.19
      3744999.62     10520660.17
#Sta/Elev= 30
  4301.7  254.14  4309.1  253.18  4332.7  253.18  4351.2  250.49  4437.8   245.9
  4516.2  239.33  4581.1  236.11  4673.1  229.41  4817.6   224.4  4888.7  221.51
  4903.4  222.84  4910.5  221.61  4918.1  222.09  4924.2  220.22  4938.9  219.42
  4959.8  220.93  4974.5  220.24  4975.7   211.2  4978.5   210.7  4981.7   211.2
  4995.4  211.65  5003.7  213.45  5009.9  219.61  5031.8  221.85  5052.5  221.78
  5081.8  221.57  5124.5  225.03  5131.8  227.13  5153.7  230.27  5231.8  231.91
#Mann= 6 ,-1 , 0
  4301.7     .16       0  4332.7     .05       0  4910.5     .12       0
  4975.7     .07       0  4981.7     .12       0  5052.5     .16       0
Bank Sta=4817.6,5124.5
XS Rating Curve= 0 ,0
Exp/Cntr=0.3,0.1

Type RM Length L Ch R = 1 ,20091   ,498,498,498
BEGIN DESCRIPTION:
CEDAR BRANCH 8.0
END DESCRIPTION:
XS GIS Cut Line= 3
      3745149.62     10519610.16      3744799.61     10520210.19
      3744699.59     10520410.22
#Sta/Elev= 30
  4297.1  245.56  4310.8   243.7  4342.2  242.16    4348  240.59  4400.9  237.52
  4406.7  235.95  4428.2  234.17  4588.6  226.28  4700.3  223.62  4780.5  221.89
  4807.8  218.59  4829.7  220.94  4908.5   219.9  4919.4  218.65  4978.1  220.08
  4983.9  213.06  4988.9  211.17  4997.1  210.73  4999.9  210.23  5003.1  210.73
  5005.7  216.75  5022.5  218.45  5036.5  219.49  5067.2  218.36  5103.6  220.27
  5134.3  220.25  5156.7  223.72    5175  226.06  5201.4  229.91  5215.4  230.74
#Mann= 5 ,-1 , 0
  4297.1     .05       0  4908.5     .12       0  4997.1     .07       0
  5003.1     .12       0    5175     .16       0
Bank Sta=4700.3,5156.7
XS Rating Curve= 0 ,0
Exp/Cntr=0.3,0.1

Type RM Length L Ch R = 1 ,19593   ,409,409,409
BEGIN DESCRIPTION:
CEDAR BRANCH 7.0
END DESCRIPTION:
XS GIS Cut Line= 3
       3745049.6      10519510.2      3744449.61     10519910.19
      3744199.65     10520110.16
#Sta/Elev= 30
  4296.1  243.86  4498.9  229.94    4556  225.09  4692.7  223.04  4808.4  220.33
  4859.5  222.49  4880.5   221.6  4922.5  218.64  4967.6  219.37  4981.1  217.87
  4988.6  210.81  5000.7  210.25  5003.4  209.75  5006.7  210.25  5009.7  215.41
  5014.2  217.35  5053.2  218.11  5059.6  219.27  5067.6  218.12  5081.2   220.5
  5088.4  216.43  5094.8  219.47  5102.8  218.73  5109.2  226.32  5117.2  226.65
  5123.6  228.43  5129.7  227.95  5158.9  231.33  5209.3  234.12  5337.3   239.2
#Mann= 5 ,-1 , 0
  4296.1     .05       0  4880.5     .12       0  5000.7     .07       0
  5006.7     .12       0  5129.7     .16       0
Bank Sta=4692.7,5109.2
XS Rating Curve= 0 ,0
Exp/Cntr=0.3,0.1

Type RM Length L Ch R = 1 ,19184   ,1132,1132,1132
BEGIN DESCRIPTION:
CEDAR BRANCH 6.0
END DESCRIPTION:
XS GIS Cut Line= 3
      3744949.57      10519460.2      3744349.61     10519610.19
      3744099.59     10519860.21
#Sta/Elev= 30
  4360.7  237.58  4378.7  235.92  4405.4  234.87  4425.1  234.45  4432.8  232.93
  4461.2  230.62  4502.4  229.84  4515.3  228.65  4556.5  227.17  4609.3  226.16
    4773  222.22  4837.4  219.99  4873.5   216.7  4919.9  218.42  4927.6  217.11
  4968.8  217.08  4993.3  215.81  5004.4  210.42  5007.2  209.92  5010.4  210.42
  5021.5  216.38  5035.7  218.71  5078.1  221.93  5120.5  223.94  5148.8  223.22
    5163  218.92  5177.1  224.72  5223.9  228.06  5247.8  228.99  5332.7  235.93
#Mann= 6 ,-1 , 0
  4360.7     .05       0  4405.4     .16       0  4609.3     .12       0
  5004.4     .07       0  5010.4     .12       0  5223.9     .16       0
Bank Sta=4773,5177.1
XS Rating Curve= 0 ,0
Exp/Cntr=0.3,0.1

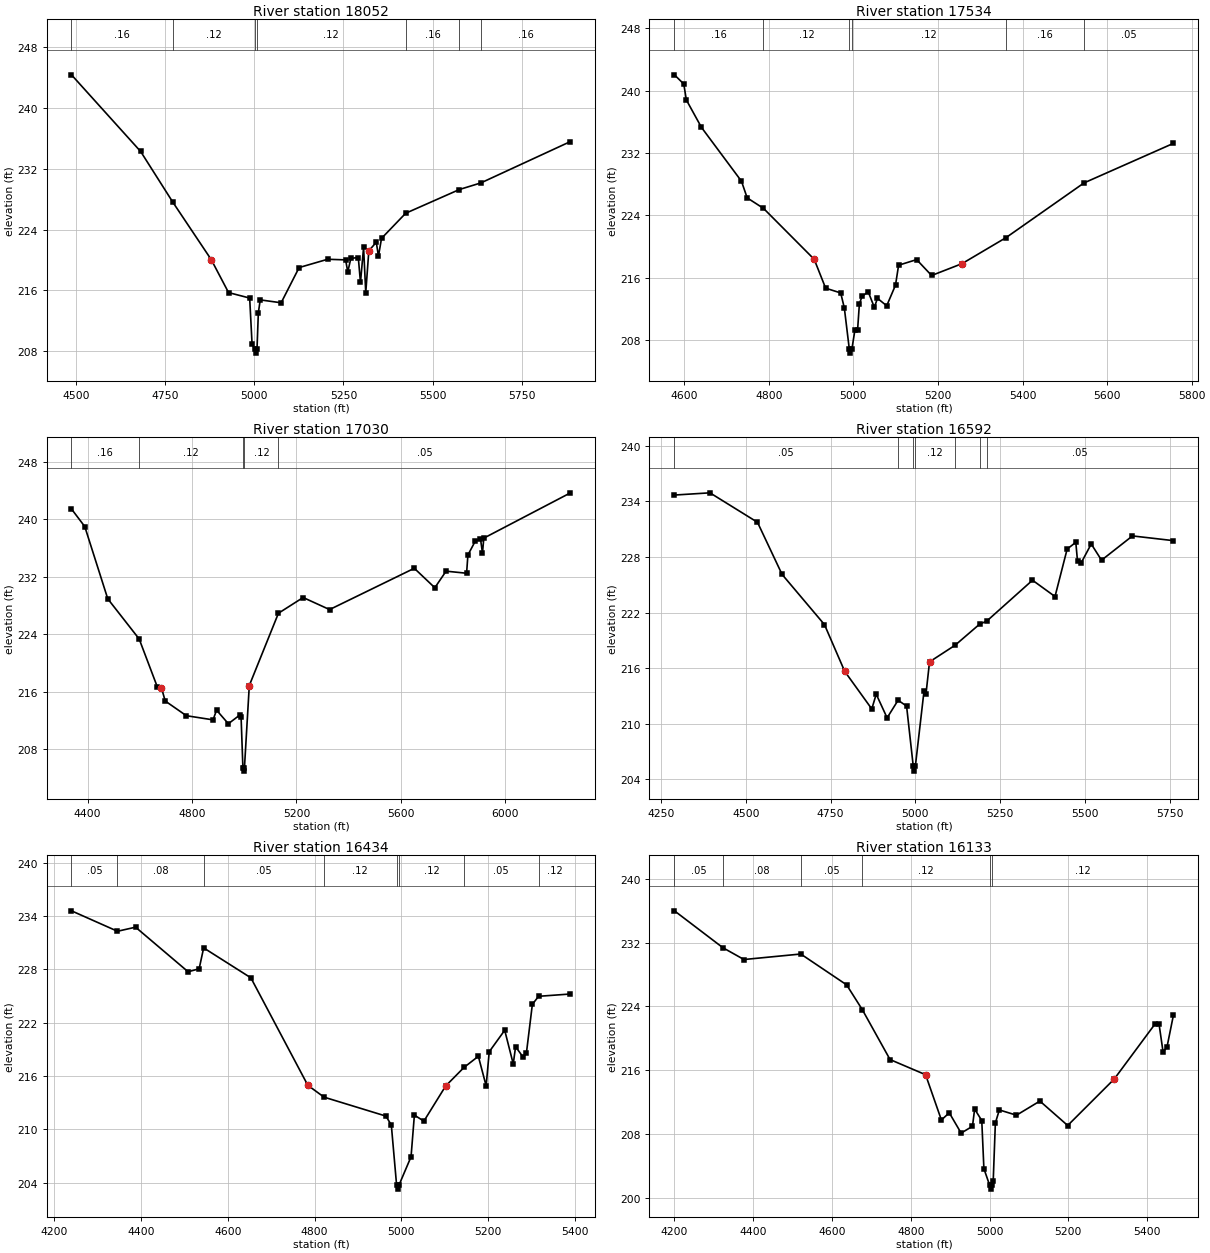
Type RM Length L Ch R = 1 ,18052   ,518,518,518
BEGIN DESCRIPTION:
CEDAR BRANCH 4.0
END DESCRIPTION:
XS GIS Cut Line= 3
      3744749.65     10518860.17      3744249.61     10519060.19
       3743549.6     10519560.19
#Sta/Elev= 30
  4487.5  244.34  4681.4  234.26  4771.5   227.6  4879.3  220.04  4927.8  215.71
    4987  214.99  4993.7  208.93  5001.5  208.25  5004.3  207.75  5007.5  208.25
  5011.3  213.06  5016.6  214.75  5075.2  214.37  5125.6     219  5205.5  220.09
  5255.9  220.01    5262  218.43  5270.6  220.21  5291.5  220.32  5297.6  217.04
  5306.3  221.64  5312.4   215.7    5321   221.2  5341.9  222.33    5348   220.5
  5356.6  222.84  5424.3  226.14  5574.8  229.26  5635.1  230.13  5886.3  235.57
#Mann= 7 ,-1 , 0
  4487.5     .16       0  4771.5     .12       0  5001.5     .07       0
  5007.5     .12       0  5424.3     .16       0  5574.8     .05       0
  5635.1     .16       0
Bank Sta=4879.3,5321
XS Rating Curve= 0 ,0
Exp/Cntr=0.3,0.1

Type RM Length L Ch R = 1 ,17534   ,504,504,504
BEGIN DESCRIPTION:
CEDAR BRANCH 3.0
END DESCRIPTION:
XS GIS Cut Line= 3
      3744199.59     10518410.22      3743949.61     10518760.19
       3743499.6      10519360.2
#Sta/Elev= 30
  4576.8  242.05  4598.9  240.87    4605  238.82  4640.7   235.3  4735.3  228.39
  4748.8  226.25  4787.4   224.9  4907.3  218.36  4934.4  214.65    4970  214.04
  4978.6  212.11  4990.4  206.81  4993.1  206.31  4996.4  206.81  5003.8  209.34
    5010  209.34  5014.2  212.64  5020.4  213.59    5035   214.2  5049.6  212.18
  5056.9  213.35  5078.8  212.39  5099.6  215.04  5106.9   217.6  5149.6  218.32
    5185  216.28  5256.9   217.8  5361.2  221.15  5545.5  228.17  5756.9  233.25
#Mann= 6 ,-1 , 0
  4576.8     .16       0  4787.4     .12       0  4990.4     .07       0
  4996.4     .12       0  5361.2     .16       0  5545.5     .05       0
Bank Sta=4907.3,5256.9
XS Rating Curve= 0 ,0
Exp/Cntr=0.3,0.1

Type RM Length L Ch R = 1 ,17030   ,438,438,438
BEGIN DESCRIPTION:
CEDAR BRANCH 2.0
END DESCRIPTION:
XS GIS Cut Line= 3
      3744099.61     10518310.19      3743499.61     10518660.19
      3743299.61     10519860.21
#Sta/Elev= 30
  4338.2  241.42  4389.1  238.97  4477.1  228.91  4597.5  223.31  4666.9  216.64
  4682.6  216.54  4697.1  214.68  4778.1  212.63  4880.3  212.05  4893.9   213.4
    4939  211.51    4982   212.7  4987.8  212.42  4994.7  205.41  4997.4  204.91
  5000.7  205.41  5019.2  216.83  5130.8   226.9  5225.4  229.09  5326.8  227.41
  5651.2  233.16  5729.8  230.45  5772.9  232.76  5851.5  232.47  5856.5  235.01
  5884.4  236.92  5904.7  237.26  5912.3  235.28  5917.4  237.36  6249.4  243.67
#Mann= 5 ,-1 , 0
  4338.2     .16       0  4597.5     .12       0  4994.7     .07       0
  5000.7     .12       0  5130.8     .05       0
Bank Sta=4682.6,5019.2
XS Rating Curve= 0 ,0
Exp/Cntr=0.3,0.1

Type RM Length L Ch R = 1 ,16592   ,158,158,158
BEGIN DESCRIPTION:
Mapping XS 631659c8
END DESCRIPTION:
XS GIS Cut Line= 6
       3744094.2     10518083.66      3743812.12     10518096.68
      3743369.42     10518339.74      3743312.99      10518422.2
      3743308.65     10518495.99      3743391.11     10518999.43
#Sta/Elev= 30
  4289.4  234.68  4394.1  234.92  4534.3  231.74  4606.7  226.12  4731.8   220.7
  4791.4  215.66  4871.3   211.6  4884.4  213.19  4916.5  210.64  4948.9  212.54
  4973.9  211.91  4993.7  205.39  4996.5  204.89  4999.7  205.39  5025.5  213.58
  5031.2  213.24  5041.6  216.68  5117.2  218.48    5189  220.74  5210.4  221.08
  5345.2  225.49  5411.6  223.73  5447.4  228.85  5472.9  229.58    5478  227.53
    5488  227.31  5518.4   229.4  5548.8  227.65    5640  230.27  5760.8  229.76
#Mann= 7 ,-1 , 0
  4289.4     .05       0  4948.9     .12       0  4993.7     .07       0
  4999.7     .12       0  5117.2     .05       0    5189     .12       0
  5210.4     .05       0
Bank Sta=4791.4,5041.6
XS Rating Curve= 0 ,0
Exp/Cntr=0.3,0.1

Type RM Length L Ch R = 1 ,16434   ,302,302,302
BEGIN DESCRIPTION:
Mapping XS 336fcc60
END DESCRIPTION:
XS GIS Cut Line= 5
      3744115.92     10517996.85      3743781.74     10517949.11
      3743339.03     10518187.83      3743286.95     10518218.21
      3743200.13     10518452.62
#Sta/Elev= 30
  4239.2  234.59  4345.3  232.29    4387  232.75  4508.2  227.73  4533.6  228.07
    4544  230.42  4652.9  227.05  4784.3  214.95  4821.7  213.62  4964.3  211.49
  4976.8  210.49  4988.9  203.77  4991.6  203.27  4994.9  203.77  5022.3  206.91
    5030   211.6  5051.9  210.92  5102.2  214.88  5144.3  216.96  5177.5  218.22
  5195.5  214.89  5202.6  218.73  5238.3  221.15    5258  217.36  5263.4   219.3
  5280.8  218.12  5288.4   218.6  5302.1  224.07  5316.5  224.97    5390  225.23
#Mann= 8 ,-1 , 0
  4239.2     .05       0  4345.3     .08       0    4544     .05       0
  4821.7     .12       0  4988.9     .07       0  4994.9     .12       0
  5144.3     .05       0  5316.5     .12       0
Bank Sta=4784.3,5102.2
XS Rating Curve= 0 ,0
Exp/Cntr=0.3,0.1

Type RM Length L Ch R = 1 ,16133   ,258,258,258
BEGIN DESCRIPTION:
CEDAR BRANCH 1.0
END DESCRIPTION:
XS GIS Cut Line= 4
      3744135.69      10517935.4      3743399.56     10517886.78
      3743253.73     10517949.28      3743205.26     10518316.31
#Sta/Elev= 30
  4200.1  235.98  4323.1  231.36  4376.6  229.88  4520.8  230.57  4637.1  226.71
  4677.2  223.58  4747.4  217.35  4837.6  215.45  4877.7  209.78  4897.7  210.68
  4927.8  208.14  4956.6  208.99  4962.1  211.15  4980.2  209.71  4985.6  203.69
  5000.1  201.62  5002.8  201.12  5006.1  201.62  5009.2  202.08  5014.7   209.4
  5024.8  211.04  5068.3  210.38  5127.7  212.15  5198.3  209.09  5316.6  214.92
  5420.2  221.82  5430.3  221.76  5440.4   218.3  5450.4  218.93  5466.7  222.92
#Mann= 6 ,-1 , 0
  4200.1     .05       0  4323.1     .08       0  4520.8     .05       0
  4677.2     .12       0  5000.1     .07       0  5006.1     .12       0
Bank Sta=4837.6,5316.6
XS Rating Curve= 0 ,0
Exp/Cntr=0.3,0.1

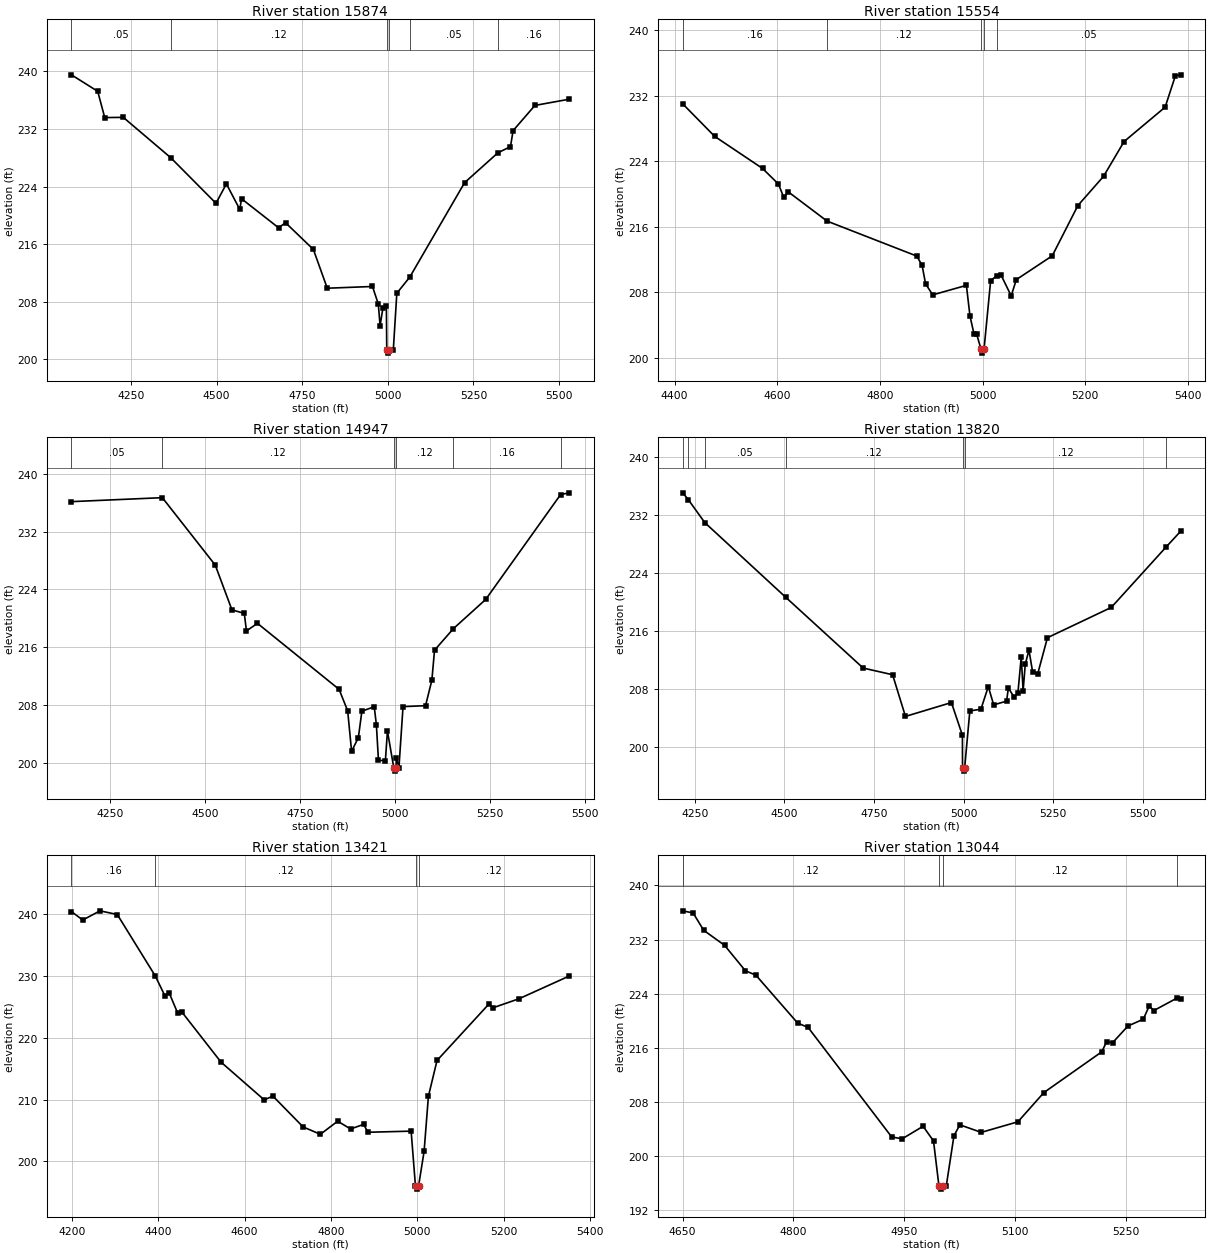
Type RM Length L Ch R = 1 ,15874   ,320,320,320
BEGIN DESCRIPTION:
Mapping XS ms235n23
END DESCRIPTION:
XS GIS Cut Line= 3
      3744205.15     10517831.23      3743142.62     10517643.73
       3742857.9     10517400.67
#Sta/Elev= 30
  4076.4  239.53  4153.1  237.24  4173.6  233.59  4227.8  233.62  4366.2  228.02
  4498.4  221.68  4528.8  224.38  4567.9  220.83    4573  222.31  4681.1  218.28
  4701.5  218.98  4782.7  215.27  4823.3  209.88  4955.3  210.12  4972.4  207.67
  4977.5  204.67  4985.8  207.12  4995.9  207.41    4997  201.36  4999.8  200.86
    5003  201.36  5016.2  201.36  5026.4  209.18  5064.3  211.43  5224.3  224.55
  5321.6   228.7  5358.2  229.55  5365.9  231.78  5429.6  235.28  5529.7  236.14
#Mann= 6 ,-1 , 0
  4076.4     .05       0  4366.2     .12       0    4997     .07       0
    5003     .12       0  5064.3     .05       0  5321.6     .16       0
Bank Sta=4997,5003
XS Rating Curve= 0 ,0
Exp/Cntr=0.3,0.1

Type RM Length L Ch R = 1 ,15554   ,607,607,607
BEGIN DESCRIPTION:
Mapping XS n2d5gi22
END DESCRIPTION:
XS GIS Cut Line= 3
      3743899.61     10517560.19      3743349.61     10517410.19
       3742949.6     10517410.19
#Sta/Elev= 30
  4415.8  230.98    4478  227.02  4571.3  223.11  4602.4   221.2  4612.7  219.57
  4621.4  220.26  4697.1  216.69  4871.9  212.43  4882.2  211.31  4889.1  209.04
    4903   207.7  4968.6  208.86  4975.5  205.16  4983.3  202.96  4988.4  202.96
    4997   201.1  4999.8   200.6    5003   201.1  5015.9  209.45  5027.5  210.01
  5035.9  210.14  5055.9  207.58  5065.9  209.56  5135.9  212.46  5185.9  218.59
  5235.9  222.15  5275.9  226.39  5355.9  230.58  5375.9  234.41  5385.9  234.52
#Mann= 5 ,-1 , 0
  4415.8     .16       0  4697.1     .12       0    4997     .07       0
    5003     .12       0  5027.5     .05       0
Bank Sta=4997,5003
XS Rating Curve= 0 ,0
Exp/Cntr=0.3,0.1

Type RM Length L Ch R = 1 ,14947   ,1127,1127,1127
BEGIN DESCRIPTION:
Mapping XS ax48ya21
END DESCRIPTION:
XS GIS Cut Line= 3
      3743600.94     10516317.36      3743253.73     10516970.12
      3742725.96     10517192.33
#Sta/Elev= 30
  4147.5  236.14  4387.1  236.69  4526.6  227.35  4570.5  221.16  4603.1  220.67
  4608.8  218.24  4637.8  219.29    4853  210.15  4875.6  207.17  4885.9  201.57
  4903.8  203.48    4913  207.13  4945.6  207.74  4951.2  205.28  4956.7  200.32
    4975  200.28  4980.4  204.38    4997  199.33  4999.8  198.83    5003  199.33
  5004.1  200.64  5010.7  199.33  5021.5  207.76  5080.8  207.89  5097.5  211.42
  5104.5  215.57  5154.3  218.56  5239.4   222.6  5436.8  237.12  5459.5  237.36
#Mann= 6 ,-1 , 0
  4147.5     .05       0  4387.1     .12       0    4997     .07       0
    5003     .12       0  5154.3     .16       0  5436.8     .12       0
Bank Sta=4997,5003
XS Rating Curve= 0 ,0
Exp/Cntr=0.3,0.1

Type RM Length L Ch R = 1 ,13820   ,399,399,399
BEGIN DESCRIPTION:
Mapping XS o1p3dg20
END DESCRIPTION:
XS GIS Cut Line= 2
      3743087.05     10515713.22      3742746.78     10517060.41
#Sta/Elev= 30
    4216   235.1  4231.5  234.16  4277.6  230.99  4503.2   220.7  4719.7  210.92
  4801.8     210  4837.7  204.25    4966  206.16  4996.7  201.64    4997   197.2
  4999.8   196.7    5003   197.2  5017.4  205.01  5048.3  205.24  5068.9  208.36
    5084  205.84  5119.9  206.36    5125  208.16  5141.1   206.9  5151.5  207.43
  5160.9   212.5  5166.1  207.77  5172.1  211.44  5182.4  213.41  5192.7  210.37
  5207.1  210.17    5234  215.11  5412.3  219.29  5566.1  227.67  5605.5  229.78
#Mann= 7 ,-1 , 0
    4216     .05       0  4231.5     .12       0  4277.6     .05       0
  4503.2     .12       0    4997     .07       0    5003     .12       0
  5566.1     .16       0
Bank Sta=4997,5003
XS Rating Curve= 0 ,0
Exp/Cntr=0.3,0.1

Type RM Length L Ch R = 1 ,13421   ,377,377,377
BEGIN DESCRIPTION:
Mapping XS nk30dj19
END DESCRIPTION:
XS GIS Cut Line= 2
      3742614.84     10515734.04      3742649.54     10516886.01
#Sta/Elev= 30
  4199.3  240.45  4225.5  239.08  4265.5  240.57  4305.5  239.97  4393.6     230
  4415.6  226.82  4425.6  227.28  4445.6  223.95  4455.6  224.13  4545.6  216.07
  4645.7  209.95  4665.7  210.57  4735.7  205.57  4775.7  204.38  4815.7   206.5
  4845.7  205.24  4875.8  205.99  4885.8  204.71  4985.8  204.89  4995.8     196
    4997     196  4999.8   195.5    5003     196  5015.8  201.61  5025.8  210.55
  5045.8  216.34  5165.9  225.48  5175.9  224.88  5235.9  226.34  5351.8  230.01
#Mann= 4 ,-1 , 0
  4199.3     .16       0  4393.6     .12       0    4997     .07       0
    5003     .12       0
Bank Sta=4997,5003
XS Rating Curve= 0 ,0
Exp/Cntr=0.3,0.1

Type RM Length L Ch R = 1 ,13044   ,448,448,448
BEGIN DESCRIPTION:
Mapping XS ng2j6k18
END DESCRIPTION:
XS GIS Cut Line= 3
      3742099.62      10516260.2      3742349.61     10516510.19
      3742549.61     10516760.19
#Sta/Elev= 30
  4650.3  236.24  4664.4  235.92  4678.6  233.37  4706.9  231.15  4735.1  227.39
  4749.3  226.74  4805.8  219.67    4820  219.02  4933.1  202.85  4947.3  202.58
  4975.6  204.43  4989.7  202.26    4997  195.65  4999.8  195.15    5003  195.65
    5007  195.65  5017.4  203.05  5025.4  204.64  5054.3  203.53  5103.9  205.09
  5139.1  209.41  5217.5  215.43  5223.9  216.91    5232  216.76  5252.8  219.23
  5273.6  220.24  5281.6  222.18    5288  221.52  5319.6  223.38    5324  223.29
#Mann= 4 ,-1 , 0
  4650.3     .12       0    4997     .07       0    5003     .12       0
  5319.6     .16       0
Bank Sta=4997,5003
XS Rating Curve= 0 ,0
Exp/Cntr=0.3,0.1

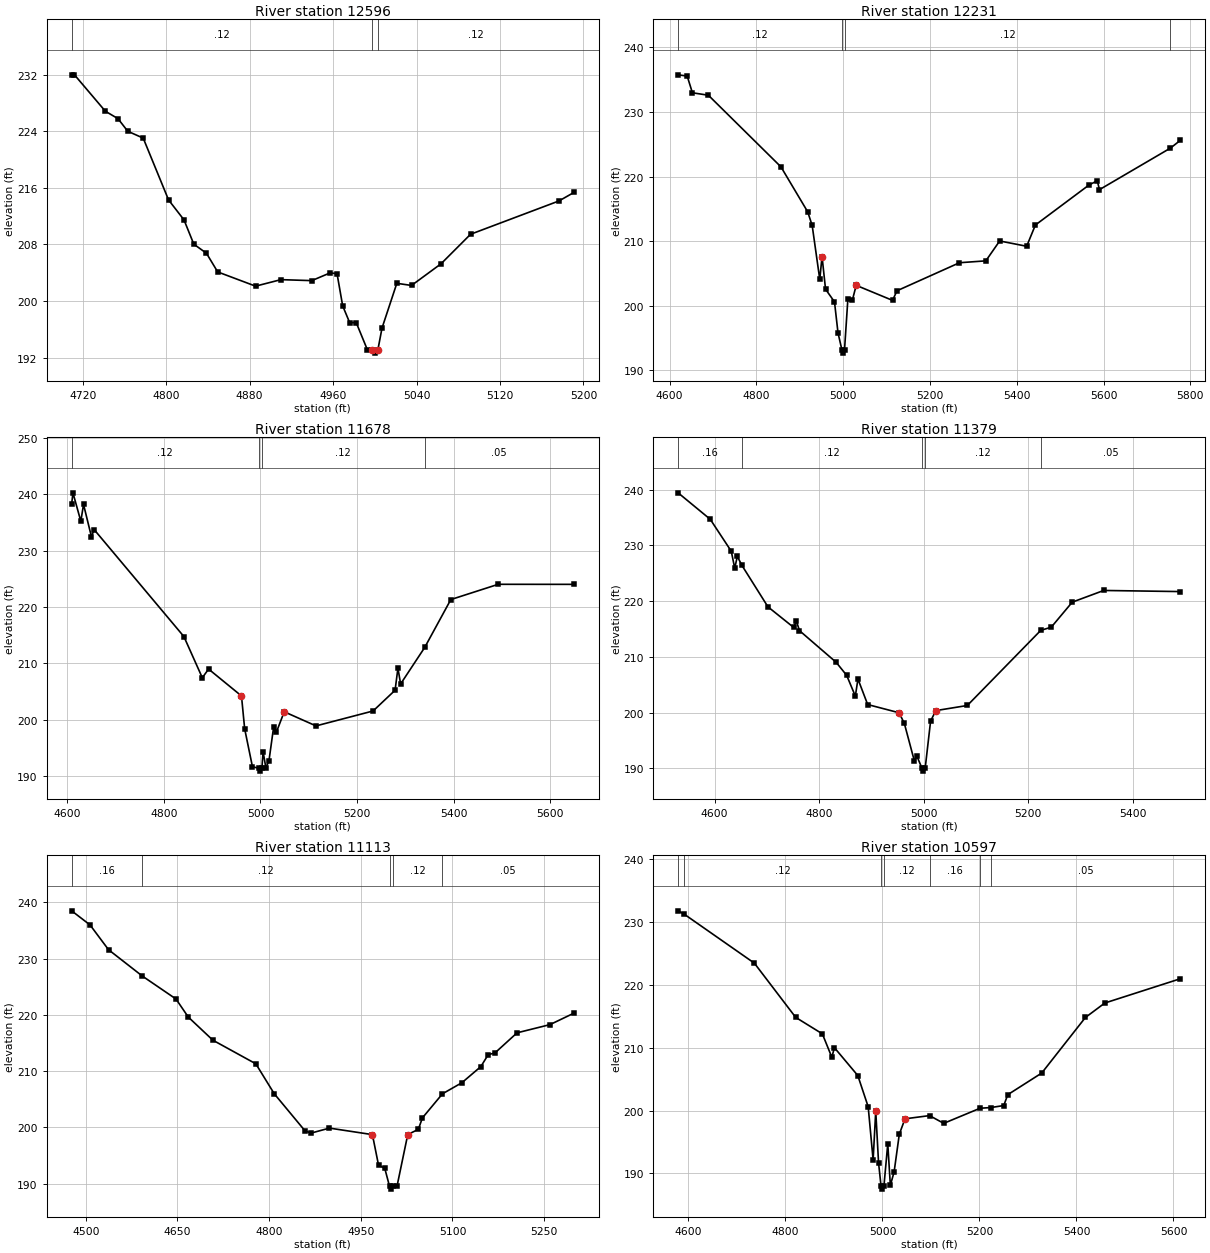
Type RM Length L Ch R = 1 ,12596   ,365,365,365
BEGIN DESCRIPTION:
Mapping XS ksj49k17
END DESCRIPTION:
XS GIS Cut Line= 3
      3741899.62     10516510.22      3741999.61     10516760.19
      3742149.64     10516910.22
#Sta/Elev= 30
  4709.4  231.96  4712.1  231.96  4741.7  226.82  4753.8  225.77  4763.2  223.99
    4778  223.02  4802.3  214.29  4817.1  211.47  4826.5  208.04  4838.6  206.76
  4849.4  204.12  4885.7  202.11    4910  203.03  4939.6  202.89  4957.1  203.98
  4963.8  203.88  4969.2  199.33  4975.9  196.96  4982.2  196.96  4992.8  193.15
    4997  193.15  4999.8  192.65    5003  193.15  5006.9  196.18  5021.1  202.51
  5035.2  202.21  5063.5  205.27  5091.8  209.44  5176.6  214.15  5190.8  215.34
#Mann= 3 ,-1 , 0
  4709.4     .12       0    4997     .07       0    5003     .12       0
Bank Sta=4997,5003
XS Rating Curve= 0 ,0
Exp/Cntr=0.3,0.1

Type RM Length L Ch R = 1 ,12231   ,553,553,553
BEGIN DESCRIPTION:
Mapping XS nk39gj16
END DESCRIPTION:
XS GIS Cut Line= 2
       3741781.5     10516379.88      3741510.68     10517504.84
#Sta/Elev= 30
  4619.6  235.76  4640.5  235.57  4652.5  232.98  4689.3   232.6  4856.5  221.51
  4918.2  214.54  4928.5  212.43    4946  204.07  4951.2  207.62  4959.3  202.56
  4979.9   200.6    4988   195.8    4997  193.16  4999.8  192.66    5003  193.16
  5010.8  201.11  5021.1  200.86  5029.9  203.16  5113.6  200.83    5124  202.32
  5267.9  206.66  5328.6  206.95  5360.5  210.03  5422.7  209.21  5442.8   212.5
  5566.2  218.69  5585.3  219.35  5590.5  217.98  5753.9  224.41  5776.7  225.61
#Mann= 4 ,-1 , 0
  4619.6     .12       0    4997     .07       0    5003     .12       0
  5753.9     .05       0
Bank Sta=4951.2,5029.9
XS Rating Curve= 0 ,0
Exp/Cntr=0.3,0.1

Type RM Length L Ch R = 1 ,11678   ,299,299,299
BEGIN DESCRIPTION:
Mapping XS e34c3e65
END DESCRIPTION:
XS GIS Cut Line= 2
      3741809.29     10516345.12      3740893.64     10516837.62
#Sta/Elev= 30
  4609.1  238.31  4611.8  240.28  4628.1  235.23  4633.7  238.22    4650  232.51
  4655.7  233.75  4841.5  214.76  4879.6  207.45  4892.6  208.99  4960.7  204.22
  4967.3  198.38  4983.4  191.65    4997  191.37  4999.8  190.87    5003  191.37
  5005.4  194.35  5011.1   191.5  5017.5  192.64  5027.3  198.72    5033  197.79
  5049.2  201.41    5115   198.9  5233.2  201.55  5278.7  205.23  5284.6  209.14
  5290.2  206.35    5340  212.82  5394.1  221.33  5492.3  224.04  5648.8  224.03
#Mann= 4 ,-1 , 0
  4609.1     .12       0    4997     .07       0    5003     .12       0
    5340     .05       0
Bank Sta=4960.7,5049.2
XS Rating Curve= 0 ,0
Exp/Cntr=0.3,0.1

Type RM Length L Ch R = 1 ,11379   ,266,266,266
BEGIN DESCRIPTION:
Mapping XS f5hj7w15
END DESCRIPTION:
XS GIS Cut Line= 2
       3741850.9     10516275.68      3740893.62     10516358.92
#Sta/Elev= 30
  4530.3  239.43  4591.8  234.68    4632  228.95  4638.6  225.91  4643.6  228.02
  4652.3  226.42  4702.2  218.97  4751.5  215.27  4756.5  216.44  4762.5   214.7
  4832.7  209.02  4852.8  206.68  4869.4  202.95  4874.4  206.02    4893  201.44
  4953.2  199.96  4963.2  198.04  4982.3  191.33  4987.4  192.13    4997  189.99
  4999.8  189.49    5003  189.99  5013.4  198.47  5023.4  200.35  5083.7  201.27
  5224.2  214.75  5244.3  215.32  5284.4  219.81  5344.7  221.91  5491.2  221.71
#Mann= 5 ,-1 , 0
  4530.3     .16       0  4652.3     .12       0    4997     .07       0
    5003     .12       0  5224.2     .05       0
Bank Sta=4953.2,5023.4
XS Rating Curve= 0 ,0
Exp/Cntr=0.3,0.1

Type RM Length L Ch R = 1 ,11113   ,516,516,516
BEGIN DESCRIPTION:
Mapping XS cw3jhn14
END DESCRIPTION:
XS GIS Cut Line= 3
      3741799.62     10516060.19      3741249.61     10516110.19
      3740999.65     10516210.17
#Sta/Elev= 30
    4477   238.5  4507.1  235.99  4537.3  231.59  4592.4  226.92  4647.7  222.82
  4667.8  219.61    4708   215.5  4778.3   211.3  4808.4  205.98  4858.6   199.4
  4868.6  198.98  4898.7  199.87    4969  198.71  4979.1  193.23  4989.1  192.76
    4997  189.52  4999.8  189.02    5003  189.52  5009.2  189.52  5026.8  198.72
  5044.1  199.65  5050.8  201.69  5083.6  205.97  5115.4  207.94  5146.4  210.81
  5158.5  212.94  5169.3  213.22  5205.6  216.81  5259.5  218.27  5298.5   220.3
#Mann= 5 ,-1 , 0
    4477     .16       0  4592.4     .12       0    4997     .07       0
    5003     .12       0  5083.6     .05       0
Bank Sta=4969,5026.8
XS Rating Curve= 0 ,0
Exp/Cntr=0.3,0.1

Type RM Length L Ch R = 1 ,10597   ,551,551,551
BEGIN DESCRIPTION:
Mapping XS hv591h13
END DESCRIPTION:
XS GIS Cut Line= 3
      3741816.24     10515859.01      3741191.23     10515622.89
      3740823.92     10515629.82
#Sta/Elev= 30
  4578.6  231.76  4591.3  231.22  4735.8  223.44    4821  214.82    4876   212.2
  4895.5  208.49  4900.9     210  4949.1  205.57  4970.5  200.61  4980.7  192.16
  4986.1  199.93  4991.9   191.7    4997  188.01  4999.8  187.51    5003  188.01
  5010.9  194.72  5016.2  188.11    5024  190.26  5034.7  196.24  5046.4  198.69
    5097   199.2  5126.3  197.97  5201.2  200.37  5223.4  200.48    5250   200.8
  5258.4  202.53  5328.4  205.97  5418.4   214.8  5458.4   217.1  5614.1  220.96
#Mann= 7 ,-1 , 0
  4578.6     .16       0  4591.3     .12       0    4997     .07       0
    5003     .12       0    5097     .16       0  5201.2     .12       0
  5223.4     .05       0
Bank Sta=4986.1,5046.4
XS Rating Curve= 0 ,0
Exp/Cntr=0.3,0.1

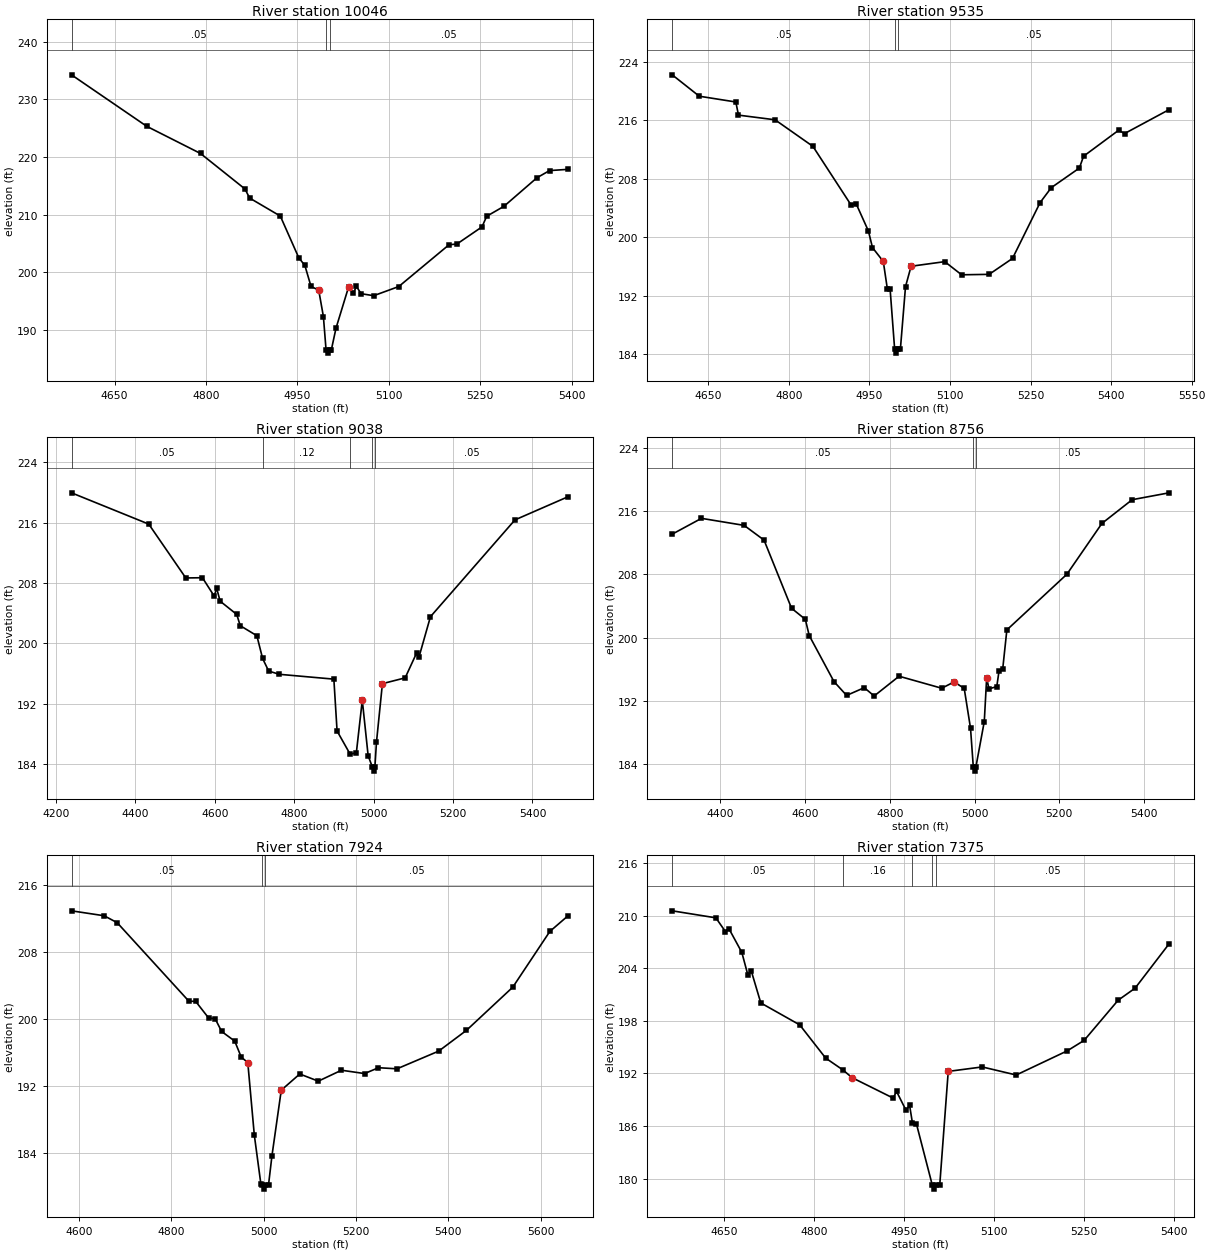
Type RM Length L Ch R = 1 ,10046   ,511,511,511
BEGIN DESCRIPTION:
Mapping XS d2g49f12
END DESCRIPTION:
XS GIS Cut Line= 3
      3741699.63     10515260.19      3741299.61     10515210.19
      3740899.65     10515310.18
#Sta/Elev= 30
  4579.2  234.23  4702.7   225.3  4790.9  220.59  4863.9  214.43  4871.5  212.86
  4921.9  209.73  4952.1  202.52  4962.2  201.16  4972.3  197.52  4984.9  196.89
  4992.6   192.3    4997  186.46  4999.8  185.96    5003  186.46  5005.5  186.46
  5013.3  190.29  5033.9  197.42  5041.6  196.34  5046.8  197.52  5054.5  196.27
  5075.1  195.92  5116.3  197.51  5198.8  204.76  5211.7  204.88  5252.9  207.86
  5260.6   209.7    5289  211.43  5343.1  216.38  5363.7  217.62  5394.6  217.84
#Mann= 3 ,-1 , 0
  4579.2     .05       0    4997     .03       0    5003     .05       0
Bank Sta=4984.9,5033.9
XS Rating Curve= 0 ,0
Exp/Cntr=0.3,0.1

Type RM Length L Ch R = 1 ,9535    ,497,497,497
BEGIN DESCRIPTION:
Mapping XS ehh57j11
END DESCRIPTION:
XS GIS Cut Line= 3
      3741699.58     10514760.19      3741299.61     10514710.19
      3740799.61     10514860.19
#Sta/Elev= 30
  4582.8  222.24  4633.2  219.31  4701.2  218.52  4706.2  216.72  4774.3  216.08
  4844.8  212.44  4915.3  204.47  4925.4  204.56  4948.1  200.85  4955.7  198.57
  4975.8  196.68  4983.4  192.91  4988.5  192.91    4997  184.62  4999.8  184.12
    5003  184.62  5007.6  184.62  5017.2  193.23  5027.6  196.02  5090.3  196.65
  5121.6  194.85  5172.9  194.91  5216.4  197.09  5267.8  204.74  5288.7  206.79
  5340.9  209.47  5348.7  211.09  5413.9  214.64  5425.2   214.2  5507.9  217.47
#Mann= 3 ,-1 , 0
  4582.8     .05       0    4997     .03       0    5003     .05       0
Bank Sta=4975.8,5027.6
XS Rating Curve= 0 ,0
Exp/Cntr=0.3,0.1

Type RM Length L Ch R = 1 ,9038    ,282,282,282
BEGIN DESCRIPTION:
Mapping XS er4h6b10
END DESCRIPTION:
XS GIS Cut Line= 3
      3741599.63     10514010.18      3740949.61     10514460.19
      3740649.59     10514810.21
#Sta/Elev= 30
  4238.8  219.95  4433.4   215.8  4526.7  208.66  4568.6  208.69  4598.3  206.25
  4604.4   207.3  4613.2  205.58  4655.1  203.82  4663.8  202.33  4705.7     201
  4720.2  197.98  4735.5  196.31  4762.5  195.88  4899.7  195.24  4907.8  188.36
  4940.9  185.27  4956.4   185.5  4971.3  192.44  4986.1  185.07    4997  183.54
  4999.8  183.04    5003  183.54  5007.1  186.91    5022  194.64  5079.3  195.41
  5107.9  198.68  5114.5  198.24    5143  203.52  5355.9  216.36  5490.4  219.45
#Mann= 5 ,-1 , 0
  4238.8     .05       0  4720.2     .12       0  4940.9     .05       0
    4997     .03       0    5003     .05       0
Bank Sta=4971.3,5022
XS Rating Curve= 0 ,0
Exp/Cntr=0.3,0.1

Type RM Length L Ch R = 1 ,8756    ,832,832,832
BEGIN DESCRIPTION:
Mapping XS n21jd926
END DESCRIPTION:
XS GIS Cut Line= 3
      3741010.67     10513720.12      3740642.62     10514602.06
      3740580.11     10514810.43
#Sta/Elev= 30
    4286  213.09  4355.1  215.09  4455.8   214.2  4502.8  212.34  4567.8  203.71
  4600.3  202.31  4609.5  200.26    4668  194.43  4697.8  192.68  4739.5  193.66
  4762.9  192.61  4821.7  195.11  4922.4  193.59  4951.7  194.39  4975.5  193.57
  4990.4  188.53    4997   183.6  4999.8   183.1    5003   183.6  5022.9  189.38
  5028.5  194.89    5034  193.51  5052.4   193.8  5057.8   195.8  5066.3  195.97
  5076.2  200.97    5218  208.02  5300.7  214.45  5372.1  217.45  5459.2  218.32
#Mann= 3 ,-1 , 0
    4286     .05       0    4997     .03       0    5003     .05       0
Bank Sta=4951.7,5028.5
XS Rating Curve= 0 ,0
Exp/Cntr=0.3,0.1

Type RM Length L Ch R = 1 ,7924    ,549,549,549
BEGIN DESCRIPTION:
Mapping XS d3rh6k25
END DESCRIPTION:
XS GIS Cut Line= 3
      3740749.57     10513710.22      3740449.61     10514010.19
      3740499.61     10514660.15
#Sta/Elev= 30
  4583.7  212.96  4654.4  212.37  4682.6  211.54  4838.2  202.12  4852.4  202.13
  4880.6  200.13  4894.8  200.04  4908.9  198.51  4937.2  197.36  4951.3  195.44
  4965.5  194.79  4979.6  186.12  4993.8  180.26    4997  180.13  4999.8  179.63
    5003  180.13  5010.4  180.13  5017.9  183.65    5038  191.48  5078.1  193.42
  5118.2  192.56  5168.4  193.87  5218.5  193.47  5248.6  194.17  5288.7  194.04
    5379  196.16  5439.2  198.65  5539.5  203.82  5619.7  210.49  5659.8   212.4
#Mann= 3 ,-1 , 0
  4583.7     .05       0    4997     .03       0    5003     .05       0
Bank Sta=4965.5,5038
XS Rating Curve= 0 ,0
Exp/Cntr=0.3,0.1

Type RM Length L Ch R = 1 ,7375    ,0,0,0
BEGIN DESCRIPTION:
Mapping XS ba23de24
END DESCRIPTION:
XS GIS Cut Line= 3
      3739849.63     10513960.22      3740049.61     10514310.19
      3740349.58     10514610.16
#Sta/Elev= 30
  4564.1  210.55  4636.8  209.75  4652.6  208.19  4658.4  208.53    4680  205.81
    4690  203.25  4695.8  203.68  4711.6  200.04  4776.4  197.54  4819.6  193.75
  4848.5  192.39  4863.5  191.52  4931.9  189.19  4937.7  189.94  4953.5  187.78
  4959.3  188.38    4964  186.39  4970.7  186.26    4997   179.3  4999.8   178.8
    5003   179.3  5009.6   179.3  5023.7  192.23  5080.3  192.74  5136.9  191.82
  5221.7  194.57    5250  195.77  5306.6  200.35  5334.9  201.73  5391.4  206.78
#Mann= 5 ,-1 , 0
  4564.1     .05       0  4848.5     .16       0    4964     .05       0
    4997     .03       0    5003     .05       0
Bank Sta=4863.5,5023.7
XS Rating Curve= 0 ,0
Exp/Cntr=0.3,0.1

Chan Stop Cuts=-1
Use User Specified Reach Order=0
Composite Channel Slope=5