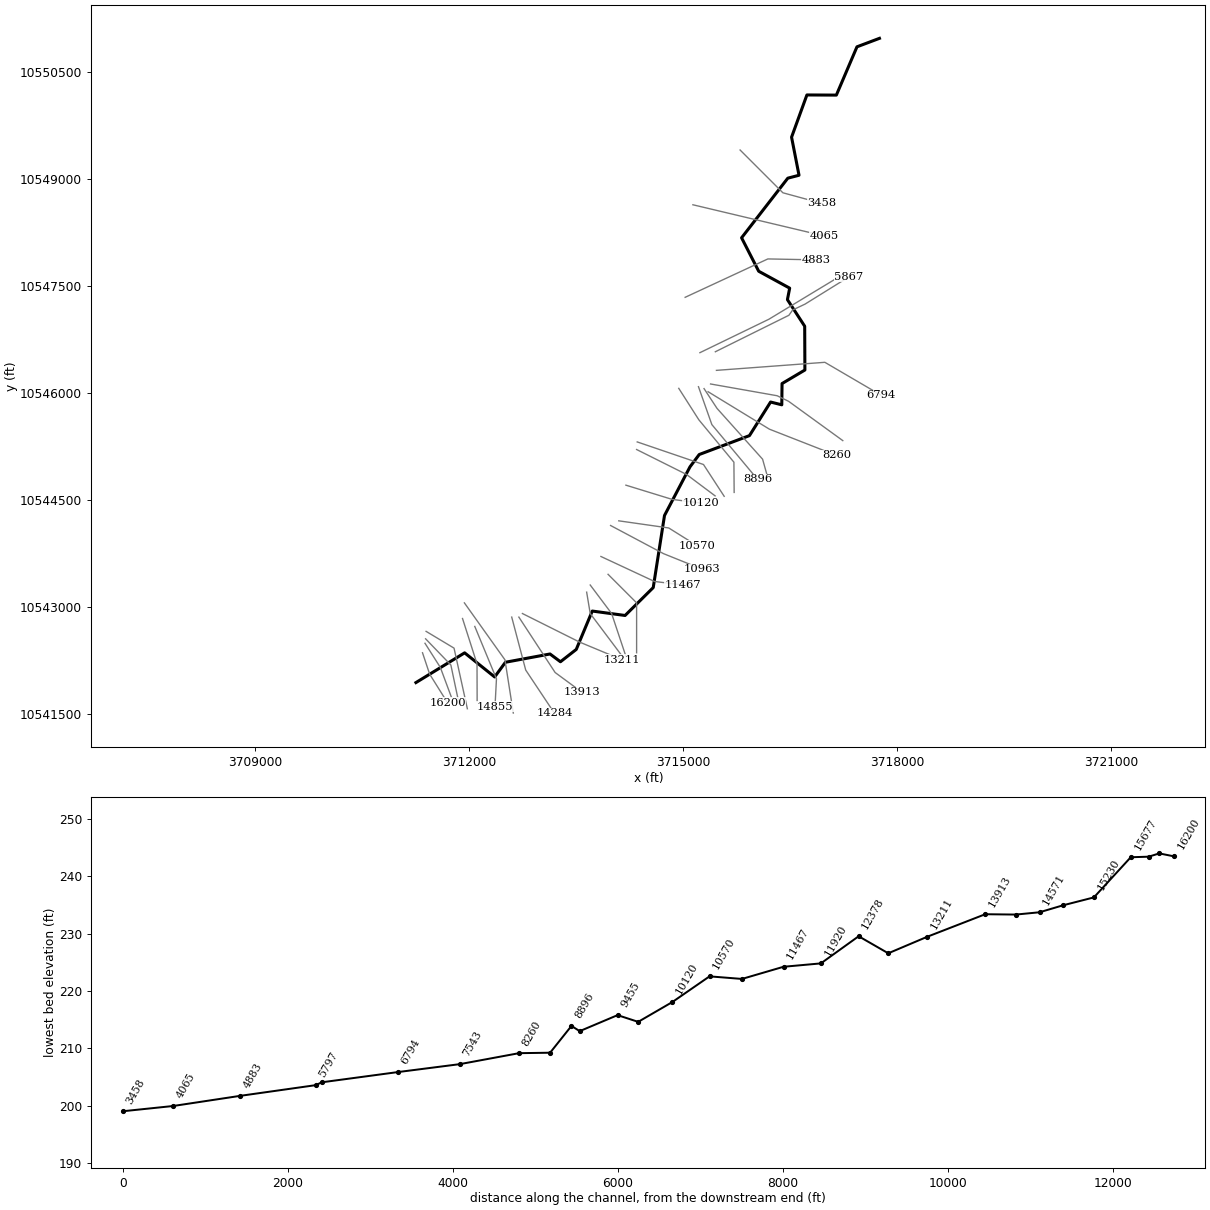
--- EADS CREEK.prj (project) ---

Proj Title=EADS CREEK Base Level Engineering
Current Plan=p01
Default Exp/Contr=0.3,0.1
English Units
Geom File=g01
Flow File=f01
Plan File=p01
Y Axis Title=Elevation
X Axis Title(PF)=Main Channel Distance
X Axis Title(XS)=Station
BEGIN DESCRIPTION:
EADS CREEK
END DESCRIPTION:
DSS Export Rating Curves= 0
DSS Export Rating Curve Sorted= 0
DSS Export Volume Flow Curves= 0
DXF OffsetX= 0
DXF OffsetY= 0
DXF ScaleX= 1
DXF ScaleY= 10

--- EADS CREEK.p01 (plan) ---

Plan Title=Multiple Run
Short Identifier=Multiple
Geom File=g01
Flow File=f01
Subcritical Flow
K Sum by GR= 0
Std Step Tol= 0.01
Critical Tol= 0.01
Num of Std Step Trials= 20
Max Error Tol= 0.3
Flow Tol Ratio= 0.001
Split Flow NTrial= 30
Split Flow Tol= 0.02
Split Flow Ratio= 0.02
Log Output Level= 0
Friction Slope Method= 1
Unsteady Friction Slope Method= 2
Unsteady Bridges Friction Slope Method= 1
Parabolic Critical Depth
Global Vel Dist=  1 , 1 , 1
Global Log Level= 0
CheckData=True
Encroach Param= -1, 0, 0, 0
BEGIN DESCRIPTION:
Multiple Run
END DESCRIPTION:

--- EADS CREEK.f01 (steady flow) ---

Flow Title=Multiple
Program Version=4.10
Number of Profiles= 7
Profile Names=10-year,25-year,50-year,1pct_min,100-year,1pct_plu,500-year
River Rch & RM=EADS CREEK,Reach-1         ,16200
     858    1194    1477    1343    1816    2456    2756
River Rch & RM=EADS CREEK,Reach-1         ,8996
    1305    1849    2318    2129    2880    3894    4468
River Rch & RM=EADS CREEK,Reach-1         ,8260
    1886    2686    3375    3104    4197    5676    6525
River Rch & RM=EADS CREEK,Reach-1         ,6794
    1886    2686    3375    3104    4197    5676    6525
Boundary for River Rch & Prof#=EADS CREEK,Reach-1         , 1
Up Type= 0
Dn Type= 3
Dn Slope=0.002
Boundary for River Rch & Prof#=EADS CREEK,Reach-1         , 2
Up Type= 0
Dn Type= 3
Dn Slope=0.002
Boundary for River Rch & Prof#=EADS CREEK,Reach-1         , 3
Up Type= 0
Dn Type= 3
Dn Slope=0.002
Boundary for River Rch & Prof#=EADS CREEK,Reach-1         , 4
Up Type= 0
Dn Type= 3
Dn Slope=0.002
Boundary for River Rch & Prof#=EADS CREEK,Reach-1         , 5
Up Type= 0
Dn Type= 3
Dn Slope=0.002
Boundary for River Rch & Prof#=EADS CREEK,Reach-1         , 6
Up Type= 0
Dn Type= 3
Dn Slope=0.002
Boundary for River Rch & Prof#=EADS CREEK,Reach-1         , 7
Up Type= 0
Dn Type= 3
Dn Slope=0.002
DSS Import GetInterval= 0
DSS Import GetPeak= 0
DSS Import FillOption= 0

--- EADS CREEK.g01 (geometry) ---

Geom Title=Existing Conditions
Program Version=4.10

River Reach=EADS CREEK      ,Reach-1
Reach XY= 30
      3711257.25       10541942.      3711939.75       10542359.
       3712360.5       10542021.      3712511.25       10542227.
      3713136.25       10542343.       3713282.5       10542234.
        3713504.       10542407.      3713728.25       10542945.
      3714188.25       10542883.       3714582.5       10543274.
       3714740.5       10544285.       3715097.5       10544967.
        3715227.       10545140.        3715931.       10545405.
        3716227.       10545876.        3716384.       10545837.
      3716387.75       10546135.      3716707.75       10546325.
        3716705.       10546939.        3716463.       10547312.
       3716494.5       10547473.       3716060.5       10547710.
       3715820.5       10548179.      3716468.25       10549015.
       3716625.5       10549056.        3716521.       10549590.
        3716736.       10550182.      3717148.75       10550180.
       3717437.5       10550857.      3717752.75       10550976.

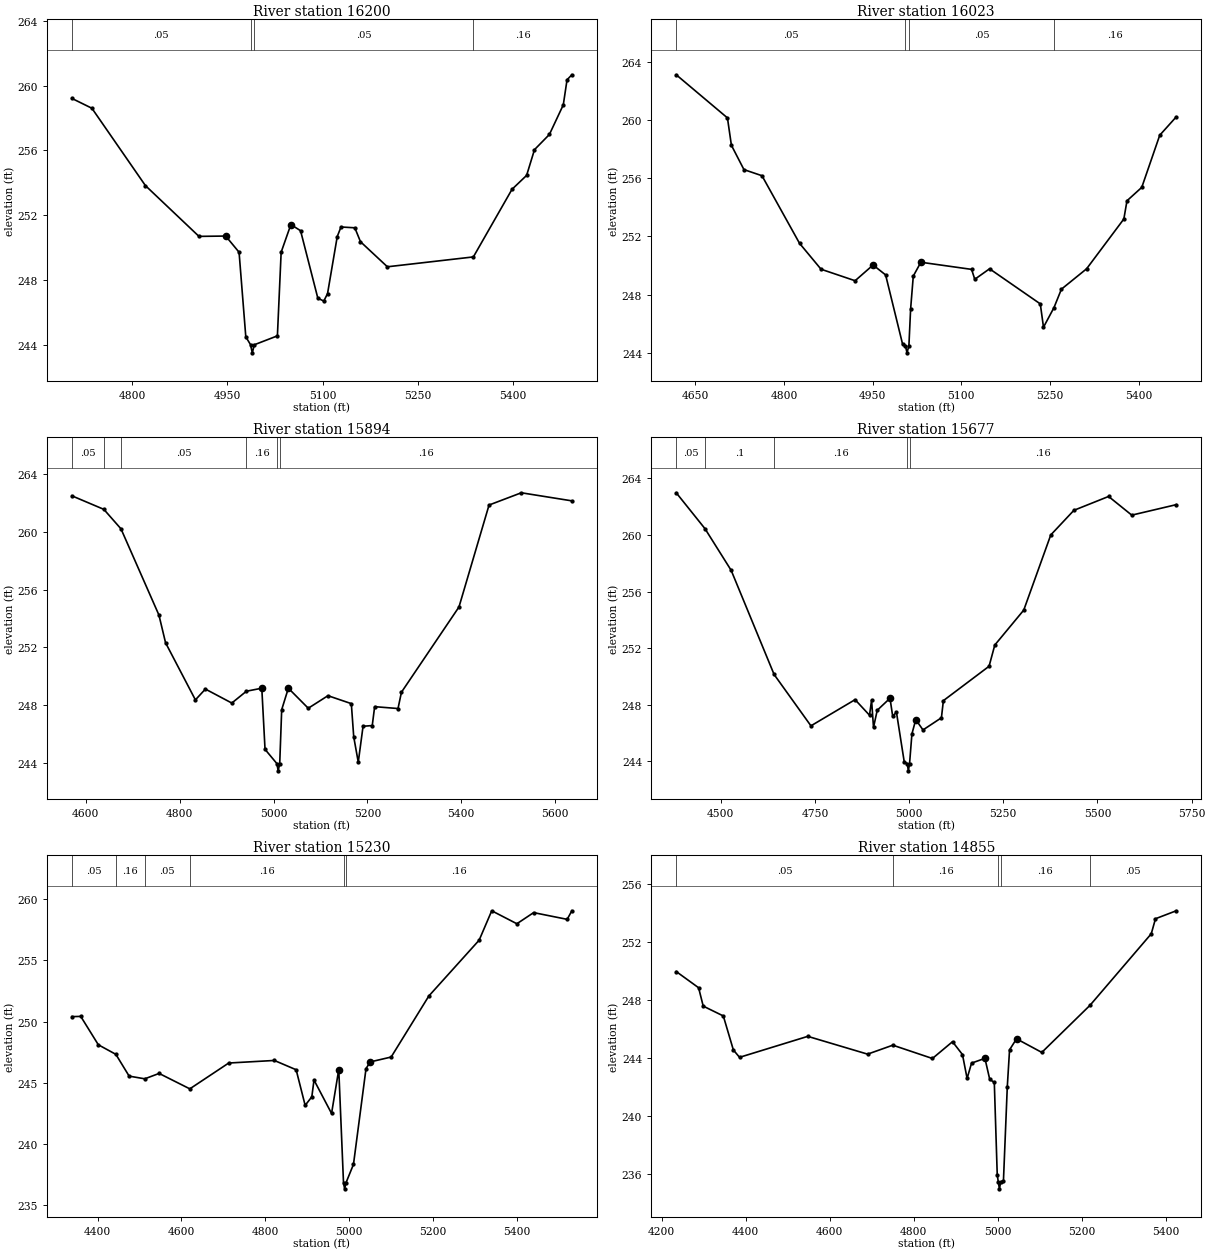
Type RM Length L Ch R = 1 ,16200   ,177,177,177
BEGIN DESCRIPTION:
EADS CREEK 29.0
END DESCRIPTION:
XS GIS Cut Line= 3
      3711349.61     10542360.18      3711449.61     10542060.19
       3711699.6      10541660.2
#Sta/Elev= 30
    4705  259.22  4736.6  258.61  4820.9  253.83  4905.3  250.69  4947.4  250.71
  4968.5  249.71  4979.1  244.48  4986.6  243.99  4989.3  243.49  4992.6  243.99
  5028.9  244.54  5034.8  249.71  5050.1  251.42  5065.4  251.04  5092.6  246.87
    5102  246.69  5107.9  247.15  5123.2  250.68  5129.1  251.27  5150.9  251.22
  5159.8  250.36  5202.2  248.81  5337.7  249.42  5398.6   253.6  5421.6  254.46
    5434  256.05  5457.5  256.99  5479.4  258.82  5485.3  260.37  5492.9  260.68
#Mann= 4 ,-1 , 0
    4705     .05       0  4986.6     .03       0  4992.6     .05       0
  5337.7     .16       0
Bank Sta=4947.4,5050.1
XS Rating Curve= 0 ,0
Exp/Cntr=0.3,0.1

Type RM Length L Ch R = 1 ,16023   ,129,129,129
BEGIN DESCRIPTION:
Mapping XS 3da1cf2b
END DESCRIPTION:
XS GIS Cut Line= 3
      3711384.14     10542493.28      3711599.44      10542154.7
      3711753.94     10541738.06
#Sta/Elev= 30
  4617.8  263.09  4704.4  260.13  4711.1  258.25  4732.3  256.58  4762.8  256.16
  4826.3  251.52  4862.7  249.74  4920.3  248.95  4950.7  250.03  4971.9  249.35
  5000.7  244.58  5005.3   244.5  5008.1     244  5011.3   244.5  5014.2  247.02
  5018.7  249.27  5031.5  250.22  5117.3  249.73  5122.7  249.05  5147.7  249.77
  5233.5  247.36  5238.9  245.76  5256.7  247.11  5269.2  248.37  5311.8  249.77
  5374.8  253.19  5380.1  254.44  5405.1  255.36  5435.5  258.94  5463.4   260.2
#Mann= 4 ,-1 , 0
  4617.8     .05       0  5005.3     .03       0  5011.3     .05       0
  5256.7     .16       0
Bank Sta=4950.7,5031.5
XS Rating Curve= 0 ,0
Exp/Cntr=0.3,0.1

Type RM Length L Ch R = 1 ,15894   ,217,217,217
BEGIN DESCRIPTION:
Mapping XS 44f1b895
END DESCRIPTION:
XS GIS Cut Line= 3
      3711392.87     10542555.71      3711747.01     10542187.69
      3711861.49     10541644.77
#Sta/Elev= 30
  4570.2   262.5  4638.4  261.56  4674.9  260.21  4755.8  254.23  4769.9  252.31
  4833.5  248.35  4854.8   249.1  4911.1  248.13  4942.2  248.95    4975  249.16
  4981.9  244.92  5007.2  243.93  5009.9  243.43  5013.2  243.93  5017.4  247.67
  5031.6  249.16    5074  247.77    5116  248.64  5165.8  248.09  5170.9  245.79
  5180.6  244.03  5190.8  246.52  5210.4  246.57  5215.5  247.88  5265.3  247.75
  5272.6  248.88  5395.2  254.79  5459.3  261.86  5528.1  262.71  5635.8  262.15
#Mann= 6 ,-1 , 0
  4570.2     .05       0  4638.4      .1       0  4674.9     .05       0
  4942.2     .16       0  5007.2     .07       0  5013.2     .16       0
Bank Sta=4975,5031.6
XS Rating Curve= 0 ,0
Exp/Cntr=0.3,0.1

Type RM Length L Ch R = 1 ,15677   ,447,447,447
BEGIN DESCRIPTION:
EADS CREEK 28.0
END DESCRIPTION:
XS GIS Cut Line= 3
      3711399.57     10542660.21      3711791.32     10542425.05
      3711977.86     10541574.79
#Sta/Elev= 30
  4381.7  262.98  4458.1  260.44  4527.5   257.5  4641.5  250.14  4739.3  246.51
  4856.5  248.36  4894.8  247.26  4900.3  248.32  4905.4   246.4  4915.3  247.61
  4949.2  248.46  4956.2  247.21  4966.4  247.46  4986.9  243.98  4995.1  243.83
  4997.9  243.33  5001.1  243.83  5007.4  245.94  5017.6  246.95  5036.8  246.22
  5085.7  247.08  5090.9  248.29  5212.2  250.72  5227.4  252.22  5304.3  254.69
    5376     260  5437.4  261.74  5529.5  262.72    5591   261.4  5709.1  262.14
#Mann= 5 ,-1 , 0
  4381.7     .05       0  4458.1      .1       0  4641.5     .16       0
  4995.1     .07       0  5001.1     .16       0
Bank Sta=4949.2,5017.6
XS Rating Curve= 0 ,0
Exp/Cntr=0.3,0.1

Type RM Length L Ch R = 1 ,15230   ,375,375,375
BEGIN DESCRIPTION:
Mapping XS ac9d36be
END DESCRIPTION:
XS GIS Cut Line= 3
      3711910.22     10542840.42      3712113.33     10542205.05
      3712115.06       10541679.
#Sta/Elev= 30
  4338.5   250.4  4359.7  250.42  4401.7   248.1  4443.5  247.32  4475.2  245.54
  4512.5  245.32  4546.7  245.76    4620   244.5  4712.8  246.61  4821.7  246.82
  4873.7  246.06  4895.2  243.15  4911.1  243.85  4916.3  245.22  4958.2  242.49
  4975.4  246.08  4986.7  236.83  4989.4  236.33  4992.7  236.83  5010.5  238.33
  5040.4  246.15  5050.4   246.7  5100.4   247.1  5190.4  252.09  5310.4  256.65
  5340.4  259.05  5400.4  257.99  5440.4   258.9  5520.4  258.35  5531.6  259.05
#Mann= 6 ,-1 , 0
  4338.5     .05       0  4443.5     .16       0  4512.5     .05       0
    4620     .16       0  4986.7     .07       0  4992.7     .16       0
Bank Sta=4975.4,5050.4
XS Rating Curve= 0 ,0
Exp/Cntr=0.3,0.1

Type RM Length L Ch R = 1 ,14855   ,284,284,284
BEGIN DESCRIPTION:
Mapping XS 1fc3ed5b
END DESCRIPTION:
XS GIS Cut Line= 3
      3712082.08     10542729.34       3712385.9     10541994.98
      3712365.06     10541600.86
#Sta/Elev= 30
    4235  249.97  4288.2  248.85  4299.2  247.58    4347   246.9  4370.9  244.55
  4385.6  244.04  4547.9  245.49  4690.2  244.26  4750.2  244.88  4844.4  243.96
  4892.2  245.12  4915.9  244.23  4926.9  242.58  4937.5  243.64  4969.3  243.97
  4980.8  242.51  4991.6  242.31  4998.6  235.92    5001  235.45  5003.8  234.95
    5007  235.45  5013.3  235.46  5022.5     242  5027.9  244.56  5044.5  245.32
  5104.6  244.38  5219.4  247.64    5365  252.58    5375  253.62  5424.4  254.17
#Mann= 5 ,-1 , 0
    4235     .05       0  4750.2     .16       0    5001     .07       0
    5007     .16       0  5219.4     .05       0
Bank Sta=4969.3,5044.5
XS Rating Curve= 0 ,0
Exp/Cntr=0.3,0.1

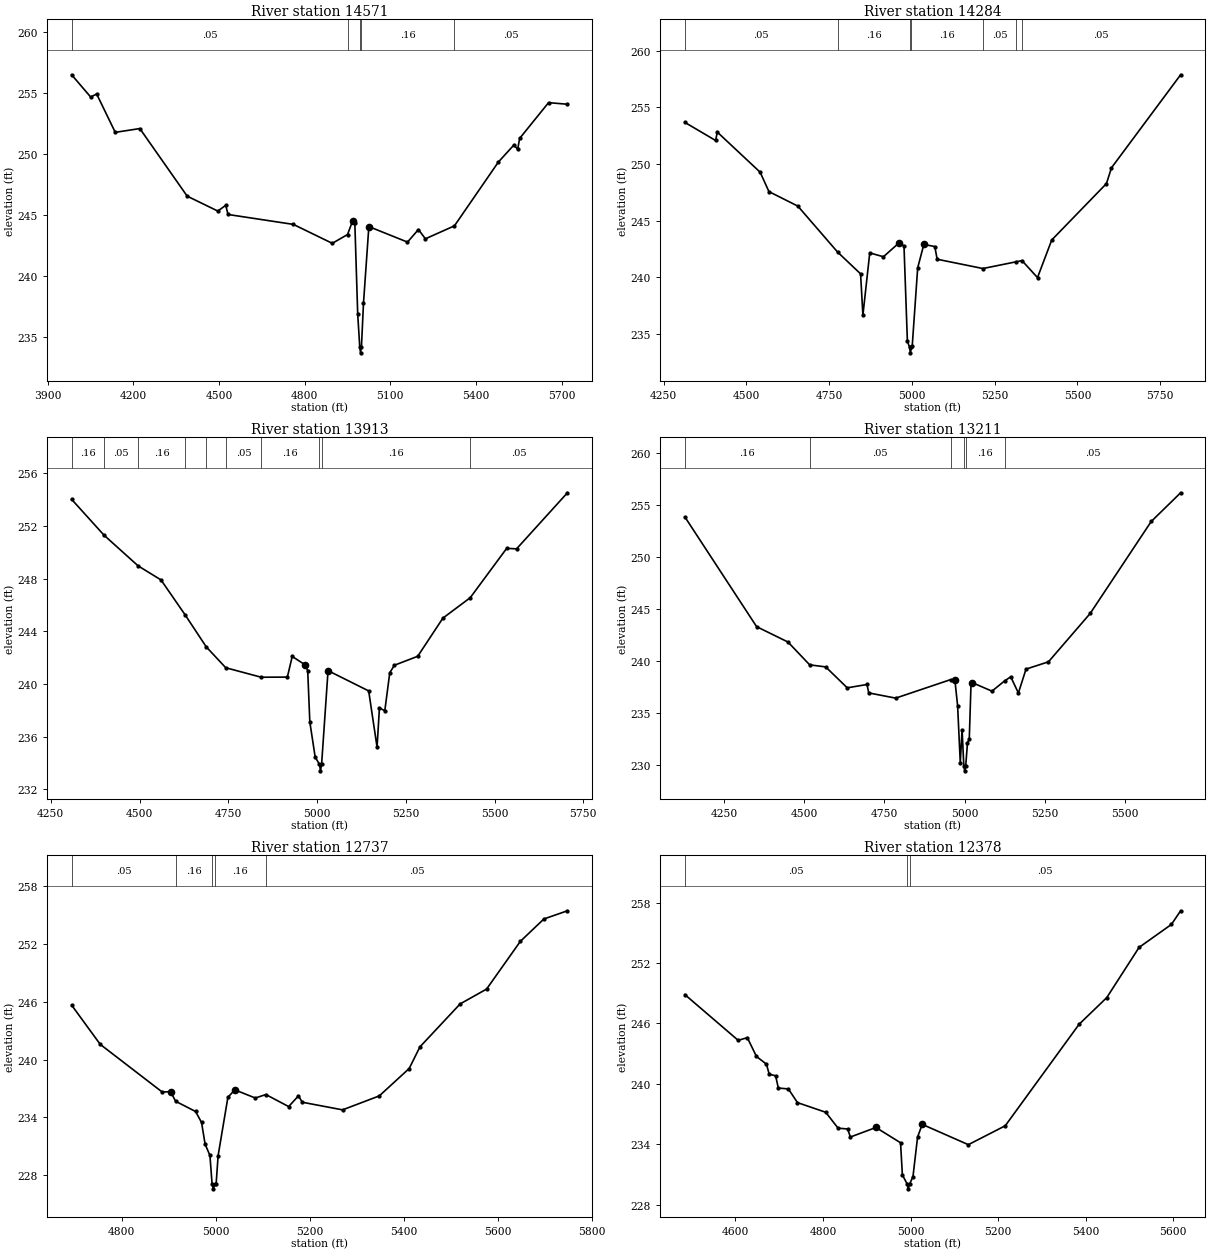
Type RM Length L Ch R = 1 ,14571   ,287,287,287
BEGIN DESCRIPTION:
EADS CREEK 27.0
END DESCRIPTION:
XS GIS Cut Line= 3
      3711936.17     10543059.71      3712504.72     10542261.13
      3712621.87     10541514.86
#Sta/Elev= 30
  3984.4  256.49    4051  254.67  4071.9  254.92  4137.1  251.78  4223.1  252.09
  4388.9  246.56  4496.1  245.34  4523.9  245.81  4531.8  245.06  4760.4  244.25
  4896.9   242.7  4950.3  243.42  4967.7  244.51  4975.8  244.37  4985.9   236.9
    4993  234.24  4995.8  233.74    4999  234.24  5006.1  237.79  5024.9  244.07
  5160.2   242.8  5198.5  243.83  5222.8  243.07  5324.5  244.13  5478.3  249.35
  5532.5  250.74    5546   250.4  5552.7  251.28    5654  254.21  5720.1  254.08
#Mann= 5 ,-1 , 0
  3984.4     .05       0  4950.3     .16       0    4993     .07       0
    4999     .16       0  5324.5     .05       0
Bank Sta=4967.7,5024.9
XS Rating Curve= 0 ,0
Exp/Cntr=0.3,0.1

Type RM Length L Ch R = 1 ,14284   ,371,371,371
BEGIN DESCRIPTION:
EADS CREEK 26.0
END DESCRIPTION:
XS GIS Cut Line= 3
      3712599.61     10542860.17      3712795.52     10542117.91
      3713199.62     10541510.18
#Sta/Elev= 30
  4314.3  253.68  4407.2  252.08  4412.4  252.82  4541.8  249.28  4568.3  247.57
  4655.6  246.29  4775.8  242.23  4845.1  240.31  4852.1  236.66  4872.8  242.16
  4914.1  241.82  4960.8  243.03  4976.2  242.79  4986.5  234.37  4992.9  233.84
  4995.6  233.34  4998.9  233.84  5001.1  233.94  5017.6  240.84  5036.2  242.91
  5069.3  242.72  5076.4   241.6  5214.7  240.78  5315.8  241.38  5332.7  241.48
  5379.5  239.98  5422.5   243.3  5587.8  248.28  5602.9  249.67  5811.8  257.88
#Mann= 7 ,-1 , 0
  4314.3     .05       0  4775.8     .16       0  4992.9     .07       0
  4998.9     .16       0  5214.7     .05       0  5315.8     .16       0
  5332.7     .05       0
Bank Sta=4960.8,5036.2
XS Rating Curve= 0 ,0
Exp/Cntr=0.3,0.1

Type RM Length L Ch R = 1 ,13913   ,702,702,702
BEGIN DESCRIPTION:
EADS CREEK 25.0
END DESCRIPTION:
XS GIS Cut Line= 3
       3712699.6     10542860.21      3713207.84     10542083.18
        3713585.     10541805.73
#Sta/Elev= 30
  4308.7  254.02  4399.9   251.3  4495.9  248.97  4560.5   247.9  4628.6  245.24
  4687.8  242.82  4742.9  241.23  4842.7  240.51  4916.4  240.52  4930.1  242.09
  4965.9  241.46  4973.7  241.02  4979.7  237.11  4994.8  234.44  5006.9   233.9
  5009.7   233.4  5012.9   233.9    5031  241.01  5145.5  239.47  5169.1   235.2
  5175.8  238.18  5190.9  237.96  5204.9  240.85  5217.9  241.42  5283.6   242.1
  5354.6     245  5431.6  246.55  5534.3   250.3  5562.1  250.26  5705.4  254.52
#Mann= 10 ,-1 , 0
  4308.7     .16       0  4399.9     .05       0  4495.9     .16       0
  4628.6     .05       0  4687.8     .16       0  4742.9     .05       0
  4842.7     .16       0  5006.9     .07       0  5012.9     .16       0
  5431.6     .05       0
Bank Sta=4965.9,5031
XS Rating Curve= 0 ,0
Exp/Cntr=0.3,0.1

Type RM Length L Ch R = 1 ,13211   ,474,474,474
BEGIN DESCRIPTION:
EADS CREEK 24.0
END DESCRIPTION:
XS GIS Cut Line= 3
      3712749.65     10542910.17      3713549.61     10542510.19
      3714149.63     10542260.18
#Sta/Elev= 30
  4128.2  253.89  4351.8  243.34  4449.6  241.86    4517  239.67    4567  239.47
  4634.1  237.46  4695.6  237.78  4701.1  236.97    4785  236.47  4956.2  238.25
  4969.5  238.17  4977.9  235.74  4986.2  230.26  4991.8  233.44  4997.2  229.98
    5000  229.48  5003.2  229.98  5008.6  232.16  5014.2  232.52  5019.8  237.97
  5022.6  237.97  5084.9  237.14  5124.1  238.12  5143.4  238.52  5167.2  236.96
    5191  239.26  5260.9  239.96  5390.9  244.61    5581  253.45  5672.6  256.21
#Mann= 6 ,-1 , 0
  4128.2     .16       0    4517     .05       0  4956.2     .16       0
  4997.2     .07       0  5003.2     .16       0  5124.1     .05       0
Bank Sta=4969.5,5022.6
XS Rating Curve= 0 ,0
Exp/Cntr=0.3,0.1

Type RM Length L Ch R = 1 ,12737   ,359,359,359
BEGIN DESCRIPTION:
EADS CREEK 23.0
END DESCRIPTION:
XS GIS Cut Line= 3
      3713649.62     10543210.14      3713699.61     10542910.19
      3714149.62     10542310.18
#Sta/Elev= 30
  4693.8  245.66  4754.6  241.59  4886.4  236.64  4904.1  236.68  4914.9  235.68
  4957.3  234.62    4970  233.48  4977.6  231.22  4987.8  230.06  4992.4  227.09
  4995.1  226.59  4998.4  227.09    5001  227.09  5005.2  230.03    5026  236.09
  5040.6  236.87  5084.3  236.02  5106.8  236.38  5155.2  235.13    5176  236.24
  5184.3  235.58  5269.8  234.79  5347.9  236.24  5411.4  239.08  5434.3  241.33
  5519.8  245.79    5576  247.33  5647.9  252.29  5697.9  254.61  5747.9  255.46
#Mann= 5 ,-1 , 0
  4693.8     .05       0  4914.9     .16       0  4992.4     .07       0
  4998.4     .16       0  5106.8     .05       0
Bank Sta=4904.1,5040.6
XS Rating Curve= 0 ,0
Exp/Cntr=0.3,0.1

Type RM Length L Ch R = 1 ,12378   ,458,458,458
BEGIN DESCRIPTION:
EADS CREEK 22.0
END DESCRIPTION:
XS GIS Cut Line= 3
       3713699.6     10543310.21      3713999.61     10542910.19
      3714199.62     10542310.17
#Sta/Elev= 30
  4484.5  248.87  4606.4  244.32  4627.2  244.59  4648.1  242.72    4671  241.95
  4677.2  240.95  4691.8   240.8  4698.1  239.58    4721  239.49  4741.8  238.13
  4806.4  237.17  4834.5  235.59  4856.4  235.51  4862.6  234.71    4921  235.66
  4977.2  234.14  4981.4  230.95  4992.1  230.06  4994.8  229.56  4998.1  230.06
  5005.6  230.77  5016.1   234.7  5026.7  235.97  5132.1  233.95  5216.4  235.83
  5385.1  245.92  5448.3  248.57  5522.1  253.56  5595.9  255.84    5617   257.2
#Mann= 3 ,-1 , 0
  4484.5     .05       0  4992.1     .03       0  4998.1     .05       0
Bank Sta=4921,5026.7
XS Rating Curve= 0 ,0
Exp/Cntr=0.3,0.1

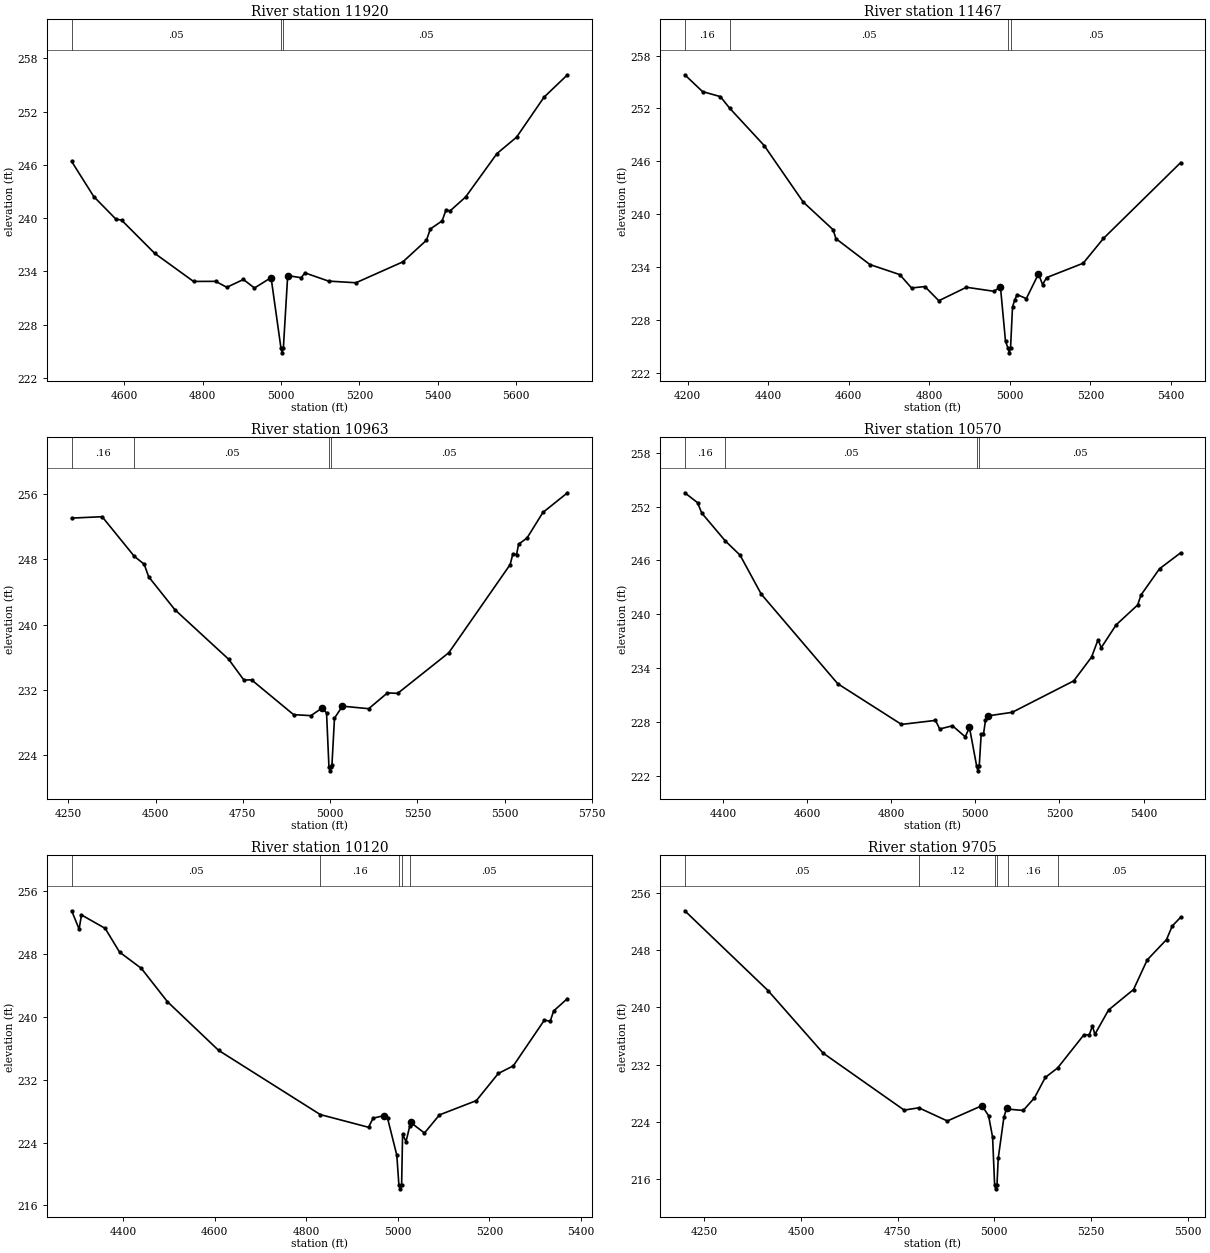
Type RM Length L Ch R = 1 ,11920   ,453,453,453
BEGIN DESCRIPTION:
EADS CREEK 21.0
END DESCRIPTION:
XS GIS Cut Line= 3
      3713949.62     10543460.18      3714349.61     10543060.19
      3714349.61     10542360.16
#Sta/Elev= 30
  4465.5  246.38  4522.1  242.42  4578.6  239.88  4592.8  239.78  4677.6  236.03
  4776.6  232.87  4833.2  232.88  4861.5  232.21  4903.9  233.09  4932.2  232.13
  4974.6   233.3  4999.9  225.33  5002.6  224.83  5005.9  225.33    5017  233.53
  5051.2  233.29  5061.2  233.83  5121.2  232.91  5191.2  232.72  5311.2  235.08
  5371.2  237.51  5381.2  238.78  5411.2  239.69  5421.2  240.93  5431.2   240.8
  5471.2  242.38  5551.2  247.27  5601.2  249.11  5671.2  253.61  5731.2  256.14
#Mann= 3 ,-1 , 0
  4465.5     .05       0  4999.9     .03       0  5005.9     .05       0
Bank Sta=4974.6,5017
XS Rating Curve= 0 ,0
Exp/Cntr=0.3,0.1

Type RM Length L Ch R = 1 ,11467   ,504,504,504
BEGIN DESCRIPTION:
EADS CREEK 20.0
END DESCRIPTION:
XS GIS Cut Line= 3
       3713849.6     10543710.19      3714599.61     10543360.19
      3714999.64     10543310.18
#Sta/Elev= 30
  4193.1  255.83  4237.2  253.92  4281.4  253.35  4304.2  252.05  4390.2  247.79
  4487.1  241.37  4561.2  238.23  4568.3  237.21  4652.6  234.27  4726.7  233.13
  4755.9  231.61    4789  231.77  4823.7  230.16  4892.3  231.69  4960.8  231.23
  4976.6  231.76  4989.2  225.55  4995.7  224.74  4998.4  224.24  5001.7  224.74
  5006.6  229.45  5012.1  230.26    5018  230.86  5040.9   230.4  5071.1  233.21
  5081.2     232  5091.3  232.79    5182  234.42  5232.4  237.24  5423.9  245.85
#Mann= 4 ,-1 , 0
  4193.1     .16       0  4304.2     .05       0  4995.7     .03       0
  5001.7     .05       0
Bank Sta=4976.6,5071.1
XS Rating Curve= 0 ,0
Exp/Cntr=0.3,0.1

Type RM Length L Ch R = 1 ,10963   ,393,393,393
BEGIN DESCRIPTION:
EADS CREEK 19.0
END DESCRIPTION:
XS GIS Cut Line= 3
      3713984.78      10544144.8      3714726.94     10543749.85
      3715264.85     10543532.95
#Sta/Elev= 30
  4259.4  253.07  4346.8  253.24  4438.9  248.39  4467.3  247.42  4480.1  245.88
  4555.2  241.85  4708.9   235.8  4752.9  233.24  4774.9  233.26  4895.4     229
    4945  228.88  4977.6  229.83  4989.8   229.2  4996.6  222.62  4999.3  222.12
  5002.6  222.62  5005.2  222.82  5012.5  228.57  5035.2  230.04  5110.5  229.73
  5164.2  231.66  5193.7  231.61  5340.2  236.59  5515.9  247.38  5523.5  248.68
  5534.3  248.61    5540  249.87  5564.2  250.63  5609.7  253.76  5680.1  256.17
#Mann= 4 ,-1 , 0
  4259.4     .16       0  4438.9     .05       0  4996.6     .03       0
  5002.6     .05       0
Bank Sta=4977.6,5035.2
XS Rating Curve= 0 ,0
Exp/Cntr=0.3,0.1

Type RM Length L Ch R = 1 ,10570   ,450,450,450
BEGIN DESCRIPTION:
EADS CREEK 18.0
END DESCRIPTION:
XS GIS Cut Line= 3
       3714099.6     10544210.19      3714799.61     10544110.19
      3715199.59      10543860.2
#Sta/Elev= 30
  4309.2  253.54  4339.5  252.44  4349.6  251.28  4405.4  248.18  4440.5   246.6
    4491  242.25  4672.9  232.27  4824.4  227.74  4905.2  228.19  4915.3  227.23
  4945.6  227.59  4975.9  226.36    4986   227.4  5003.2  223.07    5006  222.57
  5009.2  223.07  5013.8  226.63  5019.3  226.63    5024  228.18  5029.9  228.69
  5087.7  229.09  5233.9  232.59  5276.3  235.24  5291.7  237.17  5299.3  236.29
  5334.7  238.83    5386  241.05  5393.7  242.15  5437.9  245.08    5488  246.85
#Mann= 4 ,-1 , 0
  4309.2     .16       0  4405.4     .05       0  5003.2     .03       0
  5009.2     .05       0
Bank Sta=4986,5029.9
XS Rating Curve= 0 ,0
Exp/Cntr=0.3,0.1

Type RM Length L Ch R = 1 ,10120   ,415,415,415
BEGIN DESCRIPTION:
EADS CREEK 17.0
END DESCRIPTION:
XS GIS Cut Line= 3
      3714199.66     10544710.17      3714849.61     10544510.19
      3715249.57     10544460.19
#Sta/Elev= 30
  4287.3  253.52  4303.6  251.19  4308.8  252.99  4360.5  251.28  4391.9  248.26
  4439.6  246.18  4496.5  241.94  4608.3  235.74  4830.4  227.56  4935.9  225.94
  4945.7   227.1  4969.8  227.43  4977.4  227.09  4997.6  222.38  5002.1   218.6
  5004.9   218.1  5008.1   218.6  5010.2  225.06  5017.7  224.12  5026.1  226.15
  5027.8  226.56    5058  225.21  5090.8  227.52  5171.4  229.34  5219.3   232.8
    5252  233.76    5320   239.6  5332.6  239.44  5340.2  240.76  5370.4  242.34
#Mann= 5 ,-1 , 0
  4287.3     .05       0  4830.4     .16       0  5002.1     .07       0
  5008.1     .16       0  5026.1     .05       0
Bank Sta=4969.8,5027.8
XS Rating Curve= 0 ,0
Exp/Cntr=0.3,0.1

Type RM Length L Ch R = 1 ,9705    ,250,250,250
BEGIN DESCRIPTION:
EADS CREEK 16.0
END DESCRIPTION:
XS GIS Cut Line= 3
      3714349.59      10545210.2      3715049.61     10544860.19
      3715449.57     10544560.22
#Sta/Elev= 30
  4199.5  253.52  4414.7  242.37  4557.3  233.62  4766.9  225.65  4804.9  225.97
  4878.7  224.13  4968.2  226.27  4985.3  224.87  4995.7  221.87    5001  215.14
  5003.8  214.64    5007  215.14  5010.3  218.92  5024.9  224.63  5032.1  225.92
  5036.6  225.78  5074.9   225.6    5104  227.36  5132.1  230.22  5163.9  231.54
  5232.1  236.19  5245.7  236.17    5254  237.42  5260.3  236.24  5295.7  239.65
  5360.3  242.51  5395.7  246.65  5445.7   249.5  5460.3  251.38  5482.1  252.61
#Mann= 6 ,-1 , 0
  4199.5     .05       0  4804.9     .12       0    5001     .07       0
    5007     .12       0  5036.6     .16       0  5163.9     .05       0
Bank Sta=4968.2,5032.1
XS Rating Curve= 0 ,0
Exp/Cntr=0.3,0.1

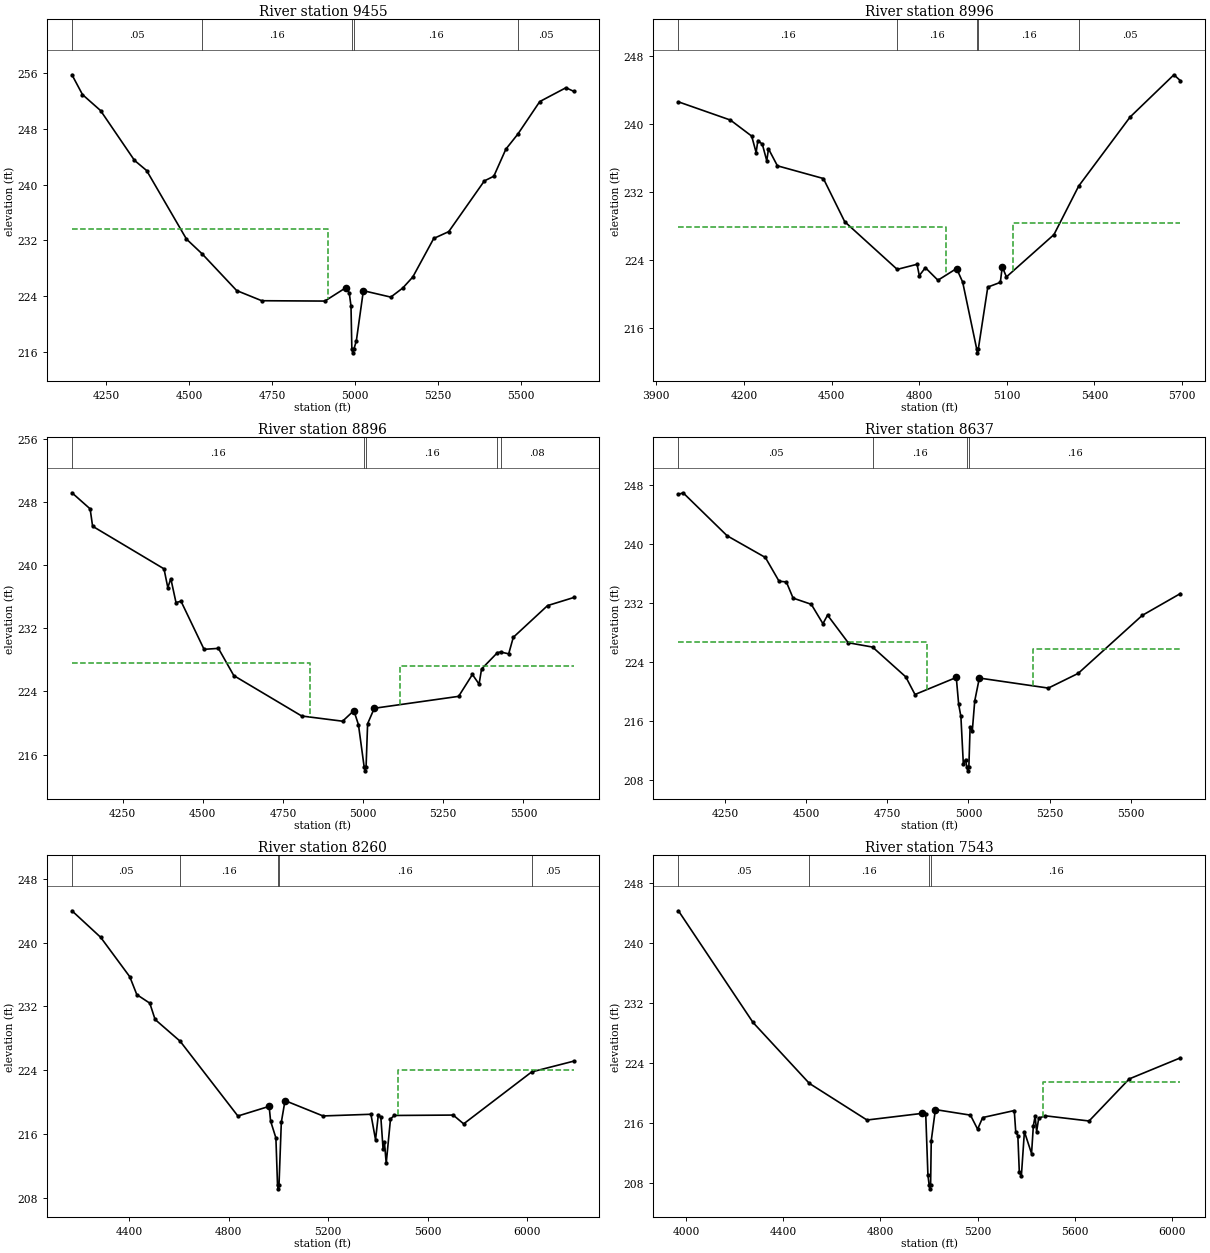
Type RM Length L Ch R = 1 ,9455    ,459,459,459
BEGIN DESCRIPTION:
EADS CREEK 15.0
END DESCRIPTION:
XS GIS Cut Line= 3
      3714358.05     10545316.68      3715286.84     10544999.85
      3715576.84     10544554.02
#Sta/Elev= 30
    4146  255.77  4177.8  252.92  4232.2  250.63  4334.5  243.47  4371.1  242.01
  4491.2  232.16  4538.6  230.03  4642.6  224.76  4718.2   223.3  4908.4  223.25
  4971.8  225.17    4982  224.43  4987.3  222.55  4989.9  216.31  4992.7  215.81
  4995.9  216.31  5003.5  217.56  5024.6  224.74  5107.3  223.82  5143.2  225.12
  5173.5   226.7  5236.8  232.25    5282  233.23  5389.4  240.52  5417.9  241.19
  5454.2  245.08  5490.4  247.25  5556.4  251.92  5635.4  253.91  5659.2  253.38
#Mann= 5 ,-1 , 0
    4146     .05       0  4538.6     .16       0  4989.9     .07       0
  4995.9     .16       0  5490.4     .05       0
#XS Ineff= 2 , 0
         4918.41  233.65
Permanent Ineff=
       F       F
Bank Sta=4971.8,5024.6
XS Rating Curve= 0 ,0
Exp/Cntr=0.3,0.1

Type RM Length L Ch R = 1 ,8996    ,100,100,100
BEGIN DESCRIPTION:
Mapping XS 0eeb7f19
END DESCRIPTION:
XS GIS Cut Line= 4
      3714940.43     10546067.83      3715221.67     10545626.87
      3715713.09     10545032.41      3715716.52     10544608.32
#Sta/Elev= 30
  3975.8  242.61  4153.9  240.46  4226.7  238.57  4241.9  236.63  4247.8  238.05
  4263.1  237.62  4278.3  235.66  4284.2  237.07  4314.7  235.07  4472.1  233.57
  4545.2  228.48  4724.9  222.86  4792.9  223.46  4800.5  222.12  4821.3  223.06
  4864.3  221.58  4928.2  222.96    4949  221.36  4996.8  213.52  4999.6  213.02
  5002.8  213.52    5035  220.77    5078  221.33  5084.5  223.17  5098.8  221.97
  5261.6  226.96  5346.2  232.68  5522.3  240.82  5672.3   245.8  5694.2  245.11
#Mann= 5 ,-1 , 0
  3975.8     .16       0  4724.9     .16       0  4996.8     .07       0
  5002.8     .16       0  5346.2     .05       0
#XS Ineff= 2 , 0
         4893.18  227.87 5121.59          228.27
Permanent Ineff=
       F       F
Bank Sta=4928.2,5084.5
XS Rating Curve= 0 ,0
Exp/Cntr=0.3,0.1

Type RM Length L Ch R = 1 ,8896    ,259,259,259
BEGIN DESCRIPTION:
EADS CREEK 14.0
END DESCRIPTION:
XS GIS Cut Line= 3
      3715216.54     10546090.96      3715404.02     10545559.75
      3716045.47     10544790.01
#Sta/Elev= 30
  4091.9  249.17  4148.6  247.13  4156.3  244.93    4379  239.53  4390.8  237.16
  4400.3  238.28  4416.4  235.26  4432.1  235.42  4503.9  229.33  4548.7  229.45
  4596.7     226  4808.4  220.88  4935.9  220.22  4971.1  221.56  4985.4  219.78
  5003.2  214.43    5006  213.93  5009.2  214.43    5014   219.9  5034.8  221.86
  5297.8  223.37  5340.8  226.14  5361.6  224.92  5369.4  226.84  5418.9  228.91
  5428.5  228.99    5454  228.76  5468.3  230.85  5575.1  234.87  5657.2   235.9
#Mann= 5 ,-1 , 0
  4091.9     .16       0  5003.2     .04       0  5009.2     .16       0
  5418.9     .12       0  5428.5     .08       0
#XS Ineff= 2 , 0
         4833.52  227.57 5113.75          227.22
Permanent Ineff=
       F       F
Bank Sta=4971.1,5034.8
XS Rating Curve= 0 ,0
Exp/Cntr=0.3,0.1

Type RM Length L Ch R = 1 ,8637    ,377,377,377
BEGIN DESCRIPTION:
EADS CREEK 13.0
END DESCRIPTION:
XS GIS Cut Line= 4
      3715294.63     10546064.12      3715476.94     10545786.31
      3716114.96      10545074.5      3716184.39     10544827.15
#Sta/Elev= 30
    4107  246.73  4121.4  246.96    4257  241.13  4374.6  238.19  4416.8  234.97
  4439.3  234.87    4460  232.68    4516  231.84  4551.9  229.21  4566.1  230.37
  4629.7  226.63  4704.7  226.04  4806.9     222  4835.3  219.61  4962.4  221.92
  4969.8  218.26  4976.6  216.63  4984.1   210.2  4990.8  210.79  4995.1  209.76
  4997.9  209.26  5001.1  209.76    5005  215.22  5011.7  214.67  5019.2  218.74
  5033.4  221.84  5245.7  220.48  5337.6  222.47  5534.7  230.33  5652.1  233.29
#Mann= 4 ,-1 , 0
    4107     .05       0  4704.7     .16       0  4995.1     .07       0
  5001.1     .16       0
#XS Ineff= 2 , 0
         4872.39  226.78 5199.66          225.78
Permanent Ineff=
       F       F
Bank Sta=4962.4,5033.4
XS Rating Curve= 0 ,0
Exp/Cntr=0.3,0.1

Type RM Length L Ch R = 1 ,8260    ,717,717,717
BEGIN DESCRIPTION:
EADS CREEK 12.0
END DESCRIPTION:
XS GIS Cut Line= 3
      3715351.06     10546020.69      3716210.45     10545495.51
      3717152.31     10545126.58
#Sta/Elev= 30
  4169.6  243.97  4285.1  240.65  4402.3  235.71  4430.5  233.48  4482.7  232.41
    4504  230.37  4604.7  227.65    4837  218.29  4962.7   219.5  4968.6  217.66
  4989.9  215.55  4996.4  209.68  4999.2  209.18  5002.4  209.68  5011.7  217.51
  5026.6  220.22  5179.4   218.3  5372.1  218.51  5390.7  215.32  5401.9  218.45
  5412.1  218.11  5420.9  214.18  5426.3  215.08  5433.6  212.37  5450.8  217.92
  5465.8  218.36    5703  218.41  5745.1  217.31  6018.8  223.81  6188.3  225.16
#Mann= 5 ,-1 , 0
  4169.6     .05       0  4604.7     .16       0  4999.2     .07       0
  5002.4     .16       0  6018.8     .05       0
#XS Ineff= 2 , 0
                         5481.53          224.07
Permanent Ineff=
       F       F
Bank Sta=4962.7,5026.6
XS Rating Curve= 0 ,0
Exp/Cntr=0.3,0.1

Type RM Length L Ch R = 1 ,7543    ,749,749,749
BEGIN DESCRIPTION:
EADS CREEK 11.0
END DESCRIPTION:
XS GIS Cut Line= 4
      3715385.81     10546129.19      3716318.95     10545964.26
      3716479.54     10545886.13      3717238.87     10545335.08
#Sta/Elev= 30
    3969  244.32  4275.8  229.44  4507.5  221.32  4744.6  216.44  4972.9  217.33
  4986.3   217.2  4995.2  209.13  5000.3  207.77  5003.1  207.27  5006.3  207.77
  5008.9  213.67  5025.9  217.83  5170.2  217.09  5199.6  215.22  5220.5  216.77
  5350.4   217.7  5356.6   214.8  5365.1  214.37  5371.2  209.48  5379.5  208.94
  5392.1  214.89  5421.5  211.97  5428.9  215.67  5436.2  216.94  5442.4  214.91
  5450.9  216.69  5478.3     217  5658.1  216.31  5823.5  221.92  6033.4  224.72
#Mann= 4 ,-1 , 0
    3969     .05       0  4507.5     .16       0  5000.3     .07       0
  5006.3     .16       0
#XS Ineff= 2 , 0
                         5467.05          221.52
Permanent Ineff=
       F       F
Bank Sta=4972.9,5025.9
XS Rating Curve= 0 ,0
Exp/Cntr=0.3,0.1

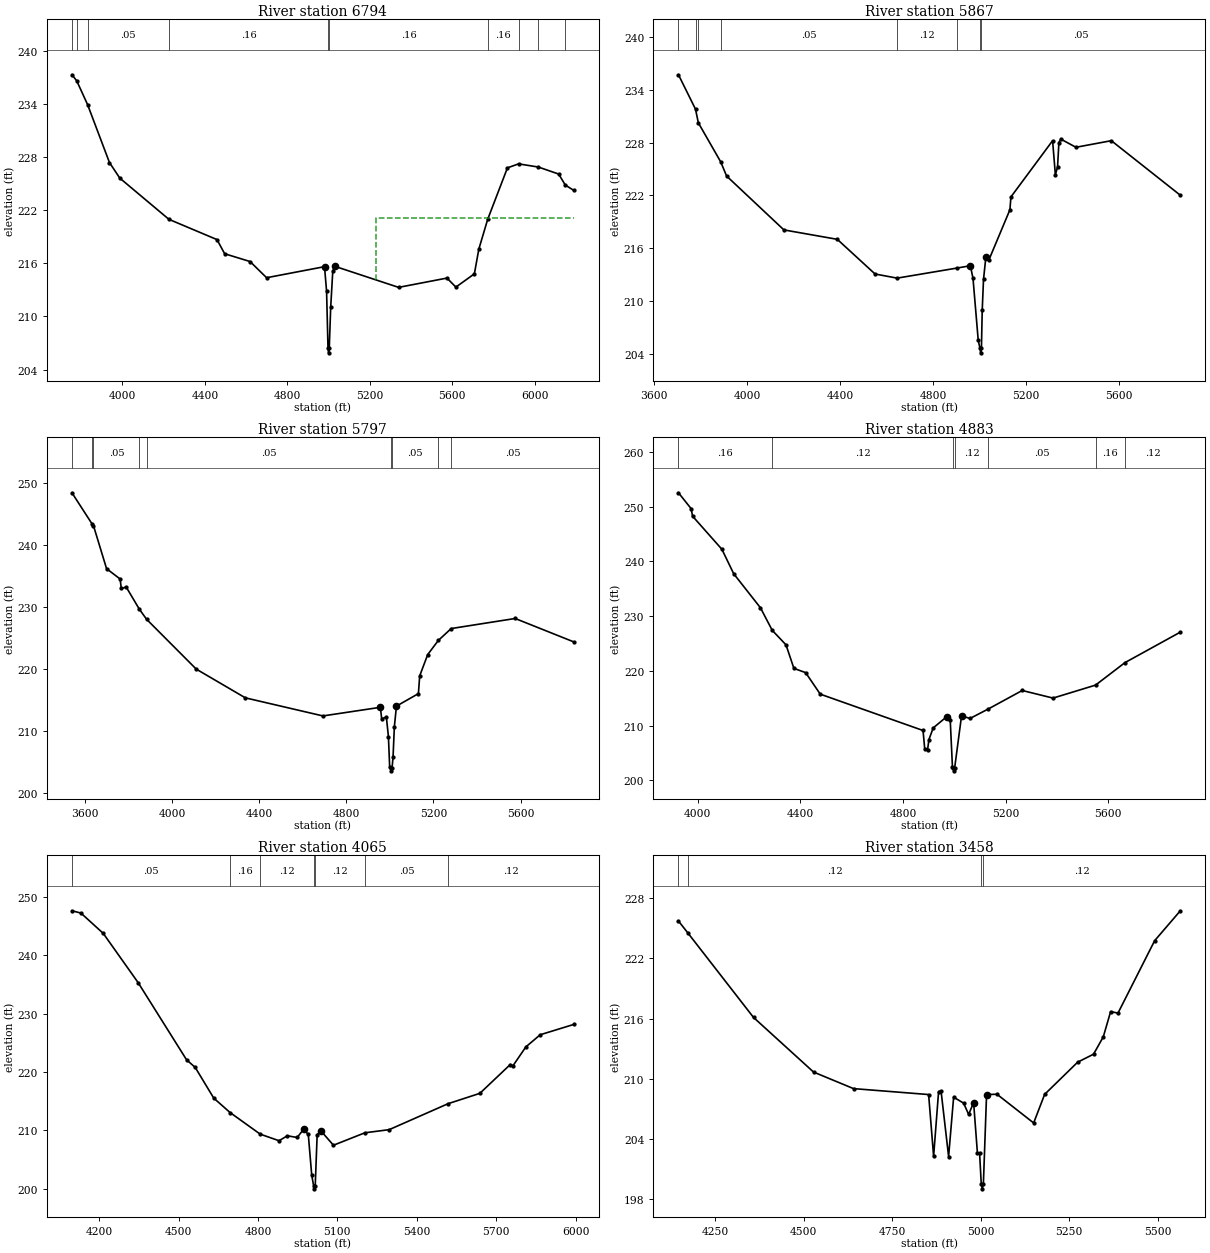
Type RM Length L Ch R = 1 ,6794    ,927,927,927
BEGIN DESCRIPTION:
EADS CREEK 10.0
END DESCRIPTION:
XS GIS Cut Line= 3
      3715468.22     10546320.16      3716987.36     10546433.01
      3717772.93     10545972.95
#Sta/Elev= 30
  3755.3  237.32  3778.2  236.65  3831.1  233.95  3937.2   227.4  3987.3  225.64
  4225.6  220.98  4458.6  218.69  4495.9  217.09  4619.1  216.21  4699.3  214.38
  4980.1  215.63  4990.1  212.87  4997.1  206.39  4999.9  205.89  5003.1  206.39
  5010.1  211.04  5020.2  215.13  5030.2  215.67  5339.3  213.29  5573.9  214.34
  5617.3  213.32  5706.9  214.82  5728.4  217.61  5771.4  220.98  5867.2   226.8
  5921.1  227.25  6017.3  226.89  6115.6   226.1  6147.6  224.86    6189  224.25
#Mann= 10 ,-1 , 0
  3755.3     .05       0  3778.2     .16       0  3831.1     .05       0
  4225.6     .16       0  4997.1     .07       0  5003.1     .16       0
  5771.4     .16       0  5921.1     .12       0  6017.3     .16       0
  6147.6     .12       0
#XS Ineff= 2 , 0
                         5228.41          221.16
Permanent Ineff=
       F       F
Bank Sta=4980.1,5030.2
XS Rating Curve= 0 ,0
Exp/Cntr=0.3,0.1

Type RM Length L Ch R = 1 ,5867    ,70,70,70
BEGIN DESCRIPTION:
Mapping XS b1ac663c
END DESCRIPTION:
XS GIS Cut Line= 5
      3715452.98     10546581.12      3716483.88     10547092.73
      3716535.97     10547166.52      3716709.58     10547248.98
      3717326.34     10547632.18
#Sta/Elev= 30
  3705.1   235.7  3778.4  231.79  3790.6  230.24  3886.7  225.81  3912.3  224.19
  4158.8  218.07  4388.5     217    4551  213.06    4646  212.59  4904.8  213.74
  4961.2     214  4972.5  212.56    4995  205.51  5002.7   204.6  5005.4   204.1
  5008.7   204.6  5012.2  208.96  5017.7  212.44  5027.8  214.98  5040.4  214.63
  5131.3  220.36  5135.7  221.82    5315  228.21  5326.9  224.34  5336.3  225.22
  5342.1     228  5350.4  228.39  5415.4  227.46  5567.7  228.21  5864.6  222.01
#Mann= 8 ,-1 , 0
  3705.1     .05       0  3778.4     .16       0  3790.6     .08       0
  3886.7     .05       0    4646     .12       0  4904.8     .05       0
  5002.7     .04       0  5008.7     .05       0
Bank Sta=4961.2,5027.8
XS Rating Curve= 0 ,0
Exp/Cntr=0.3,0.1

Type RM Length L Ch R = 1 ,5797    ,914,914,914
BEGIN DESCRIPTION:
Mapping XS 2fa8a560
END DESCRIPTION:
XS GIS Cut Line= 3
      3715236.85     10546568.11        3716203.     10547036.86
      3717256.13     10547673.94
#Sta/Elev= 30
  3539.8  248.38  3633.4   243.3  3638.7  243.08  3698.8  236.16  3760.9   234.5
  3766.5  232.97    3789   233.2  3849.2  229.64  3882.9     228  4110.6  219.99
  4336.3  215.36  4692.5  212.45  4956.3  213.84  4962.2  211.98  4983.7  212.27
  4993.2  209.13    4999  204.17  5004.1  204.11  5006.8  203.61  5010.1  204.11
  5014.5  205.87  5020.4  210.67    5030  214.03  5130.9  216.04  5136.8   218.9
  5173.6  222.33  5222.5  224.61  5281.5  226.52  5575.2  228.14  5844.5  224.37
#Mann= 9 ,-1 , 0
  3539.8     .05       0  3633.4     .08       0  3638.7     .05       0
  3849.2     .08       0  3882.9     .05       0  5004.1     .04       0
  5010.1     .05       0  5222.5     .16       0  5281.5     .05       0
Bank Sta=4956.3,5030
XS Rating Curve= 0 ,0
Exp/Cntr=0.3,0.1

Type RM Length L Ch R = 1 ,4883    ,818,818,818
BEGIN DESCRIPTION:
EADS CREEK 9.0
END DESCRIPTION:
XS GIS Cut Line= 3
      3715029.89     10547344.47      3716188.75     10547882.66
      3716865.18     10547869.65
#Sta/Elev= 30
  3925.9  252.55  3975.2  249.65  3980.7  248.28  4095.1  242.22  4140.9  237.76
  4245.3  231.53    4291  227.42  4344.6  224.77  4375.4  220.47  4421.2  219.69
    4478  215.76  4878.3  209.12  4884.8  205.78  4895.7   205.5  4901.2  207.47
  4917.9  209.59  4969.9  211.62  4984.1   211.1  4992.8  202.44  4995.3  202.25
    4998  201.75  5001.3  202.25  5028.2  211.79  5061.3  211.32  5132.3  213.05
  5264.5  216.43  5384.5  215.04    5550  217.41  5664.6  221.52  5880.2  227.09
#Mann= 7 ,-1 , 0
  3925.9     .16       0    4291     .12       0  4995.3     .07       0
  5001.3     .12       0  5132.3     .05       0    5550     .16       0
  5664.6     .12       0
Bank Sta=4969.9,5028.2
XS Rating Curve= 0 ,0
Exp/Cntr=0.3,0.1

Type RM Length L Ch R = 1 ,4065    ,607,607,607
BEGIN DESCRIPTION:
EADS CREEK 8.0
END DESCRIPTION:
XS GIS Cut Line= 2
      3715138.35     10548642.22      3716982.98     10548203.85
#Sta/Elev= 30
  4097.4  247.61  4131.2  247.22  4215.6  243.74  4347.3  235.31  4530.4  222.08
  4563.3  220.76  4633.2  215.51  4694.8  213.04  4808.7  209.34  4879.9  208.21
  4911.1  209.06  4948.1  208.77  4972.4  210.14  4990.3   209.3  5003.2  202.36
  5010.5  200.47  5013.2  199.97  5016.5  200.47  5023.8  209.21  5037.6  209.92
  5085.4  207.44    5204  209.57  5295.9  210.11    5518  214.55  5638.5  216.33
  5753.5  221.27  5763.8  221.07  5812.3  224.29  5866.6  226.37  5993.4  228.14
#Mann= 7 ,-1 , 0
  4097.4     .05       0  4694.8     .16       0  4808.7     .12       0
  5010.5     .07       0  5016.5     .12       0    5204     .05       0
    5518     .12       0
Bank Sta=4972.4,5037.6
XS Rating Curve= 0 ,0
Exp/Cntr=0.3,0.1

Type RM Length L Ch R = 1 ,3458    ,457,457,457
BEGIN DESCRIPTION:
EADS CREEK 7.0
END DESCRIPTION:
XS GIS Cut Line= 3
      3715799.64     10549410.16      3716399.61     10548810.19
      3716949.63     10548660.18
#Sta/Elev= 30
  4145.8  225.73  4172.6  224.53  4357.9  216.13  4527.6  210.69  4640.7  209.04
  4852.9  208.45    4867   202.3  4881.1  208.75  4888.2  208.76  4909.4  202.28
  4923.6  208.19  4951.9  207.59    4966  206.47  4980.1  207.64  4990.8  202.65
  4996.9  202.65  5001.7  199.56  5004.4  199.06  5007.7  199.56  5016.7  208.45
  5046.1  208.48  5149.8  205.62  5180.9  208.47  5274.1  211.67  5319.1  212.47
  5346.7   214.2  5367.4  216.71  5388.2  216.56  5491.8  223.77  5564.4  226.75
#Mann= 4 ,-1 , 0
  4145.8     .16       0  4172.6     .12       0  5001.7     .07       0
  5007.7     .12       0
Bank Sta=4980.1,5016.7
XS Rating Curve= 0 ,0
Exp/Cntr=0.3,0.1