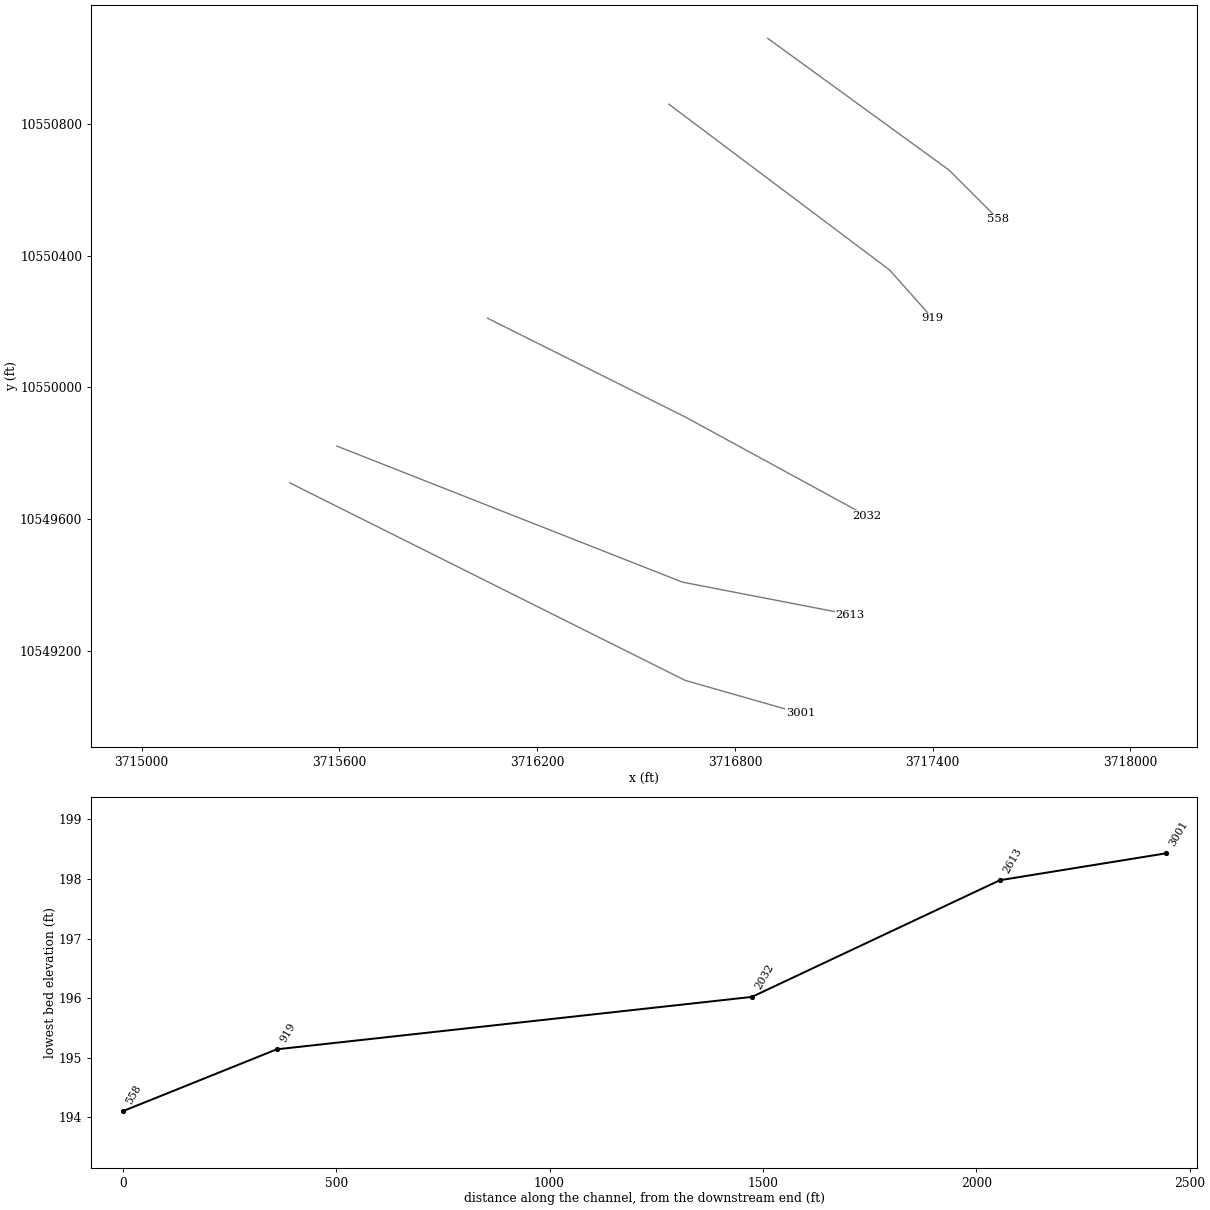
HEC-RAS study EADS CREEK.prj: EADS CREEK Base Level Engineering

--- EADS CREEK.g01 (geometry) --- (continued)

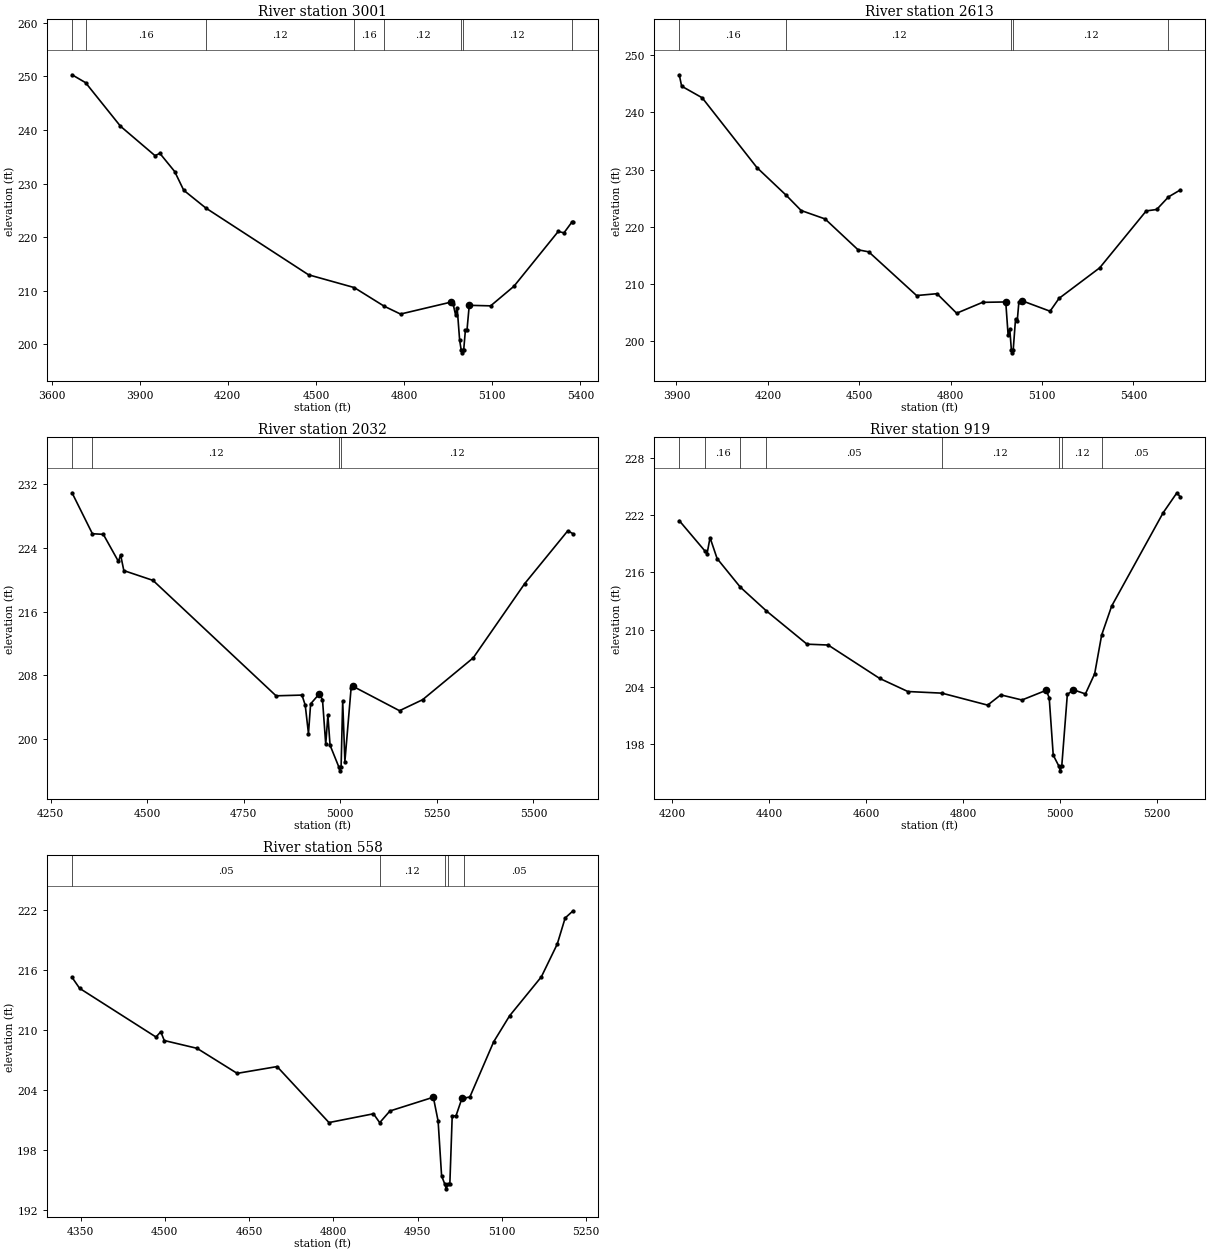
Type RM Length L Ch R = 1 ,3001    ,388,388,388
BEGIN DESCRIPTION:
EADS CREEK 6.0
END DESCRIPTION:
XS GIS Cut Line= 3
      3715449.58     10549710.21      3716649.61     10549110.19
      3716999.62     10549010.18
#Sta/Elev= 30
  3669.8  250.27  3715.9   248.8  3834.7  240.68  3952.1   235.2  3968.9  235.61
  4019.2  232.23    4050  228.74  4125.4  225.42  4474.8  212.98  4630.3   210.6
  4732.1  207.13  4787.9  205.66  4958.4  207.87  4966.8  207.56  4975.1  205.57
  4980.7  206.86  4989.1  200.84  4994.5  198.93  4997.3  198.43  5000.5  198.93
  5003.1  199.04  5008.7  202.61  5014.1  202.61  5021.9  207.29  5094.7  207.19
    5174  210.84  5324.8  221.06  5344.3   220.8  5370.7  222.76  5375.5  222.87
#Mann= 8 ,-1 , 0
  3669.8     .05       0  3715.9     .16       0  4125.4     .12       0
  4630.3     .16       0  4732.1     .12       0  4994.5     .07       0
  5000.5     .12       0  5370.7     .05       0
Bank Sta=4958.4,5021.9
XS Rating Curve= 0 ,0
Exp/Cntr=0.3,0.1

Type RM Length L Ch R = 1 ,2613    ,581,581,581
BEGIN DESCRIPTION:
EADS CREEK 5.0
END DESCRIPTION:
XS GIS Cut Line= 3
      3715592.35     10549821.91        3716641.      10549408.7
      3717149.62     10549310.19
#Sta/Elev= 30
  3909.2  246.55    3917  244.56  3984.5  242.53  4164.2  230.34  4260.7  225.48
  4309.4  222.84  4387.9  221.37  4496.2  215.98  4531.3  215.62  4688.4  207.99
  4755.4  208.31  4819.9   204.9    4905   206.8  4981.1  206.87  4988.9  201.09
  4994.3  202.16  4999.6  198.48  5002.3  197.98  5005.6  198.48  5013.3  203.94
  5018.7  203.47  5024.1  206.78  5032.9  207.11  5126.6  205.25    5156  207.49
  5289.6  212.83  5442.3  222.77  5476.7  223.02  5515.4  225.22  5554.4  226.44
#Mann= 5 ,-1 , 0
  3909.2     .16       0  4260.7     .12       0  4999.6     .07       0
  5005.6     .12       0  5515.4     .05       0
Bank Sta=4981.1,5032.9
XS Rating Curve= 0 ,0
Exp/Cntr=0.3,0.1

Type RM Length L Ch R = 1 ,2032    ,1113,1113,1113
BEGIN DESCRIPTION:
EADS CREEK 4.0
END DESCRIPTION:
XS GIS Cut Line= 3
      3716049.65     10550210.17      3716649.61     10549910.19
      3717199.63     10549610.17
#Sta/Elev= 30
  4305.5  230.93  4358.2  225.79  4386.5  225.71  4425.6  222.31  4431.2  223.14
  4439.6  221.16  4515.1  219.93  4833.7  205.44  4900.8  205.53  4909.2  204.27
  4917.6   200.7  4923.2  204.43  4945.5  205.67  4953.9  204.97  4962.3  199.35
  4967.9     203  4973.5  199.24  4996.1  196.52  4998.8  196.02  5002.1  196.52
  5006.2  204.83  5011.9  197.19    5028  206.43  5033.7  206.61  5153.3  203.57
  5213.1  204.95  5344.1   210.2  5477.5  219.53    5589  226.16  5602.8  225.78
#Mann= 4 ,-1 , 0
  4305.5     .16       0  4358.2     .12       0  4996.1     .07       0
  5002.1     .12       0
Bank Sta=4945.5,5033.7
XS Rating Curve= 0 ,0
Exp/Cntr=0.3,0.1

Type RM Length L Ch R = 1 ,919     ,361,361,361
BEGIN DESCRIPTION:
EADS CREEK 2.0
END DESCRIPTION:
XS GIS Cut Line= 3
       3716599.6     10550860.19      3717269.48     10550356.62
      3717399.58     10550210.22
#Sta/Elev= 30
  4214.5  221.45  4266.8   218.3  4271.8  217.95    4278  219.66  4292.6  217.46
  4340.4  214.46  4394.2  211.96    4478  208.46  4521.7  208.37  4627.9  204.86
  4686.2  203.48  4756.4  203.31  4850.8  202.05  4877.8  203.13  4921.6  202.59
  4971.6  203.61  4977.8  202.82  4986.1  196.79  4997.7  195.64  5000.5  195.14
  5003.7  195.64  5015.2  203.17  5027.8  203.66  5052.5  203.23  5071.6  205.35
    5086  209.42  5106.7  212.47  5212.9  222.28  5241.3  224.38  5248.4  223.93
#Mann= 8 ,-1 , 0
  4214.5     .12       0  4266.8     .16       0  4340.4     .12       0
  4394.2     .05       0  4756.4     .12       0  4997.7     .07       0
  5003.7     .12       0    5086     .05       0
Bank Sta=4971.6,5027.8
XS Rating Curve= 0 ,0
Exp/Cntr=0.3,0.1

Type RM Length L Ch R = 1 ,558     ,0,0,0
BEGIN DESCRIPTION:
EADS CREEK 1.0
END DESCRIPTION:
XS GIS Cut Line= 3
      3716899.65     10551060.16      3717449.61     10550660.19
      3717599.64     10550510.16
#Sta/Elev= 30
  4334.9  215.29  4348.4  214.19  4484.4  209.31  4492.9  209.84  4499.1  208.96
  4557.4  208.18  4628.9  205.67    4700  206.35  4792.4  200.74  4871.6  201.62
  4882.7  200.73  4900.9   201.9  4978.2  203.28  4986.7  200.89  4992.9   195.4
  4998.4   194.6  5001.2   194.1  5004.4   194.6  5007.6  194.62  5011.8  201.41
  5018.5  201.41  5029.1  203.16  5033.3   203.2  5043.2   203.3  5085.6  208.83
  5113.9  211.43  5170.5  215.34  5198.8  218.62  5212.9  221.24  5227.1  221.96
#Mann= 5 ,-1 , 0
  4334.9     .05       0  4882.7     .12       0  4998.4     .07       0
  5004.4     .12       0  5033.3     .05       0
Bank Sta=4978.2,5029.1
XS Rating Curve= 0 ,0
Exp/Cntr=0.3,0.1

Chan Stop Cuts=-1
Use User Specified Reach Order=0
Composite Channel Slope=5