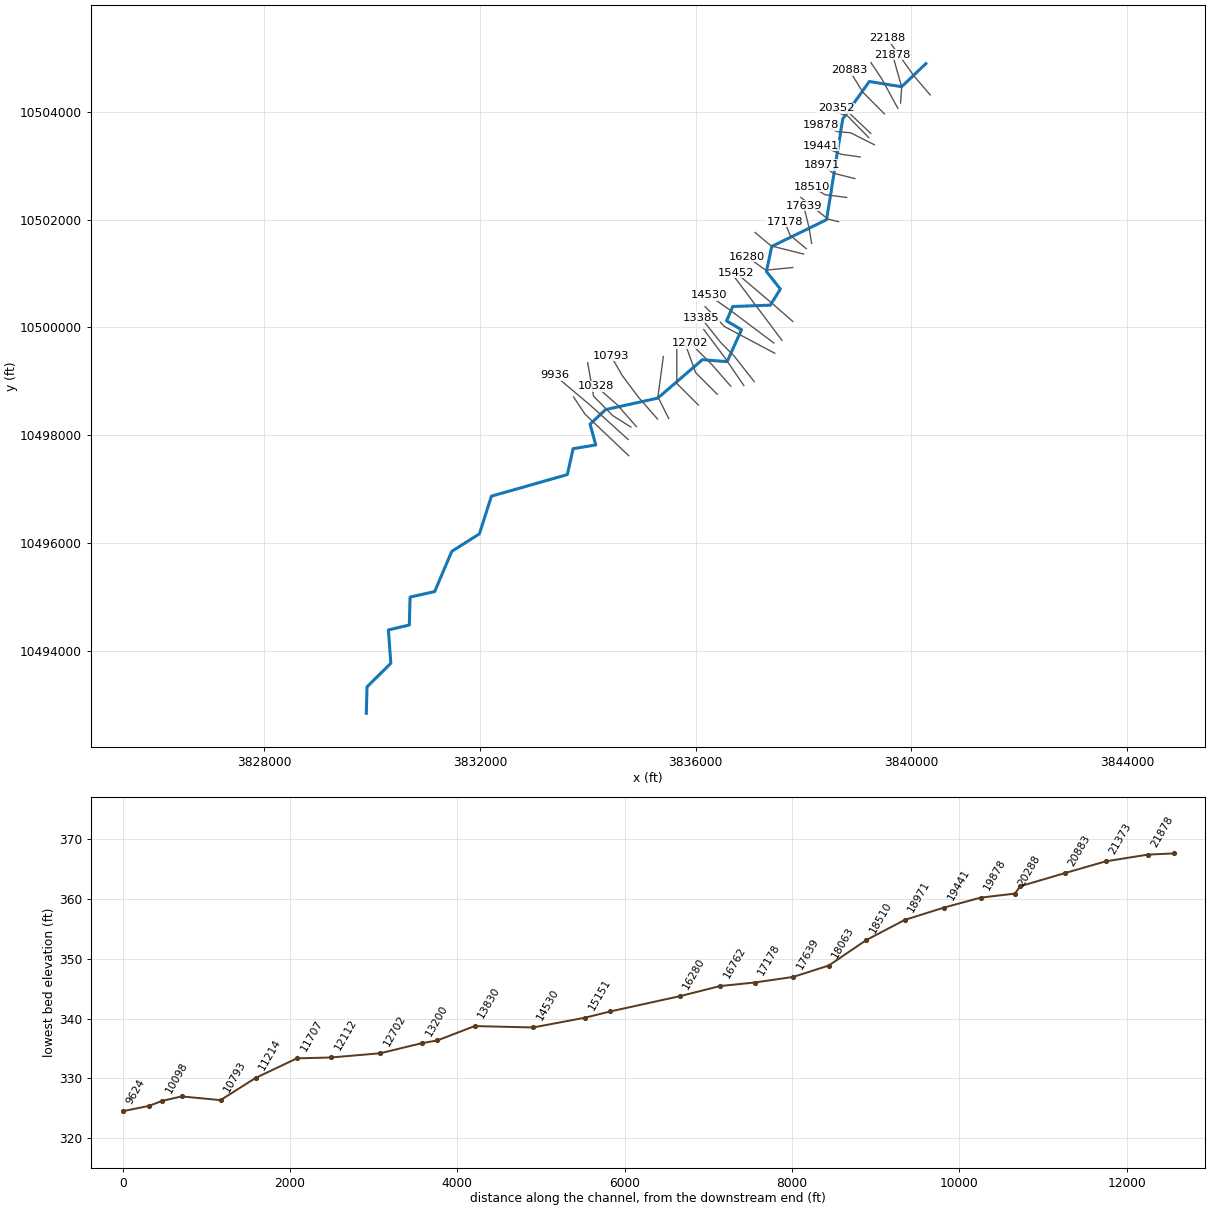
--- FLAT BRANCH.prj (project) ---

Proj Title=FLAT BRANCH Base Level Engineering
Current Plan=p01
Default Exp/Contr=0.3,0.1
English Units
Geom File=g01
Flow File=f01
Plan File=p01
Y Axis Title=Elevation
X Axis Title(PF)=Main Channel Distance
X Axis Title(XS)=Station
BEGIN DESCRIPTION:
FLAT BRANCH
END DESCRIPTION:
DSS Export Rating Curves= 0
DSS Export Rating Curve Sorted= 0
DSS Export Volume Flow Curves= 0
DXF OffsetX= 0
DXF OffsetY= 0
DXF ScaleX= 1
DXF ScaleY= 10

--- FLAT BRANCH.p01 (plan) ---

Plan Title=Multiple Run
Short Identifier=Multiple
Geom File=g01
Flow File=f01
Subcritical Flow
K Sum by GR= 0
Std Step Tol= 0.01
Critical Tol= 0.01
Num of Std Step Trials= 20
Max Error Tol= 0.3
Flow Tol Ratio= 0.001
Split Flow NTrial= 30
Split Flow Tol= 0.02
Split Flow Ratio= 0.02
Log Output Level= 0
Friction Slope Method= 1
Unsteady Friction Slope Method= 2
Unsteady Bridges Friction Slope Method= 1
Parabolic Critical Depth
Global Vel Dist=  1 , 1 , 1
Global Log Level= 0
CheckData=True
Encroach Param= -1, 0, 0, 0
BEGIN DESCRIPTION:
Multiple Run
END DESCRIPTION:

--- FLAT BRANCH.f01 (steady flow) ---

Flow Title=Multiple
Program Version=4.10
Number of Profiles= 7
Profile Names=10-year,25-year,50-year,1pct_min,100-year,1pct_plu,500-year
River Rch & RM=FLAT BRANCH,Reach-1         ,22188
     690     927    1122     996    1347    1822    1950
River Rch & RM=FLAT BRANCH,Reach-1         ,15452
     972    1327    1622    1453    1964    2657    2894
River Rch & RM=FLAT BRANCH,Reach-1         ,10793
    1183    1631    2005    1807    2443    3304    3641
River Rch & RM=FLAT BRANCH,Reach-1         ,7886
    1375    1906    2352    2126    2875    3888    4311
River Rch & RM=FLAT BRANCH,Reach-1         ,6700
    1375    1906    2352    2126    2875    3888    4311
River Rch & RM=FLAT BRANCH,Reach-1         ,3187
    1500    2085    2577    2332    3154    4265    4742
River Rch & RM=FLAT BRANCH,Reach-1         ,2935
    1500    2085    2577    2332    3154    4265    4742
Boundary for River Rch & Prof#=FLAT BRANCH,Reach-1         , 1
Up Type= 0
Dn Type= 3
Dn Slope=0.0028
Boundary for River Rch & Prof#=FLAT BRANCH,Reach-1         , 2
Up Type= 0
Dn Type= 3
Dn Slope=0.0028
Boundary for River Rch & Prof#=FLAT BRANCH,Reach-1         , 3
Up Type= 0
Dn Type= 3
Dn Slope=0.0028
Boundary for River Rch & Prof#=FLAT BRANCH,Reach-1         , 4
Up Type= 0
Dn Type= 3
Dn Slope=0.0028
Boundary for River Rch & Prof#=FLAT BRANCH,Reach-1         , 5
Up Type= 0
Dn Type= 3
Dn Slope=0.0028
Boundary for River Rch & Prof#=FLAT BRANCH,Reach-1         , 6
Up Type= 0
Dn Type= 3
Dn Slope=0.0028
Boundary for River Rch & Prof#=FLAT BRANCH,Reach-1         , 7
Up Type= 0
Dn Type= 3
Dn Slope=0.0028
DSS Import GetInterval= 0
DSS Import GetPeak= 0
DSS Import FillOption= 0

--- FLAT BRANCH.g01 (geometry) ---

Geom Title=Existing Conditions
Program Version=4.10

River Reach=FLAT BRANCH     ,Reach-1
Reach XY= 30
        3840269.       10504891.       3839818.5       10504463.
      3839219.25       10504559.      3838727.25       10503867.
      3838426.75       10501997.        3837410.       10501501.
      3837311.25       10501036.       3837569.5       10500710.
      3837383.75       10500412.        3836687.       10500387.
       3836572.5       10500121.      3836849.75       10499956.
      3836582.25       10499365.       3836124.5       10499401.
      3835296.25       10498688.      3834328.75       10498475.
        3834041.       10498205.       3834146.5       10497821.
       3833726.5       10497750.       3833619.5       10497270.
       3832211.5       10496870.      3831989.25       10496171.
      3831477.25       10495847.      3831158.75       10495100.
      3830703.25       10494999.       3830689.5       10494481.
      3830301.25       10494389.      3830346.25       10493771.
       3829904.5       10493333.        3829892.       10492842.

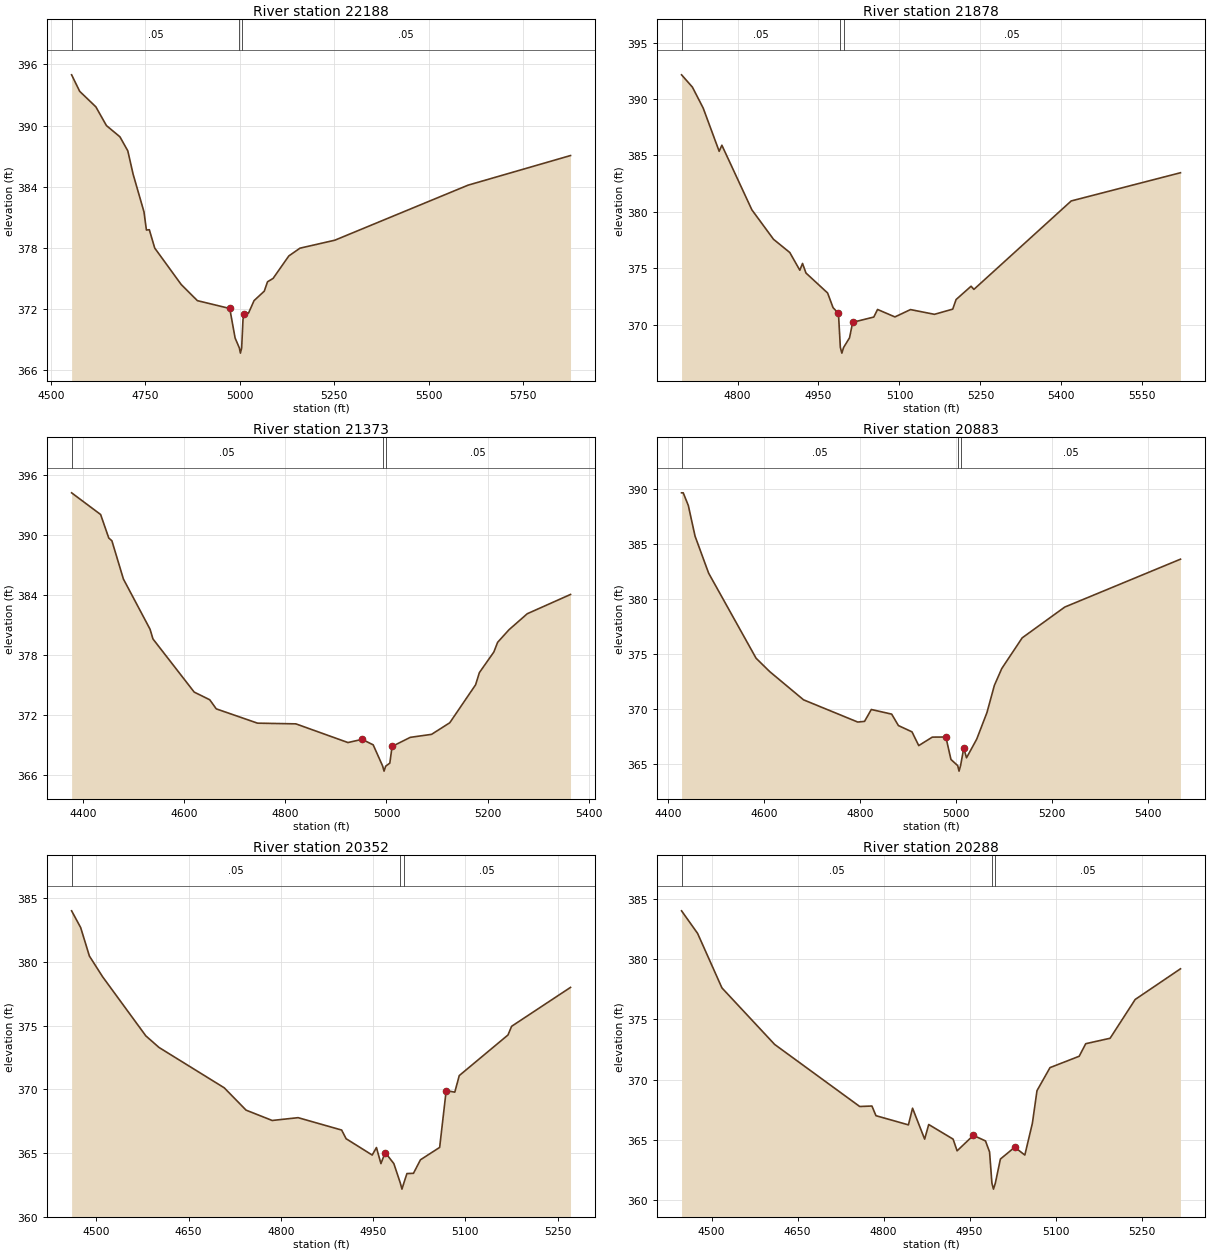
Type RM Length L Ch R = 1 ,22188   ,310,310,310
BEGIN DESCRIPTION:
FLAT BRANCH 43.0
END DESCRIPTION:
XS GIS Cut Line= 3
      3840349.63     10504310.16      3840049.61     10504660.19
      3839549.63     10505360.15
#Sta/Elev= 30
  4554.6  394.98    4576  393.36  4618.8  391.84  4646.8     390  4682.5   388.9
  4703.4  387.52  4717.6  385.21  4746.2  381.54  4752.7  379.75  4760.4  379.78
  4774.7  377.98  4844.9   374.4  4887.7  372.82  4973.4  372.05  4987.6  369.15
  4998.9  368.17  5001.6  367.67  5004.9  368.17  5008.5     371  5012.3  371.54
    5023  371.59  5037.7  372.82  5064.8  373.75  5073.4  374.67  5088.1     375
  5129.9  377.21  5159.4  377.97  5251.6  378.75  5604.3  384.15  5875.8  387.06
#Mann= 3 ,-1 , 0
  4554.6     .05       0  4998.9     .03       0  5004.9     .05       0
Bank Sta=4973.4,5012.3
XS Rating Curve= 0 ,0
Exp/Cntr=0.3,0.1

Type RM Length L Ch R = 1 ,21878   ,505,505,505
BEGIN DESCRIPTION:
FLAT BRANCH 42.0
END DESCRIPTION:
XS GIS Cut Line= 3
      3839799.61     10504160.16      3839819.73     10504458.27
       3839649.6      10505060.2
#Sta/Elev= 30
  4696.3  392.14  4716.4  391.05  4736.4  389.19    4766  385.36    4771   385.9
  4826.6  380.17  4866.7  377.56  4896.8  376.39  4915.4  374.82  4920.4  375.42
  4926.8  374.57  4966.9   372.8    4977   371.5    4987  370.99  4990.5  367.97
  4993.3  367.47  4996.5  367.97  5007.5  368.83  5013.3   370.2  5052.5  370.67
  5059.4  371.34  5091.6  370.68  5120.4  371.33  5164.8  370.91  5198.7  371.37
  5204.9  372.22  5232.7   373.4  5237.9  373.12  5418.2  380.96  5620.6  383.46
#Mann= 3 ,-1 , 0
  4696.3     .05       0  4990.5     .03       0  4996.5     .05       0
Bank Sta=4987,5013.3
XS Rating Curve= 0 ,0
Exp/Cntr=0.3,0.1

Type RM Length L Ch R = 1 ,21373   ,490,490,490
BEGIN DESCRIPTION:
FLAT BRANCH 41.0
END DESCRIPTION:
XS GIS Cut Line= 3
      3839749.59     10504060.22      3839449.61     10504610.19
      3839249.62     10504910.18
#Sta/Elev= 30
  4377.1  394.19  4434.5  392.02  4450.6  389.67  4456.8  389.39  4479.6  385.56
  4532.3  380.54    4538  379.57  4619.6  374.25  4650.4  373.48  4663.3  372.57
  4744.9  371.14  4820.8  371.07  4923.8   369.2  4951.8  369.52  4973.7  368.97
  4992.5  366.84  4995.2  366.34  4998.5  366.84  5006.6  367.14  5011.1  368.81
  5047.1  369.72  5089.2  370.02  5125.2  371.18  5176.3  374.98  5183.8   376.2
  5212.4  378.26  5219.9  379.23  5242.4  380.49  5278.5  382.09  5364.1  384.02
#Mann= 3 ,-1 , 0
  4377.1     .05       0  4992.5     .03       0  4998.5     .05       0
Bank Sta=4951.8,5011.1
XS Rating Curve= 0 ,0
Exp/Cntr=0.3,0.1

Type RM Length L Ch R = 1 ,20883   ,531,531,531
BEGIN DESCRIPTION:
FLAT BRANCH 40.0
END DESCRIPTION:
XS GIS Cut Line= 3
      3839499.58     10503960.22      3839099.61     10504360.19
      3838851.08     10504765.41
#Sta/Elev= 30
  4427.4  389.65  4430.9  389.65  4441.5   388.5  4455.6  385.71  4483.9  382.35
  4582.9  374.62  4611.2  373.41  4681.9  370.84    4795  368.82  4809.2  368.88
  4823.3  369.96  4865.8  369.54  4879.9   368.5  4908.2  367.93  4922.3  366.68
  4950.6  367.45  4978.9  367.46  4989.5  365.42  5003.6  364.86  5006.4  364.36
  5009.6  364.86  5016.2  366.45    5022  365.57  5043.3  367.27  5064.6  369.68
  5080.1  372.15  5095.5  373.68  5138.1  376.47    5227  379.27  5468.4  383.62
#Mann= 3 ,-1 , 0
  4427.4     .05       0  5003.6     .03       0  5009.6     .05       0
Bank Sta=4978.9,5016.2
XS Rating Curve= 0 ,0
Exp/Cntr=0.3,0.1

Type RM Length L Ch R = 1 ,20352   ,64,64,64
BEGIN DESCRIPTION:
FLAT BRANCH 39.0
END DESCRIPTION:
XS GIS Cut Line= 3
      3839246.75     10503596.41      3838855.75       10503967.
       3838599.6     10504060.19
#Sta/Elev= 30
  4459.7  383.99  4474.4  382.68  4488.6  380.45    4510  378.83  4580.4  374.19
  4601.9  373.28  4707.9  370.12  4743.4  368.37  4785.9  367.56    4828  367.78
  4898.8  366.81  4906.1  366.13  4948.5  364.85  4955.4  365.44  4962.7  364.18
  4969.6  365.05  4983.7  364.18  4994.1  362.68  4996.9  362.18  5000.1  362.68
    5005   363.4  5015.6  363.42    5027  364.48  5058.2  365.45  5068.8   369.9
  5082.8  369.78  5090.1  371.08  5169.3  374.26  5175.2  374.94    5271  377.99
#Mann= 3 ,-1 , 0
  4459.7     .05       0  4994.1     .03       0  5000.1     .05       0
Bank Sta=4969.6,5068.8
XS Rating Curve= 0 ,0
Exp/Cntr=0.3,0.1

Type RM Length L Ch R = 1 ,20288   ,410,410,410
BEGIN DESCRIPTION:
Mapping XS 59a71f1a
END DESCRIPTION:
XS GIS Cut Line= 3
      3839208.46     10503519.53      3838817.81     10503917.99
      3838524.12     10504023.26
#Sta/Elev= 30
  4447.7  383.98  4475.7  382.11  4518.1   377.6    4610  372.92  4758.4  367.78
  4779.7  367.82  4786.7  367.02  4843.3  366.26  4850.5  367.64  4871.6  365.08
  4878.7  366.29  4921.2  365.08  4928.2  364.11  4956.5  365.39  4977.7  364.93
  4984.8  364.02  4988.9  361.44  4991.6  360.94  4994.9  361.44  5003.7  363.43
  5028.7  364.41  5046.3  363.76  5059.5   366.4  5067.5  369.09  5090.2     371
  5141.1  371.94  5152.5  372.98    5195  373.43  5238.7  376.64  5317.7  379.18
#Mann= 3 ,-1 , 0
  4447.7     .05       0  4988.9     .03       0  4994.9     .05       0
Bank Sta=4956.5,5028.7
XS Rating Curve= 0 ,0
Exp/Cntr=0.3,0.1

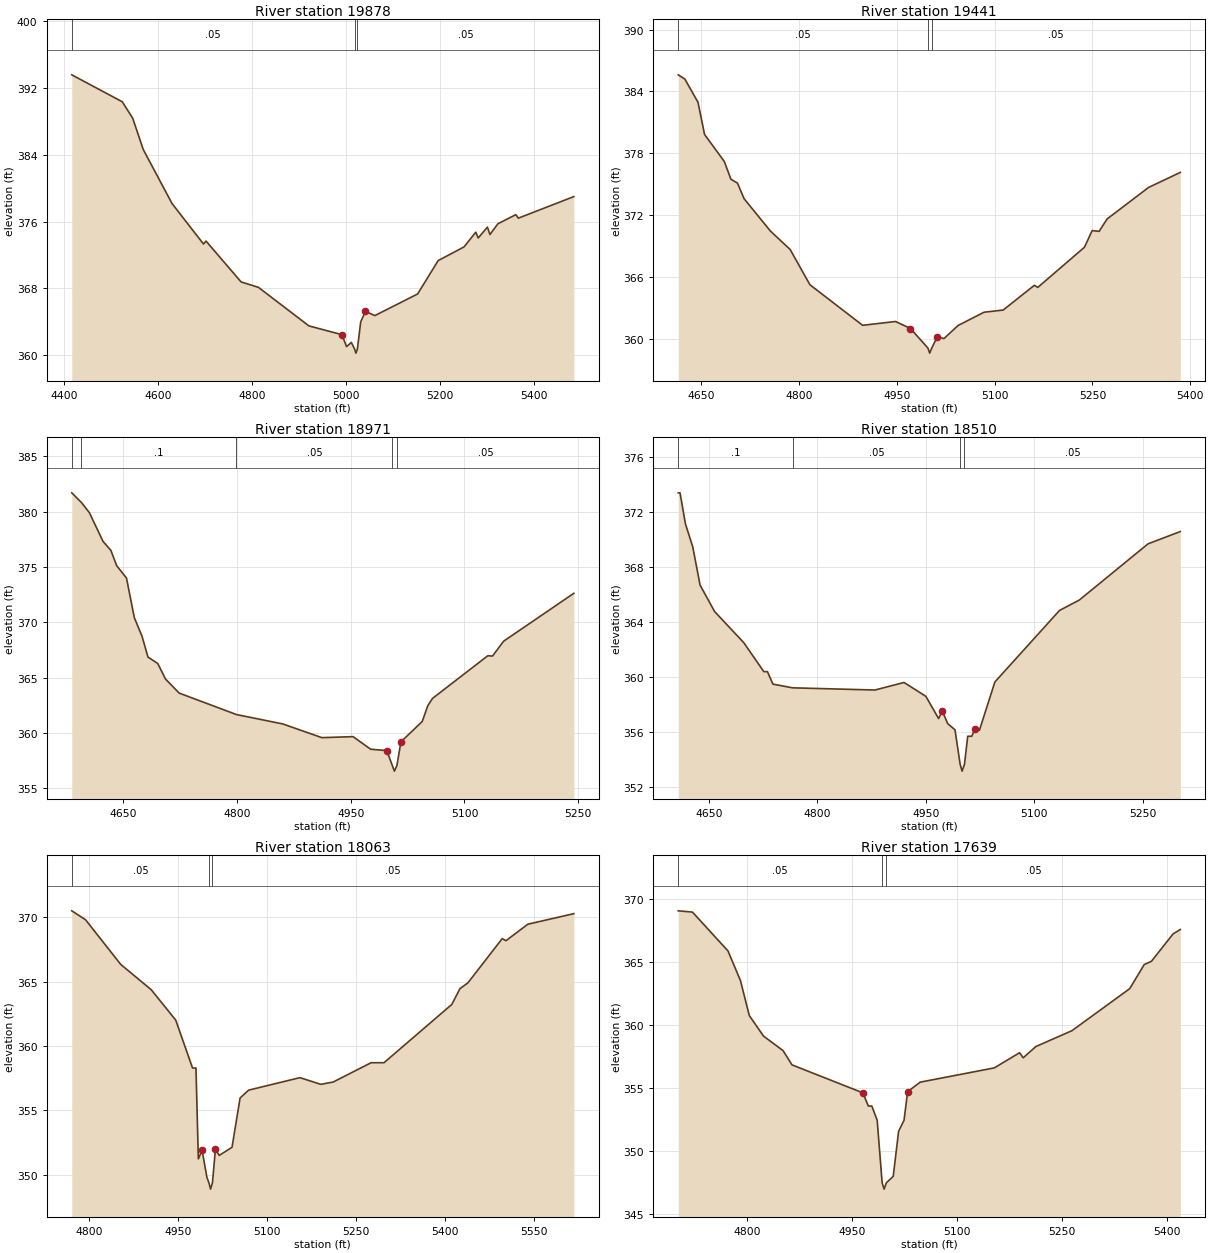
Type RM Length L Ch R = 1 ,19878   ,437,437,437
BEGIN DESCRIPTION:
FLAT BRANCH 38.0
END DESCRIPTION:
XS GIS Cut Line= 4
      3839311.48     10503387.31      3838870.47     10503609.55
       3838641.3     10503626.91      3838318.38     10503748.44
#Sta/Elev= 30
    4416  393.56  4523.4  390.34  4545.7  388.37  4568.1  384.63  4629.4  378.16
  4696.3  373.32  4701.9  373.66  4776.4  368.78  4813.4  368.13  4920.7  363.52
  4990.9  362.47    5001  361.04    5011  361.54    5018  360.76  5020.8  360.26
    5024  360.76    5031  363.99  5041.1  365.26  5061.1  364.75  5152.2  367.34
  5195.9  371.33    5251  372.97  5275.9  374.73  5281.2  374.04  5300.8  375.34
  5306.1  374.45  5323.1  375.74  5361.2  376.83  5366.6  376.41  5484.7  378.99
#Mann= 3 ,-1 , 0
    4416     .05       0    5018     .03       0    5024     .05       0
Bank Sta=4990.9,5041.1
XS Rating Curve= 0 ,0
Exp/Cntr=0.3,0.1

Type RM Length L Ch R = 1 ,19441   ,470,470,470
BEGIN DESCRIPTION:
FLAT BRANCH 37.0
END DESCRIPTION:
XS GIS Cut Line= 3
      3839049.62     10503160.19      3838699.61     10503210.19
      3838314.61     10503369.69
#Sta/Elev= 30
  4614.6  385.61  4624.7   385.2  4644.9  382.95    4655  379.82  4685.3   377.2
  4695.4  375.48  4705.5   375.1  4715.6  373.59    4756  370.45  4786.3  368.66
  4816.6  365.24  4897.5   361.3    4948  361.67  4970.9  360.99  4997.6   359.1
  5000.4   358.6  5003.6   359.1  5012.1  360.19  5022.3  360.01  5043.9  361.28
  5083.8  362.57  5113.1  362.78  5160.9  365.18  5166.3  364.98  5237.9  368.88
  5249.6  370.49  5260.4  370.42  5272.6  371.62  5336.2  374.68  5384.9  376.14
#Mann= 3 ,-1 , 0
  4614.6     .05       0  4997.6     .03       0  5003.6     .05       0
Bank Sta=4970.9,5012.1
XS Rating Curve= 0 ,0
Exp/Cntr=0.3,0.1

Type RM Length L Ch R = 1 ,18971   ,461,461,461
BEGIN DESCRIPTION:
FLAT BRANCH 36.0
END DESCRIPTION:
XS GIS Cut Line= 3
      3838949.63     10502760.18      3838549.61     10502860.19
      3838349.63     10503010.17
#Sta/Elev= 30
    4582  381.71  4594.8  380.83  4605.2  379.92  4623.3  377.31  4633.6   376.5
  4641.3  375.11  4654.2     374  4664.5  370.42  4674.8  368.71  4682.5  366.85
  4695.4  366.27  4705.7  364.86  4723.7  363.59  4799.2  361.65  4860.3   360.8
  4911.9  359.56  4953.1  359.65  4976.3  358.51  4997.5  358.39  5004.9  357.03
  5007.6  356.53  5010.9  357.03  5016.2  359.18  5044.3  361.02  5051.6  362.44
  5057.9  363.11  5130.8  366.97    5137  366.94  5151.6  368.28  5244.3  372.62
#Mann= 5 ,-1 , 0
    4582     .05       0  4594.8      .1       0  4799.2     .05       0
  5004.9     .03       0  5010.9     .05       0
Bank Sta=4997.5,5016.2
XS Rating Curve= 0 ,0
Exp/Cntr=0.3,0.1

Type RM Length L Ch R = 1 ,18510   ,447,447,447
BEGIN DESCRIPTION:
FLAT BRANCH 35.0
END DESCRIPTION:
XS GIS Cut Line= 3
      3838799.56     10502410.19      3838399.61     10502460.19
      3838149.62     10502610.18
#Sta/Elev= 30
  4607.4  373.42  4609.9  373.42  4617.4  371.15  4627.5  369.48  4637.6   366.7
  4657.7  364.77  4698.1   362.5  4725.8  360.39  4730.8  360.39  4738.4  359.48
  4765.7  359.21  4879.5  359.05  4919.8   359.6    4950  358.59  4967.6  356.97
  4972.7  357.52  4980.2   356.6  4990.3  356.15  4997.4  353.64  5000.1  353.14
  5003.4  353.64  5007.9  355.68  5013.4  355.68  5018.2  356.22  5024.1  356.12
  5045.5  359.64  5134.9  364.85  5162.1   365.6  5257.3   369.7    5302   370.6
#Mann= 4 ,-1 , 0
  4607.4      .1       0  4765.7     .05       0  4997.4     .03       0
  5003.4     .05       0
Bank Sta=4972.7,5018.2
XS Rating Curve= 0 ,0
Exp/Cntr=0.3,0.1

Type RM Length L Ch R = 1 ,18063   ,424,424,424
BEGIN DESCRIPTION:
FLAT BRANCH 34.0
END DESCRIPTION:
XS GIS Cut Line= 3
      3838649.65     10501960.18      3838449.61     10502010.19
      3837949.62     10502410.18
#Sta/Elev= 30
  4771.1  370.51  4794.3  369.82  4853.6  366.35  4905.1  364.38  4946.4  362.02
  4974.7   358.3  4980.5   358.3  4984.5  351.24  4990.9   351.9  4998.9  349.81
  5002.3  349.39  5005.1  348.89  5008.3  349.39  5013.3  351.99  5019.7  351.51
  5041.3  352.14  5054.9  355.97  5069.3  356.58  5155.8  357.55    5191  357.03
  5211.8  357.21  5275.8  358.71  5297.5  358.71  5411.9  363.24  5425.5  364.46
  5439.1  364.92  5496.8  368.35  5503.2  368.19    5540  369.47  5617.6  370.29
#Mann= 3 ,-1 , 0
  4771.1     .05       0  5002.3     .03       0  5008.3     .05       0
Bank Sta=4990.9,5013.3
XS Rating Curve= 0 ,0
Exp/Cntr=0.3,0.1

Type RM Length L Ch R = 1 ,17639   ,461,461,461
BEGIN DESCRIPTION:
FLAT BRANCH 33.0
END DESCRIPTION:
XS GIS Cut Line= 3
      3838149.62     10501560.14      3838099.61     10501860.19
      3837999.61     10502260.19
#Sta/Elev= 30
  4701.9  369.05  4722.2  368.95  4772.9  365.87  4790.7  363.52  4803.3  360.75
  4823.6  359.12  4851.5  357.97  4864.2  356.84  4965.5  354.62  4973.1  353.58
  4978.2  353.57  4985.8  352.45  4992.9  347.49  4995.7  346.99  4998.9  347.49
  5008.7     348  5016.4  351.58  5024.1  352.44  5029.3  354.72  5047.3  355.47
    5153   356.6    5189   357.8  5194.2   357.4  5212.2  358.29  5263.8  359.55
  5346.2  362.88  5366.9  364.79  5377.2  365.05  5408.1  367.22  5418.4  367.57
#Mann= 3 ,-1 , 0
  4701.9     .05       0  4992.9     .03       0  4998.9     .05       0
Bank Sta=4965.5,5029.3
XS Rating Curve= 0 ,0
Exp/Cntr=0.3,0.1

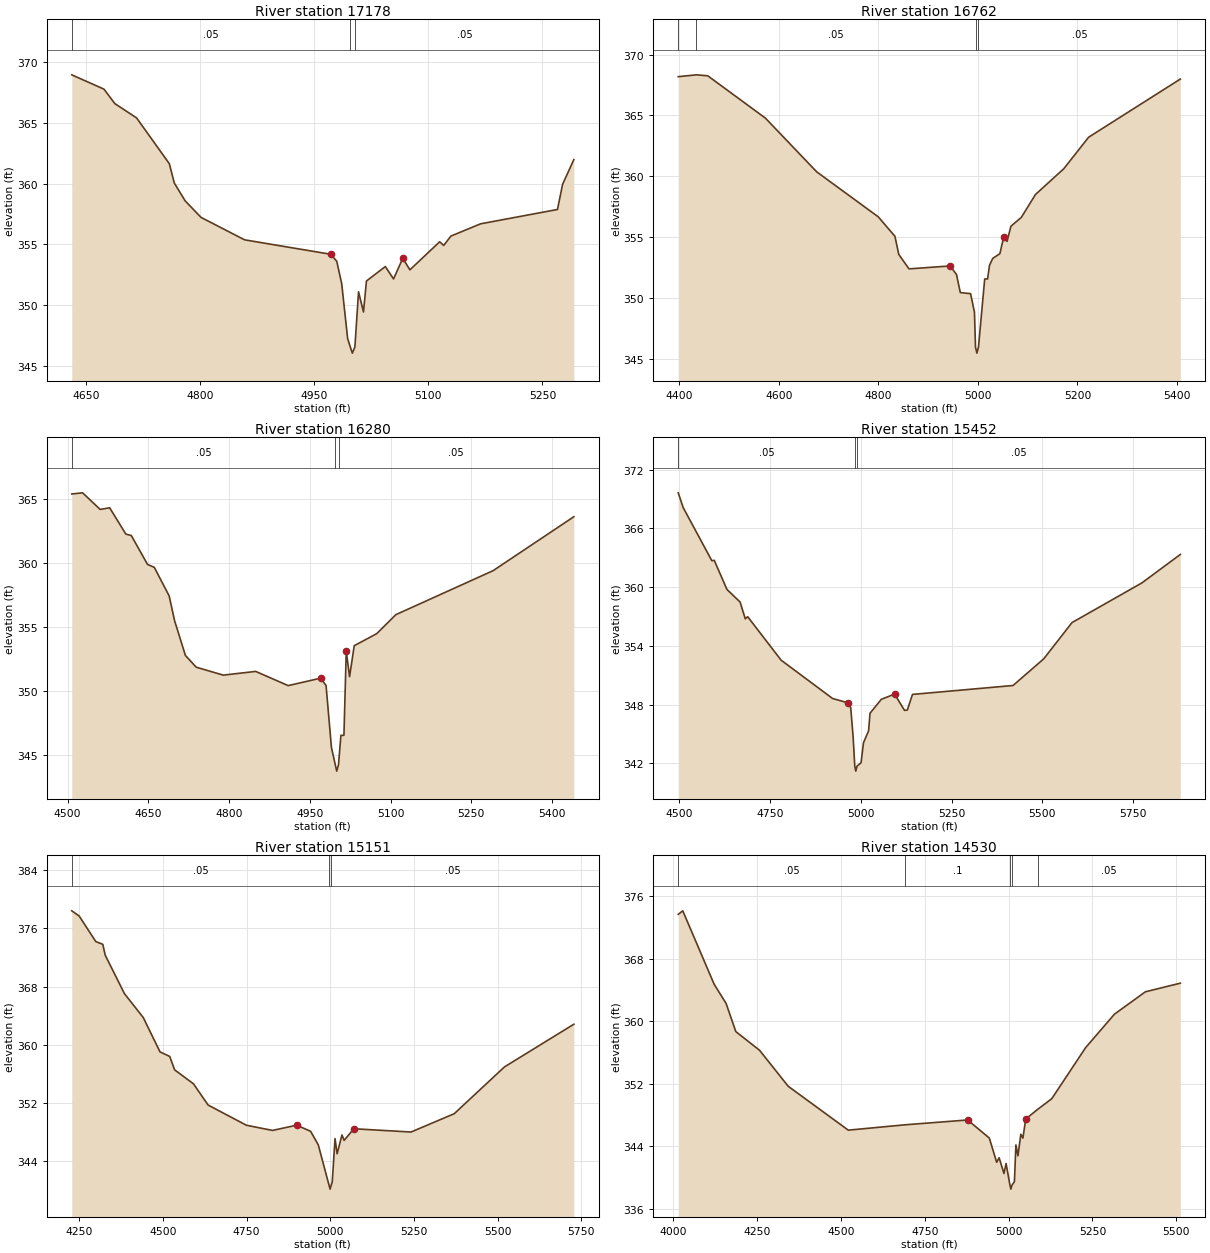
Type RM Length L Ch R = 1 ,17178   ,416,416,416
BEGIN DESCRIPTION:
FLAT BRANCH 32.0
END DESCRIPTION:
XS GIS Cut Line= 3
      3838049.58     10501460.22      3837749.61     10501710.19
      3837649.62     10501960.16
#Sta/Elev= 30
  4631.5  368.97  4673.8  367.79  4688.1   366.6  4716.7  365.42  4759.7  361.65
  4766.2  360.06  4780.5  358.59  4801.3  357.23  4858.6  355.38  4971.9  354.19
  4979.7  353.61  4986.2  351.76    4994  347.24  4997.5  346.55  5000.2  346.05
  5003.5  346.55  5008.3   351.1  5014.8  349.44  5018.7  351.99  5043.5  353.18
  5054.3  352.16  5066.4  353.86  5075.8  352.91  5114.9  355.22  5120.2  354.92
  5129.7  355.69  5168.7   356.7  5269.7  357.88  5276.4  359.95  5291.2  361.99
#Mann= 3 ,-1 , 0
  4631.5     .05       0  4997.5     .03       0  5003.5     .05       0
Bank Sta=4971.9,5066.4
XS Rating Curve= 0 ,0
Exp/Cntr=0.3,0.1

Type RM Length L Ch R = 1 ,16762   ,482,482,482
BEGIN DESCRIPTION:
FLAT BRANCH 31.0
END DESCRIPTION:
XS GIS Cut Line= 3
       3837999.6     10501360.19      3837399.61     10501510.19
      3837099.59     10501760.21
#Sta/Elev= 30
  4397.7  368.19  4434.3  368.34    4457  368.26  4572.9  364.78    4676  360.36
  4799.7  356.66  4833.2  355.06  4840.9  353.57  4861.5  352.38    4944  352.62
  4956.9  351.92  4964.6  350.43  4985.2  350.34    4993  348.82  4995.1  345.95
  4997.9  345.45  5001.1  345.95  5013.6  351.55  5019.4  351.55  5023.3  352.68
  5029.8  353.24  5044.1  353.63    5052  355.04  5058.5  354.64  5066.3  355.89
  5087.1  356.61  5115.7   358.5  5172.4  360.61  5222.5  363.21  5406.7  367.99
#Mann= 4 ,-1 , 0
  4397.7     .16       0  4434.3     .05       0  4995.1     .03       0
  5001.1     .05       0
Bank Sta=4944,5052
XS Rating Curve= 0 ,0
Exp/Cntr=0.3,0.1

Type RM Length L Ch R = 1 ,16280   ,828,828,828
BEGIN DESCRIPTION:
FLAT BRANCH 30.0
END DESCRIPTION:
XS GIS Cut Line= 3
      3837799.66     10501110.19      3837299.61     10501060.19
      3836949.58     10501310.21
#Sta/Elev= 30
  4507.7  365.43  4527.8  365.52  4560.5  364.22  4578.1  364.35  4608.2  362.29
  4618.3  362.18  4648.4  359.92    4661  359.69  4688.6  357.46  4698.7  355.52
  4718.8   352.8  4738.9  351.88  4789.1  351.26  4849.4  351.55  4909.7  350.44
    4970  351.02  4980.1  350.45  4990.1  345.59  4997.2  344.25  4999.9  343.75
  5003.2  344.25  5007.7  346.55  5013.3  346.55  5017.6  353.12  5023.8  351.14
  5032.4  353.56  5074.1   354.5  5109.8  355.99  5290.4  359.43  5440.4  363.65
#Mann= 3 ,-1 , 0
  4507.7     .05       0  4997.2     .03       0  5003.2     .05       0
Bank Sta=4970,5017.6
XS Rating Curve= 0 ,0
Exp/Cntr=0.3,0.1

Type RM Length L Ch R = 1 ,15452   ,301,301,301
BEGIN DESCRIPTION:
FLAT BRANCH 29.0
END DESCRIPTION:
XS GIS Cut Line= 3
      3837799.64     10500110.16      3837399.61     10500460.19
      3836749.63     10501010.17
#Sta/Elev= 30
  4497.1  369.64  4510.9  368.12  4589.7   362.7  4596.3  362.74  4631.4  359.76
  4667.5  358.48  4681.8  356.76  4688.4  356.98  4780.5  352.54  4922.4  348.62
  4964.6  348.18  4972.2  347.69  4978.8  344.73  4983.4   341.7  4986.2   341.2
  4989.4   341.7  5000.7  342.06  5007.3  344.09  5021.5  345.32  5025.3  347.11
  5056.6  348.54    5093  349.07  5120.4  347.41  5128.1  347.44  5142.4  349.04
  5419.3  349.95  5503.8  352.67  5581.8  356.38  5774.1  360.43  5880.1  363.34
#Mann= 3 ,-1 , 0
  4497.1     .05       0  4983.4     .03       0  4989.4     .05       0
Bank Sta=4964.6,5093
XS Rating Curve= 0 ,0
Exp/Cntr=0.3,0.1

Type RM Length L Ch R = 1 ,15151   ,621,621,621
BEGIN DESCRIPTION:
FLAT BRANCH 28.0
END DESCRIPTION:
XS GIS Cut Line= 3
      3837599.61     10499760.18      3837080.15     10500453.06
      3836699.61     10500960.18
#Sta/Elev= 30
  4227.9  378.42  4249.8  377.72  4299.8  374.19  4320.6  373.82  4327.9  372.32
  4385.2  367.04  4441.5  363.75  4491.5  359.03  4520.6   358.4  4535.2  356.56
  4591.5  354.64  4635.2  351.72  4749.8  348.94  4827.8  348.23  4899.8  348.95
  4941.5  348.11  4964.4  346.24  4996.8  340.66  4999.6  340.16  5002.8  340.66
  5006.1  341.14  5014.4  347.11  5020.7  345.02  5035.2  347.61  5041.5  346.86
  5070.7  348.46  5241.5  348.01  5370.6  350.53  5520.6  356.96  5727.9  362.83
#Mann= 3 ,-1 , 0
  4227.9     .05       0  4996.8     .03       0  5002.8     .05       0
Bank Sta=4899.8,5070.7
XS Rating Curve= 0 ,0
Exp/Cntr=0.3,0.1

Type RM Length L Ch R = 1 ,14530   ,700,700,700
BEGIN DESCRIPTION:
FLAT BRANCH 27.0
END DESCRIPTION:
XS GIS Cut Line= 3
      3837449.59     10499710.21      3836649.61     10500310.19
      3836243.15     10500597.81
#Sta/Elev= 30
  4014.4  373.65  4027.9   374.1  4121.7   364.7  4157.1  362.27  4186.2  358.66
  4257.1  356.27  4342.5  351.67  4521.7  346.06  4690.3  346.74  4877.9  347.36
  4942.5  345.05  4964.4  341.95  4971.7  342.53  4986.2  340.52  4992.5   341.8
  5004.1  339.02  5006.8  338.52  5010.1  339.02  5017.4  339.48  5021.8  344.17
  5027.9  342.78  5036.5  345.54  5042.7  345.04  5051.1  347.48  5086.5  348.71
  5128.8  350.08  5229.8  356.61  5315.9  360.89  5408.2  363.75  5512.3  364.85
#Mann= 5 ,-1 , 0
  4014.4     .05       0  4690.3      .1       0  5004.1     .07       0
  5010.1      .1       0  5086.5     .05       0
Bank Sta=4877.9,5051.1
XS Rating Curve= 0 ,0
Exp/Cntr=0.3,0.1

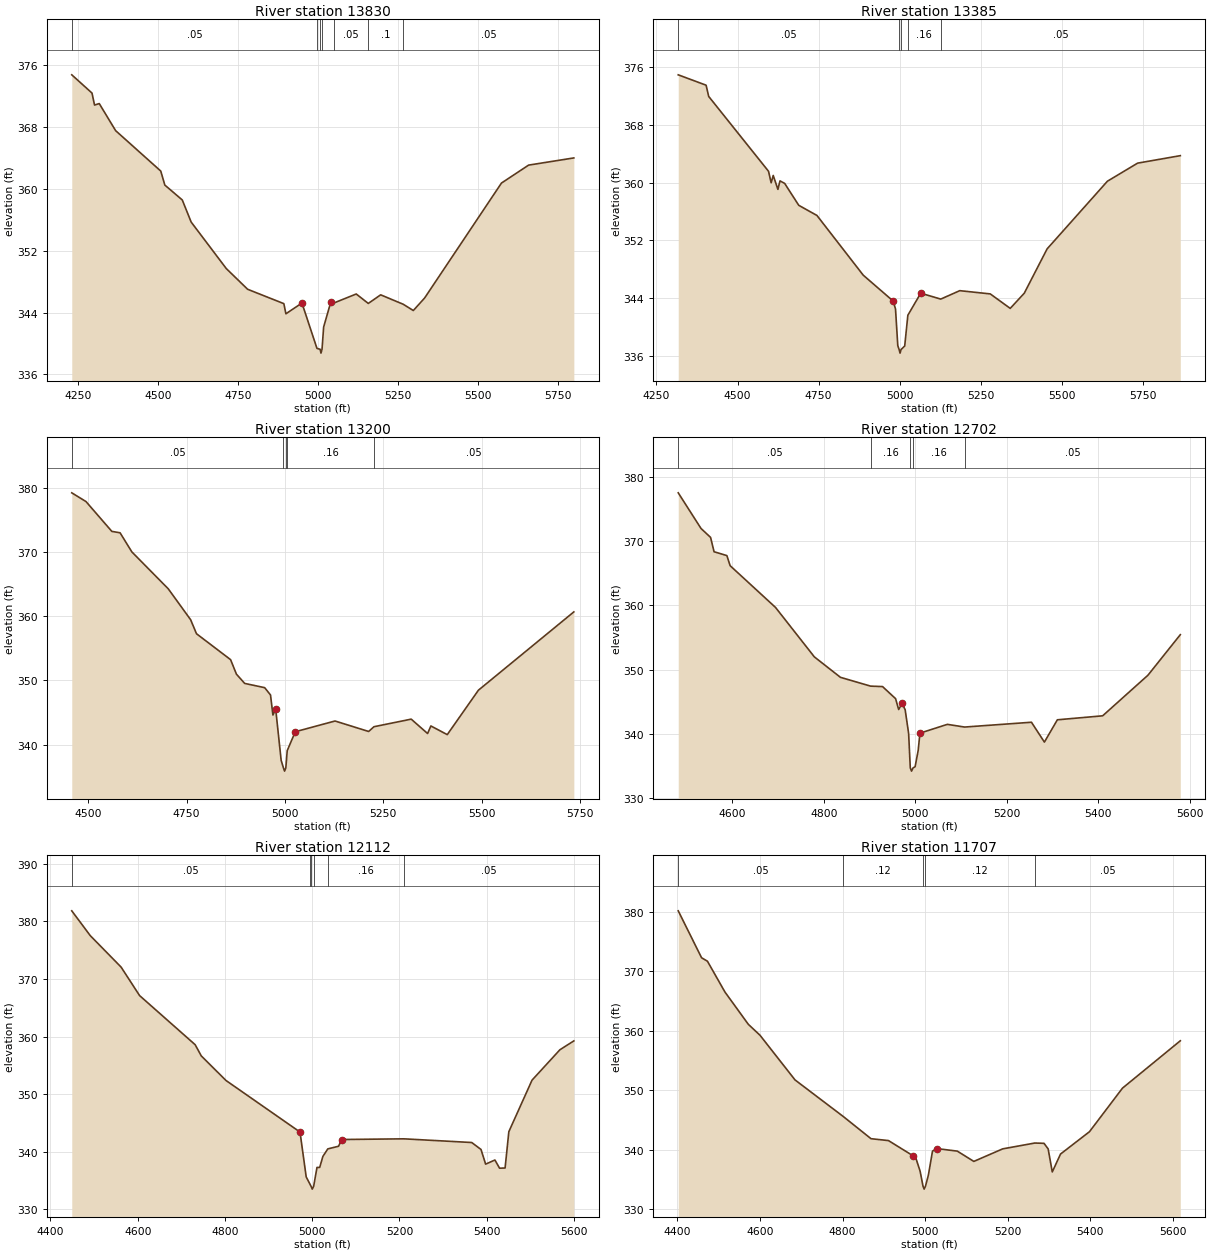
Type RM Length L Ch R = 1 ,13830   ,445,445,445
BEGIN DESCRIPTION:
FLAT BRANCH 26.0
END DESCRIPTION:
XS GIS Cut Line= 3
      3837465.56     10499520.78      3836533.28     10500015.56
      3836174.31     10500384.93
#Sta/Elev= 30
  4229.5  374.75  4292.8  372.39  4300.7  370.84  4315.5  371.03  4366.7  367.53
  4507.9   362.3  4520.6  360.49  4575.2  358.56  4602.9  355.71  4712.8  349.69
  4779.6  347.01  4892.9  345.15  4899.3  343.84  4949.5  345.23  4996.5  339.36
  5006.3  339.25    5009  338.75  5012.3  339.25  5017.4  342.13    5040  345.39
  5048.5  345.22  5119.3   346.4    5157  345.18  5195.8  346.29  5266.4  345.07
  5297.9  344.26  5333.2  345.88  5573.6  360.75  5658.5  363.07    5800     364
#Mann= 7 ,-1 , 0
  4229.5     .05       0  4996.5     .16       0  5006.3     .07       0
  5012.3     .16       0  5048.5     .05       0    5157      .1       0
  5266.4     .05       0
Bank Sta=4949.5,5040
XS Rating Curve= 0 ,0
Exp/Cntr=0.3,0.1

Type RM Length L Ch R = 1 ,13385   ,185,185,185
BEGIN DESCRIPTION:
FLAT BRANCH 25.0
END DESCRIPTION:
XS GIS Cut Line= 4
      3837085.35     10498994.74      3836720.78     10499458.27
      3836460.36     10499723.89      3836095.76     10500182.25
#Sta/Elev= 30
  4317.3  374.98  4403.2  373.54  4411.2  371.98  4595.6  361.59  4603.7  359.99
  4610.1  361.01  4624.5  359.08  4630.9  360.26  4645.3  359.91  4688.7  356.87
  4744.8  355.46  4887.5  347.17  4979.9  343.57    4987  342.46    4994  337.38
  4998.1  336.85  5000.9  336.35  5004.1  336.85  5015.3  337.34    5025  341.61
  5064.7  344.67  5126.4  343.85    5185  345.02    5279  344.57  5340.5  342.56
  5383.8  344.67  5454.2  350.82    5640  360.21    5733  362.72  5864.7  363.76
#Mann= 5 ,-1 , 0
  4317.3     .05       0  4998.1     .03       0  5004.1     .05       0
    5025     .16       0  5126.4     .05       0
Bank Sta=4979.9,5064.7
XS Rating Curve= 0 ,0
Exp/Cntr=0.3,0.1

Type RM Length L Ch R = 1 ,13200   ,498,498,498
BEGIN DESCRIPTION:
FLAT BRANCH 24.0
END DESCRIPTION:
XS GIS Cut Line= 3
      3836892.65     10498921.81      3836533.28     10499447.85
      3836149.58     10499960.23
#Sta/Elev= 30
  4457.7   379.2  4493.9  377.84  4559.6   373.2  4580.6  372.98  4610.5  370.01
  4703.2  364.26  4760.1  359.45    4775  357.27  4861.7  353.24  4876.6  350.98
  4897.6  349.54  4948.4  348.88  4963.3  347.74  4969.4  344.62  4976.5  345.51
  4990.4  337.55  4996.2  336.39    4999  335.89  5002.2  336.39  5005.8  339.08
  5026.3  342.02  5127.4  343.69  5212.9  342.06  5226.4   342.8  5321.2  343.98
  5362.9  341.74  5371.2  342.92  5412.9  341.57  5492.1  348.48  5734.9  360.67
#Mann= 5 ,-1 , 0
  4457.7     .05       0  4996.2     .03       0  5002.2     .05       0
  5005.8     .16       0  5226.4     .05       0
Bank Sta=4976.5,5026.3
XS Rating Curve= 0 ,0
Exp/Cntr=0.3,0.1

Type RM Length L Ch R = 1 ,12702   ,590,590,590
BEGIN DESCRIPTION:
FLAT BRANCH 23.0
END DESCRIPTION:
XS GIS Cut Line= 3
      3836649.59     10498910.21      3836299.61     10499310.19
      3835899.59     10499710.21
#Sta/Elev= 30
    4482  377.52  4531.8  371.97  4552.7  370.58  4560.3  368.35  4588.3  367.75
  4595.4  366.18  4694.6  359.68  4779.5  351.98  4836.5   348.8  4902.4  347.43
  4928.5  347.36    4957  345.48  4963.7  343.79  4971.2  344.73  4977.9  343.76
  4985.5  340.06  4989.1   334.7  4991.9   334.2  4995.1   334.7  4999.7  334.89
  5006.4  337.44  5010.2  340.11  5070.1  341.48  5107.8  341.06  5253.9  341.81
  5282.2  338.72  5310.5  342.19  5409.5  342.81  5508.5  349.13  5579.2  355.44
#Mann= 5 ,-1 , 0
    4482     .05       0  4902.4     .16       0  4989.1     .07       0
  4995.1     .16       0  5107.8     .05       0
Bank Sta=4971.2,5010.2
XS Rating Curve= 0 ,0
Exp/Cntr=0.3,0.1

Type RM Length L Ch R = 1 ,12112   ,405,405,405
BEGIN DESCRIPTION:
FLAT BRANCH 22.0
END DESCRIPTION:
XS GIS Cut Line= 3
      3836399.58     10498760.22      3835999.61     10499160.19
       3835799.6     10499710.21
#Sta/Elev= 30
  4448.8  381.85  4491.2  377.54  4561.9  372.07  4604.3  367.12  4731.6  358.59
  4745.7  356.64  4802.3  352.37    4972  343.41  4986.2  335.61  4995.1  334.31
  4997.3  333.99  5000.1  333.49  5003.3  333.99  5010.9  337.26  5017.1  337.26
  5024.4  339.17  5035.7  340.48  5060.3  340.94  5067.6  342.11  5209.9  342.23
  5365.6  341.59  5386.9  340.38  5397.5  337.83  5418.8  338.55  5429.4  337.13
  5442.1  337.16  5450.7  343.47  5503.9  352.43  5567.8  357.71  5599.7  359.25
#Mann= 6 ,-1 , 0
  4448.8     .05       0  4995.1     .12       0  4997.3     .07       0
  5003.3     .12       0  5035.7     .16       0  5209.9     .05       0
Bank Sta=4972,5067.6
XS Rating Curve= 0 ,0
Exp/Cntr=0.3,0.1

Type RM Length L Ch R = 1 ,11707   ,493,493,493
BEGIN DESCRIPTION:
FLAT BRANCH 21.0
END DESCRIPTION:
XS GIS Cut Line= 3
      3836049.59     10498560.21      3835649.61     10498960.19
      3835649.61     10499610.24
#Sta/Elev= 30
  4402.2  380.14  4458.7  372.25  4472.9  371.67  4515.3  366.49  4571.9  361.06
  4600.2  359.22    4685  351.71  4801.8  345.56  4868.9  341.83  4911.3  341.51
  4970.4  338.97  4977.9   338.5  4987.9  336.36  4994.9  333.85  4997.6  333.35
  5000.9  333.85  5007.9  335.71  5017.9  339.74  5027.9  340.17  5077.9  339.74
  5117.9  338.01  5187.9  340.12  5265.7   341.1  5287.9  341.05  5297.9  340.11
  5307.9  336.24  5327.9  339.25  5397.9     343  5477.9  350.33  5617.9  358.29
#Mann= 5 ,-1 , 0
  4402.2     .05       0  4801.8     .12       0  4994.9     .07       0
  5000.9     .12       0  5265.7     .05       0
Bank Sta=4970.4,5027.9
XS Rating Curve= 0 ,0
Exp/Cntr=0.3,0.1

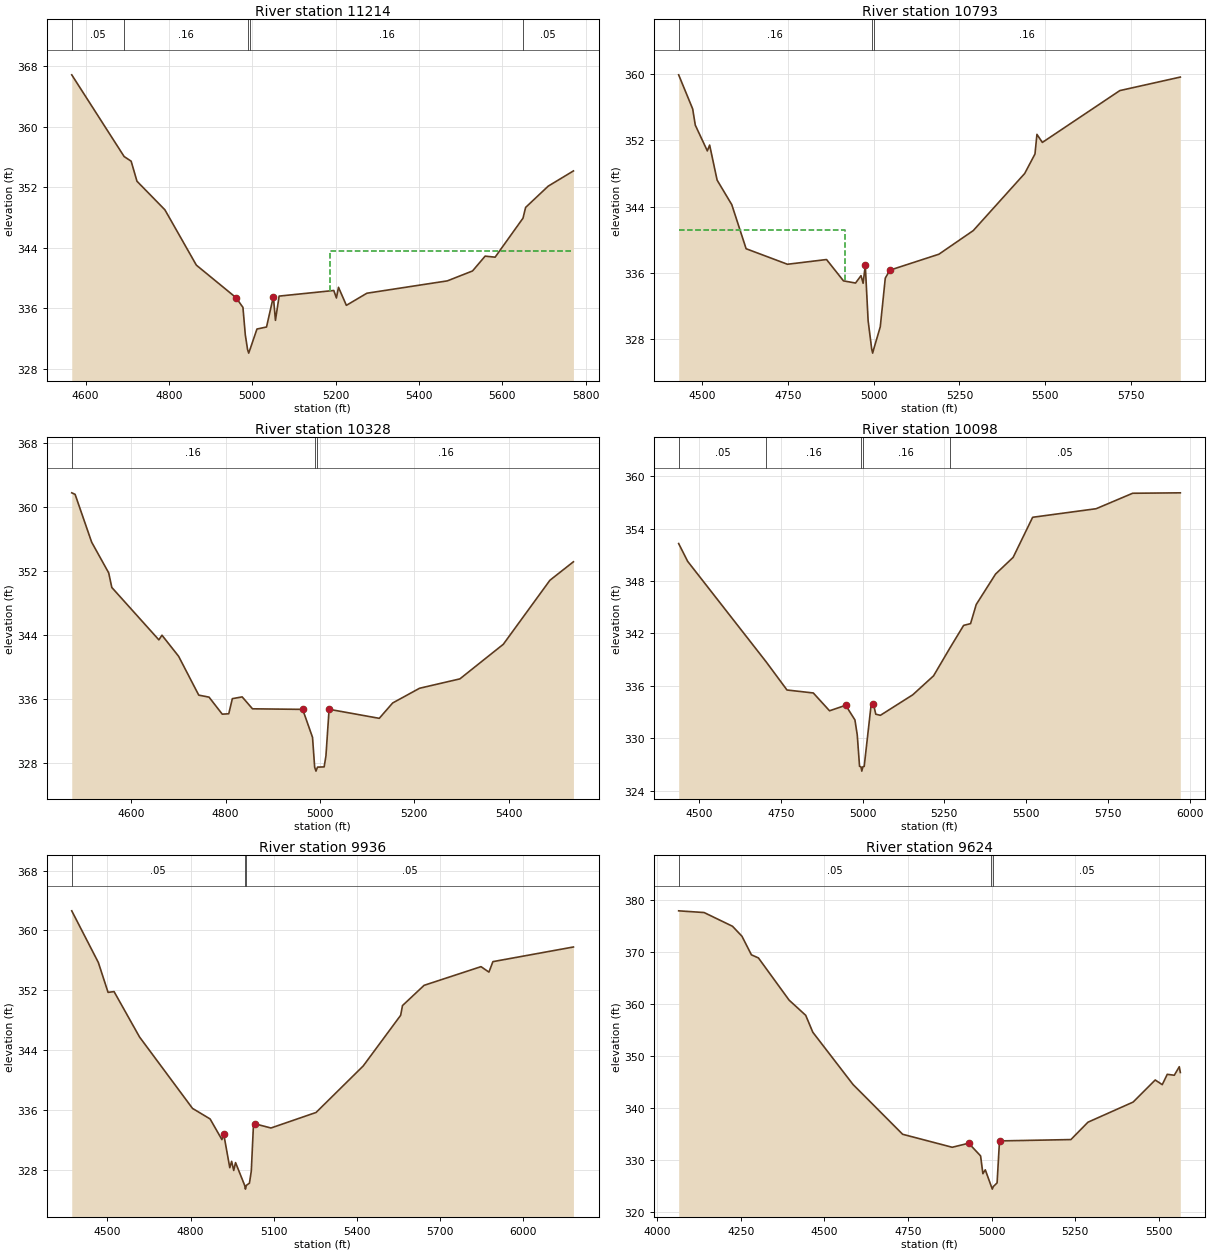
Type RM Length L Ch R = 1 ,11214   ,421,421,421
BEGIN DESCRIPTION:
FLAT BRANCH 20.0
END DESCRIPTION:
XS GIS Cut Line= 3
       3835499.6     10498310.22      3835299.61     10498710.19
      3835399.61     10499460.17
#Sta/Elev= 30
    4567  366.83  4692.7  356.04  4709.5  355.43  4723.5  352.78  4790.6     349
    4866   341.7  4961.1  337.41  4977.8  336.12  4983.4  332.53  4988.8  330.58
  4991.6  330.08  4994.8  330.58  5011.4  333.26  5034.4  333.53  5050.8  337.54
  5055.8  334.41  5064.6  337.61  5195.8  338.35  5202.1  337.36  5207.1  338.77
    5226  336.39  5275.2  337.99  5468.2  339.62  5528.7  340.93    5559  342.89
  5582.9  342.75  5649.8   347.9  5656.1  349.32  5710.3  352.13  5770.8  354.14
#Mann= 5 ,-1 , 0
    4567     .05       0  4692.7     .16       0  4988.8     .07       0
  4994.8     .16       0  5649.8     .05       0
#XS Ineff= 2 , 0
                          5187.5          343.57
Permanent Ineff=
       F       F
Bank Sta=4961.1,5050.8
XS Rating Curve= 0 ,0
Exp/Cntr=0.3,0.1

Type RM Length L Ch R = 1 ,10793   ,465,465,465
BEGIN DESCRIPTION:
FLAT BRANCH 19.0
END DESCRIPTION:
XS GIS Cut Line= 4
      3835290.24     10498302.89      3834940.23      10498702.9
      3834640.23      10499102.9      3834425.47      10499476.1
#Sta/Elev= 30
  4431.8  359.86  4472.7  355.75  4480.3   353.8  4515.4   350.7  4522.1   351.4
  4543.9  347.18  4586.6  344.23  4628.4  338.92  4748.9  337.05  4862.8  337.62
  4912.2  335.05  4947.3  334.79  4963.3  335.68  4969.4  334.76  4975.7  336.92
    4984  330.25  4994.4  326.85  4997.2  326.35  5000.4  326.85  5019.4  329.52
    5034  335.38  5047.4  336.34  5190.3  338.26  5290.3   341.1  5440.3  347.98
  5470.3  350.33    5476  352.69  5491.8  351.72  5717.5  357.96  5893.9  359.59
#Mann= 3 ,-1 , 0
  4431.8     .16       0  4994.4     .07       0  5000.4     .16       0
#XS Ineff= 2 , 0
         4916.36  341.17
Permanent Ineff=
       F       F
Bank Sta=4975.7,5047.4
XS Rating Curve= 0 ,0
Exp/Cntr=0.3,0.1

Type RM Length L Ch R = 1 ,10328   ,230,230,230
BEGIN DESCRIPTION:
FLAT BRANCH 18.0
END DESCRIPTION:
XS GIS Cut Line= 3
      3834899.61     10498160.19      3834549.61     10498560.19
      3834149.62     10498910.18
#Sta/Elev= 30
  4474.1  361.76  4481.2  361.57  4516.3  355.59  4552.4  351.75    4559  349.93
  4658.7  343.38  4665.3  343.96  4700.5  341.33  4743.2  336.47    4765  336.22
    4793  334.09  4806.8  334.14  4814.4  336.03  4835.2  336.25  4857.1  334.76
  4963.4  334.69  4984.3  331.19  4988.8  327.47  4991.6  326.97  4994.8  327.47
  5008.9   327.5  5012.7  328.87  5019.4   334.7  5125.7  333.57  5154.1  335.49
  5211.1  337.33  5296.5   338.5  5388.6  342.83  5487.3  350.83  5537.1  353.14
#Mann= 3 ,-1 , 0
  4474.1     .16       0  4988.8     .07       0  4994.8     .16       0
Bank Sta=4963.4,5019.4
XS Rating Curve= 0 ,0
Exp/Cntr=0.3,0.1

Type RM Length L Ch R = 1 ,10098   ,162,162,162
BEGIN DESCRIPTION:
Mapping XS b3e4417b
END DESCRIPTION:
XS GIS Cut Line= 4
      3834798.86       10498151.      3834460.36     10498364.52
      3834106.19     10498723.89      3833996.81     10499343.73
#Sta/Elev= 30
  4437.6  352.29  4465.2  350.25  4705.3  338.74  4768.9  335.52  4849.4  335.18
    4899  333.14  4948.4  333.77  4976.7  332.09  4983.8  330.37  4990.8  326.78
    4995  326.73  4997.7  326.23    5001  326.73    5005  326.77  5026.2  333.82
  5033.3  333.92  5040.4  332.75  5054.5  332.62  5153.5  334.97  5217.1  337.14
  5266.7   340.3  5309.1  342.92  5330.3  343.12  5347.6  345.31  5406.8   348.8
  5460.5  350.71  5520.2   355.3  5714.3  356.28    5826  358.05  5971.8   358.1
#Mann= 5 ,-1 , 0
  4437.6     .05       0  4705.3     .16       0    4995     .07       0
    5001     .16       0  5266.7     .05       0
Bank Sta=4948.4,5033.3
XS Rating Curve= 0 ,0
Exp/Cntr=0.3,0.1

Type RM Length L Ch R = 1 ,9936    ,312,312,312
BEGIN DESCRIPTION:
FLAT BRANCH 17.0
END DESCRIPTION:
XS GIS Cut Line= 3
      3834746.85     10497921.78      3834043.69     10498557.23
      3833383.44      10499113.5
#Sta/Elev= 30
  4371.1  362.62  4467.1  355.71  4502.2  351.71  4523.9  351.81  4615.8  345.74
  4807.1  336.18  4870.6  334.77  4913.2  332.01    4920  332.71  4941.6  328.25
  4948.3   329.1  4955.8  327.88  4962.5  328.93  4995.4  325.88  4998.1  325.38
  5001.4  325.88  5012.6  326.18  5019.3   327.8  5026.8  333.74  5033.5  334.11
  5090.3  333.56  5253.2  335.64  5423.3  341.86  5558.5  348.64  5565.1  349.94
  5643.1  352.65  5848.6  355.15  5877.2  354.42  5891.5  355.82  6182.2  357.78
#Mann= 3 ,-1 , 0
  4371.1     .05       0  4995.4     .03       0  5001.4     .05       0
Bank Sta=4920,5033.5
XS Rating Curve= 0 ,0
Exp/Cntr=0.3,0.1

Type RM Length L Ch R = 1 ,9624    ,269,269,269
BEGIN DESCRIPTION:
Mapping XS 8888d4f0
END DESCRIPTION:
XS GIS Cut Line= 3
      3834757.44     10497620.36      3833947.25     10498391.07
      3833734.53     10498710.15
#Sta/Elev= 30
  4063.5  378.01  4139.7  377.68  4224.7  375.04    4253  373.12  4281.3  369.55
  4302.3  368.95  4394.2  360.83  4443.9  357.91    4465  354.67  4585.1  344.64
  4733.9  335.04  4882.4  332.54  4931.7  333.32  4967.3  330.88  4974.2  327.46
  4981.4   328.2  4999.5  324.99  5002.3  324.49  5005.5  324.99  5016.7  325.69
  5023.9  333.76  5237.6  334.02  5288.7  337.36  5423.9  341.23    5490  345.48
  5511.1  344.58  5526.1  346.57  5547.1  346.39  5562.1  348.03  5565.2  346.92
#Mann= 3 ,-1 , 0
  4063.5     .05       0  4999.5     .03       0  5005.5     .05       0
Bank Sta=4931.7,5023.9
XS Rating Curve= 0 ,0
Exp/Cntr=0.3,0.1