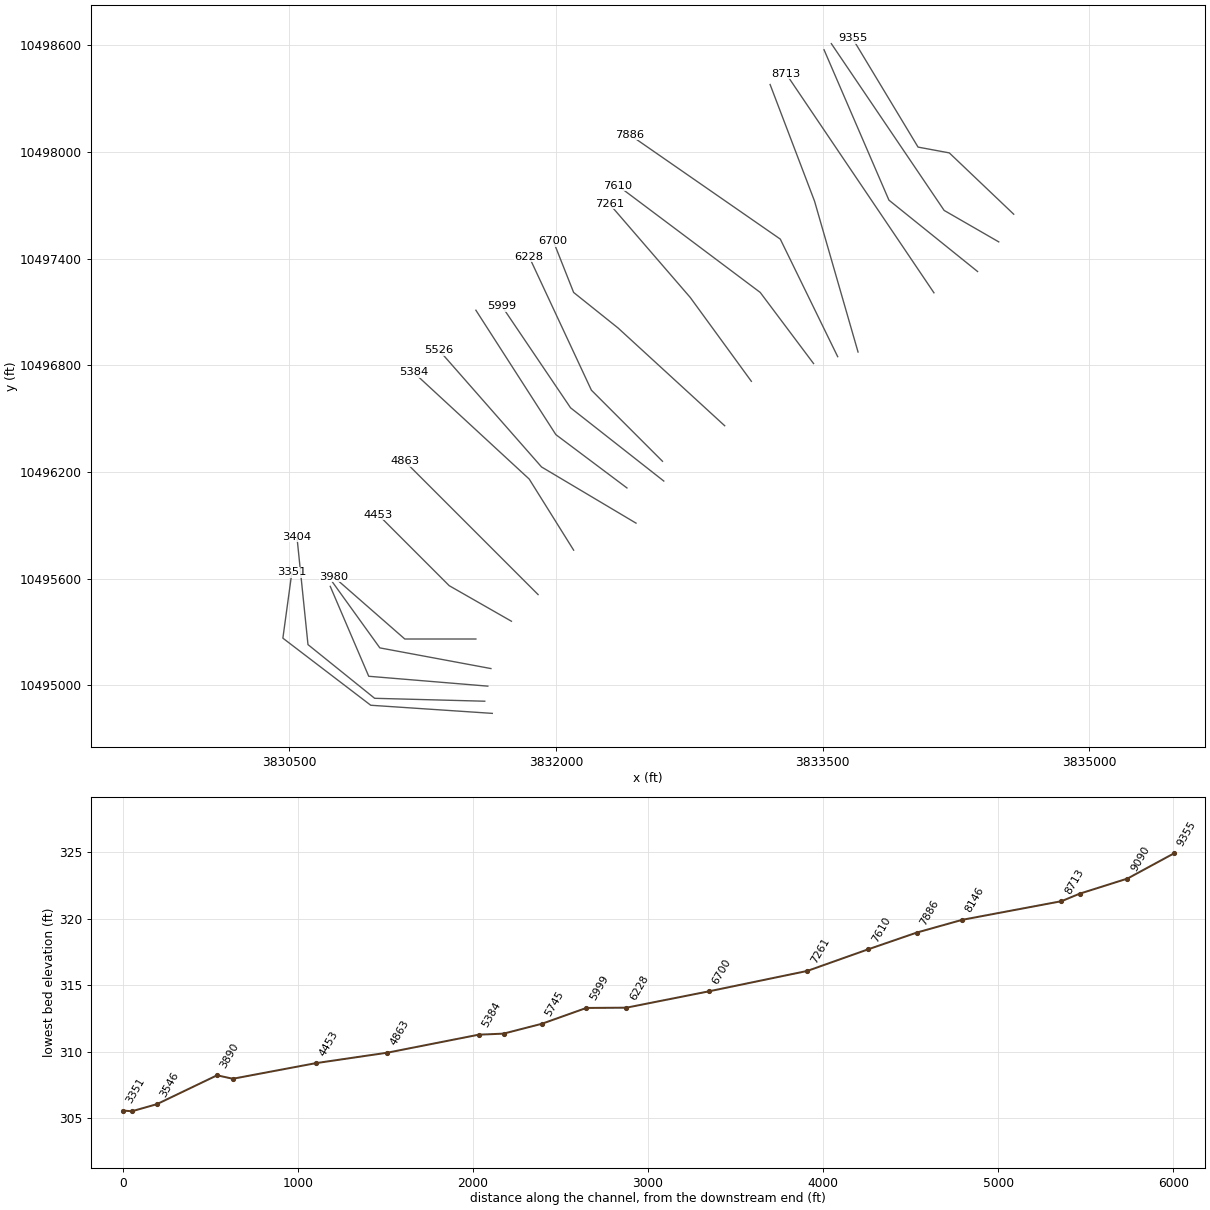
HEC-RAS study FLAT BRANCH.prj: FLAT BRANCH Base Level Engineering

--- FLAT BRANCH.g01 (geometry) --- (continued)

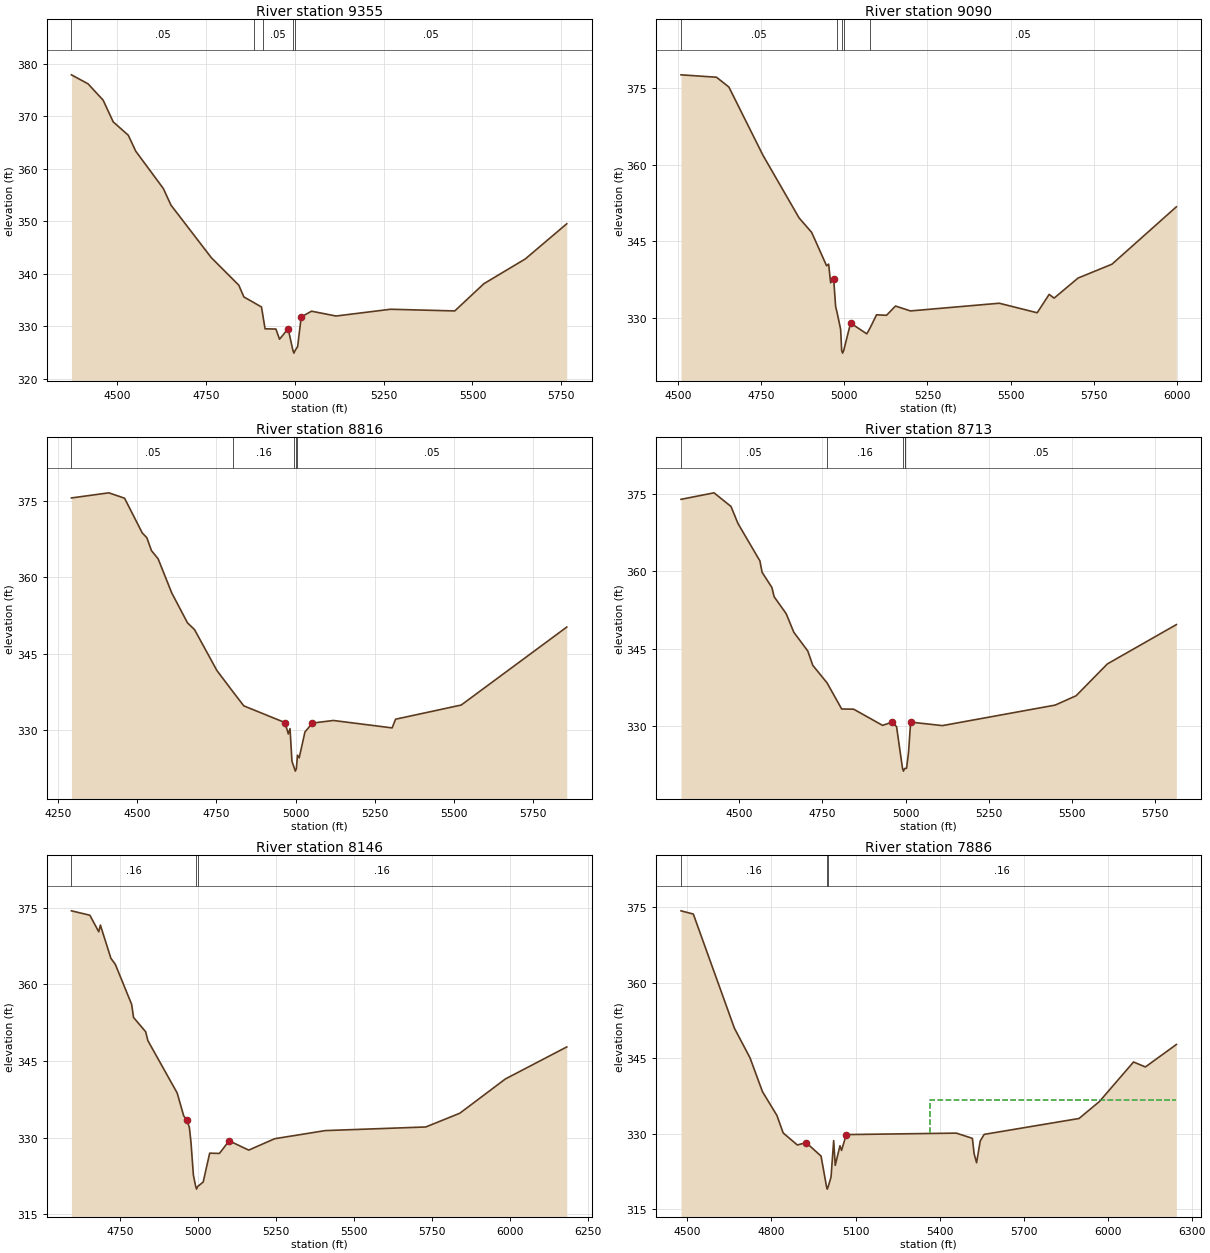
Type RM Length L Ch R = 1 ,9355    ,265,265,265
BEGIN DESCRIPTION:
Mapping XS 337a5f04
END DESCRIPTION:
XS GIS Cut Line= 4
       3834575.8     10497650.42      3834213.38     10497995.48
       3834037.6     10498028.04      3833668.66     10498640.04
#Sta/Elev= 30
  4371.6  377.93  4418.3  376.22  4460.8  373.11  4489.1  368.97  4531.6  366.42
  4552.6  363.38  4630.3  356.26  4651.7   353.1    4765  343.11  4842.6  337.84
  4856.8  335.61  4884.1  334.56  4906.4  333.69  4911.4  331.63  4916.5  329.53
    4947  329.49  4957.2  327.55  4981.4  329.55  4994.9   325.4  4997.6   324.9
  5000.9   325.4  5008.1  326.14  5018.2   331.8  5047.2  332.89  5116.1  331.97
  5269.5  333.26  5450.3  332.94    5532  338.12  5648.8  342.85  5765.4  349.55
#Mann= 5 ,-1 , 0
  4371.6     .05       0  4884.1     .16       0  4911.4     .05       0
  4994.9     .03       0  5000.9     .05       0
Bank Sta=4981.4,5018.2
XS Rating Curve= 0 ,0
Exp/Cntr=0.3,0.1

Type RM Length L Ch R = 1 ,9090    ,274,274,274
BEGIN DESCRIPTION:
FLAT BRANCH 16.0
END DESCRIPTION:
XS GIS Cut Line= 3
       3834491.6     10497494.73      3834184.32     10497671.81
      3833549.63     10498610.16
#Sta/Elev= 30
    4510  377.68  4616.5  377.21  4653.8  375.28  4755.8  361.91  4864.5  349.58
  4902.4  346.72  4947.2  340.17  4953.3  340.49  4959.3  336.83  4968.3  337.65
  4974.3  332.18  4978.6     331  4989.3  327.71  4992.5  323.51  4995.2  323.01
  4998.5  323.51  5019.2  328.91  5067.9   326.8    5078  327.98  5097.1  330.54
  5127.1  330.44  5154.1  332.26    5199   331.3  5465.6  332.81  5579.6  330.94
  5615.5  334.55  5630.5  333.82  5702.4  337.76  5804.2  340.48  5997.5  351.75
#Mann= 5 ,-1 , 0
    4510     .05       0  4978.6     .16       0  4992.5     .07       0
  4998.5     .16       0    5078     .05       0
Bank Sta=4968.3,5019.2
XS Rating Curve= 0 ,0
Exp/Cntr=0.3,0.1

Type RM Length L Ch R = 1 ,8816    ,103,103,103
BEGIN DESCRIPTION:
Mapping XS 8b057bad
END DESCRIPTION:
XS GIS Cut Line= 3
      3834372.47     10497328.05      3833873.76     10497729.57
      3833508.57     10498575.77
#Sta/Elev= 30
  4293.4  375.65  4411.3  376.66  4460.9   375.6  4516.9  368.75  4531.3  367.82
  4545.7  365.29  4566.7  363.68  4609.7  356.96  4659.3  351.07  4681.6  349.73
  4752.1  341.68    4804  337.39  4836.9  334.72    4967  331.42  4977.2  329.19
  4982.7  330.24  4988.8  323.81  4996.7  322.37  4999.4  321.87  5002.7  322.37
  5004.3  323.58  5006.2  325.01  5011.6  324.49  5029.7  329.57  5053.2  331.33
  5119.5  331.84  5304.6  330.38  5315.5  332.09  5522.5  334.88  5855.3  350.23
#Mann= 5 ,-1 , 0
  4293.4     .05       0    4804     .16       0  4996.7     .07       0
  5002.7     .16       0  5004.3     .05       0
Bank Sta=4967,5053.2
XS Rating Curve= 0 ,0
Exp/Cntr=0.3,0.1

Type RM Length L Ch R = 1 ,8713    ,567,567,567
BEGIN DESCRIPTION:
FLAT BRANCH 15.0
END DESCRIPTION:
XS GIS Cut Line= 2
      3834127.01      10497208.3      3833294.14     10498441.98
#Sta/Elev= 30
  4325.3  373.92  4424.5  375.18  4475.5  372.54  4496.5  369.24  4562.4     362
  4568.9   359.8  4598.4  356.86  4605.1  355.07  4641.3  351.79  4664.3  348.19
  4706.3  344.56  4721.2  341.79  4764.2  338.39  4808.1  333.34  4844.1   333.3
  4930.9  330.17  4958.1  330.75    4973  329.94    4991  321.81  4993.8  321.31
    4997  321.81  4998.1  321.82    5003  321.85    5009  324.92  5015.3   330.8
  5110.9  330.12  5449.6  334.09  5512.6   335.9  5606.5  342.06  5813.8  349.67
#Mann= 5 ,-1 , 0
  4325.3     .05       0  4764.2     .16       0    4991     .03       0
    4997     .16       0  4998.1     .05       0
Bank Sta=4958.1,5015.3
XS Rating Curve= 0 ,0
Exp/Cntr=0.3,0.1

Type RM Length L Ch R = 1 ,8146    ,260,260,260
BEGIN DESCRIPTION:
FLAT BRANCH 14.0
END DESCRIPTION:
XS GIS Cut Line= 3
      3833699.94     10496874.94      3833455.15     10497723.89
      3833205.15     10498380.15
#Sta/Elev= 30
    4595   374.4    4654  373.54  4682.5  370.29  4687.7  371.61  4721.3  365.12
  4735.8  363.89  4787.8  356.08  4793.9  353.52  4832.7  350.72  4839.8  348.98
  4933.5  338.74  4954.3  334.28  4964.7  333.41  4972.6  331.98  4977.8  329.05
  4985.5  322.65  4992.9  320.41  4995.7  319.91  4998.9  320.41  5016.8   321.3
  5037.6  326.95  5068.8   326.9    5100  329.37  5162.5  327.55  5245.7  329.78
  5407.7  331.37  5729.5  332.08  5838.4  334.77  5984.3  341.48  6180.8  347.75
#Mann= 3 ,-1 , 0
    4595     .16       0  4992.9     .03       0  4998.9     .16       0
Bank Sta=4964.7,5100
XS Rating Curve= 0 ,0
Exp/Cntr=0.3,0.1

Type RM Length L Ch R = 1 ,7886    ,276,276,276
BEGIN DESCRIPTION:
Mapping XS 2deafd27
END DESCRIPTION:
XS GIS Cut Line= 3
      3833585.37     10496848.87      3833262.44     10497510.35
      3832414.07     10498098.49
#Sta/Elev= 30
    4477  374.26  4520.9  373.62  4667.6  350.93  4723.3  345.05  4767.8  338.32
  4819.3   333.6  4841.8  330.11  4892.4  327.72  4923.6   328.2  4976.9  325.52
  4996.5  319.45  4999.2  318.95  5002.5  319.45  5012.6  321.35    5022   328.6
  5027.6  323.67  5044.5  327.57  5050.1  326.64    5067  329.79  5459.9  330.08
  5517.3  329.04  5523.4  325.99  5532.2   324.2  5545.1  328.49  5559.2  329.83
    5898  332.99  5970.6  336.35  6092.6  344.22  6134.8  343.23  6245.4  347.69
#Mann= 3 ,-1 , 0
    4477     .16       0  4996.5     .03       0  5002.5     .16       0
#XS Ineff= 2 , 0
                         5365.06          336.72
Permanent Ineff=
       F       F
Bank Sta=4923.6,5067
XS Rating Curve= 0 ,0
Exp/Cntr=0.3,0.1

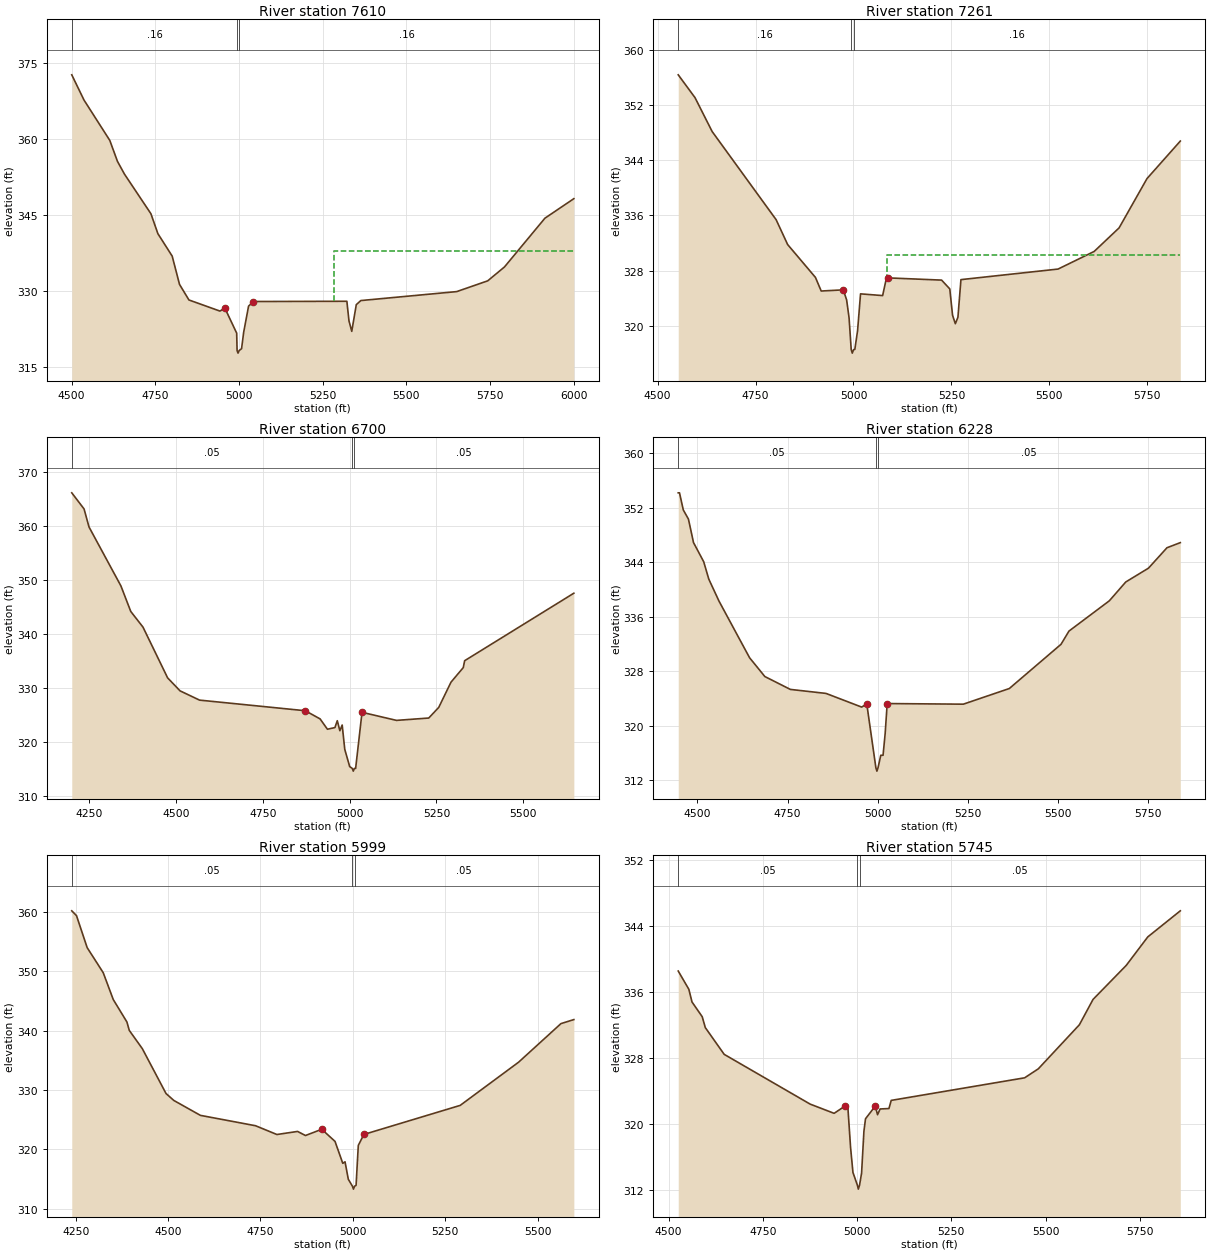
Type RM Length L Ch R = 1 ,7610    ,349,349,349
BEGIN DESCRIPTION:
FLAT BRANCH 13.0
END DESCRIPTION:
XS GIS Cut Line= 3
      3833449.63     10496810.16      3833149.61     10497210.19
      3832349.64     10497810.17
#Sta/Elev= 30
  4500.3  372.71  4536.8  367.73  4613.9  359.75  4636.8  355.61  4657.6   353.1
  4736.8  345.25  4757.6  341.31  4800.3  336.88  4822.2  331.29  4850.3  328.21
    4943  326.01  4957.6  326.61    4993  321.65  4994.2   318.2    4997   317.7
  5000.2   318.2  5007.6  318.58  5013.9  321.83  5028.5  326.99    5043   327.9
  5322.2  327.95  5328.5  324.08  5336.8     322  5350.3  327.28  5363.9  328.09
  5650.3  329.86    5743  331.99    5793  334.73  5913.9  344.37  6000.3  348.23
#Mann= 3 ,-1 , 0
  4500.3     .16       0  4994.2     .03       0  5000.2     .16       0
#XS Ineff= 2 , 0
                         5282.61          337.95
Permanent Ineff=
       F       F
Bank Sta=4957.6,5043
XS Rating Curve= 0 ,0
Exp/Cntr=0.3,0.1

Type RM Length L Ch R = 1 ,7261    ,561,561,561
BEGIN DESCRIPTION:
FLAT BRANCH 12.0
END DESCRIPTION:
XS GIS Cut Line= 3
      3833099.59     10496710.21      3832755.93     10497181.79
       3832299.6      10497710.2
#Sta/Elev= 30
  4552.6  356.36  4595.4  353.06  4639.2  348.15  4802.5  335.39  4831.9  331.79
  4902.9  327.03  4917.6  325.06    4974  325.23  4982.5  323.77  4988.7  321.18
  4994.2  316.57  4996.9  316.07  5000.2  316.57  5003.4  316.61  5010.4   319.3
    5018  324.65  5074.4   324.4  5082.9  326.63  5089.1  326.96  5224.9  326.64
  5245.8  325.37  5252.9  321.55    5260  320.33  5266.6  321.26  5274.3  326.71
  5522.2  328.24  5614.4  330.79    5678   334.2  5749.3  341.34  5834.3  346.77
#Mann= 3 ,-1 , 0
  4552.6     .16       0  4994.2     .07       0  5000.2     .16       0
#XS Ineff= 2 , 0
                         5084.55          330.21
Permanent Ineff=
       F       F
Bank Sta=4974,5089.1
XS Rating Curve= 0 ,0
Exp/Cntr=0.3,0.1

Type RM Length L Ch R = 1 ,6700    ,472,472,472
BEGIN DESCRIPTION:
FLAT BRANCH 11.0
END DESCRIPTION:
XS GIS Cut Line= 4
      3832949.58     10496460.21      3832349.61     10497010.19
      3832099.61     10497210.19       3831985.1     10497499.49
#Sta/Elev= 30
  4200.2  366.16  4235.6  363.17  4249.8  359.83  4341.7  348.89    4370  344.16
  4405.2  341.25  4476.1  331.84  4511.9  329.43    4568  327.71  4872.6  325.74
  4915.1  324.22  4936.1  322.31  4957.7  322.62  4964.5  323.89  4971.9  322.04
  4978.6  323.09    4986  318.58  5000.2  315.38  5007.7  315.04  5010.5  314.54
  5013.7  315.04  5017.3  315.04  5035.7  325.45    5135  323.95  5227.8  324.39
  5256.6  326.37  5291.8  331.04  5327.1  333.74  5331.1  335.02  5645.4  347.54
#Mann= 3 ,-1 , 0
  4200.2     .05       0  5007.7     .03       0  5013.7     .05       0
Bank Sta=4872.6,5035.7
XS Rating Curve= 0 ,0
Exp/Cntr=0.3,0.1

Type RM Length L Ch R = 1 ,6228    ,229,229,229
BEGIN DESCRIPTION:
FLAT BRANCH 10.0
END DESCRIPTION:
XS GIS Cut Line= 3
      3832599.59      10496260.2      3832199.61     10496660.19
      3831849.61     10497410.18
#Sta/Elev= 30
  4446.7  354.21  4450.2  354.21  4460.8  351.69    4475  350.35  4489.1   346.9
  4517.4  344.08  4531.5  341.53  4559.8   338.3  4644.7  329.97  4687.1  327.21
  4757.8  325.32  4856.8  324.73  4955.8  322.72  4969.9   323.2  4995.2  313.81
    4998  313.31  5001.2  313.81  5008.8  315.64  5015.1  315.64    5021  318.87
  5026.6  323.24  5237.8  323.15  5365.5  325.45    5509  331.95    5531  333.89
    5643  338.34  5688.7  341.11  5751.7  343.14    5803  346.14    5840  346.89
#Mann= 3 ,-1 , 0
  4446.7     .05       0  4995.2     .03       0  5001.2     .05       0
Bank Sta=4969.9,5026.6
XS Rating Curve= 0 ,0
Exp/Cntr=0.3,0.1

Type RM Length L Ch R = 1 ,5999    ,254,254,254
BEGIN DESCRIPTION:
Mapping XS 75207eee
END DESCRIPTION:
XS GIS Cut Line= 3
      3832606.91     10496148.99      3832082.36     10496561.05
      3831695.15     10497134.17
#Sta/Elev= 30
  4239.5  360.22  4252.3  359.41  4281.2  354.01  4324.6  349.79  4351.8  345.26
  4388.7  341.48  4395.1  340.06  4430.4  336.98  4494.6  329.41  4515.8  328.24
  4587.6  325.73  4736.8  323.98  4794.6   322.5  4850.6  323.02  4871.9  322.33
    4916  323.38  4951.9  321.34  4972.9  317.64    4979   317.9  4987.9  314.95
    4999  313.79  5001.8  313.29    5005  313.79  5008.9  313.92  5014.9  320.66
  5029.9  322.51  5290.6  327.41  5448.6  334.69  5563.3   341.2  5598.2  341.88
#Mann= 3 ,-1 , 0
  4239.5     .05       0    4999     .03       0    5005     .05       0
Bank Sta=4916,5029.9
XS Rating Curve= 0 ,0
Exp/Cntr=0.3,0.1

Type RM Length L Ch R = 1 ,5745    ,219,219,219
BEGIN DESCRIPTION:
FLAT BRANCH 9.0
END DESCRIPTION:
XS GIS Cut Line= 3
      3832399.64     10496110.17      3831999.61     10496410.19
      3831549.61     10497110.19
#Sta/Elev= 30
  4525.5  338.57  4553.7  336.35    4562  334.82  4589.1  333.03  4597.4   331.7
  4647.4  328.46  4875.5  322.42  4939.1   321.3  4968.2  322.19  4975.5   322.1
  4982.8  317.14  4989.1  314.12  5000.7   312.6  5003.4   312.1  5006.7   312.6
    5012  314.05  5018.2  319.12  5022.4  320.64  5048.3  322.18  5054.3  321.13
  5061.2  321.83  5084.6  321.88  5090.6  322.87  5444.6  325.61  5480.9   326.7
  5589.9  332.05  5626.2  335.13  5714.1  339.25  5771.5  342.72  5857.7  345.88
#Mann= 3 ,-1 , 0
  4525.5     .05       0  5000.7     .03       0  5006.7     .05       0
Bank Sta=4968.2,5048.3
XS Rating Curve= 0 ,0
Exp/Cntr=0.3,0.1

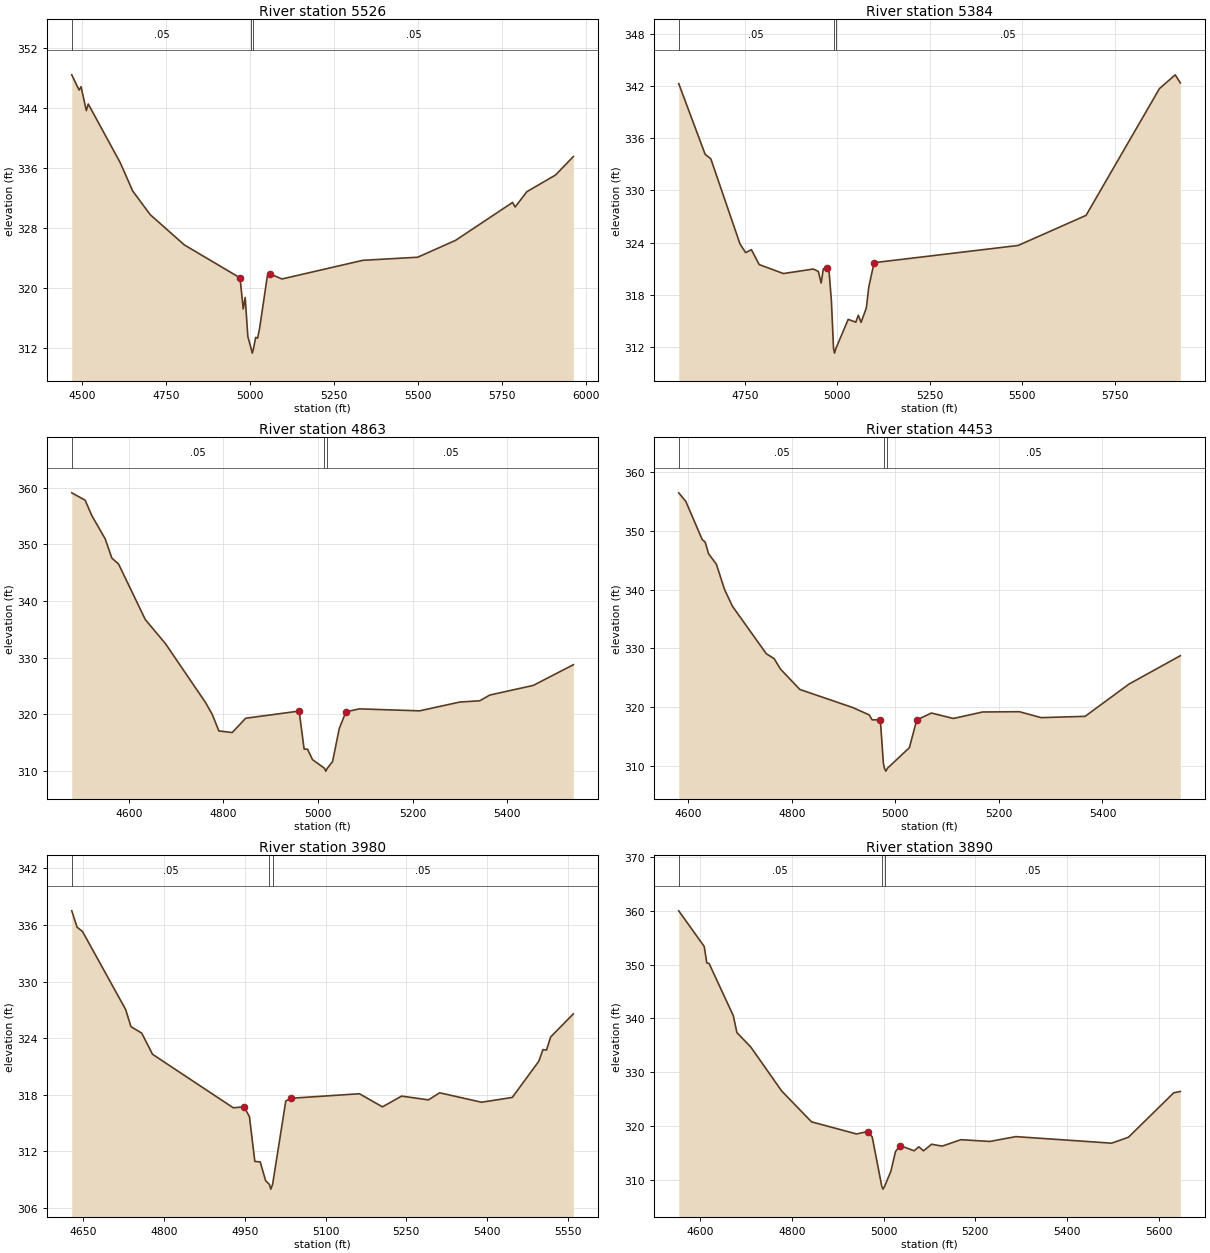
Type RM Length L Ch R = 1 ,5526    ,142,142,142
BEGIN DESCRIPTION:
Mapping XS b86c30fc
END DESCRIPTION:
XS GIS Cut Line= 3
      3832450.58     10495912.19      3831918.96     10496228.33
       3831341.1     10496886.54
#Sta/Elev= 30
  4468.8  348.48  4490.8  346.45  4496.6   346.9  4512.2  343.71    4518  344.59
  4613.5  336.74  4650.5  332.98  4702.6  329.83  4804.4  325.79  4970.2   321.4
  4979.7  317.25  4985.5  318.78  4993.5  313.57  5003.9  311.86  5006.7  311.36
  5009.9  311.86  5016.7  313.46  5022.5  313.36  5028.4  314.65  5051.7  321.68
  5059.5  321.92  5095.2  321.25  5336.2  323.74  5499.4  324.15  5612.3   326.4
  5782.2  331.46  5789.8  330.85  5824.9   332.9  5910.3  335.12  5963.2  337.58
#Mann= 3 ,-1 , 0
  4468.8     .05       0  5003.9     .03       0  5009.9     .05       0
Bank Sta=4970.2,5059.5
XS Rating Curve= 0 ,0
Exp/Cntr=0.3,0.1

Type RM Length L Ch R = 1 ,5384    ,521,521,521
BEGIN DESCRIPTION:
FLAT BRANCH 8.0
END DESCRIPTION:
XS GIS Cut Line= 3
      3832099.63     10495760.16      3831849.61     10496160.19
      3831199.63     10496760.17
#Sta/Elev= 30
  4571.2  342.27  4642.6  334.14  4657.9  333.63  4736.9  323.83  4752.3  322.83
  4767.6  323.18  4788.8  321.46  4854.3  320.43    4935  320.95  4948.6  320.68
  4956.3  319.34  4962.2  320.98  4971.6   321.1  4977.5  320.77    4984  317.31
  4989.8  311.78  4992.6  311.28  4995.8  311.78  5029.4  315.16    5050  314.84
  5056.8  315.64  5064.2  314.81  5078.4  316.46  5085.2  318.91  5099.4  321.68
  5488.9  323.66  5672.6  327.12  5871.1   341.7  5913.6  343.28  5927.5  342.35
#Mann= 3 ,-1 , 0
  4571.2     .05       0  4989.8     .03       0  4995.8     .05       0
Bank Sta=4971.6,5099.4
XS Rating Curve= 0 ,0
Exp/Cntr=0.3,0.1

Type RM Length L Ch R = 1 ,4863    ,410,410,410
BEGIN DESCRIPTION:
FLAT BRANCH 7.0
END DESCRIPTION:
XS GIS Cut Line= 3
       3831899.6      10495510.2      3831549.61     10495860.19
      3831149.64     10496260.15
#Sta/Elev= 30
  4479.2   359.1  4507.5   357.8  4521.6  355.09  4549.9  350.97    4564  347.57
  4578.2  346.52  4634.8   336.7  4677.2  332.47    4762  322.06  4776.2  319.97
  4790.3  317.03  4818.6  316.75  4846.9  319.27    4960  320.54  4970.6  313.81
  4977.7  313.81  4988.3  311.96  5013.6  310.43  5016.3  309.93  5019.6  310.43
  5030.7  311.63  5044.9  317.47    5059  320.41  5087.3  320.93  5214.6  320.58
  5299.4  322.13  5341.9  322.36  5363.1  323.37    5455  325.07  5539.8  328.73
#Mann= 3 ,-1 , 0
  4479.2     .05       0  5013.6     .03       0  5019.6     .05       0
Bank Sta=4960,5059
XS Rating Curve= 0 ,0
Exp/Cntr=0.3,0.1

Type RM Length L Ch R = 1 ,4453    ,473,473,473
BEGIN DESCRIPTION:
FLAT BRANCH 6.0
END DESCRIPTION:
XS GIS Cut Line= 3
      3831749.61     10495360.19      3831399.61     10495560.19
      3830999.61     10495960.19
#Sta/Elev= 30
  4581.6  356.43  4595.3  354.97  4626.9  348.49  4632.7  348.05  4639.2  346.08
  4654.3   344.3  4670.1     340  4685.3  337.16  4750.8  329.08  4765.9  328.25
  4778.1  326.48  4815.5  323.02  4917.8  319.94  4949.4   318.7  4955.2  317.85
    4971  317.86  4976.8  310.55  4978.8  309.64  4981.6  309.14  4984.8  309.64
  5027.1  313.13  5041.3  317.84  5069.6  319.01    5112  318.09  5168.6  319.19
  5239.3  319.24  5281.7  318.23  5366.5  318.45  5451.4  323.94  5550.4  328.75
#Mann= 3 ,-1 , 0
  4581.6     .05       0  4978.8     .03       0  4984.8     .05       0
Bank Sta=4971,5041.3
XS Rating Curve= 0 ,0
Exp/Cntr=0.3,0.1

Type RM Length L Ch R = 1 ,3980    ,90,90,90
BEGIN DESCRIPTION:
FLAT BRANCH 5.0
END DESCRIPTION:
XS GIS Cut Line= 3
       3831549.6     10495260.19      3831149.61     10495260.19
      3830749.61     10495610.19
#Sta/Elev= 30
  4628.6   337.5  4638.6  335.76  4648.6  335.31  4728.6  327.04  4738.6  325.21
  4758.6  324.52  4778.6  322.28  4928.6   316.6  4948.6   316.7  4958.6  315.66
  4968.6  310.91  4978.6  310.86  4988.6  308.88  4995.6  308.47  4998.3  307.97
  5001.6  308.47  5026.1  317.32  5035.7  317.61  5162.9  318.09  5205.6   316.7
  5241.2  317.84    5291  317.44  5311.9  318.19  5389.7  317.19  5446.7   317.7
    5496  321.54  5503.6  322.77  5510.3  322.73  5517.9  324.11  5560.1  326.57
#Mann= 3 ,-1 , 0
  4628.6     .05       0  4995.6     .03       0  5001.6     .05       0
Bank Sta=4948.6,5035.7
XS Rating Curve= 0 ,0
Exp/Cntr=0.3,0.1

Type RM Length L Ch R = 1 ,3890    ,344,344,344
BEGIN DESCRIPTION:
Mapping XS 30a71bde
END DESCRIPTION:
XS GIS Cut Line= 3
      3831634.22     10495093.91      3831009.19     10495210.24
      3830741.82     10495581.77
#Sta/Elev= 30
  4553.6  360.01  4609.2  353.37  4614.7  350.35  4619.8  350.21  4672.6  340.49
  4680.4  337.36  4710.9  334.64  4778.1  326.48  4843.1  320.75  4941.4  318.49
  4965.2  318.95  4975.3  317.96  4996.3  308.73    4999  308.23  5002.3  308.73
    5016  311.53  5026.2  315.23  5036.4  316.33  5066.9  315.36    5077  316.11
  5087.2  315.36  5104.8  316.58  5127.9  316.23  5168.6  317.43  5231.9   317.1
  5288.4     318  5497.3  316.78  5533.9  317.88  5632.8  326.16  5647.1   326.4
#Mann= 3 ,-1 , 0
  4553.6     .05       0  4996.3     .03       0  5002.3     .05       0
Bank Sta=4965.2,5036.4
XS Rating Curve= 0 ,0
Exp/Cntr=0.3,0.1

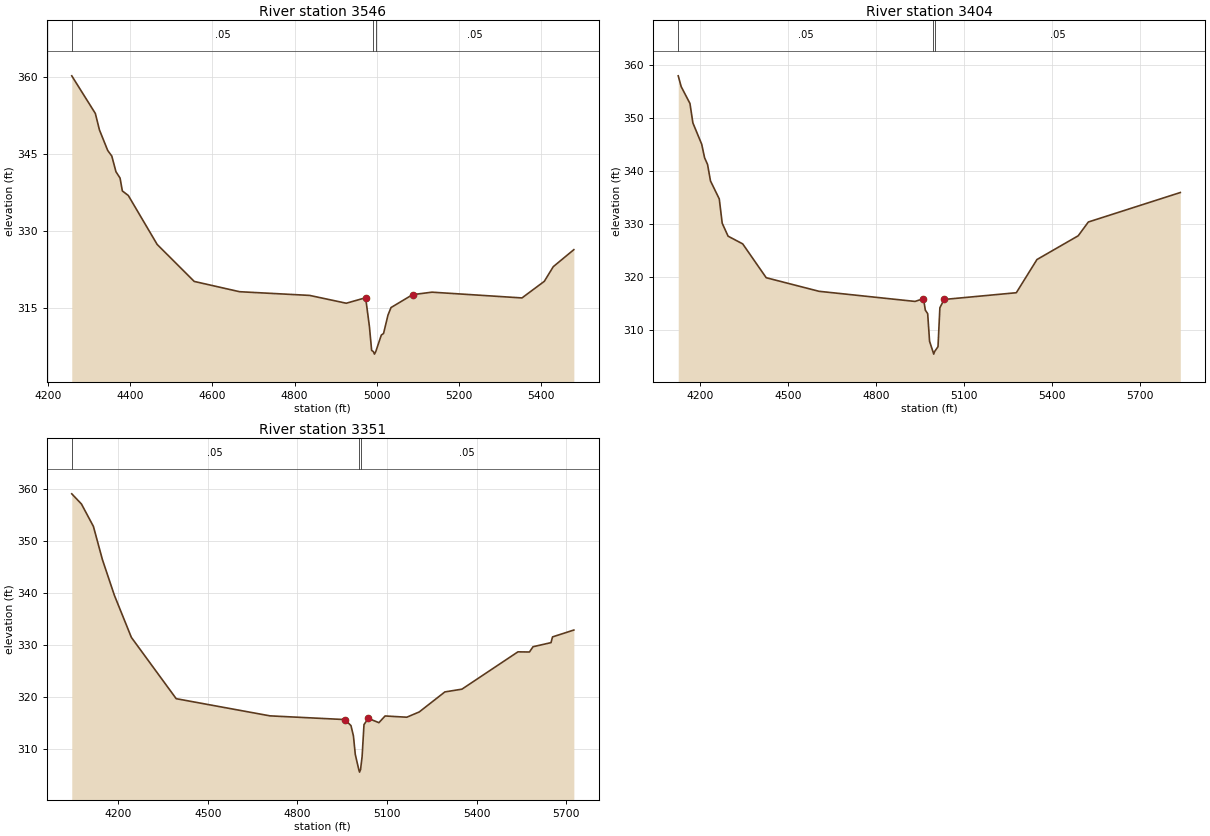
Type RM Length L Ch R = 1 ,3546    ,142,142,142
BEGIN DESCRIPTION:
Mapping XS c1f4ec68
END DESCRIPTION:
XS GIS Cut Line= 3
      3831616.82     10494994.96      3830946.69     10495050.52
      3830730.17     10495556.29
#Sta/Elev= 30
  4257.4  360.19  4314.8  352.87  4324.8  349.67  4344.9  345.68  4354.9  344.58
    4365  341.54    4375   340.3  4380.6   337.8  4395.1  336.91  4465.3   327.4
  4555.6   320.2    4666   318.2  4836.6  317.48  4925.9  315.96    4973  317.03
  4982.2  311.43  4987.6  306.79  4991.7  306.56  4994.5  306.06  4997.7  306.56
  5011.2  309.77  5016.6  310.07  5027.4  313.65  5034.8  315.12  5087.4  317.63
  5134.6  318.11  5353.7  316.99  5408.1  320.22  5429.9  323.07    5480  326.38
#Mann= 3 ,-1 , 0
  4257.4     .05       0  4991.7     .03       0  4997.7     .05       0
Bank Sta=4973,5087.4
XS Rating Curve= 0 ,0
Exp/Cntr=0.3,0.1

Type RM Length L Ch R = 1 ,3404    ,53,53,53
BEGIN DESCRIPTION:
FLAT BRANCH 4.0
END DESCRIPTION:
XS GIS Cut Line= 4
      3831599.58     10494910.19      3830979.89     10494926.58
      3830604.89     10495228.67      3830542.53     10495836.64
#Sta/Elev= 30
  4126.4  358.02  4136.4  355.99  4166.4   352.8  4176.4  349.14  4206.4  345.13
  4216.4  342.55  4226.4  341.31  4236.4   338.2  4266.4   334.8  4276.4  330.22
  4296.4  327.78  4346.4  326.32  4426.5  319.94  4606.5  317.38  4934.1  315.47
  4962.9     316  4969.3  313.82  4977.3  313.16  4983.7  307.95  4995.1  306.03
  4997.8  305.53  5001.1  306.03  5012.5  306.94  5018.9  314.27  5033.3  315.84
  5279.6  317.11    5350  323.37  5490.7  327.85  5525.3  330.45    5839  336.01
#Mann= 3 ,-1 , 0
  4126.4     .05       0  4995.1     .03       0  5001.1     .05       0
Bank Sta=4962.9,5033.3
XS Rating Curve= 0 ,0
Exp/Cntr=0.3,0.1

Type RM Length L Ch R = 1 ,3351    ,53,53,53
BEGIN DESCRIPTION:
Mapping XS 4e82d72f
END DESCRIPTION:
XS GIS Cut Line= 4
        3831642.     10494841.75      3830957.98     10494887.46
      3830463.61     10495264.93      3830514.34     10495635.63
#Sta/Elev= 30
    4044  359.05  4076.5  357.09  4116.5  352.79  4146.6  346.42  4186.7  339.56
  4243.7  331.46  4393.8  319.69  4707.9  316.39  4958.4  315.68  4979.2  314.52
  4987.4  312.55  4993.7  308.96  5005.3  306.08    5008  305.58  5011.3  306.08
  5016.5  308.58  5022.8  314.71  5037.3  315.91  5072.7  315.08  5093.5  316.37
  5166.1  316.13  5207.8  317.14  5293.7  320.99  5350.9  321.52  5538.5  328.69
    5577  328.66    5589  329.67  5649.2  330.46  5654.3  331.56  5725.7  332.88
#Mann= 3 ,-1 , 0
    4044     .05       0  5005.3     .03       0  5011.3     .05       0
Bank Sta=4958.4,5037.3
XS Rating Curve= 0 ,0
Exp/Cntr=0.3,0.1