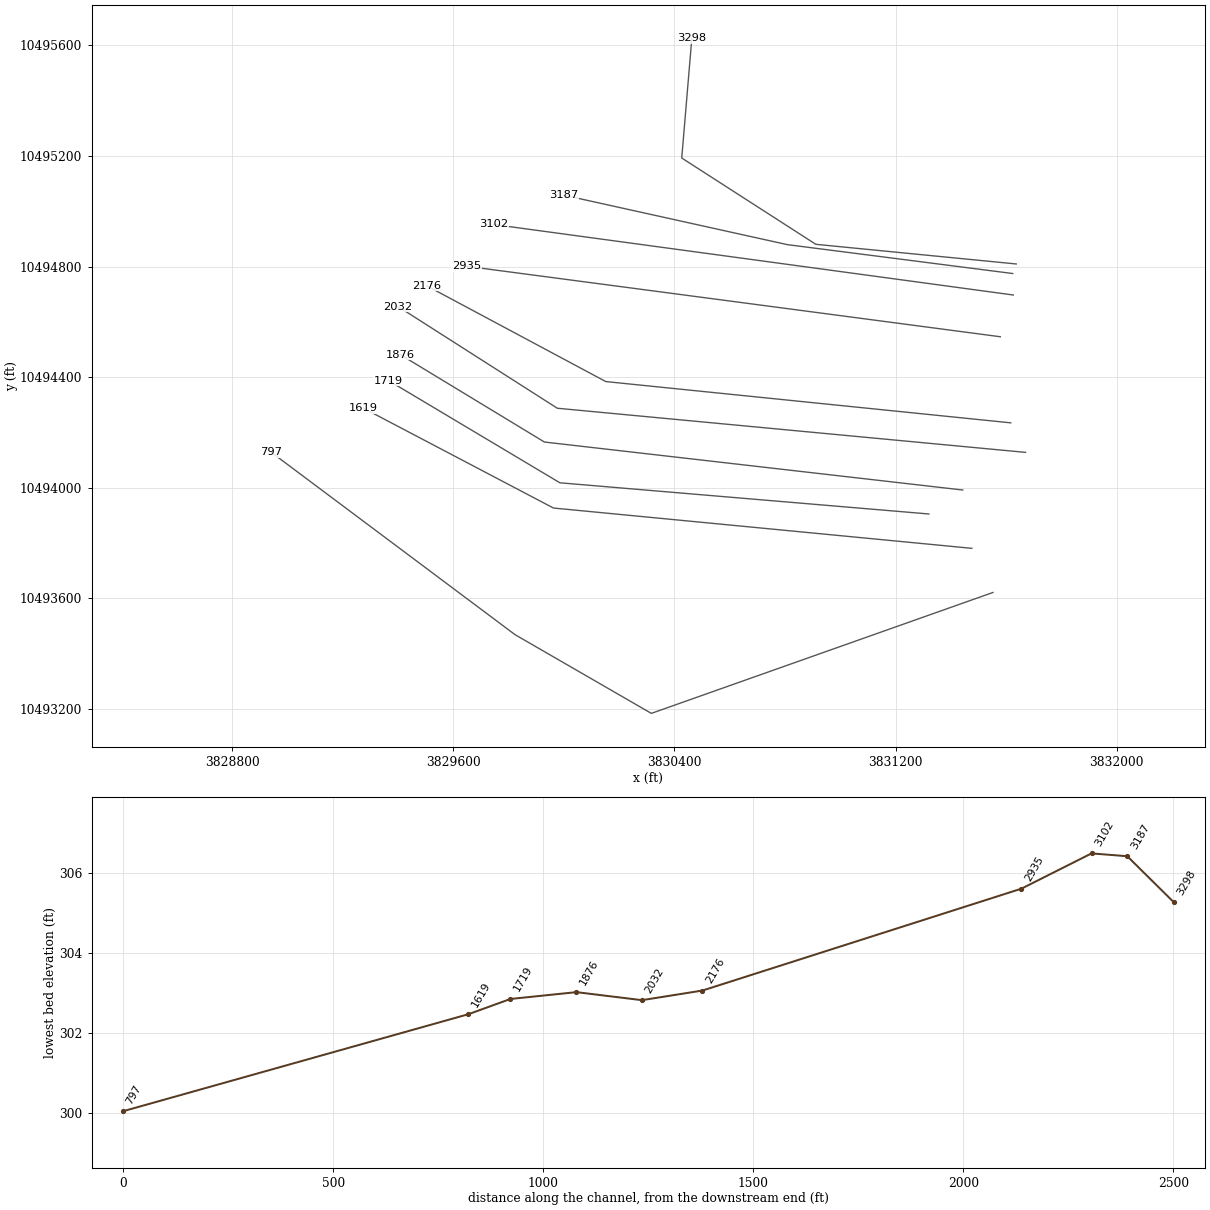
HEC-RAS study FLAT BRANCH.prj: FLAT BRANCH Base Level Engineering

--- FLAT BRANCH.g01 (geometry) --- (continued)

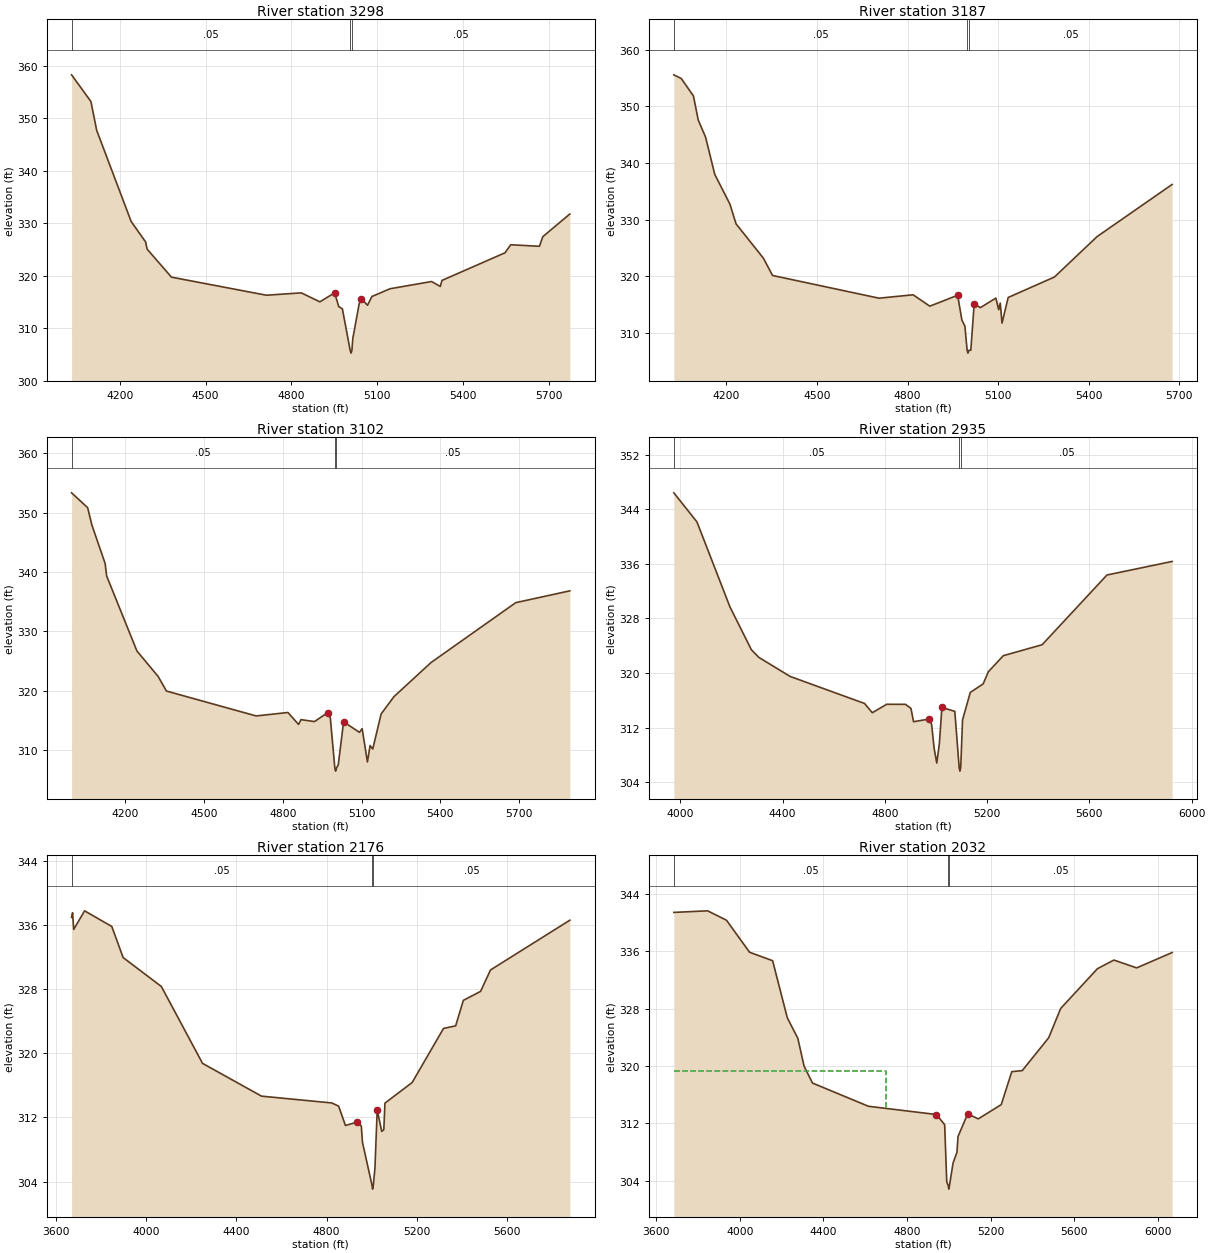
Type RM Length L Ch R = 1 ,3298    ,111,111,111
BEGIN DESCRIPTION:
Mapping XS 289539c9
END DESCRIPTION:
XS GIS Cut Line= 4
      3831636.84     10494809.39      3830911.53     10494880.54
      3830426.32     10495192.81      3830462.82     10495625.88
#Sta/Elev= 30
  4032.1  358.27  4099.7  353.18  4119.8   347.7  4240.3  330.33  4290.6  326.45
    4296  325.07    4381  319.73  4712.6  316.29  4834.5  316.74  4899.4  315.03
  4950.9  316.74  4965.3  314.13    4978   313.7  5005.3  305.76  5008.1  305.26
  5011.3  305.76  5014.3     308  5036.7  314.67  5044.6  315.64  5065.8  314.37
    5081  316.04  5144.3  317.52  5289.6   318.9    5320  317.96  5325.9  319.11
    5546  324.37  5566.1   325.9  5666.4  325.61  5678.1  327.44  5772.5  331.76
#Mann= 3 ,-1 , 0
  4032.1     .05       0  5005.3     .03       0  5011.3     .05       0
Bank Sta=4950.9,5044.6
XS Rating Curve= 0 ,0
Exp/Cntr=0.3,0.1

Type RM Length L Ch R = 1 ,3187    ,85,85,85
BEGIN DESCRIPTION:
Mapping XS 9a4c9b90
END DESCRIPTION:
XS GIS Cut Line= 3
        3831624.     10494774.81      3830808.36     10494879.36
      3829999.45     10495058.41
#Sta/Elev= 30
  4025.6  355.55  4050.2   354.9  4090.5  351.82  4106.4  347.57  4130.8  344.54
  4161.1  337.98  4211.5  332.71  4231.7  329.24  4322.4  323.17  4352.6  320.12
  4705.5  316.11  4818.3  316.71  4873.6   314.7  4965.9  316.63  4979.8  312.28
    4990  311.16  4997.3  306.91    5000  306.41  5003.3  306.91  5009.5  306.93
  5020.7  315.14  5041.2  314.44  5092.4  316.13  5101.9  314.07    5107  315.25
  5112.9  311.72  5133.4  316.24  5286.6  319.85  5427.7  326.98  5676.4  336.19
#Mann= 3 ,-1 , 0
  4025.6     .05       0  4997.3     .03       0  5003.3     .05       0
Bank Sta=4965.9,5020.7
XS Rating Curve= 0 ,0
Exp/Cntr=0.3,0.1

Type RM Length L Ch R = 1 ,3102    ,167,167,167
BEGIN DESCRIPTION:
Mapping XS 0e69a1a4
END DESCRIPTION:
XS GIS Cut Line= 2
      3831626.12     10494697.06      3829745.86     10494952.28
#Sta/Elev= 30
  3995.5  353.33  4056.7  350.83  4072.7  347.93  4123.2  341.45  4129.2  339.32
  4244.3  326.71    4325  322.43  4356.8  319.96  4698.4  315.77  4819.5  316.35
  4859.9  314.34  4869.3  315.15  4920.4  314.82  4970.9  316.32    4981  315.38
  4998.1  306.98  5000.9  306.48  5004.1  306.98  5011.2  307.56  5031.4  314.78
  5091.9  313.01  5102.1  313.63  5122.2  308.02  5132.3  310.79  5142.4   310.2
  5174.4  316.11  5223.2  319.02  5364.4  324.76    5687  334.84    5893  336.83
#Mann= 3 ,-1 , 0
  3995.5     .05       0  4998.1     .03       0  5004.1     .05       0
Bank Sta=4970.9,5031.4
XS Rating Curve= 0 ,0
Exp/Cntr=0.3,0.1

Type RM Length L Ch R = 1 ,2935    ,759,759,759
BEGIN DESCRIPTION:
FLAT BRANCH 3.0
END DESCRIPTION:
XS GIS Cut Line= 2
      3831579.22     10494546.03       3829646.9     10494801.24
#Sta/Elev= 30
  3974.4  346.44  4064.8  342.17    4194  329.69  4277.6  323.42  4306.9  322.29
  4429.6  319.49  4720.4  315.53  4750.7  314.17  4807.1  315.41  4880.6   315.4
    4902   314.8  4912.1  312.85  4972.6  313.24  4982.7  312.47  4992.8  308.91
  5002.9  306.79    5013   309.6    5023  314.95  5073.5  314.37  5090.6   306.1
  5093.4   305.6  5096.6   306.1  5103.7  313.11    5134  317.15  5184.4   318.4
  5204.6  320.18  5263.2  322.54  5415.2  324.15  5668.6  334.38  5923.5  336.37
#Mann= 3 ,-1 , 0
  3974.4     .05       0  5090.6     .03       0  5096.6     .05       0
Bank Sta=4972.6,5023
XS Rating Curve= 0 ,0
Exp/Cntr=0.3,0.1

Type RM Length L Ch R = 1 ,2176    ,144,144,144
BEGIN DESCRIPTION:
Mapping XS 307f2806
END DESCRIPTION:
XS GIS Cut Line= 3
      3831616.92     10494234.51      3830151.63     10494383.82
      3829503.47     10494730.43
#Sta/Elev= 30
  3669.7  336.96  3674.2  337.54  3679.2  335.46  3727.3  337.78  3847.9  335.83
  3898.2  331.95  4067.5  328.34    4250  318.75  4511.4  314.66    4823  313.81
  4853.1  313.41  4883.3     311  4933.5  311.41  4953.6  310.94  4958.7   308.9
  5000.9  303.56  5003.6  303.06  5006.9  303.56  5013.9  305.65    5024  312.94
  5044.1  310.26  5053.3  310.48  5058.3  313.79  5178.9  316.36  5317.9  323.11
  5371.7  323.43  5405.7  326.61  5482.1  327.73    5526   330.4  5877.6  336.61
#Mann= 3 ,-1 , 0
  3669.7     .05       0  5000.9     .03       0  5006.9     .05       0
Bank Sta=4933.5,5024
XS Rating Curve= 0 ,0
Exp/Cntr=0.3,0.1

Type RM Length L Ch R = 1 ,2032    ,156,156,156
BEGIN DESCRIPTION:
Mapping XS 5f792057
END DESCRIPTION:
XS GIS Cut Line= 3
      3831670.56     10494127.62      3829976.07     10494287.35
      3829399.83     10494655.31
#Sta/Elev= 30
  3683.5  341.43  3845.2  341.65  3935.6  340.34  4046.1  335.87  4156.5  334.69
  4226.8  326.72  4277.1  323.87  4307.2  319.97  4347.4  317.62  4615.1  314.38
  4940.6  313.23  4980.2  311.81  4990.2  303.85  4997.3  303.32    5000  302.82
  5003.3  303.32  5020.4  306.46  5039.1  307.97  5044.1  310.16  5090.7  313.33
  5140.9  312.62  5251.1  314.61  5301.6  319.21  5351.8  319.36  5478.3  323.94
  5535.8  328.03  5711.8  333.58  5790.5  334.78  5899.6  333.69  6069.2  335.83
#Mann= 3 ,-1 , 0
  3683.5     .05       0  4997.3     .03       0  5003.3     .05       0
#XS Ineff= 2 , 0
            4700  319.33
Permanent Ineff=
       F       F
Bank Sta=4940.6,5090.7
XS Rating Curve= 0 ,0
Exp/Cntr=0.3,0.1

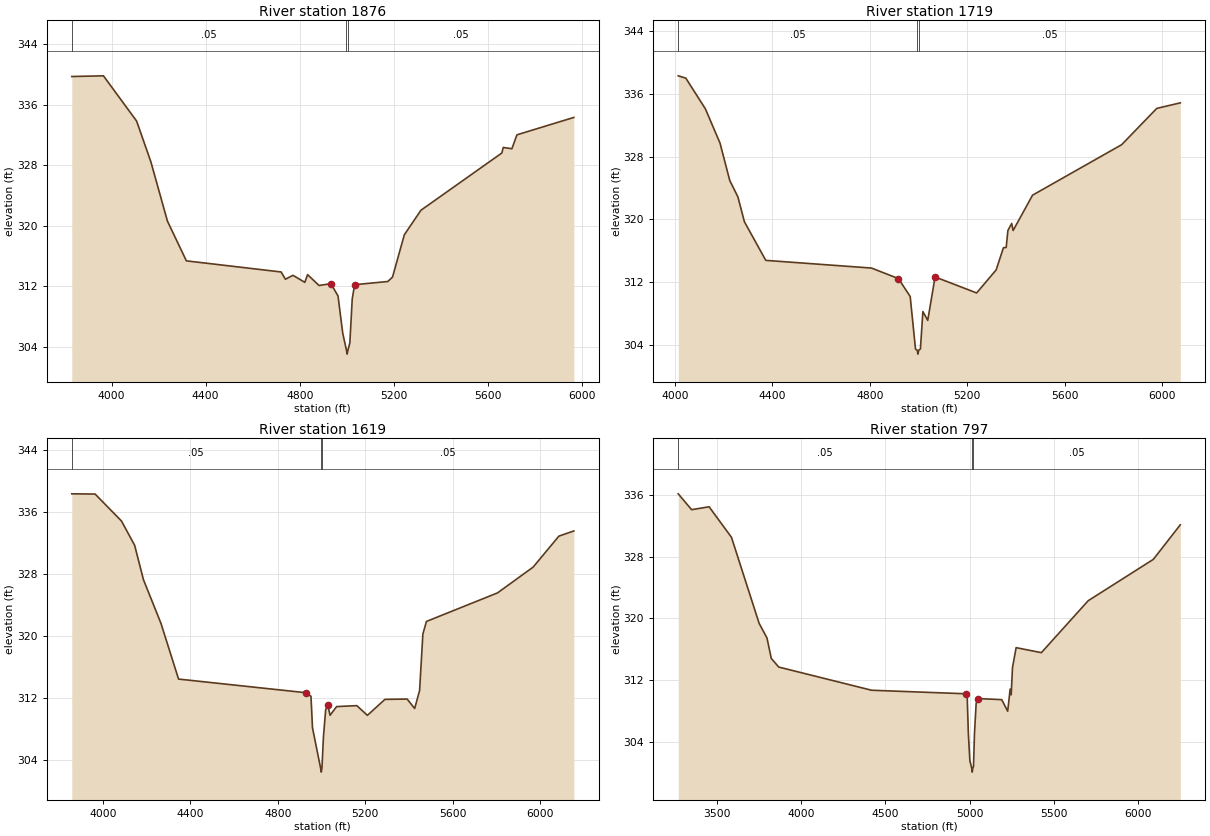
Type RM Length L Ch R = 1 ,1876    ,157,157,157
BEGIN DESCRIPTION:
Mapping XS c4876798
END DESCRIPTION:
XS GIS Cut Line= 3
      3831443.32     10493991.45      3829929.41     10494165.07
      3829408.59     10494481.03
#Sta/Elev= 30
  3831.1  339.72  3965.7  339.81  4106.6  333.83    4167  328.46  4237.5  320.61
    4318  315.35  4720.6  313.88  4738.7  312.92  4770.9  313.44  4821.3  312.51
  4832.9  313.53  4881.7  312.09    4932  312.34  4962.2  310.71  4982.3  305.78
  4998.2  303.52  5000.9  303.02  5004.2  303.52  5012.5  304.52  5022.6   310.3
  5032.6   312.2  5173.6  312.62  5193.7   313.2    5244   318.8  5314.5  322.04
  5658.3  329.61  5664.2  330.34    5701  330.17  5722.3  332.01  5964.1  334.31
#Mann= 3 ,-1 , 0
  3831.1     .05       0  4998.2     .03       0  5004.2     .05       0
Bank Sta=4932,5032.6
XS Rating Curve= 0 ,0
Exp/Cntr=0.3,0.1

Type RM Length L Ch R = 1 ,1719    ,100,100,100
BEGIN DESCRIPTION:
Mapping XS f252cf02
END DESCRIPTION:
XS GIS Cut Line= 3
      3831320.49     10493904.72      3829985.43     10494017.56
      3829365.68     10494387.33
#Sta/Elev= 30
  4013.5  338.29  4044.5     338  4124.8   334.1    4185  329.73  4225.1  324.96
  4258.4  322.88  4285.3   319.7    4373  314.79  4807.2  313.81  4917.6  312.47
  4965.9  310.19  4987.8  303.48  4994.9  303.35  4997.6  302.85  5000.9  303.35
  5007.9  303.51    5018  308.27    5038  307.15  5068.1  312.68  5238.7  310.64
    5319  313.58  5348.7   316.4  5360.1  316.43  5367.1  318.59  5382.6  319.49
  5388.5  318.59  5468.3  323.09  5834.2  329.52  5978.2  334.14    6075  334.85
#Mann= 3 ,-1 , 0
  4013.5     .05       0  4994.9     .03       0  5000.9     .05       0
Bank Sta=4917.6,5068.1
XS Rating Curve= 0 ,0
Exp/Cntr=0.3,0.1

Type RM Length L Ch R = 1 ,1619    ,822,822,822
BEGIN DESCRIPTION:
FLAT BRANCH 2.0
END DESCRIPTION:
XS GIS Cut Line= 3
      3831476.05     10493780.41      3829962.18     10493926.24
      3829274.72     10494287.33
#Sta/Elev= 30
  3857.5  338.39  3964.4  338.36    4085  334.88  4145.3  331.74  4185.5  327.31
  4265.8  321.66  4346.2  314.48  4928.9  312.72  4952.1  312.26    4959   308.2
  4996.2  302.97    4999  302.47  5002.2  302.97  5009.2  307.05  5019.3  310.52
  5029.3  311.07  5039.4  309.81  5069.5  310.93  5161.9  311.05  5210.2   309.8
  5290.5  311.86  5392.3   311.9  5426.5  310.68  5449.1     313  5464.1   320.3
  5480.5  321.92  5805.5   325.6  5968.6  328.93  6086.5  332.93  6154.9   333.6
#Mann= 3 ,-1 , 0
  3857.5     .05       0  4996.2     .03       0  5002.2     .05       0
Bank Sta=4928.9,5029.3
XS Rating Curve= 0 ,0
Exp/Cntr=0.3,0.1

Type RM Length L Ch R = 1 ,797     ,0,0,0
BEGIN DESCRIPTION:
FLAT BRANCH 1.0
END DESCRIPTION:
XS GIS Cut Line= 4
      3831552.49     10493620.69      3830316.35     10493183.18
      3829823.29      10493467.9      3828941.38     10494127.61
#Sta/Elev= 30
    3269  336.18  3348.5  334.12  3452.4   334.5  3585.1  330.54  3749.4  319.37
  3796.1  317.46  3821.7  314.81  3866.1  313.69  4417.7  310.68  4979.6  310.22
  4985.3  309.82  4992.2  305.03  5001.1  301.54  5012.3  300.55  5015.1  300.05
  5018.3  300.55  5022.7   300.8  5028.4     305  5038.4  308.97    5050   309.6
  5190.3  309.46  5225.8  307.96  5240.3  310.83  5246.6  310.08  5254.2   313.6
  5275.8  316.21  5425.8  315.56  5703.7   322.3  6090.7  327.67    6251  332.16
#Mann= 3 ,-1 , 0
    3269     .05       0  5012.3     .03       0  5018.3     .05       0
Bank Sta=4979.6,5050
XS Rating Curve= 0 ,0
Exp/Cntr=0.3,0.1

Chan Stop Cuts=-1
Use User Specified Reach Order=0
Composite Channel Slope=5