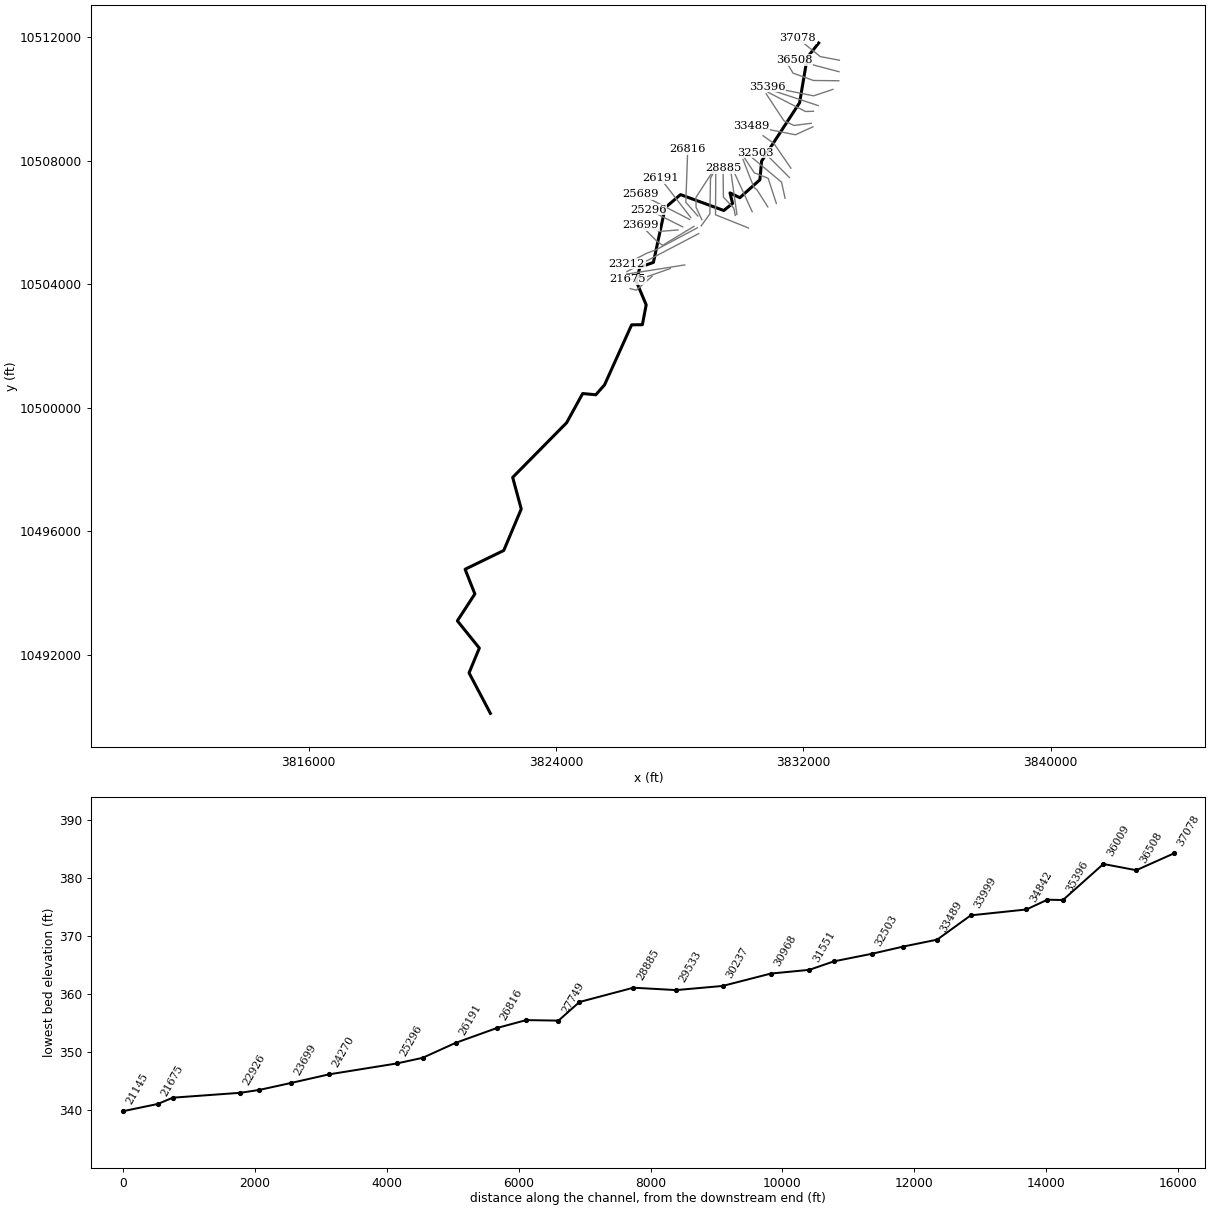
--- HAMMOND CREEK.prj (project) ---

Proj Title=HAMMOND CREEK Base Level Engineering
Current Plan=p01
Default Exp/Contr=0.3,0.1
English Units
Geom File=g01
Flow File=f01
Plan File=p01
Y Axis Title=Elevation
X Axis Title(PF)=Main Channel Distance
X Axis Title(XS)=Station
BEGIN DESCRIPTION:
HAMMOND CREEK
END DESCRIPTION:
DSS Export Rating Curves= 0
DSS Export Rating Curve Sorted= 0
DSS Export Volume Flow Curves= 0
DXF OffsetX= 0
DXF OffsetY= 0
DXF ScaleX= 1
DXF ScaleY= 10

--- HAMMOND CREEK.p01 (plan) ---

Plan Title=Multiple Run
Short Identifier=Multiple
Geom File=g01
Flow File=f01
Subcritical Flow
K Sum by GR= 0
Std Step Tol= 0.01
Critical Tol= 0.01
Num of Std Step Trials= 20
Max Error Tol= 0.3
Flow Tol Ratio= 0.001
Split Flow NTrial= 30
Split Flow Tol= 0.02
Split Flow Ratio= 0.02
Log Output Level= 0
Friction Slope Method= 1
Unsteady Friction Slope Method= 2
Unsteady Bridges Friction Slope Method= 1
Parabolic Critical Depth
Global Vel Dist=  1 , 1 , 1
Global Log Level= 0
CheckData=True
Encroach Param= -1, 0, 0, 0
BEGIN DESCRIPTION:
Multiple Run
END DESCRIPTION:

--- HAMMOND CREEK.f01 (steady flow) ---

Flow Title=Multiple
Program Version=4.10
Number of Profiles= 7
Profile Names=10-year,25-year,50-year,1pct_min,100-year,1pct_plu,500-year
River Rch & RM=HAMMOND CREEK,Reach-1         ,37078
     726     987    1203    1077    1457    1970    2143
River Rch & RM=HAMMOND CREEK,Reach-1         ,32978
    1042    1434    1762    1587    2146    2902    3196
River Rch & RM=HAMMOND CREEK,Reach-1         ,26816
    1458    2030    2515    2280    3084    4171    4657
River Rch & RM=HAMMOND CREEK,Reach-1         ,20449
    1566    2184    2707    2456    3321    4492    5020
River Rch & RM=HAMMOND CREEK,Reach-1         ,15819
    2080    2938    3674    3360    4544    6146    6982
River Rch & RM=HAMMOND CREEK,Reach-1         ,9951
    2147    3034    3793    3468    4690    6342    7199
River Rch & RM=HAMMOND CREEK,Reach-1         ,7481
    2147    3034    3793    3468    4690    6342    7199
River Rch & RM=HAMMOND CREEK,Reach-1         ,3629
    2239    3163    3955    3615    4889    6612    7503
Boundary for River Rch & Prof#=HAMMOND CREEK,Reach-1         , 1
Up Type= 0
Dn Type= 3
Dn Slope=0.005
Boundary for River Rch & Prof#=HAMMOND CREEK,Reach-1         , 2
Up Type= 0
Dn Type= 3
Dn Slope=0.005
Boundary for River Rch & Prof#=HAMMOND CREEK,Reach-1         , 3
Up Type= 0
Dn Type= 3
Dn Slope=0.005
Boundary for River Rch & Prof#=HAMMOND CREEK,Reach-1         , 4
Up Type= 0
Dn Type= 3
Dn Slope=0.005
Boundary for River Rch & Prof#=HAMMOND CREEK,Reach-1         , 5
Up Type= 0
Dn Type= 3
Dn Slope=0.005
Boundary for River Rch & Prof#=HAMMOND CREEK,Reach-1         , 6
Up Type= 0
Dn Type= 3
Dn Slope=0.005
Boundary for River Rch & Prof#=HAMMOND CREEK,Reach-1         , 7
Up Type= 0
Dn Type= 3
Dn Slope=0.005
DSS Import GetInterval= 0
DSS Import GetPeak= 0
DSS Import FillOption= 0

--- HAMMOND CREEK.g01 (geometry) ---

Geom Title=Existing Conditions
Program Version=4.10

River Reach=HAMMOND CREEK   ,Reach-1
Reach XY= 30
      3832499.61     10511810.19      3832130.25       10511345.
       3831881.5       10509877.      3830652.75       10507988.
      3830597.25       10507384.       3829948.5       10506803.
      3829630.25       10506959.        3829714.       10506618.
      3829429.75       10506389.        3828030.       10506903.
      3827533.25       10506479.        3827153.       10504709.
       3826717.5       10504556.       3826596.5       10504101.
      3826919.25       10503335.        3826796.       10502692.
        3826449.       10502688.       3825571.5       10500743.
      3825289.25       10500424.       3824864.5       10500464.
       3824345.5       10499518.      3822600.25       10497749.
        3822878.       10496726.      3822311.75       10495383.
       3821061.5       10494775.      3821377.25       10493976.
       3820811.5       10493106.      3821522.25       10492223.
       3821189.5       10491421.       3821879.5       10490110.

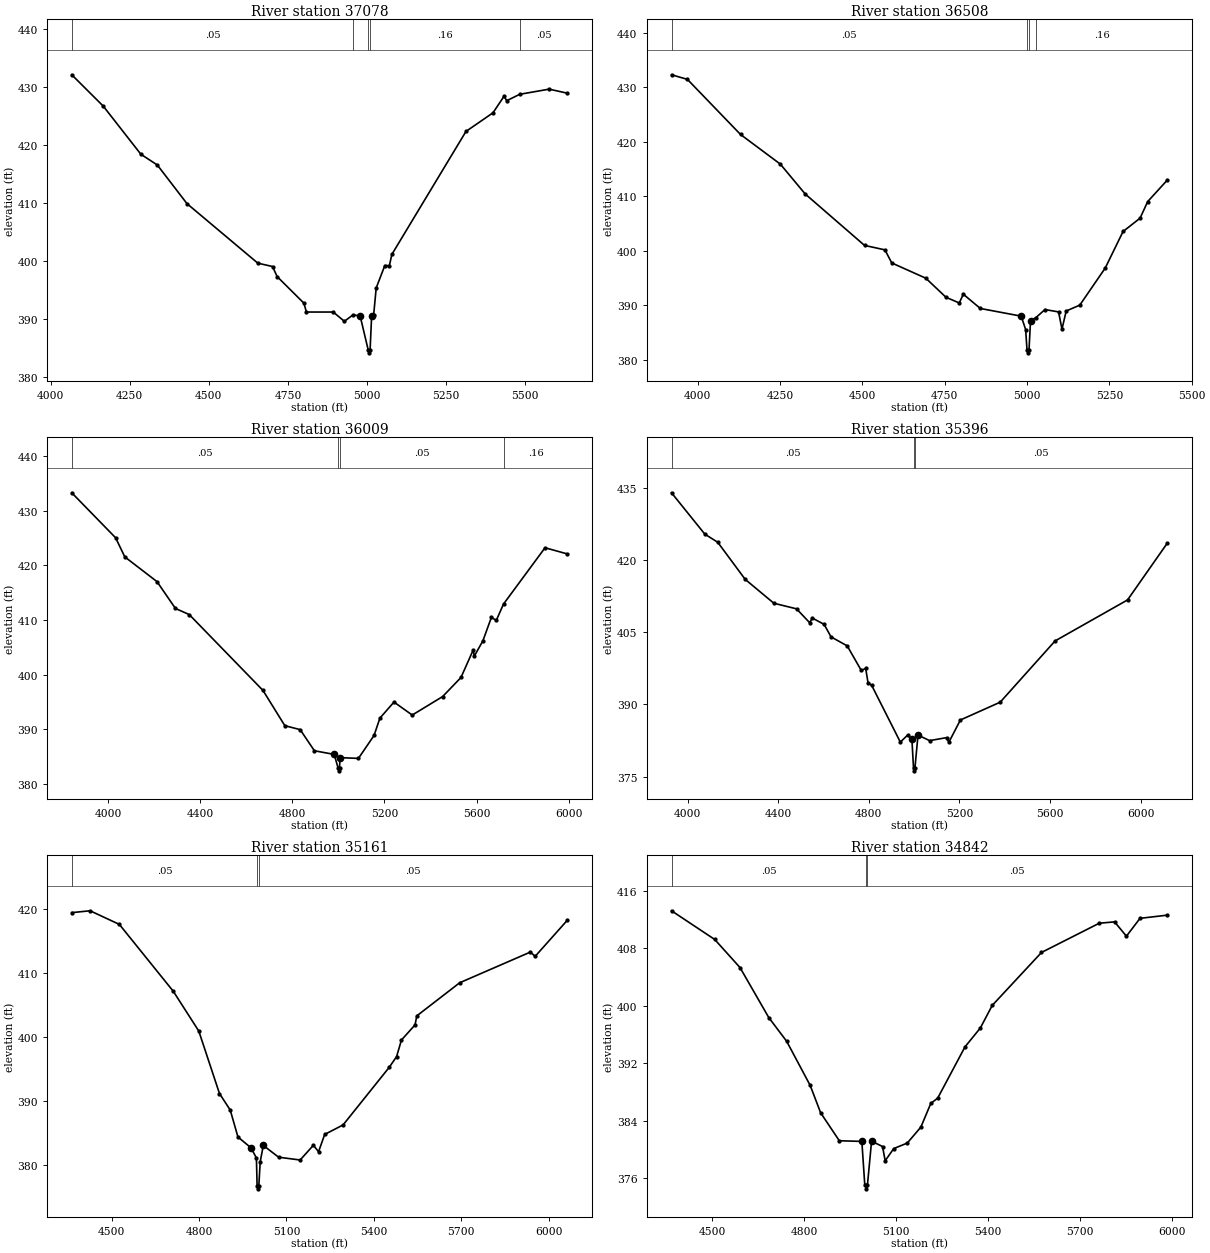
Type RM Length L Ch R = 1 ,37078   ,570,570,570
BEGIN DESCRIPTION:
HAMMOND CREEK 63.0
END DESCRIPTION:
XS GIS Cut Line= 3
      3833167.44     10511253.86      3832549.42     10511371.91
      3831820.28     10511962.17
#Sta/Elev= 30
  4066.5  432.17  4166.1  426.76    4285  418.46  4337.1   416.6  4430.8  409.94
  4654.8  399.67  4701.4  399.09  4715.8  397.36  4800.5  392.77  4808.5  391.24
  4893.2  391.24  4928.4  389.64  4956.6  390.78  4978.5  390.52  5003.8   384.7
  5006.5   384.2  5009.8   384.7  5014.7  390.62  5021.1  390.77  5029.1  395.39
  5056.3  399.26  5070.7  399.24  5078.7  401.19    5313   422.4  5398.4  425.61
  5433.6  428.49  5441.6  427.69  5482.8   428.8  5575.9  429.69  5633.8  428.99
#Mann= 5 ,-1 , 0
  4066.5     .05       0  4956.6     .16       0  5003.8     .07       0
  5009.8     .16       0  5482.8     .05       0
Bank Sta=4978.5,5014.7
XS Rating Curve= 0 ,0
Exp/Cntr=0.3,0.1

Type RM Length L Ch R = 1 ,36508   ,499,499,499
BEGIN DESCRIPTION:
HAMMOND CREEK 62.0
END DESCRIPTION:
XS GIS Cut Line= 3
      3833156.18     10510881.46      3832099.61     10511160.19
      3831699.64     10511260.18
#Sta/Elev= 30
  3920.7  432.32  3968.9  431.48  4130.2  421.37  4251.1  415.93  4326.5  410.46
  4506.7  401.02  4568.7   400.2  4589.4   397.8  4692.8     395  4754.1   391.5
  4794.4  390.46  4806.6  392.07  4858.3  389.45  4982.4  388.04  4995.9  385.59
  5000.1  381.81  5002.8  381.31  5006.1  381.81  5010.8  387.23  5026.8  387.76
  5054.6  389.25  5095.9  388.82  5106.2  385.66  5119.1  388.99  5160.3  390.06
  5237.6  396.87  5291.7  403.57  5343.3  406.01  5366.5  409.06  5425.7  412.98
#Mann= 4 ,-1 , 0
  3920.7     .05       0  5000.1     .04       0  5006.1     .05       0
  5026.8     .16       0
Bank Sta=4982.4,5010.8
XS Rating Curve= 0 ,0
Exp/Cntr=0.3,0.1

Type RM Length L Ch R = 1 ,36009   ,613,613,613
BEGIN DESCRIPTION:
HAMMOND CREEK 61.0
END DESCRIPTION:
XS GIS Cut Line= 4
      3833150.15     10510588.93       3832329.8     10510597.61
      3831670.08     10510836.32       3831344.6     10511378.79
#Sta/Elev= 30
  3840.7  433.32  4031.2  425.08  4071.3  421.57  4211.3  417.04  4291.3  412.13
  4351.3  411.01  4671.9  397.11  4766.9  390.65  4833.5  389.93  4895.3  386.06
  4981.5  385.39  4998.5  382.88  5001.2  382.38  5004.5  382.88  5006.8   384.8
  5086.7  384.66  5154.7  388.86    5180  392.03  5241.3  394.98  5320.6   392.6
  5452.9  395.99  5532.5  399.48    5585  404.46  5590.9  403.43  5627.8   406.2
  5664.7  410.49  5686.1  409.95  5717.5  412.94  5897.9  423.25  5995.3  422.11
#Mann= 4 ,-1 , 0
  3840.7     .05       0  4998.5     .03       0  5004.5     .05       0
  5717.5     .16       0
Bank Sta=4981.5,5006.8
XS Rating Curve= 0 ,0
Exp/Cntr=0.3,0.1

Type RM Length L Ch R = 1 ,35396   ,235,235,235
BEGIN DESCRIPTION:
HAMMOND CREEK 60.0
END DESCRIPTION:
XS GIS Cut Line= 3
      3832959.11      10510309.4      3832334.14     10510101.08
      3830834.35     10510399.65
#Sta/Elev= 30
  3929.2  433.97  4076.3  425.37  4133.2  423.69  4254.5  415.97    4381  411.01
  4481.1  409.85  4539.1  406.96  4550.6  407.94  4602.8  406.62  4633.4  404.02
  4704.8  402.15  4766.9  397.04  4786.3  397.47  4796.5  394.52  4812.9  393.93
  4939.3  382.15  4971.3   383.6  4990.3  382.75  4997.5  376.68  5000.2  376.18
  5003.5  376.68  5017.3  383.61  5068.4  382.46  5143.2  383.08  5153.4  382.12
  5204.4  386.75  5380.1  390.45  5622.4  403.18  5942.2   411.7  6117.2  423.47
#Mann= 3 ,-1 , 0
  3929.2     .05       0  4997.5     .03       0  5003.5     .05       0
Bank Sta=4990.3,5017.3
XS Rating Curve= 0 ,0
Exp/Cntr=0.3,0.1

Type RM Length L Ch R = 1 ,35161   ,319,319,319
BEGIN DESCRIPTION:
HAMMOND CREEK 59.0
END DESCRIPTION:
XS GIS Cut Line= 2
      3832483.44     10509785.11      3830868.89     10510319.82
#Sta/Elev= 30
  4363.5  419.45  4426.4  419.74  4526.8  417.61  4711.8  407.15  4799.4  400.92
  4870.3  391.15  4907.3  388.56  4933.7  384.35  4978.5  382.66  4997.1  381.06
  4999.4  376.74  5002.1  376.24  5005.4  376.74  5010.1  380.48  5020.7  383.03
  5073.3  381.19  5147.1  380.75  5192.6  383.06  5210.3  382.04  5231.3  384.75
  5294.5  386.24  5452.6  395.24    5478  396.92  5494.7  399.52  5541.4  401.89
  5547.4   403.3  5694.6  408.48  5937.1  413.28  5953.5  412.61  6064.3  418.28
#Mann= 3 ,-1 , 0
  4363.5     .05       0  4999.4     .03       0  5005.4     .05       0
Bank Sta=4978.5,5020.7
XS Rating Curve= 0 ,0
Exp/Cntr=0.3,0.1

Type RM Length L Ch R = 1 ,34842   ,843,843,843
BEGIN DESCRIPTION:
HAMMOND CREEK 58.0
END DESCRIPTION:
XS GIS Cut Line= 3
      3832330.63     10509601.08      3832070.26     10509594.13
      3830863.77     10510214.71
#Sta/Elev= 30
  4366.8  413.19  4507.9   409.2  4590.3   405.3  4684.2  398.35  4742.5  395.06
  4819.2  388.93  4853.4  385.12  4914.3  381.24  4987.8  381.15  4997.3  375.14
    5000  375.06  5002.7  374.56    5006  375.06  5019.5  381.18  5055.3  380.44
  5063.9  378.46  5091.7  380.15    5136  380.92  5180.4  383.14  5212.7  386.42
  5235.2  387.16  5324.4  394.29  5374.3   396.9  5413.1  400.04  5573.9   407.4
  5762.3  411.46  5812.3  411.65    5851  409.66  5895.3  412.14    5984  412.58
#Mann= 3 ,-1 , 0
  4366.8     .05       0    5000     .03       0    5006     .05       0
Bank Sta=4987.8,5019.5
XS Rating Curve= 0 ,0
Exp/Cntr=0.3,0.1

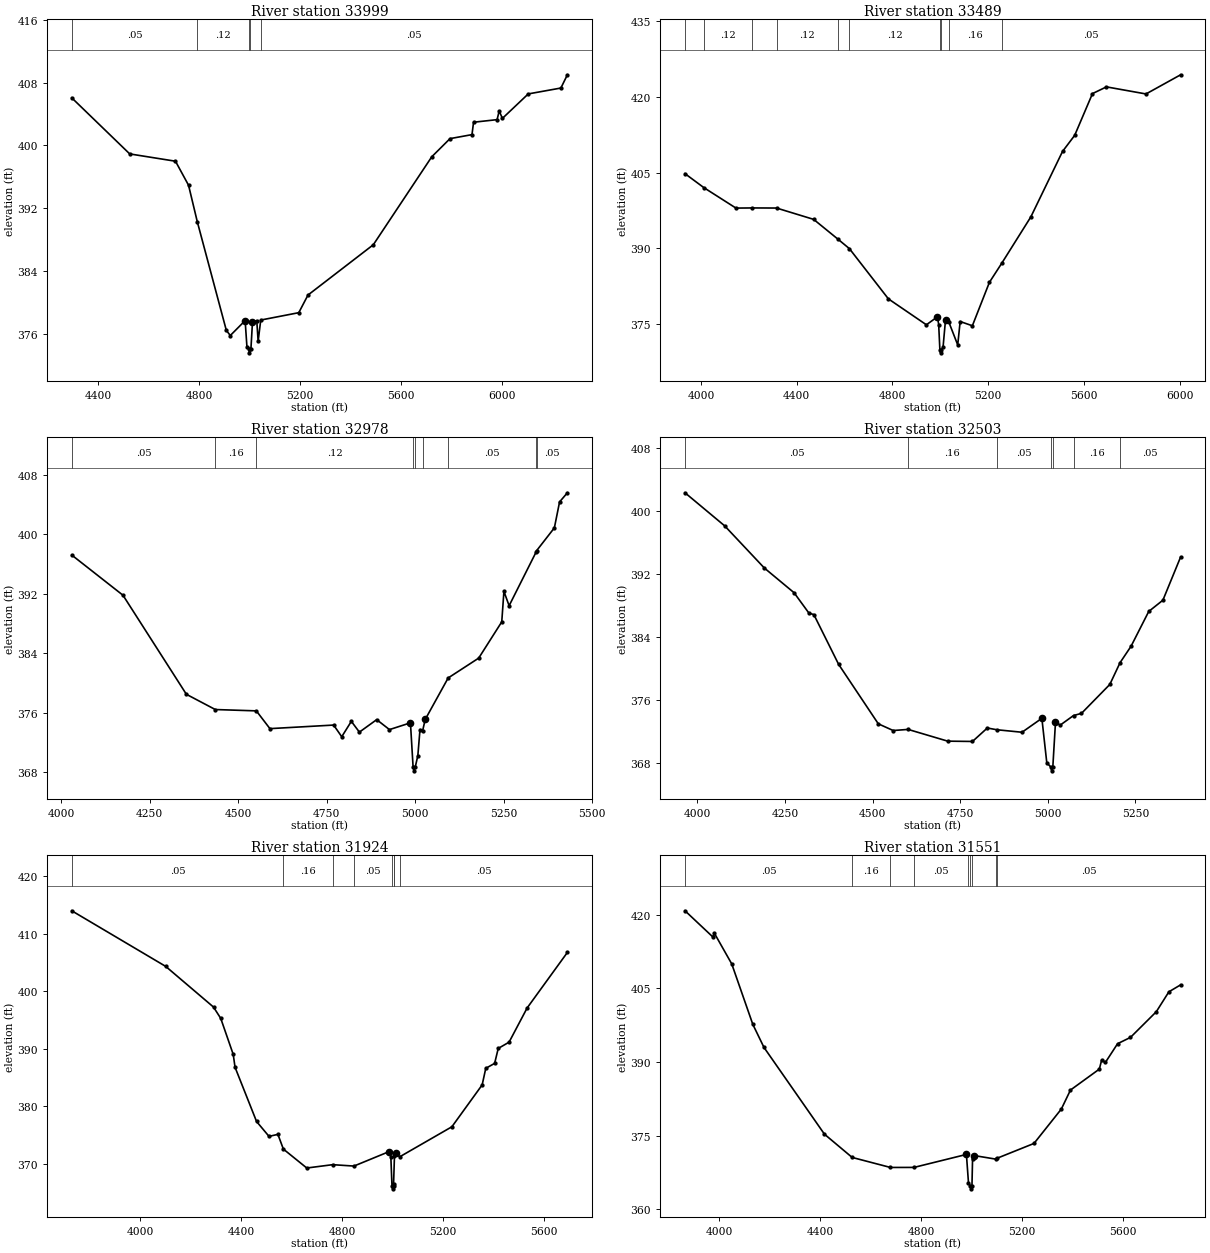
Type RM Length L Ch R = 1 ,33999   ,510,510,510
BEGIN DESCRIPTION:
HAMMOND CREEK 57.0
END DESCRIPTION:
XS GIS Cut Line= 4
      3832257.71     10509212.18       3831702.2     10509142.75
      3831375.81     10509292.05      3830800.04     10510166.11
#Sta/Elev= 30
    4294  406.06  4523.9  398.91  4705.3  397.98  4757.1  394.92  4791.6  390.29
    4907  376.41  4922.7  375.76  4981.5  377.66  4988.6  374.34    4996  374.05
  4998.8  373.55    5002  374.05  5004.5  374.08  5010.6  377.44  5027.6  377.66
  5033.1  375.03  5043.4  377.73  5194.2  378.67  5230.8  380.92  5489.8  387.33
  5721.7  398.55    5794  400.86  5881.1  401.37  5887.3  402.95  5980.7  403.28
  5988.9  404.39  6001.7  403.44  6104.2  406.56  6233.6  407.31  6259.4     409
#Mann= 5 ,-1 , 0
    4294     .05       0  4791.6     .12       0    4996     .07       0
    5002     .12       0  5043.4     .05       0
Bank Sta=4981.5,5010.6
XS Rating Curve= 0 ,0
Exp/Cntr=0.3,0.1

Type RM Length L Ch R = 1 ,33489   ,511,511,511
BEGIN DESCRIPTION:
HAMMOND CREEK 56.0
END DESCRIPTION:
XS GIS Cut Line= 4
      3832313.35     10509097.62      3831747.34     10508840.66
      3831011.23      10508986.5      3830324.12     10509111.42
#Sta/Elev= 30
  3933.4  404.77  4011.9  402.02  4146.2  397.97  4213.5     398  4315.8  397.98
  4470.8  395.74  4571.5  391.86  4620.1  389.96  4783.1  380.03  4941.8  374.91
    4988   376.5  4993.1  374.94  4998.2  369.87    5001  369.37  5004.2  369.87
  5011.4  370.52  5021.6  375.88  5035.7  375.42  5072.6  370.94  5082.8  375.56
  5133.8  374.72  5205.1  383.31  5256.8  387.09  5378.2  396.24  5510.4  409.16
  5561.2  412.34  5635.5  420.59  5693.9  421.92  5859.1  420.52  6003.8  424.31
#Mann= 10 ,-1 , 0
  3933.4     .05       0  4011.9     .12       0  4213.5     .16       0
  4315.8     .12       0  4571.5     .16       0  4620.1     .12       0
  4998.2     .07       0  5004.2     .12       0  5035.7     .16       0
  5256.8     .05       0
Bank Sta=4988,5021.6
XS Rating Curve= 0 ,0
Exp/Cntr=0.3,0.1

Type RM Length L Ch R = 1 ,32978   ,475,475,475
BEGIN DESCRIPTION:
HAMMOND CREEK 55.0
END DESCRIPTION:
XS GIS Cut Line= 3
       3831599.6     10507760.21      3831049.61     10508560.19
      3830699.63     10508810.18
#Sta/Elev= 30
  4029.6  397.23  4174.4  391.82  4353.6  378.49  4435.3  376.44  4551.3  376.26
  4589.7  373.87  4769.8  374.35  4792.7  372.78  4819.8  374.85  4842.6   373.4
  4891.5  375.08  4927.6  373.74  4986.9  374.65  4994.4  368.69  4997.1  368.19
  5000.4  368.69  5007.8  370.23  5013.9  373.75  5021.2  373.56  5028.7  375.11
  5093.5  380.69  5179.8  383.36    5245  388.24  5251.1  392.34  5265.8  390.41
  5341.7   397.6  5343.2   397.8  5393.7  400.89  5408.4  404.38  5430.5  405.61
#Mann= 9 ,-1 , 0
  4029.6     .05       0  4435.3     .16       0  4551.3     .12       0
  4994.4     .07       0  5000.4     .12       0  5021.2     .16       0
  5093.5     .05       0  5341.7     .16       0  5343.2     .05       0
Bank Sta=4986.9,5028.7
XS Rating Curve= 0 ,0
Exp/Cntr=0.3,0.1

Type RM Length L Ch R = 1 ,32503   ,579,579,579
BEGIN DESCRIPTION:
HAMMOND CREEK 54.0
END DESCRIPTION:
XS GIS Cut Line= 3
      3831549.64     10507460.16      3830799.61     10508210.19
      3830449.57     10508260.19
#Sta/Elev= 30
  3964.5  402.26  4077.7  398.06  4190.8  392.71  4275.7  389.57  4318.1  386.98
  4332.2  386.79  4402.9  380.47  4516.1  372.92  4558.5  372.07  4601.1  372.21
  4714.1  370.72  4784.8  370.68  4827.2  372.39    4854  372.17  4926.2  371.85
  4982.8  373.62  4996.9  367.97  5008.1  367.45  5010.8  366.95  5014.1  367.45
  5021.7  373.13  5035.3  372.76  5073.1  373.97  5095.9  374.25  5176.7  377.92
    5206  380.69  5237.3  382.77  5287.8  387.19  5328.2  388.62  5378.8  394.11
#Mann= 7 ,-1 , 0
  3964.5     .05       0  4601.1     .16       0    4854     .05       0
  5008.1     .03       0  5014.1     .05       0  5073.1     .16       0
    5206     .05       0
Bank Sta=4982.8,5021.7
XS Rating Curve= 0 ,0
Exp/Cntr=0.3,0.1

Type RM Length L Ch R = 1 ,31924   ,373,373,373
BEGIN DESCRIPTION:
HAMMOND CREEK 53.0
END DESCRIPTION:
XS GIS Cut Line= 3
      3831411.63     10506786.49      3831297.05     10507307.33
      3830198.07     10508224.01
#Sta/Elev= 30
  3727.7  413.98  4100.1  404.31  4289.5  397.24  4318.2  395.27  4367.6  389.02
  4374.9  386.77  4460.1  377.35  4509.5  374.76  4544.7  375.11  4566.4  372.55
  4659.2  369.26  4761.7  369.84  4846.2   369.6  4985.9  372.12  4992.4  371.21
  4996.9  366.14  4999.7  365.64  5002.9  366.14  5003.2  366.55  5006.7  371.29
  5013.2  371.79  5027.6  371.21  5234.3  376.43  5354.3  383.71  5368.6  386.59
  5403.7  387.45    5418  390.05    5461  391.14  5532.6  397.09  5692.1  406.74
#Mann= 8 ,-1 , 0
  3727.7     .05       0  4566.4     .16       0  4761.7     .07       0
  4846.2     .05       0  4996.9     .03       0  5002.9     .05       0
  5003.2     .16       0  5027.6     .05       0
Bank Sta=4985.9,5013.2
XS Rating Curve= 0 ,0
Exp/Cntr=0.3,0.1

Type RM Length L Ch R = 1 ,31551   ,583,583,583
BEGIN DESCRIPTION:
HAMMOND CREEK 52.0
END DESCRIPTION:
XS GIS Cut Line= 4
      3831130.38     10506614.62      3830864.76     10507432.33
      3830416.84     10507609.41      3830073.84     10508129.11
#Sta/Elev= 30
  3863.9  420.76  3974.7  415.41  3979.9  416.23  4049.1  409.95  4132.6  397.65
  4176.9  392.95  4416.5   375.3  4526.3  370.57  4678.1  368.53  4771.3  368.54
  4979.1  371.18  4987.2  365.46    4995  364.68  4997.8  364.18    5001  364.68
  5003.4  370.16  5008.8  370.96  5095.1  370.23  5099.4  370.38  5246.9  373.42
  5355.3  380.42  5391.4  384.28  5505.8  388.54  5514.9  390.36  5529.8   389.9
  5578.1  393.71  5629.3     395  5731.6  400.22  5781.4  404.27    5828  405.69
#Mann= 9 ,-1 , 0
  3863.9     .05       0  4526.3     .16       0  4678.1     .07       0
  4771.3     .05       0  4987.2     .07       0    4995     .07       0
    5001     .07       0  5095.1     .16       0  5099.4     .05       0
Bank Sta=4979.1,5008.8
XS Rating Curve= 0 ,0
Exp/Cntr=0.3,0.1

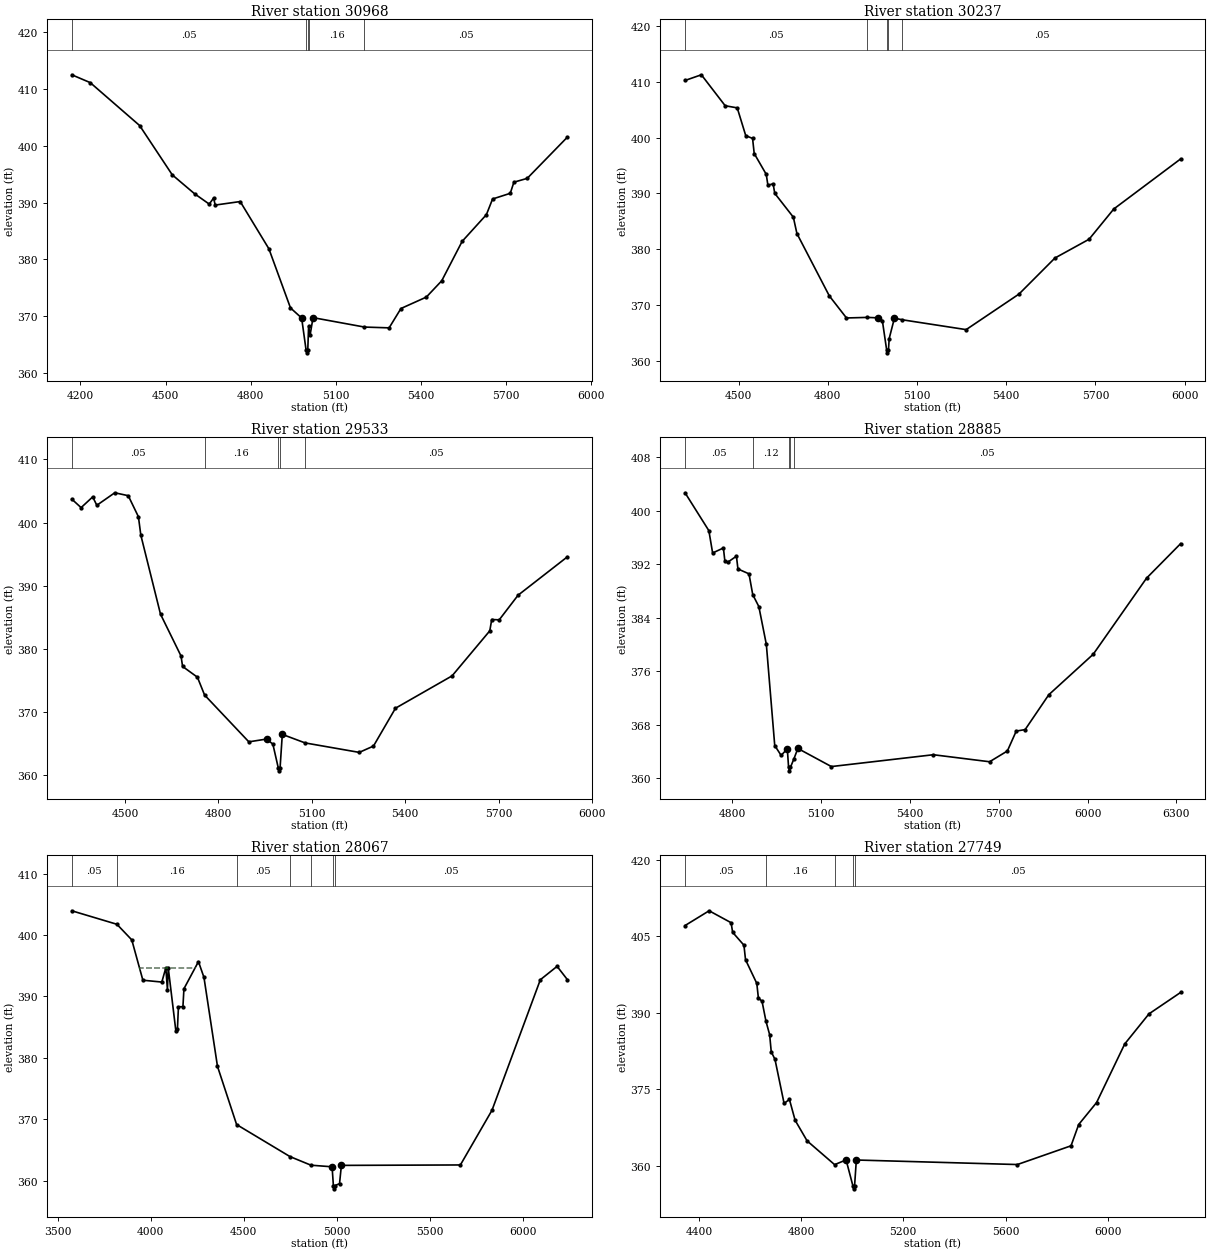
Type RM Length L Ch R = 1 ,30968   ,731,731,731
BEGIN DESCRIPTION:
HAMMOND CREEK 51.0
END DESCRIPTION:
XS GIS Cut Line= 4
      3830854.34     10506505.24      3830500.17     10507062.54
      3830406.42     10507130.25       3830052.5     10508035.89
#Sta/Elev= 30
  4169.3  412.52  4234.4  411.14  4408.7  403.58  4523.9  394.89  4602.6  391.56
  4654.3  389.74  4669.5   390.8  4675.5  389.57  4763.5  390.19  4864.7  381.87
  4940.9  371.45  4980.2  369.68  4995.9  364.04  4998.6  363.54  5001.9  364.04
  5004.8  368.25  5010.1  366.67  5020.4  369.74  5201.9  368.08  5288.8  367.94
  5330.6  371.35  5420.1  373.36  5474.4  376.23  5546.4  383.17    5632  387.88
  5653.8  390.64  5716.2  391.64    5729   393.6  5775.9  394.27  5917.6  401.53
#Mann= 5 ,-1 , 0
  4169.3     .05       0  4995.9     .03       0  5001.9     .05       0
  5004.8     .16       0  5201.9     .05       0
Bank Sta=4980.2,5020.4
XS Rating Curve= 0 ,0
Exp/Cntr=0.3,0.1

Type RM Length L Ch R = 1 ,30237   ,704,704,704
BEGIN DESCRIPTION:
HAMMOND CREEK 50.0
END DESCRIPTION:
XS GIS Cut Line= 2
      3830349.15     10506348.96      3829656.41     10507864.66
#Sta/Elev= 30
  4320.1  410.22    4375  411.24  4455.1  405.69  4495.6  405.31  4524.2  400.34
  4547.2  399.83  4552.7  397.13  4593.2   393.4  4598.7  391.46  4616.3  391.69
  4621.8  389.99  4684.3  385.72  4696.3  382.79  4805.2  371.62    4863  367.66
  4932.9  367.76  4970.1  367.68  4983.6  367.19  4998.1  361.91  5000.9  361.41
  5004.1  361.91  5006.6  363.97  5024.1  367.62    5051  367.33  5265.4  365.57
    5443  371.94  5563.9   378.4  5678.8  381.77  5761.8  387.19  5986.6  396.16
#Mann= 5 ,-1 , 0
  4320.1     .05       0  4932.9     .16       0  4998.1     .07       0
  5004.1     .16       0    5051     .05       0
Bank Sta=4970.1,5024.1
XS Rating Curve= 0 ,0
Exp/Cntr=0.3,0.1

Type RM Length L Ch R = 1 ,29533   ,648,648,648
BEGIN DESCRIPTION:
HAMMOND CREEK 49.0
END DESCRIPTION:
XS GIS Cut Line= 2
      3829854.34     10506260.49      3829630.62     10507836.89
#Sta/Elev= 30
  4328.6  403.71  4358.6  402.36  4395.9  404.06  4409.1  402.73  4466.8  404.71
  4510.1  404.25  4542.8  400.91  4550.5     398  4613.7   385.5  4679.6  378.88
  4684.7  377.22  4732.3  375.52  4755.3   372.7  4897.5  365.29  4954.5  365.73
  4974.7  364.93  4991.9   361.2  4994.7   360.7  4997.9   361.2    5005  366.47
  5078.2  365.12  5252.2  363.62  5297.9  364.62  5368.6  370.61  5550.4  375.73
  5671.6  382.86  5677.8  384.65  5701.9   384.6  5762.5   388.5  5920.8  394.57
#Mann= 5 ,-1 , 0
  4328.6     .05       0  4755.3     .16       0  4991.9     .07       0
  4997.9     .16       0  5078.2     .05       0
Bank Sta=4954.5,5005
XS Rating Curve= 0 ,0
Exp/Cntr=0.3,0.1

Type RM Length L Ch R = 1 ,28885   ,818,818,818
BEGIN DESCRIPTION:
HAMMOND CREEK 48.0
END DESCRIPTION:
XS GIS Cut Line= 4
      3829802.27     10506229.16      3829750.17     10506468.79
      3829416.84     10506822.95      3829406.43     10507765.41
#Sta/Elev= 30
  4640.3  402.72  4720.8  397.05  4733.5  393.71  4769.9  394.46    4775  392.45
  4784.6  392.33  4813.9  393.23    4819  391.32  4856.3  390.59    4869  387.48
  4889.6  385.69    4915  380.02  4943.3   364.9  4964.8  363.42  4985.8   364.4
  4990.1  361.61  4992.9  361.11  4996.1  361.61  5007.8  362.87  5021.4  364.46
  5134.6  361.75  5479.1  363.52  5669.1  362.47  5729.1  364.08  5759.1  367.06
  5789.1  367.28  5869.1   372.5  6019.2  378.56  6199.2  389.94  6314.4  395.11
#Mann= 5 ,-1 , 0
  4640.3     .05       0    4869     .12       0  4990.1     .07       0
  4996.1     .12       0  5007.8     .05       0
Bank Sta=4985.8,5021.4
XS Rating Curve= 0 ,0
Exp/Cntr=0.3,0.1

Type RM Length L Ch R = 1 ,28067   ,318,318,318
BEGIN DESCRIPTION:
HAMMOND CREEK 47.0
END DESCRIPTION:
XS GIS Cut Line= 3
      3830229.35     10505822.95      3829161.63     10506250.04
      3829172.05     10507765.44
#Sta/Elev= 30
  3575.2  403.94  3818.1  401.74    3898   399.2  3957.7  392.63  4059.6  392.33
  4081.1  394.65  4089.7   391.1 4093.94  394.69    4135  384.39  4143.5  384.66
  4148.9  388.29  4173.1  388.33  4178.5  391.24  4256.6  395.66  4286.2  393.09
  4358.9   378.6  4461.8  369.12    4749   363.9  4861.8   362.5  4975.3  362.24
  4982.3  359.15  4985.1  358.65  4988.3  359.15  5015.3   359.5  5025.3  362.47
  5665.3  362.54  5835.3  371.45  6095.3  392.71  6185.4  394.89  6240.6  392.73
#Mann= 7 ,-1 , 0
  3575.2     .05       0  3818.1     .16       0  4461.8     .05       0
    4749     .16       0  4861.8     .05       0  4982.3     .03       0
  4988.3     .05       0
#XS Ineff= 1 ,-1
 3942.74    4245  394.69
Permanent Ineff=
       F
Bank Sta=4975.3,5025.3
XS Rating Curve= 0 ,0
Exp/Cntr=0.3,0.1

Type RM Length L Ch R = 1 ,27749   ,489,489,489
BEGIN DESCRIPTION:
HAMMOND CREEK 46.0
END DESCRIPTION:
XS GIS Cut Line= 4
       3828698.1     10505890.68      3828979.34     10506281.29
      3829000.17     10507437.54      3829145.29     10507701.86
#Sta/Elev= 30
  4345.9  407.14  4440.2  410.04  4526.1   407.7  4532.2  405.81  4576.4  403.28
  4582.6  400.43  4626.7  395.78  4632.9  392.93  4647.2  392.27  4662.7  388.33
    4677  385.71  4683.2  382.36  4697.9  380.86  4733.5  372.22  4754.4     373
  4776.6  368.92  4823.5  364.87  4931.2   360.2  4976.1  361.13  5003.2  355.95
  5005.9  355.45  5009.2  355.95  5016.2  361.11  5646.3  360.22  5856.3   363.9
  5886.3  368.08  5956.3  372.39  6066.5   383.9  6161.3   389.8  6285.2  394.01
#Mann= 5 ,-1 , 0
  4345.9     .05       0  4662.7     .16       0  4931.2     .05       0
  5003.2     .03       0  5009.2     .05       0
Bank Sta=4976.1,5016.2
XS Rating Curve= 0 ,0
Exp/Cntr=0.3,0.1

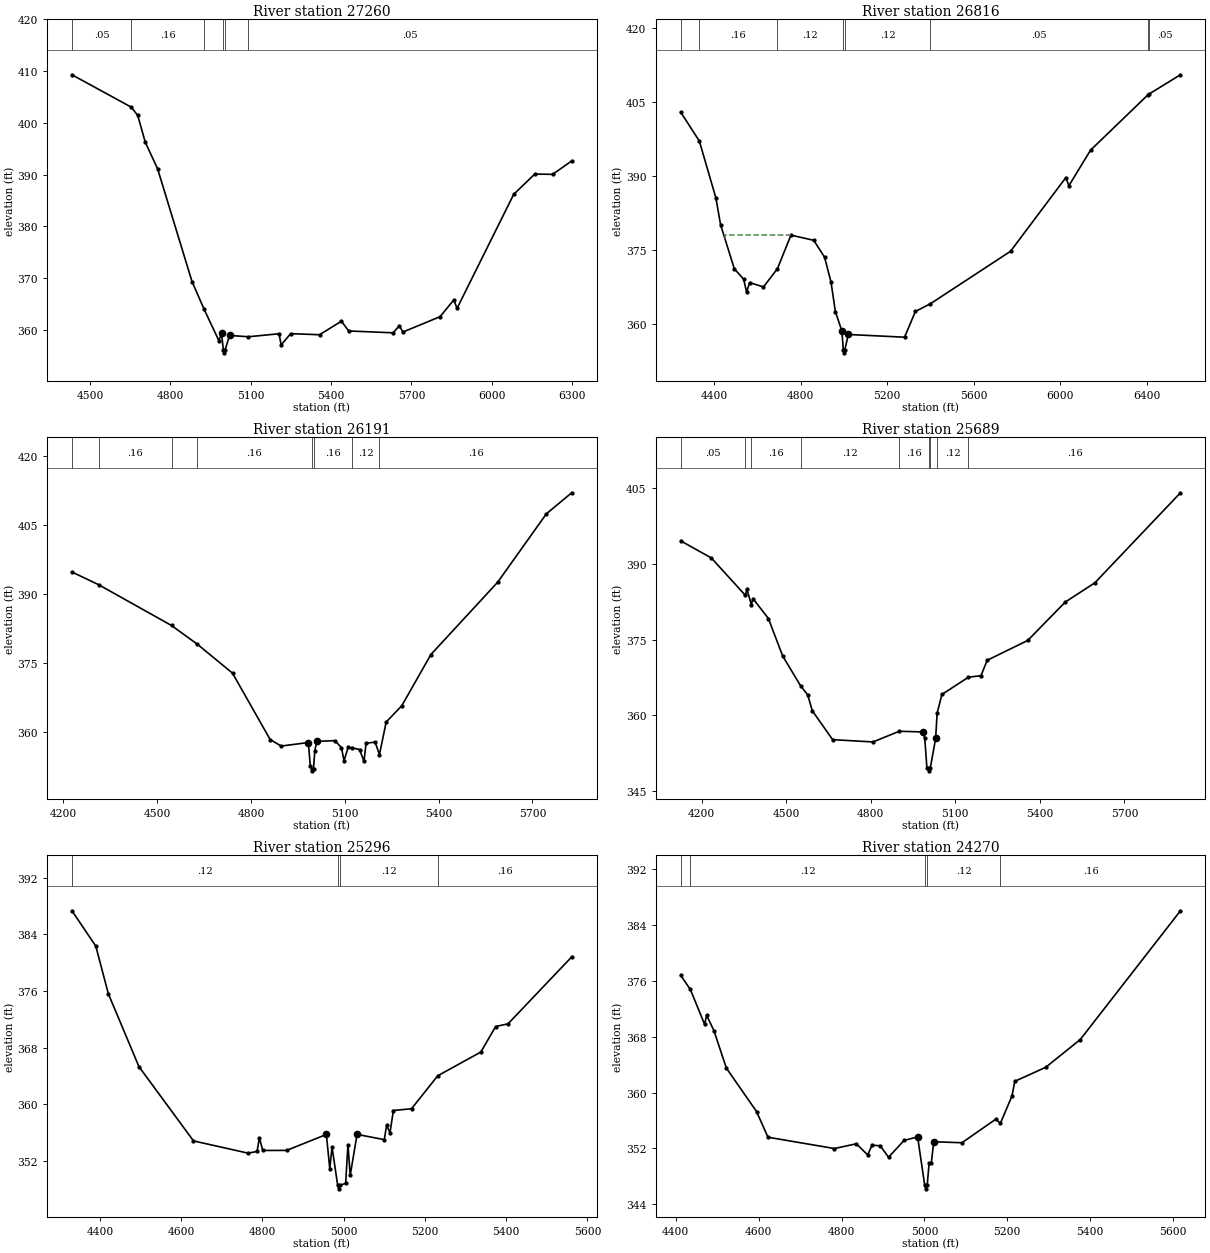
Type RM Length L Ch R = 1 ,27260   ,444,444,444
BEGIN DESCRIPTION:
HAMMOND CREEK 45.0
END DESCRIPTION:
XS GIS Cut Line= 4
      3828718.93     10506093.77      3828531.42     10506494.83
      3828531.42     10506817.75      3829130.37     10507739.61
#Sta/Elev= 30
  4433.1   409.3  4654.1  403.05  4678.5  401.45  4706.8  396.24  4752.5  391.15
  4881.2  369.31  4926.3  363.96  4981.2  357.91  4991.2  359.29  4998.2  356.04
  5000.9  355.54  5004.2  356.04  5021.2  358.91  5091.2  358.65  5206.1  359.23
  5213.6  357.07  5249.4  359.25    5357  359.04  5438.7  361.65  5465.8  359.77
  5631.8  359.41  5654.8  360.78  5668.1  359.56  5807.1  362.54  5857.6  365.75
  5870.4  364.16  6081.9  386.21  6160.3   390.1  6226.9  390.05  6298.1  392.64
#Mann= 6 ,-1 , 0
  4433.1     .05       0  4654.1     .16       0  4926.3     .12       0
  4998.2     .07       0  5004.2     .12       0  5091.2     .05       0
Bank Sta=4991.2,5021.2
XS Rating Curve= 0 ,0
Exp/Cntr=0.3,0.1

Type RM Length L Ch R = 1 ,26816   ,625,625,625
BEGIN DESCRIPTION:
HAMMOND CREEK 44.0
END DESCRIPTION:
XS GIS Cut Line= 3
      3828590.21     10506210.47      3828201.33      10506654.9
       3828263.8     10508376.12
#Sta/Elev= 30
    4244  402.97  4330.2  397.12    4407  385.56  4428.9   380.1  4492.5  371.19
  4535.2  369.13  4549.2  366.46  4562.7  368.42  4627.2  367.54  4691.8  371.24
  4754.4  378.04  4859.9  376.99  4909.9  373.57  4939.9  368.49  4959.9  362.53
  4989.9  358.64  4996.9  354.68  4999.7  354.18  5002.9  354.68    5020   357.9
  5280.1  357.35  5330.2  362.56  5400.1  364.14  5770.5  374.76  6026.7  389.71
  6040.6  388.05  6140.7  395.25  6406.5  406.47  6409.2  406.57  6556.9  410.54
#Mann= 8 ,-1 , 0
    4244     .05       0  4330.2     .16       0  4691.8     .12       0
  4996.9     .07       0  5002.9     .12       0  5400.1     .05       0
  6406.5     .16       0  6409.2     .05       0
#XS Ineff= 1 ,-1
    4449  4754.4     378
Permanent Ineff=
       F
Bank Sta=4989.9,5020
XS Rating Curve= 0 ,0
Exp/Cntr=0.3,0.1

Type RM Length L Ch R = 1 ,26191   ,502,502,502
BEGIN DESCRIPTION:
HAMMOND CREEK 43.0
END DESCRIPTION:
XS GIS Cut Line= 2
      3828361.05     10506161.84      3827382.07     10507425.49
#Sta/Elev= 30
  4227.2  394.78  4313.1     392  4545.6  383.17  4627.8  379.13  4740.7  372.83
  4861.1  358.43  4896.4  357.01  4983.3  357.77  4989.6  352.62  4993.8  352.13
  4996.5  351.63  4999.8  352.13  5004.1  356.04  5010.4  358.02  5068.4  358.18
  5089.2  356.67  5097.4  353.83  5110.6   356.7  5122.5  356.62  5147.2  356.26
  5161.2  353.69    5168  357.63    5197  357.86  5210.7  355.16  5232.3  362.23
  5282.1  365.75  5375.3  376.87    5589  392.57  5744.7  407.41  5825.7  411.97
#Mann= 8 ,-1 , 0
  4227.2     .05       0  4313.1     .16       0  4545.6     .12       0
  4627.8     .16       0  4993.8     .07       0  4999.8     .16       0
  5122.5     .12       0  5210.7     .16       0
Bank Sta=4983.3,5010.4
XS Rating Curve= 0 ,0
Exp/Cntr=0.3,0.1

Type RM Length L Ch R = 1 ,25689   ,393,393,393
BEGIN DESCRIPTION:
HAMMOND CREEK 42.0
END DESCRIPTION:
XS GIS Cut Line= 2
      3828326.31     10506099.36      3826749.97     10506911.83
#Sta/Elev= 30
  4125.4   394.5  4234.2  391.12  4355.1  383.72    4360  384.99  4376.1  381.92
  4382.1  383.07  4436.7  379.15  4487.3  371.75  4551.8  365.77    4576  364.08
  4592.5  360.92  4664.6  355.21  4807.9  354.76    4901  356.87  4985.9  356.74
  4991.5  355.51  4999.2  349.63    5005  349.55  5007.8  349.05    5011  349.55
  5030.2  355.47  5035.4  360.44  5052.3  364.14  5146.6  367.56    5191  367.85
  5213.1   370.9    5357  374.82    5490   382.4  5595.2  386.21  5898.8     404
#Mann= 9 ,-1 , 0
  4125.4     .05       0  4355.1     .12       0  4376.1     .16       0
  4551.8     .12       0    4901     .16       0    5005     .07       0
    5011     .16       0  5035.4     .12       0  5146.6     .16       0
Bank Sta=4985.9,5030.2
XS Rating Curve= 0 ,0
Exp/Cntr=0.3,0.1

Type RM Length L Ch R = 1 ,25296   ,1026,1026,1026
BEGIN DESCRIPTION:
HAMMOND CREEK 41.0
END DESCRIPTION:
XS GIS Cut Line= 3
      3828099.63     10505860.18      3827499.61     10506160.19
      3826999.58      10506410.2
#Sta/Elev= 30
  4331.4  387.35  4390.1  382.35  4420.9  375.63  4496.3  365.33  4630.5  354.85
  4764.7  353.12    4787  353.36  4792.6  355.27    4801   353.5  4859.7  353.51
  4957.5  355.76  4965.9  350.94  4971.5  353.98  4985.3  348.58    4988  348.08
  4991.3  348.58    5005  348.86  5010.6  354.31  5016.2  349.99    5033  355.77
  5100.1  355.03  5105.7  357.05  5114.1     356  5122.4  359.14  5167.2   359.4
  5231.6  364.05  5337.7   367.4    5374     371  5404.7  371.39  5561.3  380.84
#Mann= 4 ,-1 , 0
  4331.4     .12       0  4985.3     .07       0  4991.3     .12       0
  5231.6     .16       0
Bank Sta=4957.5,5033
XS Rating Curve= 0 ,0
Exp/Cntr=0.3,0.1

Type RM Length L Ch R = 1 ,24270   ,571,571,571
BEGIN DESCRIPTION:
HAMMOND CREEK 40.0
END DESCRIPTION:
XS GIS Cut Line= 3
      3827949.56     10505760.18      3827349.61     10505710.19
       3826799.6     10505960.19
#Sta/Elev= 30
  4411.8  376.78  4435.2  374.75  4469.5  369.76  4474.5  371.05    4492  368.86
  4522.1  363.49  4594.9  357.28  4622.5   353.6    4783  351.98  4835.7  352.66
  4863.3  351.06  4873.3  352.45  4893.4  352.38  4913.5  350.73  4951.1  353.15
  4983.7  353.64  5000.8  346.71  5003.5  346.21  5006.8  346.71  5011.3  349.84
  5016.6  349.84  5022.6  352.95  5090.7  352.81    5172  356.17  5183.6  355.61
  5211.6  359.53  5218.1   361.6  5292.8  363.61  5376.3  367.59    5618  386.02
#Mann= 5 ,-1 , 0
  4411.8     .05       0  4435.2     .12       0  5000.8     .07       0
  5006.8     .12       0  5183.6     .16       0
Bank Sta=4983.7,5022.6
XS Rating Curve= 0 ,0
Exp/Cntr=0.3,0.1

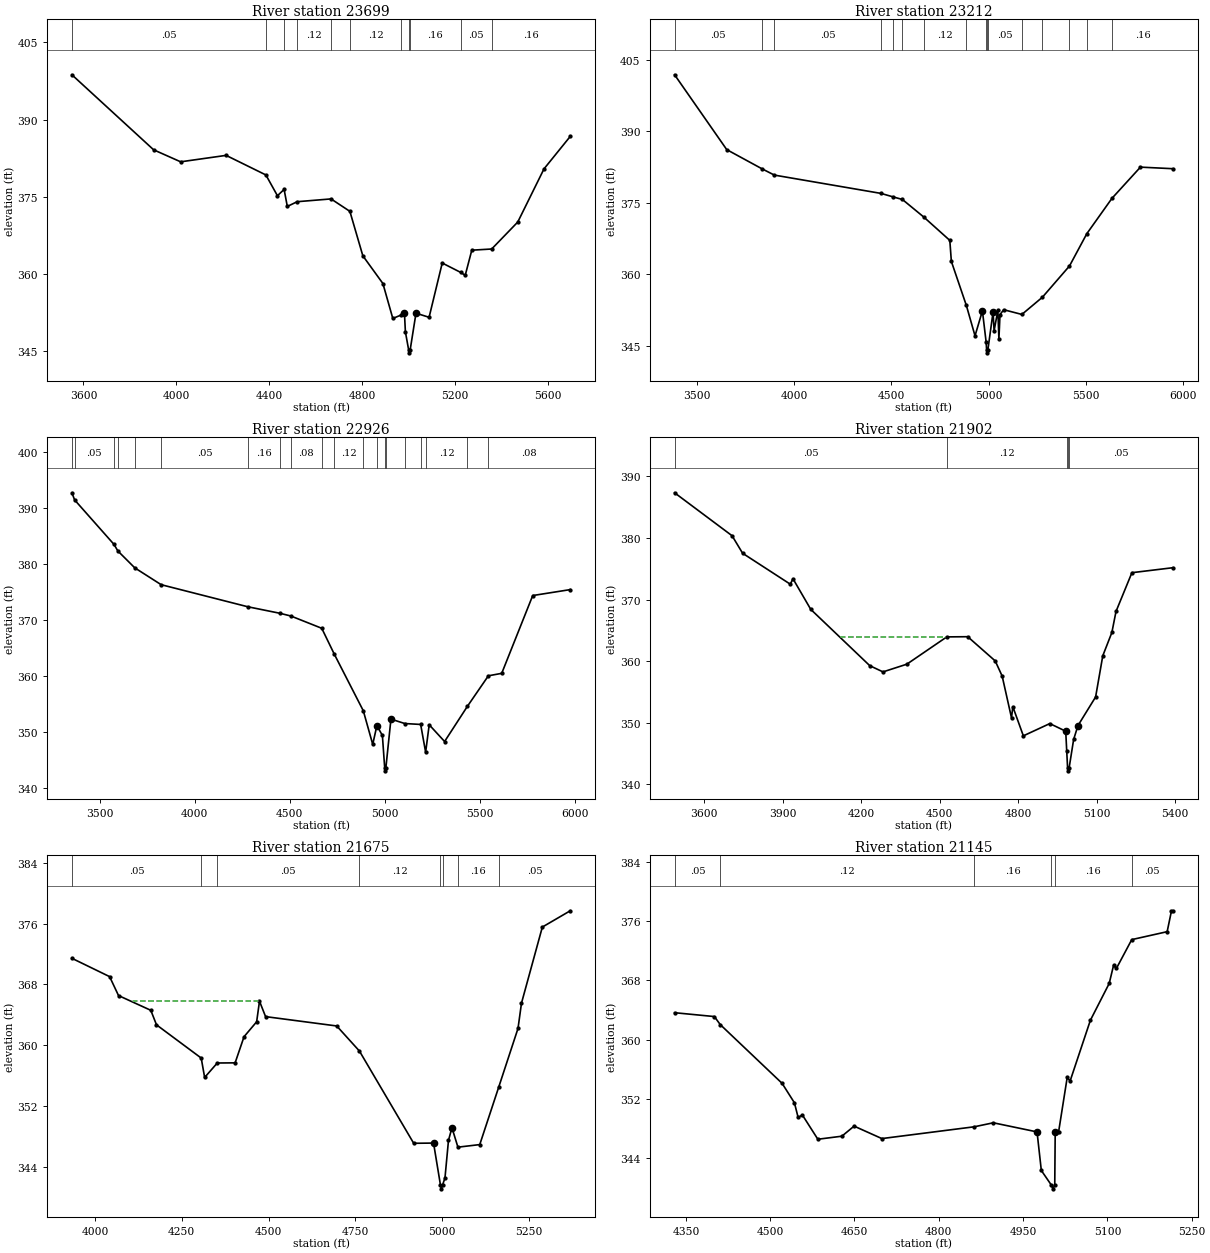
Type RM Length L Ch R = 1 ,23699   ,487,487,487
BEGIN DESCRIPTION:
HAMMOND CREEK 39.0
END DESCRIPTION:
XS GIS Cut Line= 4
      3828467.21     10505876.79      3827449.61     10505260.19
      3827249.61     10505410.19      3826749.64     10505910.16
#Sta/Elev= 30
  3550.5   398.7  3902.6  384.14    4019  381.81  4214.8  383.06  4386.2  379.26
  4435.9  375.23  4464.7  376.45  4478.5  373.15  4521.1  374.07  4666.8  374.61
    4748   372.2  4803.9  363.57  4890.3  358.19    4933  351.41  4968.7  352.08
    4983  352.56  4987.2  348.81  5001.5  345.24  5004.2  344.74  5007.5  345.24
  5032.8  352.43  5089.3  351.64  5145.9  362.17  5225.3  360.35  5244.9  359.78
  5273.2  364.66  5358.9  364.89  5471.2  370.12  5584.3  380.44  5697.4  386.74
#Mann= 11 ,-1 , 0
  3550.5     .05       0  4386.2     .12       0  4464.7     .05       0
  4521.1     .12       0  4666.8     .08       0    4748     .12       0
  4968.7     .16       0  5001.5     .07       0  5007.5     .16       0
  5225.3     .05       0  5358.9     .16       0
Bank Sta=4983,5032.8
XS Rating Curve= 0 ,0
Exp/Cntr=0.3,0.1

Type RM Length L Ch R = 1 ,23212   ,286,286,286
BEGIN DESCRIPTION:
HAMMOND CREEK 38.0
END DESCRIPTION:
XS GIS Cut Line= 4
       3828576.3     10505828.49      3827256.89     10505127.12
       3826930.5     10505002.12      3826293.09     10504669.56
#Sta/Elev= 30
  3385.1  401.82  3653.3  386.13  3833.2  382.14  3898.2  380.79  4446.9  376.95
  4508.8  376.22  4556.6  375.68  4666.4     372  4800.4   367.1  4808.3   362.7
  4885.5  353.46    4930   347.1    4968  352.33  4987.4   345.7  4989.7  344.03
  4992.5  343.53  4995.7  344.03  5022.8  352.09  5028.1  348.16  5047.5  352.45
  5052.8  346.42  5058.5  351.55  5077.5  352.57  5170.9  351.58  5276.3  355.18
  5415.8  361.74  5505.1  368.52  5634.4  375.93  5780.6  382.46  5947.8  382.13
#Mann= 16 ,-1 , 0
  3385.1     .05       0  3833.2     .08       0  3898.2     .05       0
  4446.9     .12       0  4508.8     .05       0  4556.6     .08       0
  4666.4     .12       0  4885.5     .16       0  4987.4     .05       0
  4989.7     .07       0  4995.7     .05       0  5170.9     .05       0
  5276.3      .1       0  5415.8     .16       0  5505.1     .05       0
  5634.4     .16       0
Bank Sta=4968,5022.8
XS Rating Curve= 0 ,0
Exp/Cntr=0.3,0.1

Type RM Length L Ch R = 1 ,22926   ,1024,1024,1024
BEGIN DESCRIPTION:
HAMMOND CREEK 37.0
END DESCRIPTION:
XS GIS Cut Line= 3
      3828618.03     10505641.02      3826909.66     10504745.18
      3826298.56     10504411.85
#Sta/Elev= 30
  3352.4  392.72  3366.8  391.44  3574.1   383.5  3594.6  382.32  3683.5  379.31
  3822.5   376.3  4278.2  372.36  4449.6  371.18    4506   370.7  4668.5  368.51
  4733.9  363.93  4887.4  353.77    4937  347.77    4959  351.13  4961.7  350.96
  4987.9  349.36  5000.1  343.54  5002.9  343.04  5006.1  343.54    5033  352.28
  5106.3  351.49  5189.5  351.33  5215.7  346.37  5234.5  351.27  5315.6  348.28
  5435.8  354.57  5546.2  360.02  5616.5  360.46  5779.8  374.36  5977.5  375.42
#Mann= 20 ,-1 , 0
  3352.4     .05       0  3366.8     .05       0  3574.1     .08       0
  3594.6     .05       0  3683.5     .08       0  3822.5     .05       0
  4278.2     .16       0  4449.6     .05       0    4506     .08       0
  4668.5     .05       0  4733.9     .12       0  4887.4     .08       0
  4961.7     .12       0  5000.1     .07       0  5006.1     .12       0
  5106.3     .05       0  5189.5     .16       0  5215.7     .12       0
  5435.8     .05       0  5546.2     .08       0
Bank Sta=4959,5033
XS Rating Curve= 0 ,0
Exp/Cntr=0.3,0.1

Type RM Length L Ch R = 1 ,21902   ,227,227,227
BEGIN DESCRIPTION:
HAMMOND CREEK 36.0
END DESCRIPTION:
XS GIS Cut Line= 2
      3828166.59     10504627.12      3826284.64      10504328.5
#Sta/Elev= 30
  3486.4  387.33  3706.1  380.36  3746.6  377.51  3928.9  372.49    3939  373.38
    4007  368.41  4232.6  359.27  4283.2  358.26  4374.4  359.51  4527.2  363.94
  4607.2  363.97  4712.3  360.04  4738.9  357.58  4774.6   350.8  4779.7  352.61
  4819.9  347.88  4921.1  349.87  4981.9  348.63  4985.7  345.46    4989   342.7
  4991.7   342.2    4995   342.7  5012.2   347.3  5028.8  349.55  5096.2  354.19
  5123.6  360.87  5158.4  364.66  5174.2  368.07    5235  374.36  5391.9  375.17
#Mann= 5 ,-1 , 0
  3486.4     .05       0  4527.2     .12       0  4985.7     .05       0
    4989     .03       0    4995     .05       0
#XS Ineff= 1 ,-1
    4118  4520.4  363.89
Permanent Ineff=
       F
Bank Sta=4981.9,5028.8
XS Rating Curve= 0 ,0
Exp/Cntr=0.3,0.1

Type RM Length L Ch R = 1 ,21675   ,530,530,530
BEGIN DESCRIPTION:
HAMMOND CREEK 35.0
END DESCRIPTION:
XS GIS Cut Line= 3
      3827699.62     10504510.19      3826784.66     10504189.62
      3826319.38     10504161.84
#Sta/Elev= 30
  3933.4  371.44    4042  369.03  4067.7  366.54  4160.7   364.6  4177.1  362.69
  4305.9  358.32  4315.8  355.77  4352.2  357.67  4403.6  357.69  4429.3  361.13
  4465.6  363.09  4473.8   365.8  4491.3  363.77  4696.3  362.54  4761.7  359.24
    4918  347.11  4975.2  347.14  4995.1  341.62  4997.9  341.12  5001.1  341.62
  5008.1  342.55  5018.2  347.49  5028.2  349.16  5045.4   346.6  5108.3  346.94
  5163.3  354.55  5218.5  362.22  5228.5  365.54  5288.6  375.55    5369  377.69
#Mann= 8 ,-1 , 0
  3933.4     .05       0  4305.9      .1       0  4352.2     .05       0
  4761.7     .12       0  4995.1     .07       0  5001.1     .12       0
  5045.4     .16       0  5163.3     .05       0
#XS Ineff= 1 ,-1
    4110  4473.8   365.8
Permanent Ineff=
       F
Bank Sta=4975.2,5028.2
XS Rating Curve= 0 ,0
Exp/Cntr=0.3,0.1

Type RM Length L Ch R = 1 ,21145   ,696,696,696
BEGIN DESCRIPTION:
HAMMOND CREEK 34.0
END DESCRIPTION:
XS GIS Cut Line= 3
      3827111.07     10504259.08      3826599.61     10503810.19
      3826399.58      10503860.2
#Sta/Elev= 30
  4329.9  363.63  4400.7  363.11  4411.1  362.03  4521.2   354.1  4543.1  351.48
  4549.7   349.5  4557.3  349.83  4584.8  346.56  4627.5  346.97  4649.3  348.33
  4698.7  346.65    4863  348.24    4897  348.78  4974.8  347.55  4982.4  342.35
  5000.3  340.37  5003.1  339.87  5006.3  340.37  5007.1  347.48    5013  347.48
  5028.5  354.92  5033.6  354.41  5069.7  362.61  5103.2  367.58  5110.9  370.01
  5116.1  369.62  5143.3  373.49  5206.3  374.56    5214  377.38  5216.6  377.38
#Mann= 6 ,-1 , 0
  4329.9     .05       0  4411.1     .12       0    4863     .16       0
  5000.3     .07       0  5006.3     .16       0  5143.3     .05       0
Bank Sta=4974.8,5007.1
XS Rating Curve= 0 ,0
Exp/Cntr=0.3,0.1