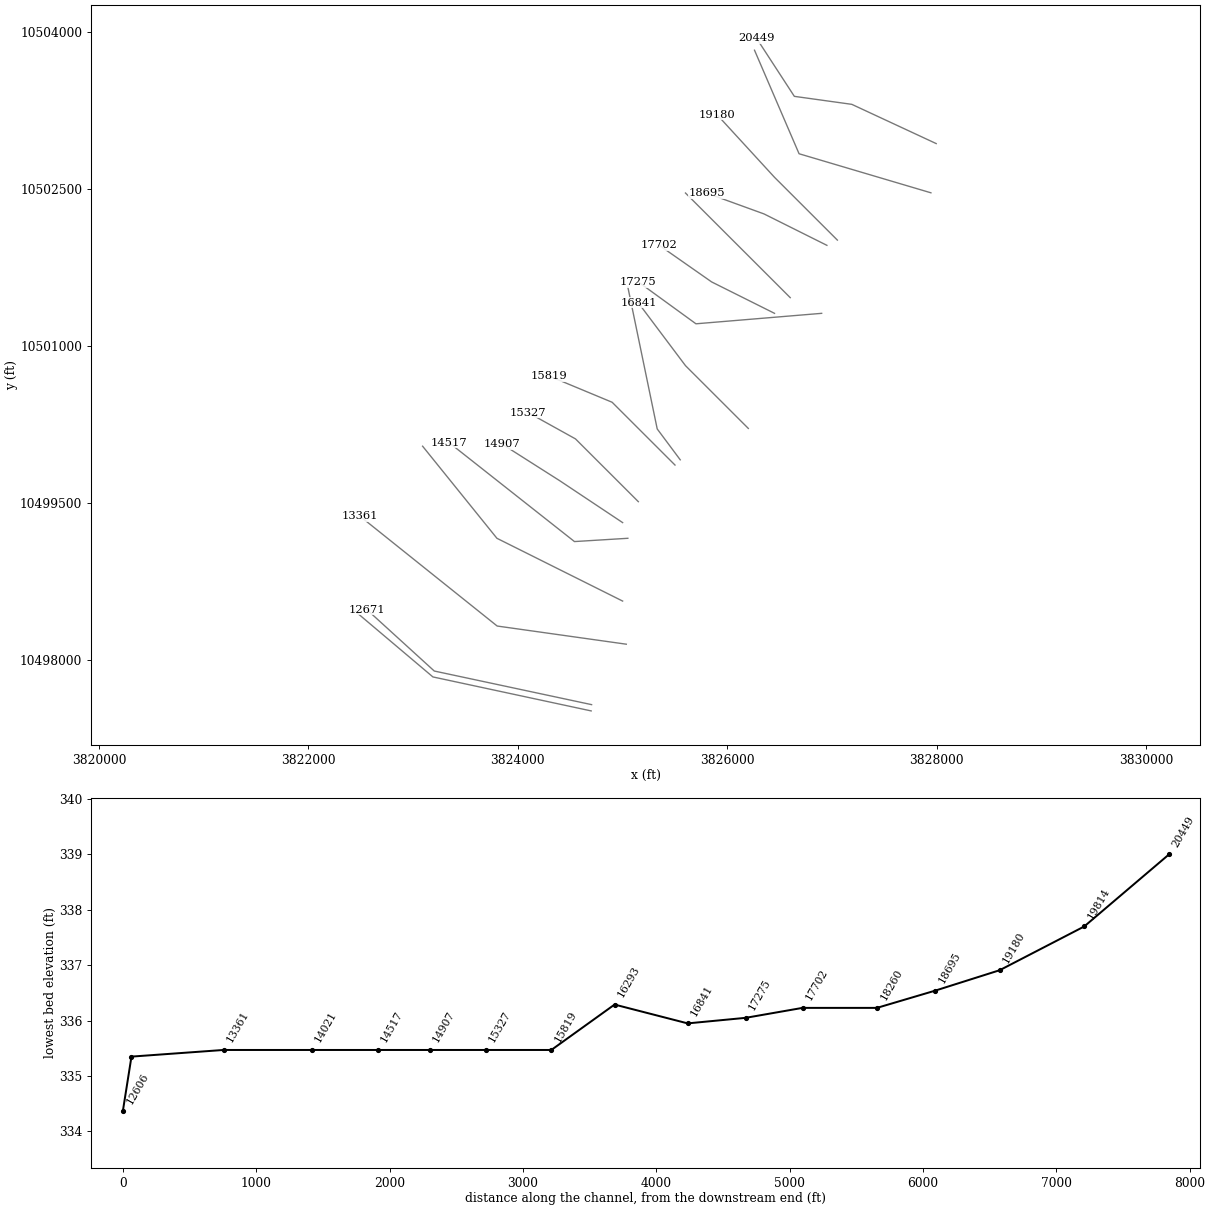
HEC-RAS study HAMMOND CREEK.prj: HAMMOND CREEK Base Level Engineering

--- HAMMOND CREEK.g01 (geometry) --- (continued)

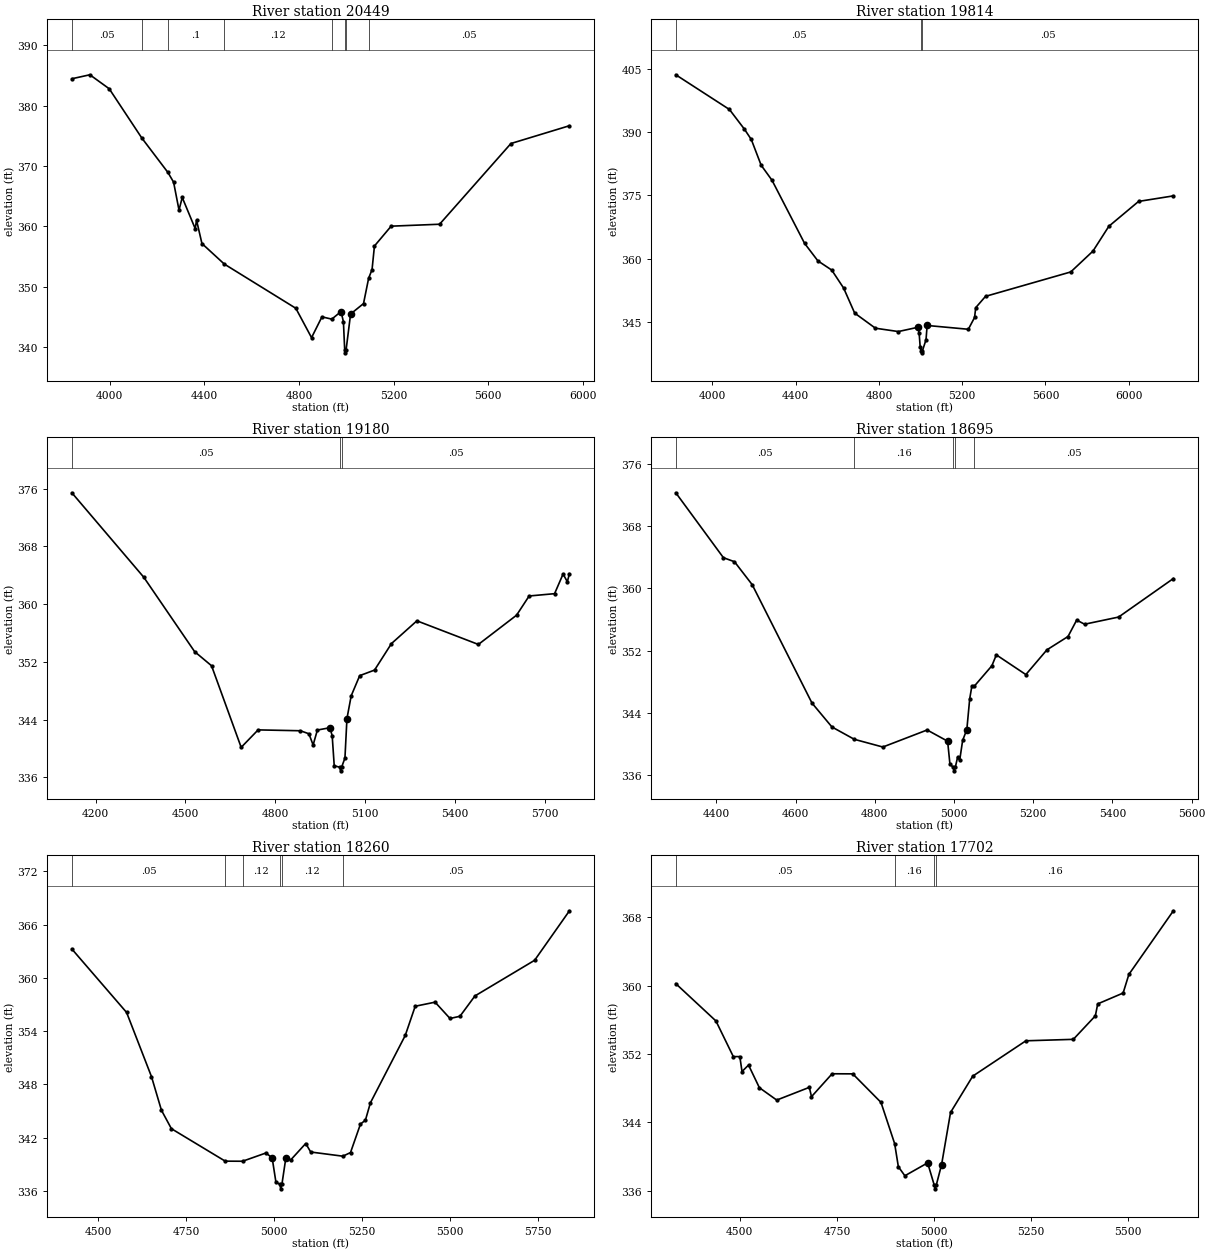
Type RM Length L Ch R = 1 ,20449   ,635,635,635
BEGIN DESCRIPTION:
HAMMOND CREEK 33.0
END DESCRIPTION:
XS GIS Cut Line= 4
      3827992.98     10502932.68      3827187.44     10503307.68
      3826638.83     10503384.06      3826277.69     10503939.66
#Sta/Elev= 30
  3839.2  384.46  3915.4  385.12  3997.3   382.8  4134.6  374.66  4245.6  368.92
  4269.6  367.31  4292.5  362.68  4306.2  364.77  4361.1  359.59  4366.6  361.01
  4389.5  357.13  4483.9  353.73  4786.7  346.39  4853.2  341.52  4897.2  344.97
  4938.8  344.59    4978  345.85  4988.1  344.14  4993.4   339.5  4996.2     339
  4999.4   339.5  5018.4  345.44  5073.1  347.17  5094.7  351.37  5109.2  352.81
  5119.3  356.72    5190  360.01  5394.9  360.33  5696.8  373.72  5944.3  376.67
#Mann= 8 ,-1 , 0
  3839.2     .05       0  4134.6     .12       0  4245.6      .1       0
  4483.9     .12       0  4938.8     .16       0  4993.4     .07       0
  4999.4     .16       0  5094.7     .05       0
Bank Sta=4978,5018.4
XS Rating Curve= 0 ,0
Exp/Cntr=0.3,0.1

Type RM Length L Ch R = 1 ,19814   ,634,634,634
BEGIN DESCRIPTION:
HAMMOND CREEK 32.0
END DESCRIPTION:
XS GIS Cut Line= 3
      3827942.68     10502462.18      3826683.97     10502835.45
      3826258.63     10503825.03
#Sta/Elev= 30
  3824.4  403.53  4082.2  395.31  4153.8  390.67  4187.1  388.21  4234.4  382.12
  4286.5  378.56    4443  363.62    4507  359.47  4573.5  357.29  4630.7  353.02
  4683.6  347.11  4783.3  343.53  4893.4  342.74  4985.4  343.73  4993.1   342.5
  4998.3  339.05  5003.2   338.2    5006   337.7  5009.2   338.2  5026.4  340.83
  5031.6  344.18  5229.5  343.28  5259.5  346.07    5265  348.39    5312  351.07
  5721.4  356.85  5828.2  361.79  5904.4  367.66  6047.3  373.55  6214.4  374.86
#Mann= 3 ,-1 , 0
  3824.4     .05       0  5003.2     .03       0  5009.2     .05       0
Bank Sta=4985.4,5031.6
XS Rating Curve= 0 ,0
Exp/Cntr=0.3,0.1

Type RM Length L Ch R = 1 ,19180   ,485,485,485
BEGIN DESCRIPTION:
HAMMOND CREEK 31.0
END DESCRIPTION:
XS GIS Cut Line= 3
      3827049.62     10502010.18      3826449.61     10502610.19
       3825899.6      10503210.2
#Sta/Elev= 30
  4120.4  375.41  4360.8  363.71  4530.5  353.42  4587.1  351.46  4686.1  340.16
  4742.7  342.58  4884.1  342.46  4912.4  342.04  4926.5  340.49  4940.7  342.56
  4982.8  342.88  4990.2  341.76    4997  337.61  5015.6  337.41  5018.3  336.91
  5021.6  337.41  5032.8  338.68  5039.5  344.15  5053.7   347.3  5082.1  350.09
  5131.7  350.86  5188.2  354.53  5273.2  357.68  5478.6  354.41  5606.2  358.46
  5648.2  361.12  5733.2  361.44  5761.6  364.16  5775.8  363.09  5782.9  364.21
#Mann= 3 ,-1 , 0
  4120.4     .05       0  5015.6     .03       0  5021.6     .05       0
Bank Sta=4982.8,5039.5
XS Rating Curve= 0 ,0
Exp/Cntr=0.3,0.1

Type RM Length L Ch R = 1 ,18695   ,435,435,435
BEGIN DESCRIPTION:
HAMMOND CREEK 30.0
END DESCRIPTION:
XS GIS Cut Line= 3
      3826949.64     10501960.17      3826349.61     10502260.19
       3825799.6     10502460.19
#Sta/Elev= 30
  4297.8  372.27    4418  363.93    4446  363.41  4490.7  360.46  4641.6  345.25
  4691.9  342.18  4748.5  340.59  4820.5   339.6  4932.3  341.79    4984  340.35
  4989.9  337.37  4997.6  337.04  5000.3  336.54  5003.6  337.04  5009.2  338.29
  5014.5  337.91  5021.9  340.44  5032.5  341.85  5039.8  345.82  5045.1  347.39
  5051.7  347.44  5095.7  350.04    5107  351.44  5181.5  348.91  5234.7  352.09
  5287.9   353.8  5309.8  355.91  5329.8  355.38  5415.6   356.3  5553.9  361.25
#Mann= 5 ,-1 , 0
  4297.8     .05       0  4748.5     .16       0  4997.6     .07       0
  5003.6     .16       0  5051.7     .05       0
Bank Sta=4984,5032.5
XS Rating Curve= 0 ,0
Exp/Cntr=0.3,0.1

Type RM Length L Ch R = 1 ,18260   ,558,558,558
BEGIN DESCRIPTION:
HAMMOND CREEK 29.0
END DESCRIPTION:
XS GIS Cut Line= 3
      3826599.64     10501460.16      3826199.61     10501860.19
      3825599.58     10502460.22
#Sta/Elev= 30
  4425.9  363.26  4581.5  356.11  4652.2  348.88  4680.5  345.09  4708.8  343.01
  4861.8  339.35  4911.1  339.34  4977.5  340.27  4995.2  339.72  5005.8  337.01
  5016.9  336.73  5019.7  336.23  5022.9  336.73  5034.1  339.71  5048.2   339.5
  5090.6  341.34  5104.8  340.38  5196.2  339.91  5217.9  340.32  5246.2  343.53
  5260.3  343.97  5274.5  345.93  5373.5  353.52  5401.8  356.81  5458.3  357.27
  5500.7  355.43    5529  355.68  5571.5  357.97  5741.2  361.99  5840.2  367.57
#Mann= 6 ,-1 , 0
  4425.9     .05       0  4861.8     .16       0  4911.1     .12       0
  5016.9     .07       0  5022.9     .12       0  5196.2     .05       0
Bank Sta=4995.2,5034.1
XS Rating Curve= 0 ,0
Exp/Cntr=0.3,0.1

Type RM Length L Ch R = 1 ,17702   ,427,427,427
BEGIN DESCRIPTION:
HAMMOND CREEK 28.0
END DESCRIPTION:
XS GIS Cut Line= 3
       3826449.6     10501310.19      3825849.61     10501610.19
      3825349.64     10501960.17
#Sta/Elev= 30
    4335  360.25  4438.4  355.88  4483.1  351.71  4499.9  351.71  4505.5  349.96
  4522.3  350.72  4550.2  348.07  4594.9  346.62  4678.8  348.11  4684.4  347.02
  4737.5   349.7  4790.6  349.69  4863.3  346.35  4898.5  341.52    4908  338.82
  4924.8  337.76  4983.4  339.27    5000  336.73  5002.8  336.23    5006  336.73
  5019.3  339.06  5042.4  345.17  5099.5  349.42  5236.4  353.56  5358.5  353.73
  5415.2  356.48  5421.3  357.88  5486.7  359.15  5501.5  361.33  5616.1  368.78
#Mann= 4 ,-1 , 0
    4335     .05       0  4898.5     .16       0    5000     .07       0
    5006     .16       0
Bank Sta=4983.4,5019.3
XS Rating Curve= 0 ,0
Exp/Cntr=0.3,0.1

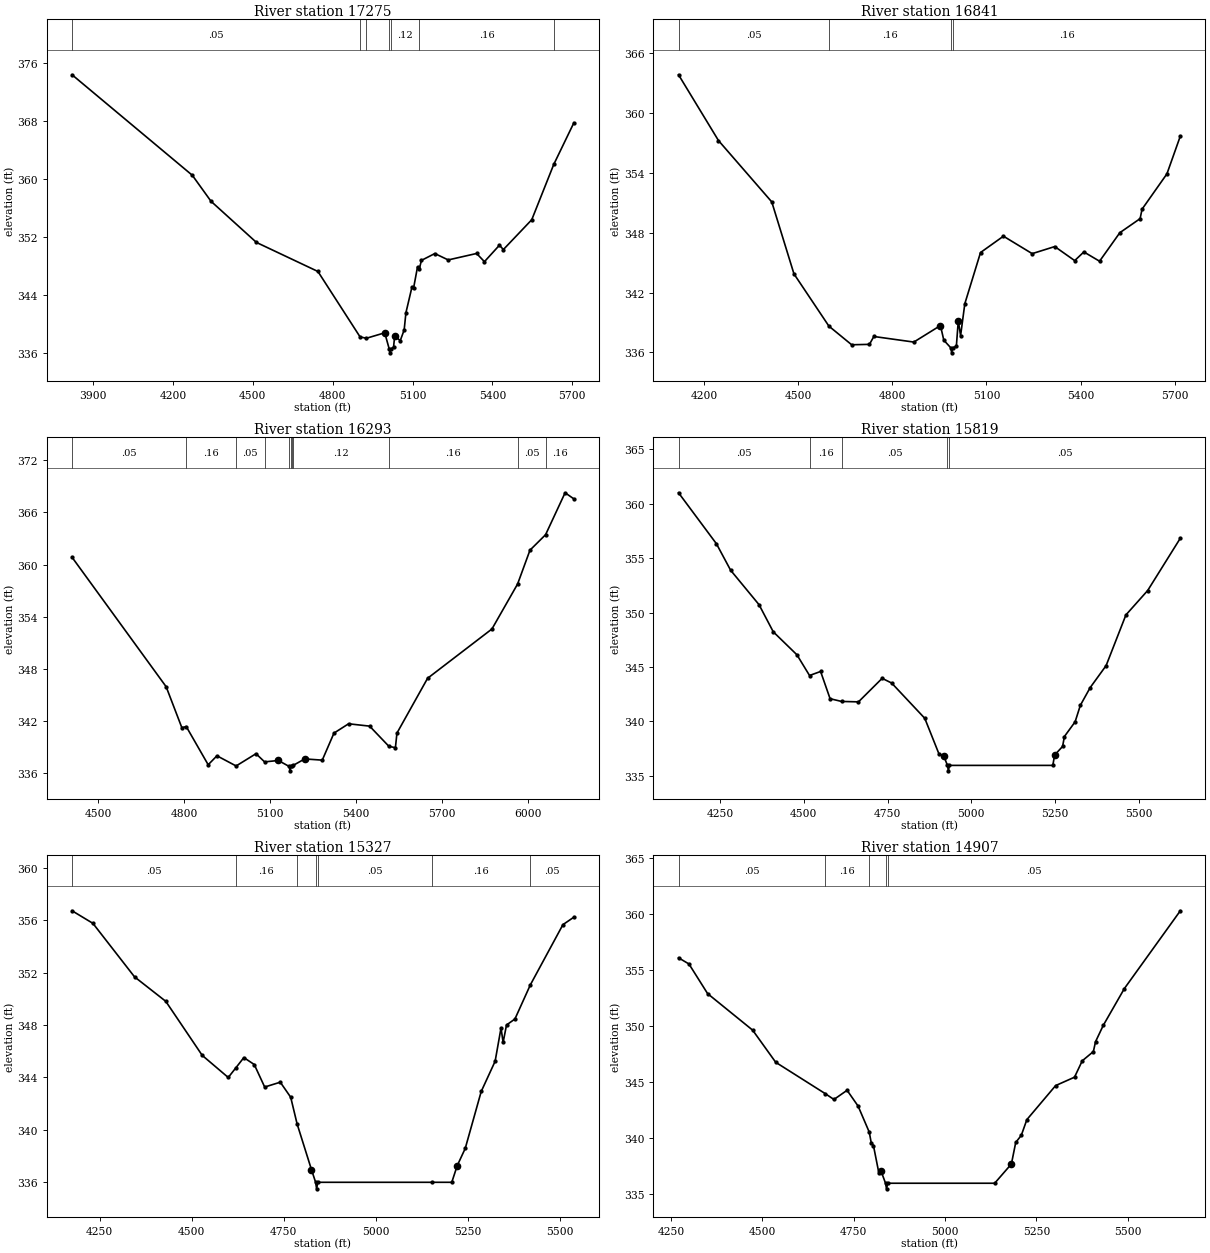
Type RM Length L Ch R = 1 ,17275   ,434,434,434
BEGIN DESCRIPTION:
HAMMOND CREEK 27.0
END DESCRIPTION:
XS GIS Cut Line= 3
      3826899.65     10501310.19      3825699.61     10501210.19
      3825149.59      10501610.2
#Sta/Elev= 30
  3821.6  374.36  4273.2  360.51  4343.4  356.93    4514  351.26  4744.8  347.26
  4903.2  338.24    4927  338.06  4995.7  338.81  5012.8  336.55  5015.5  336.05
  5018.8  336.55  5028.9  336.86  5033.1  338.39    5054  337.73  5068.7  339.21
  5075.3  341.58  5098.1  345.14  5104.2     345  5118.9  347.91    5125  347.54
  5133.6  348.79  5183.8  349.73  5234.1  348.85  5340.7  349.74  5370.1  348.61
  5426.5  350.88  5441.2  350.28  5547.8  354.39  5630.3     362  5705.9  367.74
#Mann= 7 ,-1 , 0
  3821.6     .05       0  4903.2     .16       0    4927     .12       0
  5012.8     .07       0  5018.8     .12       0    5125     .16       0
  5630.3     .05       0
Bank Sta=4995.7,5033.1
XS Rating Curve= 0 ,0
Exp/Cntr=0.3,0.1

Type RM Length L Ch R = 1 ,16841   ,548,548,548
BEGIN DESCRIPTION:
HAMMOND CREEK 26.0
END DESCRIPTION:
XS GIS Cut Line= 3
      3826199.59      10500210.2      3825599.61     10500810.19
      3825149.61     10501410.18
#Sta/Elev= 30
  4119.3  363.84  4246.6  357.24  4416.3  351.09    4487  343.87  4598.3  338.63
  4670.8  336.76  4727.4   336.8  4741.5  337.59  4868.8  337.03  4953.7  338.69
  4964.3  337.22  4986.7  336.45  4989.4  335.95  4992.7  336.45  5004.3   336.6
  5010.5  339.18  5017.8  337.67  5031.3  340.88  5081.3  346.01  5154.3  347.65
  5245.9   345.9  5317.8  346.61  5381.3   345.2  5410.5  346.07  5460.5  345.14
  5525.1     348  5589.7  349.41  5595.9  350.36  5675.1   353.9  5717.8  357.69
#Mann= 4 ,-1 , 0
  4119.3     .05       0  4598.3     .16       0  4986.7     .07       0
  4992.7     .16       0
Bank Sta=4953.7,5010.5
XS Rating Curve= 0 ,0
Exp/Cntr=0.3,0.1

Type RM Length L Ch R = 1 ,16293   ,474,474,474
BEGIN DESCRIPTION:
HAMMOND CREEK 25.0
END DESCRIPTION:
XS GIS Cut Line= 3
      3825549.59     10499910.22       3825329.8     10500205.25
      3825049.61     10501560.18
#Sta/Elev= 30
  4408.3  360.84  4736.7  345.96  4791.5  341.25  4806.9  341.38  4883.4  336.99
    4914  338.02  4980.9  336.85  5050.3  338.26  5080.3  337.32  5128.4  337.48
  5166.3  336.79    5169  336.29  5172.3  336.79  5177.7  336.88  5179.7  336.91
  5220.3  337.66  5281.6  337.52  5322.5  340.63  5373.5   341.7  5446.9  341.43
  5514.2  339.11  5536.9  338.95  5542.3  340.63  5649.2  346.93  5873.9   352.6
  5963.4  357.77  6006.6  361.66  6061.1  363.44  6129.2  368.26  6159.8  367.56
#Mann= 11 ,-1 , 0
  4408.3     .05       0  4806.9     .16       0  4980.9     .05       0
  5080.3     .16       0  5166.3    .035       0  5172.3     .16       0
  5177.7     .05       0  5179.7     .12       0  5514.2     .16       0
  5963.4     .05       0  6061.1     .16       0
Bank Sta=5128.4,5220.3
XS Rating Curve= 0 ,0
Exp/Cntr=0.3,0.1

Type RM Length L Ch R = 1 ,15819   ,492,492,492
BEGIN DESCRIPTION:
HAMMOND CREEK 24.0
END DESCRIPTION:
XS GIS Cut Line= 3
      3825499.63     10499860.17      3824899.61     10500460.19
      3824299.57      10500710.2
#Sta/Elev= 30
  4125.9  360.99  4239.1  356.31  4281.5  353.88  4366.3  350.72  4408.8  348.23
  4479.5  346.12  4517.1  344.22  4550.2  344.59  4578.5  342.09  4612.7  341.84
  4663.3   341.8    4734  343.96  4762.3  343.53  4861.3  340.29  4903.7  337.02
  4917.9  336.84    4929  335.97  4931.8  335.47    4935  335.97  5243.7  335.97
  5249.1  336.92  5272.9  337.71  5278.3  338.62  5310.3  339.97    5326  341.49
  5355.3  343.11  5402.9  345.13    5462  349.78    5527  352.02  5624.5  356.82
#Mann= 5 ,-1 , 0
  4125.9     .05       0  4517.1     .16       0  4612.7     .05       0
    4929    .033       0    4935     .05       0
Bank Sta=4917.9,5249.1
XS Rating Curve= 0 ,0
Exp/Cntr=0.3,0.1

Type RM Length L Ch R = 1 ,15327   ,420,420,420
BEGIN DESCRIPTION:
HAMMOND CREEK 23.0
END DESCRIPTION:
XS GIS Cut Line= 3
      3825149.61     10499510.18      3824549.61     10500110.19
      3824099.62     10500360.18
#Sta/Elev= 30
  4175.3  356.72  4231.9  355.76    4345  351.67  4429.9   349.8  4528.9  345.67
  4599.6  343.98  4619.8   344.7    4642   345.5  4670.3  344.97  4698.6  343.25
    4741  343.62  4769.3  342.47  4786.6  340.44  4825.8  336.93    4837  335.97
  4839.7  335.47    4843  335.97  5152.4  335.97  5206.9  335.97  5221.7  337.24
  5243.5  338.56  5286.9  342.91  5324.7  345.22  5340.7  347.76  5346.4  346.66
  5355.6  347.99  5378.5  348.45  5420.4  351.06  5508.9  355.66  5538.6  356.23
#Mann= 7 ,-1 , 0
  4175.3     .05       0  4619.8     .16       0  4786.6     .05       0
    4837    .033       0    4843     .05       0  5152.4     .16       0
  5420.4     .05       0
Bank Sta=4825.8,5221.7
XS Rating Curve= 0 ,0
Exp/Cntr=0.3,0.1

Type RM Length L Ch R = 1 ,14907   ,390,390,390
BEGIN DESCRIPTION:
HAMMOND CREEK 22.0
END DESCRIPTION:
XS GIS Cut Line= 3
      3824999.61     10499310.19      3824399.61     10499710.19
      3823849.64     10500060.17
#Sta/Elev= 30
    4271   356.1  4299.5  355.55  4350.6   352.9  4473.8  349.64  4536.9  346.77
  4672.5  343.97  4696.2  343.45  4732.2  344.27  4762.3  342.86  4792.9  340.53
  4798.3  339.57  4804.3  339.34  4819.3  336.86  4825.4  337.03  4837.4  335.97
  4840.1  335.47  4843.4  335.97    5136  335.97  5181.8  337.69  5193.6  339.61
  5208.9  340.25  5224.1  341.65  5302.8  344.69  5354.5  345.44  5375.6   346.9
  5406.1  347.73    5412  348.61  5433.2  350.07  5490.8  353.35    5644   360.3
#Mann= 5 ,-1 , 0
    4271     .05       0  4672.5     .16       0  4792.9     .05       0
  4837.4    .033       0  4843.4     .05       0
Bank Sta=4825.4,5181.8
XS Rating Curve= 0 ,0
Exp/Cntr=0.3,0.1

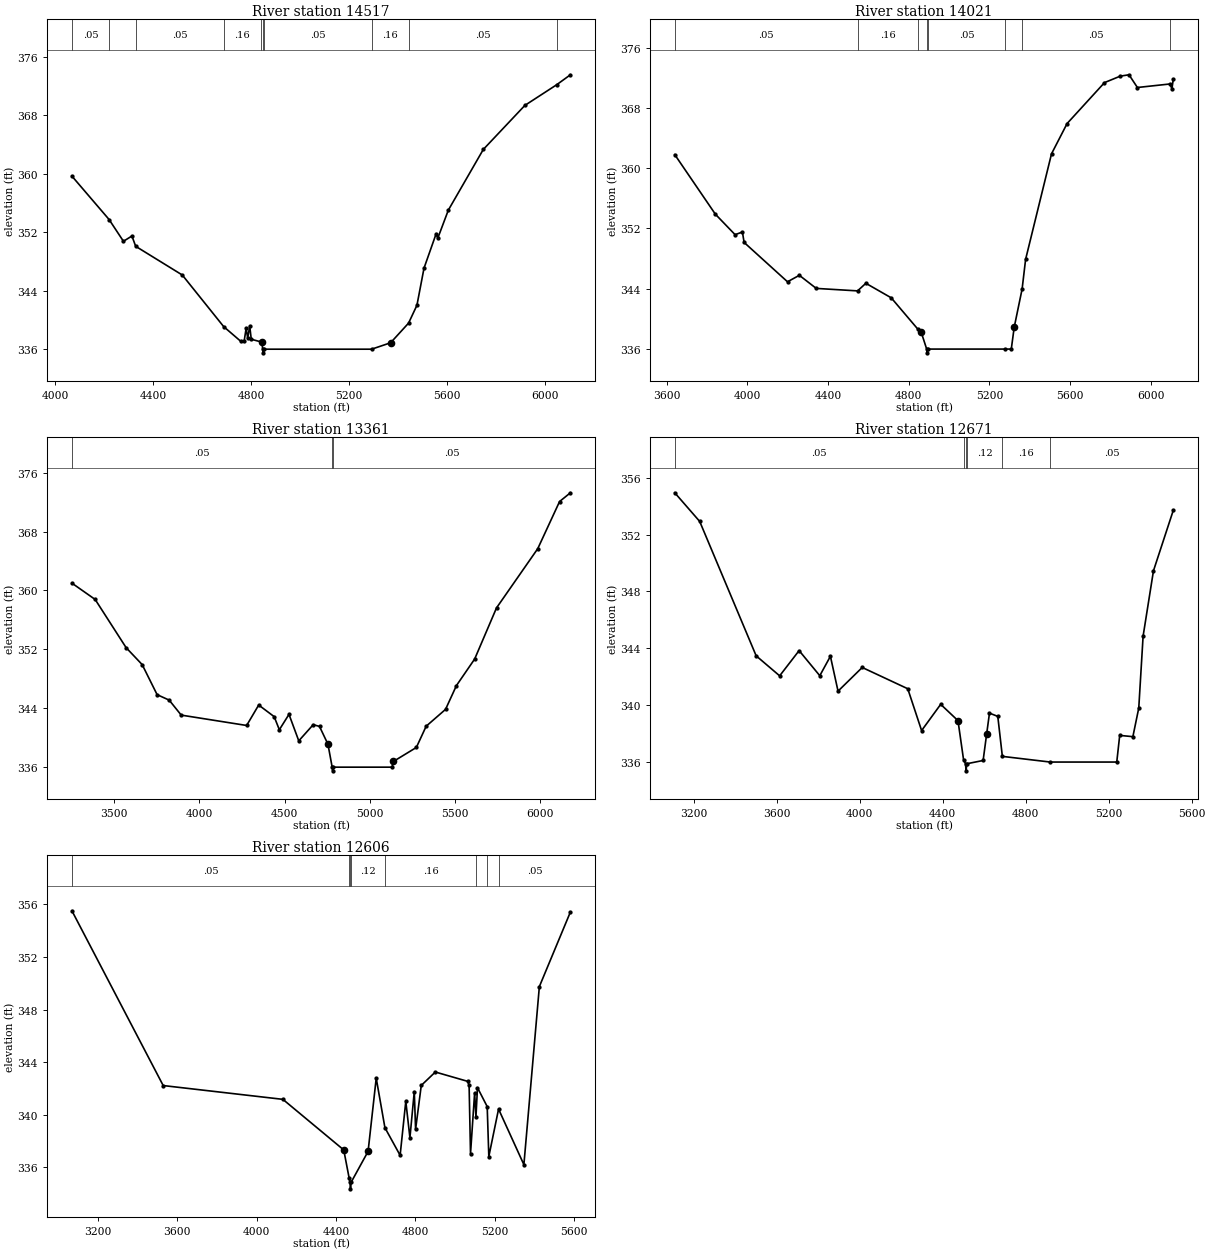
Type RM Length L Ch R = 1 ,14517   ,496,496,496
BEGIN DESCRIPTION:
HAMMOND CREEK 21.0
END DESCRIPTION:
XS GIS Cut Line= 3
      3825049.59     10499160.19      3824539.87     10499128.86
      3823343.29     10500073.99
#Sta/Elev= 30
  4067.9  359.66  4219.7  353.72  4278.3  350.74  4312.9  351.46  4328.4  350.05
  4518.7  346.12  4687.6  339.06  4757.3  337.05  4771.3  337.09  4779.4  338.84
  4785.8  337.45  4793.9  339.16  4800.2  337.33  4838.6  336.98  4843.5  336.97
  4846.9  335.97  4849.7  335.47  4852.9  335.97  5291.6  335.97  5369.3  336.85
  5442.6  339.54  5476.7  341.98  5505.6  347.06  5555.3  351.79  5561.7  351.15
    5605  355.01  5747.7  363.31  5917.5  369.34  6046.6  372.15  6103.4  373.53
#Mann= 10 ,-1 , 0
  4067.9     .05       0  4219.7     .08       0  4328.4     .05       0
  4687.6     .16       0  4838.6     .05       0  4846.9    .033       0
  4852.9     .05       0  5291.6     .16       0  5442.6     .05       0
  6046.6     .16       0
Bank Sta=4843.5,5369.3
XS Rating Curve= 0 ,0
Exp/Cntr=0.3,0.1

Type RM Length L Ch R = 1 ,14021   ,660,660,660
BEGIN DESCRIPTION:
HAMMOND CREEK 20.0
END DESCRIPTION:
XS GIS Cut Line= 3
      3824999.65     10498560.17      3823799.61     10499160.19
      3823090.22     10500040.31
#Sta/Elev= 30
  3639.8   361.8  3841.1  353.89  3938.9  351.17  3975.3  351.52  3983.6  350.14
  4198.9  344.91  4257.6  345.77  4341.4  344.03  4546.3   343.7  4587.4  344.71
  4713.2  342.78  4845.1  338.62  4861.3  338.26    4889  335.97  4891.8  335.47
    4895  335.97  5277.4  335.97  5308.6  335.97    5323  338.86  5362.3  343.95
  5379.6  347.89  5508.1  361.91  5585.3  365.93  5770.8  371.37  5849.2  372.23
  5892.4  372.41    5934  370.72  6095.9  371.19  6105.1  370.54  6111.9  371.81
#Mann= 8 ,-1 , 0
  3639.8     .05       0  4546.3     .16       0  4845.1     .05       0
    4889    .033       0    4895     .05       0  5277.4     .16       0
  5362.3     .05       0  6095.9     .16       0
Bank Sta=4861.3,5323
XS Rating Curve= 0 ,0
Exp/Cntr=0.3,0.1

Type RM Length L Ch R = 1 ,13361   ,690,690,690
BEGIN DESCRIPTION:
HAMMOND CREEK 19.0
END DESCRIPTION:
XS GIS Cut Line= 3
      3825034.65     10498147.96      3823802.03     10498321.56
      3822491.24     10499371.93
#Sta/Elev= 30
  3252.5     361  3388.9  358.78  3570.7  352.22  3664.7  349.92  3752.4  345.83
  3823.1  345.09  3893.8  343.05  4277.6  341.64  4348.3  344.42  4439.1  342.84
  4469.4  341.06    4526  343.15  4583.4  339.55  4668.2  341.75    4705  341.51
  4754.6  339.09  4779.3  335.97  4782.1  335.47  4785.3  335.97  5130.7  335.97
  5138.7  336.75  5273.2  338.65  5330.8  341.54  5444.4  343.83  5508.4  347.07
  5615.3  350.68  5743.4  357.63  5985.4  365.69  6113.4   372.1    6177  373.29
#Mann= 3 ,-1 , 0
  3252.5     .05       0  4779.3    .033       0  4785.3     .05       0
Bank Sta=4754.6,5138.7
XS Rating Curve= 0 ,0
Exp/Cntr=0.3,0.1

Type RM Length L Ch R = 1 ,12671   ,65,65,65
BEGIN DESCRIPTION:
HAMMOND CREEK 18.0
END DESCRIPTION:
XS GIS Cut Line= 3
      3824703.38     10497570.33      3823201.62     10497891.52
       3822560.5     10498476.32
#Sta/Elev= 30
  3107.9  354.96  3228.1  352.94  3500.4  343.46  3613.6  342.05  3707.4  343.83
  3807.1  342.06  3858.3  343.43  3895.1  340.97  4011.7  342.64  4231.2  341.14
    4298  338.19    4390  340.04  4473.4  338.89  4500.3  336.13  4509.7  335.85
  4512.4  335.35  4515.7  335.85  4594.6  336.08  4611.6  337.95  4625.2  339.42
  4665.3  339.19  4687.3  336.37  4918.1  335.97  5238.9  335.97  5253.1  337.85
  5316.6  337.76    5345  339.78  5365.9  344.85  5415.9  349.46  5511.4  353.72
#Mann= 6 ,-1 , 0
  3107.9     .05       0  4500.3     .12       0  4509.7    .033       0
  4515.7     .12       0  4687.3     .16       0  4918.1     .05       0
Bank Sta=4473.4,4611.6
XS Rating Curve= 0 ,0
Exp/Cntr=0.3,0.1

Type RM Length L Ch R = 1 ,12606   ,80,80,80
BEGIN DESCRIPTION:
HAMMOND CREEK 17.0
END DESCRIPTION:
XS GIS Cut Line= 3
      3824699.58      10497510.2       3823188.6     10497835.09
      3822449.63     10498460.17
#Sta/Elev= 30
  3068.5  355.52  3528.8  342.22  4132.2  341.17  4439.1  337.32  4465.9  335.21
  4470.3  334.86  4473.1  334.36  4476.3  334.86  4561.8  337.21  4602.8  342.78
  4646.7  339.01  4723.3  336.91  4751.9  341.02  4772.7  338.25  4794.7  341.76
  4801.3  338.89  4829.9  342.23  4900.8  343.25  5063.9  342.54  5071.1  342.24
  5078.2  337.03    5099  341.67  5105.6  339.83  5113.3  342.06  5162.3  340.62
  5170.5  336.82  5219.6  340.43  5347.3   336.2  5425.3  349.75  5581.9  355.43
#Mann= 8 ,-1 , 0
  3068.5     .05       0  4465.9     .12       0  4470.3     .07       0
  4476.3     .12       0  4646.7     .16       0  5105.6     .05       0
  5162.3     .16       0  5219.6     .05       0
Bank Sta=4439.1,4561.8
XS Rating Curve= 0 ,0
Exp/Cntr=0.3,0.1