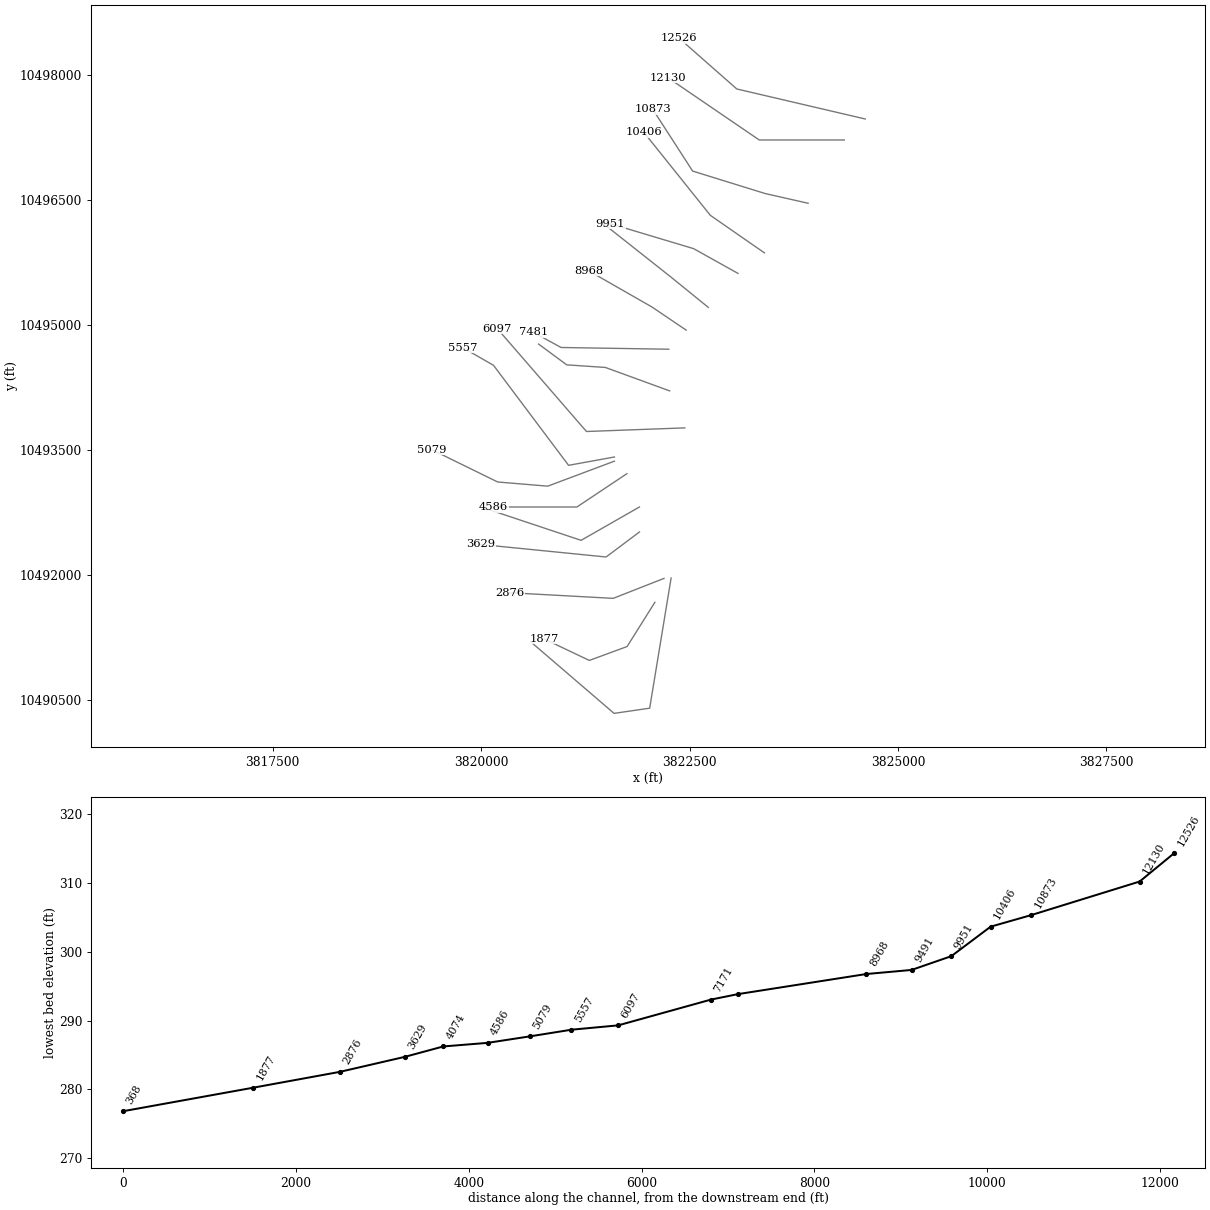
HEC-RAS study HAMMOND CREEK.prj: HAMMOND CREEK Base Level Engineering

--- HAMMOND CREEK.g01 (geometry) --- (continued)

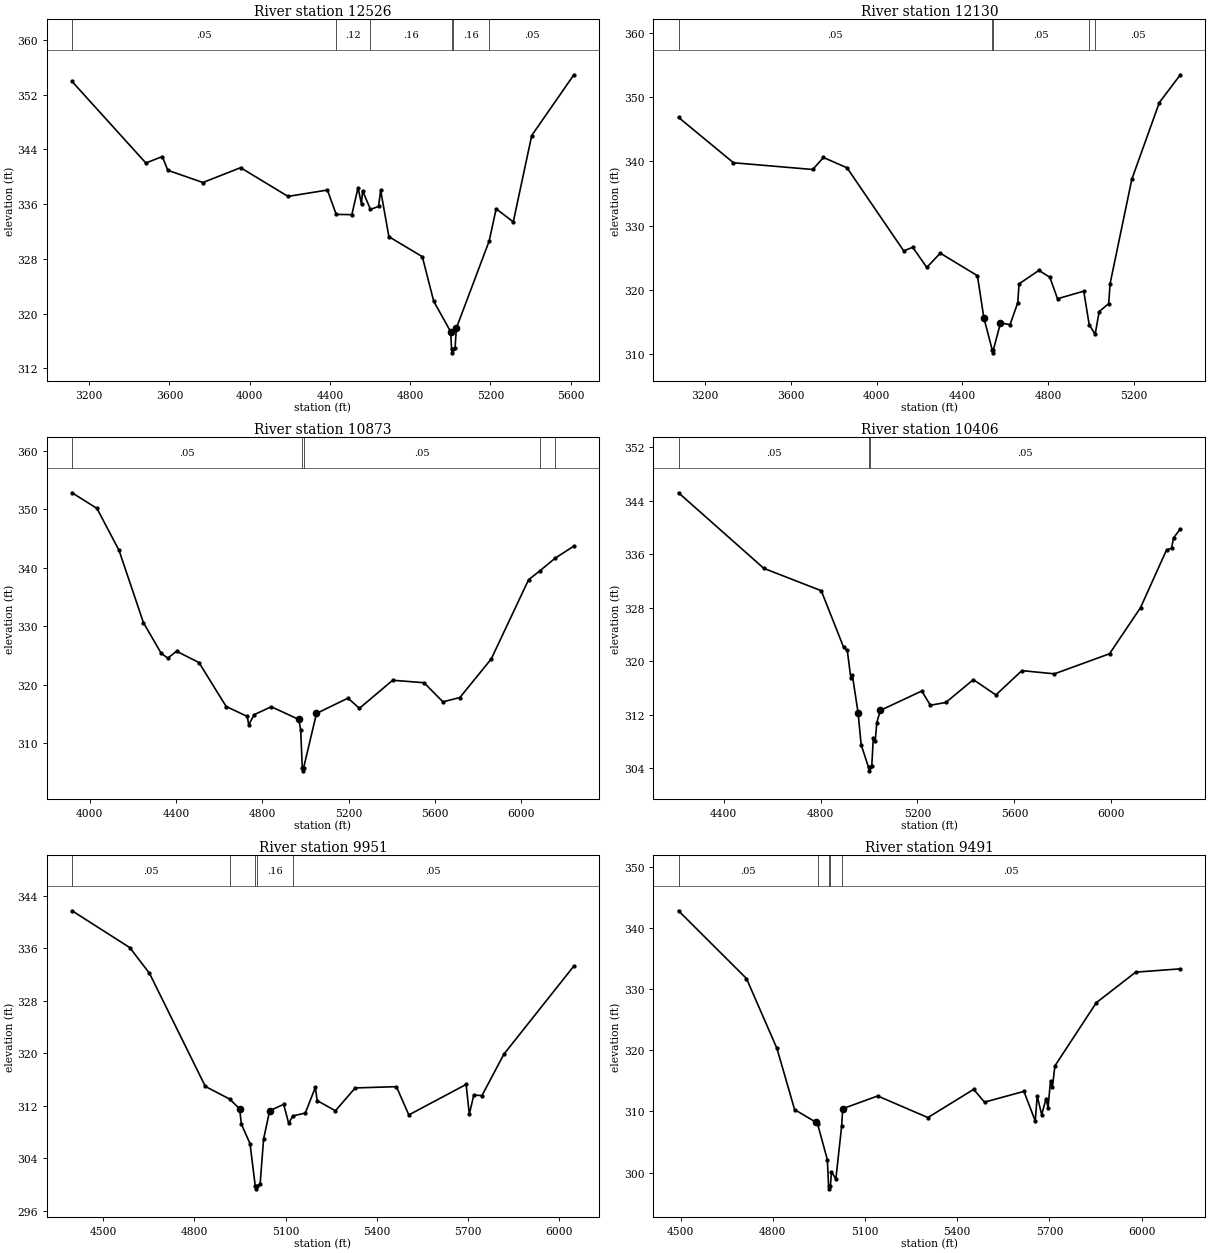
Type RM Length L Ch R = 1 ,12526   ,396,396,396
BEGIN DESCRIPTION:
HAMMOND CREEK 16.0
END DESCRIPTION:
XS GIS Cut Line= 3
      3824607.85     10497466.17      3823067.07     10497826.41
      3822376.98     10498434.04
#Sta/Elev= 30
  3114.7  353.92  3482.6     342  3564.8  342.95    3592  340.94  3767.1  339.15
    3955  341.32  4191.2  337.12  4387.8  338.05  4431.6  334.49  4509.6  334.45
  4540.4  338.39  4557.8  335.98    4563  337.95  4602.5  335.21  4642.8  335.66
  4653.3     338  4694.3  331.23  4860.9  328.31  4917.8  321.79  5002.3  317.34
  5006.9  314.75  5009.6  314.25  5012.9  314.75  5024.1   314.9  5030.7  317.86
  5194.4  330.61    5229  335.31  5314.4  333.39  5406.4  346.02  5616.5   354.9
#Mann= 6 ,-1 , 0
  3114.7     .05       0  4431.6     .12       0  4602.5     .16       0
  5006.9     .07       0  5012.9     .16       0  5194.4     .05       0
Bank Sta=5002.3,5030.7
XS Rating Curve= 0 ,0
Exp/Cntr=0.3,0.1

Type RM Length L Ch R = 1 ,12130   ,1257,1257,1257
BEGIN DESCRIPTION:
HAMMOND CREEK 15.0
END DESCRIPTION:
XS GIS Cut Line= 3
      3824356.09     10497214.43      3823336.17     10497214.43
      3822243.53      10497960.2
#Sta/Elev= 30
  3075.1  346.86  3331.6  339.79  3701.6  338.74  3751.6  340.61  3861.6  339.01
  4126.5  326.06  4168.4  326.62  4234.2  323.48  4297.1   325.7  4470.6  322.19
  4500.4  315.66  4539.3  310.67  4542.1  310.17  4545.3  310.67  4578.2  314.82
    4623  314.57  4658.9  317.98    4665  320.92  4757.7  323.02  4808.6  321.95
  4844.5   318.6  4967.1  319.78  4992.3  314.58  5020.2  313.05  5038.9  316.59
  5083.6  317.85  5089.7   320.9  5191.4  337.22    5320  349.18  5417.9   353.5
#Mann= 5 ,-1 , 0
  3075.1     .05       0  4539.3     .07       0  4545.3     .05       0
  4992.3     .16       0  5020.2     .05       0
Bank Sta=4500.4,4578.2
XS Rating Curve= 0 ,0
Exp/Cntr=0.3,0.1

Type RM Length L Ch R = 1 ,10873   ,467,467,467
BEGIN DESCRIPTION:
HAMMOND CREEK 14.0
END DESCRIPTION:
XS GIS Cut Line= 4
      3823922.12     10496454.88      3823405.61     10496572.07
      3822537.56     10496841.17      3822056.61     10497586.41
#Sta/Elev= 30
  3918.4  352.84  4033.8  350.16  4136.3  342.97  4249.1  330.63  4331.4  325.39
  4361.9  324.56  4402.9  325.74  4506.7   323.8  4632.5  316.29  4730.2   314.6
    4737  313.17  4762.8  314.91  4841.7  316.25  4968.9  314.08  4977.8  312.32
  4985.3  305.79    4988  305.29  4991.3  305.79  5051.1  315.11    5197  317.72
    5250  315.98  5404.2  320.78  5549.4  320.36  5637.1  317.09  5715.7  317.83
  5860.9  324.42  6034.1  337.98  6086.3  339.49  6156.9  341.65  6243.8  343.72
#Mann= 5 ,-1 , 0
  3918.4     .05       0  4985.3     .03       0  4991.3     .05       0
  6086.3      .1       0  6156.9     .05       0
Bank Sta=4968.9,5051.1
XS Rating Curve= 0 ,0
Exp/Cntr=0.3,0.1

Type RM Length L Ch R = 1 ,10406   ,455,455,455
BEGIN DESCRIPTION:
HAMMOND CREEK 13.0
END DESCRIPTION:
XS GIS Cut Line= 3
      3823398.66     10495859.41      3822749.61     10496310.19
      3821949.58     10497310.22
#Sta/Elev= 30
  4213.8  345.21  4565.7  333.91  4802.8  330.56  4895.3  322.08  4910.2  321.65
    4925  317.46  4931.1  317.96  4954.7  312.33  4967.5  307.53    4998  304.12
  5000.7  303.62    5004  304.12  5011.2  304.27  5017.6  308.51  5025.6  308.09
    5032  310.82  5046.5  312.66  5217.7  315.56    5253  313.43    5317  313.85
  5430.6  317.26  5523.5  314.97  5630.7  318.61  5765.2  318.13  5992.5  321.13
  6120.6  328.04  6227.8  336.66  6248.6  336.92  6256.6  338.47  6284.7  339.79
#Mann= 3 ,-1 , 0
  4213.8     .05       0    4998     .03       0    5004     .05       0
Bank Sta=4954.7,5046.5
XS Rating Curve= 0 ,0
Exp/Cntr=0.3,0.1

Type RM Length L Ch R = 1 ,9951    ,460,460,460
BEGIN DESCRIPTION:
HAMMOND CREEK 12.0
END DESCRIPTION:
XS GIS Cut Line= 3
      3823081.53     10495613.24      3822549.61     10495910.19
      3821549.64     10496210.18
#Sta/Elev= 30
  4396.7  341.69  4586.6  336.09  4651.7  332.17  4835.7  314.94    4916  313.01
  4948.6  311.53  4954.5   309.2    4983  306.22    5000  299.84  5002.8  299.34
    5006  299.84  5016.3  300.04  5027.6   306.9  5047.7  311.24  5093.8  312.21
  5110.3  309.33    5124  310.44  5165.1  310.88  5198.2  314.79  5204.3  312.78
  5264.3  311.23  5329.5  314.71  5465.3   314.9  5506.2   310.6    5695  315.24
  5705.4  310.71  5720.2  313.61  5747.2  313.55  5819.4  319.85  6049.9  333.27
#Mann= 5 ,-1 , 0
  4396.7     .05       0    4916     .16       0    5000     .07       0
    5006     .16       0    5124     .05       0
Bank Sta=4948.6,5047.7
XS Rating Curve= 0 ,0
Exp/Cntr=0.3,0.1

Type RM Length L Ch R = 1 ,9491    ,523,523,523
BEGIN DESCRIPTION:
HAMMOND CREEK 11.0
END DESCRIPTION:
XS GIS Cut Line= 3
      3822725.67     10495205.22      3822272.37      10495573.2
      3821449.42     10496224.26
#Sta/Elev= 30
    4493  342.79  4714.2  331.71  4813.3  320.29  4870.8  310.29  4941.2   308.2
  4945.7  307.92  4977.4   302.1  4981.3  297.84  4984.1  297.34  4987.3  297.84
  4990.8  300.12  5005.1  298.95  5023.8  307.56  5027.4  310.44  5141.1  312.52
  5304.6  308.99  5453.6   313.6  5488.9  311.51  5617.1  313.27    5654  308.44
  5660.4  312.51  5674.9  309.45  5689.3  312.08  5695.7  310.61  5703.7     315
  5710.1  314.01  5717.9  317.43  5852.8  327.77    5981  332.76  6126.2   333.3
#Mann= 5 ,-1 , 0
    4493     .05       0  4945.7     .16       0  4981.3     .07       0
  4987.3     .16       0  5023.8     .05       0
Bank Sta=4941.2,5027.4
XS Rating Curve= 0 ,0
Exp/Cntr=0.3,0.1

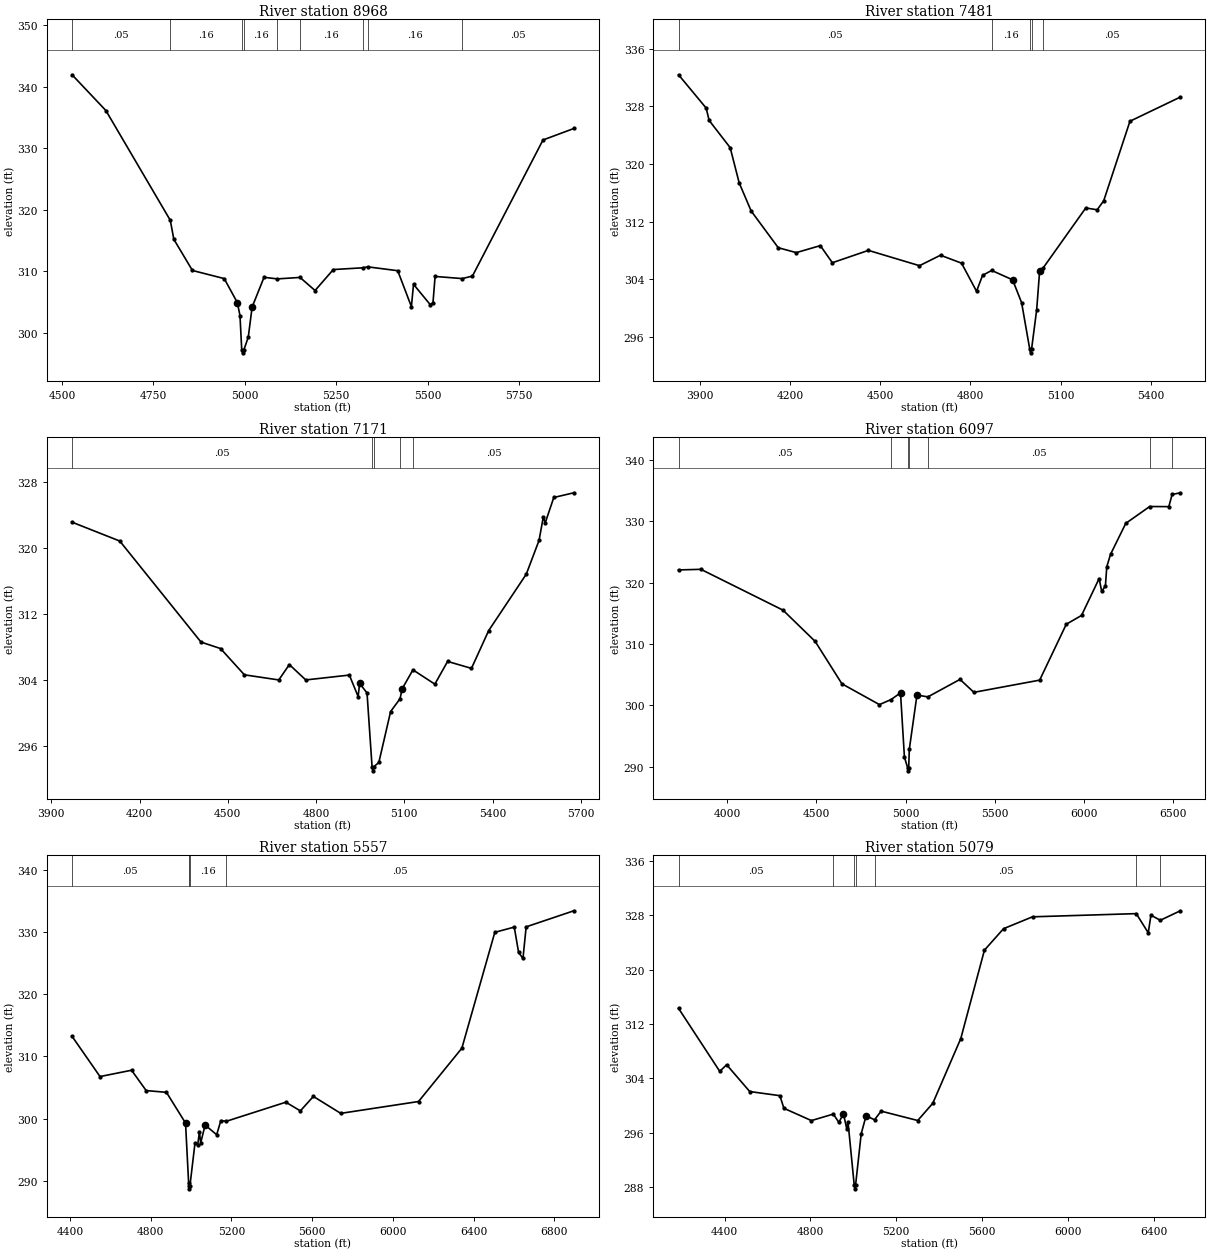
Type RM Length L Ch R = 1 ,8968    ,1487,1487,1487
BEGIN DESCRIPTION:
HAMMOND CREEK 10.0
END DESCRIPTION:
XS GIS Cut Line= 3
      3822459.86     10494932.58      3822049.61     10495210.19
      3821288.78     10495645.67
#Sta/Elev= 30
  4527.8  341.95  4620.2  336.14  4796.4  318.29    4806  315.21  4856.9  310.14
  4943.8  308.82  4979.7  304.92  4986.9  302.81  4991.7  297.25  4994.4  296.75
  4997.7  297.25  5009.6  299.31  5020.1  304.19  5052.7  309.03    5089  308.77
    5151  309.01  5192.2  306.88  5242.1  310.29  5321.9  310.57  5336.2  310.73
  5418.2   310.1  5455.6  304.26  5461.4  307.89  5507.1  304.58  5514.6  304.88
  5520.4  309.17  5594.5  308.82  5622.5  309.23  5815.4  331.35  5899.8  333.22
#Mann= 9 ,-1 , 0
  4527.8     .05       0  4796.4     .16       0  4991.7     .07       0
  4997.7     .16       0    5089     .05       0    5151     .16       0
  5321.9     .05       0  5336.2     .16       0  5594.5     .05       0
Bank Sta=4979.7,5020.1
XS Rating Curve= 0 ,0
Exp/Cntr=0.3,0.1

Type RM Length L Ch R = 1 ,7481    ,310,310,310
BEGIN DESCRIPTION:
HAMMOND CREEK 9.0
END DESCRIPTION:
XS GIS Cut Line= 3
      3822251.51     10494703.41      3820959.87     10494724.24
      3820627.79     10494905.85
#Sta/Elev= 30
  3828.3  332.37  3920.2  327.76  3930.2  326.04  4000.2  322.27  4030.2  317.38
  4070.2  313.48  4160.2   308.4  4220.2  307.72  4300.3  308.69  4340.3  306.32
  4460.3  308.03  4630.3  305.91  4700.3  307.36  4770.3  306.26  4820.3  302.36
  4840.3  304.57  4870.7  305.25  4940.3  303.95  4970.3  300.78  4997.4  294.33
  5000.1  293.83  5003.4  294.33  5020.4  299.79  5030.4  305.23  5042.4  305.62
  5183.8  313.91  5221.8  313.66  5243.6  314.91  5330.9  325.93  5498.6  329.28
#Mann= 5 ,-1 , 0
  3828.3     .05       0  4870.7     .16       0  4997.4     .07       0
  5003.4     .16       0  5042.4     .05       0
Bank Sta=4940.3,5030.4
XS Rating Curve= 0 ,0
Exp/Cntr=0.3,0.1

Type RM Length L Ch R = 1 ,7171    ,1074,1074,1074
BEGIN DESCRIPTION:
HAMMOND CREEK 8.0
END DESCRIPTION:
XS GIS Cut Line= 4
      3822261.92     10494203.42      3821491.12     10494484.66
      3821027.58     10494515.91      3820689.55     10494765.53
#Sta/Elev= 30
  3970.7  323.13  4132.8  320.85  4408.9  308.62  4475.3  307.84  4556.3  304.66
  4673.2  304.04  4709.1   305.9  4764.9  304.04    4913  304.63  4942.9  302.03
  4947.9  303.63  4973.1  302.46  4990.2  293.54  4992.9  293.04  4996.2  293.54
  5013.2  294.05  5053.3  300.22  5085.4  301.77  5092.4  302.96  5129.1  305.26
  5203.6  303.53  5246.9  306.28    5328  305.44  5386.5  310.01  5514.3  316.84
  5557.7  320.93  5572.3  323.79  5578.6  323.04  5607.8  326.12    5676  326.69
#Mann= 5 ,-1 , 0
  3970.7     .05       0  4990.2     .03       0  4996.2     .05       0
  5085.4     .16       0  5129.1     .05       0
Bank Sta=4947.9,5092.4
XS Rating Curve= 0 ,0
Exp/Cntr=0.3,0.1

Type RM Length L Ch R = 1 ,6097    ,540,540,540
BEGIN DESCRIPTION:
HAMMOND CREEK 7.0
END DESCRIPTION:
XS GIS Cut Line= 3
      3822444.72     10493759.51      3821264.16     10493716.11
      3820196.47     10494948.73
#Sta/Elev= 30
    3727  322.06  3852.2  322.16  4312.5   315.5  4492.6  310.41  4642.7  303.49
  4852.9   300.1  4917.8  300.92    4971  302.01  4992.9  291.54  5010.8   289.8
  5013.5   289.3  5016.8   289.8  5020.4  292.84  5063.2  301.66  5124.3  301.36
  5304.4  304.21  5382.3   302.1  5750.8  304.09  5899.9   313.2  5985.4  314.64
  6084.2  320.66  6098.4  318.55  6119.3  319.46  6126.9  322.57  6147.8  324.59
  6233.3  329.65  6367.5   332.4  6474.6  332.38  6493.1  334.36  6539.1  334.64
#Mann= 7 ,-1 , 0
    3727     .05       0  4917.8     .16       0  5010.8     .07       0
  5016.8     .16       0  5124.3     .05       0  6367.5     .08       0
  6493.1     .05       0
Bank Sta=4971,5063.2
XS Rating Curve= 0 ,0
Exp/Cntr=0.3,0.1

Type RM Length L Ch R = 1 ,5557    ,478,478,478
BEGIN DESCRIPTION:
HAMMOND CREEK 6.0
END DESCRIPTION:
XS GIS Cut Line= 4
      3821599.58     10493410.18      3821049.61     10493310.19
      3820149.61     10494510.19      3819779.78     10494723.06
#Sta/Elev= 30
  4410.8  313.24  4549.3  306.76  4705.5  307.78  4777.9   304.5  4878.3  304.22
  4972.9  299.27  4988.2   289.6  4988.7  289.17  4991.4  288.67  4994.7  289.17
  5019.8  296.07  5033.3  295.78  5041.7  297.85  5047.9  296.06  5069.8  298.95
  5127.1  297.39  5147.9  299.67  5174.5  299.55  5469.8  302.63  5541.7  301.23
  5606.2  303.56  5741.7  300.83  6127.1  302.74  6341.7  311.33    6505     330
  6601.3  330.84  6622.8  326.75  6644.4  325.79  6660.2  330.88  6896.5  333.47
#Mann= 5 ,-1 , 0
  4410.8     .05       0  4988.2     .16       0  4988.7     .07       0
  4994.7     .16       0  5174.5     .05       0
Bank Sta=4972.9,5069.8
XS Rating Curve= 0 ,0
Exp/Cntr=0.3,0.1

Type RM Length L Ch R = 1 ,5079    ,493,493,493
BEGIN DESCRIPTION:
HAMMOND CREEK 5.0
END DESCRIPTION:
XS GIS Cut Line= 4
      3821599.62     10493360.19      3820799.61     10493060.19
      3820199.61     10493110.19      3819406.52      10493499.1
#Sta/Elev= 30
  4185.2  314.31  4377.5  305.02  4409.5     306  4517.2  302.05  4657.8  301.44
  4676.5  299.58  4804.7  297.77  4907.2  298.73  4932.8  297.49  4954.2  298.79
  4969.3  296.59  4975.5  297.54  5004.6  288.21  5007.3  287.71  5010.6  288.21
  5036.9  295.82  5059.7  298.47  5099.1  297.89  5129.9  299.16  5300.5  297.78
  5370.8  300.32  5501.2  309.85  5611.6  322.89  5700.7  326.05  5835.7   327.8
  6319.5  328.27  6375.5  325.44  6387.9  328.04  6431.7  327.29    6525  328.69
#Mann= 7 ,-1 , 0
  4185.2     .05       0  4907.2     .16       0  5004.6     .07       0
  5010.6     .16       0  5099.1     .05       0  6319.5     .08       0
  6431.7     .05       0
Bank Sta=4954.2,5059.7
XS Rating Curve= 0 ,0
Exp/Cntr=0.3,0.1

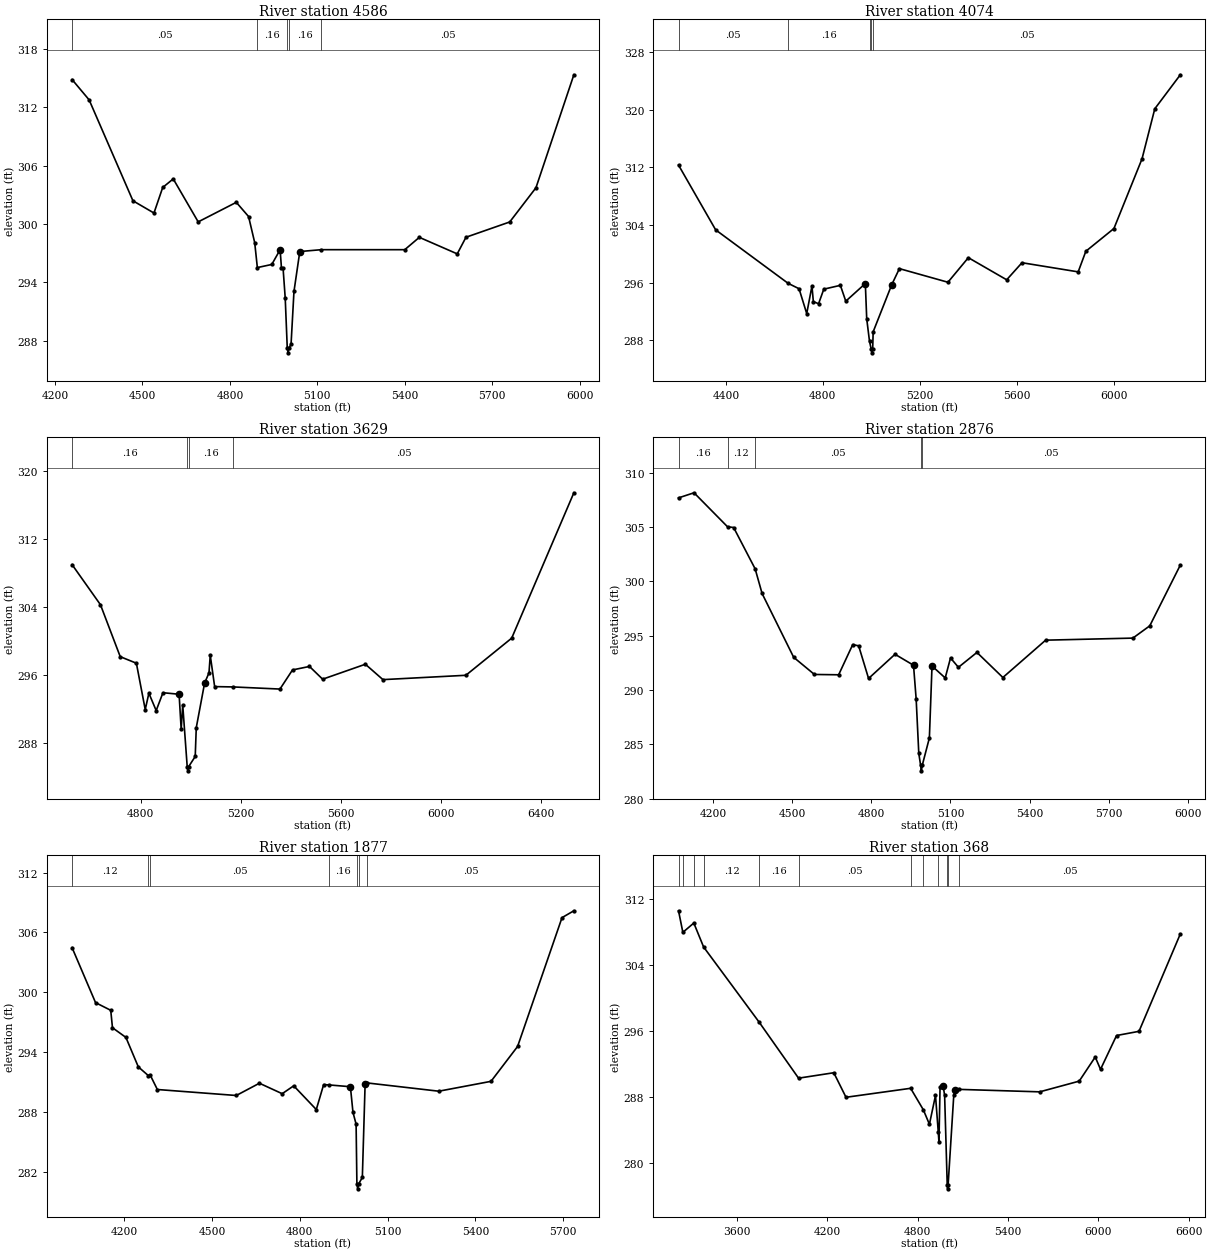
Type RM Length L Ch R = 1 ,4586    ,512,512,512
BEGIN DESCRIPTION:
HAMMOND CREEK 4.0
END DESCRIPTION:
XS GIS Cut Line= 3
      3821749.58     10493210.17      3821149.61     10492810.19
      3820149.58     10492810.19
#Sta/Elev= 30
  4258.7  314.87  4317.2  312.78  4467.5   302.4  4539.6  301.14  4569.6  303.77
  4605.7  304.65  4691.3  300.23    4822  302.24  4864.1  300.78  4885.1   298.1
  4894.2  295.53  4943.7  295.85  4972.3  297.37  4976.8  295.52  4982.3  295.52
  4989.8  292.39  4996.8  287.26  4999.5  286.76  5002.8  287.26  5009.8  287.64
  5019.8  293.07  5039.8  297.18  5113.6  297.37  5399.8  297.37  5449.8  298.64
  5579.8  296.94  5609.8  298.65  5759.8  300.22  5849.8  303.74  5979.8  315.36
#Mann= 5 ,-1 , 0
  4258.7     .05       0  4894.2     .16       0  4996.8     .07       0
  5002.8     .16       0  5113.6     .05       0
Bank Sta=4972.3,5039.8
XS Rating Curve= 0 ,0
Exp/Cntr=0.3,0.1

Type RM Length L Ch R = 1 ,4074    ,445,445,445
BEGIN DESCRIPTION:
HAMMOND CREEK 3.0
END DESCRIPTION:
XS GIS Cut Line= 3
      3821899.61     10492810.19      3821199.61     10492410.19
      3819999.65     10492810.18
#Sta/Elev= 30
  4204.7   312.3    4358  303.31    4657  295.89  4702.1  295.14  4733.8  291.69
  4755.4  295.52  4761.1  293.35  4782.7  293.06  4804.3  295.08  4872.7  295.61
    4895  293.41  4975.7  295.86  4981.4  290.96  4992.9  287.85    5000  286.74
  5002.8  286.24    5006  286.74    5008  289.16  5084.7   295.7  5116.3  297.93
  5316.6  296.04  5400.9  299.45  5559.1  296.38  5622.3  298.75  5854.2  297.48
  5885.8  300.34  6001.8   303.5  6117.7  313.17  6170.4  320.12  6275.8  324.84
#Mann= 5 ,-1 , 0
  4204.7     .05       0    4657     .16       0  4992.9     .05       0
    5000     .03       0    5006     .05       0
Bank Sta=4975.7,5084.7
XS Rating Curve= 0 ,0
Exp/Cntr=0.3,0.1

Type RM Length L Ch R = 1 ,3629    ,753,753,753
BEGIN DESCRIPTION:
HAMMOND CREEK 2.0
END DESCRIPTION:
XS GIS Cut Line= 3
      3821899.64     10492510.21      3821499.61     10492210.19
      3819999.63     10492360.19
#Sta/Elev= 30
  4525.9  308.99  4639.5  304.27  4718.6  298.16  4783.2  297.39  4818.6  291.94
  4833.2  293.86  4862.4  291.82  4889.5  293.92  4954.1  293.74  4962.4  289.64
  4968.6  292.47  4986.5  285.23  4989.2  284.73  4992.5  285.23  5018.6  286.42
  5022.8  289.81  5056.1  295.05  5073.7  296.26  5078.7  298.33  5096.3  294.64
  5170.7   294.6  5357.6  294.35  5407.8   296.6  5475.7  297.01  5528.4  295.51
  5699.3  297.27  5769.6  295.46  6101.3  295.97  6284.7  300.34  6533.4  317.44
#Mann= 4 ,-1 , 0
  4525.9     .16       0  4986.5     .07       0  4992.5     .16       0
  5170.7     .05       0
Bank Sta=4954.1,5056.1
XS Rating Curve= 0 ,0
Exp/Cntr=0.3,0.1

Type RM Length L Ch R = 1 ,2876    ,999,999,999
BEGIN DESCRIPTION:
Mapping XS 849933f3
END DESCRIPTION:
XS GIS Cut Line= 3
      3822194.23      10491953.4      3821584.87     10491713.82
      3820340.07     10491781.53
#Sta/Elev= 30
  4069.5   307.7  4128.2  308.17  4255.1  305.04  4278.3  304.97  4359.8  301.16
  4386.1  298.89  4505.8  293.01  4584.4  291.43  4676.2   291.4  4729.5  294.18
    4752  294.07  4789.6  291.06  4889.8  293.29  4959.9  292.28  4969.9  289.17
  4979.9  284.15  4986.9  283.05  4989.7  282.55  4992.9  283.05    5020  285.58
    5030  292.21    5080  291.11  5100.1  292.95  5130.1  292.09  5200.2  293.46
  5298.5  291.15  5460.6  294.59  5791.1  294.78  5855.1  295.91  5970.9  301.51
#Mann= 5 ,-1 , 0
  4069.5     .16       0  4255.1     .12       0  4359.8     .05       0
  4986.9     .03       0  4992.9     .05       0
Bank Sta=4959.9,5030
XS Rating Curve= 0 ,0
Exp/Cntr=0.3,0.1

Type RM Length L Ch R = 1 ,1877    ,1509,1509,1509
BEGIN DESCRIPTION:
Mapping XS 0f774c96
END DESCRIPTION:
XS GIS Cut Line= 4
      3822084.87     10491666.95      3821751.53      10491135.7
      3821298.41     10490969.03      3820753.05     10491228.73
#Sta/Elev= 30
  4022.2  304.47  4102.4  298.95  4154.3  298.18  4160.2  296.43  4206.1  295.46
  4248.5   292.5  4282.6  291.63  4288.4  291.72  4313.5  290.23  4583.1  289.63
  4662.1  290.86  4739.9  289.81  4779.3   290.6  4856.4  288.22  4881.5  290.72
  4899.9  290.69  4972.9  290.51  4981.7  287.94  4992.4  286.75  4995.1  280.76
  4997.8  280.26  5001.1  280.76  5013.7   281.4  5023.2  290.81  5030.1  290.89
  5274.8  290.06  5453.2  291.05    5544  294.55  5695.7  307.48  5736.2  308.17
#Mann= 7 ,-1 , 0
  4022.2     .12       0  4282.6     .16       0  4288.4     .05       0
  4899.9     .16       0  4995.1     .07       0  5001.1     .16       0
  5030.1     .05       0
Bank Sta=4972.9,5023.2
XS Rating Curve= 0 ,0
Exp/Cntr=0.3,0.1

Type RM Length L Ch R = 1 ,368     ,0,0,0
BEGIN DESCRIPTION:
HAMMOND CREEK 1.0
END DESCRIPTION:
XS GIS Cut Line= 4
      3822279.31     10491957.75      3822022.37     10490396.12
      3821595.28     10490333.62      3820595.28     10491192.99
#Sta/Elev= 30
  3212.3  310.61    3241  307.99  3313.8  309.12  3378.9  306.21    3749  297.05
  4009.5  290.28  4243.5  290.94  4324.6  287.96  4753.9  289.05  4838.2  286.44
  4878.6  284.68    4919  288.18  4937.6  283.69  4941.9  282.53  4949.3  289.22
  4969.5  289.37  4979.6   288.2  4996.9  277.34  4999.6  276.84  5002.9  277.34
  5040.3  288.18  5050.4  288.82  5074.4  288.92  5611.2  288.62  5873.5  289.92
  5979.9  292.85    6015  291.35  6121.5  295.46  6270.7  295.97  6545.1   307.8
#Mann= 12 ,-1 , 0
  3212.3     .16       0    3241     .12       0  3313.8     .16       0
  3378.9     .12       0    3749     .16       0  4009.5     .05       0
  4753.9      .1       0  4838.2     .12       0  4937.6     .16       0
  4996.9     .07       0  5002.9     .16       0  5074.4     .05       0
Bank Sta=4969.5,5050.4
XS Rating Curve= 0 ,0
Exp/Cntr=0.3,0.1

Chan Stop Cuts=-1
Use User Specified Reach Order=0
Composite Channel Slope=5