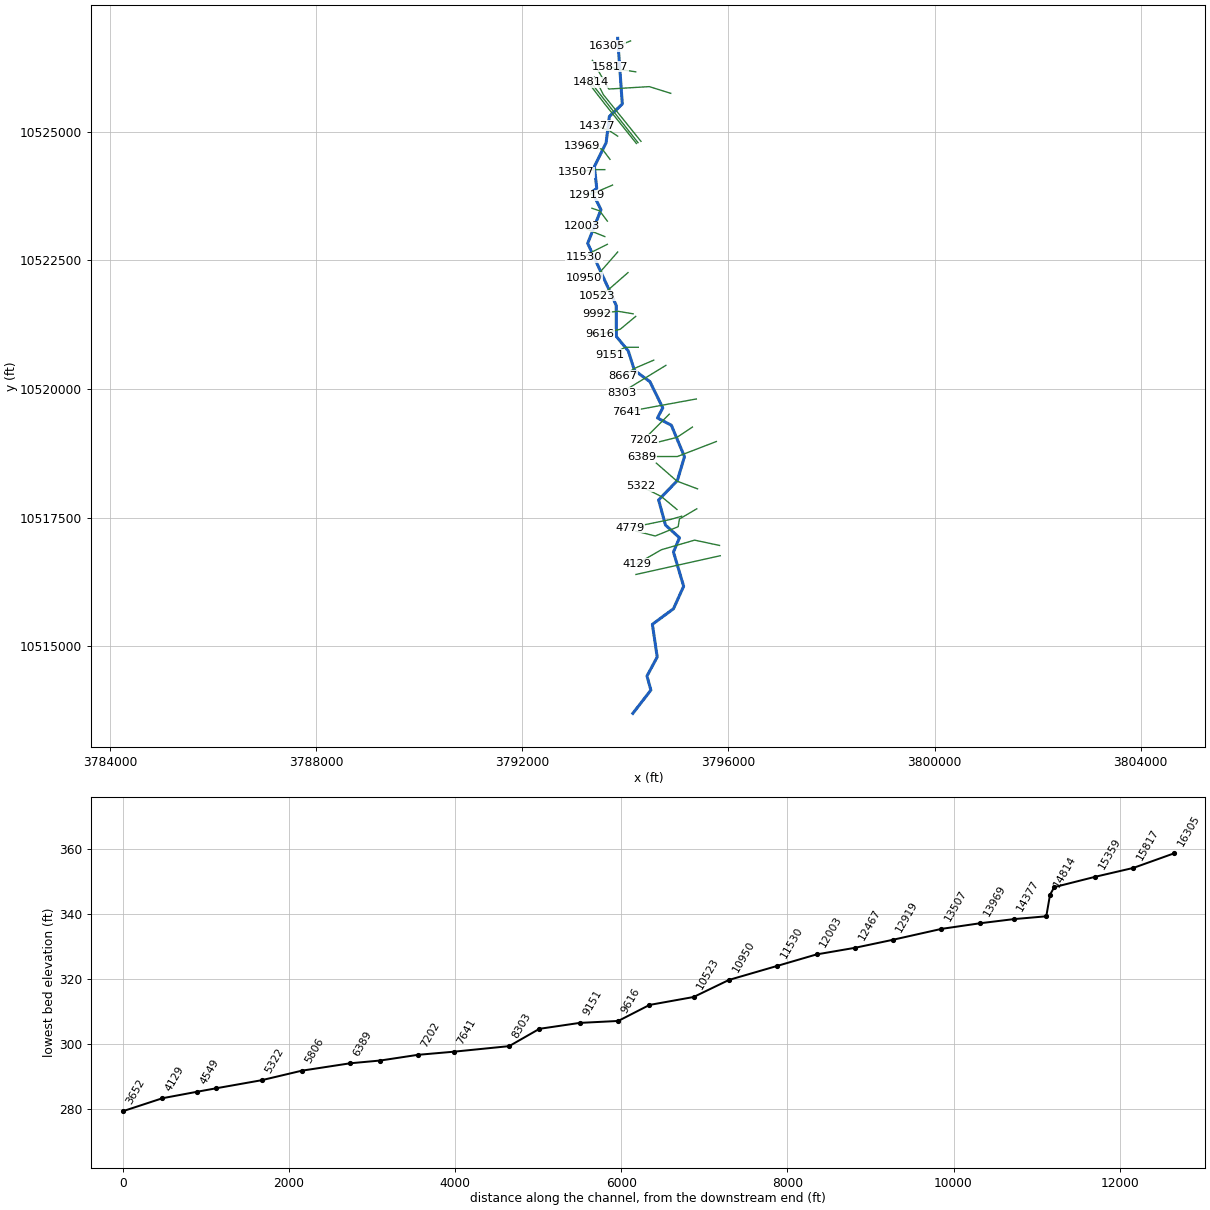
--- HAYS BRANCH.prj (project) ---

Proj Title=HAYS BRANCH Base Level Engineering
Current Plan=p01
Default Exp/Contr=0.3,0.1
English Units
Geom File=g01
Flow File=f01
Plan File=p01
BEGIN DESCRIPTION:
HAYS BRANCH
END DESCRIPTION:

--- HAYS BRANCH.p01 (plan) ---

Plan Title=Multiple Run
Short Identifier=Multiple
Geom File=g01
Flow File=f01
Subcritical Flow
K Sum by GR= 0
Std Step Tol= 0.01
Critical Tol= 0.01
Num of Std Step Trials= 20
Max Error Tol= 0.3
Flow Tol Ratio= 0.001
Split Flow NTrial= 30
Split Flow Tol= 0.02
Split Flow Ratio= 0.02
Log Output Level= 0
Friction Slope Method= 1
Unsteady Friction Slope Method= 2
Unsteady Bridges Friction Slope Method= 1
Parabolic Critical Depth
Global Vel Dist=  1 , 1 , 1
Global Log Level= 0
CheckData=True
Encroach Param= -1, 0, 0, 0
BEGIN DESCRIPTION:
Multiple Run
END DESCRIPTION:

--- HAYS BRANCH.f01 (steady flow) ---

Flow Title=Multiple
Number of Profiles=7
Profile Names=10-year,25-year,50-year,1pct_min,100-year,1pct_plu,500-year
River Rch & RM= HAYS BRANCH,Reach-1,16305
     966    1348    1673    1526    2063    2790    3148
River Rch & RM= HAYS BRANCH,Reach-1,12467
    1269    1790    2238    2053    2776    3754    4289
River Rch & RM= HAYS BRANCH,Reach-1,7202
    1390    1961    2451    2247    3038    4109    4686
Boundary for River Rch & Prof#=HAYS BRANCH,Reach-1,1
Up Type=0
Dn Type=3
Dn Slope=0.005
Boundary for River Rch & Prof#=HAYS BRANCH,Reach-1,2
Up Type=0
Dn Type=3
Dn Slope=0.005
Boundary for River Rch & Prof#=HAYS BRANCH,Reach-1,3
Up Type=0
Dn Type=3
Dn Slope=0.005
Boundary for River Rch & Prof#=HAYS BRANCH,Reach-1,4
Up Type=0
Dn Type=3
Dn Slope=0.005
Boundary for River Rch & Prof#=HAYS BRANCH,Reach-1,5
Up Type=0
Dn Type=3
Dn Slope=0.005
Boundary for River Rch & Prof#=HAYS BRANCH,Reach-1,6
Up Type=0
Dn Type=3
Dn Slope=0.005
Boundary for River Rch & Prof#=HAYS BRANCH,Reach-1,7
Up Type=0
Dn Type=3
Dn Slope=0.005

--- HAYS BRANCH.g01 (geometry) ---

Geom Title=Existing Conditions

River Reach=HAYS BRANCH,Reach-1
Reach XY= 30
      3793849.61     10526810.19      3793939.25     10525535.00
      3793688.25     10525293.00      3793625.00     10524782.00
      3793398.25     10524322.00      3793443.00     10523896.00
      3793352.50     10523831.00      3793525.50     10523481.00
      3793267.50     10522829.00      3793821.50     10521624.00
      3793822.75     10521021.00      3794055.25     10520739.00
      3794175.25     10520360.00      3794475.25     10520143.00
      3794724.50     10519634.00      3794621.50     10519437.00
      3794891.25     10519296.00      3795145.75     10518685.00
      3795007.25     10518221.00      3794644.00     10517845.00
      3794777.75     10517357.00      3795049.00     10517111.00
      3794932.00     10516834.00      3795129.75     10516169.00
      3794933.00     10515733.00      3794523.00     10515429.00
      3794616.75     10514795.00      3794418.14     10514425.49
      3794493.80     10514152.00      3794144.00     10513700.00

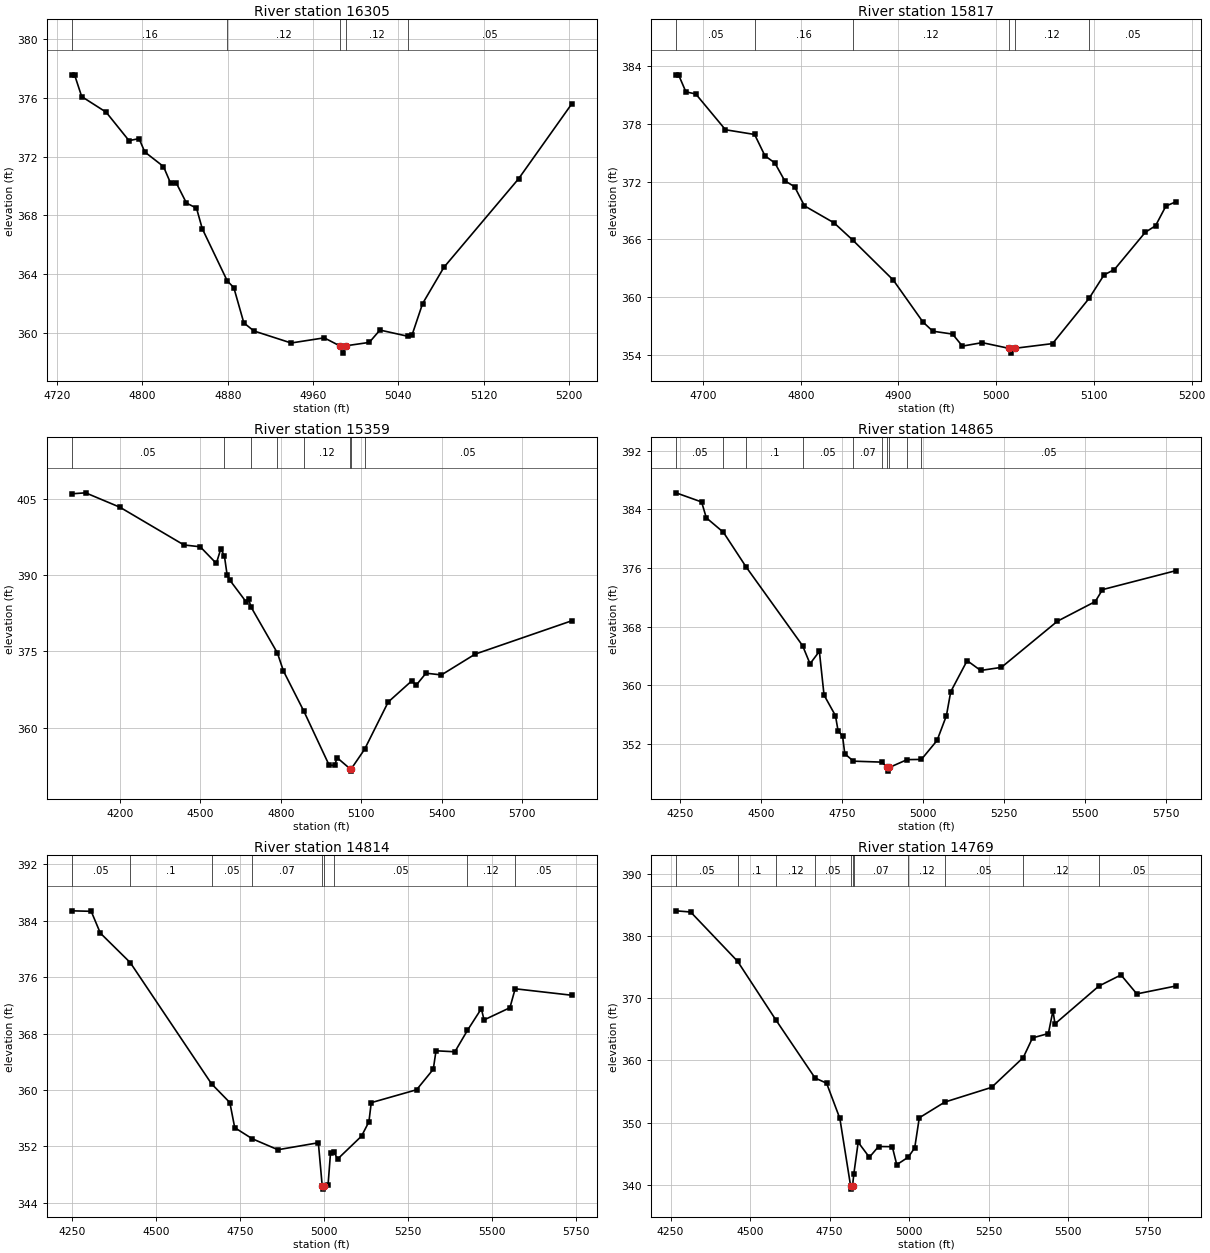
Type RM Length L Ch R = 1,16305,488,488,488
BEGIN DESCRIPTION:
HAYS BRANCH 32.0
END DESCRIPTION:
XS GIS Cut Line= 3
      3794099.58     10526760.18      3793849.61     10526660.19
      3793649.63     10526660.19
#Sta/Elev= 30
  4733.6  377.56  4736.3  377.56  4743.0  376.08  4765.9  375.02  4787.4  373.08
  4796.8  373.22  4802.2  372.31  4819.7  371.32  4826.5  370.17  4831.8  370.19
  4841.3  368.83  4850.7  368.49  4856.1  367.09  4879.6  363.53  4885.7  363.08
  4895.1  360.68  4904.5  360.13  4939.5  359.31  4970.5  359.66  4985.0  359.12
  4987.8  358.62  4991.0  359.12  5012.8  359.35  5022.8  360.19  5048.8  359.77
  5052.8  359.83  5062.8  361.99  5082.8  364.46  5152.8  370.48  5202.8  375.59
#Mann=5,-1,0
  4733.6    0.16       0  4879.6    0.12       0  4985.0    0.07       0
  4991.0    0.12       0  5048.8    0.05       0
Bank Sta=4985,4991
Exp/Cntr=0.3,0.1

Type RM Length L Ch R = 1,15817,458,458,458
BEGIN DESCRIPTION:
HAYS BRANCH 31.0
END DESCRIPTION:
XS GIS Cut Line= 3
      3794199.65     10526160.18      3793849.61     10526210.19
      3793699.62     10526260.18
#Sta/Elev= 30
  4672.4  383.09  4675.0  383.09  4682.5  381.32  4692.6  381.10  4723.0  377.38
  4752.8  376.89  4763.4  374.67  4773.5  373.93  4783.6  372.08  4793.7  371.46
  4803.8  369.47  4834.1  367.70  4853.2  365.91  4894.7  361.75  4925.0  357.40
  4935.1  356.44  4955.3  356.14  4965.4  354.89  4985.6  355.25  5012.9  354.66
  5015.6  354.16  5018.9  354.66  5057.6  355.15  5095.0  359.85  5110.3  362.29
  5120.9  362.85  5152.5  366.72  5163.0  367.40  5173.6  369.45  5184.1  369.90
#Mann=6,-1,0
  4672.4    0.05       0  4752.8    0.16       0  4853.2    0.12       0
  5012.9    0.07       0  5018.9    0.12       0  5095.0    0.05       0
Bank Sta=5012.9,5018.9
Exp/Cntr=0.3,0.1

Type RM Length L Ch R = 1,15359,494,494,494
BEGIN DESCRIPTION:
HAYS BRANCH 30.0
END DESCRIPTION:
XS GIS Cut Line= 4
      3794879.24     10525742.21      3794462.61     10525872.40
      3793676.16     10525825.53      3793358.47     10526382.78
#Sta/Elev= 30
  4019.6  405.98  4071.6  406.17  4199.9  403.33  4438.3  395.92  4499.2  395.56
  4559.3  392.29  4575.8  395.15  4589.4  393.75  4599.4  390.06  4609.4  389.01
  4669.5  384.79  4679.5  385.34  4688.2  383.76  4787.1  374.67  4809.7  371.12
  4885.9  363.21  4980.0  352.62  5000.1  352.55  5010.1  354.07  5057.2  351.94
  5059.9  351.44  5063.2  351.94  5112.4  355.74  5200.4  365.03  5288.5  369.20
  5304.4  368.32  5341.4  370.70  5399.0  370.36  5524.8  374.45  5885.4  381.01
#Mann=8,-1,0
  4019.6    0.05       0  4589.4     0.1       0  4688.2    0.16       0
  4787.1     0.1       0  4885.9    0.12       0  5057.2    0.07       0
  5063.2    0.12       0  5112.4    0.05       0
Bank Sta=5057.2,5063.2
Exp/Cntr=0.3,0.1

Type RM Length L Ch R = 1,14865,51,51,51
BEGIN DESCRIPTION:
Mapping XS ffb44e50
END DESCRIPTION:
XS GIS Cut Line= 3
      3794301.17     10524809.88      3793571.99     10525716.15
      3793400.10     10526054.72
#Sta/Elev= 30
  4237.2  386.26  4316.2  385.01  4330.6  382.85  4383.4  380.87  4453.4  376.14
  4627.7  365.38  4650.6  362.91  4679.4  364.61  4693.8  358.64  4729.0  355.83
  4737.0  353.79  4751.0  353.03  4757.8  350.62  4784.5  349.61  4872.0  349.48
  4889.2  348.75  4891.9  348.25  4895.2  348.75  4950.1  349.82  4994.2  349.85
  5042.5  352.44  5071.3  355.82  5084.7  359.10  5135.3  363.34  5176.9  362.00
  5240.9  362.42  5413.6  368.72  5530.5  371.41  5552.8  373.04  5780.1  375.64
#Mann=10,-1,0
  4237.2    0.05       0  4383.4    0.16       0  4453.4     0.1       0
  4627.7    0.05       0  4784.5    0.07       0  4872.0    0.05       0
  4889.2    0.03       0  4895.2    0.05       0  4950.1    0.07       0
  4994.2    0.05       0
Bank Sta=4889.2,4895.2
Exp/Cntr=0.3,0.1

Type RM Length L Ch R = 1,14814,45,45,45
BEGIN DESCRIPTION:
HAYS BRANCH 29.0
END DESCRIPTION:
XS GIS Cut Line= 2
      3794243.85     10524783.88      3793327.43     10525955.44
#Sta/Elev= 30
  4248.9  385.41  4307.0  385.34  4334.1  382.25  4423.0  378.07  4664.9  360.86
  4719.3  358.20  4733.8  354.64  4785.8  353.07  4862.2  351.51  4982.5  352.50
  4993.9  346.42  4996.7  345.92  4999.9  346.42  5011.4  346.53  5018.7  351.07
  5027.7  351.21  5040.3  350.21  5110.9  353.44  5132.9  355.48  5139.8  358.19
  5274.6  360.02  5324.3  362.93  5332.4  365.55  5388.5  365.41  5425.9  368.45
  5467.2  371.52  5475.3  369.93  5552.2  371.66  5567.8  374.35  5736.3  373.43
#Mann=9,-1,0
  4248.9    0.05       0  4423.0     0.1       0  4664.9    0.05       0
  4785.8    0.07       0  4993.9    0.07       0  4999.9    0.07       0
  5027.7    0.05       0  5425.9    0.12       0  5567.8    0.05       0
Bank Sta=4993.9,4999.9
Exp/Cntr=0.3,0.1

Type RM Length L Ch R = 1,14769,392,392,392
BEGIN DESCRIPTION:
Mapping XS 72eb4f33
END DESCRIPTION:
XS GIS Cut Line= 3
      3794212.59     10524768.27      3793608.45     10525523.44
      3793238.63     10526002.64
#Sta/Elev= 30
  4267.3  384.08  4313.3  383.89  4460.7  375.97  4580.7  366.56  4704.5  357.17
  4740.7  356.34  4782.4  350.66  4816.2  339.79  4818.9  339.29  4822.2  339.79
  4826.4  341.78  4840.0  346.83  4875.2  344.42  4904.0  346.15  4947.2  346.12
  4961.3  343.22  4997.5  344.44  5017.7  345.93  5032.1  350.77  5112.3  353.30
  5259.5  355.67  5359.0  360.47  5388.1  363.63  5437.9  364.33  5452.4  368.01
  5458.7  365.89  5596.6  371.97  5666.2  373.76  5716.0  370.71  5839.7  371.99
#Mann=11,-1,0
  4267.3    0.05       0  4460.7     0.1       0  4580.7    0.12       0
  4704.5    0.05       0  4816.2    0.07       0  4822.2    0.05       0
  4826.4    0.07       0  4997.5    0.12       0  5112.3    0.05       0
  5359.0    0.12       0  5596.6    0.05       0
Bank Sta=4816.2,4822.2
Exp/Cntr=0.3,0.1

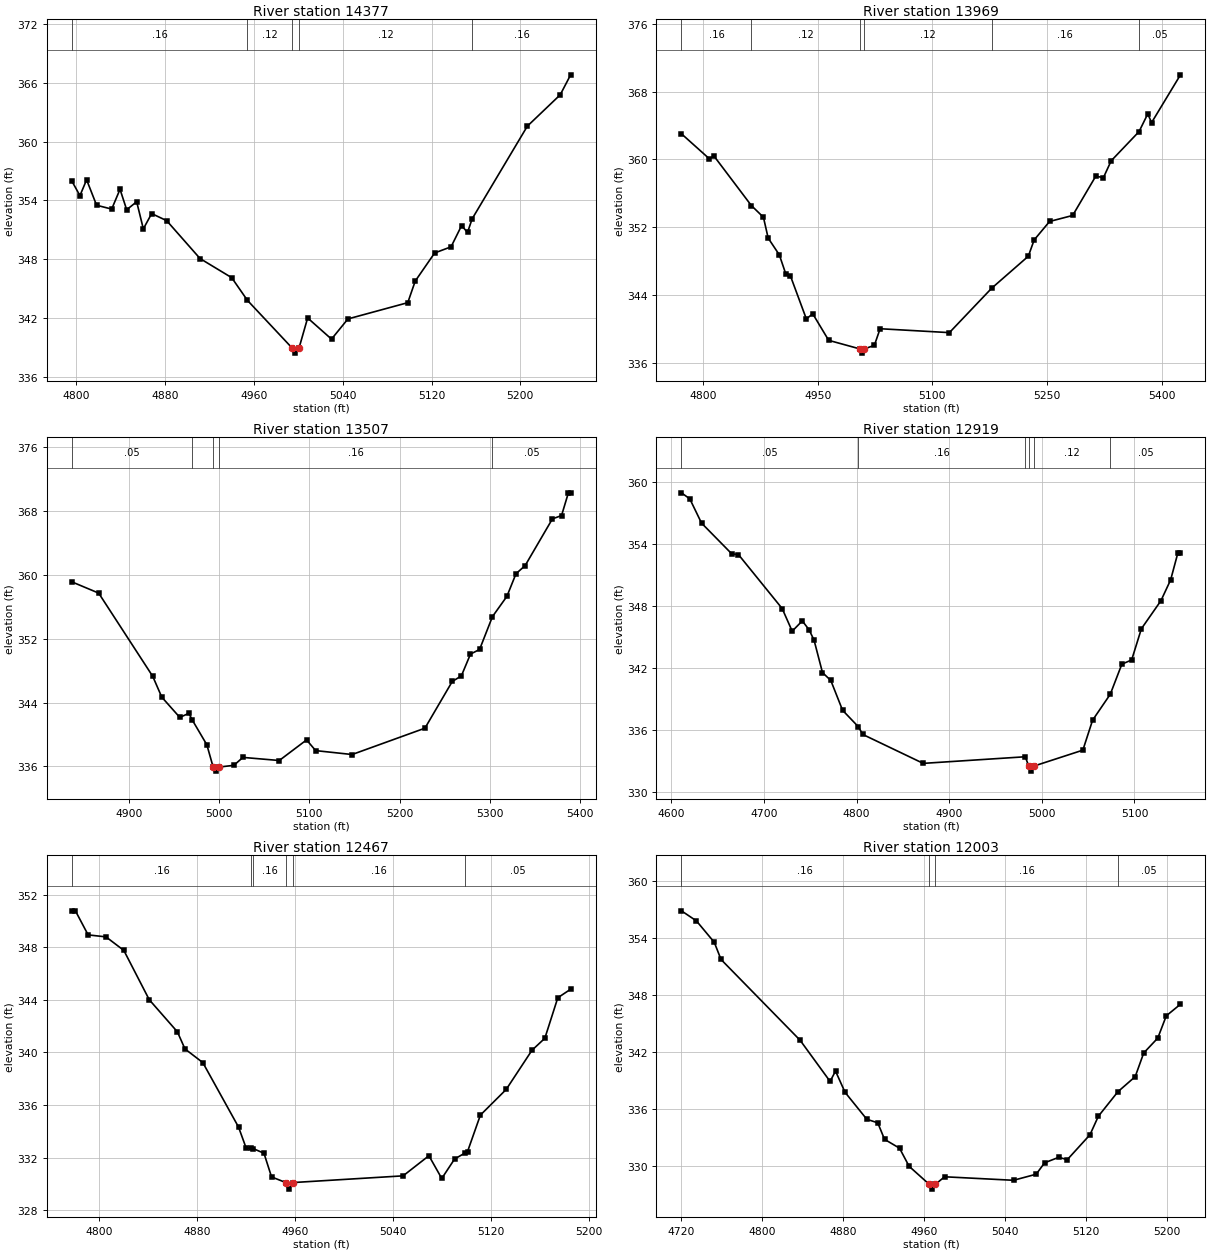
Type RM Length L Ch R = 1,14377,408,408,408
BEGIN DESCRIPTION:
HAYS BRANCH 28.0
END DESCRIPTION:
XS GIS Cut Line= 3
      3793849.62     10524910.18      3793699.61     10525010.19
      3793449.65     10525110.17
#Sta/Elev= 30
  4795.8  356.02  4803.3  354.49  4809.3  356.11  4818.3  353.51  4831.9  353.12
  4839.4  355.14  4845.4  353.05  4854.4  353.87  4860.4  351.10  4867.9  352.66
  4881.4  351.94  4911.5  348.07  4940.0  346.12  4954.2  343.80  4994.6  338.92
  4997.4  338.42  5000.6  338.92  5008.4  342.01  5029.9  339.85  5044.7  341.91
  5098.6  343.57  5105.3  345.77  5122.8  348.64  5137.6  349.27  5147.1  351.44
  5152.4  350.73  5156.6  352.13  5206.3  361.58  5235.9  364.78  5245.3  366.82
#Mann=5,-1,0
  4795.8    0.16       0  4954.2    0.12       0  4994.6    0.07       0
  5000.6    0.12       0  5156.6    0.16       0
Bank Sta=4994.6,5000.6
Exp/Cntr=0.3,0.1

Type RM Length L Ch R = 1,13969,462,462,462
BEGIN DESCRIPTION:
HAYS BRANCH 27.0
END DESCRIPTION:
XS GIS Cut Line= 3
      3793699.59     10524460.21      3793549.61     10524660.19
      3793149.59     10524710.19
#Sta/Elev= 30
  4771.6  363.03  4808.0  360.09  4814.3  360.39  4863.1  354.56  4878.9  353.18
  4885.1  350.72  4899.7  348.74  4908.0  346.53  4914.3  346.24  4935.1  341.17
  4943.4  341.79  4964.3  338.65  5005.0  337.64  5007.8  337.14  5011.0  337.64
  5024.1  338.06  5031.6  340.02  5122.3  339.56  5177.6  344.80  5225.6  348.58
  5233.2  350.50  5253.4  352.68  5283.6  353.39  5313.8  358.02  5323.9  357.86
  5334.0  359.84  5370.5  363.29  5381.9  365.38  5386.9  364.35  5424.7  369.99
#Mann=6,-1,0
  4771.6    0.16       0  4863.1    0.12       0  5005.0    0.07       0
  5011.0    0.12       0  5177.6    0.16       0  5370.5    0.05       0
Bank Sta=5005,5011
Exp/Cntr=0.3,0.1

Type RM Length L Ch R = 1,13507,588,588,588
BEGIN DESCRIPTION:
HAYS BRANCH 26.0
END DESCRIPTION:
XS GIS Cut Line= 3
      3793599.58     10524260.19      3793399.61     10524260.19
      3793049.63     10524210.19
#Sta/Elev= 30
  4836.3  359.14  4866.3  357.72  4926.3  347.29  4936.3  344.69  4956.3  342.15
  4966.3  342.66  4970.2  341.81  4986.3  338.72  4993.3  335.92  4996.0  335.42
  4999.3  335.92  5016.3  336.15  5026.3  337.14  5066.6  336.75  5096.9  339.33
  5107.0  337.99  5147.4  337.50  5228.2  340.80  5258.5  346.65  5268.6  347.35
  5278.7  350.08  5288.8  350.66  5303.1  354.78  5319.1  357.31  5329.2  360.15
  5339.3  361.16  5369.6  367.02  5379.7  367.43  5387.3  370.28  5389.8  370.28
#Mann=5,-1,0
  4836.3    0.05       0  4970.2    0.16       0  4993.3    0.07       0
  4999.3    0.16       0  5303.1    0.05       0
Bank Sta=4993.3,4999.3
Exp/Cntr=0.3,0.1

Type RM Length L Ch R = 1,12919,452,452,452
BEGIN DESCRIPTION:
HAYS BRANCH 25.0
END DESCRIPTION:
XS GIS Cut Line= 3
      3793749.58     10523960.17      3793399.61     10523810.19
      3793249.58     10523760.18
#Sta/Elev= 30
  4610.8  358.98  4619.8  358.40  4632.5  356.05  4665.2  353.07  4672.4  353.00
  4719.6  347.78  4730.4  345.59  4741.3  346.59  4748.6  345.73  4754.0  344.73
  4763.1  341.59  4772.1  340.82  4784.8  337.94  4801.9  336.34  4806.6  335.60
  4871.9  332.80  4982.1  333.44  4985.8  332.55  4988.6  332.05  4991.8  332.55
  5044.3  334.08  5054.8  336.98  5073.9  339.49  5086.4  342.40  5097.0  342.81
  5107.5  345.83  5128.6  348.54  5139.1  350.56  5147.0  353.20  5149.7  353.20
#Mann=6,-1,0
  4610.8    0.05       0  4801.9    0.16       0  4982.1    0.12       0
  4985.8    0.07       0  4991.8    0.12       0  5073.9    0.05       0
Bank Sta=4985.8,4991.8
Exp/Cntr=0.3,0.1

Type RM Length L Ch R = 1,12467,464,464,464
BEGIN DESCRIPTION:
HAYS BRANCH 24.0
END DESCRIPTION:
XS GIS Cut Line= 3
      3793649.61     10523260.19      3793499.61     10523460.19
      3793349.62     10523510.18
#Sta/Elev= 30
  4777.2  350.77  4780.3  350.77  4790.7  348.94  4805.3  348.79  4819.9  347.76
  4840.7  344.01  4863.7  341.57  4869.9  340.27  4884.5  339.23  4913.7  334.33
  4919.9  332.74  4924.3  332.70  4925.7  332.69  4934.5  332.34  4940.7  330.54
  4952.3  330.11  4955.1  329.61  4958.3  330.11  5048.3  330.62  5069.4  332.15
  5079.9  330.42  5090.4  331.90  5098.6  332.34  5101.0  332.47  5111.5  335.24
  5132.6  337.19  5153.7  340.17  5164.2  341.08  5174.8  344.16  5185.3  344.81
#Mann=6,-1,0
  4777.2    0.16       0  4924.3    0.07       0  4925.7    0.16       0
  4952.3    0.07       0  4958.3    0.16       0  5098.6    0.05       0
Bank Sta=4952.3,4958.3
Exp/Cntr=0.3,0.1

Type RM Length L Ch R = 1,12003,473,473,473
BEGIN DESCRIPTION:
HAYS BRANCH 23.0
END DESCRIPTION:
XS GIS Cut Line= 3
      3793599.65     10522960.17      3793349.61     10523060.19
      3793149.61     10523160.19
#Sta/Elev= 30
  4720.7  356.86  4735.5  355.80  4753.1  353.55  4759.8  351.74  4837.9  343.24
  4867.5  338.91  4872.9  339.99  4882.3  337.76  4903.8  334.92  4914.6  334.55
  4921.3  332.81  4936.1  331.88  4945.6  329.97  4965.5  328.07  4968.2  327.57
  4971.5  328.07  4980.6  328.87  5048.7  328.50  5071.1  329.14  5079.4  330.34
  5093.4  330.92  5101.8  330.67  5124.2  333.29  5132.5  335.24  5151.8  337.82
  5168.9  339.41  5177.3  341.90  5191.2  343.47  5199.6  345.81  5213.6  347.03
#Mann=4,-1,0
  4720.7    0.16       0  4965.5    0.07       0  4971.5    0.16       0
  5151.8    0.05       0
Bank Sta=4965.5,4971.5
Exp/Cntr=0.3,0.1

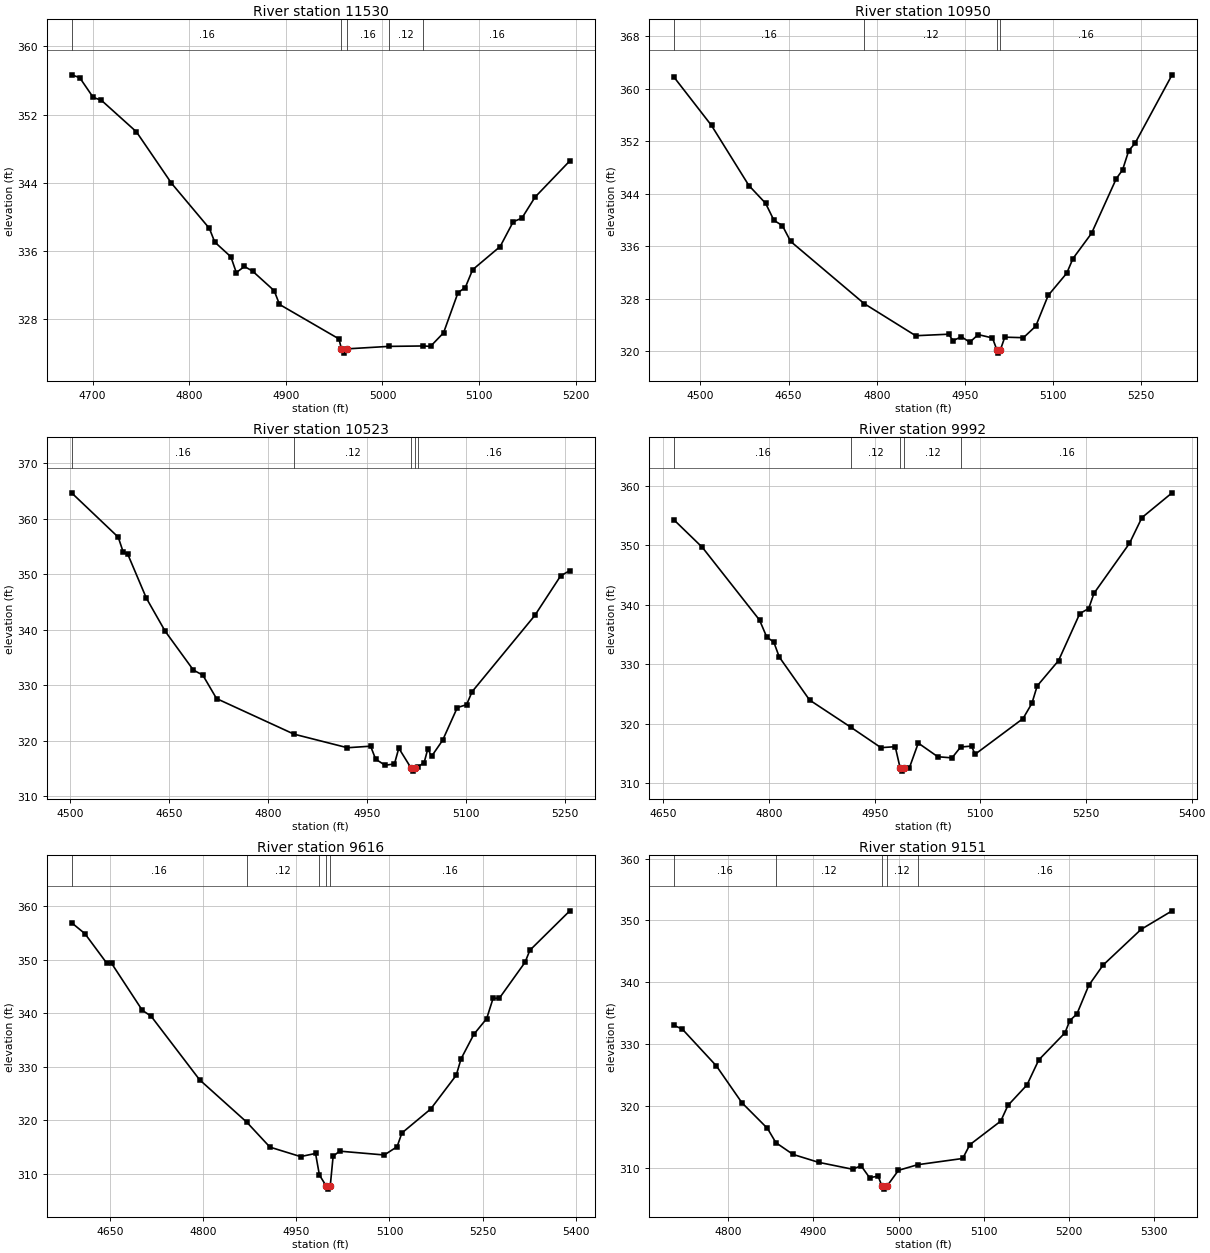
Type RM Length L Ch R = 1,11530,580,580,580
BEGIN DESCRIPTION:
HAYS BRANCH 22.0
END DESCRIPTION:
XS GIS Cut Line= 3
      3793649.63     10522810.20      3793349.61     10522660.19
      3793199.62     10522560.20
#Sta/Elev= 30
  4678.2  356.67  4686.6  356.34  4700.6  354.02  4709.0  353.69  4745.3  349.99
  4781.6  343.96  4820.8  338.67  4826.4  337.06  4843.1  335.33  4848.7  333.48
  4857.1  334.20  4865.5  333.66  4887.9  331.36  4893.4  329.75  4954.9  325.71
  4957.5  324.54  4960.3  324.04  4963.5  324.54  5006.3  324.83  5042.2  324.88
  5049.7  324.83  5063.2  326.42  5078.2  331.14  5085.7  331.73  5093.3  333.82
  5121.8  336.54  5135.3  339.44  5144.3  339.87  5157.9  342.33  5193.9  346.58
#Mann=5,-1,0
  4678.2    0.16       0  4957.5    0.07       0  4963.5    0.16       0
  5006.3    0.12       0  5042.2    0.16       0
Bank Sta=4957.5,4963.5
Exp/Cntr=0.3,0.1

Type RM Length L Ch R = 1,10950,427,427,427
BEGIN DESCRIPTION:
HAYS BRANCH 21.0
END DESCRIPTION:
XS GIS Cut Line= 3
      3793849.61     10522660.20      3793499.61     10522260.19
      3793199.65     10522160.20
#Sta/Elev= 30
  4454.7  361.78  4518.8  354.39  4582.4  345.25  4610.8  342.55  4625.1  339.94
  4639.3  339.16  4653.5  336.74  4778.5  327.28  4866.2  322.39  4922.2  322.62
  4929.7  321.64  4944.0  322.23  4958.2  321.40  4972.5  322.56  4996.8  322.05
  5004.3  320.24  5007.0  319.74  5010.3  320.24  5017.8  322.17  5049.5  322.09
  5070.5  323.85  5091.6  328.52  5123.2  331.91  5133.8  334.14  5165.4  337.98
  5207.6  346.32  5218.1  347.61  5228.7  350.57  5239.2  351.65  5302.4  362.10
#Mann=4,-1,0
  4454.7    0.16       0  4778.5    0.12       0  5004.3    0.07       0
  5010.3    0.16       0
Bank Sta=5004.3,5010.3
Exp/Cntr=0.3,0.1

Type RM Length L Ch R = 1,10523,531,531,531
BEGIN DESCRIPTION:
HAYS BRANCH 20.0
END DESCRIPTION:
XS GIS Cut Line= 3
      3794049.62     10522260.20      3793649.61     10521910.19
      3793449.64     10521810.20
#Sta/Elev= 30
  4502.2  364.69  4572.9  356.69  4580.5  353.98  4587.2  353.66  4615.6  345.67
  4644.1  339.71  4686.8  332.71  4701.1  331.80  4721.9  327.57  4839.3  321.15
  4920.3  318.70  4955.4  318.98  4963.0  316.64  4977.3  315.54  4991.5  315.78
  4998.1  318.62  5017.0  314.98  5019.7  314.48  5023.0  314.98  5026.5  315.21
  5036.5  316.01  5042.1  318.51  5047.7  317.14  5064.5  320.04  5086.8  325.95
  5100.8  326.46  5109.2  328.81  5204.2  342.56  5243.4  349.71  5257.3  350.66
#Mann=5,-1,0
  4502.2    0.16       0  4839.3    0.12       0  5017.0    0.07       0
  5023.0    0.12       0  5026.5    0.16       0
Bank Sta=5017,5023
Exp/Cntr=0.3,0.1

Type RM Length L Ch R = 1,9992,376,376,376
BEGIN DESCRIPTION:
HAYS BRANCH 19.0
END DESCRIPTION:
XS GIS Cut Line= 3
      3794149.65     10521460.18      3793849.61     10521510.19
      3793449.61     10521460.19
#Sta/Elev= 30
  4664.9  354.33  4705.5  349.67  4786.6  337.45  4796.7  334.62  4806.9  333.73
  4814.5  331.25  4857.6  324.00  4916.6  319.39  4958.9  315.99  4979.2  316.15
  4986.2  312.54  4989.0  312.04  4992.2  312.54  4999.3  312.60  5011.9  316.76
  5039.6  314.46  5059.8  314.27  5072.1  316.10  5087.5  316.25  5092.5  314.87
  5160.6  320.88  5173.2  323.44  5180.7  326.37  5211.0  330.63  5241.2  338.55
  5253.8  339.39  5261.3  341.95  5311.7  350.36  5329.4  354.69  5372.2  358.86
#Mann=5,-1,0
  4664.9    0.16       0  4916.6    0.12       0  4986.2    0.07       0
  4992.2    0.12       0  5072.1    0.16       0
Bank Sta=4986.2,4992.2
Exp/Cntr=0.3,0.1

Type RM Length L Ch R = 1,9616,465,465,465
BEGIN DESCRIPTION:
HAYS BRANCH 18.0
END DESCRIPTION:
XS GIS Cut Line= 3
      3794199.60     10521410.18      3793899.61     10521160.19
      3793499.62     10521060.19
#Sta/Elev= 30
  4587.8  356.91  4609.3  354.86  4644.4  349.36  4652.2  349.32  4701.7  340.55
  4716.0  339.43  4794.1  327.55  4870.1  319.63  4907.4  314.97  4956.8  313.20
  4980.9  313.79  4987.1  309.76  4998.5  307.62  5001.2  307.12  5004.5  307.62
  5009.2  313.25  5019.5  314.22  5091.7  313.50  5112.3  315.05  5120.0  317.61
  5166.4  322.09  5207.6  328.41  5215.4  331.48  5236.0  336.06  5256.6  338.98
  5266.9  342.76  5277.2  342.82  5318.5  349.52  5326.2  351.76  5390.6  359.13
#Mann=5,-1,0
  4587.8    0.16       0  4870.1    0.12       0  4987.1    0.16       0
  4998.5    0.07       0  5004.5    0.16       0
Bank Sta=4998.5,5004.5
Exp/Cntr=0.3,0.1

Type RM Length L Ch R = 1,9151,484,484,484
BEGIN DESCRIPTION:
HAYS BRANCH 17.0
END DESCRIPTION:
XS GIS Cut Line= 3
      3794249.57     10520810.19      3793999.61     10520810.19
      3793699.58     10520660.17
#Sta/Elev= 30
  4736.0  333.04  4746.0  332.41  4786.0  326.46  4816.0  320.50  4846.0  316.35
  4855.9  314.04  4876.0  312.14  4906.0  310.86  4946.0  309.74  4956.0  310.30
  4966.0  308.37  4976.0  308.62  4980.5  307.02  4983.2  306.52  4986.5  307.02
  4999.9  309.56  5022.4  310.47  5075.4  311.48  5083.8  313.71  5120.1  317.53
  5128.5  320.06  5150.9  323.38  5164.8  327.44  5195.6  331.82  5201.2  333.79
  5209.6  334.87  5223.5  339.49  5240.3  342.77  5285.0  348.56  5321.4  351.56
#Mann=5,-1,0
  4736.0    0.16       0  4855.9    0.12       0  4980.5    0.07       0
  4986.5    0.12       0  5022.4    0.16       0
Bank Sta=4980.5,4986.5
Exp/Cntr=0.3,0.1

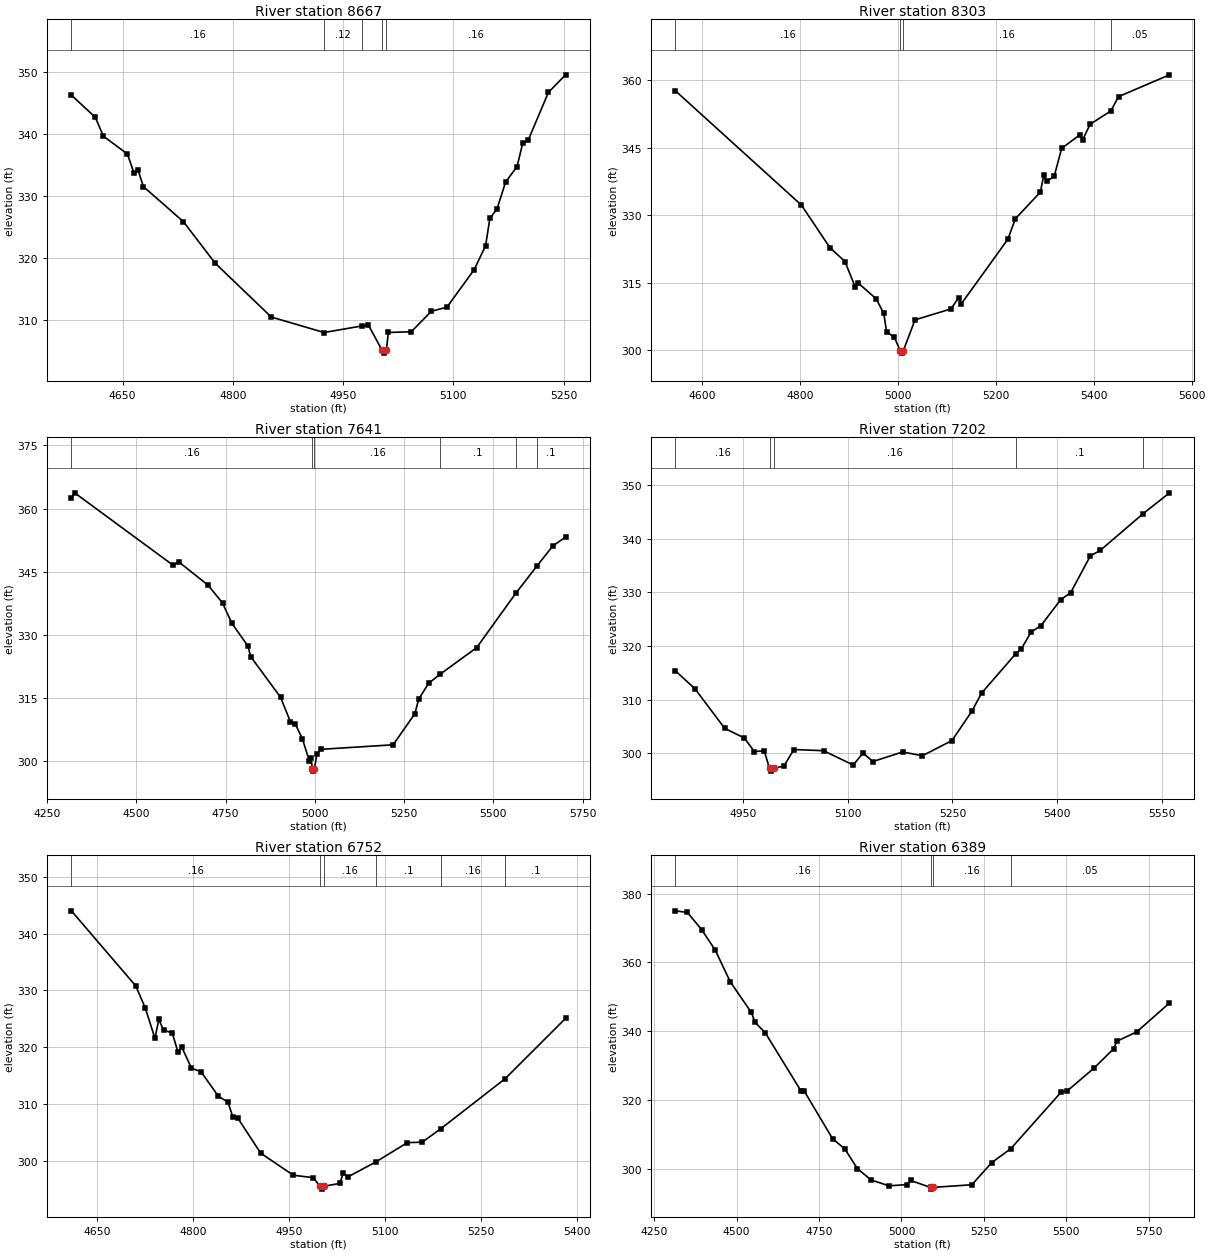
Type RM Length L Ch R = 1,8667,364,364,364
BEGIN DESCRIPTION:
HAYS BRANCH 16.0
END DESCRIPTION:
XS GIS Cut Line= 3
      3794549.62     10520560.19      3794199.61     10520410.19
      3793949.65     10520260.21
#Sta/Elev= 30
  4580.3  346.25  4612.9  342.66  4623.8  339.64  4656.5  336.76  4665.5  333.71
  4671.0  334.19  4678.2  331.52  4732.6  325.88  4776.1  319.16  4852.3  310.51
  4924.1  308.02  4975.7  309.08  4984.4  309.22  5002.8  305.20  5005.6  304.70
  5008.8  305.20  5011.6  308.03  5042.7  308.14  5069.9  311.43  5091.3  312.11
  5128.3  318.15  5143.8  321.98  5149.6  326.40  5159.3  327.90  5171.0  332.24
  5186.6  334.74  5194.3  338.50  5202.1  339.09  5229.3  346.69  5252.6  349.51
#Mann=5,-1,0
  4580.3    0.16       0  4924.1    0.12       0  4975.7    0.16       0
  5002.8    0.07       0  5008.8    0.16       0
Bank Sta=5002.8,5008.8
Exp/Cntr=0.3,0.1

Type RM Length L Ch R = 1,8303,662,662,662
BEGIN DESCRIPTION:
HAYS BRANCH 15.0
END DESCRIPTION:
XS GIS Cut Line= 2
      3794785.57     10520459.23      3793924.52     10519931.49
#Sta/Elev= 30
  4544.8  357.72  4802.6  332.28  4860.7  322.84  4891.5  319.75  4912.8  313.99
  4918.7  314.95  4955.4  311.45  4970.8  308.19  4976.7  304.05  4992.1  302.98
  5004.6  299.88  5007.3  299.38  5010.6  299.88  5034.7  306.78  5108.2  309.21
  5123.6  311.68  5129.5  310.37  5224.3  324.68  5239.7  329.25  5290.7  335.16
  5297.7  338.88  5303.6  337.56  5319.0  338.66  5334.4  344.92  5371.2  347.87
  5377.0  346.73  5392.5  350.27  5434.9  353.22  5450.5  356.40  5554.7  361.25
#Mann=4,-1,0
  4544.8    0.16       0  5004.6    0.07       0  5010.6    0.16       0
  5434.9    0.05       0
Bank Sta=5004.6,5010.6
Exp/Cntr=0.3,0.1

Type RM Length L Ch R = 1,7641,439,439,439
BEGIN DESCRIPTION:
HAYS BRANCH 14.0
END DESCRIPTION:
XS GIS Cut Line= 2
      3795375.83     10519806.43      3794014.70     10519556.43
#Sta/Elev= 30
  4318.3  362.58  4327.4  363.75  4603.1  346.56  4619.5  347.32  4700.8  341.85
  4741.5  337.62  4767.5  332.80  4812.7  327.38  4820.6  324.85  4904.2  315.20
  4931.8  309.36  4944.8  308.94  4965.2  305.37  4984.9  300.01  4990.0  300.88
  4992.7  298.18  4995.4  297.68  4998.7  298.18  5005.8  301.76  5016.0  302.85
  5219.3  303.93  5280.3  311.33  5290.5  314.71  5318.8  318.54  5351.8  320.74
  5453.2  326.99  5562.7  339.89  5621.0  346.27  5666.7  351.16  5702.2  353.24
#Mann=6,-1,0
  4318.3    0.16       0  4992.7    0.07       0  4998.7    0.16       0
  5351.8     0.1       0  5562.7    0.05       0  5621.0     0.1       0
Bank Sta=4992.7,4998.7
Exp/Cntr=0.3,0.1

Type RM Length L Ch R = 1,7202,450,450,450
BEGIN DESCRIPTION:
HAYS BRANCH 13.0
END DESCRIPTION:
XS GIS Cut Line= 3
      3794849.58     10519510.16      3794749.61     10519410.19
      3794349.58     10519010.16
#Sta/Elev= 30
  4853.4  315.41  4881.6  312.03  4924.1  304.67  4952.3  302.86  4966.5  300.34
  4980.6  300.50  4988.2  297.20  4991.0  296.70  4994.2  297.20  5008.9  297.67
  5023.1  300.72  5065.5  300.51  5107.9  297.84  5122.1  300.06  5136.2  298.49
  5178.6  300.27  5206.9  299.56  5249.3  302.40  5277.6  307.84  5291.8  311.26
  5340.2  318.52  5348.3  319.44  5362.5  322.62  5376.6  323.81  5404.9  328.66
  5419.0  329.93  5447.3  336.81  5461.5  337.83  5522.8  344.67  5560.5  348.55
#Mann=5,-1,0
  4853.4    0.16       0  4988.2    0.07       0  4994.2    0.16       0
  5340.2     0.1       0  5522.8    0.05       0
Bank Sta=4988.2,4994.2
Exp/Cntr=0.3,0.1

Type RM Length L Ch R = 1,6752,363,363,363
BEGIN DESCRIPTION:
HAYS BRANCH 12.0
END DESCRIPTION:
XS GIS Cut Line= 3
      3795299.63     10519260.20      3794999.61     10519060.19
      3794599.60     10518960.19
#Sta/Elev= 30
  4609.6  344.03  4710.3  330.79  4725.3  326.87  4740.3  321.53  4746.3  324.87
  4753.8  323.01  4767.4  322.49  4776.4  319.08  4782.4  319.98  4797.4  316.28
  4812.4  315.66  4839.5  311.33  4854.5  310.30  4862.0  307.72  4869.5  307.56
  4905.6  301.31  4956.7  297.41  4988.2  296.98  4998.1  295.46  5000.9  294.96
  5004.1  295.46  5029.4  295.97  5034.6  297.72  5042.3  297.13  5086.0  299.77
  5135.1  303.16  5158.3  303.24  5187.0  305.58  5287.9  314.42  5382.5  325.07
#Mann=6,-1,0
  4609.6    0.16       0  4998.1    0.07       0  5004.1    0.16       0
  5086.0     0.1       0  5187.0    0.16       0  5287.9     0.1       0
Bank Sta=4998.1,5004.1
Exp/Cntr=0.3,0.1

Type RM Length L Ch R = 1,6389,583,583,583
BEGIN DESCRIPTION:
HAYS BRANCH 11.0
END DESCRIPTION:
XS GIS Cut Line= 3
      3795764.69     10518980.04      3795007.75     10518688.37
      3794320.24     10518688.37
#Sta/Elev= 30
  4314.1  375.00  4350.9  374.52  4394.6  369.46  4435.5  363.53  4480.3  354.45
  4544.6  345.47  4555.4  342.68  4587.5  339.46  4694.6  322.75  4705.4  322.56
  4791.1  308.75  4828.4  305.78  4866.1  300.09  4907.6  296.78  4962.2  295.08
  5016.1  295.41  5027.6  296.62  5088.2  294.61  5090.9  294.11  5094.2  294.61
  5213.4  295.38  5273.4  301.79  5331.6  305.87  5483.4  322.21  5503.4  322.72
  5583.4  329.24  5643.4  334.92  5653.4  337.11  5713.4  339.81  5812.8  348.21
#Mann=4,-1,0
  4314.1    0.16       0  5088.2    0.07       0  5094.2    0.16       0
  5331.6    0.05       0
Bank Sta=5088.2,5094.2
Exp/Cntr=0.3,0.1

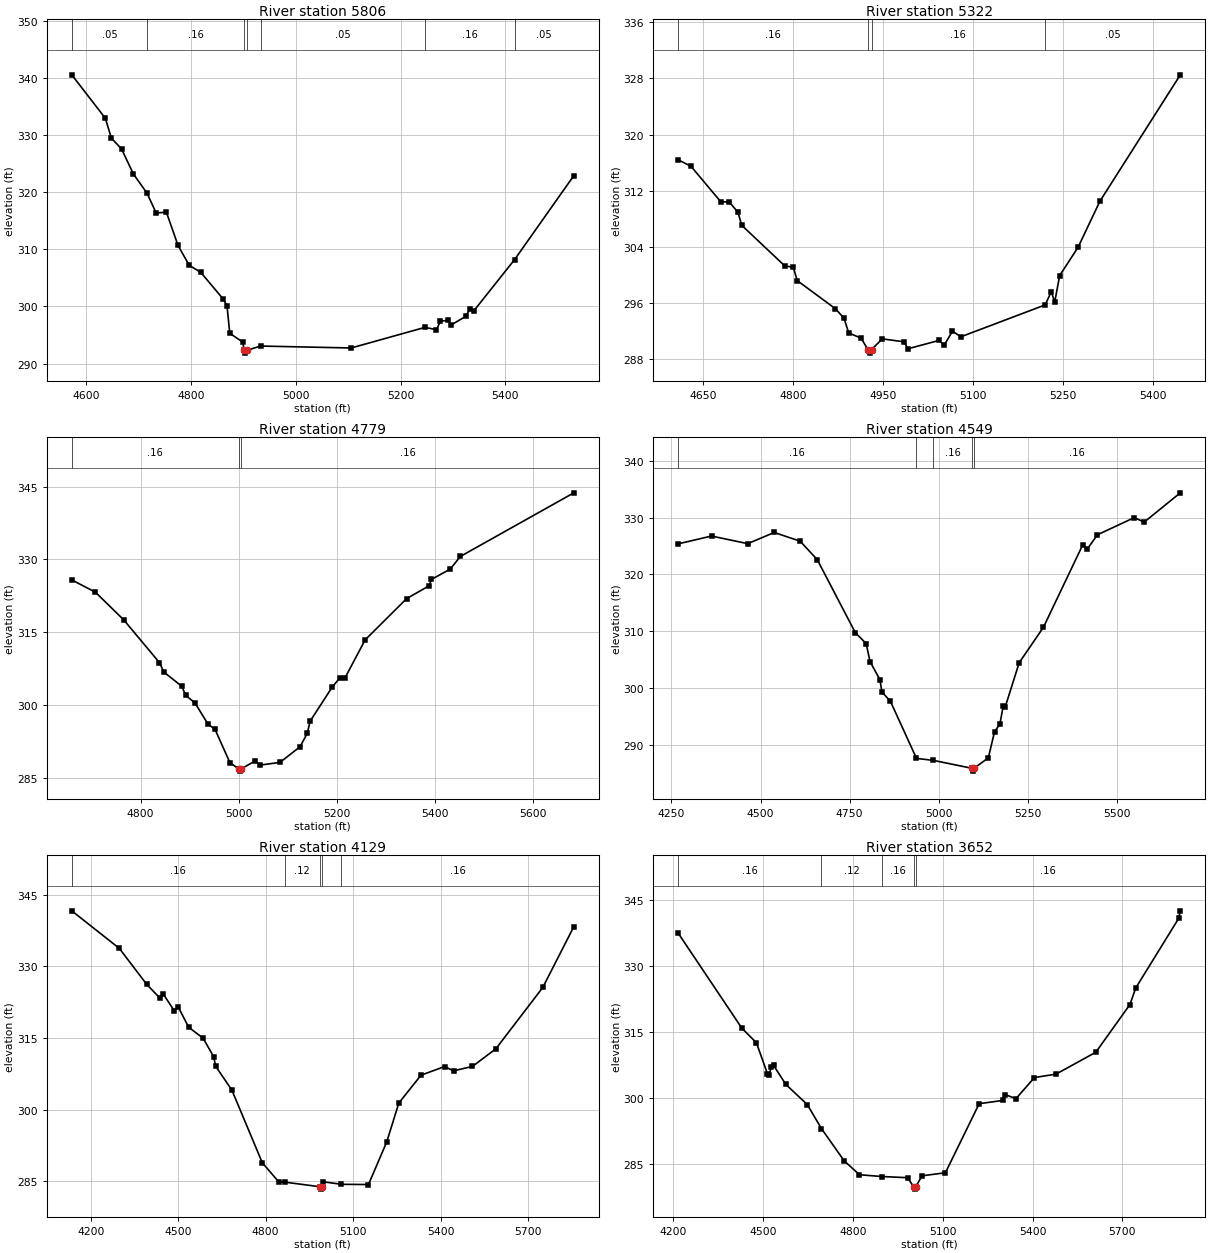
Type RM Length L Ch R = 1,5806,484,484,484
BEGIN DESCRIPTION:
HAYS BRANCH 10.0
END DESCRIPTION:
XS GIS Cut Line= 3
      3795399.60     10518060.19      3794999.61     10518210.19
      3794599.61     10518560.19
#Sta/Elev= 30
  4572.0  340.57  4636.1  332.96  4647.6  329.49  4667.2  327.57  4689.5  323.23
  4715.8  319.82  4733.1  316.38  4752.7  316.51  4774.9  310.68  4796.3  307.21
  4818.5  305.96  4860.4  301.38  4868.4  300.17  4873.7  295.30  4898.6  293.76
  4901.0  292.33  4903.7  291.83  4907.0  292.33  4932.6  293.07  5105.5  292.73
  5246.4  296.34  5268.3  295.94  5275.9  297.40  5290.1  297.60  5296.7  296.77
  5325.2  298.32  5331.9  299.58  5339.5  299.21  5417.6  308.22  5530.7  322.92
#Mann=7,-1,0
  4572.0    0.05       0  4715.8    0.16       0  4901.0   0.033       0
  4907.0    0.16       0  4932.6    0.05       0  5246.4    0.16       0
  5417.6    0.05       0
Bank Sta=4901,4907
Exp/Cntr=0.3,0.1

Type RM Length L Ch R = 1,5322,543,543,543
BEGIN DESCRIPTION:
HAYS BRANCH 9.0
END DESCRIPTION:
XS GIS Cut Line= 3
      3794999.58     10517660.22      3794699.61     10517910.19
      3794299.59     10518110.20
#Sta/Elev= 30
  4607.9  316.40  4629.3  315.47  4678.8  310.44  4693.1  310.39  4707.4  308.96
  4713.9  307.08  4785.5  301.32  4799.9  301.11  4806.4  299.22  4870.2  295.21
  4884.5  293.87  4892.3  291.78  4913.1  291.02  4924.4  289.40  4927.2  288.90
  4930.4  289.40  4948.3  290.93  4984.7  290.51  4991.2  289.52  5043.1  290.71
  5051.5  290.01  5065.5  292.03  5079.4  291.22  5220.1  295.76  5230.4  297.65
  5236.0  296.15  5244.3  299.93  5275.1  303.97  5311.4  310.50  5445.6  328.49
#Mann=4,-1,0
  4607.9    0.16       0  4924.4    0.07       0  4930.4    0.16       0
  5220.1    0.05       0
Bank Sta=4924.4,4930.4
Exp/Cntr=0.3,0.1

Type RM Length L Ch R = 1,4779,230,230,230
BEGIN DESCRIPTION:
HAYS BRANCH 8.0
END DESCRIPTION:
XS GIS Cut Line= 3
      3795091.09     10517528.65      3794875.81     10517466.15
      3794092.83     10517306.79
#Sta/Elev= 30
  4659.7  325.79  4708.0  323.25  4765.4  317.59  4838.3  308.78  4847.5  306.82
  4883.9  303.90  4892.0  302.01  4910.6  300.51  4937.5  296.08  4951.4  295.09
  4982.0  288.18  4999.5  286.94  5002.2  286.44  5005.5  286.94  5033.1  288.51
  5043.7  287.68  5084.1  288.24  5124.9  291.46  5139.8  294.26  5145.3  296.69
  5190.4  303.73  5206.6  305.70  5216.8  305.68  5257.6  313.45  5342.1  321.94
  5387.6  324.56  5392.7  325.89  5431.1  328.02  5451.5  330.61  5682.9  343.71
#Mann=3,-1,0
  4659.7    0.16       0  4999.5    0.07       0  5005.5    0.16       0
Bank Sta=4999.5,5005.5
Exp/Cntr=0.3,0.1

Type RM Length L Ch R = 1,4549,420,420,420
BEGIN DESCRIPTION:
HAYS BRANCH 7.0
END DESCRIPTION:
XS GIS Cut Line= 5
      3795384.48     10517672.77      3795048.37     10517475.55
      3795023.37     10517325.55      3794578.92     10517144.99
      3794204.22     10517239.36
#Sta/Elev= 30
  4269.3  325.39  4362.6  326.76  4464.2  325.42  4538.5  327.39  4611.2  325.85
  4659.0  322.62  4765.8  309.76  4796.2  307.83  4807.3  304.63  4835.0  301.45
  4840.4  299.32  4864.4  297.65  4937.4  287.61  4985.0  287.26  5092.8  285.87
  5095.5  285.37  5098.8  285.87  5138.9  287.71  5156.3  292.33  5171.3  293.64
  5180.4  296.80  5185.8  296.58  5225.3  304.45  5293.4  310.70  5403.5  325.20
  5416.7  324.51  5444.8  326.98  5547.9  330.00  5576.0  329.22  5677.2  334.37
#Mann=5,-1,0
  4269.3    0.16       0  4937.4    0.12       0  4985.0    0.16       0
  5092.8    0.07       0  5098.8    0.16       0
Bank Sta=5092.8,5098.8
Exp/Cntr=0.3,0.1

Type RM Length L Ch R = 1,4129,477,477,477
BEGIN DESCRIPTION:
HAYS BRANCH 6.0
END DESCRIPTION:
XS GIS Cut Line= 4
      3795826.13     10516961.66      3795342.81     10517064.44
      3794698.37     10516878.32      3794215.02     10516600.54
#Sta/Elev= 30
  4134.9  341.60  4298.1  333.74  4392.2  326.19  4436.6  323.39  4448.3  324.24
  4486.2  320.71  4499.4  321.57  4535.8  317.25  4585.4  314.95  4622.1  311.05
  4628.1  309.13  4684.4  304.06  4788.5  288.89  4844.2  284.94  4865.1  284.84
  4986.1  283.87  4988.8  283.37  4992.1  283.87  4996.7  284.91  5060.1  284.38
  5152.8  284.33  5215.2  293.22  5256.9  301.38  5333.0  307.21  5413.7  309.01
  5444.6  308.12  5509.3  309.04  5589.8  312.73  5750.8  325.57  5857.3  338.30
#Mann=5,-1,0
  4134.9    0.16       0  4865.1    0.12       0  4986.1    0.07       0
  4992.1    0.12       0  5060.1    0.16       0
Bank Sta=4986.1,4992.1
Exp/Cntr=0.3,0.1

Type RM Length L Ch R = 1,3652,341,341,341
BEGIN DESCRIPTION:
Mapping XS cbb296b3
END DESCRIPTION:
XS GIS Cut Line= 2
      3795840.04     10516761.66      3794204.31     10516397.85
#Sta/Elev= 30
  4217.5  337.37  4429.7  315.86  4478.4  312.54  4515.0  305.56  4521.9  305.17
  4527.0  307.12  4535.5  307.43  4576.5  303.11  4648.2  298.53  4695.5  293.09
  4771.1  285.80  4822.4  282.63  4896.4  282.23  4982.7  281.96  5003.8  279.87
  5006.5  279.37  5009.8  279.87  5031.3  282.39  5109.2  283.08  5221.9  298.73
  5302.7  299.49  5307.8  300.80  5344.8  299.88  5406.3  304.66  5478.0  305.42
  5611.2  310.39  5725.1  321.21  5744.3  324.94  5887.8  340.73  5893.2  342.44
#Mann=5,-1,0
  4217.5    0.16       0  4695.5    0.12       0  4896.4    0.16       0
  5003.8    0.07       0  5009.8    0.16       0
Bank Sta=5003.8,5009.8
Exp/Cntr=0.3,0.1