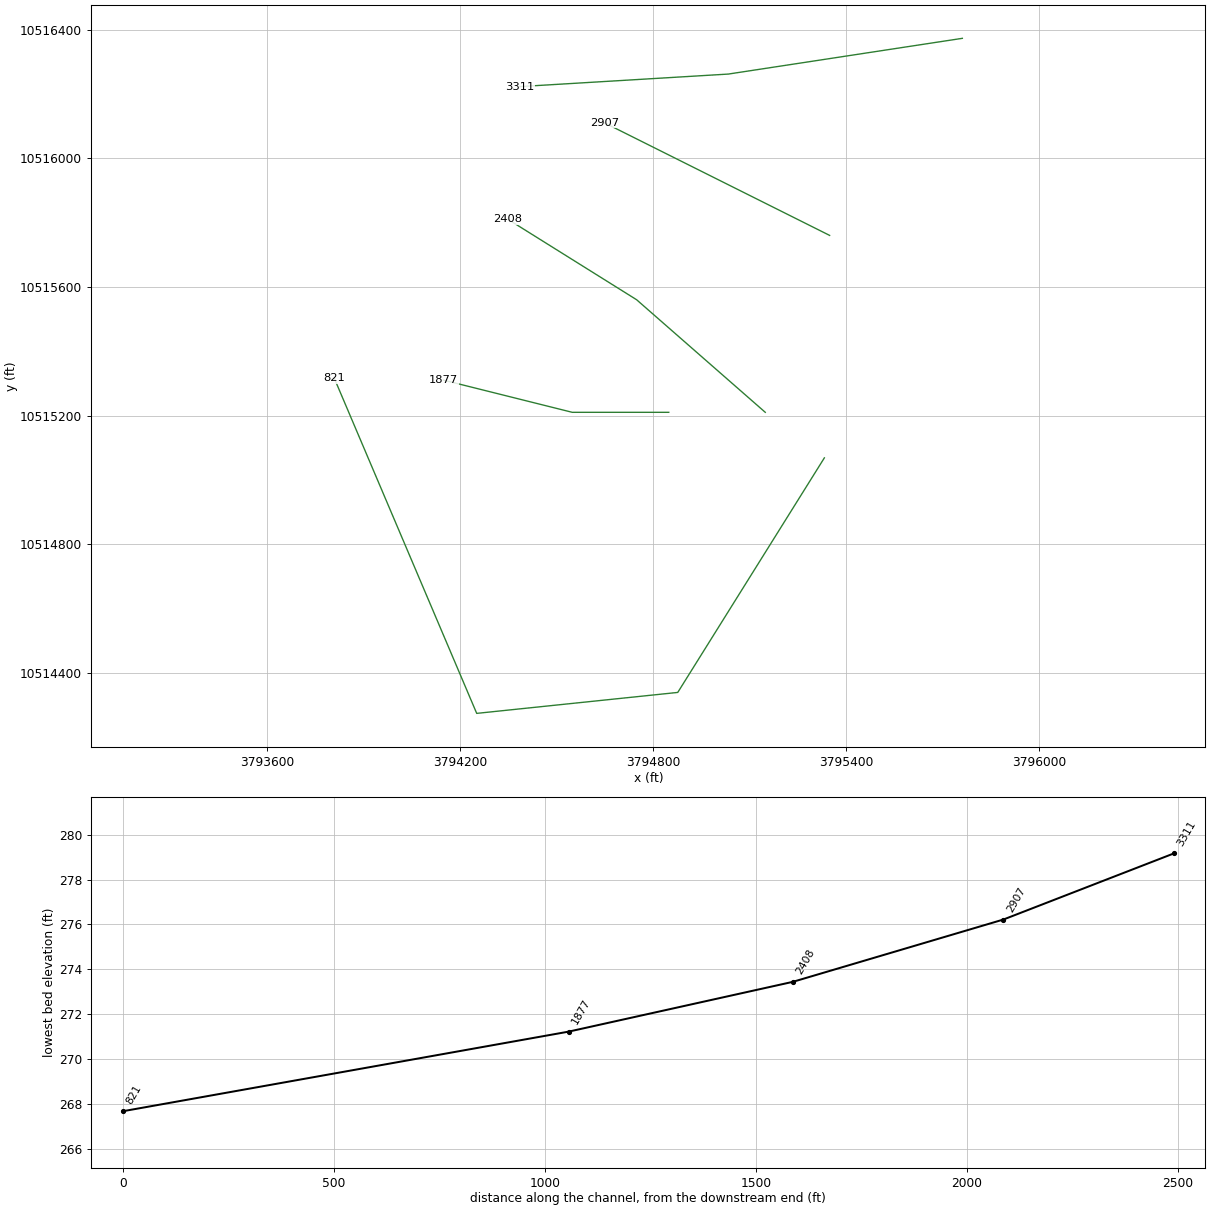
HEC-RAS study HAYS BRANCH.prj: HAYS BRANCH Base Level Engineering

--- HAYS BRANCH.g01 (geometry) --- (continued)

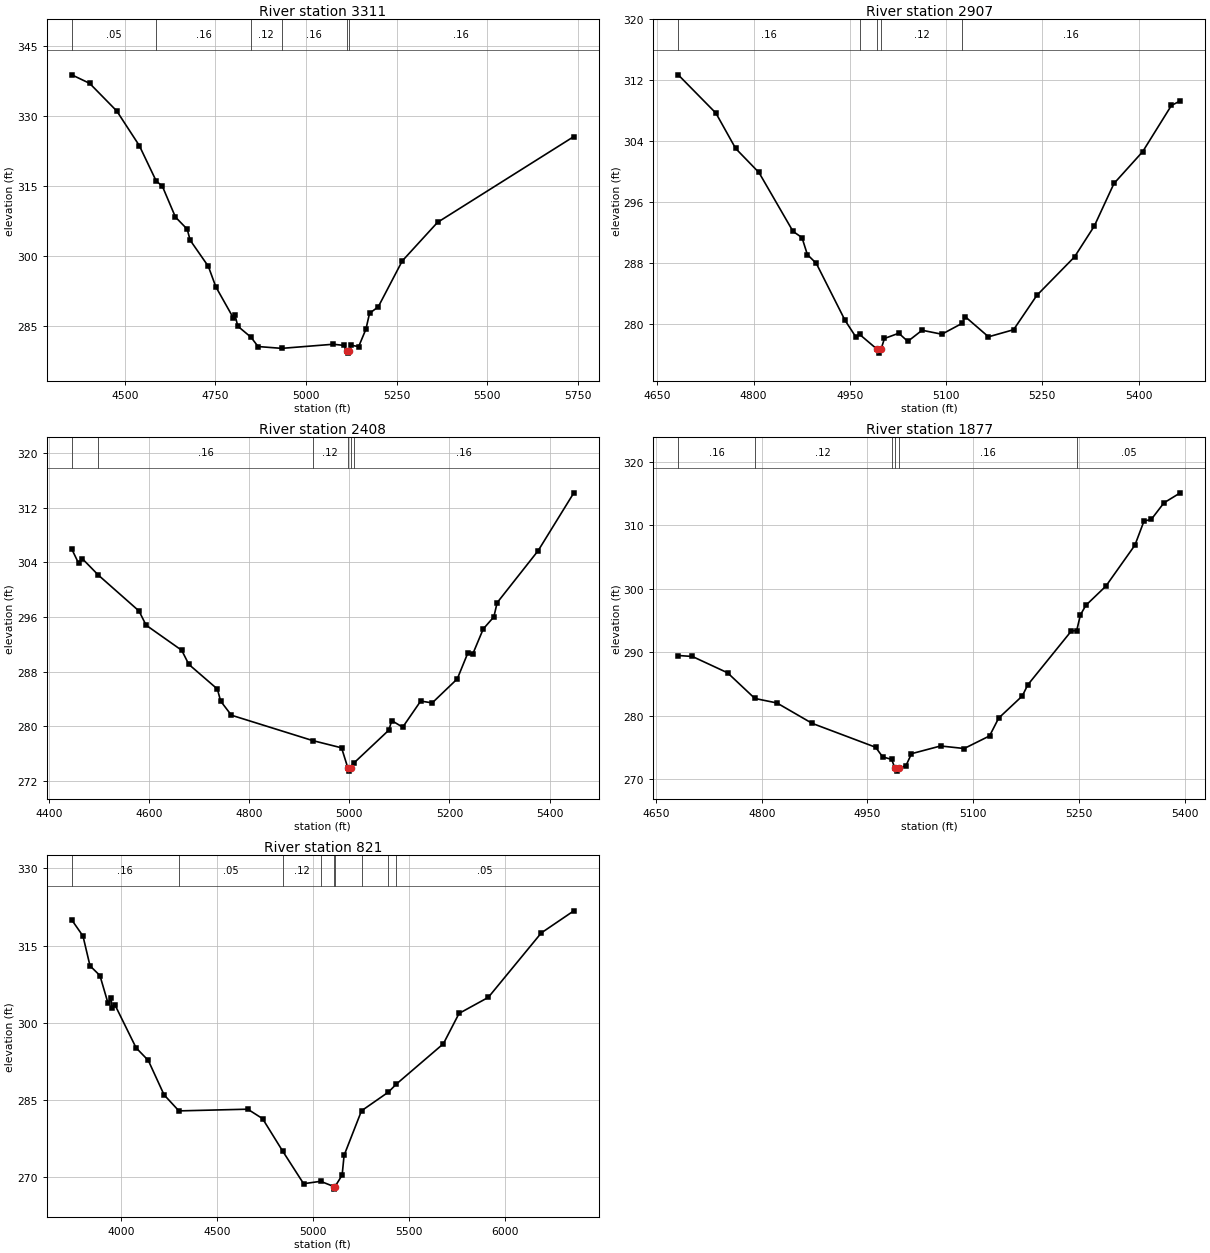
Type RM Length L Ch R = 1,3311,404,404,404
BEGIN DESCRIPTION:
HAYS BRANCH 5.0
END DESCRIPTION:
XS GIS Cut Line= 3
      3795762.26     10516372.77      3795034.48     10516261.66
      3794387.26     10516222.77
#Sta/Elev= 30
  4353.9  338.76  4403.1  336.94  4478.0  331.01  4540.2  323.60  4586.7  316.03
  4603.7  314.91  4639.8  308.30  4672.2  305.71  4680.3  303.36  4730.6  297.74
  4751.1  293.38  4799.2  286.74  4804.2  287.23  4811.8  284.94  4848.2  282.57
  4867.7  280.58  4932.9  280.19  5074.8  281.07  5105.0  280.82  5112.0  279.67
  5114.8  279.17  5118.0  279.67  5125.0  280.85  5145.1  280.57  5165.1  284.30
  5175.1  287.70  5199.1  289.08  5265.3  298.91  5362.6  307.17  5738.5  325.54
#Mann=6,-1,0
  4353.9    0.05       0  4586.7    0.16       0  4848.2    0.12       0
  4932.9    0.16       0  5112.0    0.07       0  5118.0    0.16       0
Bank Sta=5112,5118
Exp/Cntr=0.3,0.1

Type RM Length L Ch R = 1,2907,499,499,499
BEGIN DESCRIPTION:
HAYS BRANCH 4.0
END DESCRIPTION:
XS GIS Cut Line= 3
      3795349.62     10515760.18      3795049.61     10515910.19
      3794649.64     10516110.17
#Sta/Elev= 30
  4682.5  312.72  4741.2  307.70  4772.0  303.06  4808.3  299.91  4861.4  292.19
  4875.4  291.37  4883.8  289.14  4897.7  287.99  4942.5  280.52  4959.2  278.36
  4965.3  278.67  4992.6  276.72  4995.3  276.22  4998.6  276.72  5003.9  278.14
  5026.3  278.83  5040.3  277.76  5062.6  279.22  5093.4  278.70  5125.3  280.14
  5129.7  281.01  5166.1  278.36  5205.2  279.29  5241.5  283.80  5300.2  288.84
  5331.0  292.88  5361.7  298.47  5406.4  302.64  5451.2  308.70  5465.1  309.31
#Mann=5,-1,0
  4682.5    0.16       0  4965.3    0.12       0  4992.6    0.07       0
  4998.6    0.12       0  5125.3    0.16       0
Bank Sta=4992.6,4998.6
Exp/Cntr=0.3,0.1

Type RM Length L Ch R = 1,2408,531,531,531
BEGIN DESCRIPTION:
HAYS BRANCH 3.0
END DESCRIPTION:
XS GIS Cut Line= 3
      3795149.58     10515210.21      3794749.61     10515560.19
      3794349.59     10515810.20
#Sta/Elev= 30
  4445.3  305.95  4459.0  303.87  4466.6  304.53  4498.6  302.13  4579.6  296.89
  4593.8  294.81  4665.0  291.13  4679.2  289.07  4736.2  285.46  4742.8  283.69
  4764.2  281.63  4926.8  277.91  4984.4  276.85  4996.8  273.94  4999.5  273.44
  5002.8  273.94  5008.6  274.60  5078.8  279.44  5084.7  280.84  5106.5  279.87
  5142.5  283.70  5165.5  283.43  5215.6  286.95  5236.8  290.76  5246.2  290.53
  5267.5  294.26  5288.7  296.03  5295.2  298.10  5377.1  305.71  5448.5  314.19
#Mann=6,-1,0
  4445.3    0.05       0  4498.6    0.16       0  4926.8    0.12       0
  4996.8    0.07       0  5002.8    0.12       0  5008.6    0.16       0
Bank Sta=4996.8,5002.8
Exp/Cntr=0.3,0.1

Type RM Length L Ch R = 1,1877,1056,1056,1056
BEGIN DESCRIPTION:
HAYS BRANCH 2.0
END DESCRIPTION:
XS GIS Cut Line= 3
      3794849.62     10515210.19      3794549.61     10515210.19
      3794149.63     10515310.18
#Sta/Elev= 30
  4681.5  289.47  4701.5  289.32  4751.5  286.74  4790.2  282.69  4821.5  281.98
  4871.5  278.76  4961.5  274.99  4971.5  273.47  4984.3  273.07  4988.8  271.72
  4991.6  271.22  4994.8  271.72  5004.7  272.10  5012.4  273.97  5053.7  275.19
  5087.2  274.79  5123.2  276.78  5136.1  279.59  5169.6  283.08  5177.4  284.84
  5239.2  293.34  5246.8  293.41  5252.1  295.89  5259.8  297.39  5288.2  300.42
  5329.4  306.89  5342.3  310.70  5352.6  310.95  5370.6  313.57  5393.8  315.15
#Mann=6,-1,0
  4681.5    0.16       0  4790.2    0.12       0  4984.3    0.16       0
  4988.8    0.07       0  4994.8    0.16       0  5246.8    0.05       0
Bank Sta=4988.8,4994.8
Exp/Cntr=0.3,0.1

Type RM Length L Ch R = 1,821,0,0,0
BEGIN DESCRIPTION:
HAYS BRANCH 1.0
END DESCRIPTION:
XS GIS Cut Line= 4
      3795333.28     10515068.59      3794877.54     10514339.42
      3794252.54     10514274.31      3793809.99     10515315.61
#Sta/Elev= 30
  3741.7  319.97  3800.2  316.84  3836.8  311.06  3888.7  309.16  3931.1  303.75
  3946.5  304.76  3952.4  302.88  3967.7  303.41  4077.4  295.12  4141.0  292.67
  4223.3  285.99  4300.7  282.87  4659.8  283.20  4737.1  281.37  4841.4  275.10
  4951.4  268.72  5040.2  269.19  5109.3  268.17  5112.0  267.67  5115.3  268.17
  5152.5  270.40  5162.5  274.22  5253.5  282.89  5393.8  286.52  5435.9  288.10
  5680.6  295.91  5762.5  301.81  5915.2  304.93  6191.6  317.45  6361.4  321.74
#Mann=9,-1,0
  3741.7    0.16       0  4300.7    0.05       0  4841.4    0.12       0
  5040.2    0.16       0  5109.3    0.07       0  5115.3    0.16       0
  5253.5    0.05       0  5393.8     0.1       0  5435.9    0.05       0
Bank Sta=5109.3,5115.3
Exp/Cntr=0.3,0.1

Chan Stop Cuts=-1