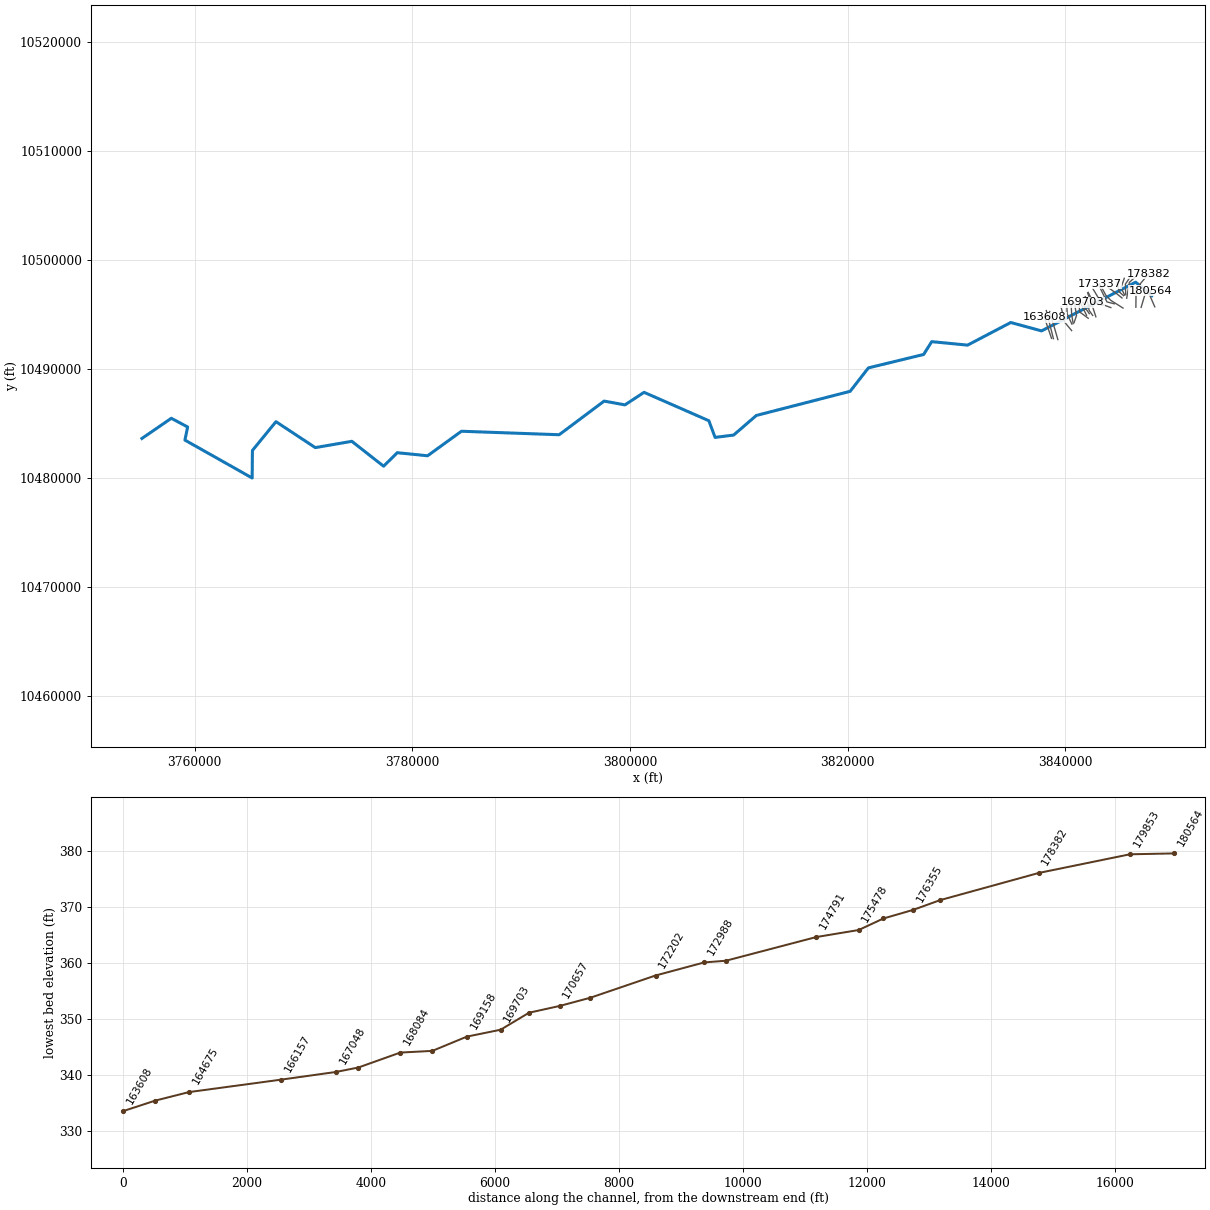
--- HURRICANE BAYOU.prj (project) ---

Proj Title=HURRICANE BAYOU Base Level Engineering
Current Plan=p01
Default Exp/Contr=0.3,0.1
English Units
Geom File=g01
Flow File=f01
Plan File=p01
Y Axis Title=Elevation
X Axis Title(PF)=Main Channel Distance
X Axis Title(XS)=Station
BEGIN DESCRIPTION:
HURRICANE BAYOU
END DESCRIPTION:
DSS File=dss
DSS Export Rating Curves= 0
DSS Export Rating Curve Sorted= 0
DSS Export Volume Flow Curves= 0
DXF OffsetX= 0
DXF OffsetY= 0
DXF ScaleX= 1
DXF ScaleY= 10

--- HURRICANE BAYOU.p01 (plan) ---

Plan Title=Multiple Run
Program Version=4.10
Short Identifier=Multiple Run
Geom File=g01
Flow File=f01
Subcritical Flow
K Sum by GR= 0
Std Step Tol= 0.01
Critical Tol= 0.01
Num of Std Step Trials= 20
Max Error Tol= 0.3
Flow Tol Ratio= 0.001
Split Flow NTrial= 30
Split Flow Tol= 0.02
Split Flow Ratio= 0.02
Log Output Level= 0
Friction Slope Method= 1
Unsteady Friction Slope Method= 2
Unsteady Bridges Friction Slope Method= 1
Parabolic Critical Depth
Global Vel Dist= 1 , 1 , 1
Global Log Level= 0
CheckData=True
Encroach Param=-1 ,0,0, 0
BEGIN DESCRIPTION:
Multiple Run
END DESCRIPTION:
Computation Interval=1HOUR
Output Interval=1HOUR
Run HTab= 0
Run UNet= 0
Run PostProcess= 0
Run WQNet= 0
UNET Theta= 1
UNET Theta Warmup= 1
UNET ZTol= 0.02
UNET ZSATol= 0.05
UNET MxIter= 20
UNET MaxInSteps= 0
UNET DtIC= 0
UNET DtMin= 0
UNET MaxCRTS= 20
UNET WFStab= 2
UNET SFStab= 1
UNET WFX= 1
UNET SFX= 1
UNET DSS MLevel= 4
UNET DZMax Abort= 100
UNET Convert EG Bridges= 0
UNET Use Existing IB Tables=-1
UNET Froude Reduction=False
UNET Froude Limit= 1
UNET Froude Power= 10
UNET Time Slicing=0,0, 5
UNET Junction Losses=0
Instantaneous Interval=1HOUR
DSS File=dss
Write IC File= 0
Write IC File at Sim End=0
Echo Input=False
Echo Parameters=False
Echo Output=False
Write Detailed= 0
WQ AD Non Conservative
WQ ULTIMATE=-1
WQ Max Comp Step=1HOUR
WQ Output Interval=15MIN
WQ Output Selected Increments= 0
WQ Output face flow=0
WQ Output face velocity=0
WQ Output face area=0
WQ Output face dispersion=0
WQ Output cell volume=0
WQ Output cell surface area=0
WQ Output cell continuity=0
WQ Output cumulative cell continuity=0
WQ Output face conc=0
WQ Output face dconc_dx=0
WQ Output face courant=0
WQ Output face peclet=0
WQ Output face adv mass=0
WQ Output face disp mass=0
WQ Output cell mass=0
WQ Output cell source sink temp=0
WQ Output cell source sink nsm=0
WQ Output MaxMinRange=-1
WQ Daily Max Min Mean=-1
WQ Daily Range=0
WQ Daily Time=0
WQ Create Restart=0
WQ Fixed Restart=0
WQ System Summary=0
WQ Use Fixed Temperature=0
Sorting and Armoring Iterations= 10
XS Update Threshold= 0.02
Hydraulics Update Threshold= 0.02
Energy Slope Method= 1
Volume Change Method= 0
XS Weighting Method= 0
Number of US Weighted Cross Sections= 1
Number of DS Weighted Cross Sections= 1
Upstream XS Weight=0.25
Main XS Weight=0.5
Downstream XS Weight=0.25
Number of DS XS's Weighted with US Boundary= 1
Upstream Boundary Weight= 1
Weight of XSs Associated with US Boundary= 0
Number of US XS's Weighted with DS Boundary= 1
Downstream Boundary Weight= 0.5
Weight of XSs Associated with DS Boundary= 0.5
Sediment Output Level= 4
Mass or Volume Output= 0
Output Increment Type= 1
Profile and TS Output Increment= 10
XS Output Flag= 0
XS Output Increment= 10
Disregard all LS=0
Disregard all Conn=0
Disregard all Breaches=0
Disregard all Pumps=0

--- HURRICANE BAYOU.f01 (steady flow) ---

Flow Title=Multiple
Program Version=4.10
Number of Profiles= 7
Profile Names=10-year,25-year,50-year,1pct_min,100-year,1pct_plu,500-year
River Rch & RM=HURRICANE BAYOU,Reach-1         ,180564
     571     767     928     825    1116    1510    1621
River Rch & RM=HURRICANE BAYOU,Reach-1         ,179853
     757    1025    1245    1111    1503    2032    2194
River Rch & RM=HURRICANE BAYOU,Reach-1         ,170657
     973    1333    1634    1468    1985    2685    2943
River Rch & RM=HURRICANE BAYOU,Reach-1         ,169158
     973    1333    1634    1468    1985    2685    2943
River Rch & RM=HURRICANE BAYOU,Reach-1         ,168084
    1357    1886    2332    2111    2855    3862    4300
River Rch & RM=HURRICANE BAYOU,Reach-1         ,167048
    1357    1886    2332    2111    2855    3862    4300
River Rch & RM=HURRICANE BAYOU,Reach-1         ,161701
    1449    2021    2506    2275    3077    4162    4659
River Rch & RM=HURRICANE BAYOU,Reach-1         ,158689
    1898    2674    3338    3048    4122    5575    6313
River Rch & RM=HURRICANE BAYOU,Reach-1         ,151343
    1965    2767    3452    3150    4260    5762    6516
River Rch & RM=HURRICANE BAYOU,Reach-1         ,145408
    2914    4163    5245    4828    6529    8830   10162
River Rch & RM=HURRICANE BAYOU,Reach-1         ,139862
    3260    4666    5886    5424    7335    9920   11436
River Rch & RM=HURRICANE BAYOU,Reach-1         ,135705
    3285    4703    5934    5469    7396   10002   11536
River Rch & RM=HURRICANE BAYOU,Reach-1         ,135182
    3285    4703    5934    5469    7396   10002   11536
River Rch & RM=HURRICANE BAYOU,Reach-1         ,134175
    3421    4895    6173    5685    7689   10398   11975
River Rch & RM=HURRICANE BAYOU,Reach-1         ,131593
    4643    6708    8518    7893   10674   14435   16827
River Rch & RM=HURRICANE BAYOU,Reach-1         ,129007
    4667    6737    8551    7920   10710   14484   16866
River Rch & RM=HURRICANE BAYOU,Reach-1         ,124749
    5249    7592    9649    8947   12099   16363   19092
River Rch & RM=HURRICANE BAYOU,Reach-1         ,123359
    5249    7592    9649    8947   12099   16363   19092
River Rch & RM=HURRICANE BAYOU,Reach-1         ,117967
    5305    7667    9738    9022   12202   16502   19227
River Rch & RM=HURRICANE BAYOU,Reach-1         ,116542
    6097    8825   11221   10405   14072   19031   22206
River Rch & RM=HURRICANE BAYOU,Reach-1         ,116229
    6097    8825   11221   10405   14072   19031   22206
River Rch & RM=HURRICANE BAYOU,Reach-1         ,115947
    6097    8825   11221   10405   14072   19031   22206
River Rch & RM=HURRICANE BAYOU,Reach-1         ,106707
    6097    8825   11221   10405   14072   19031   22206
River Rch & RM=HURRICANE BAYOU,Reach-1         ,101789
    6251    9033   11474   10627   14371   19436   22621
River Rch & RM=HURRICANE BAYOU,Reach-1         ,93819
    6239    8998   11413   10555   14274   19304   22400
River Rch & RM=HURRICANE BAYOU,Reach-1         ,92767
    7418   10708   13592   12574   17005   22997   26697
River Rch & RM=HURRICANE BAYOU,Reach-1         ,84846
    7418   10708   13592   12574   17005   22997   26697
River Rch & RM=HURRICANE BAYOU,Reach-1         ,81755
    7418   10708   13592   12574   17005   22997   26697
River Rch & RM=HURRICANE BAYOU,Reach-1         ,69655
    7418   10708   13592   12574   17005   22997   26697
River Rch & RM=HURRICANE BAYOU,Reach-1         ,66435
    7735   11166   14176   13114   17735   23985   27843
River Rch & RM=HURRICANE BAYOU,Reach-1         ,60226
    7735   11166   14176   13114   17735   23985   27843
River Rch & RM=HURRICANE BAYOU,Reach-1         ,58171
    8433   12156   15418   14247   19267   26056   30171
River Rch & RM=HURRICANE BAYOU,Reach-1         ,56681
    8433   12156   15418   14247   19267   26056   30171
River Rch & RM=HURRICANE BAYOU,Reach-1         ,38537
    8433   12156   15418   14247   19267   26056   30171
River Rch & RM=HURRICANE BAYOU,Reach-1         ,35102
    8433   12156   15418   14247   19267   26056   30171
River Rch & RM=HURRICANE BAYOU,Reach-1         ,30553
    8370   12049   15267   14093   19059   25775   29784
River Rch & RM=HURRICANE BAYOU,Reach-1         ,27891
    8520   12274   15561   14371   19435   26284   30404
River Rch & RM=HURRICANE BAYOU,Reach-1         ,25310
    8520   12274   15561   14371   19435   26284   30404
River Rch & RM=HURRICANE BAYOU,Reach-1         ,15406
    8478   12189   15431   14231   19246   26028   30019
River Rch & RM=HURRICANE BAYOU,Reach-1         ,12375
    8649   12441   15755   14534   19655   26582   30675
Boundary for River Rch & Prof#=HURRICANE BAYOU,Reach-1         , 1
Up Type= 0
Dn Type= 3
Dn Slope=0.0015
Boundary for River Rch & Prof#=HURRICANE BAYOU,Reach-1         , 2
Up Type= 0
Dn Type= 3
Dn Slope=0.0015
Boundary for River Rch & Prof#=HURRICANE BAYOU,Reach-1         , 3
Up Type= 0
Dn Type= 3
Dn Slope=0.0015
Boundary for River Rch & Prof#=HURRICANE BAYOU,Reach-1         , 4
Up Type= 0
Dn Type= 3
Dn Slope=0.0015
Boundary for River Rch & Prof#=HURRICANE BAYOU,Reach-1         , 5
Up Type= 0
Dn Type= 3
Dn Slope=0.0015
Boundary for River Rch & Prof#=HURRICANE BAYOU,Reach-1         , 6
Up Type= 0
Dn Type= 3
Dn Slope=0.0015
Boundary for River Rch & Prof#=HURRICANE BAYOU,Reach-1         , 7
Up Type= 0
Dn Type= 3
Dn Slope=0.0015
DSS Import GetInterval= 0
DSS Import GetPeak= 0
DSS Import FillOption= 0

--- HURRICANE BAYOU.g01 (geometry) ---

Geom Title=Existing Conditions
Program Version=4.10

River Reach=HURRICANE BAYOU ,Reach-1
Reach XY= 30
      3847952.62       10496758.       3846460.5       10497996.
      3837814.75       10493527.      3834986.25       10494296.
       3831014.5       10492220.        3827719.       10492540.
       3826978.5       10491363.      3821905.25       10490134.
       3820228.5       10487984.        3811605.       10485768.
        3809521.       10483970.      3807817.25       10483755.
        3807243.       10485286.      3801289.75       10487890.
        3799534.       10486740.      3797621.25       10487087.
      3793489.75       10484001.      3784508.75       10484321.
      3781398.75       10482072.        3778612.       10482352.
      3777355.25       10481112.      3774438.75       10483397.
       3771078.5       10482820.        3767465.       10485200.
        3765302.       10482559.        3765279.       10480033.
      3759099.61     10483510.19      3759349.61     10484710.19
      3757849.61     10485510.19      3755149.61     10483660.19

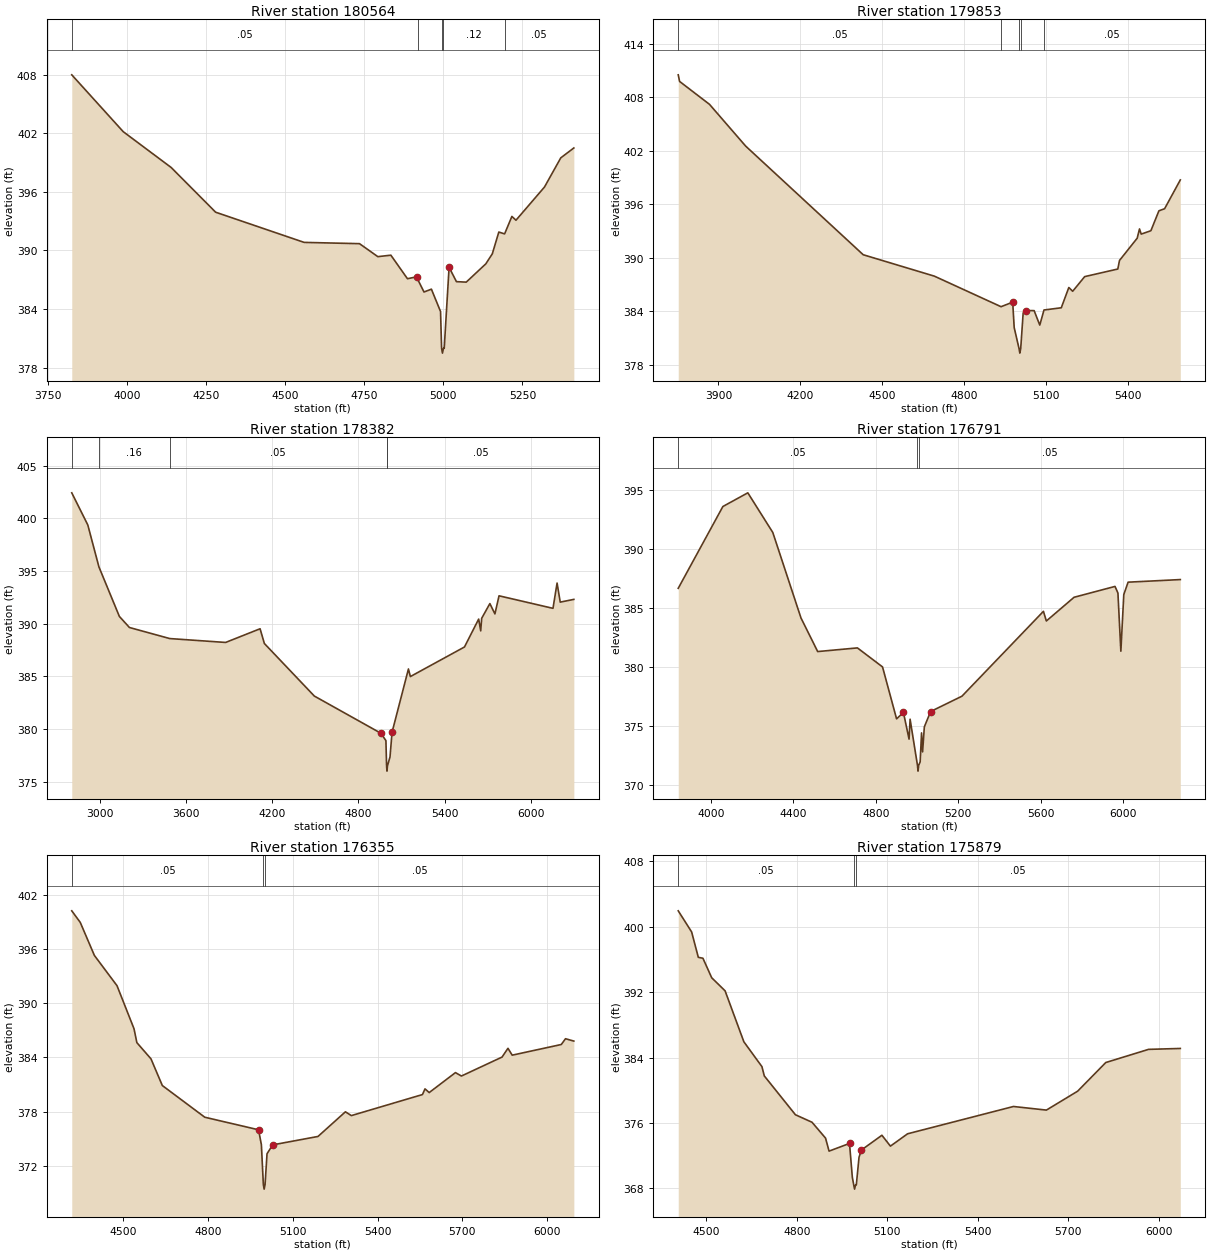
Type RM Length L Ch R = 1 ,180564  ,711,711,711
BEGIN DESCRIPTION:
HURRICANE BAYOU 168.0
END DESCRIPTION:
XS GIS Cut Line= 3
       3848218.2      10495733.1      3847749.61     10496810.19
      3847849.61     10497210.17
#Sta/Elev= 30
  3825.6  407.99  3988.2  402.17  4139.8   398.5  4280.4  393.92    4560  390.83
    4735   390.7    4793  389.37  4834.2  389.52  4886.6  387.11  4915.4   387.3
  4918.6  387.07  4938.9  385.75  4962.3  386.04  4991.2  383.75  4994.5  379.99
  4997.2  379.49  5000.5  379.99  5002.8  379.99  5018.2  388.28  5041.4  386.81
  5072.4  386.76  5134.2  388.63  5154.8  389.66  5175.4  391.89  5193.7   391.7
  5216.7  393.49  5229.6   393.1  5319.7   396.5  5371.3  399.49  5412.5   400.5
#Mann= 5 ,-1 , 0
  3825.6     .05       0  4918.6     .12       0  4994.5     .07       0
  5000.5     .12       0  5193.7     .05       0
Bank Sta=4915.4,5018.2
XS Rating Curve= 0 ,0
Exp/Cntr=0.3,0.1

Type RM Length L Ch R = 1 ,179853  ,1471,1471,1471
BEGIN DESCRIPTION:
HURRICANE BAYOU 167.0
END DESCRIPTION:
XS GIS Cut Line= 3
      3846962.97     10495681.04      3847348.39     10496967.51
      3847749.62      10497260.2
#Sta/Elev= 30
  3752.9   410.5  3757.9  409.76  3867.6  407.19  3999.9  402.52  4430.6  390.35
  4691.5  387.95  4935.7  384.53  4978.4  385.04  4983.8   382.2  5001.7  379.83
  5004.5  379.33  5007.7  379.83  5016.7  383.82  5025.6   384.1  5056.9  384.09
  5077.6  382.47    5093  384.16  5156.4  384.41    5184  386.68  5198.2  386.26
  5242.2   387.9  5363.5  388.75  5369.7  389.71  5434.5   392.2    5443  393.24
  5449.2  392.66  5484.7  393.04  5514.1  395.27  5534.9   395.5  5592.5  398.73
#Mann= 5 ,-1 , 0
  3752.9     .05       0  4935.7     .07       0  5001.7     .07       0
  5007.7     .07       0    5093     .05       0
Bank Sta=4978.4,5025.6
XS Rating Curve= 0 ,0
Exp/Cntr=0.3,0.1

Type RM Length L Ch R = 1 ,178382  ,1591,1591,1591
BEGIN DESCRIPTION:
HURRICANE BAYOU 166.0
END DESCRIPTION:
XS GIS Cut Line= 3
      3846482.08     10495698.46      3846499.44     10497391.12
       3847662.6      10498771.3
#Sta/Elev= 30
  2803.3  402.43    2915  399.38  2992.4   395.4    3135  390.69  3205.1  389.64
  3485.7  388.59  3875.1  388.22  4115.1  389.52  4145.1  388.12  4493.1  383.13
  4956.6   379.6  4991.8   378.9  4996.5   376.5  4999.2     376  5002.5   376.5
  5020.3  377.35  5034.6  379.69  5148.7   385.7  5162.1  384.98  5539.1  387.79
    5638  390.44  5652.3  389.32  5658.8  390.51    5716  391.91  5751.2  390.93
  5779.8  392.65  6155.7  391.46  6184.2  393.86  6206.2  392.05    6301  392.31
#Mann= 5 ,-1 , 0
  2803.3     .05       0  2992.4     .16       0  3485.7     .05       0
  4996.5     .03       0  5002.5     .05       0
Bank Sta=4956.6,5034.6
XS Rating Curve= 0 ,0
Exp/Cntr=0.3,0.1

Type RM Length L Ch R = 1 ,176791  ,436,436,436
BEGIN DESCRIPTION:
HURRICANE BAYOU 165.0
END DESCRIPTION:
XS GIS Cut Line= 3
       3845638.4     10496523.29      3845883.19     10497976.85
      3846591.39     10498626.11
#Sta/Elev= 30
  3841.9  386.65  4058.4  393.58  4179.4  394.74  4300.5  391.38  4437.1  384.14
  4518.2  381.29  4710.9   381.6  4832.6  379.99  4900.7  375.59    4934  376.13
  4961.3  373.87  4966.3  375.56    5002  371.66  5004.7  371.16    5008  371.66
  5015.1  371.94  5021.8   374.4  5026.9  372.79  5035.4  374.91  5065.8  376.21
  5217.9  377.51  5612.9   384.7  5627.1  383.88  5761.5  385.89    5960  386.81
  5974.2  386.25  5988.4  381.32  6002.6  386.12  6023.5  387.17  6276.7  387.39
#Mann= 3 ,-1 , 0
  3841.9     .05       0    5002     .03       0    5008     .05       0
Bank Sta=4934,5065.8
XS Rating Curve= 0 ,0
Exp/Cntr=0.3,0.1

Type RM Length L Ch R = 1 ,176355  ,476,476,476
BEGIN DESCRIPTION:
HURRICANE BAYOU 164.0
END DESCRIPTION:
XS GIS Cut Line= 3
      3845549.61     10496860.22      3845518.53     10497816.47
      3845979.07     10498492.69
#Sta/Elev= 30
  4319.1  400.23  4349.1  398.95  4399.1  395.29  4479.1  391.94  4539.2  387.17
  4549.2  385.64  4599.2  383.84  4639.2  380.89  4789.3  377.38  4979.4  375.99
  4989.4  374.34  4996.4  369.92  4999.2  369.42  5002.4  369.92  5009.4  373.34
  5029.4  374.32  5189.5  375.25  5286.5  377.98  5307.5  377.56  5558.9  379.89
  5567.8  380.52  5582.7  380.11  5675.5  382.32  5696.5  381.94  5840.2  384.04
  5861.1  385.01  5876.1  384.25  6049.6  385.43  6064.5  386.07    6094  385.81
#Mann= 3 ,-1 , 0
  4319.1     .05       0  4996.4     .03       0  5002.4     .05       0
Bank Sta=4979.4,5029.4
XS Rating Curve= 0 ,0
Exp/Cntr=0.3,0.1

Type RM Length L Ch R = 1 ,175879  ,401,401,401
BEGIN DESCRIPTION:
HURRICANE BAYOU 163.0
END DESCRIPTION:
XS GIS Cut Line= 3
      3845449.61     10496810.19      3845119.23     10497495.29
      3845415.09     10498349.72
#Sta/Elev= 30
  4406.6  401.95    4451  399.37  4473.2  396.26  4488.5  396.15  4517.6  393.76
    4562  392.16  4624.2  385.93  4684.1  382.89    4692  381.75  4795.2     377
  4850.3  376.08  4895.1  374.14  4906.7  372.55  4974.5  373.49  4983.9  369.34
  4988.6   368.4  4991.3   367.9  4994.6   368.4  4997.1  368.42  5006.1  371.81
  5014.2  372.69    5082  374.49  5110.2  373.16  5167.1  374.67  5518.1  378.01
  5627.4  377.57  5730.9  379.88  5824.3  383.39  5966.1     385  6071.4  385.11
#Mann= 3 ,-1 , 0
  4406.6     .05       0  4988.6     .03       0  4994.6     .05       0
Bank Sta=4974.5,5014.2
XS Rating Curve= 0 ,0
Exp/Cntr=0.3,0.1

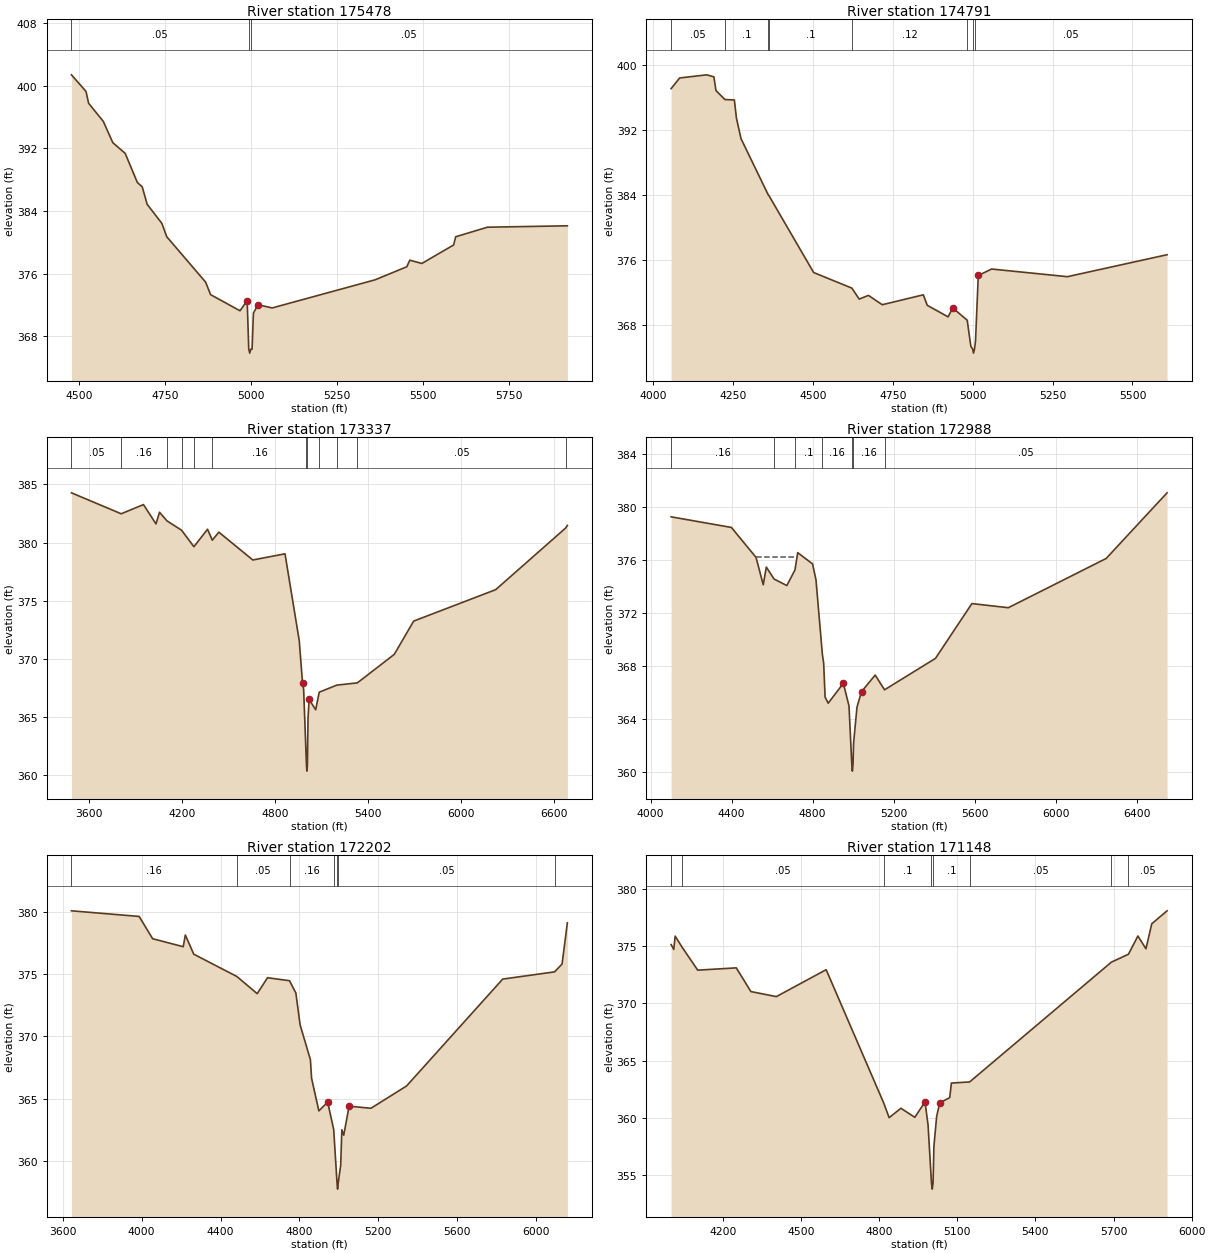
Type RM Length L Ch R = 1 ,175478  ,687,687,687
BEGIN DESCRIPTION:
HURRICANE BAYOU 162.0
END DESCRIPTION:
XS GIS Cut Line= 3
       3845349.6      10496760.2      3844949.61     10497110.19
      3844752.88     10497996.73
#Sta/Elev= 30
  4478.7  401.38  4520.9  399.26  4528.5  397.75  4571.2  395.43  4598.7  392.72
  4634.8  391.34  4669.9  387.64  4684.2  387.07  4698.4  384.85  4741.1  382.41
  4755.4   380.7  4868.3   374.9  4882.5  373.31    4968  371.25  4988.8  372.55
  4993.4  366.34  4996.2  365.84  4999.4  366.34  5003.1  366.35  5006.9  370.95
  5020.4  372.02  5061.4  371.61    5360   375.2  5452.2  376.87  5460.9  377.71
  5495.8  377.29  5588.1  379.65  5594.1   380.7  5686.2  381.92  5918.3   382.1
#Mann= 3 ,-1 , 0
  4478.7     .05       0  4993.4     .03       0  4999.4     .05       0
Bank Sta=4988.8,5020.4
XS Rating Curve= 0 ,0
Exp/Cntr=0.3,0.1

Type RM Length L Ch R = 1 ,174791  ,1454,1454,1454
BEGIN DESCRIPTION:
HURRICANE BAYOU 160.0
END DESCRIPTION:
XS GIS Cut Line= 3
        3845206.     10496549.14      3844598.39     10497035.22
      3843969.94     10497485.96
#Sta/Elev= 30
  4056.8   397.1  4083.3  398.41  4168.2   398.8  4190.6  398.55    4197  396.86
  4225.1  395.76  4254.6  395.71    4261   393.5  4275.4  390.95  4361.1     384
  4362.4  383.97  4502.7  374.49  4622.3  372.57  4645.2  371.22    4674  371.68
  4717.3  370.53  4845.7  371.75  4858.1  370.46  4923.2  369.04  4937.9  370.13
  4983.1  368.63  4994.4  365.42    5000  365.08  5002.7  364.58    5006  365.08
  5009.1  366.11  5017.7  374.13  5059.5  374.92  5296.5  373.98  5608.3  376.68
#Mann= 8 ,-1 , 0
  4056.8     .05       0  4225.1      .1       0  4361.1     .16       0
  4362.4      .1       0  4622.3     .12       0  4983.1     .05       0
    5000     .03       0    5006     .05       0
Bank Sta=4937.9,5017.7
XS Rating Curve= 0 ,0
Exp/Cntr=0.3,0.1

Type RM Length L Ch R = 1 ,173337  ,349,349,349
BEGIN DESCRIPTION:
HURRICANE BAYOU 159.0
END DESCRIPTION:
XS GIS Cut Line= 4
      3845301.54     10495620.28      3844181.73     10496323.42
      3843730.34     10496783.49      3843140.98     10497866.86
#Sta/Elev= 30
  3485.5  384.28  3806.4  382.48  3950.1  383.27  4030.9  381.61  4053.8  382.61
  4101.7  381.87  4195.9  381.07  4275.7  379.65  4363.6  381.15  4394.3  380.21
  4436.7   380.9  4655.8  378.51  4863.5  379.04  4955.5  371.57  4976.7  367.92
  4983.8  367.38    5002  360.87  5004.7  360.37    5008  360.87  5012.1  364.91
  5019.1  366.53  5061.5  365.64  5084.2  367.15  5197.6  367.76  5330.1  367.95
  5568.5   370.4  5693.9  373.26    6223  375.96  6673.9  381.25  6685.6  381.48
#Mann= 12 ,-1 , 0
  3485.5     .05       0  3806.4     .16       0  4101.7     .05       0
  4195.9     .16       0  4275.7     .12       0  4394.3     .16       0
    5002     .07       0    5008     .16       0  5084.2     .05       0
  5197.6     .16       0  5330.1     .05       0  6673.9     .08       0
#XS Ineff= 1 ,-1
  4190.4  4363.6     381
Permanent Ineff=
       F
Bank Sta=4976.7,5019.1
XS Rating Curve= 0 ,0
Exp/Cntr=0.3,0.1

Type RM Length L Ch R = 1 ,172988  ,786,786,786
BEGIN DESCRIPTION:
HURRICANE BAYOU 158.0
END DESCRIPTION:
XS GIS Cut Line= 3
      3844494.23     10496010.92      3843825.83     10496184.53
      3843049.59     10497760.22
#Sta/Elev= 30
  4101.7  379.24    4399  378.44  4520.7  376.18  4556.1  374.12  4571.4  375.45
  4609.6  374.55  4672.6  374.06  4712.8  375.24  4726.4  376.54  4799.6  375.69
  4816.5  374.48  4847.8  368.89  4854.3  368.22  4861.4  365.65  4876.6  365.19
  4951.3  366.69  4979.3  364.99  4993.2  360.57  4995.9  360.07  4999.2  360.57
  5001.8  362.15  5018.7  364.89  5041.1  366.06  5108.5  367.31  5154.7   366.2
  5406.1  368.57  5585.8   372.7  5765.5  372.39  6248.3   376.1  6548.8  381.05
#Mann= 7 ,-1 , 0
  4101.7     .16       0  4609.6     .12       0  4712.8      .1       0
  4847.8     .16       0  4993.2     .07       0  4999.2     .16       0
  5154.7     .05       0
#XS Ineff= 1 ,-1
  4520.7  4726.4   376.2
Permanent Ineff=
       F
Bank Sta=4951.3,5041.1
XS Rating Curve= 0 ,0
Exp/Cntr=0.3,0.1

Type RM Length L Ch R = 1 ,172202  ,1054,1054,1054
BEGIN DESCRIPTION:
HURRICANE BAYOU 157.0
END DESCRIPTION:
XS GIS Cut Line= 3
      3844181.69     10495663.71      3843400.48     10495950.15
      3842532.43     10497391.12
#Sta/Elev= 30
    3644  380.08  3987.1  379.63  4055.6  377.84  4210.7   377.2  4221.4  378.14
    4264   376.6  4482.5  374.81  4585.7  373.43  4638.1  374.71  4749.6  374.47
  4781.8  373.48  4803.2  370.93  4855.6  368.12  4861.4  366.64  4898.3  364.02
  4943.1  364.72  4973.6  362.52  4990.5  358.24  4993.2  357.74  4996.5  358.24
    5009  359.65  5014.8   362.5  5024.5  362.07  5051.7   364.4  5162.4  364.23
    5343  366.02  5830.4   374.6  6093.4  375.18  6131.4  375.81  6158.3  379.12
#Mann= 7 ,-1 , 0
    3644     .16       0  4482.5     .05       0  4749.6     .16       0
  4973.6     .05       0  4990.5     .03       0  4996.5     .05       0
  6093.4     .08       0
Bank Sta=4943.1,5051.7
XS Rating Curve= 0 ,0
Exp/Cntr=0.3,0.1

Type RM Length L Ch R = 1 ,171148  ,491,491,491
BEGIN DESCRIPTION:
HURRICANE BAYOU 156.0
END DESCRIPTION:
XS GIS Cut Line= 3
      3843399.63     10495860.18      3842548.12     10496167.38
      3842099.59     10497060.23
#Sta/Elev= 30
  4001.1  375.12  4011.1   374.7  4016.5  375.86  4043.6  374.88  4103.2  372.89
  4251.3  373.09  4307.3  371.02  4405.1  370.58  4596.4  372.93  4817.4  361.29
  4838.3  360.01  4883.5  360.83  4936.9  360.04    4976  361.39  4987.8  359.35
  5000.9  354.27  5003.7  353.77  5006.9  354.27  5010.2  357.51  5020.7  360.12
  5032.6   361.3  5070.9  361.76  5077.3  363.03  5147.4  363.13  5691.8  373.59
  5757.3  374.28  5793.5  375.87  5824.5  374.76  5846.8  376.94  5905.5  378.07
#Mann= 8 ,-1 , 0
  4001.1     .16       0  4043.6     .05       0  4817.4      .1       0
  5000.9     .07       0  5006.9      .1       0  5147.4     .05       0
  5691.8     .08       0  5757.3     .05       0
Bank Sta=4976,5032.6
XS Rating Curve= 0 ,0
Exp/Cntr=0.3,0.1

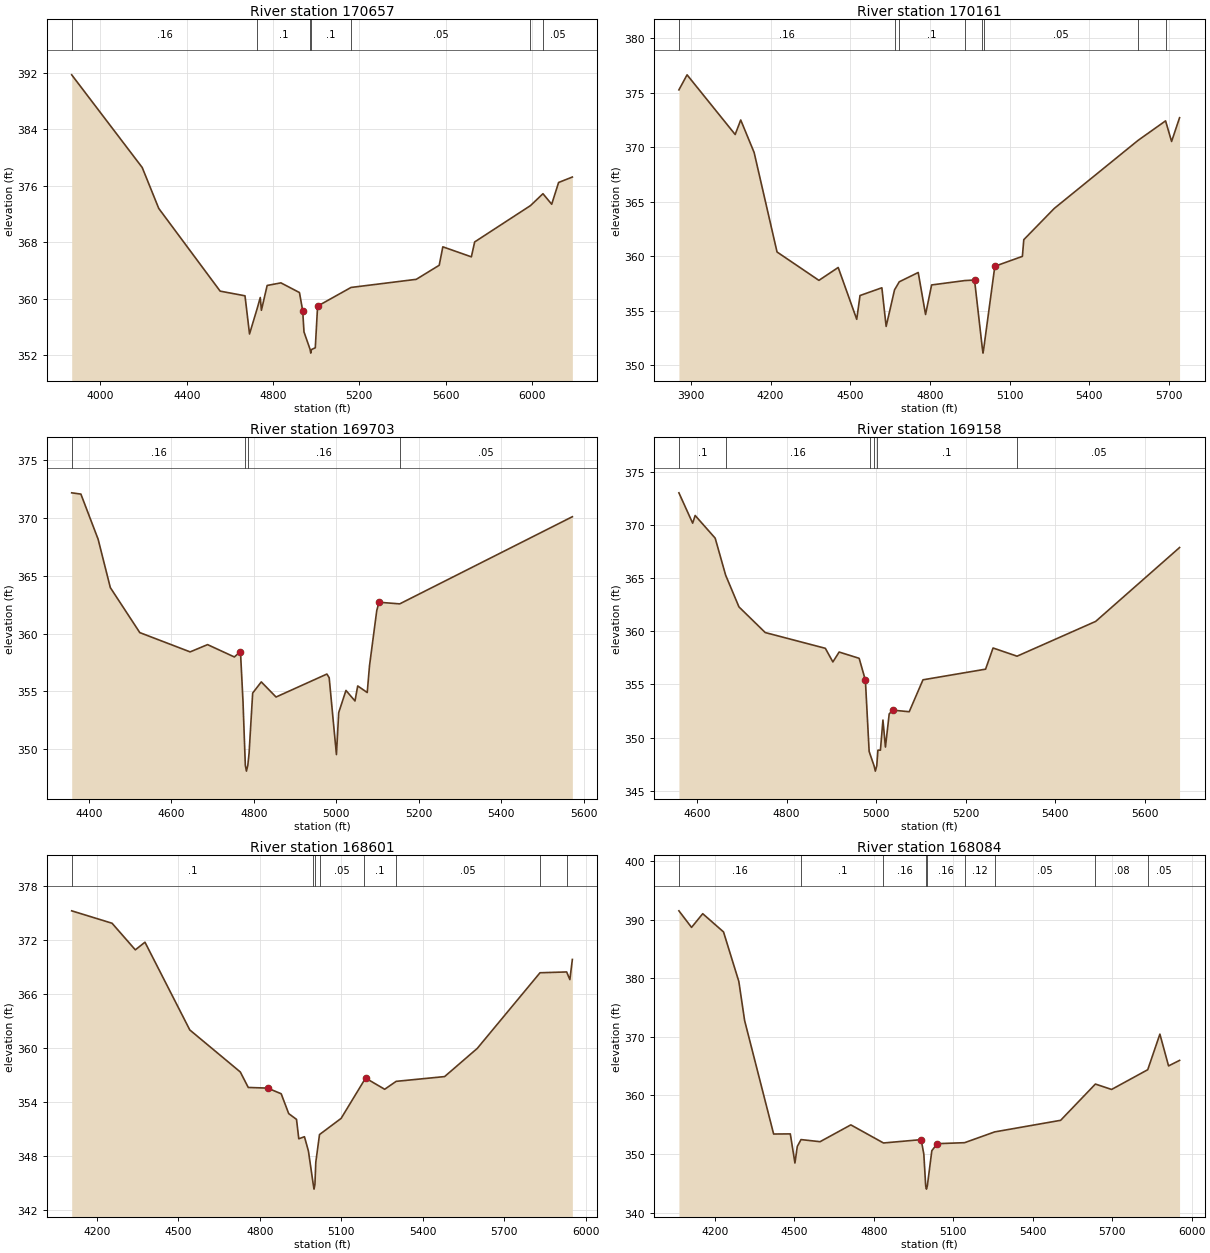
Type RM Length L Ch R = 1 ,170657  ,496,496,496
BEGIN DESCRIPTION:
HURRICANE BAYOU 155.0
END DESCRIPTION:
XS GIS Cut Line= 3
      3842806.73     10494816.48      3842449.61     10495910.19
      3842049.61     10497010.18
#Sta/Elev= 30
  3866.9  391.69  4193.8  378.58  4270.5  372.79  4555.1  361.09  4670.3  360.43
  4691.3  355.03  4727.2  358.67  4741.1  360.19  4746.4  358.38    4773  361.89
  4836.8  362.26  4922.8  360.89  4937.7  358.33  4943.8  355.32  4972.4  352.82
  4975.1  352.32  4978.4  352.82  4996.2  353.08  5006.9  358.97  5161.8  361.61
  5464.3  362.76  5570.7  364.75  5587.4  367.36  5719.7  365.94    5735  368.05
  5993.8  373.19  6051.6  374.87  6092.1  373.38  6124.1  376.46  6187.9  377.23
#Mann= 7 ,-1 , 0
  3866.9     .16       0  4727.2      .1       0  4972.4     .07       0
  4978.4      .1       0  5161.8     .05       0  5993.8     .08       0
  6051.6     .05       0
Bank Sta=4937.7,5006.9
XS Rating Curve= 0 ,0
Exp/Cntr=0.3,0.1

Type RM Length L Ch R = 1 ,170161  ,458,458,458
BEGIN DESCRIPTION:
HURRICANE BAYOU 154.0
END DESCRIPTION:
XS GIS Cut Line= 4
      3842509.88     10494946.64      3842176.52     10495420.64
      3842114.02     10495941.47      3841832.76     10496670.66
#Sta/Elev= 30
  3854.8  375.24  3885.5  376.62  4066.7  371.15  4087.6  372.48  4138.1   369.5
  4224.4  360.38  4382.1  357.78  4454.7  358.96  4524.5  354.21  4536.9  356.39
  4619.2   357.1  4635.3  353.56  4666.9  356.91  4684.8  357.65  4756.1   358.5
  4783.7  354.65  4806.5  357.36  4931.4  357.76  4968.2  357.81  4997.3  351.61
  5000.1  351.11  5003.3  351.61  5044.6  359.07  5148.4  359.98  5153.7  361.51
  5268.3  364.37    5584  370.61  5687.7   372.4  5710.3  370.51  5740.4  372.69
#Mann= 8 ,-1 , 0
  3854.8     .16       0  4666.9     .05       0  4684.8      .1       0
  4931.4     .05       0  4997.3     .03       0  5003.3     .05       0
    5584     .08       0  5687.7     .05       0
Bank Sta=4968.2,5044.6
XS Rating Curve= 0 ,0
Exp/Cntr=0.3,0.1

Type RM Length L Ch R = 1 ,169703  ,545,545,545
BEGIN DESCRIPTION:
HURRICANE BAYOU 153.0
END DESCRIPTION:
XS GIS Cut Line= 3
      3842199.62     10495110.17      3841849.61     10495610.19
      3841599.61     10496160.19
#Sta/Elev= 30
  4358.2  372.19  4380.5  372.08  4422.3  368.17  4451.9  363.98  4523.4  360.08
  4645.5  358.41  4687.8  359.04  4752.8  357.97  4767.6  358.44  4773.7  354.15
  4779.4  348.58  4782.1  348.08  4785.4  348.58  4788.5  349.64  4797.2  354.84
  4818.1  355.81  4853.9   354.5  4977.3  356.49  4982.8  356.17  5000.4  349.51
  5005.9  353.15  5023.5  355.07  5045.4  354.16    5052  355.46  5075.1  354.89
  5080.6   357.2  5098.2  361.99  5103.7  362.71  5153.9  362.57  5572.7  370.12
#Mann= 4 ,-1 , 0
  4358.2     .16       0  4779.4     .07       0  4785.4     .16       0
  5153.9     .05       0
Bank Sta=4767.6,5103.7
XS Rating Curve= 0 ,0
Exp/Cntr=0.3,0.1

Type RM Length L Ch R = 1 ,169158  ,557,557,557
BEGIN DESCRIPTION:
HURRICANE BAYOU 152.0
END DESCRIPTION:
XS GIS Cut Line= 3
       3841949.6     10494960.21      3841749.61     10495360.19
      3841449.62     10495960.17
#Sta/Elev= 30
  4559.7     373  4590.4  370.15    4596  370.87  4640.7  368.74    4664  365.27
  4693.8  362.28  4752.5  359.87  4886.7  358.39  4903.5  357.11  4917.5  358.04
  4962.2  357.45  4976.1   355.4  4984.5   348.7  4986.9   348.4  4995.5  347.35
  4998.3  346.85  5001.5  347.35  5004.1  348.82  5009.7  348.82  5015.3  351.65
  5020.9  349.11  5029.3  352.23  5037.6  352.58    5074  352.43  5104.7  355.43
  5244.5  356.43  5261.2  358.42  5314.8  357.65  5490.4  360.92  5677.7  367.86
#Mann= 6 ,-1 , 0
  4559.7      .1       0    4664     .16       0  4986.9      .1       0
  4995.5     .07       0  5001.5      .1       0  5314.8     .05       0
Bank Sta=4976.1,5037.6
XS Rating Curve= 0 ,0
Exp/Cntr=0.3,0.1

Type RM Length L Ch R = 1 ,168601  ,517,517,517
BEGIN DESCRIPTION:
HURRICANE BAYOU 151.0
END DESCRIPTION:
XS GIS Cut Line= 3
      3842103.24     10494686.48      3841316.78     10495264.61
      3841254.29     10496129.16
#Sta/Elev= 30
  4107.3  375.27  4255.8  373.89  4341.5  370.93    4377  371.78    4542  362.02
    4728  357.34  4757.2  355.62  4828.3  355.55  4878.4  354.92  4906.1  352.71
  4934.8  352.07  4943.2  349.91  4964.1  350.14  4978.7  348.54  4996.6  344.81
  4999.3  344.31  5002.6  344.81  5005.8   347.3  5019.5  350.38    5099  352.18
  5183.6  356.39  5189.2  356.66  5259.4  355.42  5301.7   356.3    5480  356.83
  5600.3  359.97  5831.1  368.38  5929.2  368.47    5941  367.62  5950.2  369.86
#Mann= 8 ,-1 , 0
  4107.3      .1       0  4996.6     .07       0  5002.6      .1       0
  5019.5     .05       0  5183.6      .1       0  5301.7     .05       0
  5831.1     .08       0  5929.2     .05       0
Bank Sta=4828.3,5189.2
XS Rating Curve= 0 ,0
Exp/Cntr=0.3,0.1

Type RM Length L Ch R = 1 ,168084  ,676,676,676
BEGIN DESCRIPTION:
HURRICANE BAYOU 150.0
END DESCRIPTION:
XS GIS Cut Line= 3
      3840801.15     10494274.99      3841025.12     10494941.69
      3840837.62     10496113.57
#Sta/Elev= 30
  4064.5  391.53  4112.2   388.7  4154.4  391.04  4232.9  387.93  4290.7  379.47
  4312.6  372.79  4422.1  353.42  4485.1  353.44  4502.5  348.47  4511.4   351.3
  4525.5  352.47  4597.4  352.11  4713.5  354.98  4836.8  351.89    4979  352.46
  4989.1  349.99  4996.2  344.51    4999  344.01  5002.2  344.51  5019.3  350.57
  5039.7  351.77    5143  351.94  5256.5  353.78  5505.6  355.76  5636.8  361.95
    5698  361.03  5834.4   364.4  5880.3  370.48    5913  365.05  5954.6  365.99
#Mann= 9 ,-1 , 0
  4064.5     .16       0  4525.5      .1       0  4836.8     .16       0
  4996.2     .07       0  5002.2     .16       0    5143     .12       0
  5256.5     .05       0  5636.8     .08       0  5834.4     .05       0
Bank Sta=4979,5039.7
XS Rating Curve= 0 ,0
Exp/Cntr=0.3,0.1

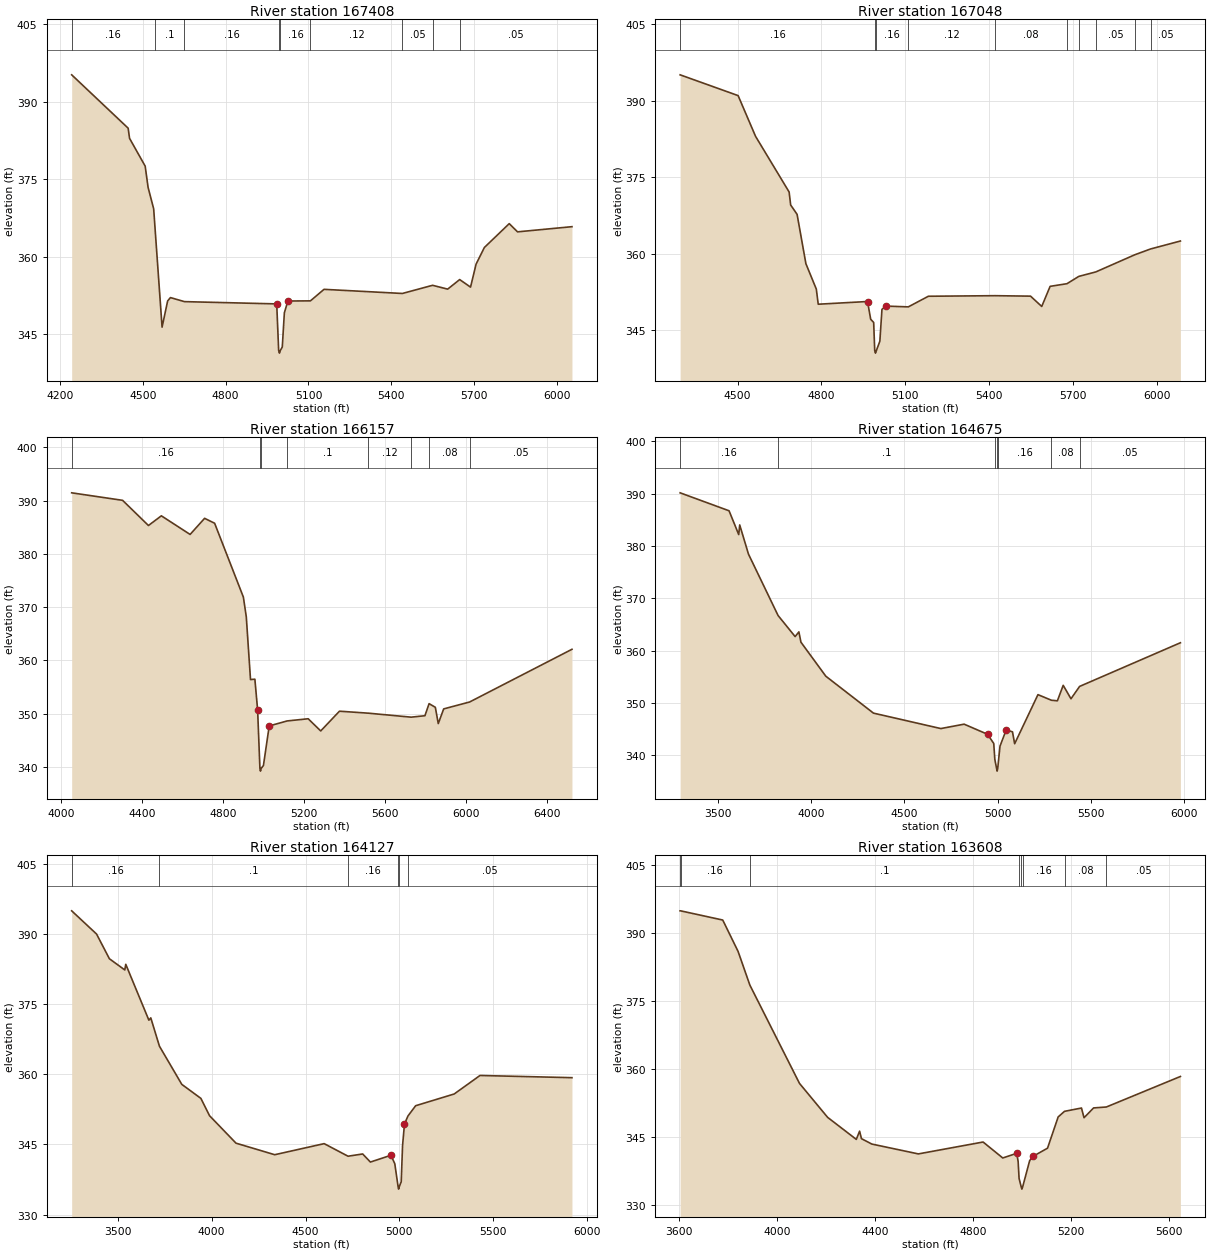
Type RM Length L Ch R = 1 ,167408  ,360,360,360
BEGIN DESCRIPTION:
HURRICANE BAYOU 149.0
END DESCRIPTION:
XS GIS Cut Line= 3
      3840717.82     10494196.91      3840582.41     10495035.44
      3840530.43     10495997.04
#Sta/Elev= 30
  4242.1  395.23  4446.7   384.9  4451.8  382.93  4508.4  377.55  4518.9  373.45
  4539.2  369.27    4544  365.62  4569.6  346.38  4589.8  351.46    4600   352.1
  4650.6  351.32  4984.9  350.88    4992  341.85  4994.8  341.35    4998  341.85
  5005.1  342.55  5012.6  349.16  5025.4  351.44  5107.1  351.47  5156.3   353.7
  5440.1   352.9  5549.6  354.48  5604.3  353.74  5647.7  355.59  5687.1  354.13
  5707.1  358.57  5737.2   361.8  5827.3  366.42  5857.4  364.83  6054.5  365.83
#Mann= 9 ,-1 , 0
  4242.1     .16       0    4544      .1       0  4650.6     .16       0
    4992     .07       0    4998     .16       0  5107.1     .12       0
  5440.1     .05       0  5549.6     .08       0  5647.7     .05       0
Bank Sta=4984.9,5025.4
XS Rating Curve= 0 ,0
Exp/Cntr=0.3,0.1

Type RM Length L Ch R = 1 ,167048  ,891,891,891
BEGIN DESCRIPTION:
HURRICANE BAYOU 148.0
END DESCRIPTION:
XS GIS Cut Line= 3
      3840598.55     10494151.93        3840168.     10495082.49
      3840140.24     10495845.75
#Sta/Elev= 30
  4294.7  395.07  4502.1     391  4564.4  383.03  4684.5  372.12    4690  369.58
    4713  367.74  4744.5  358.08  4781.7  353.11  4788.6  350.14  4964.9  350.67
  4976.2   347.2  4986.9  346.56  4990.6  341.06  4993.3  340.56  4996.6  341.06
    5009   342.9  5016.5  349.14    5031  349.77  5110.8  349.62  5182.5   351.7
  5421.1  351.81  5547.9  351.72  5587.9   349.7  5617.9  353.64  5678.2  354.16
  5720.5  355.59  5781.5  356.47  5920.9  359.83    5977  360.96  6083.8  362.52
#Mann= 10 ,-1 , 0
  4294.7     .16       0  4990.6     .07       0  4996.6     .16       0
  5110.8     .12       0  5421.1     .08       0  5678.2     .05       0
  5720.5     .16       0  5781.5     .05       0  5920.9     .16       0
    5977     .05       0
Bank Sta=4964.9,5031
XS Rating Curve= 0 ,0
Exp/Cntr=0.3,0.1

Type RM Length L Ch R = 1 ,166157  ,1482,1482,1482
BEGIN DESCRIPTION:
HURRICANE BAYOU 147.0
END DESCRIPTION:
XS GIS Cut Line= 3
      3840577.72     10493554.71      3839949.61     10494310.19
      3839598.67     10495755.61
#Sta/Elev= 30
  4052.7  391.47  4304.1  390.06  4431.7  385.33  4495.5  387.15  4637.4  383.65
    4709  386.68  4758.5  385.75  4900.4  371.88  4914.8  368.17  4935.6  356.39
  4957.2  356.45  4970.7  350.69  4982.1  339.68  4984.8  339.18  4988.1  339.68
  4999.4  340.24    5028  347.67  5116.9  348.61  5220.4  349.02  5282.2  346.73
  5374.8  350.44  5517.1  350.07  5728.6  349.32  5796.7  349.59  5817.3  351.86
  5848.1  351.17  5862.6  348.11  5889.3  350.87  6017.4  352.17  6522.6  362.07
#Mann= 8 ,-1 , 0
  4052.7     .16       0  4982.1     .07       0  4988.1     .16       0
  5116.9      .1       0  5517.1     .12       0  5728.6     .05       0
  5817.3     .08       0  6017.4     .05       0
Bank Sta=4970.7,5028
XS Rating Curve= 0 ,0
Exp/Cntr=0.3,0.1

Type RM Length L Ch R = 1 ,164675  ,548,548,548
BEGIN DESCRIPTION:
HURRICANE BAYOU 145.0
END DESCRIPTION:
XS GIS Cut Line= 2
      3839313.84     10492728.29      3838564.21      10495303.4
#Sta/Elev= 30
  3297.9  390.13  3560.3   386.7  3612.1  382.15  3617.3     384  3664.4  378.42
  3823.1  366.69  3914.4  362.67  3934.6  363.57  3945.6   361.6    4079   355.1
  4334.4  348.05  4695.6   345.1  4820.5  345.94  4945.8  344.01  4979.3  342.25
    4985  339.22  4994.5  337.47  4997.3  336.97  5000.5  337.47  5012.8  341.75
  5046.3  344.86  5079.8  344.47  5091.3   342.2  5216.3  351.58  5288.3  350.51
  5320.4   350.4  5351.6  353.36  5393.3  350.79  5439.5  353.15  5979.9  361.49
#Mann= 7 ,-1 , 0
  3297.9     .16       0  3823.1      .1       0    4985     .16       0
  4994.5     .07       0  5000.5     .16       0  5288.3     .08       0
  5439.5     .05       0
Bank Sta=4945.8,5046.3
XS Rating Curve= 0 ,0
Exp/Cntr=0.3,0.1

Type RM Length L Ch R = 1 ,164127  ,519,519,519
BEGIN DESCRIPTION:
HURRICANE BAYOU 144.0
END DESCRIPTION:
XS GIS Cut Line= 2
      3838904.12     10492811.61      3838251.33     10495395.01
#Sta/Elev= 30
  3254.4  394.97    3387     390  3455.3  384.72  3537.4  382.32  3542.5  383.53
  3665.6  371.58  3675.8  372.07  3721.9  366.01  3840.9  357.85  3942.6  354.85
  3988.8  351.14  4129.7  345.27  4335.9   342.8  4599.2  345.17  4726.3  342.48
  4804.4  342.96  4845.4  341.23  4954.8  342.68  4975.4  340.88  4993.1  335.94
  4995.8  335.44  4999.1  335.94  5009.6  337.01  5016.7  344.69    5027  349.39
  5045.7  351.09  5086.5  353.28  5291.7  355.79  5429.3  359.75    5919  359.28
#Mann= 6 ,-1 , 0
  3254.4     .16       0  3721.9      .1       0  4726.3     .16       0
  4993.1     .07       0  4999.1     .16       0  5045.7     .05       0
Bank Sta=4954.8,5027
XS Rating Curve= 0 ,0
Exp/Cntr=0.3,0.1

Type RM Length L Ch R = 1 ,163608  ,1036,1036,1036
BEGIN DESCRIPTION:
HURRICANE BAYOU 143.0
END DESCRIPTION:
XS GIS Cut Line= 2
      3838730.48     10492839.48       3838070.7     10494772.48
#Sta/Elev= 30
  3604.6  394.88  3606.4  394.88  3778.6  392.85  3841.3  385.93  3889.2  378.53
  4091.9  356.86  4206.7  349.38  4323.9  344.52  4337.3  346.33    4345  344.68
  4387.3  343.49  4577.3  341.32  4841.6  343.94  4921.9  340.42    4979  341.45
  4984.6  339.64  4988.5  335.91  4997.1  334.06  4999.9  333.56  5003.1  334.06
  5031.8  339.86  5047.2  340.84  5104.6  342.58  5148.1  349.47  5173.9   350.7
  5243.2  351.43  5253.7  349.29  5292.6  351.45    5345  351.66  5647.1  358.38
#Mann= 8 ,-1 , 0
  3604.6      .1       0  3606.4     .16       0  3889.2      .1       0
  4988.5     .16       0  4997.1     .07       0  5003.1     .16       0
  5173.9     .08       0    5345     .05       0
Bank Sta=4979,5047.2
XS Rating Curve= 0 ,0
Exp/Cntr=0.3,0.1