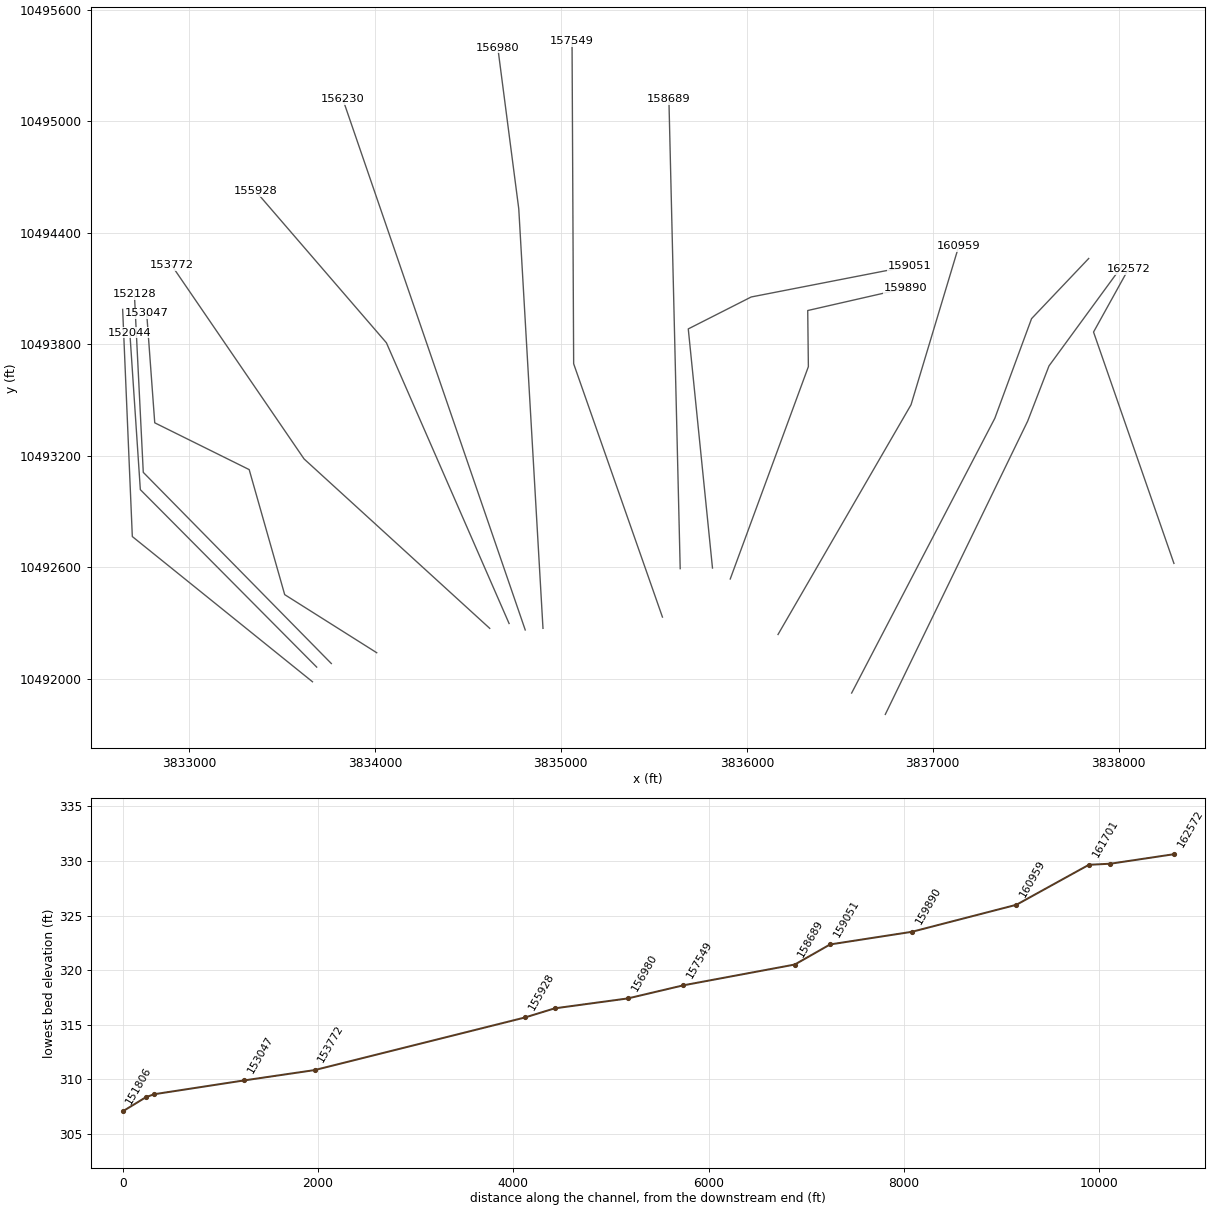
HEC-RAS study HURRICANE BAYOU.prj: HURRICANE BAYOU Base Level Engineering

--- HURRICANE BAYOU.g01 (geometry) --- (continued)

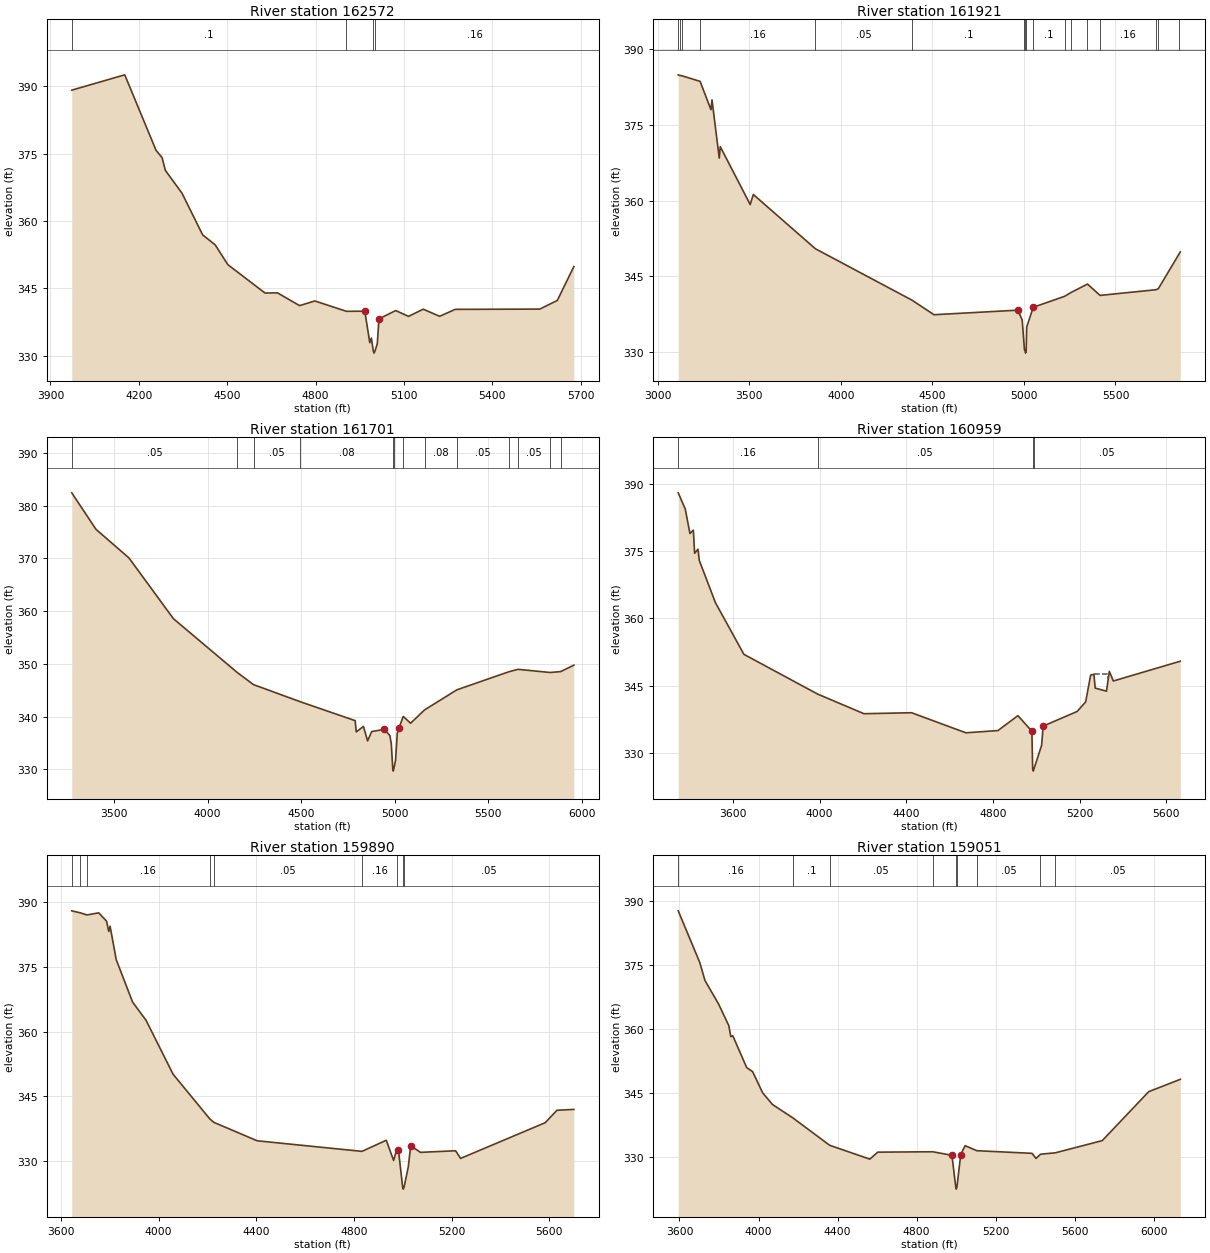
Type RM Length L Ch R = 1 ,162572  ,651,651,651
BEGIN DESCRIPTION:
HURRICANE BAYOU 142.0
END DESCRIPTION:
XS GIS Cut Line= 3
       3838296.9     10492620.27      3837864.61     10493865.04
      3838052.12     10494203.59
#Sta/Elev= 30
  3972.4  389.09  4152.3   392.5  4258.6  375.71  4279.1  374.09  4289.9  371.28
  4346.6  366.19  4416.9   356.9  4459.3   354.7  4502.2   350.3  4628.6  343.98
    4671  344.02  4745.9  341.18  4797.6  342.22  4904.9  339.92  4967.4  339.94
  4984.3  332.94  4989.6  333.98  4996.1  331.12  4998.9  330.62  5002.1  331.12
  5009.7  332.71  5015.4  338.23  5072.3  340.09  5115.6  338.79  5165.7  340.39
  5221.4  338.81  5274.4  340.35  5561.5  340.41    5621  342.34  5677.1  349.86
#Mann= 4 ,-1 , 0
  3972.4      .1       0  4904.9     .16       0  4996.1     .07       0
  5002.1     .16       0
Bank Sta=4967.4,5015.4
XS Rating Curve= 0 ,0
Exp/Cntr=0.3,0.1

Type RM Length L Ch R = 1 ,161921  ,220,220,220
BEGIN DESCRIPTION:
HURRICANE BAYOU 141.0
END DESCRIPTION:
XS GIS Cut Line= 4
      3836744.81     10491807.73      3837510.45     10493385.87
      3837625.03     10493682.75      3838020.88     10494224.44
#Sta/Elev= 30
  3111.1  384.96  3119.6  384.83    3129   384.8  3230.7  383.66    3290  378.03
  3295.6  379.99  3335.2  368.44  3340.7  370.72  3504.3  359.22  3521.3  361.22
  3860.4  350.46  4389.1  340.24  4508.4  337.37  4966.3  338.27  4990.4  336.33
  5002.9  330.35  5006.1  330.25  5008.9  329.75  5012.1  330.25    5015  334.93
  5048.4  338.59    5052  338.86  5222.1  341.02  5256.6  341.77  5347.1  343.45
  5415.9   341.2  5722.1  342.33  5734.4  342.54  5847.1   349.4  5854.3  349.84
#Mann= 17 ,-1 , 0
  3111.1     .05       0  3119.6     .08       0    3129     .05       0
  3230.7     .16       0  3860.4     .05       0  4389.1      .1       0
  5002.9     .05       0  5006.1     .07       0  5012.1     .05       0
  5048.4      .1       0  5222.1     .08       0  5256.6     .16       0
  5347.1     .08       0  5415.9     .16       0  5722.1     .05       0
  5734.4     .16       0  5847.1     .08       0
Bank Sta=4966.3,5052
XS Rating Curve= 0 ,0
Exp/Cntr=0.3,0.1

Type RM Length L Ch R = 1 ,161701  ,742,742,742
BEGIN DESCRIPTION:
HURRICANE BAYOU 140.0
END DESCRIPTION:
XS GIS Cut Line= 4
      3836563.81     10491922.72       3837333.8     10493401.06
      3837531.28     10493937.09      3837838.58     10494260.89
#Sta/Elev= 30
  3273.5  382.41  3402.7   375.5  3579.5  370.06    3817  358.55  4157.8  348.36
  4245.2  346.05  4496.4  342.79  4788.9  339.22  4794.5  337.08  4833.1  338.12
  4855.2  335.38  4877.3  337.16  4943.7  337.55  4974.2  336.41    4982  334.82
  4989.7  330.15  4992.4  329.65  4995.7  330.15  5004.6  331.66    5014  336.87
  5024.4  337.91  5045.6  340.02  5085.3  338.73  5159.6  341.25  5332.9  345.07
    5611  348.49  5659.5  348.95  5830.6  348.35  5887.9  348.52    5958  349.74
#Mann= 13 ,-1 , 0
  3273.5     .05       0  4157.8     .08       0  4245.2     .05       0
  4496.4     .08       0  4989.7     .07       0  4995.7     .08       0
  5045.6     .05       0  5159.6     .08       0  5332.9     .05       0
    5611     .08       0  5659.5     .05       0  5830.6     .08       0
  5887.9     .05       0
Bank Sta=4943.7,5024.4
XS Rating Curve= 0 ,0
Exp/Cntr=0.3,0.1

Type RM Length L Ch R = 1 ,160959  ,1069,1069,1069
BEGIN DESCRIPTION:
HURRICANE BAYOU 139.0
END DESCRIPTION:
XS GIS Cut Line= 3
      3836167.92     10492237.79      3836883.19     10493473.89
       3837139.7     10494326.62
#Sta/Elev= 30
  3346.9  387.94  3379.4  384.31  3400.9  378.88  3416.7  379.64  3422.5  374.49
  3438.2  375.39    3444  372.91  3518.6   363.5  3650.1  351.99  3990.2  343.15
  4204.6  338.77  4424.2  338.99  4675.3  334.52  4823.4  335.02  4915.5  338.34
    4980  334.88  4983.7  326.49  4986.5  325.99  4989.7  326.49    5025  331.73
  5032.2  336.01  5188.9  339.27  5228.3  341.39  5251.5  347.37  5266.6  347.54
  5272.4  344.47  5324.6  343.79  5337.8   348.2    5356  346.05  5665.5  350.46
#Mann= 4 ,-1 , 0
  3346.9     .16       0  3990.2     .05       0  4983.7     .03       0
  4989.7     .05       0
#XS Ineff= 1 ,-1
  5266.6  5332.6  347.54
Permanent Ineff=
       F
Bank Sta=4980,5032.2
XS Rating Curve= 0 ,0
Exp/Cntr=0.3,0.1

Type RM Length L Ch R = 1 ,159890  ,839,839,839
BEGIN DESCRIPTION:
HURRICANE BAYOU 137.0
END DESCRIPTION:
XS GIS Cut Line= 4
      3835910.97     10492536.41      3836331.11     10493678.76
      3836327.63     10493980.84      3836851.97     10494100.64
#Sta/Elev= 30
  3644.1     388  3678.7  387.54  3706.5  387.05  3754.7  387.53  3786.6   385.6
  3795.7  383.21  3801.1  384.44  3826.2   376.7  3893.2  366.87  3948.1  362.67
  4059.3  350.14  4208.9  339.84  4225.6  339.01  4403.6  334.72  4833.1  332.27
  4932.7  334.84  4962.7  330.15  4976.5  332.85  4982.7  332.51  4999.7  324.02
  5002.4  323.52  5005.7  324.02  5022.7  328.61  5032.7  333.57  5072.7  332.04
  5216.7  332.41  5237.2  330.64  5583.9  338.91    5632  341.79  5701.2  341.99
#Mann= 9 ,-1 , 0
  3644.1     .16       0  3678.7      .1       0  3706.5     .16       0
  4208.9      .1       0  4225.6     .05       0  4833.1     .16       0
  4976.5     .05       0  4999.7     .03       0  5005.7     .05       0
Bank Sta=4982.7,5032.7
XS Rating Curve= 0 ,0
Exp/Cntr=0.3,0.1

Type RM Length L Ch R = 1 ,159051  ,362,362,362
BEGIN DESCRIPTION:
HURRICANE BAYOU 136.0
END DESCRIPTION:
XS GIS Cut Line= 4
      3835815.48     10492595.42      3835685.27     10493881.88
      3836023.81     10494053.76      3836876.34      10494220.1
#Sta/Elev= 30
  3593.7  387.76  3702.8   375.6  3729.2  371.37  3797.7  365.88  3849.8  360.77
  3859.8   358.2  3869.9   358.4  3940.2  350.92  3970.4  349.96  4020.6  345.02
  4070.9  342.24  4174.6  339.08  4360.3  332.66  4563.4  329.41  4603.6  331.05
  4881.6  331.14  4979.1  330.31  4998.3  322.86  5001.1  322.36  5004.3  322.86
  5023.6  330.47  5045.8  332.57  5104.9  331.39  5384.4  330.77  5404.8  329.58
  5427.2  330.56  5502.9   330.9  5739.9  333.76  5975.3  345.27    6135  348.16
#Mann= 9 ,-1 , 0
  3593.7     .16       0  4174.6      .1       0  4360.3     .05       0
  4881.6     .16       0  4998.3     .07       0  5004.3     .16       0
  5104.9     .05       0  5427.2     .16       0  5502.9     .05       0
Bank Sta=4979.1,5023.6
XS Rating Curve= 0 ,0
Exp/Cntr=0.3,0.1

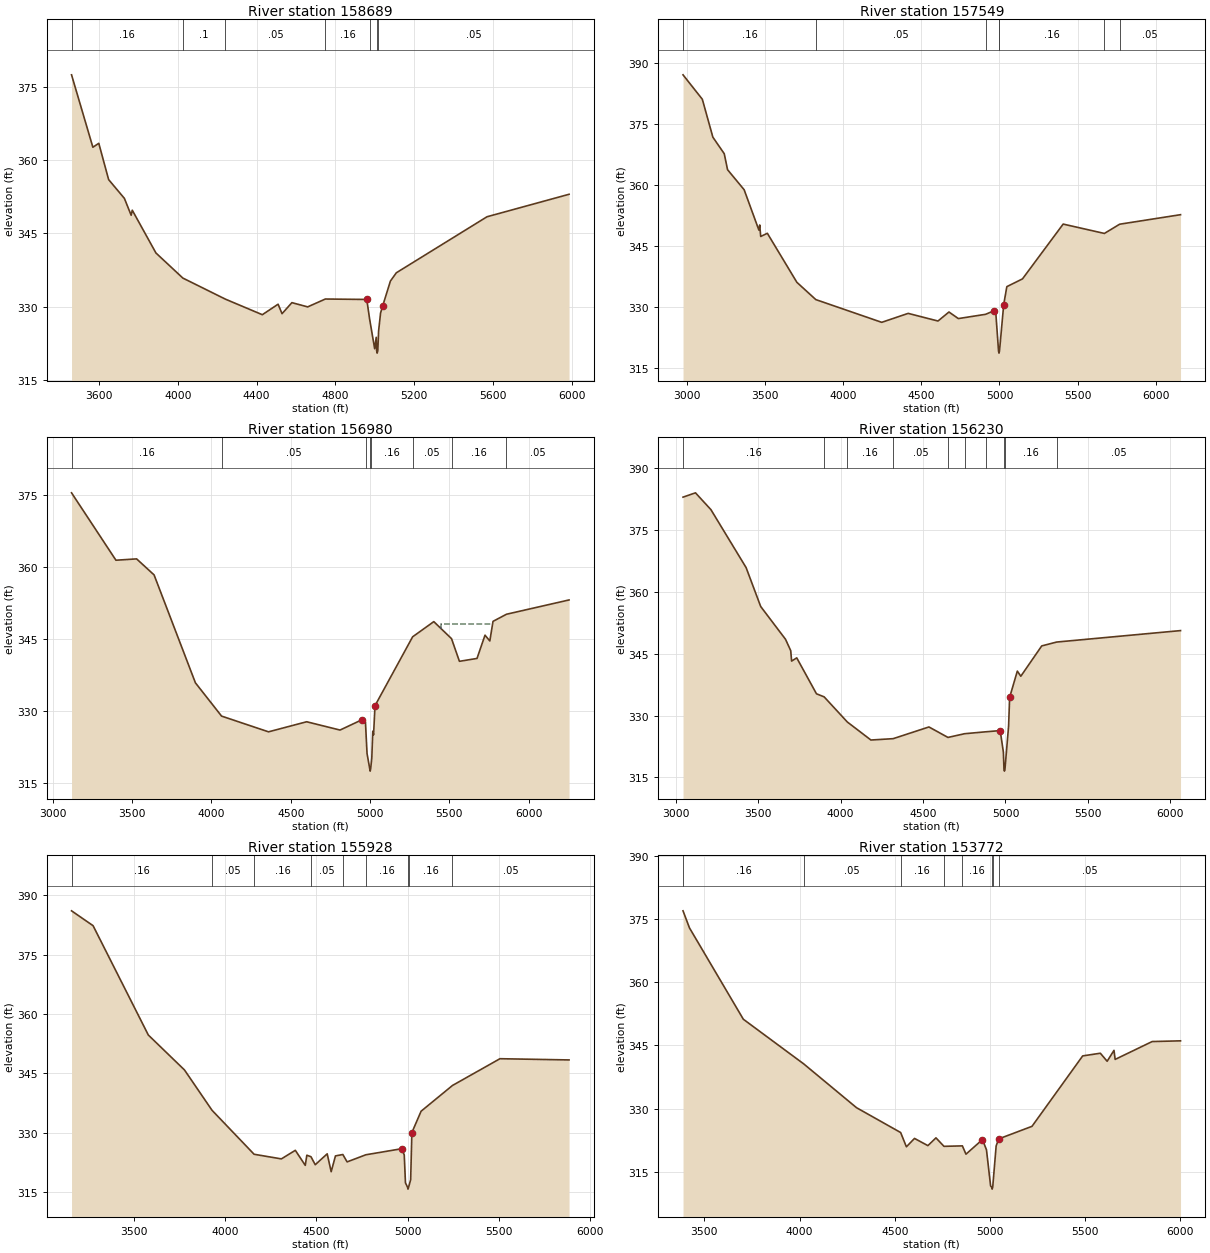
Type RM Length L Ch R = 1 ,158689  ,1140,1140,1140
BEGIN DESCRIPTION:
HURRICANE BAYOU 134.0
END DESCRIPTION:
XS GIS Cut Line= 2
      3835641.87     10492591.95      3835581.14     10495116.62
#Sta/Elev= 30
  3460.2  377.46  3568.5  362.64  3598.5  363.45  3648.5  356.02  3728.5  352.18
  3762.8  348.73  3768.5  349.76  3888.6  341.01  4025.1  335.88  4241.4  331.56
  4428.7  328.38  4508.7  330.53  4528.7  328.59  4578.8  330.85  4658.8  329.98
  4748.6  331.59  4958.9   331.5  4973.2   327.5  4998.9  321.42  5006.8  323.76
  5008.8  321.02  5011.5  320.52  5014.8  321.02  5018.9  325.06  5028.9  328.74
  5038.9  330.09  5078.9  335.27  5108.9  336.96  5569.1  348.42  5985.6  353.02
#Mann= 7 ,-1 , 0
  3460.2     .16       0  4025.1      .1       0  4241.4     .05       0
  4748.6     .16       0  4973.2     .05       0  5008.8     .03       0
  5014.8     .05       0
Bank Sta=4958.9,5038.9
XS Rating Curve= 0 ,0
Exp/Cntr=0.3,0.1

Type RM Length L Ch R = 1 ,157549  ,569,569,569
BEGIN DESCRIPTION:
HURRICANE BAYOU 133.0
END DESCRIPTION:
XS GIS Cut Line= 3
      3835546.39      10492331.5      3835068.95     10493694.38
      3835060.27     10495430.47
#Sta/Elev= 30
  2977.4  387.03  3100.8  381.02  3168.2   371.7  3240.9  367.64  3262.1  363.71
  3368.1  358.78  3462.4  348.86  3467.7  350.12    3474  347.29  3516.4  348.08
  3705.3  336.02  3826.2  331.78  4247.5  326.19  4416.6  328.39  4607.3  326.51
  4677.3  328.73  4737.3  327.11  4911.2  328.16  4967.3  329.06  4977.3  328.22
  4994.3  319.12  4997.1  318.62  5000.3  319.12  5027.3  330.56  5047.3  334.96
  5147.3  336.87  5407.3  350.34  5670.8  348.04  5768.6  350.31  6157.6  352.65
#Mann= 7 ,-1 , 0
  2977.4     .16       0  3826.2     .05       0  4911.2     .16       0
  4994.3     .03       0  5000.3     .16       0  5670.8     .16       0
  5768.6     .05       0
Bank Sta=4967.3,5027.3
XS Rating Curve= 0 ,0
Exp/Cntr=0.3,0.1

Type RM Length L Ch R = 1 ,156980  ,750,750,750
BEGIN DESCRIPTION:
Mapping XS 04caccb9
END DESCRIPTION:
XS GIS Cut Line= 3
      3834904.02     10492270.79      3834773.81     10494527.71
      3834661.01     10495395.44
#Sta/Elev= 30
  3118.3  375.43  3398.2  361.38  3528.4  361.66  3638.6  358.32    3899  335.83
  4063.9  328.89  4359.8  325.61  4600.2  327.71  4810.5  325.98  4950.7  328.16
  4970.8  327.64  4975.2  324.75  4980.8  321.08  4997.8  317.92  5000.6  317.42
  5003.8  317.92  5010.8  320.19  5016.9  325.74  5021.9  324.99  5030.9  331.06
  5268.2  345.42  5401.6  348.58  5513.3  345.03    5563  340.31  5673.9  340.91
  5724.3  345.76  5754.6  344.55  5774.8  348.64  5859.5  350.12    6254   353.1
#Mann= 8 ,-1 , 0
  3118.3     .16       0  4063.9     .05       0  4975.2     .16       0
  4997.8     .07       0  5003.8     .16       0  5268.2     .05       0
  5513.3     .16       0  5859.5     .05       0
#XS Ineff= 1 ,-1
  5448.7  5774.8  348.19
Permanent Ineff=
       F
Bank Sta=4950.7,5030.9
XS Rating Curve= 0 ,0
Exp/Cntr=0.3,0.1

Type RM Length L Ch R = 1 ,156230  ,302,302,302
BEGIN DESCRIPTION:
HURRICANE BAYOU 131.0
END DESCRIPTION:
XS GIS Cut Line= 2
      3834808.53     10492262.11       3833828.1     10495116.63
#Sta/Elev= 30
  3043.8  383.01  3119.3  384.06    3213  379.98  3426.5  365.91    3515  356.47
  3665.6  348.51  3697.2  345.75  3702.5  343.22  3733.7     344  3853.4  335.28
  3899.8  334.54  4040.4  328.44  4183.7  324.06  4318.6  324.39  4535.7  327.23
    4651  324.69  4752.1  325.59  4878.9  326.05    4968  326.35  4987.3  321.11
  4990.9  317.01  4993.7  316.51  4996.9  317.01    5019  327.52  5025.2  334.41
  5071.9  340.79    5093  339.54  5219.9   346.9  5310.2  347.84    6062  350.62
#Mann= 10 ,-1 , 0
  3043.8     .16       0  3899.8     .05       0  4040.4     .16       0
  4318.6     .05       0    4651     .16       0  4752.1     .05       0
  4878.9     .16       0  4990.9     .07       0  4996.9     .16       0
  5310.2     .05       0
Bank Sta=4968,5025.2
XS Rating Curve= 0 ,0
Exp/Cntr=0.3,0.1

Type RM Length L Ch R = 1 ,155928  ,2156,2156,2156
BEGIN DESCRIPTION:
HURRICANE BAYOU 130.0
END DESCRIPTION:
XS GIS Cut Line= 3
      3834721.74     10492296.79      3834062.01     10493807.23
      3833358.85     10494623.24
#Sta/Elev= 30
  3158.7   386.1  3276.7  382.34  3579.4  354.67  3777.5  345.83  3928.3  335.63
  4158.8   324.5  4308.2  323.33  4384.6   325.5  4439.1  321.69  4447.6  324.26
  4470.3  323.88  4493.7  321.86  4559.2  324.61    4581  320.08  4604.4  324.08
  4644.9  324.44  4668.3  322.57  4770.8  324.37    4967   325.9  4981.3  324.34
  4987.9  317.28  4999.2  316.18  5001.9  315.68  5005.2  316.18  5016.4  318.07
    5023  329.98  5073.5  335.39  5245.5  341.91  5505.7  348.68  5884.1  348.37
#Mann= 9 ,-1 , 0
  3158.7     .16       0  3928.3     .05       0  4158.8     .16       0
  4470.3     .05       0  4644.9      .1       0  4770.8     .16       0
  4999.2     .07       0  5005.2     .16       0  5245.5     .05       0
Bank Sta=4967,5023
XS Rating Curve= 0 ,0
Exp/Cntr=0.3,0.1

Type RM Length L Ch R = 1 ,153772  ,725,725,725
BEGIN DESCRIPTION:
HURRICANE BAYOU 129.0
END DESCRIPTION:
XS GIS Cut Line= 3
       3834617.6     10492270.74       3833619.3     10493182.23
      3832907.47     10494223.93
#Sta/Elev= 30
  3387.7  376.94  3421.4   372.9  3704.5   351.2  4021.9  340.59    4299   330.2
  4530.9   324.3  4561.1  320.91  4603.7   322.9    4674  321.19  4716.5  323.03
  4758.5  321.02  4855.2  321.13  4874.1  319.16  4960.8  322.63  4981.8  320.19
  5003.5  311.62  5008.6  311.36  5011.4  310.86  5014.6  311.36  5032.6  321.12
  5045.1  322.66  5047.5  322.81  5220.9  325.77  5487.1  342.49  5579.9  343.13
  5615.7  341.22  5651.6  343.81  5657.7  341.66  5852.1   345.9  6001.2  346.07
#Mann= 8 ,-1 , 0
  3387.7     .16       0  4021.9     .05       0  4530.9     .16       0
  4758.5     .05       0  4855.2     .16       0  5008.6     .07       0
  5014.6     .16       0  5045.1     .05       0
Bank Sta=4960.8,5047.5
XS Rating Curve= 0 ,0
Exp/Cntr=0.3,0.1

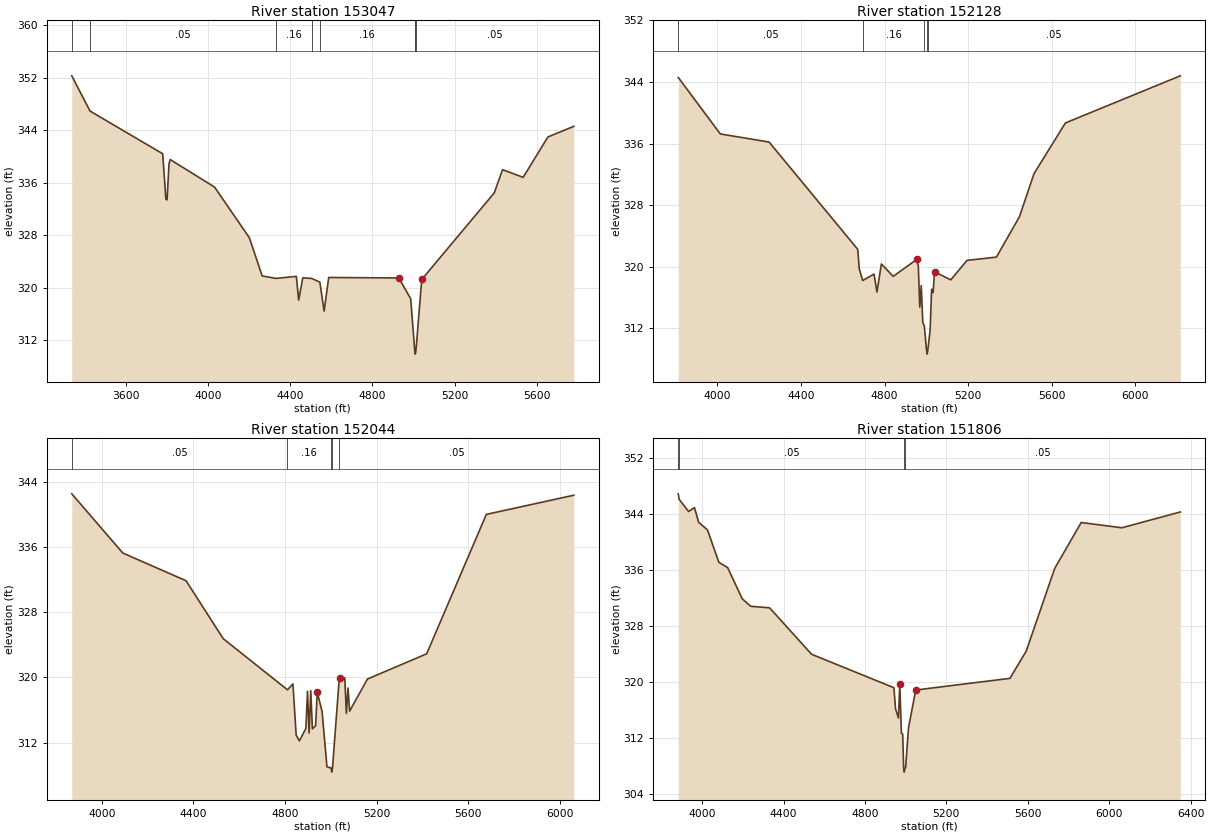
Type RM Length L Ch R = 1 ,153047  ,919,919,919
BEGIN DESCRIPTION:
HURRICANE BAYOU 128.0
END DESCRIPTION:
XS GIS Cut Line= 5
      3834009.86     10492139.68      3833515.05     10492452.19
      3833324.07     10493124.94      3832816.26     10493376.67
      3832772.93     10493966.03
#Sta/Elev= 30
  3338.1  352.29  3426.7  346.93  3780.5  340.42  3795.8  333.52  3801.7   333.4
  3811.1  338.89    3817  339.54  4032.6  335.35  4201.9  327.64  4264.3  321.82
  4331.9  321.44  4430.6  321.75  4441.9  318.13  4461.8  321.53  4505.4  321.43
  4544.9  320.87  4565.8  316.46  4587.9  321.58    4929  321.51  4986.9  318.33
  5005.7  310.75  5006.3  310.41  5009.1  309.91  5012.3  310.41  5040.6  321.28
  5393.5  334.47  5433.6     338  5533.9  336.83  5654.2  342.98  5780.4   344.6
#Mann= 8 ,-1 , 0
  3338.1     .16       0  3426.7     .05       0  4331.9     .16       0
  4505.4     .05       0  4544.9     .16       0  5005.7     .05       0
  5006.3     .07       0  5012.3     .05       0
Bank Sta=4929,5040.6
XS Rating Curve= 0 ,0
Exp/Cntr=0.3,0.1

Type RM Length L Ch R = 1 ,152128  ,84,84,84
BEGIN DESCRIPTION:
Mapping XS 2ccf1f67
END DESCRIPTION:
XS GIS Cut Line= 3
      3833765.84     10492081.48      3832754.56     10493110.12
      3832706.82     10494069.34
#Sta/Elev= 30
  3812.1  344.59  4013.6  337.25  4246.9   336.2  4671.2  322.26  4678.3  319.74
    4695  318.21  4749.1  319.05  4763.2  316.71  4784.4  320.36  4840.9  318.75
  4954.1  320.96  4961.1   320.1  4968.2  314.75  4975.2  317.55  4982.4  312.82
  4989.9  312.27  5000.5  309.15  5003.3  308.65  5006.5  309.15  5017.7  311.77
  5024.8  317.08  5031.8  316.64  5038.9  319.33  5116.7   318.3  5194.5  320.83
  5334.8  321.25  5444.9  326.48    5515   332.1  5665.2  338.68    6215   344.8
#Mann= 5 ,-1 , 0
  3812.1     .05       0    4695     .16       0  4989.9     .05       0
  5000.5     .03       0  5006.5     .05       0
Bank Sta=4954.1,5038.9
XS Rating Curve= 0 ,0
Exp/Cntr=0.3,0.1

Type RM Length L Ch R = 1 ,152044  ,238,238,238
BEGIN DESCRIPTION:
Mapping XS ffabcc76
END DESCRIPTION:
XS GIS Cut Line= 3
      3833687.11     10492062.28      3832738.78     10493017.12
      3832682.36     10493861.28
#Sta/Elev= 30
  3869.2  342.49  4092.2  335.23    4368  331.84  4530.6  324.73  4810.9  318.47
  4834.7  319.19  4848.8  312.92    4863  312.21  4891.3  313.75  4898.3   318.3
  4905.4  313.17  4912.5  318.38  4919.6  313.69  4933.7  314.07  4940.8   318.2
    4962   315.8  4983.2  309.03  5001.4  308.88  5004.2  308.38  5007.4  308.88
  5035.1  319.19  5039.7  319.93    5061  319.93    5068  315.57  5075.1  318.69
  5082.2  315.86    5160  319.79  5418.5  322.88  5679.1  339.97    6061  342.32
#Mann= 5 ,-1 , 0
  3869.2     .05       0  4810.9     .16       0  5001.4     .07       0
  5007.4     .16       0  5035.1     .05       0
Bank Sta=4940.8,5039.7
XS Rating Curve= 0 ,0
Exp/Cntr=0.3,0.1

Type RM Length L Ch R = 1 ,151806  ,151,151,151
BEGIN DESCRIPTION:
HURRICANE BAYOU 127.0
END DESCRIPTION:
XS GIS Cut Line= 3
      3833664.47     10491983.42      3832695.69     10492764.69
      3832643.68     10493986.93
#Sta/Elev= 30
    3882  346.94  3886.5  346.16  3932.9  344.41  3961.7  344.97  3982.5  342.86
  4025.7  341.78  4081.7  337.13  4124.8  336.38  4196.6  331.91  4238.4  330.83
  4331.2  330.61  4537.5  323.96  4942.1  319.17  4950.1  316.14  4964.5  314.83
  4970.9  319.67  4978.9  312.66  4985.3  312.54  4990.1  307.58  4992.8  307.08
  4996.1  307.58  4999.7  307.74  5014.1  313.45  5049.3  318.84  5512.4  320.51
  5592.5  324.41  5732.6  336.26  5862.7  342.83  6062.9  342.08  6349.9  344.34
#Mann= 4 ,-1 , 0
    3882     .16       0  3886.5     .05       0  4990.1     .03       0
  4996.1     .05       0
Bank Sta=4970.9,5049.3
XS Rating Curve= 0 ,0
Exp/Cntr=0.3,0.1