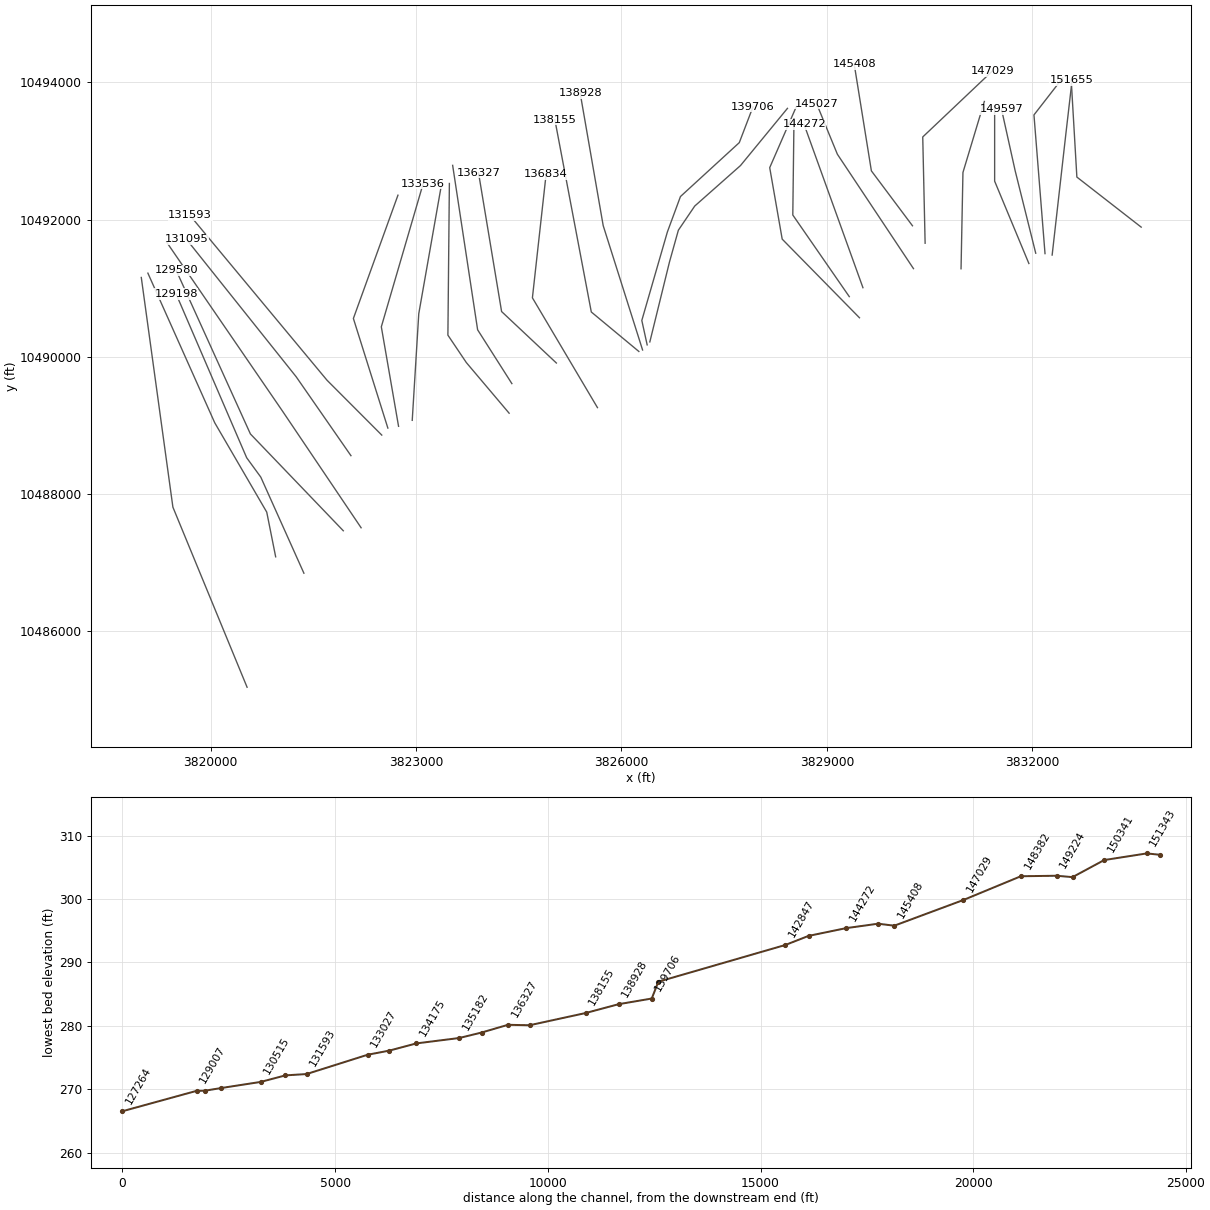
HEC-RAS study HURRICANE BAYOU.prj: HURRICANE BAYOU Base Level Engineering

--- HURRICANE BAYOU.g01 (geometry) --- (continued)

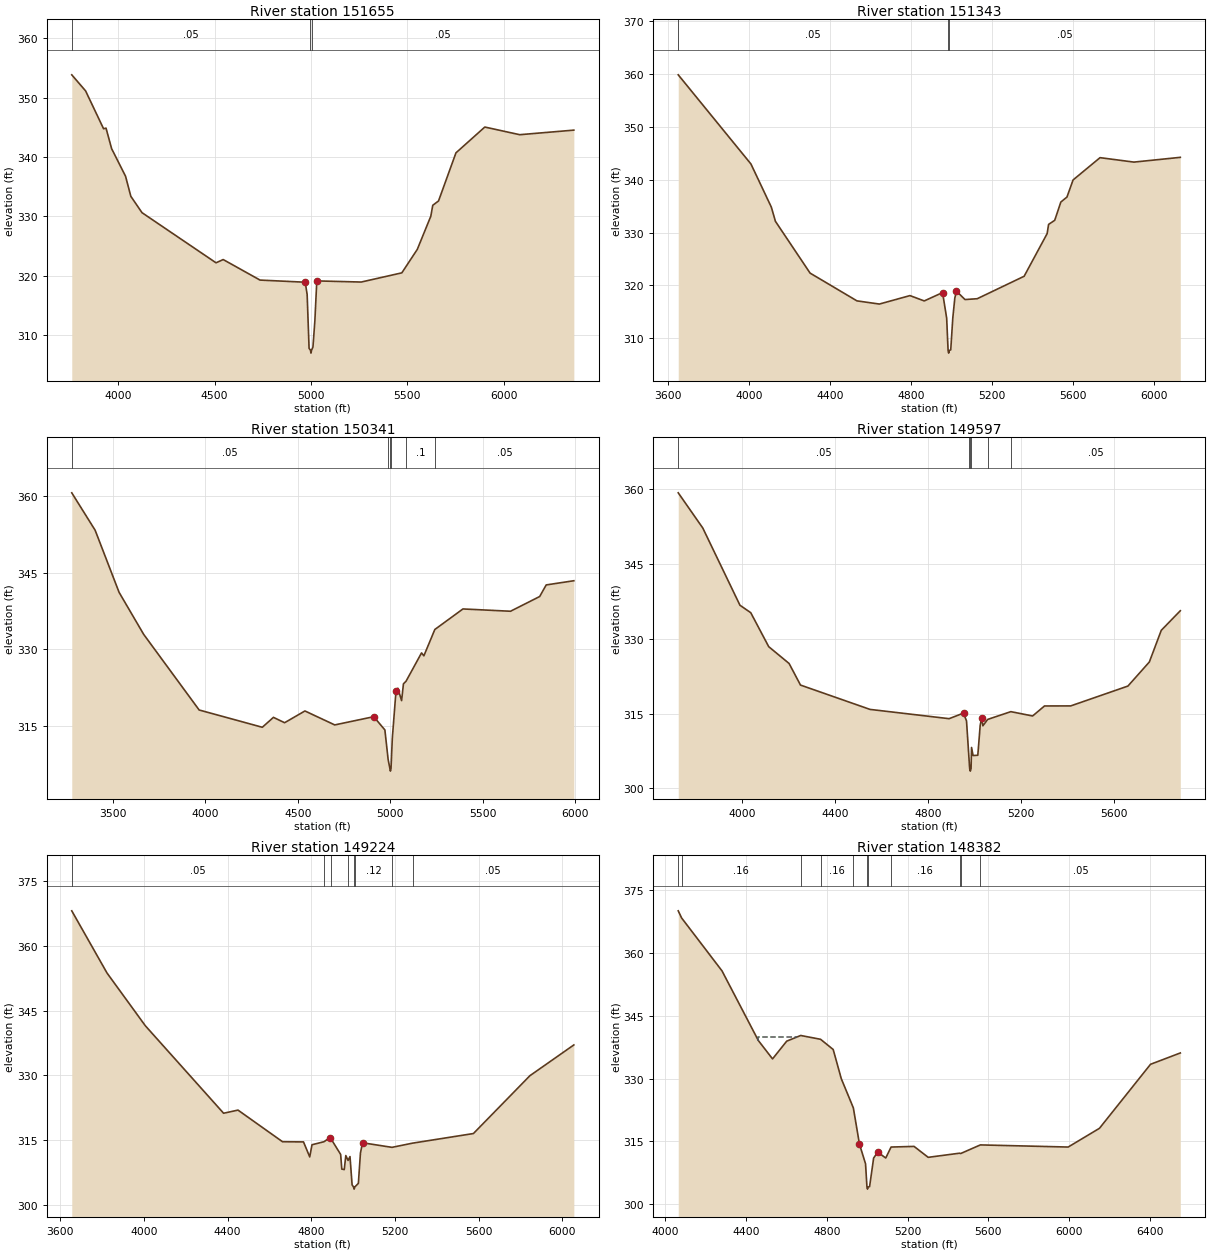
Type RM Length L Ch R = 1 ,151655  ,312,312,312
BEGIN DESCRIPTION:
Mapping XS 1616ccc8
END DESCRIPTION:
XS GIS Cut Line= 3
      3833589.85     10491890.08       3832650.4     10492619.67
      3832567.93     10494030.28
#Sta/Elev= 30
  3760.1  353.87  3831.8  351.16    3925  344.78  3937.7  344.89  3966.7  341.43
    4039  336.77  4066.2   333.4  4124.2  330.64  4507.9  322.19    4545  322.74
    4736  319.28  4970.1  318.92  4980.2  316.85  4990.2  307.77  4997.2  307.47
  4999.9  306.97  5003.2  307.47  5010.2  307.97  5020.2   312.4  5030.2  319.14
  5260.6  318.95    5471   320.5  5551.1  324.45  5621.2  330.04  5631.3  331.88
  5661.3  332.62  5751.5  340.72  5901.1  345.07    6082  343.78  6362.6  344.55
#Mann= 3 ,-1 , 0
  3760.1     .05       0  4997.2     .03       0  5003.2     .05       0
Bank Sta=4970.1,5030.2
XS Rating Curve= 0 ,0
Exp/Cntr=0.3,0.1

Type RM Length L Ch R = 1 ,151343  ,1002,1002,1002
BEGIN DESCRIPTION:
HURRICANE BAYOU 126.0
END DESCRIPTION:
XS GIS Cut Line= 3
      3832289.44     10491483.47      3832487.36     10493228.23
      3832570.58     10493946.07
#Sta/Elev= 30
  3649.5  359.87  4008.5  342.99  4109.1  334.83  4129.3  332.14  4300.4  322.34
  4531.8  317.08  4642.5  316.48  4793.5  318.08    4864  317.07  4954.5  318.65
  4974.7  313.81  4981.7  307.69  4984.5  307.19  4987.7  307.69  4994.8  307.81
  5004.9  313.83  5014.9  317.61  5023.1  318.92  5065.2  317.33  5125.6  317.49
  5357.1  321.74  5470.6  329.81  5477.9  331.56  5508.1  332.33  5538.3  335.79
  5568.5  336.73  5598.7  339.97  5731.8  344.19  5899.1  343.35  6128.1  344.25
#Mann= 3 ,-1 , 0
  3649.5     .05       0  4981.7     .03       0  4987.7     .05       0
Bank Sta=4954.5,5023.1
XS Rating Curve= 0 ,0
Exp/Cntr=0.3,0.1

Type RM Length L Ch R = 1 ,150341  ,744,744,744
BEGIN DESCRIPTION:
HURRICANE BAYOU 125.0
END DESCRIPTION:
XS GIS Cut Line= 3
      3832185.27     10491504.25      3832023.81     10493525.11
      3832444.54      10494065.3
#Sta/Elev= 30
  3279.6  360.59  3405.9  353.27  3535.2  341.12  3668.2  332.89  3967.7   318.1
  4308.8  314.72    4369  316.66  4429.2  315.61    4539  317.91  4700.1  315.18
  4910.7  316.79  4970.9   314.2  4988.5  308.41    4998  306.64  5000.8  306.14
    5004  306.64    5011  312.53  5031.1  321.89    5041  322.35  5061.2  319.93
  5071.2  323.22  5085.2  323.73  5168.9  329.27  5181.6   328.7  5240.7  333.85
  5392.6  337.87  5649.6  337.42    5807   340.3  5842.3  342.57  5991.6  343.39
#Mann= 6 ,-1 , 0
  3279.6     .05       0  4988.5     .16       0    4998     .07       0
    5004     .16       0  5085.2      .1       0  5240.7     .05       0
Bank Sta=4910.7,5031.1
XS Rating Curve= 0 ,0
Exp/Cntr=0.3,0.1

Type RM Length L Ch R = 1 ,149597  ,373,373,373
BEGIN DESCRIPTION:
HURRICANE BAYOU 124.0
END DESCRIPTION:
XS GIS Cut Line= 3
       3832049.6     10491510.23      3831749.61     10492710.19
      3831549.62     10493610.15
#Sta/Elev= 30
  3727.1  359.27  3832.7  352.21  3992.5  336.72  4038.9  335.23  4116.2  328.41
  4203.8  325.04  4252.8  320.71  4551.7  315.83  4891.8  313.97  4953.7  315.09
  4966.6  313.53  4978.1  305.42  4980.2  303.95  4982.9  303.45  4986.2  303.95
  4988.3   308.2  4994.7  306.58  5015.2  306.63  5025.5  312.67  5031.9  314.11
    5037  312.54  5057.6  313.82  5157.3  315.38  5250.8  314.51    5302  316.52
  5414.7  316.53  5660.6  320.51  5752.8  325.34    5804  331.69  5885.9  335.62
#Mann= 6 ,-1 , 0
  3727.1     .05       0  4978.1     .16       0  4980.2     .07       0
  4986.2     .16       0  5057.6     .12       0  5157.3     .05       0
Bank Sta=4953.7,5031.9
XS Rating Curve= 0 ,0
Exp/Cntr=0.3,0.1

Type RM Length L Ch R = 1 ,149224  ,842,842,842
BEGIN DESCRIPTION:
HURRICANE BAYOU 123.0
END DESCRIPTION:
XS GIS Cut Line= 3
       3831949.6     10491360.22      3831449.61     10492560.19
      3831449.61     10493660.22
#Sta/Elev= 30
  3654.9  368.15  3823.3  353.75  4006.4  341.53  4380.7  321.25  4449.5  321.98
  4662.4  314.65  4762.6  314.61  4792.4  311.13  4803.2  313.95    4861  314.66
  4887.2  315.57  4892.9  315.42  4940.2  311.71  4945.7  308.31  4957.4   308.2
  4964.9  311.45  4975.7  310.32  4984.9  311.21  4994.9  304.67  5001.9  304.17
  5004.6  303.67  5007.9  304.17  5024.9  305.01  5034.9  312.07  5044.9  314.41
  5185.6  313.35  5283.7  314.32  5574.9  316.55  5844.9  329.95  6054.9  337.08
#Mann= 8 ,-1 , 0
  3654.9     .05       0    4861     .12       0  4892.9     .16       0
  4975.7     .12       0  5001.9     .07       0  5007.9     .12       0
  5185.6     .16       0  5283.7     .05       0
Bank Sta=4887.2,5044.9
XS Rating Curve= 0 ,0
Exp/Cntr=0.3,0.1

Type RM Length L Ch R = 1 ,148382  ,1353,1353,1353
BEGIN DESCRIPTION:
HURRICANE BAYOU 122.0
END DESCRIPTION:
XS GIS Cut Line= 3
      3830959.01     10491283.72      3830986.79     10492686.52
       3831299.3     10493721.28
#Sta/Elev= 30
  4065.5  370.12  4082.2  368.42    4282  355.77    4462   339.1  4532.1  334.72
  4602.1  338.96  4671.5  340.32  4769.7  339.41  4832.1  336.97  4872.1  330.01
  4931.9  323.01  4962.1  314.36  4992.2  309.64  4999.2  304.09  5001.9  303.59
  5005.2  304.09  5012.2  304.19  5032.2  311.01  5052.2  312.44  5092.2  311.03
  5118.5  313.65  5232.2   313.8  5302.2  311.19  5457.2  312.18  5462.9   312.1
  5560.3  314.16  5994.7  313.65  6149.5  318.13  6402.1  333.43  6549.5  336.14
#Mann= 11 ,-1 , 0
  4065.5     .05       0  4082.2     .16       0  4671.5      .1       0
  4769.7     .16       0  4931.9     .12       0  4999.2     .07       0
  5005.2     .12       0  5118.5     .16       0  5457.2     .05       0
  5462.9     .16       0  5560.3     .05       0
#XS Ineff= 1 ,-1
    4462  4652.1     340
Permanent Ineff=
       F
Bank Sta=4962.1,5052.2
XS Rating Curve= 0 ,0
Exp/Cntr=0.3,0.1

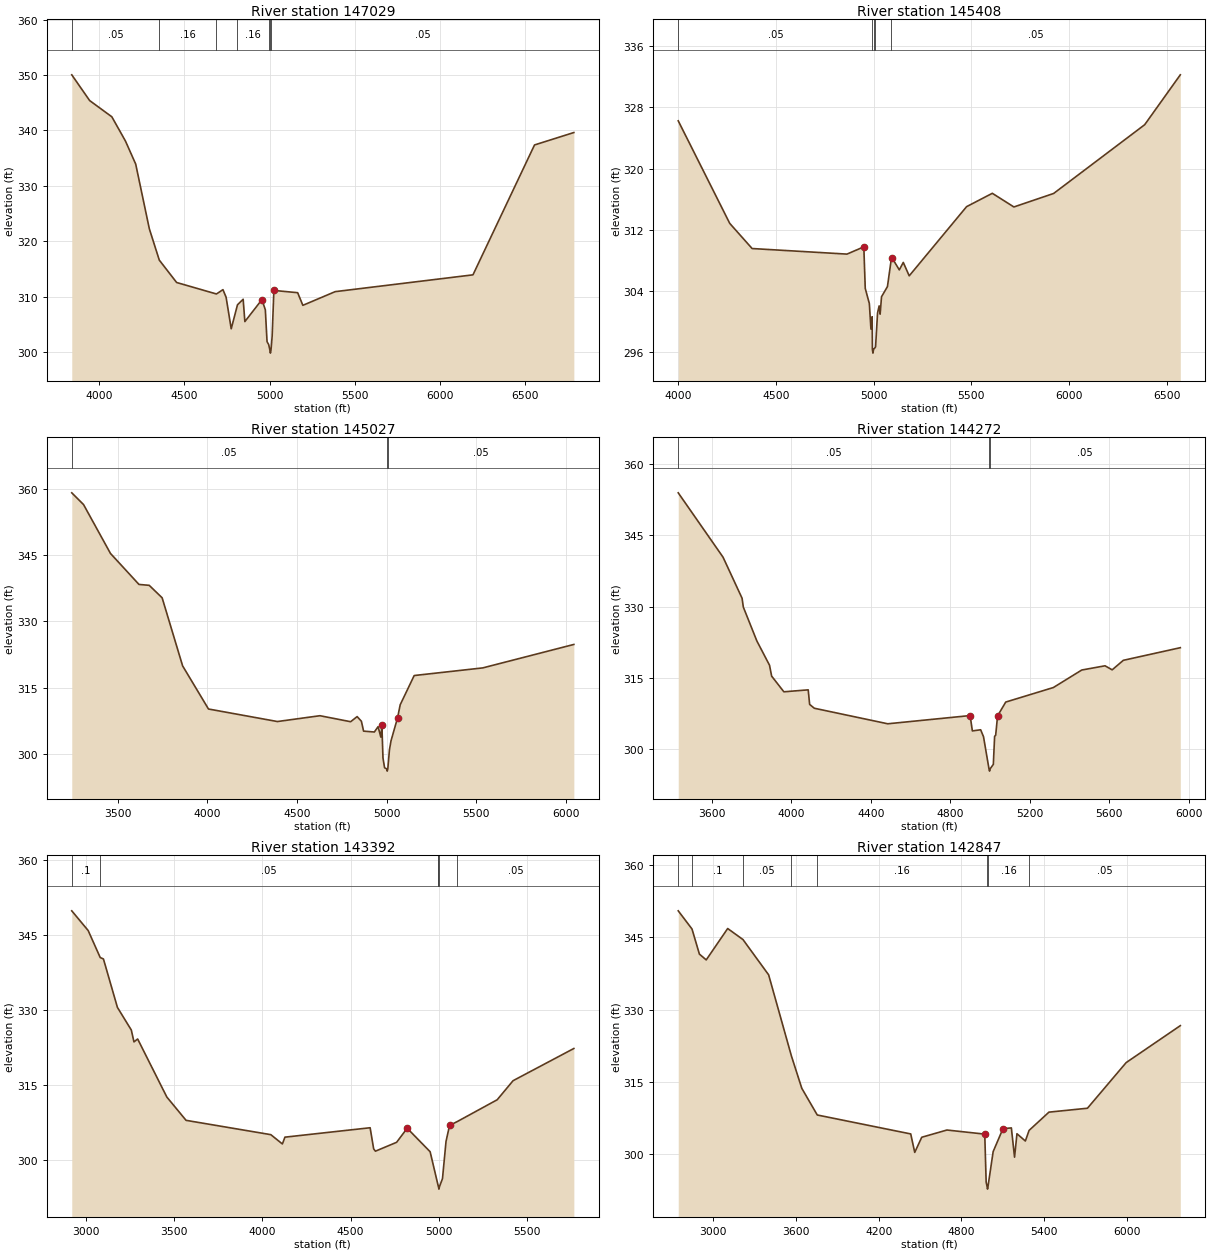
Type RM Length L Ch R = 1 ,147029  ,1621,1621,1621
BEGIN DESCRIPTION:
HURRICANE BAYOU 121.0
END DESCRIPTION:
XS GIS Cut Line= 3
       3830434.4      10491655.4      3830399.68     10493204.02
      3831413.55     10494162.33
#Sta/Elev= 30
  3839.6  350.04  3944.4   345.4  4074.5  342.47  4154.5  338.09  4214.5  333.94
  4294.5  322.26  4352.8  316.62  4454.5  312.58  4687.9  310.51  4726.2  311.29
  4744.6  309.92  4774.6  304.23  4811.4  308.56  4844.6  309.56  4854.6  305.53
  4954.7  309.49  4974.7  307.64  4984.7  301.91  4994.3  301.38  5001.7  300.34
  5004.4  299.84  5007.7  300.34  5014.7  302.95  5024.7  311.15  5164.3  310.74
  5194.7  308.46  5384.2  310.93  6192.2  313.96  6553.1  337.39  6783.7  339.63
#Mann= 7 ,-1 , 0
  3839.6     .05       0  4352.8     .16       0  4687.9     .12       0
  4811.4     .16       0  4994.3     .05       0  5001.7     .03       0
  5007.7     .05       0
Bank Sta=4954.7,5024.7
XS Rating Curve= 0 ,0
Exp/Cntr=0.3,0.1

Type RM Length L Ch R = 1 ,145408  ,381,381,381
BEGIN DESCRIPTION:
HURRICANE BAYOU 120.0
END DESCRIPTION:
XS GIS Cut Line= 3
      3830249.63     10491910.16      3829649.61     10492710.19
       3829399.6     10494260.22
#Sta/Elev= 30
  4000.2  326.25  4263.8  312.81  4378.4  309.51  4863.8  308.78  4950.2  309.73
  4957.5  304.28  4978.4  302.31  4986.7  298.95  4992.9  300.57  4994.1   296.3
  4996.9   295.8  5000.1   296.3  5006.9  296.48  5010.4  296.64  5020.5  301.06
  5028.6  301.99  5033.7  300.91  5040.8  303.19  5071.1  304.52  5090.3  308.02
  5095.5  308.25  5131.9  306.71  5152.2  307.69  5182.6  305.93  5476.3     315
    5608  316.75  5718.4  314.96    5922  316.73  6387.9  325.74  6570.3  332.28
#Mann= 5 ,-1 , 0
  4000.2     .05       0  4994.1     .03       0  5000.1     .05       0
  5006.9     .16       0  5090.3     .05       0
Bank Sta=4950.2,5095.5
XS Rating Curve= 0 ,0
Exp/Cntr=0.3,0.1

Type RM Length L Ch R = 1 ,145027  ,755,755,755
BEGIN DESCRIPTION:
HURRICANE BAYOU 119.0
END DESCRIPTION:
XS GIS Cut Line= 3
      3830264.29     10491285.58      3829153.15     10492952.28
      3828849.32     10493690.15
#Sta/Elev= 30
  3243.7  359.14  3309.3  356.49  3459.5  345.42  3618.7  338.39  3675.8  338.19
  3747.9  335.36  3862.2  319.94  4006.4  310.18  4390.9  307.34  4628.3  308.66
  4799.6   307.3  4835.7  308.46  4859.7   307.4  4871.7  305.17  4931.8  304.97
  4952.8  306.18  4967.8  303.83  4973.8  306.53  4979.9  299.11  4988.9  296.87
  5000.9  296.61  5003.6  296.11  5006.9  296.61    5016  300.93  5024.9  302.99
    5061  308.13    5076  311.13  5154.1  317.76  5536.9  319.49  6044.8   324.8
#Mann= 3 ,-1 , 0
  3243.7     .05       0  5000.9     .03       0  5006.9     .05       0
Bank Sta=4973.8,5061
XS Rating Curve= 0 ,0
Exp/Cntr=0.3,0.1

Type RM Length L Ch R = 1 ,144272  ,880,880,880
BEGIN DESCRIPTION:
HURRICANE BAYOU 118.0
END DESCRIPTION:
XS GIS Cut Line= 2
      3829526.42     10491007.82      3828667.24     10493385.76
#Sta/Elev= 30
  3430.2  353.96    3656  340.41  3751.7  331.78  3758.1  329.91  3826.1   322.8
  3889.9  317.69  3900.6   315.4  3962.1   312.1  4084.8  312.51  4091.9  309.45
  4115.5  308.64  4485.4  305.37    4900   307.1  4911.5  303.87  4953.2  304.11
  4967.5  302.66  4995.1  295.91  4997.9  295.41  5001.1  295.91    5017  296.83
  5023.5  302.74  5028.8  302.95  5038.3  307.03  5079.5  309.94  5319.5     313
  5462.2  316.68  5579.5  317.57  5615.5  316.72  5671.5  318.72  5958.6  321.38
#Mann= 3 ,-1 , 0
  3430.2     .05       0  4995.1     .03       0  5001.1     .05       0
Bank Sta=4900,5038.3
XS Rating Curve= 0 ,0
Exp/Cntr=0.3,0.1

Type RM Length L Ch R = 1 ,143392  ,545,545,545
BEGIN DESCRIPTION:
HURRICANE BAYOU 117.0
END DESCRIPTION:
XS GIS Cut Line= 3
      3829326.78      10490877.6      3828502.11     10492066.86
      3828519.47     10493464.44
#Sta/Elev= 30
  2920.4  349.78  3013.4  345.84  3081.6  340.45  3099.9  340.16  3179.1  330.49
  3257.9  325.96  3272.8   323.6  3293.7  324.18    3459  312.59    3568  307.93
  4048.3  305.07  4113.8  303.21  4128.3  304.57    4611  306.45    4631  302.23
    4641  301.77    4761  303.54    4821  306.35    4951  301.66  4997.1  294.78
    4998  294.69  5000.7  294.19    5004  294.69    5021  296.29    5041  303.71
    5061  306.91    5106  307.71    5331  312.04    5421  315.85  5765.3  322.28
#Mann= 6 ,-1 , 0
  2920.4      .1       0  3081.6     .05       0  4997.1     .16       0
    4998     .07       0    5004     .16       0    5106     .05       0
Bank Sta=4821,5061
XS Rating Curve= 0 ,0
Exp/Cntr=0.3,0.1

Type RM Length L Ch R = 1 ,142847  ,2985,2985,2985
BEGIN DESCRIPTION:
HURRICANE BAYOU 116.0
END DESCRIPTION:
XS GIS Cut Line= 4
      3829475.79     10490569.46      3828347.31      10491715.3
      3828165.02     10492756.97      3828555.11     10493649.84
#Sta/Elev= 30
  2746.8  350.49  2846.6  346.72  2900.2  341.52  2949.7  340.31  3105.3  346.82
  3216.2  344.53  3402.3  337.21  3567.4  320.38  3642.7  313.67  3754.7  308.14
  4432.4  304.21  4461.5  300.38  4512.3  303.52    4695  305.02  4969.1  304.17
  4979.3  294.21  4986.4  293.26  4989.2  292.76  4992.4  293.26    5030  300.54
  5101.1   305.3    5162  305.46  5185.1  299.39  5202.6  304.25  5263.5  302.74
  5290.5  304.94  5434.5  308.73  5713.7  309.54  5994.4  319.01  6386.9  326.67
#Mann= 8 ,-1 , 0
  2746.8     .05       0  2846.6      .1       0  3216.2     .05       0
  3567.4      .1       0  3754.7     .16       0  4986.4     .07       0
  4992.4     .16       0  5290.5     .05       0
#XS Ineff= 1 ,-1
  2850.7  3098.2  346.13
Permanent Ineff=
       F
Bank Sta=4969.1,5101.1
XS Rating Curve= 0 ,0
Exp/Cntr=0.3,0.1

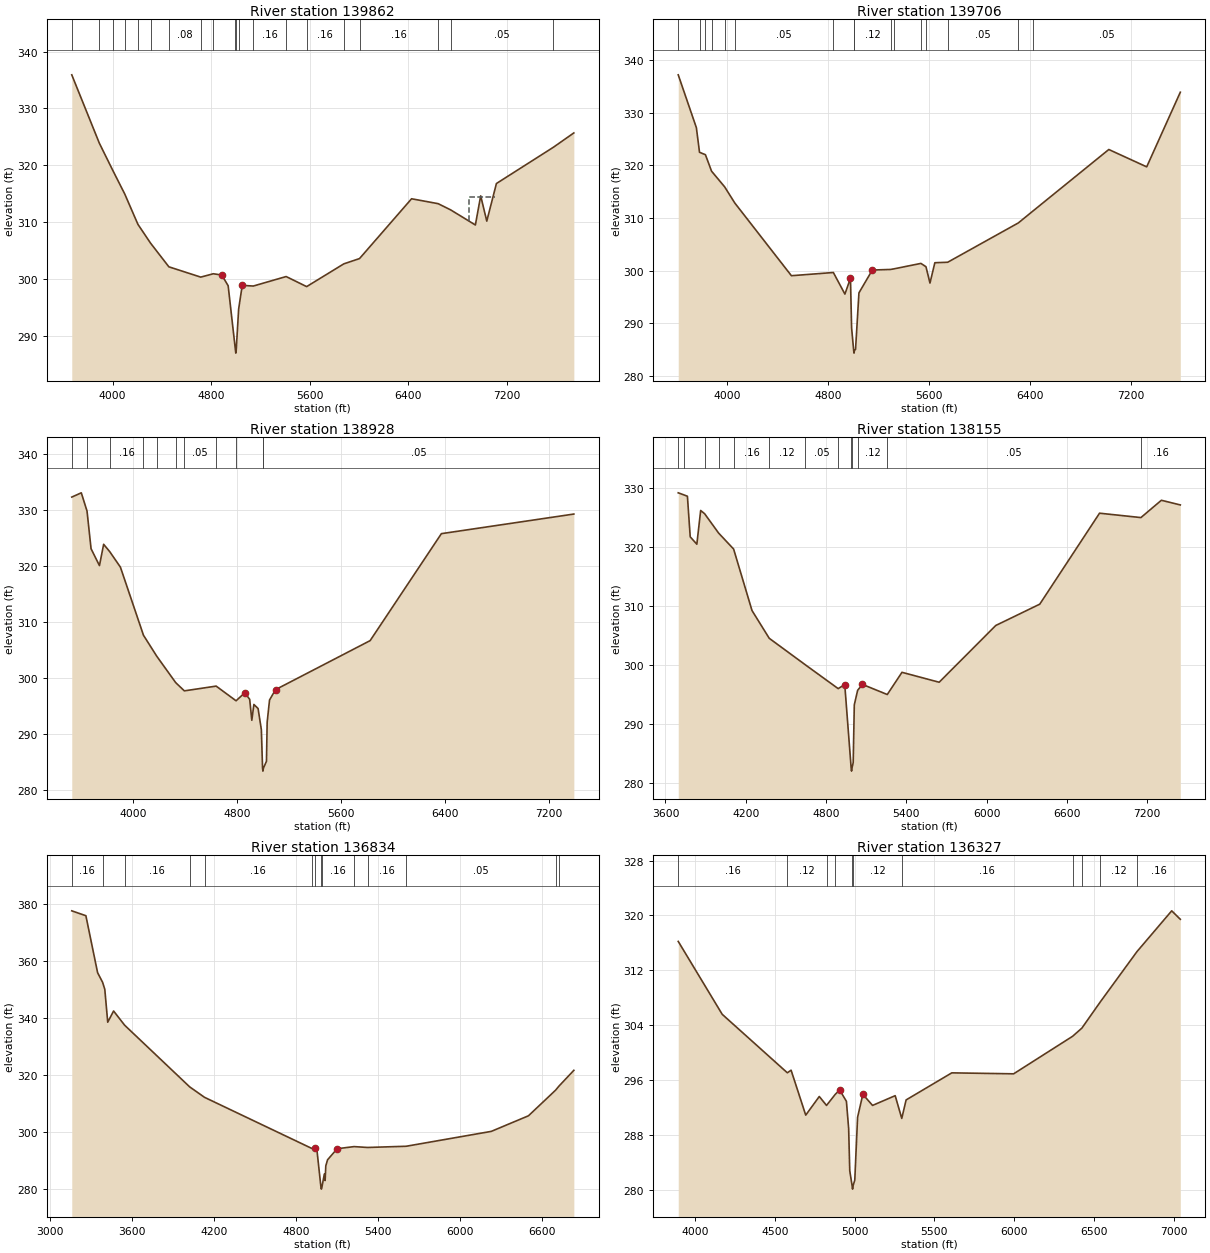
Type RM Length L Ch R = 1 ,139862  ,156,156,156
BEGIN DESCRIPTION:
HURRICANE BAYOU 113.0
END DESCRIPTION:
XS GIS Cut Line= 6
      3826414.43     10490217.88       3826700.9      10491381.1
      3826831.11     10491845.51      3827069.82     10492197.07
      3827738.22     10492787.35      3828423.99     10493620.69
#Sta/Elev= 30
  3668.3  335.92  3892.1   323.9  4001.4  319.11  4098.6  314.95  4205.5  309.62
  4307.5  306.33  4456.7  302.15  4715.5  300.34  4817.6  300.93  4886.1  300.71
    4938  298.82  4997.3  287.47  5000.1  286.97  5003.3  287.47  5023.1  294.72
  5052.3  298.89  5142.3  298.77  5408.6  300.44  5575.2  298.67  5876.9  302.67
  6004.5   303.6    6427  314.12  6642.4  313.26  6743.2  312.18  6945.1  309.51
  6988.2  314.63  7037.7  310.19  7115.9   316.8  7579.2  323.19  7744.5   325.7
#Mann= 20 ,-1 , 0
  3668.3     .16       0  3892.1     .05       0  4001.4     .08       0
  4098.6     .05       0  4205.5     .08       0  4307.5     .05       0
  4456.7     .08       0  4715.5     .05       0  4817.6     .12       0
  4997.3     .07       0  5003.3     .08       0  5023.1     .05       0
  5142.3     .16       0  5408.6     .16       0  5575.2     .16       0
  5876.9     .16       0  6004.5     .16       0  6642.4     .16       0
  6743.2     .05       0  7579.2     .05       0
#XS Ineff= 1 ,-1
  6895.6  7101.5  314.42
Permanent Ineff=
       F
Bank Sta=4886.1,5052.3
XS Rating Curve= 0 ,0
Exp/Cntr=0.3,0.1

Type RM Length L Ch R = 1 ,139706  ,778,778,778
BEGIN DESCRIPTION:
HURRICANE BAYOU 112.0
END DESCRIPTION:
XS GIS Cut Line= 6
      3826375.39     10490174.46      3826297.25      10490530.4
      3826670.52     10491819.47      3826861.49     10492335.96
      3827720.86     10493121.55       3827920.5     10493642.36
#Sta/Elev= 30
  3612.7  337.24  3756.5  327.19  3781.4  322.51  3828.3  322.05  3876.7  318.92
  3980.8  315.93  4060.9  312.87  4509.7  299.04  4842.1  299.65  4933.6  295.55
  4977.7  298.54  4986.8  289.12  5003.1  284.82  5005.8  284.32  5009.1  284.82
    5018  285.04  5044.9  295.78    5151  300.12  5295.4  300.23  5323.7  300.35
  5535.9  301.38  5576.2  300.75  5607.8  297.64  5646.6  301.51  5748.2   301.6
  6308.3  309.08  6422.9  311.32  7025.2  323.04  7325.6  319.74  7591.9  333.93
#Mann= 16 ,-1 , 0
  3612.7     .16       0  3781.4     .08       0  3828.3     .05       0
  3876.7     .16       0  3980.8     .12       0  4060.9     .05       0
  4842.1     .12       0  5003.1     .07       0  5009.1     .12       0
  5295.4     .05       0  5323.7     .08       0  5535.9     .05       0
  5576.2     .08       0  5748.2     .05       0  6308.3     .08       0
  6422.9     .05       0
Bank Sta=4977.7,5151
XS Rating Curve= 0 ,0
Exp/Cntr=0.3,0.1

Type RM Length L Ch R = 1 ,138928  ,773,773,773
BEGIN DESCRIPTION:
HURRICANE BAYOU 111.0
END DESCRIPTION:
XS GIS Cut Line= 3
      3826308.38     10490100.31       3825733.3     10491912.35
      3825396.93     10493843.77
#Sta/Elev= 30
  3528.7  332.36    3602  333.12  3646.1  329.86  3677.1  323.14  3741.6  320.13
  3773.9  323.93  3820.6  322.62  3902.9  319.85  4080.3  307.69    4182  303.96
  4328.1  299.23  4394.6  297.76  4639.3  298.61  4792.3  295.99  4859.6  297.42
  4897.1  296.25  4913.5  292.51  4929.4  295.33  4961.7  294.61  4986.9  290.83
  4996.2  283.93  4998.9  283.43  5002.2  283.93  5026.2  285.19  5031.5  292.14
  5049.8  296.13    5096  297.98  5823.5  306.73  6371.6  325.83  7390.3  329.33
#Mann= 11 ,-1 , 0
  3528.7     .16       0  3646.1     .05       0  3820.6     .16       0
  4080.3     .12       0    4182     .05       0  4328.1     .16       0
  4394.6     .05       0  4639.3     .16       0  4792.3     .05       0
  4996.2     .03       0  5002.2     .05       0
Bank Sta=4859.6,5096
XS Rating Curve= 0 ,0
Exp/Cntr=0.3,0.1

Type RM Length L Ch R = 1 ,138155  ,1321,1321,1321
BEGIN DESCRIPTION:
HURRICANE BAYOU 109.0
END DESCRIPTION:
XS GIS Cut Line= 3
       3826254.1     10490078.61      3825559.69     10490653.67
      3825028.01     10493453.12
#Sta/Elev= 30
  3695.5  329.16  3735.5  328.83  3764.1  328.58    3785  321.71  3834.5  320.46
  3863.1  326.17  3892.8  325.62    3997  322.35  4109.3  319.64  4246.7  309.23
  4375.4  304.53  4645.9  300.03  4890.4  296.01  4939.6  296.69  4987.5  282.54
  4990.3  282.04  4993.5  282.54  5002.7  283.49  5010.9  293.26  5035.9  295.73
    5072  296.72  5257.3  295.01  5367.1  298.77  5644.9  297.09  6067.9   306.7
  6396.6  310.31  6843.1  325.71  7152.3  324.97  7305.1   327.9  7446.6  327.11
#Mann= 13 ,-1 , 0
  3695.5     .16       0  3735.5     .05       0  3892.8     .16       0
    3997     .12       0  4109.3     .16       0  4375.4     .12       0
  4645.9     .05       0  4890.4     .16       0  4987.5     .07       0
  4993.5     .16       0  5035.9     .12       0  5257.3     .05       0
  7152.3     .16       0
#XS Ineff= 1 ,-1
  3770.6  3863.1  326.17
Permanent Ineff=
       F
Bank Sta=4939.6,5072
XS Rating Curve= 0 ,0
Exp/Cntr=0.3,0.1

Type RM Length L Ch R = 1 ,136834  ,507,507,507
BEGIN DESCRIPTION:
HURRICANE BAYOU 108.0
END DESCRIPTION:
XS GIS Cut Line= 3
      3825649.59     10489260.23      3824699.61     10490860.19
      3824899.61     10492660.18
#Sta/Elev= 30
  3158.9   377.5  3262.1  375.79  3347.8  355.86  3384.4  352.49  3400.5  350.02
  3421.9  338.52  3464.7  342.45  3545.5  337.48  4021.3  315.89  4129.6  312.24
    4914  294.36  4936.4  294.39  4938.2  294.36  4953.4  293.13  4981.6  280.61
  4984.3  280.11  4987.6  280.61    5006   285.4  5011.8  283.11  5016.7  288.26
  5029.7  290.39  5100.1  294.25  5223.2  294.99  5322.3  294.69  5604.3  295.11
    6227  300.32  6498.7  305.77  6697.6  314.76  6720.8   316.1  6830.7  321.69
#Mann= 14 ,-1 , 0
  3158.9     .16       0  3384.4     .05       0  3545.5     .16       0
  4021.3     .12       0  4129.6     .16       0    4914     .12       0
  4936.4     .16       0  4981.6     .07       0  4987.6     .16       0
  5223.2     .12       0  5322.3     .16       0  5604.3     .05       0
  6697.6     .16       0  6720.8     .05       0
Bank Sta=4938.2,5100.1
XS Rating Curve= 0 ,0
Exp/Cntr=0.3,0.1

Type RM Length L Ch R = 1 ,136327  ,622,622,622
BEGIN DESCRIPTION:
HURRICANE BAYOU 107.0
END DESCRIPTION:
XS GIS Cut Line= 3
      3825049.58     10489910.21      3824249.61     10490660.19
      3823912.42     10492683.33
#Sta/Elev= 30
  3894.3  316.23    4170  305.62  4578.3  297.11  4601.8  297.49  4693.6  290.95
  4778.6  293.66  4823.9  292.36    4879  293.98  4906.1  294.61  4948.6  292.96
  4962.7  288.99  4969.6  282.85  4984.4  280.68  4987.2  280.18  4990.4  280.68
    5001  281.47  5018.7  290.64  5051.7  293.97  5112.5  292.36  5254.4  293.78
  5295.6  290.47  5322.9  293.16  5609.3   297.1    5997  296.96  6366.5  302.42
  6424.4   303.6  6541.4  307.46  6769.7  314.73    6988  320.68  7041.9  319.45
#Mann= 11 ,-1 , 0
  3894.3     .16       0  4578.3     .12       0  4823.9     .16       0
    4879     .12       0  4984.4     .07       0  4990.4     .12       0
  5295.6     .16       0  6366.5     .12       0  6424.4     .16       0
  6541.4     .12       0  6769.7     .16       0
Bank Sta=4906.1,5051.7
XS Rating Curve= 0 ,0
Exp/Cntr=0.3,0.1

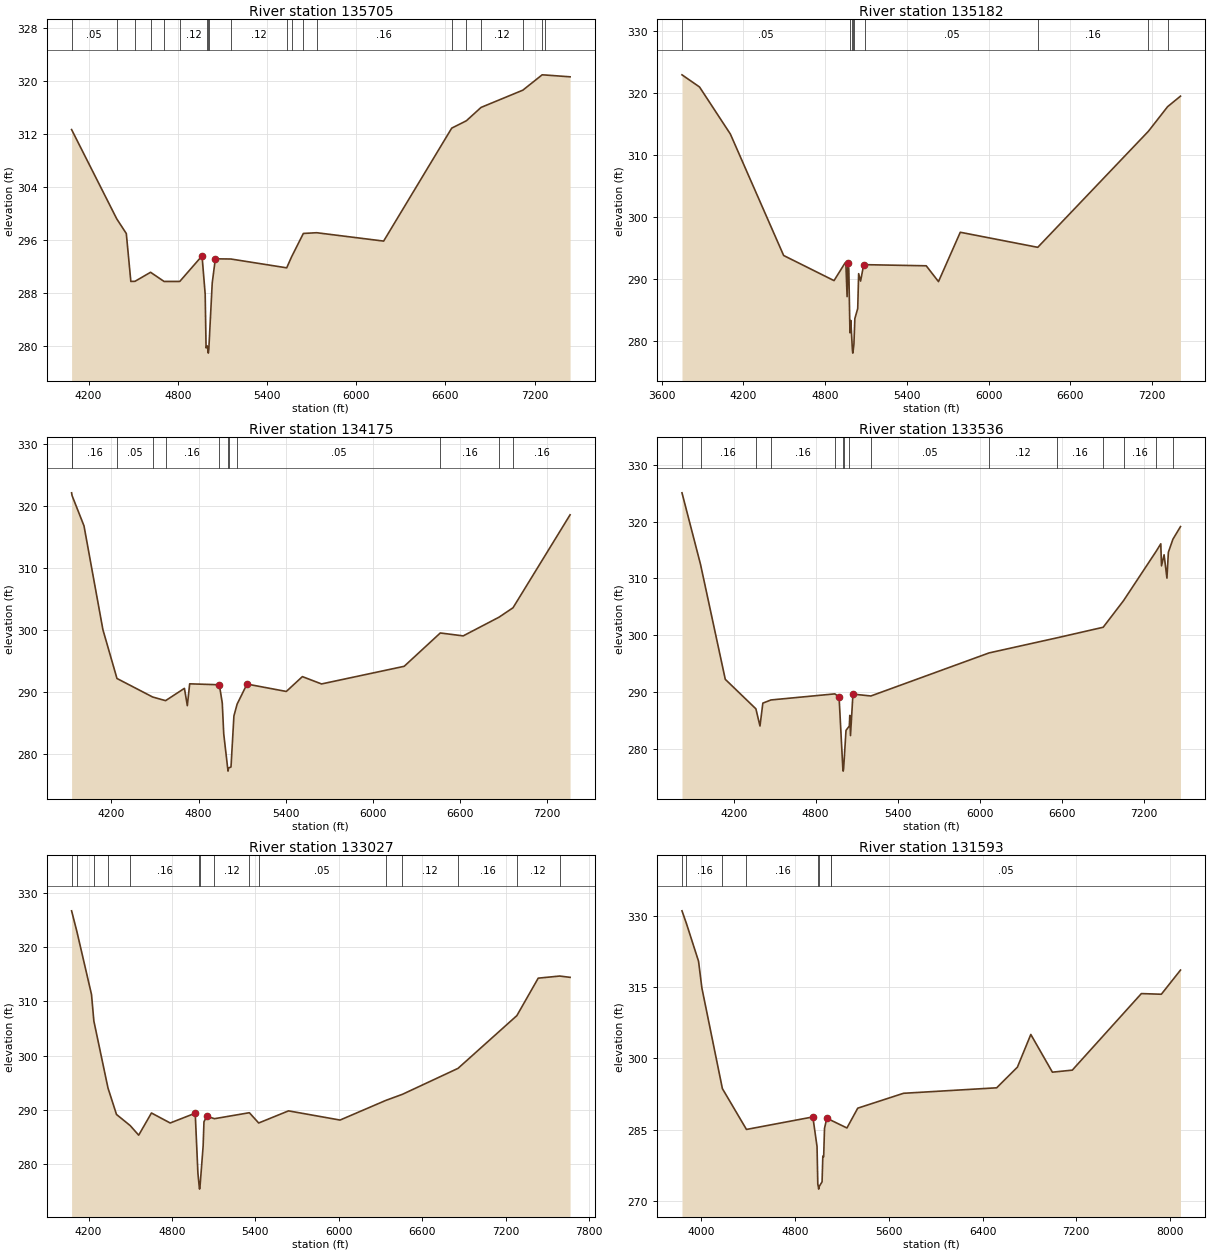
Type RM Length L Ch R = 1 ,135705  ,523,523,523
BEGIN DESCRIPTION:
HURRICANE BAYOU 106.0
END DESCRIPTION:
XS GIS Cut Line= 3
      3824399.61     10489610.19      3823899.54     10490394.38
      3823534.95     10492790.23
#Sta/Elev= 30
  4085.7  312.64  4389.7  299.18  4453.8  296.98  4484.3  289.76  4512.3  289.78
  4616.9  291.14  4707.8  289.76  4813.4  289.76  4963.3  293.61  4984.4  287.84
  4990.4  279.75  4998.3  280.05  5002.6  279.46  5005.3  278.96  5008.6  279.46
  5031.8  289.53  5052.8  293.17  5157.2  293.14  5532.8  291.81  5565.2  293.45
  5644.8  296.99  5734.1   297.1  6184.9  295.84  6642.9  312.86  6741.6  313.97
  6840.3  315.98  7121.5  318.58  7251.3  320.89  7273.7  320.86  7439.2  320.59
#Mann= 20 ,-1 , 0
  4085.7     .05       0  4389.7     .16       0  4512.3     .05       0
  4616.9     .12       0  4707.8     .05       0  4813.4     .12       0
  4998.3     .16       0  5002.6     .07       0  5008.6     .16       0
  5157.2     .12       0  5532.8     .05       0  5565.2     .16       0
  5644.8     .05       0  5734.1     .16       0  6642.9     .12       0
  6741.6     .16       0  6840.3     .12       0  7121.5     .16       0
  7251.3     .12       0  7273.7     .16       0
Bank Sta=4963.3,5052.8
XS Rating Curve= 0 ,0
Exp/Cntr=0.3,0.1

Type RM Length L Ch R = 1 ,135182  ,1007,1007,1007
BEGIN DESCRIPTION:
HURRICANE BAYOU 105.0
END DESCRIPTION:
XS GIS Cut Line= 4
      3824359.58     10489179.13      3823734.61     10489916.95
      3823465.51     10490316.26      3823487.06     10492526.09
#Sta/Elev= 30
  3749.2     323  3877.9  321.04  4104.4  313.44  4495.3  293.85    4865   289.8
  4945.9  292.65    4952  292.54  4960.9  287.21    4967  292.67  4973.3   291.7
  4980.4  283.18  4981.9  281.38    4988  283.37  4999.9   278.6  5002.7   278.1
  5005.9   278.6  5010.9  279.51  5017.9  283.69  5038.9   285.3  5045.6  290.92
  5059.9  289.72  5081.8  292.27  5095.8  292.37  5541.6  292.19  5631.6  289.64
  5791.6   297.6  6360.1  295.17  7172.4   313.9  7312.9  317.86  7407.6  319.56
#Mann= 9 ,-1 , 0
  3749.2     .05       0  4980.4     .12       0  4999.9     .07       0
  5005.9     .12       0  5010.9     .16       0  5095.8     .05       0
  6360.1     .16       0  7172.4     .12       0  7312.9     .16       0
Bank Sta=4967,5081.8
XS Rating Curve= 0 ,0
Exp/Cntr=0.3,0.1

Type RM Length L Ch R = 1 ,134175  ,639,639,639
BEGIN DESCRIPTION:
HURRICANE BAYOU 104.0
END DESCRIPTION:
XS GIS Cut Line= 3
      3822944.68     10489074.94      3823040.16     10490628.76
      3823365.53     10492474.96
#Sta/Elev= 30
  3926.2  322.07  3929.7  321.61  4011.6  316.75  4141.9  300.02  4238.6  292.17
    4484  289.19  4573.1   288.6  4702.9  290.58  4722.9  287.79  4739.1  291.31
  4940.1  291.16  4943.4  291.14  4963.4  288.22  4973.4  283.27  5000.5  277.75
  5003.2  277.25  5006.5  277.75  5023.5  277.92  5043.6  286.14  5065.8  288.05
  5133.7  291.27  5404.2  290.08  5514.9  292.47  5646.9  291.29  6215.5  294.13
  6464.3   299.5  6621.7  299.03  6868.3  302.04  6964.8  303.56  7357.6  318.53
#Mann= 12 ,-1 , 0
  3926.2     .05       0  3929.7     .16       0  4238.6     .05       0
    4484     .12       0  4573.1     .16       0  4940.1     .12       0
  5000.5     .07       0  5006.5     .12       0  5065.8     .05       0
  6464.3     .16       0  6868.3     .12       0  6964.8     .16       0
Bank Sta=4943.4,5133.7
XS Rating Curve= 0 ,0
Exp/Cntr=0.3,0.1

Type RM Length L Ch R = 1 ,133536  ,509,509,509
BEGIN DESCRIPTION:
HURRICANE BAYOU 103.0
END DESCRIPTION:
XS GIS Cut Line= 3
      3822745.03     10488988.12      3822493.29     10490437.78
      3823104.59     10492525.26
#Sta/Elev= 30
  3822.3  325.07    3958  312.47    4139  292.26  4362.9  287.07  4392.8  284.05
  4413.7  288.07    4473  288.63    4940   289.7  4971.3   289.2  4998.8  276.61
  5001.5  276.11  5004.8  276.61  5022.1  283.28  5046.3  284.05  5049.8  285.92
  5054.9  282.36  5072.8  289.66  5204.1  289.33  6069.2  296.91  6567.3  299.57
  6903.3  301.42  7052.2   306.1  7291.2   314.8  7324.7   316.1  7329.9  312.22
  7348.9  314.17  7369.7  310.06  7380.2  314.62  7413.4  316.91  7468.8  319.13
#Mann= 15 ,-1 , 0
  3822.3     .05       0    3958     .16       0  4362.9     .12       0
    4473     .16       0    4940     .12       0  4998.8     .07       0
  5004.8     .12       0  5046.3      .1       0  5204.1     .05       0
  6069.2     .12       0  6567.3     .16       0  6903.3     .12       0
  7052.2     .16       0  7291.2     .12       0  7413.4     .16       0
Bank Sta=4971.3,5072.8
XS Rating Curve= 0 ,0
Exp/Cntr=0.3,0.1

Type RM Length L Ch R = 1 ,133027  ,1434,1434,1434
BEGIN DESCRIPTION:
HURRICANE BAYOU 102.0
END DESCRIPTION:
XS GIS Cut Line= 3
      3822588.77     10488962.09       3822085.3     10490559.31
      3822736.15     10492355.64
#Sta/Elev= 30
  4077.8  326.67  4116.1  322.84    4221  311.28    4238  306.39  4339.7  294.06
  4400.8   289.2    4499  287.16  4560.4  285.39  4652.2  289.47  4786.9  287.63
    4967  289.43  4986.3  278.41  4995.5  275.96  4998.2  275.46  5001.5  275.96
  5023.9  283.39  5029.9  287.86  5050.9  288.88  5105.2  288.42  5356.3  289.52
  5423.5  287.63  5638.1  289.86  6008.7  288.17  6338.1  291.79  6457.6  292.91
    6857  297.68  7280.4  307.39  7433.9  314.28  7588.4  314.67  7663.1  314.43
#Mann= 15 ,-1 , 0
  4077.8     .16       0  4116.1     .05       0    4238     .16       0
  4339.7     .05       0    4499     .16       0  4995.5     .07       0
  5001.5     .16       0  5105.2     .12       0  5356.3      .1       0
  5423.5     .05       0  6338.1     .16       0  6457.6     .12       0
    6857     .16       0  7280.4     .12       0  7588.4     .16       0
Bank Sta=4967,5050.9
XS Rating Curve= 0 ,0
Exp/Cntr=0.3,0.1

Type RM Length L Ch R = 1 ,131593  ,498,498,498
BEGIN DESCRIPTION:
HURRICANE BAYOU 100.0
END DESCRIPTION:
XS GIS Cut Line= 3
      3822499.61     10488860.19      3821699.61     10489660.19
      3819699.59     10492060.21
#Sta/Elev= 30
  3834.6  331.17  3872.7  328.48    3976  320.52  4004.3   314.9  4179.5  293.64
    4385  285.02  4951.8  287.66  4987.5   281.4    4994   273.5  4998.8  272.92
  5001.5  272.42  5004.8  272.92  5030.4  273.96  5036.9  279.38  5044.1  279.25
  5051.2  285.24  5072.1   287.5  5104.1  287.01  5109.5  286.93  5242.6  285.33
    5335  289.51  5725.5  292.65  6520.9  293.81  6697.9  298.17  6812.4  305.07
  6996.6  297.11  7166.5  297.54  7756.2   313.7  7926.7  313.56  8090.1  318.66
#Mann= 8 ,-1 , 0
  3834.6     .05       0  3872.7     .16       0  4179.5     .05       0
    4385     .16       0  4998.8     .07       0  5004.8     .16       0
  5104.1     .16       0  5109.5     .05       0
Bank Sta=4951.8,5072.1
XS Rating Curve= 0 ,0
Exp/Cntr=0.3,0.1

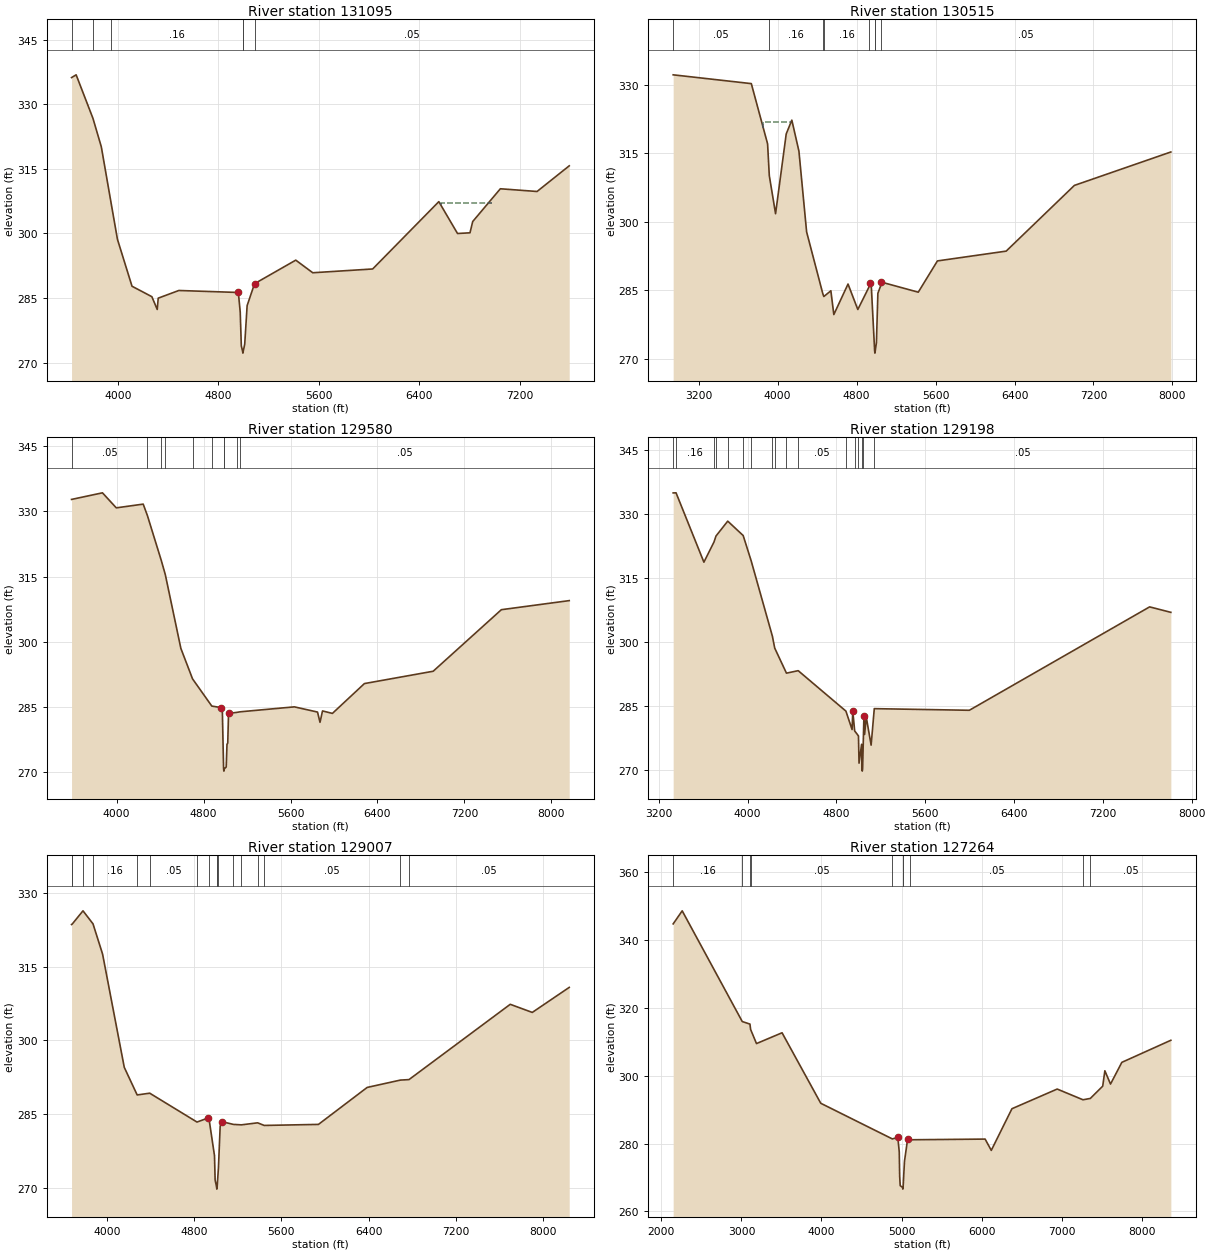
Type RM Length L Ch R = 1 ,131095  ,580,580,580
BEGIN DESCRIPTION:
HURRICANE BAYOU 99.0
END DESCRIPTION:
XS GIS Cut Line= 3
      3822049.63     10488560.15      3821249.61     10489710.19
       3819649.6      10491710.2
#Sta/Elev= 30
  3630.4  336.22    3667  336.86  3800.7  326.76  3867.4  320.14  3945.4  307.06
  3995.9  298.64  4111.8  287.75  4269.8  285.32  4312.6  282.35  4320.4  284.98
  4484.5  286.76  4958.4   286.3  4973.3  281.75    4982  273.89  4991.8  272.71
  4994.5  272.21  4997.8  272.71  5009.1   274.3  5028.3  283.25  5087.4  288.34
  5415.5  293.81  5550.8  290.88  6027.8  291.76  6554.5   307.4  6703.3     300
  6802.6  300.16  6824.2  302.78  7044.3  310.39  7336.5  309.76  7592.6  315.72
#Mann= 6 ,-1 , 0
  3630.4     .05       0  3800.7     .12       0  3945.4     .16       0
  4991.8     .07       0  4997.8     .16       0  5087.4     .05       0
#XS Ineff= 1 ,-1
  6568.1  6980.3  307.16
Permanent Ineff=
       F
Bank Sta=4958.4,5087.4
XS Rating Curve= 0 ,0
Exp/Cntr=0.3,0.1

Type RM Length L Ch R = 1 ,130515  ,935,935,935
BEGIN DESCRIPTION:
HURRICANE BAYOU 98.0
END DESCRIPTION:
XS GIS Cut Line= 3
      3822198.21     10487509.49      3821049.61     10489210.19
      3819355.64      10491675.7
#Sta/Elev= 30
  2940.9  332.24  3732.8  330.31  3897.7   317.1  3915.1  310.12  3978.6  301.77
  4086.5  319.27  4143.4   322.3  4215.4  315.49  4293.3  297.77  4457.4  284.22
  4467.8   283.6  4539.1  284.86    4569  279.64  4712.9  286.34  4812.1  280.75
  4927.4  285.77  4934.7  286.55  4949.7  285.54  4982.7  271.68  4985.4  271.18
  4988.7  271.68  5000.6  273.43  5015.5  284.32  5045.2  286.02  5051.3  286.76
  5424.8  284.55    5619  291.41  6315.6  293.56  7007.2  307.98  7984.5  315.31
#Mann= 8 ,-1 , 0
  2940.9     .05       0  3915.1     .16       0  4457.4     .05       0
  4467.8     .16       0  4927.4     .12       0  4982.7     .07       0
  4988.7     .12       0  5045.2     .05       0
#XS Ineff= 1 ,-1
  3855.7  4136.4  321.95
Permanent Ineff=
       F
Bank Sta=4934.7,5051.3
XS Rating Curve= 0 ,0
Exp/Cntr=0.3,0.1

Type RM Length L Ch R = 1 ,129580  ,382,382,382
BEGIN DESCRIPTION:
HURRICANE BAYOU 97.0
END DESCRIPTION:
XS GIS Cut Line= 3
      3821937.77     10487466.12      3820581.44      10488876.7
      3819496.36     10491263.88
#Sta/Elev= 30
  3585.2  332.77  3869.6  334.29  3996.9  330.83  4244.4  331.69  4283.6  329.03
  4410.9  318.71  4447.7  315.48    4591  298.47  4698.4  291.46  4875.6  285.19
  4958.9  284.85    4973   283.8  4984.2  270.71  4986.9  270.21  4990.2  270.71
  5008.2  271.16  5015.5  276.39  5022.4  276.67  5029.6  283.51  5104.3  283.73
  5137.2  283.87  5635.2  285.01  5848.3  283.81  5871.3  281.45  5894.4  284.07
  5985.3   283.5    6280  290.37  6912.7  293.21  7539.9  307.38  8164.3  309.47
#Mann= 10 ,-1 , 0
  3585.2     .05       0  4283.6     .16       0  4410.9     .05       0
  4447.7     .16       0  4698.4     .05       0  4875.6     .16       0
  4984.2     .07       0  4990.2     .16       0  5104.3     .16       0
  5137.2     .05       0
Bank Sta=4958.9,5029.6
XS Rating Curve= 0 ,0
Exp/Cntr=0.3,0.1

Type RM Length L Ch R = 1 ,129198  ,191,191,191
BEGIN DESCRIPTION:
HURRICANE BAYOU 96.0
END DESCRIPTION:
XS GIS Cut Line= 4
      3821362.68     10486847.64      3820733.35     10488247.36
      3820527.19     10488529.48      3819496.69     10490915.88
#Sta/Elev= 30
    3329  334.85  3354.9  334.87  3605.9  318.65  3696.4  323.35  3714.8  324.77
  3820.6  328.25  3959.7  324.88  4032.2  318.92  4223.1  301.32  4243.7  298.57
  4349.5   292.7  4455.2  293.28    4885  283.83  4940.8  279.51    4947  283.86
    4964   279.2  4998.3  278.02  5003.4  271.65  5026.5  276.07  5029.7  270.29
  5032.5  269.79  5035.7  270.29  5047.4  282.76  5053.6  278.37  5068.3  282.47
  5112.3  275.87  5140.8   284.4  5997.1  284.02  7621.3   308.2  7812.5  306.92
#Mann= 17 ,-1 , 0
    3329     .05       0  3354.9     .16       0  3696.4      .1       0
  3714.8     .08       0  3820.6     .16       0  3959.7     .08       0
  4032.2     .16       0  4223.1     .08       0  4243.7      .1       0
  4349.5     .08       0  4455.2     .05       0    4885     .16       0
    4964     .05       0  4998.3     .16       0  5029.7     .07       0
  5035.7     .16       0  5140.8     .05       0
Bank Sta=4947,5047.4
XS Rating Curve= 0 ,0
Exp/Cntr=0.3,0.1

Type RM Length L Ch R = 1 ,129007  ,1743,1743,1743
BEGIN DESCRIPTION:
HURRICANE BAYOU 95.0
END DESCRIPTION:
XS GIS Cut Line= 4
      3820950.36     10487086.34      3820820.15     10487737.38
      3820060.61     10489039.46      3819084.33     10491219.82
#Sta/Elev= 30
  3677.4  323.58  3682.8  323.65  3782.2  326.36  3873.9  323.72  3961.7  317.57
  4160.6  294.53  4278.7  288.92  4393.6  289.28  4826.9  283.41  4928.5  284.23
    4938  283.92  4987.3  276.57    4993  271.64  5005.8  270.27  5008.5  269.77
  5011.8  270.27  5023.3  274.09  5039.2  282.51  5051.8  283.51  5160.3  282.93
  5233.2  282.84  5382.5  283.25  5443.1  282.72  5939.8  282.93  6386.4  290.45
  6690.4  291.94  6769.4  292.04  7697.2  307.35  7899.2   305.7  8237.7  310.79
#Mann= 17 ,-1 , 0
  3677.4     .05       0  3682.8     .16       0  3782.2     .08       0
  3873.9     .16       0  4278.7     .08       0  4393.6     .05       0
  4826.9     .16       0    4938     .08       0  5005.8     .07       0
  5011.8     .08       0  5023.3     .05       0  5160.3     .08       0
  5233.2     .05       0  5382.5     .08       0  5443.1     .05       0
  6690.4     .08       0  6769.4     .05       0
Bank Sta=4928.5,5051.8
XS Rating Curve= 0 ,0
Exp/Cntr=0.3,0.1

Type RM Length L Ch R = 1 ,127264  ,1463,1463,1463
BEGIN DESCRIPTION:
HURRICANE BAYOU 94.0
END DESCRIPTION:
XS GIS Cut Line= 3
      3820532.96     10485186.04      3819449.61     10487810.19
      3818988.04     10491156.73
#Sta/Elev= 30
  2147.1  344.75  2259.8   348.6  3010.2  315.96  3106.2  315.21  3114.7  313.62
  3187.9  309.47  3507.4  312.65  3990.8  291.87  4885.1  281.36  4953.6  281.79
  4971.4  277.55  4976.8   270.3  4983.4  267.59  5013.4  267.06  5016.1  266.56
  5019.4  267.06  5036.6  274.76  5076.9  281.45    5106  281.11  6044.2  281.31
  6121.1  277.98  6379.1  290.26  6944.4  296.06  7266.7   292.9  7358.7   293.3
    7513  296.91    7540  301.45  7610.7  297.53    7752  303.93  8364.3  310.44
#Mann= 10 ,-1 , 0
  2147.1     .16       0  3010.2     .05       0  3106.2     .08       0
  3114.7     .05       0  4885.1     .16       0  5013.4     .07       0
  5019.4     .16       0    5106     .05       0  7266.7     .12       0
  7358.7     .05       0
Bank Sta=4953.6,5076.9
XS Rating Curve= 0 ,0
Exp/Cntr=0.3,0.1