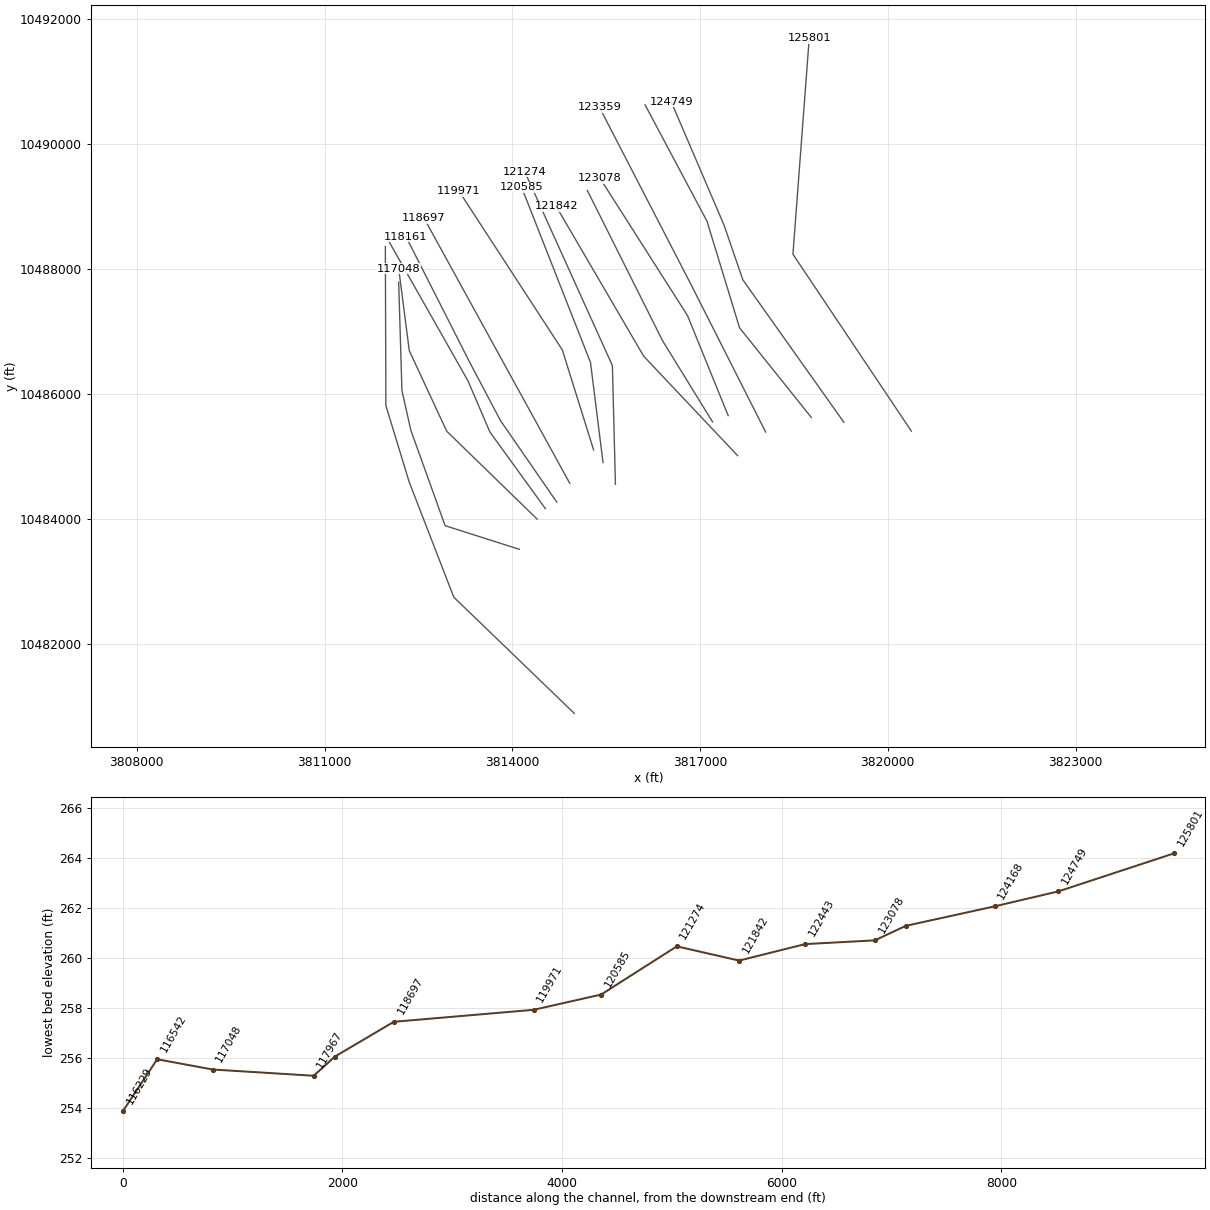
HEC-RAS study HURRICANE BAYOU.prj: HURRICANE BAYOU Base Level Engineering

--- HURRICANE BAYOU.g01 (geometry) --- (continued)

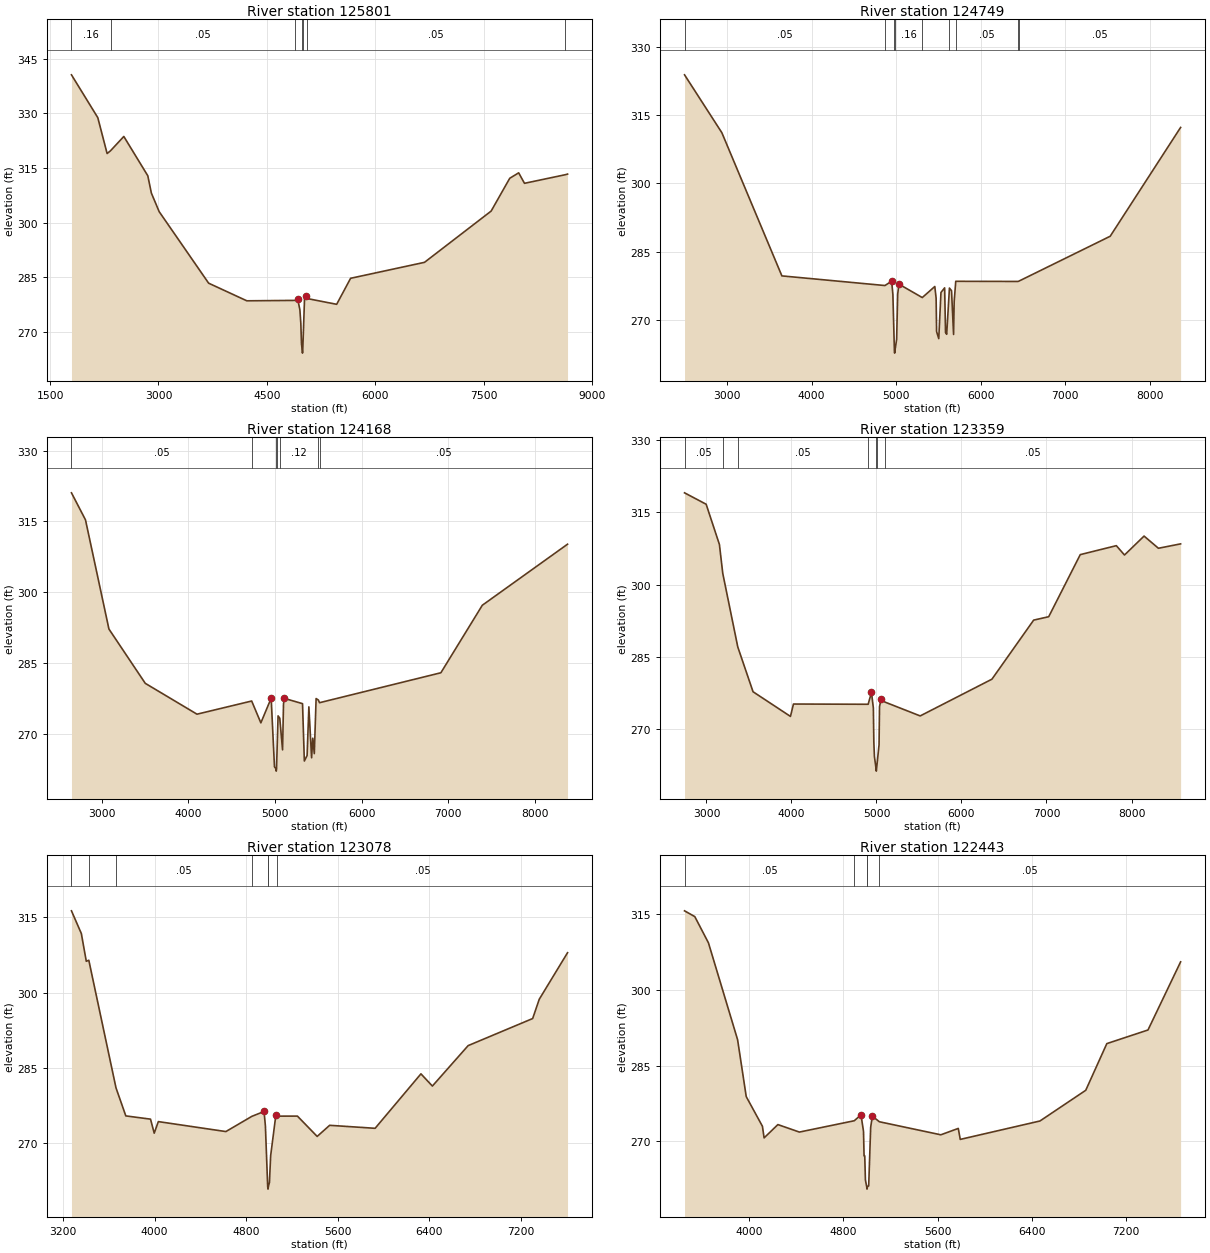
Type RM Length L Ch R = 1 ,125801  ,1052,1052,1052
BEGIN DESCRIPTION:
HURRICANE BAYOU 93.0
END DESCRIPTION:
XS GIS Cut Line= 3
      3820376.75     10485411.68      3818484.36     10488241.57
      3818744.64     10491694.65
#Sta/Elev= 30
  1796.1  340.59  2160.5  328.84  2289.6  318.98  2336.8  319.75  2520.8  323.67
  2852.9  312.88  2902.2  308.13  3010.3  303.03    3695   283.4  4223.4  278.56
  4887.8  278.67  4929.1  278.93  4958.2  276.07  4971.2  272.36  4980.2  266.82
  4991.3   264.7    4994   264.2  4997.3   264.7  5022.2  278.98  5043.2  279.82
  5059.4  279.18  5467.3   277.6  5660.3  284.74  6683.2  289.12  7605.8  303.19
  7863.1  312.19  7986.9  313.69  8067.2  310.81  8633.8  313.18  8663.3  313.35
#Mann= 7 ,-1 , 0
  1796.1     .16       0  2336.8     .05       0  4887.8     .16       0
  4991.3     .07       0  4997.3     .16       0  5059.4     .05       0
  8633.8      .1       0
Bank Sta=4929.1,5043.2
XS Rating Curve= 0 ,0
Exp/Cntr=0.3,0.1

Type RM Length L Ch R = 1 ,124749  ,581,581,581
BEGIN DESCRIPTION:
HURRICANE BAYOU 92.0
END DESCRIPTION:
XS GIS Cut Line= 4
      3819298.53     10485553.12      3817683.94     10487831.78
      3817384.46     10488704.17      3816538.11     10490683.33
#Sta/Elev= 30
  2498.1  323.83  2939.6  311.11  3649.6  279.65  4868.1  277.53  4947.8  278.48
  4962.5  275.57  4980.4  263.18  4983.2  262.68  4986.4  263.18  5006.9  265.71
  5019.2  275.61  5033.9  277.84    5310  274.89  5458.3  277.32  5473.8  274.77
  5479.4  267.42  5505.1  265.86  5531.1  276.01  5574.6  277.02  5585.2   267.2
  5598.9  266.82  5631.3  276.98  5656.1   276.4  5680.3  266.78  5687.4  274.02
  5706.1  278.46  6442.1  278.43  6451.9  278.49  7532.8  288.36  8365.7  312.27
#Mann= 9 ,-1 , 0
  2498.1     .05       0  4868.1     .16       0  4980.4     .07       0
  4986.4     .16       0    5310     .12       0  5631.3     .16       0
  5706.1     .05       0  6442.1     .16       0  6451.9     .05       0
Bank Sta=4947.8,5033.9
XS Rating Curve= 0 ,0
Exp/Cntr=0.3,0.1

Type RM Length L Ch R = 1 ,124168  ,809,809,809
BEGIN DESCRIPTION:
HURRICANE BAYOU 91.0
END DESCRIPTION:
XS GIS Cut Line= 4
       3818777.7     10485631.25      3817631.86     10487063.55
      3817111.02     10488769.28      3816121.46     10490631.23
#Sta/Elev= 30
  2651.9  321.07  2813.8  315.34  3084.3   292.2  3503.7  280.69  4100.8  274.15
  4732.1  276.94  4838.1  272.31  4957.2  277.55  4995.3  262.98  5012.9  262.58
  5015.6  262.08  5018.9  262.58  5036.8  273.79  5056.4   273.3  5088.5  266.59
  5099.5  276.33    5110   277.5  5319.1  276.38    5340  264.22  5371.8  265.38
  5392.3  275.71  5423.7  264.91  5437.4  269.06    5455  265.79  5475.9  277.46
  5502.1  277.15    5515  276.58  6916.1  282.93  7394.4  297.24  8378.2  310.18
#Mann= 7 ,-1 , 0
  2651.9     .05       0  4732.1     .16       0  5012.9     .07       0
  5018.9     .16       0  5056.4     .12       0  5502.1     .16       0
    5515     .05       0
Bank Sta=4957.2,5110
XS Rating Curve= 0 ,0
Exp/Cntr=0.3,0.1

Type RM Length L Ch R = 1 ,123359  ,281,281,281
BEGIN DESCRIPTION:
HURRICANE BAYOU 90.0
END DESCRIPTION:
XS GIS Cut Line= 3
      3818048.52     10485396.89      3816850.61     10487766.67
      3815392.28     10490592.18
#Sta/Elev= 30
  2742.6  319.08  2996.8  316.71  3152.8  308.36  3192.3  302.35  3368.9  287.08
  3548.4  277.78  3988.5  272.66  4023.7  275.23  4902.5  275.18  4941.3  277.65
  4963.6  274.41  4969.2  267.36  4976.1  264.33  4995.5   261.8  4998.3   261.3
  5001.5   261.8  5030.5  266.79  5036.1  274.66  5052.8  276.19  5102.2  275.62
  5514.4  272.76  6358.4  280.39    6849  292.65  7026.2  293.36  7397.3  306.25
  7821.4  308.11  7917.7  306.17  8147.7   310.1  8316.5  307.57  8577.6  308.48
#Mann= 7 ,-1 , 0
  2742.6     .05       0  3192.3     .16       0  3368.9     .05       0
  4902.5     .16       0  4995.5     .07       0  5001.5     .16       0
  5102.2     .05       0
Bank Sta=4941.3,5052.8
XS Rating Curve= 0 ,0
Exp/Cntr=0.3,0.1

Type RM Length L Ch R = 1 ,123078  ,635,635,635
BEGIN DESCRIPTION:
HURRICANE BAYOU 89.0
END DESCRIPTION:
XS GIS Cut Line= 3
      3817449.59     10485660.22      3816799.61     10487260.19
      3815399.63     10489460.16
#Sta/Elev= 30
  3273.3  316.32  3359.6  311.78  3402.8  306.24  3424.8  306.45  3662.4  280.95
  3748.2  275.35  3964.1   274.7  3996.4   271.9  4032.3  274.21  4622.5  272.22
  4850.3  275.27    4956  276.23  4967.9  273.32  4987.9  261.22  4990.7  260.72
  4993.9  261.22  5003.2  262.06  5013.8  267.41  5059.5  275.56  5070.5   275.3
  5247.5  275.31  5420.2  271.25  5529.4  273.47  5926.5  272.87    6327  283.75
  6426.9  281.31  6739.3  289.39  7303.1   294.8  7360.7  298.65  7607.9  307.95
#Mann= 7 ,-1 , 0
  3273.3     .05       0  3424.8     .16       0  3662.4     .05       0
  4850.3     .16       0  4987.9     .07       0  4993.9     .16       0
  5070.5     .05       0
Bank Sta=4956,5059.5
XS Rating Curve= 0 ,0
Exp/Cntr=0.3,0.1

Type RM Length L Ch R = 1 ,122443  ,601,601,601
BEGIN DESCRIPTION:
HURRICANE BAYOU 88.0
END DESCRIPTION:
XS GIS Cut Line= 3
      3817199.63     10485560.16      3816399.61     10486860.19
      3815199.59     10489260.23
#Sta/Elev= 30
    3452  315.59    3539  314.45  3654.9  309.26  3902.3  290.11  3975.6  278.86
  4112.9     273  4127.2   270.7  4244.2  273.33  4426.6  271.85  4892.6  274.09
  4949.5  275.26  4970.8  271.99  4975.5  267.16  4981.3  267.16  4986.9  262.38
  4997.8  261.07  5000.6  260.57  5003.8  261.07  5014.8   261.2  5031.6  272.77
  5045.6  275.01  5105.4  273.89  5626.9  271.31  5775.1  272.57  5791.8   270.4
  6468.3  274.04  6856.8  280.11  7035.7  289.34    7385  292.03  7661.8   305.5
#Mann= 5 ,-1 , 0
    3452     .05       0  4892.6     .16       0  4997.8     .07       0
  5003.8     .16       0  5105.4     .05       0
Bank Sta=4949.5,5045.6
XS Rating Curve= 0 ,0
Exp/Cntr=0.3,0.1

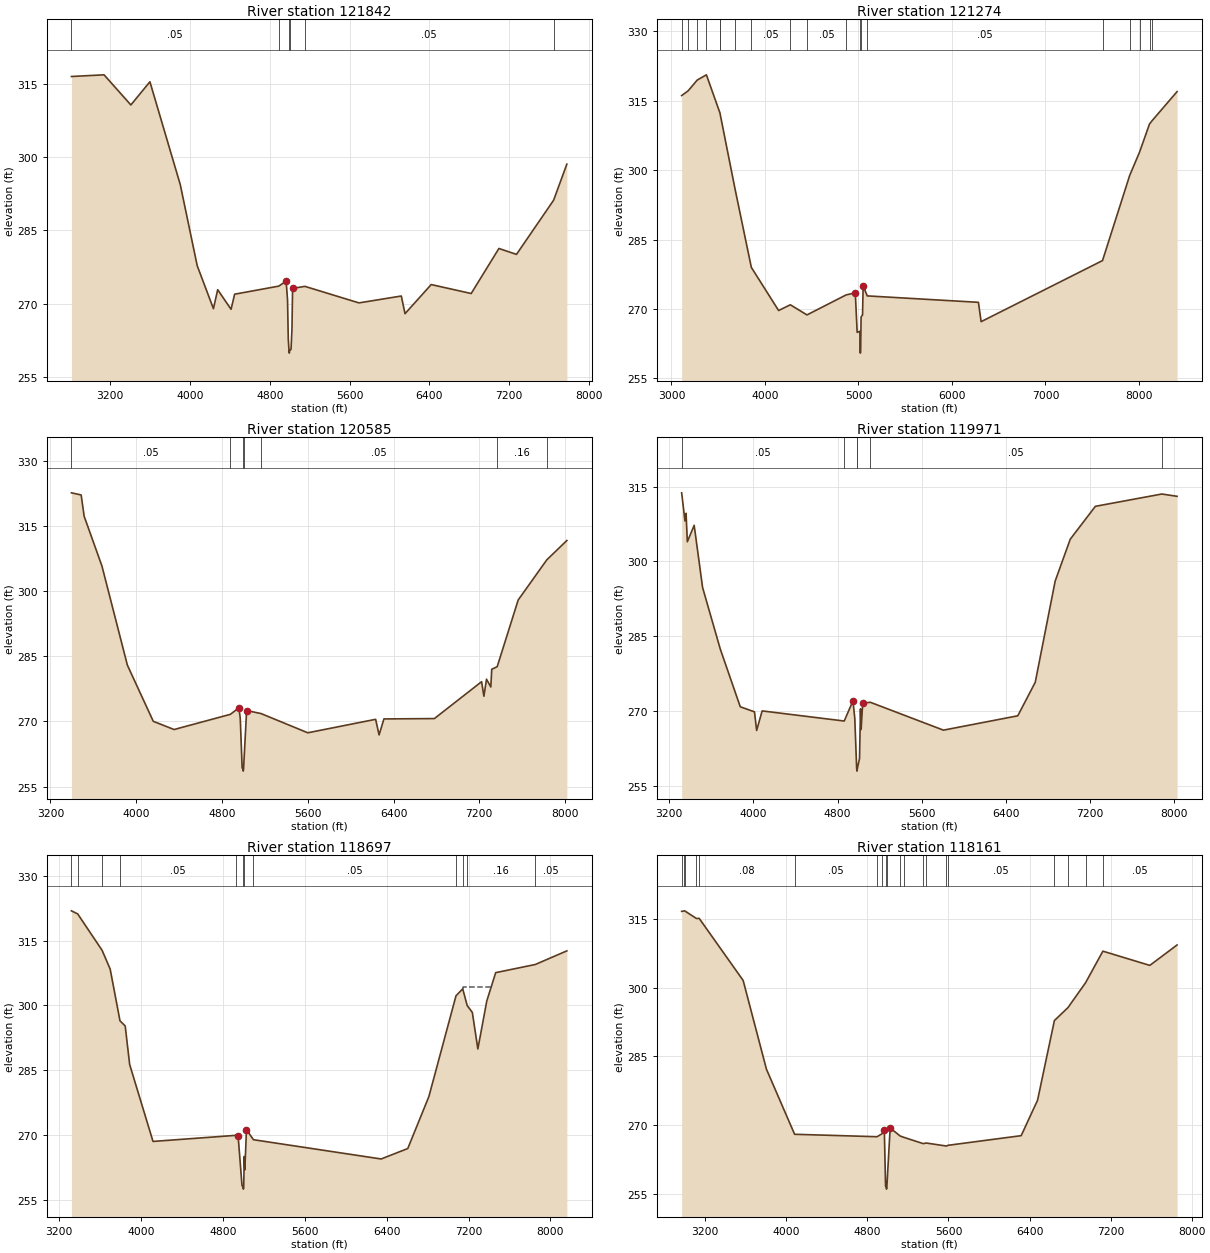
Type RM Length L Ch R = 1 ,121842  ,568,568,568
BEGIN DESCRIPTION:
HURRICANE BAYOU 87.0
END DESCRIPTION:
XS GIS Cut Line= 3
      3817601.01     10485019.35      3816099.61     10486610.19
      3814699.63     10489010.15
#Sta/Elev= 30
  2812.6  316.48  3139.7  316.82  3408.3  310.66  3599.3   315.4  3903.5  294.37
  4073.4  277.79    4236     269  4278.5  272.88  4412.8  268.87  4448.4  271.96
  4890.7  273.61  4964.7  274.63  4978.8  270.79  4986.1  262.81  4993.6  260.41
  4996.4  259.91  4999.6  260.41  5013.7  260.67  5023.2  264.89  5029.4  273.15
  5153.3  273.56  5694.7  270.18  6119.3  271.59  6156.5  267.98  6418.7  273.93
  6819.7   272.1  7097.6  281.31  7273.7   280.1  7646.2  291.19  7778.5  298.56
#Mann= 6 ,-1 , 0
  2812.6     .05       0  4890.7     .16       0  4993.6     .07       0
  4999.6     .16       0  5153.3     .05       0  7646.2     .16       0
Bank Sta=4964.7,5029.4
XS Rating Curve= 0 ,0
Exp/Cntr=0.3,0.1

Type RM Length L Ch R = 1 ,121274  ,689,689,689
BEGIN DESCRIPTION:
HURRICANE BAYOU 86.0
END DESCRIPTION:
XS GIS Cut Line= 3
      3815647.92      10484563.6      3815599.61     10486460.19
       3814199.6     10489560.22
#Sta/Elev= 30
  3108.7  316.15  3177.4  317.16  3275.5   319.5  3373.5  320.63  3519.3  312.33
    3522  311.99  3681.4  295.79    3854  279.01  4145.6  269.69  4270.9  270.93
    4449  268.74  4867.8  273.06  4965.9  273.52  4985.9  264.96  5014.7  265.21
  5017.2  260.98    5020  260.48  5023.2  260.98  5027.8  268.29  5043.3  268.72
  5049.8  275.02  5093.7  272.85  6282.8  271.46  6311.6  267.28    7610  280.48
  7901.1  298.91  8006.9  303.96  8112.8  310.01  8138.8  310.68  8407.4     317
#Mann= 19 ,-1 , 0
  3108.7     .15       0  3177.4      .1       0  3275.5     .08       0
  3373.5     .05       0  3519.3     .08       0    3522     .05       0
  3681.4     .16       0    3854     .05       0  4270.9     .16       0
    4449     .05       0  4867.8     .16       0  5017.2     .07       0
  5023.2     .16       0  5093.7     .05       0    7610     .16       0
  7901.1     .08       0  8006.9     .16       0  8112.8     .08       0
  8138.8     .05       0
Bank Sta=4965.9,5049.8
XS Rating Curve= 0 ,0
Exp/Cntr=0.3,0.1

Type RM Length L Ch R = 1 ,120585  ,614,614,614
BEGIN DESCRIPTION:
HURRICANE BAYOU 85.0
END DESCRIPTION:
XS GIS Cut Line= 3
      3815449.61     10484910.16      3815249.61     10486510.19
      3814149.61     10489310.19
#Sta/Elev= 30
  3395.7  322.58  3486.4  322.09  3514.1  317.21  3680.4  305.73  3917.3  282.95
  4159.1  270.01  4353.1  268.12  4878.3  271.62  4957.8  273.13  4970.4  270.66
    4988  259.31  4995.1  259.05  4997.9  258.55  5001.1  259.05  5029.7  272.49
  5163.4   271.8  5600.3  267.37    6233  270.47  6265.2  266.88  6310.4  270.56
  6780.9  270.64  7221.4  279.13  7242.9  275.78  7267.1   279.7  7307.4  277.91
  7315.9  281.98  7366.8  282.58  7562.6  297.92  7829.1  307.15  8016.5  311.61
#Mann= 7 ,-1 , 0
  3395.7     .05       0  4878.3     .16       0  4995.1     .07       0
  5001.1     .16       0  5163.4     .05       0  7366.8     .16       0
  7829.1     .05       0
Bank Sta=4957.8,5029.7
XS Rating Curve= 0 ,0
Exp/Cntr=0.3,0.1

Type RM Length L Ch R = 1 ,119971  ,1274,1274,1274
BEGIN DESCRIPTION:
HURRICANE BAYOU 84.0
END DESCRIPTION:
XS GIS Cut Line= 3
      3815299.62     10485110.16      3814799.61     10486710.19
      3813147.91     10489251.09
#Sta/Elev= 30
  3318.6  313.77  3350.1  308.13  3360.5  309.67  3372.6  303.95  3437.5  307.25
  3517.7  294.76  3685.3  282.45  3875.5  270.85  4010.6  269.83  4031.1   266.1
  4083.4  270.02  4863.4  267.99  4946.2  272.05  4963.5  268.54  4981.5  258.44
  4984.2  257.94  4987.5  258.44  5008.5  260.46  5017.6  270.43  5023.6  266.29
  5038.7  271.59  5111.4  271.75  5805.7  266.16  6512.2  269.04  6678.2  275.77
  6867.5  296.07  7010.6  304.46  7249.2  311.06  7880.8  313.53  8025.5  313.07
#Mann= 6 ,-1 , 0
  3318.6     .05       0  4863.4     .16       0  4981.5     .07       0
  4987.5     .16       0  5111.4     .05       0  7880.8     .16       0
Bank Sta=4946.2,5038.7
XS Rating Curve= 0 ,0
Exp/Cntr=0.3,0.1

Type RM Length L Ch R = 1 ,118697  ,536,536,536
BEGIN DESCRIPTION:
HURRICANE BAYOU 83.0
END DESCRIPTION:
XS GIS Cut Line= 2
      3814918.74     10484576.62        3812588.     10488821.43
#Sta/Elev= 30
  3318.1  321.89  3379.5  321.17  3617.8  312.75  3696.8   308.4  3792.8  296.42
  3843.7  295.24  3887.3  286.31  4115.6   268.5  4930.3  269.92  4947.6  269.72
  4985.5  258.27  4996.2  257.96  4998.9  257.46  5002.2  257.96  5007.3  265.02
    5013  261.92  5029.1   271.2  5097.5   268.9  6345.4  264.44  6605.8  266.86
  6812.3   278.9  7077.2  302.22  7142.8  303.83  7186.8  299.95  7236.9  298.37
  7290.8  289.91    7378  301.01  7465.2  307.58  7851.7  309.46  8160.7  312.62
#Mann= 12 ,-1 , 0
  3318.1     .08       0  3379.5     .05       0  3617.8     .16       0
  3792.8     .05       0  4930.3     .16       0  4996.2     .07       0
  5002.2     .16       0  5097.5     .05       0  7077.2     .08       0
  7142.8     .05       0  7186.8     .16       0  7851.7     .05       0
#XS Ineff= 1 ,-1
  7142.8  7415.4   304.2
Permanent Ineff=
       F
Bank Sta=4947.6,5029.1
XS Rating Curve= 0 ,0
Exp/Cntr=0.3,0.1

Type RM Length L Ch R = 1 ,118161  ,194,194,194
BEGIN DESCRIPTION:
HURRICANE BAYOU 82.0
END DESCRIPTION:
XS GIS Cut Line= 4
      3814710.42     10484277.13      3813811.98     10485579.21
      3813317.19     10486516.71      3812301.55     10488521.95
#Sta/Elev= 30
  2966.4  316.59    2986  316.67    2996  316.71  3112.2  315.04  3139.4  315.07
  3573.4  301.54  3803.3   282.2  4081.3  268.02  4895.2  267.49  4943.8  268.13
  4966.7  269.04  4979.1  256.66  4985.7  256.57  4988.5  256.07  4991.7  256.57
  5024.4  269.39  5123.5  267.64  5161.3  267.34  5351.8  265.98  5378.9  266.12
    5580  265.46  5596.4  265.62  6317.6  267.72  6479.2  275.44  6645.4   292.8
  6779.3  295.62  6953.3  301.05    7124  307.92  7587.3  304.82  7856.2  309.27
#Mann= 20 ,-1 , 0
  2966.4     .15       0    2986      .1       0    2996     .08       0
  3112.2     .05       0  3139.4     .08       0  4081.3     .05       0
  4895.2     .08       0  4943.8     .05       0  4985.7     .03       0
  4991.7     .05       0  5123.5     .08       0  5161.3     .05       0
  5351.8     .08       0  5378.9     .05       0    5580     .08       0
  5596.4     .05       0  6645.4     .08       0  6779.3     .05       0
  6953.3     .08       0    7124     .05       0
Bank Sta=4966.7,5024.4
XS Rating Curve= 0 ,0
Exp/Cntr=0.3,0.1

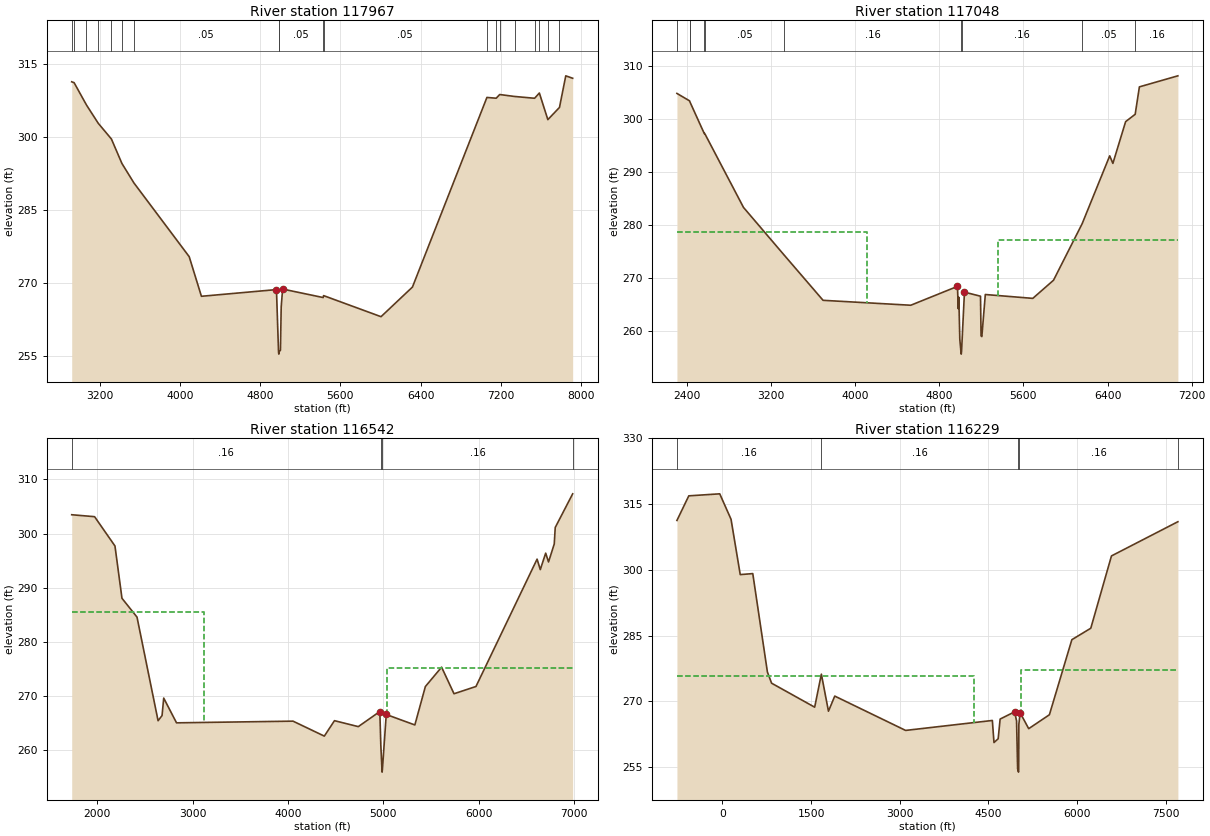
Type RM Length L Ch R = 1 ,117967  ,919,919,919
BEGIN DESCRIPTION:
HURRICANE BAYOU 81.0
END DESCRIPTION:
XS GIS Cut Line= 4
      3814528.15     10484172.93      3813642.71     10485396.92
      3813291.15     10486217.23      3812015.09     10488469.86
#Sta/Elev= 30
  2922.5  311.38  2946.3   311.2  3069.4  306.61  3187.2  302.83  3318.2   299.6
  3422.9  294.56  3542.6  290.55  4093.3  275.37  4215.1  267.21  4962.9  268.59
  4983.5   255.8  4986.3   255.3  4989.5   255.8  5002.5  256.09  5010.1  265.05
  5024.2   268.7  5428.4  266.95  5432.4  267.35  6004.9  263.01    6318  269.11
  7060.2  308.16  7152.6     308  7187.6  308.76  7335.2  308.36  7535.3  307.99
  7582.7  309.07  7667.3  303.59  7783.2   306.1    7846  312.61  7914.6  312.11
#Mann= 19 ,-1 , 0
  2922.5     .08       0  2946.3      .1       0  3069.4     .15       0
  3187.2     .08       0  3318.2     .05       0  3422.9     .08       0
  3542.6     .05       0  4983.5     .03       0  4989.5     .05       0
  5428.4     .08       0  5432.4     .05       0  7060.2     .08       0
  7152.6     .05       0  7187.6     .16       0  7335.2     .08       0
  7535.3     .16       0  7582.7     .05       0  7667.3     .16       0
  7783.2     .05       0
Bank Sta=4962.9,5024.2
XS Rating Curve= 0 ,0
Exp/Cntr=0.3,0.1

Type RM Length L Ch R = 1 ,117048  ,506,506,506
BEGIN DESCRIPTION:
HURRICANE BAYOU 80.0
END DESCRIPTION:
XS GIS Cut Line= 4
      3814397.95     10484003.66       3812952.6     10485409.94
      3812353.65       10486699.       3812184.5     10488013.15
#Sta/Elev= 30
  2305.8  304.88  2426.1  303.47  2430.4  303.23  2565.8  297.28  2569.3  297.32
  2938.6  283.31  3327.5  274.24  3695.3  265.73  4528.9   264.8  4973.2  268.37
  4980.4  264.15  4985.9  266.31  4995.3  258.36  5005.8  256.05  5008.6  255.55
  5011.8  256.05  5039.4  267.28    5192  266.51  5197.5     259  5204.8  258.87
  5237.8  266.83  5689.3   266.1  5886.2  269.53  6158.4  280.22  6420.5  293.07
  6450.8  291.64  6571.8  299.54  6662.7  300.93  6702.8  306.12  7068.8  308.21
#Mann= 10 ,-1 , 0
  2305.8     .05       0  2426.1     .08       0  2430.4      .1       0
  2565.8     .08       0  2569.3     .05       0  3327.5     .16       0
  5005.8     .07       0  5011.8     .16       0  6158.4     .05       0
  6662.7     .16       0
#XS Ineff= 2 , 0
         4113.64  278.75 5354.55          277.07
Permanent Ineff=
       F       F
Bank Sta=4973.2,5039.4
XS Rating Curve= 0 ,0
Exp/Cntr=0.3,0.1

Type RM Length L Ch R = 1 ,116542  ,313,313,313
BEGIN DESCRIPTION:
HURRICANE BAYOU 79.0
END DESCRIPTION:
XS GIS Cut Line= 5
      3814111.43     10483521.93      3812926.56     10483899.52
      3812379.69     10485422.96      3812236.46     10486060.98
      3812184.37      10487792.8
#Sta/Elev= 30
  1734.3  303.48    1974  303.12  2187.5  297.71    2261  288.05  2418.4  284.58
  2639.2  265.45  2680.8   266.4  2698.3  269.63  2832.4  265.06  4053.1  265.37
  4381.1  262.61  4487.3  265.46  4737.1  264.36  4962.6  267.15  4972.9  260.98
  4986.3  255.96  4989.6  256.46  5029.9   266.6  5329.6  264.67  5439.7  271.76
  5609.8  275.34  5739.8  270.43  5969.9  271.77  6610.2  295.28  6643.9  293.35
  6700.3  296.39  6730.3  294.76  6790.3   298.1  6800.3  301.12    6983  307.34
#Mann= 4 ,-1 , 0
  1734.3     .16       0  4972.9     .07       0  4989.6     .16       0
    6983     .16       0
#XS Ineff= 2 , 0
         3117.05  285.59 5039.77          275.17
Permanent Ineff=
       F       F
Bank Sta=4962.6,5029.9
XS Rating Curve= 0 ,0
Exp/Cntr=0.3,0.1

Type RM Length L Ch R = 1 ,116229  ,282,282,282
BEGIN DESCRIPTION:
HURRICANE BAYOU 78.0
END DESCRIPTION:
XS GIS Cut Line= 5
      3814990.44     10480897.42      3813065.13     10482755.75
      3812353.32     10484596.03      3811980.06     10485819.99
      3811971.38     10488363.36
#Sta/Elev= 30
  -768.1  311.27  -567.6  316.88   -44.2  317.34   146.8  311.54   302.5  298.92
   514.4  299.15   761.9  276.71   832.7  274.16  1561.2  268.69  1674.4  276.22
  1794.5  267.77  1900.8  271.22  3099.2  263.39  4566.1  265.66  4593.7  260.63
  4664.5  261.49  4697.4  265.98  4942.8  267.63  4975.6  265.56  4993.4  254.65
  5008.2  253.88  5011.5  254.38  5014.4  264.79    5036  267.42  5180.7  263.79
  5530.7  266.96  5910.7  284.08  6230.7  286.69  6580.7  303.18  7703.9  310.98
#Mann= 5 ,-1 , 0
  -768.1     .16       0  1674.4     .16       0  4993.4     .07       0
  5014.4     .16       0  7703.9     .05       0
#XS Ineff= 2 , 0
         4261.36  275.82 5056.82          277.24
Permanent Ineff=
       F       F
Bank Sta=4942.8,5036
XS Rating Curve= 0 ,0
Exp/Cntr=0.3,0.1