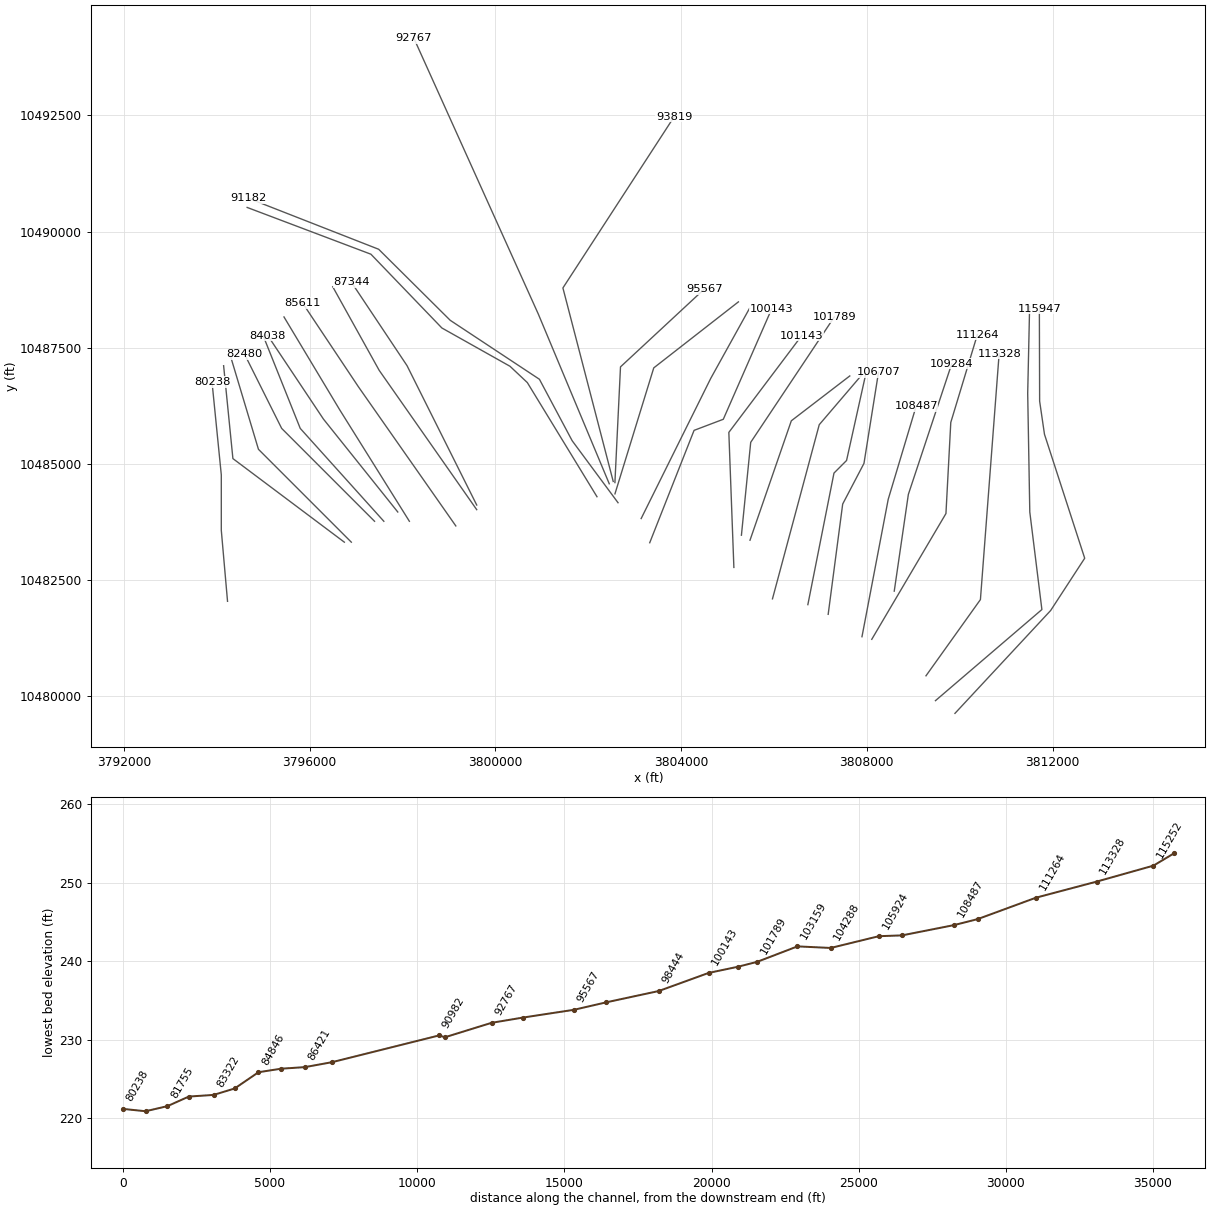
HEC-RAS study HURRICANE BAYOU.prj: HURRICANE BAYOU Base Level Engineering

--- HURRICANE BAYOU.g01 (geometry) --- (continued)

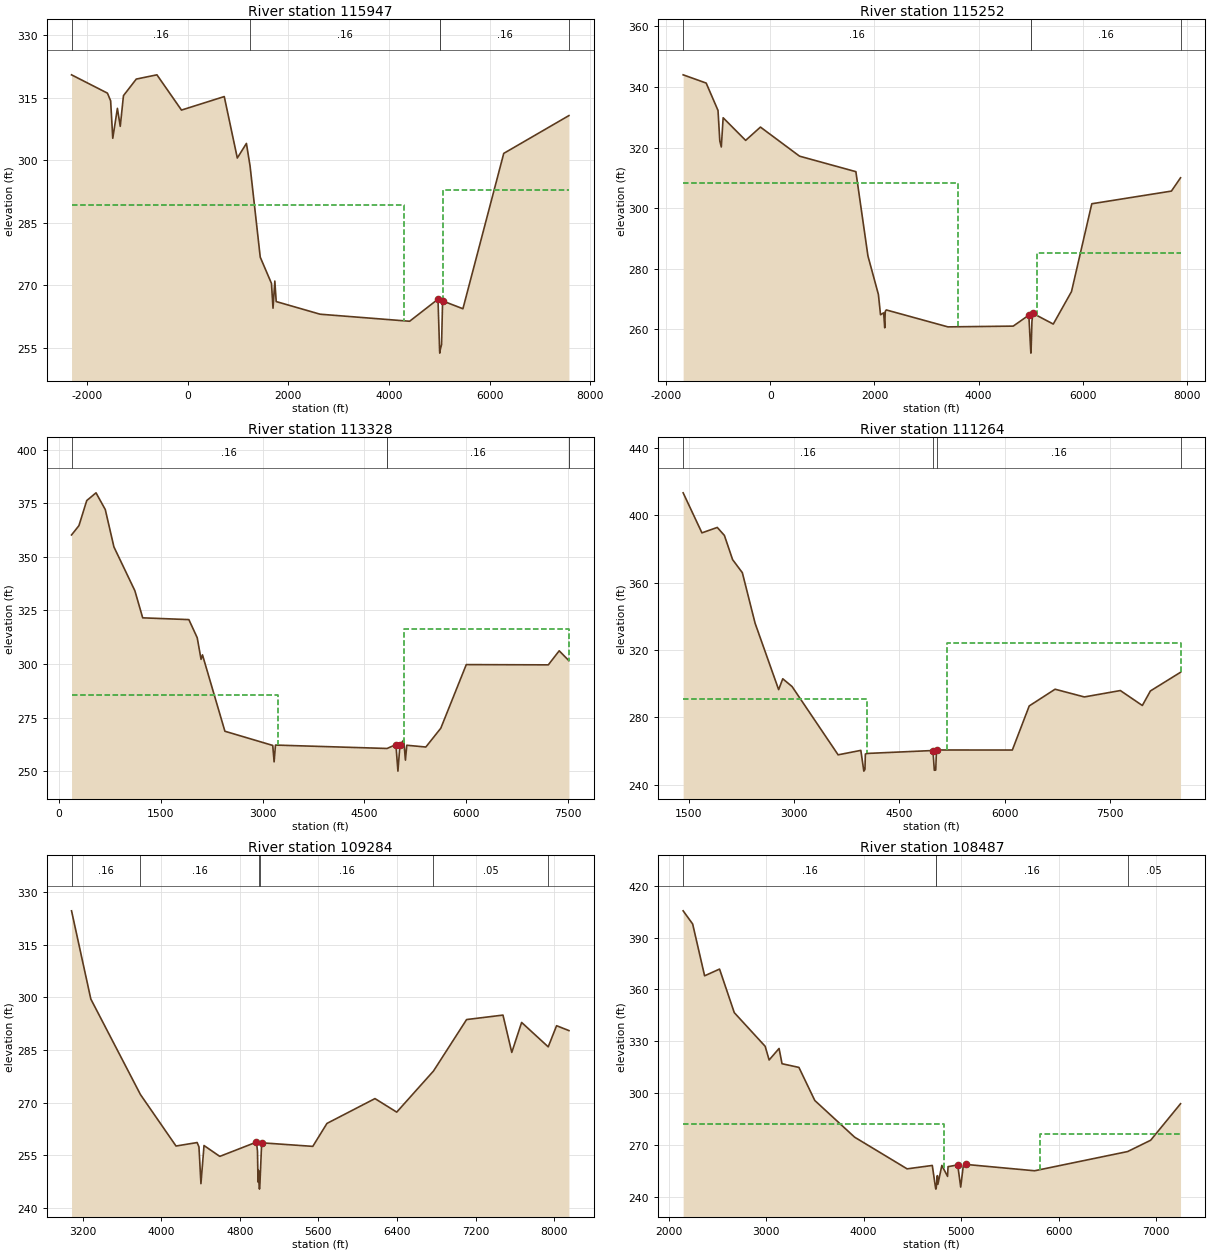
Type RM Length L Ch R = 1 ,115947  ,695,695,695
BEGIN DESCRIPTION:
HURRICANE BAYOU 169.0
END DESCRIPTION:
XS GIS Cut Line= 6
      3809897.81     10479623.77      3811958.87     10481839.49
      3812691.51     10482964.49      3811825.19     10485634.05
      3811721.02      10486347.6      3811715.31     10488335.32
#Sta/Elev= 30
 -2309.8  320.46 -1596.4  316.07 -1532.9  314.25 -1490.3  305.25 -1398.5  312.42
 -1341.8  308.11 -1277.8  315.47 -1023.3  319.44  -612.8  320.46  -124.7  312.01
     725  315.25   984.5  300.52  1165.6  304.02  1238.1  298.59  1440.3  276.76
  1663.6  270.45  1693.9  264.52  1730.1  271.03  1757.2  266.11  2629.6  263.08
  4408.9  261.39  4972.7  266.68    5005  254.25  5007.8  253.75    5011  254.25
  5043.5  255.83  5063.7  266.27  5467.9  264.39  6279.2  301.63  7574.3  310.69
#Mann= 5 ,-1 , 0
 -2309.8     .16       0  1238.1     .16       0    5005     .07       0
    5011     .16       0  7574.3     .05       0
#XS Ineff= 2 , 0
         4290.91  289.34 5068.18          292.89
Permanent Ineff=
       F       F
Bank Sta=4972.7,5063.7
XS Rating Curve= 0 ,0
Exp/Cntr=0.3,0.1

Type RM Length L Ch R = 1 ,115252  ,1924,1924,1924
BEGIN DESCRIPTION:
HURRICANE BAYOU 77.0
END DESCRIPTION:
XS GIS Cut Line= 5
      3809477.92     10479897.71      3811769.55     10481859.48
      3811509.14     10483960.18        3811464.     10486514.58
      3811505.65      10488385.6
#Sta/Elev= 30
   -1677  344.01 -1234.4  341.29 -1007.1  332.26    -972  322.16  -943.5  320.21
  -908.4  329.84  -475.9  322.38  -191.6  326.77   560.3  317.17  1642.6  312.06
  1874.4  284.26  2075.9  271.53  2116.3  264.85  2176.7  265.48  2197.3  260.54
  2206.9  265.93  2227.1  266.44  3411.5  260.85  4666.6   261.1  4966.7  264.72
  5003.7  252.69  5006.4  252.19  5009.7  252.69  5026.7  262.74  5046.7   265.3
  5436.7  261.78  5786.8  272.49  6176.9  301.47  7707.2  305.65  7882.7  310.04
#Mann= 4 ,-1 , 0
   -1677     .16       0  5003.7     .07       0  5009.7     .16       0
  7882.7     .05       0
#XS Ineff= 2 , 0
         3614.75  308.48    5125          285.17
Permanent Ineff=
       F       F
Bank Sta=4966.7,5046.7
XS Rating Curve= 0 ,0
Exp/Cntr=0.3,0.1

Type RM Length L Ch R = 1 ,113328  ,2064,2064,2064
BEGIN DESCRIPTION:
HURRICANE BAYOU 76.0
END DESCRIPTION:
XS GIS Cut Line= 3
      3809274.04     10480432.86      3810445.91     10482073.48
      3810849.56     10487372.97
#Sta/Elev= 30
   182.4  360.19   291.2  364.52   406.7  376.22   543.2  379.82   679.6  372.04
   807.4   354.6  1115.8  334.22  1231.3  321.58  1911.9  320.75  2034.8  312.31
  2091.6  302.24  2112.5  304.33  2442.9  268.74    3148  262.13  3168.1  254.48
  3188.1   262.3  4827.5  260.72  4836.5  260.76  4963.3  262.52  4993.1  250.16
  5023.4  262.48  5078.4  264.63  5103.7  255.28  5123.7  262.21  5404.5  261.39
  5625.2  270.16  6000.5  299.79  7209.7  299.67  7370.2  306.22  7513.4  301.61
#Mann= 5 ,-1 , 0
   182.4     .16       0  4827.5     .07       0  4836.5     .16       0
  7513.4     .12       0  7513.4     .05       0
#XS Ineff= 2 , 0
         3231.82   285.6 5081.82           316.3
Permanent Ineff=
       F       F
Bank Sta=4963.3,5023.4
XS Rating Curve= 0 ,0
Exp/Cntr=0.3,0.1

Type RM Length L Ch R = 1 ,111264  ,1980,1980,1980
BEGIN DESCRIPTION:
HURRICANE BAYOU 75.0
END DESCRIPTION:
XS GIS Cut Line= 4
      3808106.49     10481218.42      3809703.73     10483926.78
      3809807.89     10485888.58      3810380.81     10487780.93
#Sta/Elev= 30
  1418.2  413.39  1685.8  389.61  1904.3  392.84  2005.8  388.09  2122.9   373.7
  2261.5  365.96  2442.9  335.98  2778.6   296.5  2837.1  302.96  2969.9  298.34
    3626  257.79  3949.6  260.44  3992.3  248.11  4008.2  249.14    4014  258.23
  4035.4   258.6  4976.4  260.35  4996.5  248.63  5006.5  248.66  5016.5  248.75
  5026.5  259.93  5036.5  260.67    6108  260.64  6348.4  286.82  6716.8  296.75
  7133.2  292.17  7646.7  295.96    7960  287.09    8075  295.73  8504.2  306.82
#Mann= 4 ,-1 , 0
  1418.2     .16       0  4976.4     .07       0  5036.5     .16       0
  8504.2     .16       0
#XS Ineff= 2 , 0
         4040.91  290.87 5172.73          323.95
Permanent Ineff=
       F       F
Bank Sta=4976.4,5036.5
XS Rating Curve= 0 ,0
Exp/Cntr=0.3,0.1

Type RM Length L Ch R = 1 ,109284  ,797,797,797
BEGIN DESCRIPTION:
HURRICANE BAYOU 74.0
END DESCRIPTION:
XS GIS Cut Line= 3
      3808590.45     10482255.77      3808894.26      10484339.1
      3809827.43     10487149.46
#Sta/Elev= 30
    3085   324.6  3281.5  299.49  3786.8  272.31  4149.4  257.65  4364.5  258.64
    4383   257.4  4403.2  246.93  4434.5  257.79  4595.2   254.7  4969.1  258.77
  4979.2  256.17  4984.6  247.39  4989.6  250.71  4996.5  245.88  4999.2  245.38
  5002.5  245.88  5019.7  257.22  5029.8  258.55  5542.5  257.55  5686.7  264.08
  6175.9  271.15  6397.6   267.3    6772     279  7109.2  293.65  7479.8  294.92
  7569.5   284.3  7669.8  292.83  7940.7  285.88  8025.9   291.9  8151.6  290.51
#Mann= 6 ,-1 , 0
    3085     .16       0  3786.8     .16       0  4996.5     .07       0
  5002.5     .16       0    6772     .05       0  7940.7     .16       0
Bank Sta=4969.1,5029.8
XS Rating Curve= 0 ,0
Exp/Cntr=0.3,0.1

Type RM Length L Ch R = 1 ,108487  ,1780,1780,1780
BEGIN DESCRIPTION:
HURRICANE BAYOU 73.0
END DESCRIPTION:
XS GIS Cut Line= 3
      3807895.47     10481273.97      3808460.72      10484233.8
      3809060.73     10486233.82
#Sta/Elev= 30
  2148.9  405.47  2246.3  397.88    2369  367.91  2522.1   371.8  2673.4  346.62
    2990  327.17  3030.8  319.27  3132.6  325.92  3163.1   317.1  3336.2  314.97
  3499.1  295.85  3907.5  274.65  4445.9  256.34  4704.3   258.3  4738.1  245.12
  4740.9  244.62  4744.1  245.12  4756.4  252.43  4761.5  247.41  4802.2  258.32
  4860.7  251.99  4865.7  257.61  4964.9   258.6  4995.6   245.8  5022.1  258.13
  5046.6  258.91  5753.5  255.23  6707.9  266.34  6943.7  272.87  7250.3  293.97
#Mann= 4 ,-1 , 0
  2148.9     .16       0  4738.1     .07       0  4744.1     .16       0
  6707.9     .05       0
#XS Ineff= 2 , 0
         4822.73  281.98 5807.95           276.5
Permanent Ineff=
       F       F
Bank Sta=4964.9,5046.6
XS Rating Curve= 0 ,0
Exp/Cntr=0.3,0.1

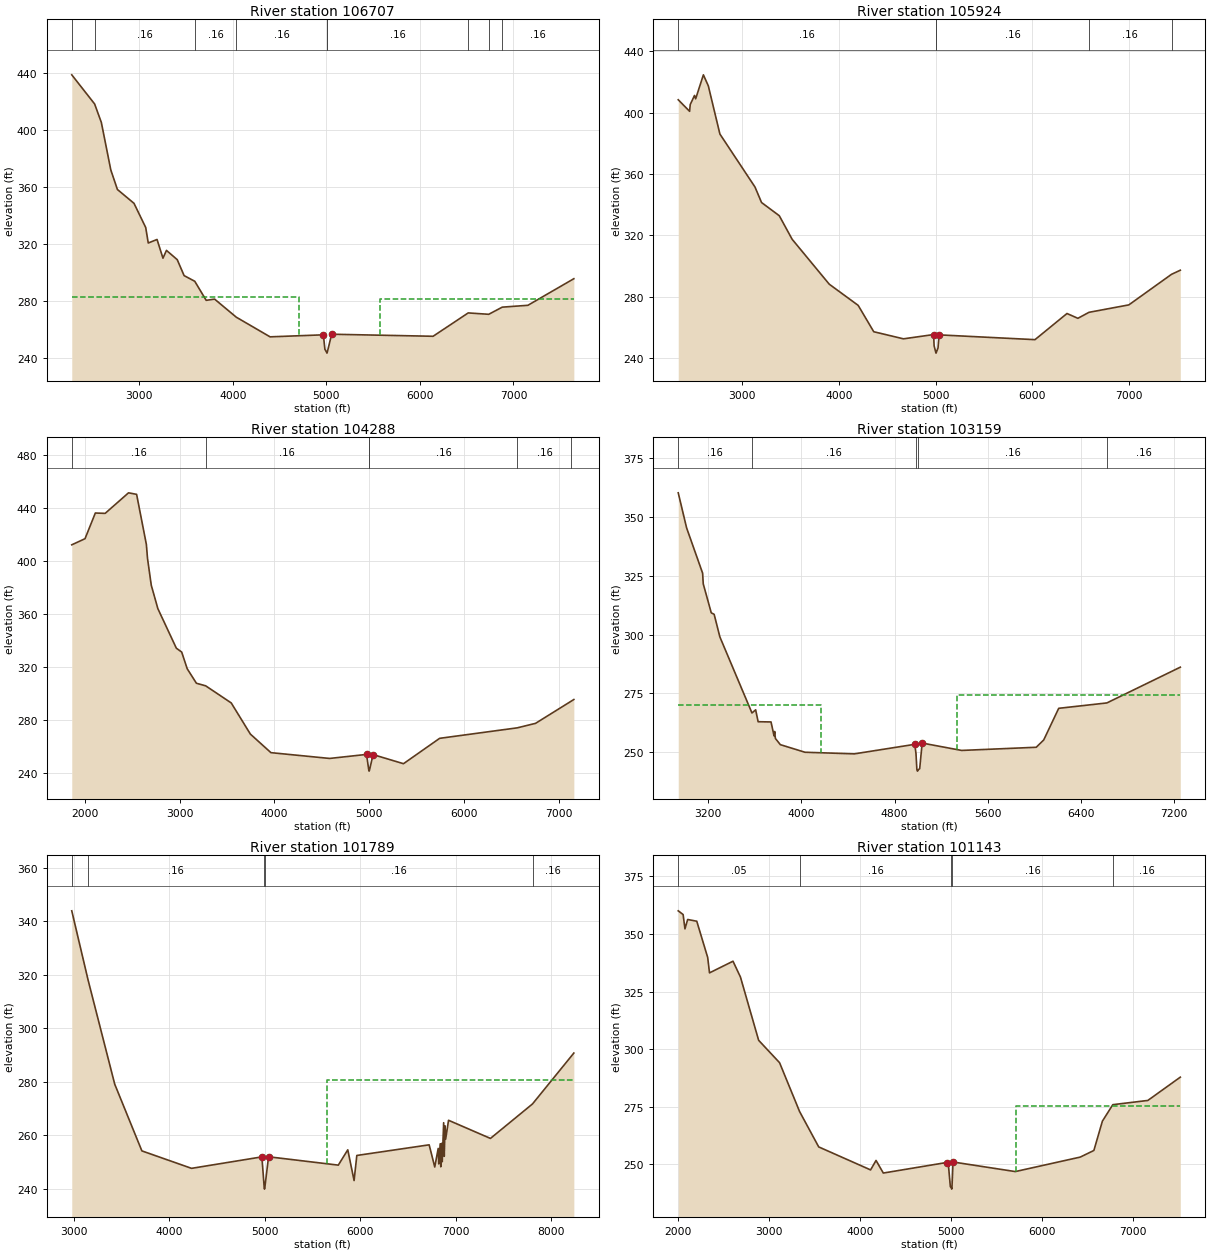
Type RM Length L Ch R = 1 ,106707  ,783,783,783
BEGIN DESCRIPTION:
HURRICANE BAYOU 71.0
END DESCRIPTION:
XS GIS Cut Line= 4
       3807167.7     10481756.59       3807480.2     10484131.64
      3807938.53     10485006.64      3808251.03     10486964.97
#Sta/Elev= 30
  2278.8  438.68  2523.2  418.21  2595.1  405.21    2696   371.9  2766.6  358.19
  2944.1  348.45  3069.2  331.49  3096.4  320.61  3190.2  323.09  3253.7  309.95
    3291  315.42    3406  308.93  3479.6  297.72  3593.6  293.73  3715.6  280.36
  3805.4  281.22  4037.4  268.52  4398.5  254.73  4967.9  256.15  4984.3  246.04
  5003.4   243.8  5006.1   243.3  5009.4   243.8  5056.5  256.57  6140.7  255.13
  6516.3  271.53  6735.3  270.56  6880.2  275.58  7154.3  276.88  7645.2  295.54
#Mann= 9 ,-1 , 0
  2278.8     .05       0  2523.2     .16       0  3593.6     .16       0
  4037.4     .16       0  5003.4     .07       0  5009.4     .16       0
  6516.3     .16       0  6735.3     .05       0  6880.2     .16       0
#XS Ineff= 2 , 0
         4710.23  282.38 5569.32          281.43
Permanent Ineff=
       F       F
Bank Sta=4967.9,5056.5
XS Rating Curve= 0 ,0
Exp/Cntr=0.3,0.1

Type RM Length L Ch R = 1 ,105924  ,1636,1636,1636
BEGIN DESCRIPTION:
HURRICANE BAYOU 70.0
END DESCRIPTION:
XS GIS Cut Line= 4
       3806730.2     10481964.97       3807292.7      10484798.3
      3807563.53     10485069.14       3807980.2     10486944.15
#Sta/Elev= 30
  2338.5  408.32    2456  400.78  2462.5  405.18  2506.9  411.14  2518.7  408.94
  2598.7  424.57  2649.7  417.36  2769.4  385.99  3132.7  351.41  3200.2  341.34
  3383.4  332.76  3516.3  317.42  3900.2  288.13  4199.3  274.33  4360.6  257.14
  4667.6  252.52  4979.7   255.3  4984.8  247.97  5001.8   243.7  5004.5   243.2
  5007.8   243.7  5025.2  246.58    5036   255.1    6028  251.98    6359  269.02
  6471.7  265.89  6586.3  269.79  6998.7  274.64    7440  294.56  7530.9  297.23
#Mann= 5 ,-1 , 0
  2338.5     .16       0  5001.8     .07       0  5007.8     .16       0
  6586.3     .16       0    7440      .1       0
Bank Sta=4979.7,5036
XS Rating Curve= 0 ,0
Exp/Cntr=0.3,0.1

Type RM Length L Ch R = 1 ,104288  ,1129,1129,1129
BEGIN DESCRIPTION:
HURRICANE BAYOU 69.0
END DESCRIPTION:
XS GIS Cut Line= 3
      3805968.41     10482090.02      3806975.34     10485839.97
      3807894.53     10486915.25
#Sta/Elev= 30
  1861.7  412.26  2001.5  416.86  2110.4  436.23  2213.9  435.95  2460.6  451.44
  2545.8   450.3  2648.8  412.57  2660.6  402.14  2700.6  381.78  2770.2  364.14
    2965  334.36  3021.6  331.42  3079.7  318.86  3176.9  307.92  3274.5  305.99
  3544.1   293.1  3746.3   269.6  3963.2  255.62  4582.4  251.26  4971.9  254.29
  4996.2   242.2    4999   241.7  5002.2   242.2  5040.6  254.17  5361.6   247.3
  5743.1  266.41    6563  274.33  6755.1  277.71  7134.1  294.55  7159.1  295.67
#Mann= 6 ,-1 , 0
  1861.7     .16       0  3274.5     .16       0  4996.2     .07       0
  5002.2     .16       0    6563     .16       0  7134.1      .1       0
Bank Sta=4971.9,5040.6
XS Rating Curve= 0 ,0
Exp/Cntr=0.3,0.1

Type RM Length L Ch R = 1 ,103159  ,1370,1370,1370
BEGIN DESCRIPTION:
HURRICANE BAYOU 67.0
END DESCRIPTION:
XS GIS Cut Line= 3
      3805484.42     10483352.46      3806374.16     10485924.04
      3807632.83     10486889.74
#Sta/Elev= 30
  2944.5  360.29  3016.2  345.39  3153.7  326.11  3159.1  321.57  3227.8  309.25
  3252.6  308.61  3301.9  298.98    3577  266.64  3608.7  267.97  3629.9  262.92
  3740.6  262.82  3766.5   256.9  3771.8  258.76    3778   255.8  3820.4  253.16
    4032  249.93  4455.3  249.24  4973.8   253.3  4984.3  249.39  4991.9  242.58
    4997   241.9  5005.5  242.53  5016.1  242.94  5037.3  253.84  5375.9   250.7
  6015.8  252.05  6080.2  255.15  6208.9  268.62  6622.2  270.91  7252.1  286.12
#Mann= 5 ,-1 , 0
  2944.5     .16       0    3577     .16       0  4984.3     .07       0
  5005.5     .16       0  6622.2     .16       0
#XS Ineff= 2 , 0
         4168.18  269.99 5334.09          274.42
Permanent Ineff=
       F       F
Bank Sta=4973.8,5037.3
XS Rating Curve= 0 ,0
Exp/Cntr=0.3,0.1

Type RM Length L Ch R = 1 ,101789  ,646,646,646
BEGIN DESCRIPTION:
HURRICANE BAYOU 66.0
END DESCRIPTION:
XS GIS Cut Line= 3
      3805299.61     10483460.17      3805499.61     10485460.19
      3807299.62      10488160.2
#Sta/Elev= 30
  2981.2  343.85  3152.1     318  3430.9  279.11  3714.9  254.21  4234.9  247.69
  4971.1  251.97  4995.7  240.43  4998.5  239.93  5001.7  240.43  5040.8  252.01
  5770.9  248.89    5870  254.61  5936.1  243.14  5964.7   252.5  6721.9  256.47
  6780.4  248.19  6816.5  255.13  6822.5  249.33  6837.5  256.87  6843.5  248.26
  6852.6  257.03  6858.6  250.16  6873.6  264.72  6879.6  252.19  6888.6  263.54
  6894.6  258.59  6924.7  265.64  7363.3  258.86  7803.5  271.74  8236.2  290.74
#Mann= 5 ,-1 , 0
  2981.2     .05       0  3152.1     .16       0  4995.7     .07       0
  5001.7     .16       0  7803.5     .16       0
#XS Ineff= 2 , 0
                         5651.14          280.68
Permanent Ineff=
       F       F
Bank Sta=4971.1,5040.8
XS Rating Curve= 0 ,0
Exp/Cntr=0.3,0.1

Type RM Length L Ch R = 1 ,101143  ,1000,1000,1000
BEGIN DESCRIPTION:
HURRICANE BAYOU 65.0
END DESCRIPTION:
XS GIS Cut Line= 3
      3805137.18     10482766.48      3805028.68     10485674.48
      3806599.64     10487760.23
#Sta/Elev= 30
  1999.4  359.98  2053.1  358.37  2073.3  352.17  2103.2  356.22  2203.2  355.47
  2323.3  339.77  2343.3  333.08  2601.7  338.13  2683.6  331.26  2883.7  303.84
  3113.9  294.12    3334  272.95  3544.2  257.61  4114.6  247.65  4174.6  251.74
  4254.7  246.28  4950.2  250.85    4971   249.6  4991.9  240.34  5003.4  239.81
  5006.2  239.31  5009.4  239.81    5021  251.08    5706  246.92  6420.2   253.2
  6570.1  256.07  6663.8  268.78  6778.3  275.93  7163.5  277.76  7520.6  287.86
#Mann= 5 ,-1 , 0
  1999.4     .05       0    3334     .16       0  5003.4     .07       0
  5009.4     .16       0  6778.3     .16       0
#XS Ineff= 2 , 0
                         5709.09          275.16
Permanent Ineff=
       F       F
Bank Sta=4950.2,5021
XS Rating Curve= 0 ,0
Exp/Cntr=0.3,0.1

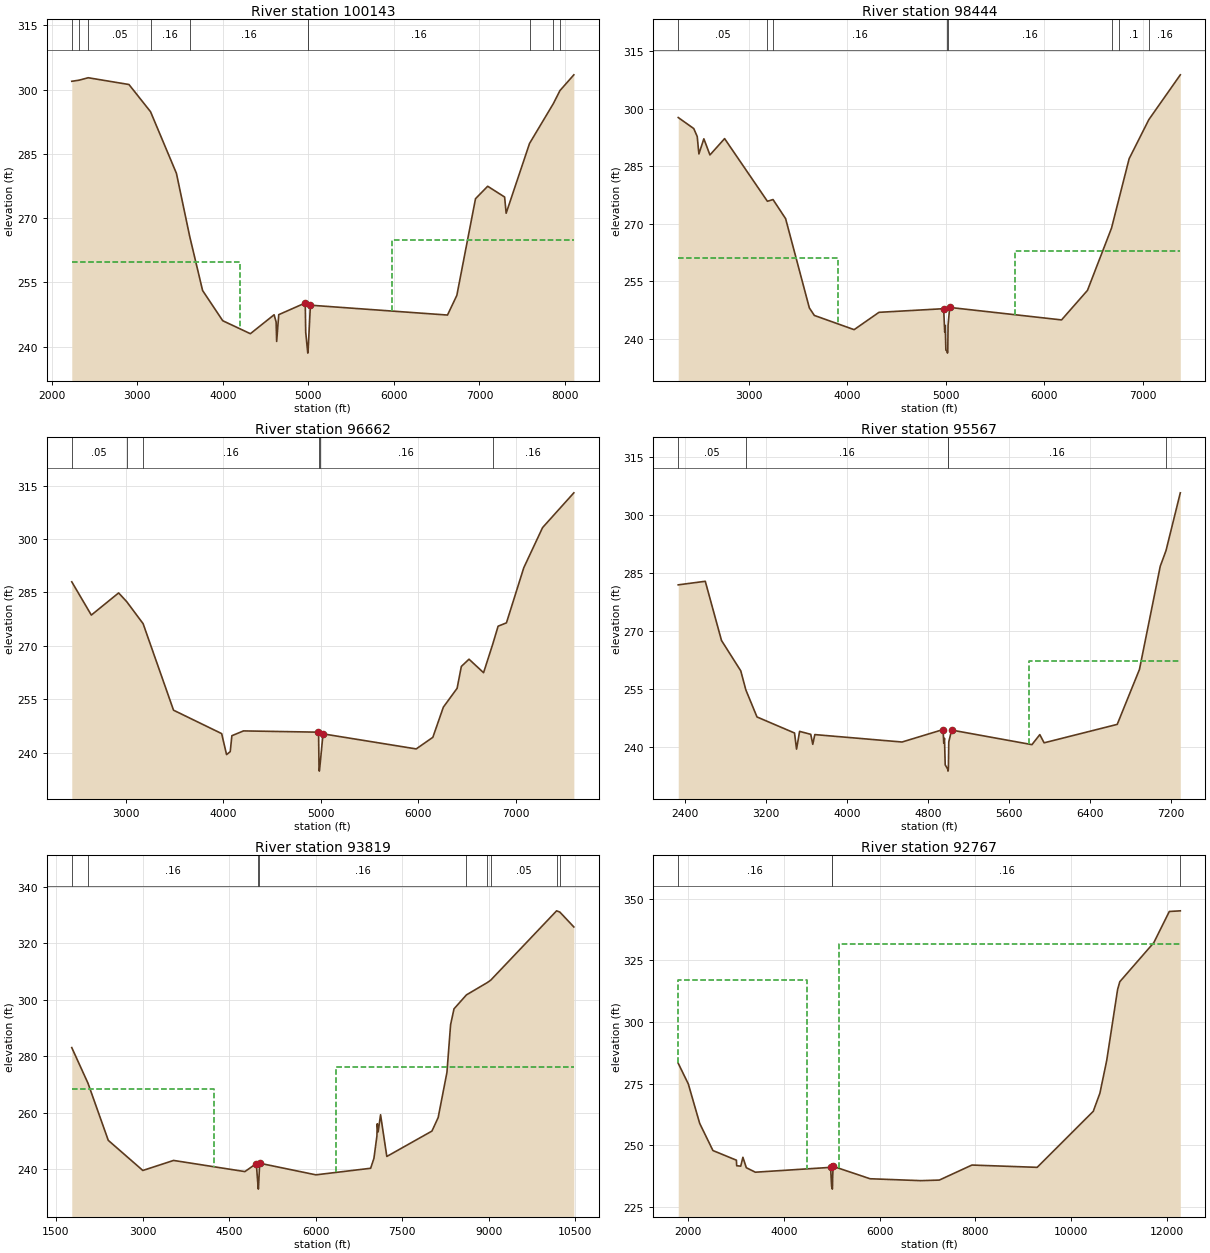
Type RM Length L Ch R = 1 ,100143  ,1699,1699,1699
BEGIN DESCRIPTION:
HURRICANE BAYOU 64.0
END DESCRIPTION:
XS GIS Cut Line= 4
      3803325.11     10483298.16      3804279.98     10485717.88
      3804909.32     10485956.59      3805950.99     10488332.91
#Sta/Elev= 30
  2234.3  301.92  2319.6  302.18  2426.7  302.75    2903  301.17    3155  294.83
  3457.8  280.45  3612.5  265.78  3763.5  253.13  3998.9  246.08  4322.1  243.05
  4599.6  247.47  4623.1  245.78  4629.4  241.25  4653.7  247.49  4963.6  250.22
    4969   243.4  4990.7  239.02  4993.5  238.52  4996.7  239.02  5023.9   249.7
  6626.3   247.4  6735.5  251.99  6953.9  274.54  7096.2  277.44  7294.1  274.93
    7312  271.15  7585.5  287.43  7863.8  296.72    7941  299.76  8103.3  303.43
#Mann= 10 ,-1 , 0
  2234.3     .05       0  2319.6     .08       0  2426.7     .05       0
    3155     .16       0  3612.5     .16       0  4990.7     .07       0
  4996.7     .16       0  7585.5     .16       0  7863.8      .1       0
    7941     .05       0
#XS Ineff= 2 , 0
         4199.43  259.71 5977.27          264.88
Permanent Ineff=
       F       F
Bank Sta=4963.6,5023.9
XS Rating Curve= 0 ,0
Exp/Cntr=0.3,0.1

Type RM Length L Ch R = 1 ,98444   ,1782,1782,1782
BEGIN DESCRIPTION:
HURRICANE BAYOU 63.0
END DESCRIPTION:
XS GIS Cut Line= 3
      3803140.67     10483819.05      3804638.05      10486835.5
      3805473.57     10488343.78
#Sta/Elev= 30
  2287.1  297.71  2444.7  294.83  2479.8  292.74  2496.6  288.21    2547  292.16
  2608.7  287.94  2757.3  292.21  3191.4  275.85  3248.5   276.3  3376.2  271.31
  3616.9  248.01  3667.5  246.05  4070.9  242.34    4323  246.86    4979  247.81
  4989.7  241.71  4995.3  243.45  5001.3  237.01  5014.7  236.71  5017.4  236.21
  5020.7  236.71  5023.6  243.47  5040.1  248.14  6174.5  244.88  6437.5  252.59
  6681.4  268.85  6762.2  277.05    6860  286.96  7059.7  297.16    7379  308.86
#Mann= 8 ,-1 , 0
  2287.1     .05       0  3191.4     .16       0  3248.5     .16       0
  5014.7     .07       0  5020.7     .16       0  6681.4     .16       0
  6762.2      .1       0  7059.7     .16       0
#XS Ineff= 2 , 0
         3909.09  260.93 5705.68          262.95
Permanent Ineff=
       F       F
Bank Sta=4979,5040.1
XS Rating Curve= 0 ,0
Exp/Cntr=0.3,0.1

Type RM Length L Ch R = 1 ,96662   ,1095,1095,1095
BEGIN DESCRIPTION:
HURRICANE BAYOU 61.0
END DESCRIPTION:
XS GIS Cut Line= 3
      3802576.42      10484350.7      3803411.92     10487063.37
      3805234.74     10488484.73
#Sta/Elev= 30
  2446.3  287.96  2646.9  278.61  2927.1  284.84  3010.8  282.35  3178.2  276.19
  3490.1  251.89  3983.9  245.31  4033.9  239.41  4071.8  240.25  4088.5  244.72
  4207.8  246.07  4967.5  245.72    4978   245.2  4982.6  235.27  4985.4  234.77
  4988.6  235.27  5023.6  245.24  5979.2  241.01    6150  244.27  6257.7  252.74
  6398.8  258.04  6442.2  264.18  6520.9  266.22  6670.2  262.42  6763.3  270.36
  6819.4  275.49  6904.9  276.43  7082.7  291.92  7275.4  303.19  7596.2  312.96
#Mann= 6 ,-1 , 0
  2446.3     .05       0  3010.8     .05       0  3178.2     .16       0
  4982.6     .07       0  4988.6     .16       0  6763.3     .16       0
Bank Sta=4967.5,5023.6
XS Rating Curve= 0 ,0
Exp/Cntr=0.3,0.1

Type RM Length L Ch R = 1 ,95567   ,1748,1748,1748
BEGIN DESCRIPTION:
HURRICANE BAYOU 60.0
END DESCRIPTION:
XS GIS Cut Line= 3
      3802575.47     10484593.65      3802695.78     10487085.07
      3804499.61     10488760.19
#Sta/Elev= 30
  2335.3     282  2602.2  282.92  2762.3  267.62  2952.6  259.75  3002.6  254.84
  3112.7  247.83  3483.2  243.68  3503.2  239.51  3533.2   244.1  3643.4  243.34
  3663.4  240.75  3683.4  243.27  4544.4  241.35  4949.1  244.57  4956.5  241.03
  4963.3  242.31  4970.6  235.45  4995.6  234.32  4998.4  233.82  5001.6  234.32
  5005.8  241.37  5034.1  244.44  5826.7  240.67  5904.4  243.26  5946.9  241.14
  6668.6  245.91  6887.9  260.11  7093.2   286.8  7149.8  290.83  7291.3   305.8
#Mann= 5 ,-1 , 0
  2335.3     .05       0  3002.6     .16       0  4995.6     .07       0
  5001.6     .16       0  7149.8     .05       0
#XS Ineff= 2 , 0
                         5794.32          262.34
Permanent Ineff=
       F       F
Bank Sta=4949.1,5034.1
XS Rating Curve= 0 ,0
Exp/Cntr=0.3,0.1

Type RM Length L Ch R = 1 ,93819   ,1052,1052,1052
BEGIN DESCRIPTION:
HURRICANE BAYOU 59.0
END DESCRIPTION:
XS GIS Cut Line= 3
      3802539.01      10484617.9      3801455.67     10488784.57
      3803851.52      10492472.1
#Sta/Elev= 30
  1773.8  283.03  2055.1  270.39  2406.4  250.13  3005.7  239.44  3538.8     243
  4774.8  239.04  4972.3  241.89  5004.6  233.32  5007.4  232.82  5010.6  233.32
  5030.9  242.01  6005.5  237.89  6954.2  240.22  7011.5  243.75  7062.9  251.65
  7068.9     256    7084  253.11  7126.2   259.2  7234.9  244.41  8017.1  253.42
  8124.9  258.22  8276.8  274.24  8340.1  291.15  8399.2  296.78  8614.9  301.74
  8977.7  306.12  9034.1  306.92 10177.6  331.56 10233.7  331.12 10476.5  325.84
#Mann= 9 ,-1 , 0
  1773.8     .05       0  2055.1     .16       0  5004.6     .07       0
  5010.6     .16       0  8614.9     .05       0  8977.7     .08       0
  9034.1     .05       0 10177.6     .08       0 10233.7     .05       0
#XS Ineff= 2 , 0
         4240.91  268.37 6361.36          276.27
Permanent Ineff=
       F       F
Bank Sta=4972.3,5030.9
XS Rating Curve= 0 ,0
Exp/Cntr=0.3,0.1

Type RM Length L Ch R = 1 ,92767   ,1585,1585,1585
BEGIN DESCRIPTION:
HURRICANE BAYOU 58.0
END DESCRIPTION:
XS GIS Cut Line= 3
      3802453.92     10484567.59      3800926.16     10488222.07
      3798247.34     10494159.57
#Sta/Elev= 30
  1798.9  283.23  2008.8  274.86  2246.1  258.86  2522.8  247.82    3013   243.9
  3018.4  241.66  3102.4  241.48  3148.2  245.08  3219.6  240.85  3407.9  239.03
  4977.4  240.99  4999.1  233.25  5010.7  232.66  5013.5  232.16  5016.7  232.66
  5020.8  237.31  5031.6   241.4  5801.7  236.37  6859.1   235.6  7245.6  235.83
  7926.1  241.93  9287.2     241 10457.7  263.74 10595.9  271.08 10738.5  284.39
 10965.3  313.17 11011.6  316.34 11720.7  332.18   12044  344.83 12273.7   345.1
#Mann= 4 ,-1 , 0
  1798.9     .16       0  5010.7     .07       0  5016.7     .16       0
 12273.7     .05       0
#XS Ineff= 2 , 0
         4486.36  316.88 5153.54          331.62
Permanent Ineff=
       F       F
Bank Sta=4977.4,5031.6
XS Rating Curve= 0 ,0
Exp/Cntr=0.3,0.1

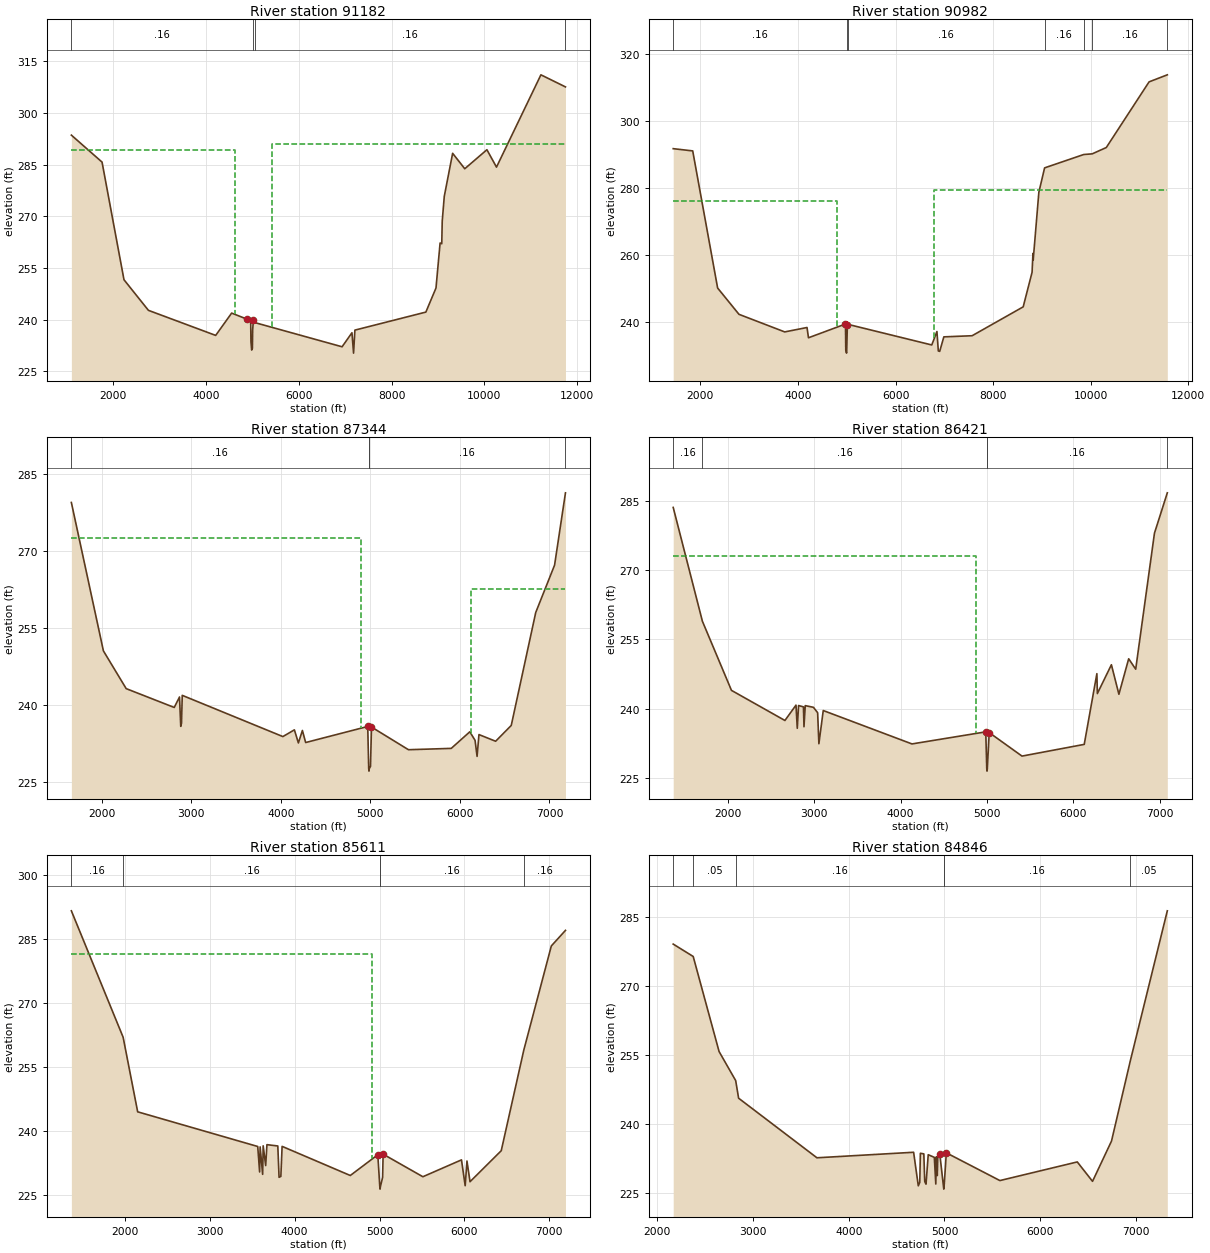
Type RM Length L Ch R = 1 ,91182   ,200,200,200
BEGIN DESCRIPTION:
Mapping XS 1c510059
END DESCRIPTION:
XS GIS Cut Line= 6
      3802642.72      10484159.6      3801655.32     10485494.21
      3800950.03     10486817.99      3799029.46     10488087.53
      3797488.66     10489617.47      3794689.18     10490713.39
#Sta/Elev= 30
  1100.6  293.54  1761.7  285.72  2234.6   251.6  2760.9  242.73  4210.5  235.46
  4554.7  241.93  4891.8  240.14  4964.8   239.5  4970.7  233.63    4986  231.21
  5001.2  231.72  5007.2  236.94  5022.4  239.88    5058  239.16  6934.4  232.16
    7147  236.23  7181.9  230.32  7210.5  236.99  8739.7  242.22  8958.1  249.21
  9046.6  262.27  9082.2  262.04  9092.3  268.59  9136.6  275.79  9316.5  288.27
  9578.1  283.79 10055.1  289.31 10261.7  284.26 11219.1  311.03 11748.1  307.53
#Mann= 4 ,-1 , 0
  1100.6     .16       0  5007.2     .07       0    5058     .16       0
 11748.1     .05       0
#XS Ineff= 2 , 0
         4622.73  289.33 5413.64          290.98
Permanent Ineff=
       F       F
Bank Sta=4891.8,5022.4
XS Rating Curve= 0 ,0
Exp/Cntr=0.3,0.1

Type RM Length L Ch R = 1 ,90982   ,3638,3638,3638
BEGIN DESCRIPTION:
HURRICANE BAYOU 57.0
END DESCRIPTION:
XS GIS Cut Line= 6
      3802189.29     10484288.87      3800689.27     10486747.25
      3800316.35     10487097.94      3798849.33      10487922.6
      3797321.56     10489511.14      3794656.58      10490518.1
#Sta/Elev= 30
  1442.3  291.66  1842.1  290.99  2352.7  250.01  2790.2  242.15  3728.2  236.89
    4185  238.21  4215.1  235.14  4973.7  239.25  4979.4  231.42  4995.3  230.55
  4998.5  231.05  5011.7  238.84    5024  239.15  6741.9  232.99    6848  237.01
  6876.3  231.21  6904.7  231.07  6989.7  235.41  7569.5  235.75  8616.1  244.38
  8798.3  254.72  8816.1  260.37  8821.4  258.41  8937.3  278.64  9055.1  285.92
  9856.7  289.91 10031.1  290.11 10319.5     292 11196.3  311.62 11570.3  313.73
#Mann= 7 ,-1 , 0
  1442.3     .16       0  4998.5     .05       0    5024     .16       0
  9055.1     .16       0  9856.7     .05       0 10031.1     .16       0
 11570.3     .05       0
#XS Ineff= 2 , 0
            4800  276.15 6797.73          279.32
Permanent Ineff=
       F       F
Bank Sta=4973.7,5011.7
XS Rating Curve= 0 ,0
Exp/Cntr=0.3,0.1

Type RM Length L Ch R = 1 ,87344   ,923,923,923
BEGIN DESCRIPTION:
HURRICANE BAYOU 56.0
END DESCRIPTION:
XS GIS Cut Line= 3
       3799599.6      10484110.2      3798099.61     10487110.19
      3796899.62     10488910.17
#Sta/Elev= 30
  1661.9  279.47  2019.7  250.56    2274  243.21  2810.7  239.54  2869.4  241.58
  2883.3  235.86  2891.7  236.48  2900.1   241.9  4023.7  233.87  4152.3  235.18
    4197  232.63  4241.7  235.06  4278.1  232.71  4971.3  235.84  4982.2  227.64
    4985  227.14  4988.2  227.64    5002  228.04  5013.2  235.73  5426.1  231.31
  5903.9  231.57  6111.2   234.8  6169.8  233.14  6192.3  230.01  6213.3  234.26
  6399.6  232.96  6573.9  236.04  6847.3  258.04  7057.6  267.26  7179.3  281.35
#Mann= 4 ,-1 , 0
  1661.9     .16       0  4982.2     .07       0  4988.2     .16       0
  7179.3     .05       0
#XS Ineff= 2 , 0
         4899.61   272.5  6126.7          262.67
Permanent Ineff=
       F       F
Bank Sta=4971.3,5013.2
XS Rating Curve= 0 ,0
Exp/Cntr=0.3,0.1

Type RM Length L Ch R = 1 ,86421   ,810,810,810
BEGIN DESCRIPTION:
HURRICANE BAYOU 55.0
END DESCRIPTION:
XS GIS Cut Line= 3
      3799599.63     10484010.15      3797499.61     10487010.19
      3796499.63     10488810.16
#Sta/Elev= 30
  1367.9  283.52  1705.8  258.92  2042.4  243.97  2661.4  237.46  2789.6  240.78
  2804.4  235.77  2819.2  240.69  2875.9   240.4    2882  236.11  2896.8  240.67
  2991.4  240.31  3040.2  239.14  3054.6  232.43  3105.2  239.61  4132.3  232.39
  4986.8     235  4998.6  227.01  5001.3  226.51  5004.6  227.01  5026.9  234.84
  5406.3  229.76    6127  232.29  6273.4  247.58  6279.1  243.28  6441.6  249.51
  6528.5  243.13  6641.7   250.8    6723  248.55  6940.3  277.96    7089  286.68
#Mann= 5 ,-1 , 0
  1367.9     .16       0  1705.8     .16       0  4998.6     .07       0
  5004.6     .16       0    7089     .16       0
#XS Ineff= 2 , 0
         4872.05  273.09
Permanent Ineff=
       F       F
Bank Sta=4986.8,5026.9
XS Rating Curve= 0 ,0
Exp/Cntr=0.3,0.1

Type RM Length L Ch R = 1 ,85611   ,765,765,765
BEGIN DESCRIPTION:
HURRICANE BAYOU 54.0
END DESCRIPTION:
XS GIS Cut Line= 3
      3799149.61     10483660.18      3797049.61     10486660.19
      3795849.61     10488460.19
#Sta/Elev= 30
  1367.2  291.65  1977.5  261.97  2148.9  244.46  3564.4  236.32  3586.6  230.34
  3592.7  236.23  3622.4  229.78  3628.5  236.48  3658.1  231.84  3672.9  236.75
  3801.1  236.44  3815.9  229.08  3836.9  229.29  3851.7  236.35  4655.6  229.51
  4979.9  234.38  5003.9  226.81  5006.7  226.31  5009.9  226.81  5036.7  229.08
  5042.7  234.52  5511.4  229.22  5966.6  233.18  6010.2  227.11  6031.2  232.91
  6067.3  228.05  6435.3  235.33  6701.2  258.95  7025.7   283.4  7192.5  287.06
#Mann= 5 ,-1 , 0
  1367.2     .16       0  1977.5     .16       0  5003.9     .07       0
  5009.9     .16       0  6701.2     .16       0
#XS Ineff= 2 , 0
         4913.39  281.62
Permanent Ineff=
       F       F
Bank Sta=4979.9,5042.7
XS Rating Curve= 0 ,0
Exp/Cntr=0.3,0.1

Type RM Length L Ch R = 1 ,84846   ,808,808,808
BEGIN DESCRIPTION:
HURRICANE BAYOU 53.0
END DESCRIPTION:
XS GIS Cut Line= 3
      3798149.59     10483760.21      3796649.61     10486160.19
      3795449.63     10488160.15
#Sta/Elev= 30
    2166  279.11  2374.8  276.42  2645.3  255.76  2818.7  249.45  2849.3  245.62
  3667.7  232.67  4677.8  233.87  4726.7  226.58    4742  227.32  4748.5  233.65
  4784.5  233.52  4793.9  227.52  4807.5  226.94  4830.5  233.34  4894.2  232.76
  4909.5  226.97  4915.4  232.89  4924.8   228.8  4930.7  233.25  4951.9  233.39
  4990.2  226.36    4993  225.86  4996.2  226.36  5019.5  233.75  5579.3  227.72
  6387.8  231.77  6547.2  227.55  6745.4   236.3  6943.7  253.89  7328.5  286.34
#Mann= 6 ,-1 , 0
    2166     .16       0  2374.8     .05       0  2818.7     .16       0
  4990.2     .07       0  4996.2     .16       0  6943.7     .05       0
Bank Sta=4951.9,5019.5
XS Rating Curve= 0 ,0
Exp/Cntr=0.3,0.1

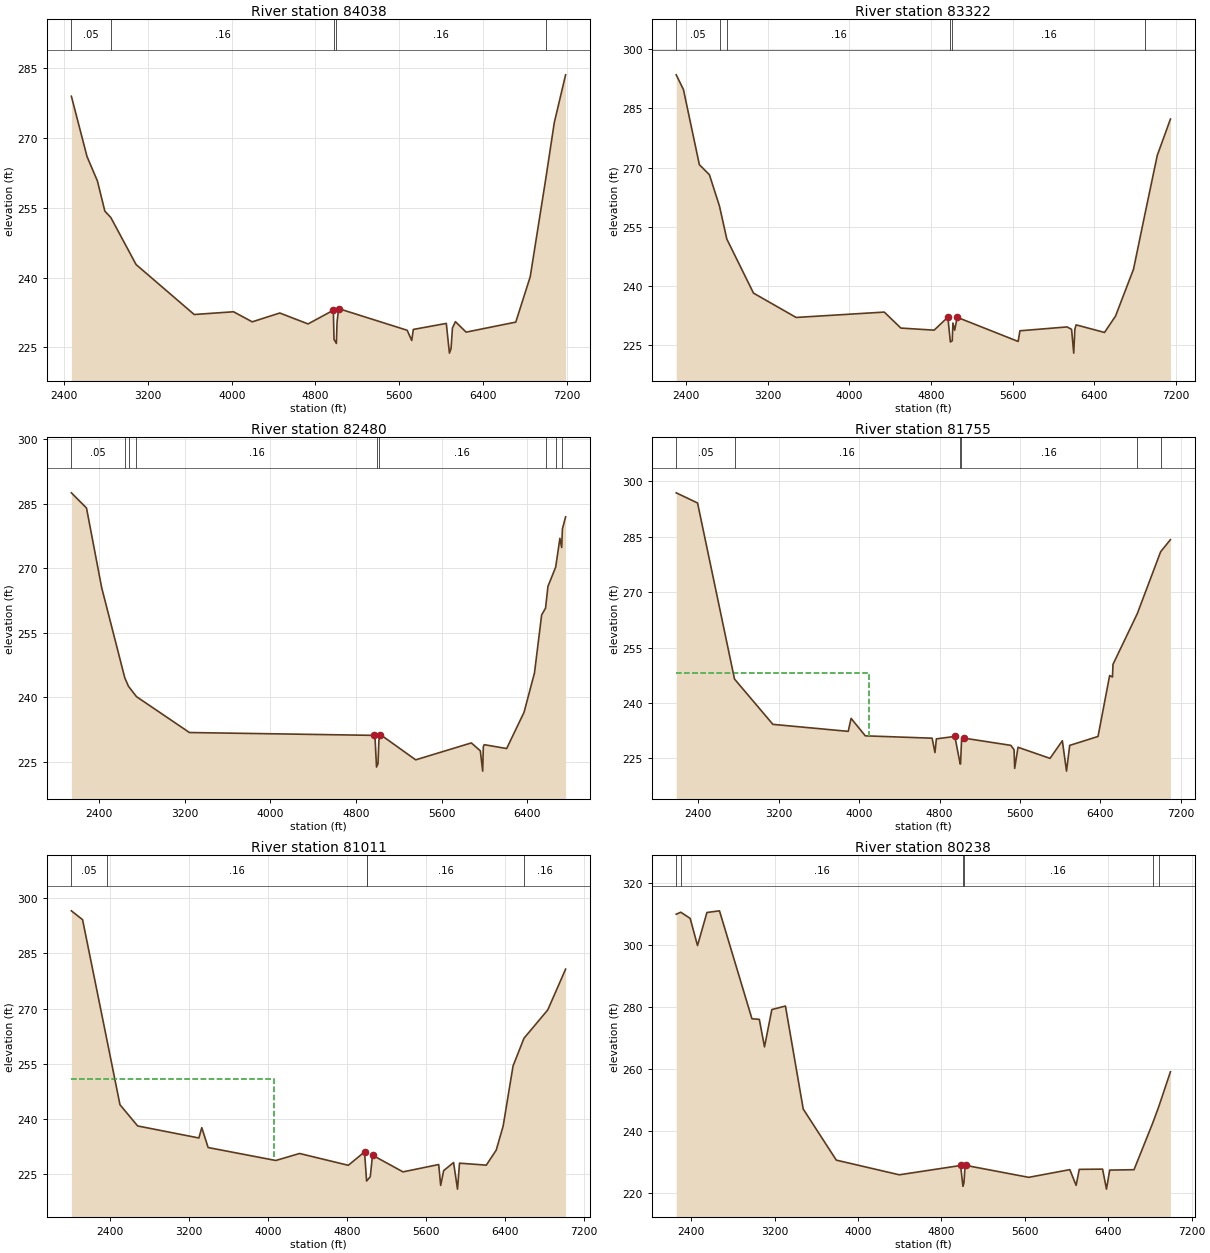
Type RM Length L Ch R = 1 ,84038   ,716,716,716
BEGIN DESCRIPTION:
HURRICANE BAYOU 52.0
END DESCRIPTION:
XS GIS Cut Line= 3
       3797899.6      10483960.2      3796299.61     10485960.19
      3795099.59     10487760.21
#Sta/Elev= 30
  2466.5  278.87  2616.2  265.93  2715.4   260.7  2786.6  254.23  2843.5  252.87
  3085.2  242.78  3640.7  232.07  4016.8  232.66  4195.3   230.5  4458.7  232.39
  4729.2  230.05  4970.9  232.99  4977.3  226.75  4999.7  225.87  5006.1  230.36
  5020.5  233.34  5676.7  228.69  5720.3   226.5  5735.3  228.87  6050.8  230.16
  6080.6  223.79  6095.9  224.73  6109.4  229.17  6137.9  230.54  6240.1  228.29
  6714.8  230.44  6853.1  240.18  7003.3  261.43  7082.9   273.2  7191.1  283.46
#Mann= 5 ,-1 , 0
  2466.5     .05       0  2843.5     .16       0  4977.3     .07       0
  4999.7     .16       0  7003.3     .05       0
Bank Sta=4970.9,5020.5
XS Rating Curve= 0 ,0
Exp/Cntr=0.3,0.1

Type RM Length L Ch R = 1 ,83322   ,842,842,842
BEGIN DESCRIPTION:
HURRICANE BAYOU 51.0
END DESCRIPTION:
XS GIS Cut Line= 3
      3797599.63     10483760.17      3795799.61     10485760.19
      3794999.62     10487760.17
#Sta/Elev= 30
  2302.3  293.49    2373  289.77  2529.2  270.72  2627.8  268.17  2726.7  260.19
  2798.2  251.88  3059.8  238.18  3477.7  232.01  4341.7  233.37  4504.6  229.32
  4830.5  228.79    4965  232.08  4989.7  225.79  5007.9  226.09  5014.6   230.6
  5032.1  228.77  5056.3  232.05  5654.1  225.93  5671.6  228.63  6133.4  229.61
  6177.8     229  6199.1  222.97  6210.1     229  6222.2  230.13  6500.9  228.21
  6608.6  232.35    6785  244.23  6899.4  258.49  7017.9  273.07  7147.1  282.28
#Mann= 6 ,-1 , 0
  2302.3     .05       0  2726.7      .1       0  2798.2     .16       0
  4989.7     .07       0  5007.9     .16       0  6899.4     .16       0
Bank Sta=4965,5056.3
XS Rating Curve= 0 ,0
Exp/Cntr=0.3,0.1

Type RM Length L Ch R = 1 ,82480   ,725,725,725
BEGIN DESCRIPTION:
HURRICANE BAYOU 50.0
END DESCRIPTION:
XS GIS Cut Line= 3
      3797399.59     10483760.21      3795399.61     10485760.19
      3794599.59     10487360.23
#Sta/Elev= 30
    2142  287.57  2283.4  284.03  2424.8  265.52    2641  244.49  2675.7  242.51
  2750.1  240.11  3245.1  231.75  4966.9  231.09  4978.8  230.64  4992.8   223.7
  5006.7  224.51  5015.1  229.94  5029.1  231.27  5358.9  225.39  5878.8  229.33
  5962.7  227.49  5984.8  222.76  5990.6  228.43    5999  228.92  6208.6  228.02
  6370.7  236.44  6468.6  245.62  6535.6  259.15    6572  260.71  6594.3  265.77
  6666.9  270.29  6706.1  276.98  6722.9  274.84  6729.3  279.13  6759.3  281.98
#Mann= 9 ,-1 , 0
    2142     .05       0    2641      .1       0  2675.7     .05       0
  2750.1     .16       0  4992.8     .07       0  5015.1     .16       0
    6572     .05       0  6666.9     .16       0  6729.3     .05       0
Bank Sta=4966.9,5029.1
XS Rating Curve= 0 ,0
Exp/Cntr=0.3,0.1

Type RM Length L Ch R = 1 ,81755   ,744,744,744
BEGIN DESCRIPTION:
HURRICANE BAYOU 49.0
END DESCRIPTION:
XS GIS Cut Line= 3
      3796899.63     10483310.17      3794899.61     10485310.19
      3794299.61     10487310.18
#Sta/Elev= 30
  2180.9  296.92  2393.1  294.17  2760.8  246.48  3142.6  234.21  3892.1  232.31
  3920.4  235.83  4061.8   231.1  4726.5  230.46  4754.8  226.57  4768.9  230.28
  4952.8  230.94  5005.8  223.47  5009.4  223.47  5019.8  230.25  5040.7  230.49
  5509.6  228.52  5541.8  227.34  5547.9  222.28    5581     228  5899.4     225
  6022.1  229.77  6063.6  221.54  6095.1  228.51    6377  230.93  6492.7  247.44
  6520.6  247.03  6525.8  250.45  6767.7   264.2  6999.9  280.97  7097.4  284.24
#Mann= 6 ,-1 , 0
  2180.9     .05       0  2760.8     .16       0  5005.8     .07       0
  5009.4     .16       0  6767.7     .16       0  6999.9     .05       0
#XS Ineff= 2 , 0
            4100  248.19
Permanent Ineff=
       F       F
Bank Sta=4952.8,5040.7
XS Rating Curve= 0 ,0
Exp/Cntr=0.3,0.1

Type RM Length L Ch R = 1 ,81011   ,773,773,773
BEGIN DESCRIPTION:
HURRICANE BAYOU 48.0
END DESCRIPTION:
XS GIS Cut Line= 3
      3796749.59      10483310.2      3794349.61     10485110.19
       3794149.6     10487110.23
#Sta/Elev= 30
  2007.2  296.57  2120.7  294.17  2370.7  261.05  2499.9  243.84  2679.1  238.07
  3299.9   234.8  3329.1  237.61  3393.6   232.2  4079.1  228.68  4320.7  230.58
  4814.5  227.37  4979.1  231.01  4999.9  223.09  5004.1  223.24  5037.3  224.27
  5059.9  230.12    5369  225.58  5730.8  227.58  5750.9   221.9    5781  225.92
  5881.5  228.12  5921.5  220.89  5941.8  227.95  6213.2  227.41  6313.7  231.49
    6384  238.02  6484.5  254.38  6595.1  261.91  6836.3  269.62  7017.2  280.71
#Mann= 5 ,-1 , 0
  2007.2     .05       0  2370.7     .16       0  4999.9     .07       0
  5004.1     .16       0  6595.1     .16       0
#XS Ineff= 2 , 0
          4062.5  250.93
Permanent Ineff=
       F       F
Bank Sta=4979.1,5059.9
XS Rating Curve= 0 ,0
Exp/Cntr=0.3,0.1

Type RM Length L Ch R = 1 ,80238   ,1474,1474,1474
BEGIN DESCRIPTION:
HURRICANE BAYOU 47.0
END DESCRIPTION:
XS GIS Cut Line= 4
      3794233.86     10482036.91      3794099.61     10483566.89
      3794099.61     10484760.19      3793899.61     10486760.16
#Sta/Elev= 30
  2256.9  310.03  2300.3  310.68  2390.7  308.69    2461  299.91  2551.3  310.59
  2671.8  311.13    2983  276.25  3053.7  276.05  3103.4  267.17  3173.7  279.22
  3304.2  280.36  3474.8  247.07  3791.9  230.56  4396.1  225.82  4983.6  228.83
  5006.2  222.11  5016.2  223.26  5026.3  228.67  5038.8  228.83  5636.8     225
  6031.2  227.49  6091.5  222.41  6121.7  227.58  6345.3  227.65  6382.7  221.19
  6413.1  227.34  6646.8  227.47  6825.2  242.48    6882  247.65    6996  259.12
#Mann= 6 ,-1 , 0
  2256.9     .05       0  2300.3     .16       0  5006.2     .07       0
  5016.2     .16       0  6825.2     .12       0    6882     .16       0
Bank Sta=4983.6,5038.8
XS Rating Curve= 0 ,0
Exp/Cntr=0.3,0.1