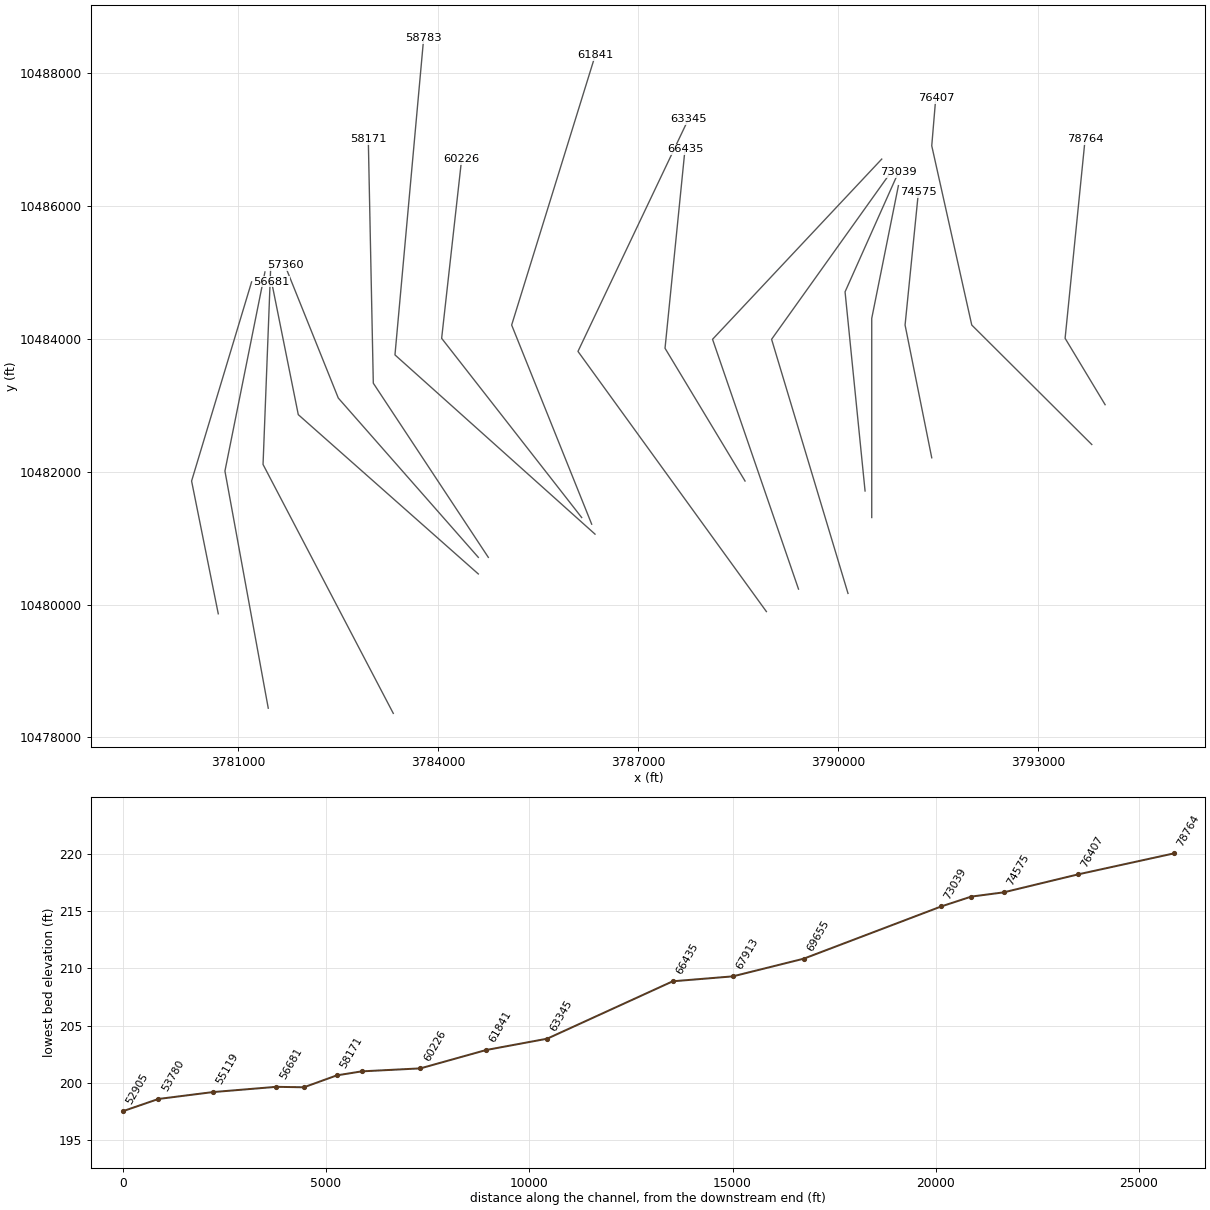
HEC-RAS study HURRICANE BAYOU.prj: HURRICANE BAYOU Base Level Engineering

--- HURRICANE BAYOU.g01 (geometry) --- (continued)

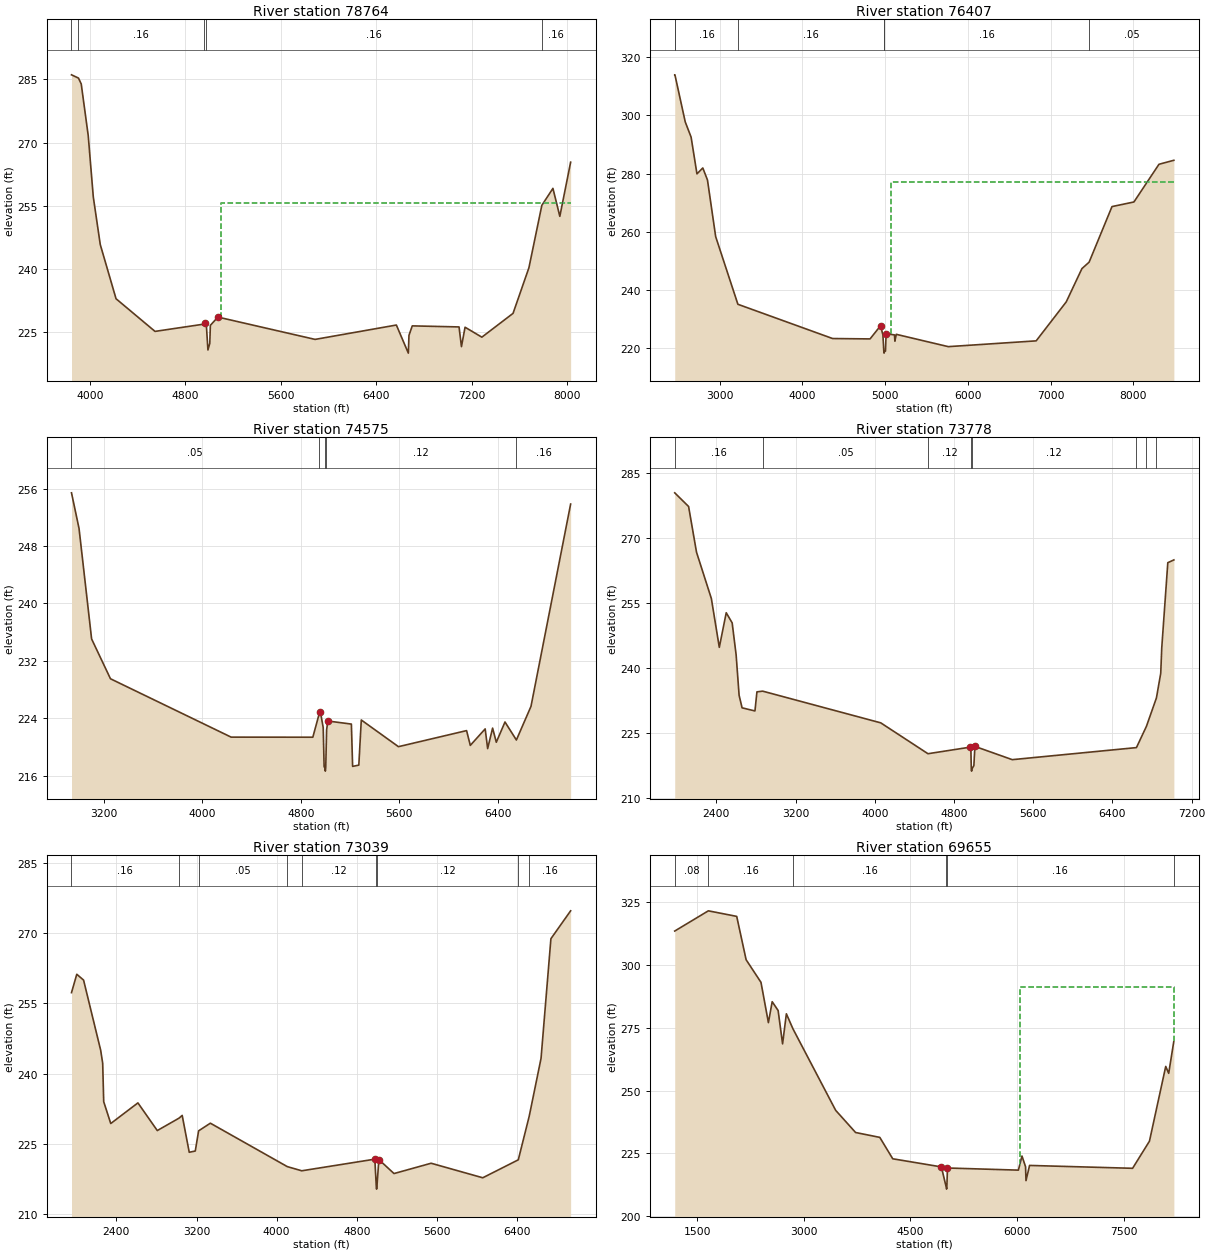
Type RM Length L Ch R = 1 ,78764   ,2357,2357,2357
BEGIN DESCRIPTION:
HURRICANE BAYOU 46.0
END DESCRIPTION:
XS GIS Cut Line= 3
      3793999.62     10483010.18      3793399.61     10484010.19
      3793699.61     10487010.22
#Sta/Elev= 30
  3845.4   286.1  3903.7  285.33    3927  283.93  3985.4  271.69  4028.1  257.08
  4086.4   245.8  4218.6  232.93  4545.1  225.18  4953.3   226.9  4961.1  227.12
  4974.5  226.96  4988.3  220.77  5003.8  222.32  5008.7  226.62  5071.9  228.58
  5885.9  223.28  6566.8  226.69  6667.1  220.02  6672.3  224.23    6700  226.49
  7091.9  226.24    7112  221.56  7142.2  226.17  7282.9  223.81  7544.2  229.46
  7677.3   240.3  7785.4  255.11  7878.3  259.14  7936.1   252.5  8026.6  265.36
#Mann= 5 ,-1 , 0
  3845.4     .16       0  3903.7     .16       0  4953.3     .05       0
  4974.5     .16       0  7785.4     .16       0
#XS Ineff= 2 , 0
                         5095.67          255.61
Permanent Ineff=
       F       F
Bank Sta=4961.1,5071.9
XS Rating Curve= 0 ,0
Exp/Cntr=0.3,0.1

Type RM Length L Ch R = 1 ,76407   ,1832,1832,1832
BEGIN DESCRIPTION:
HURRICANE BAYOU 45.0
END DESCRIPTION:
XS GIS Cut Line= 4
      3793799.63     10482410.17      3791999.61     10484210.19
      3791399.61     10486910.19       3791459.9      10487631.4
#Sta/Elev= 30
  2456.5  313.97  2458.8  313.97  2583.8  297.74  2654.5  292.53  2725.2  279.88
  2795.9  281.92  2852.5  277.77  2951.5  258.29  3220.2     235  4365.7  223.21
  4818.3  223.08  4945.5  227.64  4973.8  224.41    4985  218.69  4987.7  218.19
    4991  218.69  5004.7  218.89  5012.4  224.87  5113.5  224.46  5118.6   222.3
  5135.3  224.66    5764  220.42  6826.8  222.41  7190.5  235.83    7380  247.28
  7467.1   249.5  7743.6  268.62  8008.8  270.21  8311.5  283.18  8491.7  284.56
#Mann= 6 ,-1 , 0
  2456.5     .05       0  2458.8     .16       0  3220.2     .16       0
    4985     .07       0    4991     .16       0  7467.1     .05       0
#XS Ineff= 2 , 0
                         5073.39           277.1
Permanent Ineff=
       F       F
Bank Sta=4945.5,5012.4
XS Rating Curve= 0 ,0
Exp/Cntr=0.3,0.1

Type RM Length L Ch R = 1 ,74575   ,797,797,797
BEGIN DESCRIPTION:
HURRICANE BAYOU 44.0
END DESCRIPTION:
XS GIS Cut Line= 3
      3791399.61     10482210.16      3790999.61     10484210.19
      3791199.61     10486210.18
#Sta/Elev= 30
  2940.2  255.43  3001.4  250.46  3103.4  235.05  3256.4   229.5  4235.4  221.36
  4898.2  221.35  4948.8  224.55  4959.4  224.92  4982.3  222.69  4989.9   217.2
  4996.9  217.12  4999.7  216.62  5002.9  217.12    5010  222.38    5020  223.61
    5211  223.18    5221  217.28  5271.3  217.46  5291.4  223.75  5592.9  220.03
  6145.6  222.27  6175.8  220.21  6296.4  222.51  6316.5  219.76  6356.7  222.62
  6386.8  220.65  6457.2  223.47  6549.7  220.96  6668.2  225.65  6989.8  253.86
#Mann= 5 ,-1 , 0
  2940.2     .05       0  4948.8     .12       0  4996.9     .07       0
  5002.9     .12       0  6549.7     .16       0
Bank Sta=4959.4,5020
XS Rating Curve= 0 ,0
Exp/Cntr=0.3,0.1

Type RM Length L Ch R = 1 ,73778   ,739,739,739
BEGIN DESCRIPTION:
HURRICANE BAYOU 43.0
END DESCRIPTION:
XS GIS Cut Line= 3
      3790499.61     10481310.21      3790499.61     10484310.19
      3790899.61      10486310.2
#Sta/Elev= 30
  1980.2  280.35  2120.2   277.2  2200.2  266.67  2350.2  255.99  2430.2  244.76
  2500.2  252.73  2560.2  250.39  2600.2  243.01  2630.2  233.71  2660.2  230.83
  2790.2  230.11  2810.2  234.51  2868.4  234.67  4060.2  227.37  4537.1  220.26
  4960.2  221.76  4970.2  221.36  4974.7  216.75  4977.4  216.25  4980.7  216.75
  5000.6  217.52  5010.8  221.95  5388.1  218.89    6642  221.67  6742.8  226.57
  6843.7  233.11  6887.2  238.79  6897.4  244.61  6958.6  264.26  7019.8   264.9
#Mann= 8 ,-1 , 0
  1980.2     .16       0  2868.4     .05       0  4537.1     .12       0
  4974.7     .07       0  4980.7     .12       0    6642     .16       0
  6742.8     .05       0  6843.7     .16       0
Bank Sta=4960.2,5010.8
XS Rating Curve= 0 ,0
Exp/Cntr=0.3,0.1

Type RM Length L Ch R = 1 ,73039   ,3384,3384,3384
BEGIN DESCRIPTION:
HURRICANE BAYOU 42.0
END DESCRIPTION:
XS GIS Cut Line= 3
      3790399.61     10481710.17      3790099.61     10484710.19
      3790899.63     10486510.23
#Sta/Elev= 30
  1951.3  257.29  2004.1  261.21  2071.9  259.97  2242.8     245  2262.9  242.21
  2272.9  234.04  2343.3  229.38  2614.6  233.78  2808.1  227.88  3025.7  230.53
  3056.8  231.11  3127.2  223.25  3187.5  223.52  3220.8  227.82  3338.2  229.45
  4106.4  220.19  4250.8   219.3  4980.6  221.78  4995.4  215.89  4998.2  215.39
  5001.4  215.89    5021  221.69  5172.2  218.71  5542.9  220.91  6058.5  217.81
  6413.4  221.64  6522.6  230.95  6640.6  243.28  6739.1  268.79  6936.1  274.74
#Mann= 9 ,-1 , 0
  1951.3     .16       0  3025.7     .12       0  3220.8     .05       0
  4106.4     .16       0  4250.8     .12       0  4995.4     .07       0
  5001.4     .12       0  6413.4     .05       0  6522.6     .16       0
Bank Sta=4980.6,5021
XS Rating Curve= 0 ,0
Exp/Cntr=0.3,0.1

Type RM Length L Ch R = 1 ,69655   ,1742,1742,1742
BEGIN DESCRIPTION:
HURRICANE BAYOU 41.0
END DESCRIPTION:
XS GIS Cut Line= 3
      3790143.66     10480167.06      3788997.83     10483995.19
      3790749.61     10486460.19
#Sta/Elev= 30
  1186.2  313.43  1659.2  321.47  2057.9  319.26  2190.3  302.02  2399.3  293.04
  2503.8  277.02  2556.9  285.34  2640.4  281.84    2703  268.58  2756.3  280.53
  2849.2  274.54  3449.5  242.16  3729.9  233.34  4070.4   231.4  4252.4  222.89
  4936.8  219.66  5006.9  211.33  5009.6  210.83  5012.9  211.33  5022.3  219.23
  6019.4  218.38  6069.8  223.99  6120.3  219.73  6126.4  214.21  6176.8  220.25
  7625.7  219.11  7862.7  229.88  8091.8  259.61  8133.6  256.87  8206.2  269.73
#Mann= 6 ,-1 , 0
  1186.2     .08       0  1659.2     .16       0  2849.2     .16       0
  5006.9     .07       0  5012.9     .16       0  8206.2     .16       0
#XS Ineff= 2 , 0
                         6039.37          291.05
Permanent Ineff=
       F       F
Bank Sta=4936.8,5022.3
XS Rating Curve= 0 ,0
Exp/Cntr=0.3,0.1

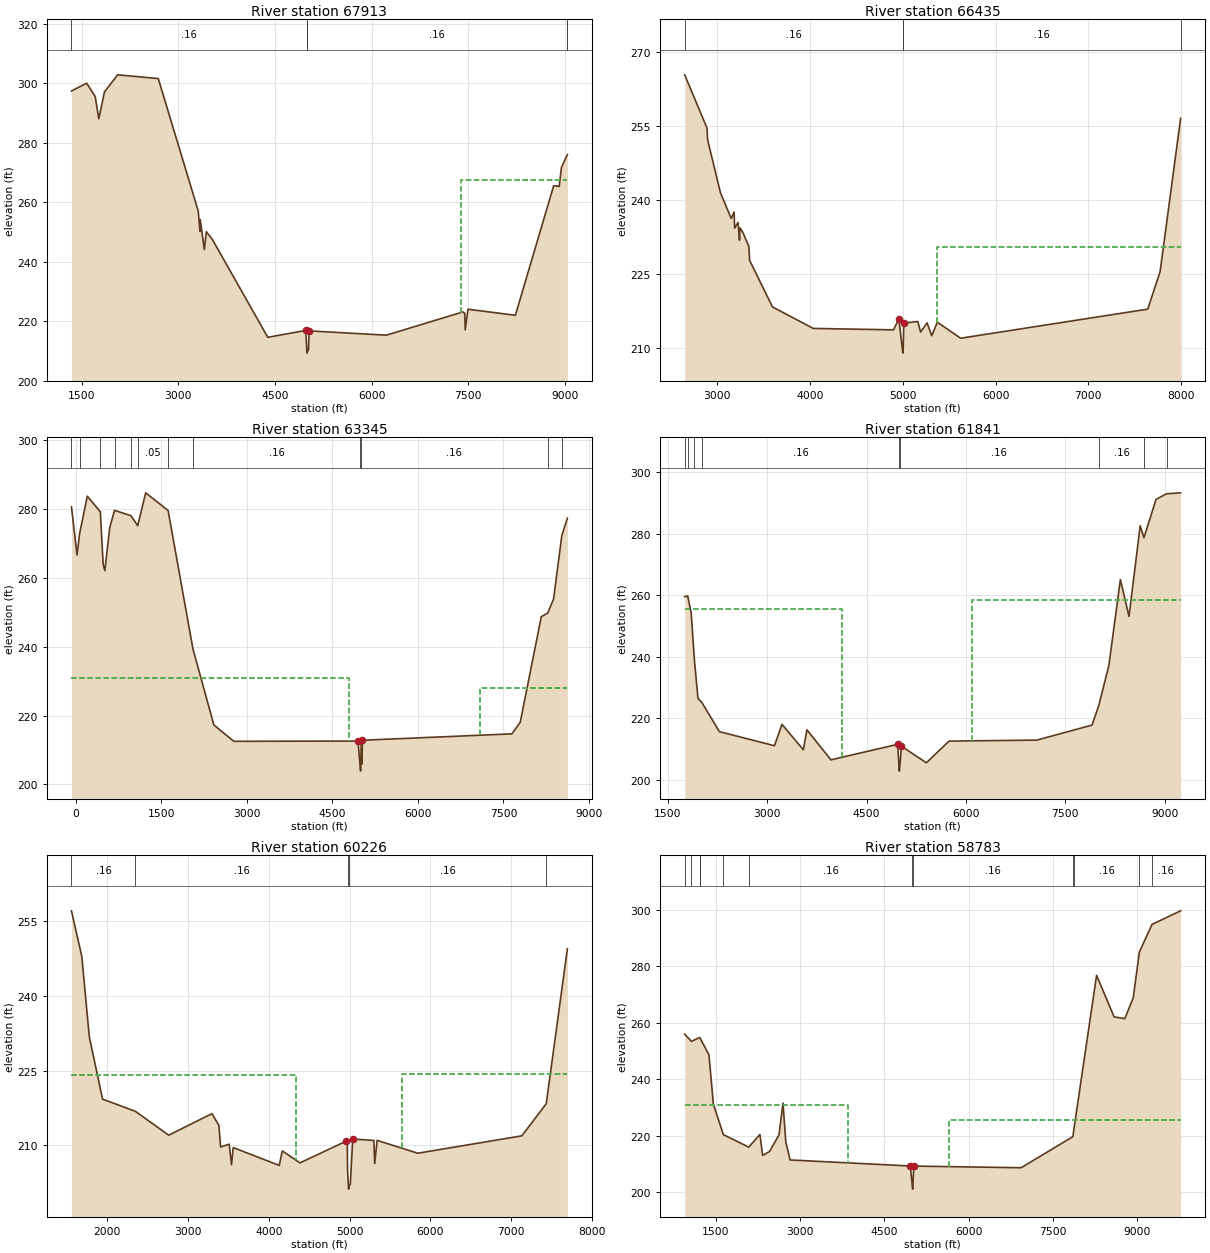
Type RM Length L Ch R = 1 ,67913   ,1478,1478,1478
BEGIN DESCRIPTION:
HURRICANE BAYOU 40.0
END DESCRIPTION:
XS GIS Cut Line= 3
      3789401.47     10480232.19      3788112.41     10483995.19
      3790649.64     10486710.22
#Sta/Elev= 30
  1342.5  297.46  1578.9  300.06  1710.3  295.62  1766.6  288.12  1855.2  297.15
  2059.2  302.88  2689.3  301.62  3309.7  257.06  3335.7  250.23    3341  254.21
  3403.6  244.14  3434.9  250.13  3528.7   247.5  4388.8  214.61  4977.9  216.93
  4994.8  209.79  4997.5  209.29  5000.8  209.79  5018.9  210.24  5029.5  216.77
  6227.5  215.33    7416  223.15  7444.3  222.67  7451.2  217.12  7493.7  224.05
  8229.4  222.02  8823.9   265.6  8908.9  265.36  8944.1  271.72  9036.2  276.07
#Mann= 5 ,-1 , 0
  1342.5     .16       0  4994.8     .07       0  5000.8     .16       0
  9036.2     .16       0  9036.2     .16       0
#XS Ineff= 2 , 0
                         7381.89           267.5
Permanent Ineff=
       F       F
Bank Sta=4977.9,5029.5
XS Rating Curve= 0 ,0
Exp/Cntr=0.3,0.1

Type RM Length L Ch R = 1 ,66435   ,3090,3090,3090
BEGIN DESCRIPTION:
HURRICANE BAYOU 39.0
END DESCRIPTION:
XS GIS Cut Line= 3
      3788599.59     10481860.22      3787399.61     10483860.19
      3787699.61     10486860.18
#Sta/Elev= 30
  2648.2  265.29  2889.2  254.48    2895  252.16    3033  241.43  3149.6  236.17
  3180.7  237.48  3186.6  234.21  3223.5  235.36    3239  231.76  3244.9  234.26
    3276  233.33  3340.1  230.46  3347.9  227.68  3594.7  218.23    4034  213.87
  4898.9  213.58  4957.2  215.76  4997.6  209.36  5000.4  208.86  5003.6  209.36
  5010.7  214.94  5161.4  215.28  5191.6  213.13  5261.9     215  5312.2  212.39
  5372.5  215.13  5623.7  211.88  7641.2  217.78  7774.4   225.4  7995.5  256.47
#Mann= 4 ,-1 , 0
  2648.2     .16       0  4997.6     .07       0  5003.6     .16       0
  7995.5     .16       0
#XS Ineff= 2 , 0
                         5368.18          230.34
Permanent Ineff=
       F       F
Bank Sta=4957.2,5010.7
XS Rating Curve= 0 ,0
Exp/Cntr=0.3,0.1

Type RM Length L Ch R = 1 ,63345   ,1504,1504,1504
BEGIN DESCRIPTION:
HURRICANE BAYOU 38.0
END DESCRIPTION:
XS GIS Cut Line= 3
      3788919.72     10479893.61      3786094.18      10483812.9
       3787749.6     10487310.17
#Sta/Elev= 30
   -79.6  280.59    17.8  266.62    65.8  273.04   198.2   283.7     427  279.16
   476.7  263.94   506.1  262.05     592  274.58   676.3  279.59   964.7  278.02
  1082.4  275.12  1222.7  284.67  1615.9  279.54  2052.3   239.3  2418.7  217.26
  2768.9  212.51  4948.2  212.58  4989.4  204.35  4992.2  203.85  4995.4  204.35
  5009.6     213  5015.1  205.89  5025.6  212.82  7646.7  214.67  7794.3  218.04
  8163.9  248.71  8277.6  249.76  8379.7  253.89  8524.3  272.31  8621.3  277.31
#Mann= 12 ,-1 , 0
   -79.6     .16       0    65.8     .05       0     427     .16       0
   676.3     .05       0   964.7     .05       0  1082.4     .05       0
  1615.9     .16       0  2052.3     .16       0  4989.4     .07       0
  4995.4     .16       0  8277.6     .16       0  8524.3     .05       0
#XS Ineff= 2 , 0
         4790.91   230.8 7081.82          227.88
Permanent Ineff=
       F       F
Bank Sta=4948.2,5009.6
XS Rating Curve= 0 ,0
Exp/Cntr=0.3,0.1

Type RM Length L Ch R = 1 ,61841   ,1615,1615,1615
BEGIN DESCRIPTION:
HURRICANE BAYOU 37.0
END DESCRIPTION:
XS GIS Cut Line= 3
      3786299.61      10481210.2      3785099.61     10484210.19
       3786354.6     10488279.05
#Sta/Elev= 30
  1752.2   259.5    1797  259.82  1850.5   254.2  1899.8  238.67  1952.8   226.5
    2012  225.15  2275.9  215.69  3107.9  211.11    3221  218.06  3544.1   209.8
    3598  216.29  3960.1  206.53  4968.5  211.56  4990.8  203.36  4993.5  202.86
  4996.8  203.36  5025.1  210.94  5401.9  205.58  5744.3  212.61  7070.5  212.94
    7903  217.81  8006.5  224.23  8157.5  237.14    8332  265.09  8461.9  253.11
  8630.5  282.53  8687.9   278.7  8869.5  291.11  9029.6  292.97  9241.3  293.26
#Mann= 9 ,-1 , 0
  1752.2     .16       0    1797     .12       0  1899.8     .16       0
    2012     .16       0  4990.8     .07       0  4996.8     .16       0
  8006.5     .16       0  8687.9     .16       0  9029.6     .05       0
#XS Ineff= 2 , 0
         4129.55  255.51 6093.18          258.56
Permanent Ineff=
       F       F
Bank Sta=4968.5,5025.1
XS Rating Curve= 0 ,0
Exp/Cntr=0.3,0.1

Type RM Length L Ch R = 1 ,60226   ,1443,1443,1443
BEGIN DESCRIPTION:
HURRICANE BAYOU 36.0
END DESCRIPTION:
XS GIS Cut Line= 3
       3786149.6     10481310.21      3784049.61     10484010.19
      3784349.61     10486710.17
#Sta/Elev= 30
  1558.7  256.98  1686.3  247.89  1779.5  231.76  1943.3  219.28  2349.6  216.84
  2762.2  212.06    3297  216.37    3383  214.03  3404.7  209.69  3510.5  210.27
  3539.5  206.17  3560.3  209.58  4130.4  206.01  4167.5  208.91  4387.4  206.52
  4957.5  210.86    4972  210.43    4976  204.88  4986.3  201.76    4989  201.26
  4992.3  201.76  5009.4  202.29  5039.6  211.29  5301.2  211.01  5311.2  206.39
  5341.4  211.02  5844.5  208.45  7132.4  211.93  7434.2  218.36  7695.8  249.38
#Mann= 5 ,-1 , 0
  1558.7     .16       0  2349.6     .16       0  4986.3     .07       0
  4992.3     .16       0  7434.2     .16       0
#XS Ineff= 2 , 0
         4332.95  224.03 5653.41          224.41
Permanent Ineff=
       F       F
Bank Sta=4957.5,5039.6
XS Rating Curve= 0 ,0
Exp/Cntr=0.3,0.1

Type RM Length L Ch R = 1 ,58783   ,612,612,612
BEGIN DESCRIPTION:
HURRICANE BAYOU 35.0
END DESCRIPTION:
XS GIS Cut Line= 3
       3786349.6      10481060.2      3783349.61     10483760.19
      3783779.99     10488529.14
#Sta/Elev= 30
   945.7  255.95  1064.1  253.38  1214.2  254.75  1224.1  254.37  1377.3  248.61
  1455.8  231.16  1633.5  220.31  2085.9  215.89  2283.9  220.37  2333.3  212.97
  2453.6   214.3    2624  220.24  2694.7  231.54  2744.4  217.75  2822.1  211.34
  4960.5   209.2  4998.9   201.5  5001.6     201  5004.9   201.5  5021.9  209.17
  6931.7  208.58  7853.4  219.61  7877.7  223.15  8275.1  276.79  8586.4  262.07
  8777.1  261.44  8927.1  268.83  9036.1  285.04  9261.9  294.86  9770.1  299.66
#Mann= 12 ,-1 , 0
   945.7     .08       0  1064.1     .16       0  1214.2     .05       0
  1224.1     .16       0  1633.5     .05       0  2085.9     .16       0
  4998.9     .07       0  5004.9     .16       0  7853.4     .05       0
  7877.7     .16       0  9036.1     .05       0  9261.9     .16       0
#XS Ineff= 2 , 0
         3852.27  230.93 5653.41          225.48
Permanent Ineff=
       F       F
Bank Sta=4960.5,5021.9
XS Rating Curve= 0 ,0
Exp/Cntr=0.3,0.1

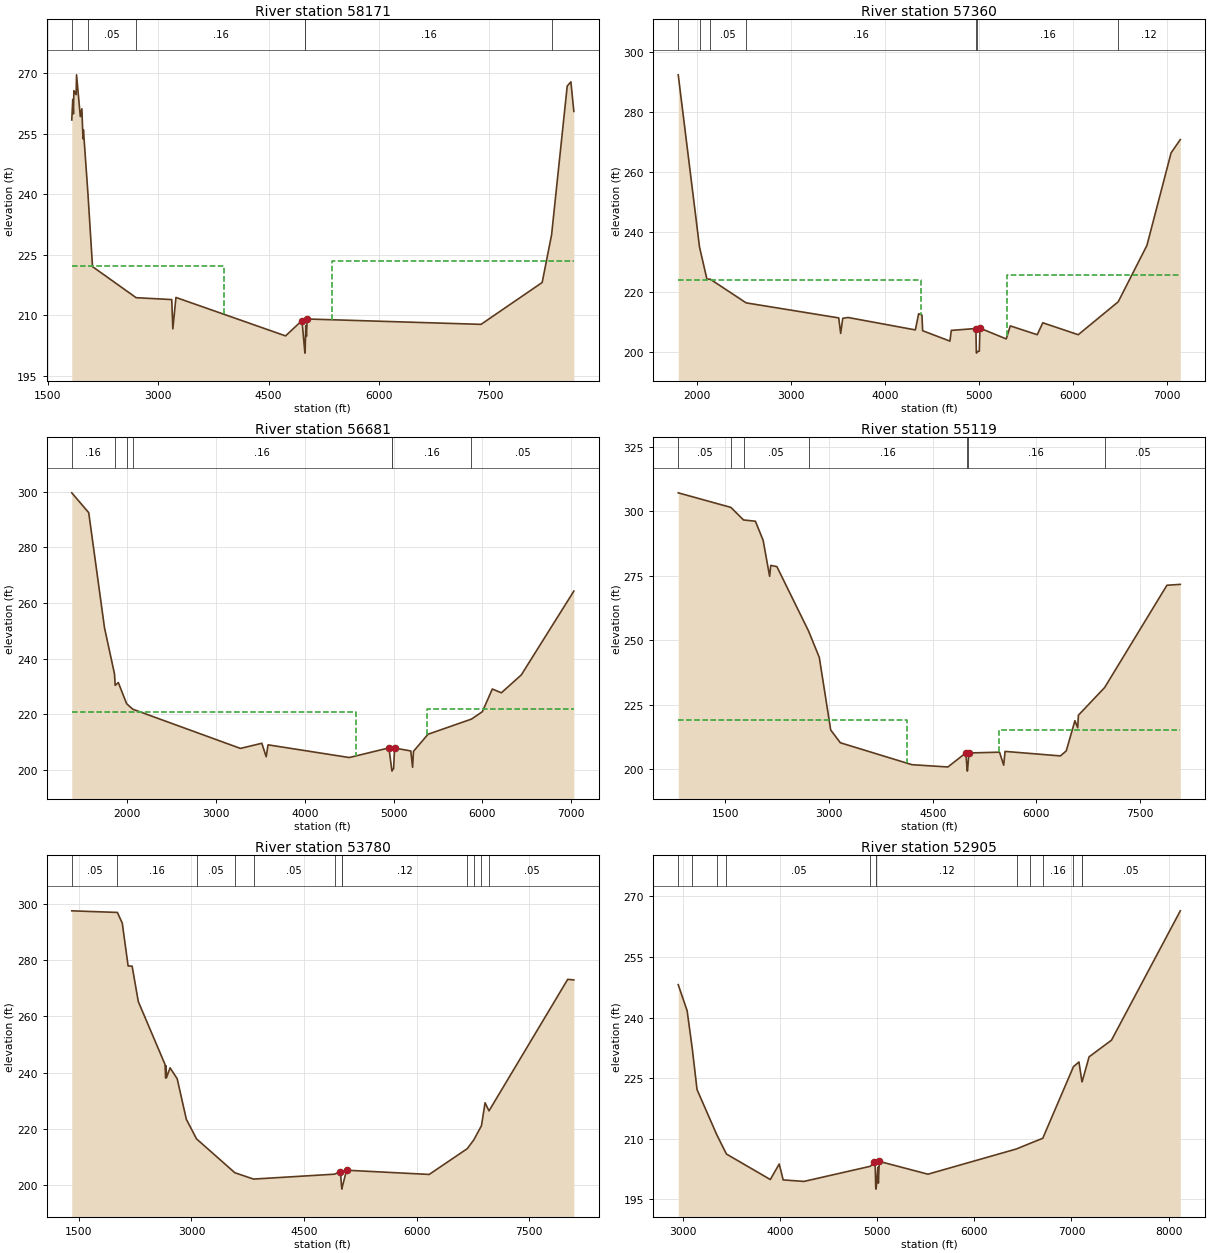
Type RM Length L Ch R = 1 ,58171   ,811,811,811
BEGIN DESCRIPTION:
HURRICANE BAYOU 34.0
END DESCRIPTION:
XS GIS Cut Line= 3
      3784749.63     10480710.15      3783024.78     10483333.86
      3782949.61     10487010.19
#Sta/Elev= 30
  1828.5  258.44  1842.1  263.53  1851.2  259.94  1857.2  265.71  1887.3   264.7
  1893.3  269.62  1944.6  259.27  1965.6  261.21  1980.7  253.76  1986.7  256.01
  2048.5  240.07  2110.2  222.09  2702.2  214.39  3185.8  213.92  3200.9  206.67
    3243  214.45  4731.4  204.92  4954.3  208.73  4991.7  201.15  4994.5  200.65
  4997.7  201.15  5004.7  207.47  5014.7  204.79  5024.7  209.11  7385.2  207.78
  8215.4  218.15  8343.3  229.98  8555.5  266.84  8605.5  267.88  8645.5  260.55
#Mann= 6 ,-1 , 0
  1828.5     .16       0  2048.5     .05       0  2702.2     .16       0
  4991.7     .07       0  4997.7     .16       0  8343.3     .16       0
#XS Ineff= 2 , 0
            3900  222.27 5368.18          223.42
Permanent Ineff=
       F       F
Bank Sta=4954.3,5024.7
XS Rating Curve= 0 ,0
Exp/Cntr=0.3,0.1

Type RM Length L Ch R = 1 ,57360   ,679,679,679
BEGIN DESCRIPTION:
HURRICANE BAYOU 33.0
END DESCRIPTION:
XS GIS Cut Line= 3
      3784599.63     10480710.16      3782499.61     10483110.19
      3781699.63     10485110.14
#Sta/Elev= 30
  1799.1  292.52  2025.6  235.02  2104.3  224.31  2139.2  224.31  2521.9  216.39
  3507.1  211.37    3528  206.18  3549.8  211.23  3606.3  211.51  4322.4  207.36
  4357.5  212.75  4392.6  212.35  4400.2  207.09  4690.6  203.62  4704.9   207.2
  4966.8  207.83  4971.4  200.11  4974.2  199.61  4977.4  200.11    5003  200.25
  5009.7  207.96  5289.8  204.35  5332.8   208.7  5619.6  205.76  5678.8  209.74
  6055.8  205.76  6481.2  216.74  6786.8  235.56    7044  266.47  7142.2  270.91
#Mann= 7 ,-1 , 0
  1799.1     .16       0  2025.6     .08       0  2139.2     .05       0
  2521.9     .16       0  4971.4     .07       0  4977.4     .16       0
  6481.2     .12       0
#XS Ineff= 2 , 0
         4384.66  223.95 5299.43          225.63
Permanent Ineff=
       F       F
Bank Sta=4966.8,5009.7
XS Rating Curve= 0 ,0
Exp/Cntr=0.3,0.1

Type RM Length L Ch R = 1 ,56681   ,1562,1562,1562
BEGIN DESCRIPTION:
HURRICANE BAYOU 32.0
END DESCRIPTION:
XS GIS Cut Line= 3
      3784599.63     10480460.17      3781899.61     10482860.19
      3781499.61     10484860.17
#Sta/Elev= 30
  1376.4  299.56  1567.5  292.43  1744.8  251.12  1857.5  234.56  1865.2  230.45
  1900.3  231.46  1994.2  223.85  2063.4  221.88  3275.1   207.8  3515.9  209.65
  3565.2   204.8  3586.1  209.09  4500.1  204.53  4946.7  207.99  4978.8  200.15
  4981.6  199.65  4984.8  200.15  4999.1  200.42  5009.3   207.3  5019.5  207.89
  5192.9  206.89  5213.3  201.04  5223.5  206.77  5386.6  212.88  5876.1  218.33
  5998.5  220.99  6110.7  229.13  6212.7  227.77    6437  234.19  7028.5  264.28
#Mann= 7 ,-1 , 0
  1376.4     .16       0  1857.5     .08       0  1994.2     .05       0
  2063.4     .16       0  4978.8     .07       0  4984.8     .16       0
  5876.1     .05       0
#XS Ineff= 2 , 0
         4571.59  220.91 5378.98          221.83
Permanent Ineff=
       F       F
Bank Sta=4946.7,5019.5
XS Rating Curve= 0 ,0
Exp/Cntr=0.3,0.1

Type RM Length L Ch R = 1 ,55119   ,1339,1339,1339
BEGIN DESCRIPTION:
HURRICANE BAYOU 31.0
END DESCRIPTION:
XS GIS Cut Line= 3
      3783324.26     10478359.91      3781371.14      10482109.9
      3781488.33      10485143.8
#Sta/Elev= 30
   817.1   307.1  1578.7  301.45  1761.8  296.58  1933.6  296.09  2045.5  288.69
  2139.6  274.72    2156  278.96  2244.4  278.49  2702.9   253.5  2858.2  243.29
  3023.1  215.15  3162.6  210.19  4199.9  201.68  4718.6   200.8  4978.2  206.26
  4997.5  199.69  5000.2  199.19  5003.5  199.69    5023  206.23  5465.8  206.54
  5525.9   201.5  5545.9  206.84  6346.5  205.09  6431.1  207.03  6556.7  218.75
  6596.7  216.02  6606.7  220.86    6987  231.62  7887.6  271.26  8081.4  271.61
#Mann= 7 ,-1 , 0
   817.1     .05       0  1578.7     .16       0  1761.8     .05       0
  2702.9     .16       0  4997.5     .07       0  5003.5     .16       0
    6987     .05       0
#XS Ineff= 2 , 0
         4131.82  219.04 5456.25          215.31
Permanent Ineff=
       F       F
Bank Sta=4978.2,5023
XS Rating Curve= 0 ,0
Exp/Cntr=0.3,0.1

Type RM Length L Ch R = 1 ,53780   ,875,875,875
BEGIN DESCRIPTION:
HURRICANE BAYOU 30.0
END DESCRIPTION:
XS GIS Cut Line= 3
      3781449.27     10478437.98      3780799.61     10482010.19
      3781399.61     10485010.17
#Sta/Elev= 30
  1404.7  297.46    2013  296.89  2077.8  293.07  2155.6  277.88    2209  277.81
  2291.2  265.23    2647  242.92  2656.2  238.05  2661.2   242.4  2667.3  238.19
  2714.6  241.68  2809.6   237.8  2931.5  223.39  3067.3  216.44  3577.5  204.42
  3826.3  202.16  4906.9   203.9  4984.7  204.85  5000.7  199.09  5003.5  198.59
  5006.7  199.09  5066.1  205.31  6167.5  203.81  6675.9  212.99  6762.8  216.12
  6863.7  221.12  6911.9  229.27  6964.5  226.39  8013.3  273.12  8094.9  272.91
#Mann= 12 ,-1 , 0
  1404.7     .05       0    2013     .16       0  3067.3     .05       0
  3577.5     .16       0  3826.3     .05       0  4906.9     .12       0
  5000.7     .07       0  5006.7     .12       0  6675.9     .16       0
  6762.8     .05       0  6863.7     .08       0  6964.5     .05       0
Bank Sta=4984.7,5066.1
XS Rating Curve= 0 ,0
Exp/Cntr=0.3,0.1

Type RM Length L Ch R = 1 ,52905   ,3764,3764,3764
BEGIN DESCRIPTION:
HURRICANE BAYOU 29.0
END DESCRIPTION:
XS GIS Cut Line= 3
      3780699.62     10479860.16      3780299.61     10481860.19
       3781199.6     10484860.16
#Sta/Elev= 30
  2949.9  248.15  3041.7  241.68  3094.5  232.31  3143.7  222.16  3347.2  210.98
  3446.5  206.21  3898.3   199.9  3990.1  203.74  4030.9   199.8  4245.1  199.43
  4927.6  203.17  4969.1  204.17  4979.3  202.95    4984  198.02  4986.7  197.52
    4990  198.02  5006.1  202.96  5011.3     199  5020.9  204.39    5522  201.22
  6435.6  207.48  6569.8  208.81  6704.8  210.11  7021.3  227.86  7077.6     229
  7108.5  224.11  7110.2  224.11    7182  230.28  7412.6   234.4  8121.6  266.43
#Mann= 13 ,-1 , 0
  2949.9     .16       0  3094.5     .12       0  3347.2     .16       0
  3446.5     .05       0  4927.6     .12       0    4984     .07       0
    4990     .12       0  6435.6     .16       0  6569.8     .12       0
  6704.8     .16       0  7021.3     .05       0  7108.5     .08       0
  7110.2     .05       0
Bank Sta=4969.1,5020.9
XS Rating Curve= 0 ,0
Exp/Cntr=0.3,0.1