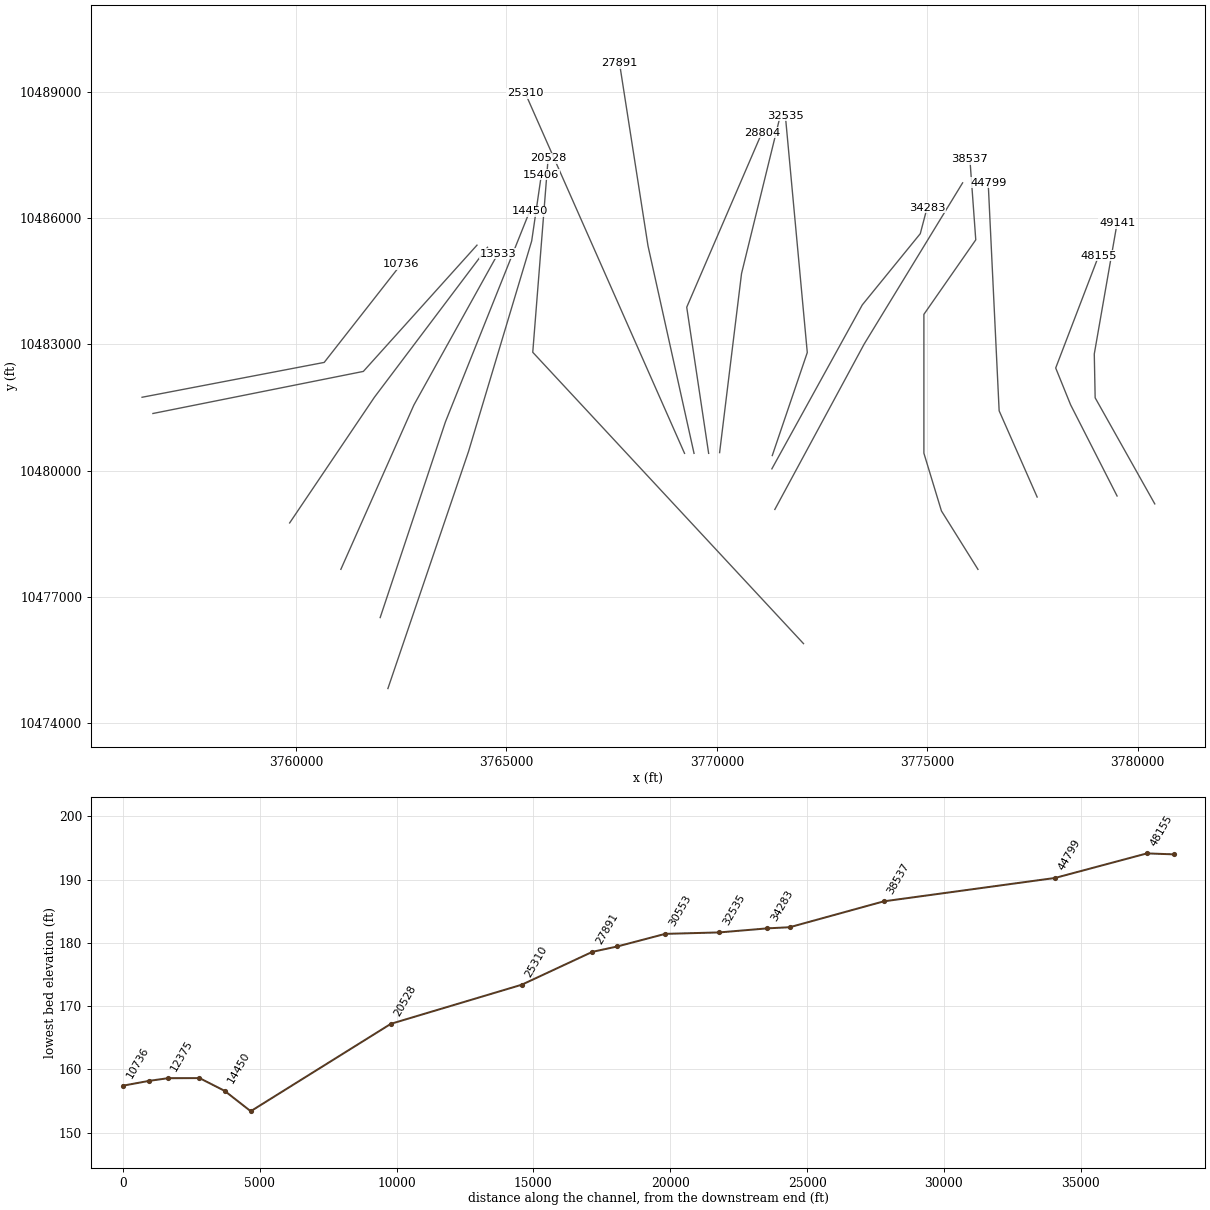
HEC-RAS study HURRICANE BAYOU.prj: HURRICANE BAYOU Base Level Engineering

--- HURRICANE BAYOU.g01 (geometry) --- (continued)

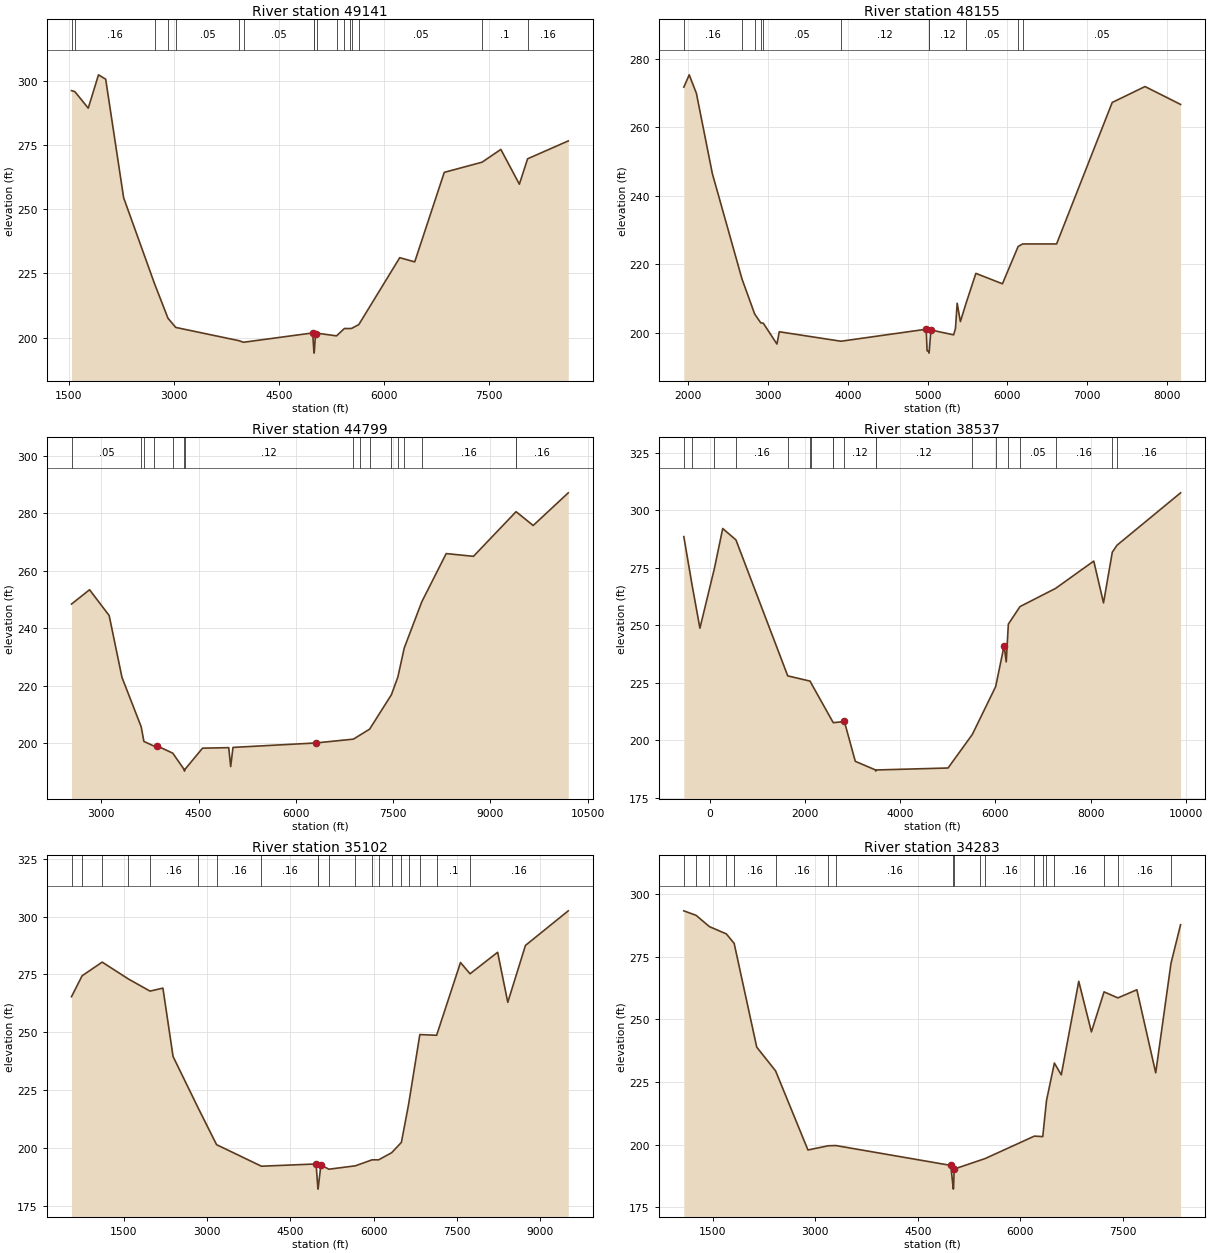
Type RM Length L Ch R = 1 ,49141   ,986,986,986
BEGIN DESCRIPTION:
HURRICANE BAYOU 28.0
END DESCRIPTION:
XS GIS Cut Line= 4
      3780404.62     10479212.23      3778987.96     10481733.04
      3778967.13      10482774.7      3779508.48     10485877.04
#Sta/Elev= 30
  1541.7  296.15  1589.9  295.74  1780.3  289.32  1926.6  302.29  2029.2  300.59
    2285  254.47  2725.4  221.03  2917.7  207.55  3027.9  203.99  3931.3  198.82
  3994.5  198.22  4980.6  201.85  4997.6  194.49  5000.3  193.99  5003.6  194.49
  5020.6  201.52  5045.8  201.74  5320.3  200.71  5432.5  203.57    5509  203.55
  5537.5  203.64  5637.8  205.09  6221.8  231.14    6435  229.49  6856.5  264.34
  7395.2  268.29  7663.2  273.26  7927.2  259.73  8044.5  269.61  8624.4  276.57
#Mann= 17 ,-1 , 0
  1541.7     .05       0  1589.9     .16       0  2725.4     .12       0
  2917.7     .16       0  3027.9     .05       0  3931.3     .16       0
  3994.5     .05       0  4997.6     .03       0  5003.6     .05       0
  5045.8     .07       0  5320.3     .12       0  5432.5     .05       0
    5509     .12       0  5537.5     .16       0  5637.8     .05       0
  7395.2      .1       0  8044.5     .16       0
Bank Sta=4980.6,5020.6
XS Rating Curve= 0 ,0
Exp/Cntr=0.3,0.1

Type RM Length L Ch R = 1 ,48155   ,3356,3356,3356
BEGIN DESCRIPTION:
HURRICANE BAYOU 27.0
END DESCRIPTION:
XS GIS Cut Line= 4
      3779508.78     10479399.74      3778404.63     10481566.37
      3778050.46     10482441.37      3779070.76     10485106.64
#Sta/Elev= 30
  1942.8   271.7  2010.6   275.3  2100.4  269.93  2300.6  246.51  2672.6  215.75
  2831.5  205.55  2907.9  202.96  2939.5  202.88  3110.6  196.79  3139.9  200.37
  3913.3  197.61  4982.5  201.11  4993.6  194.81  5014.4  194.64  5017.2  194.14
  5020.4  194.64  5041.5  200.89  5326.4  199.47  5349.4  201.33  5370.8  208.69
  5411.1  203.34    5481  208.59  5605.4   217.4  5938.3  214.36  6135.4  225.24
  6191.8  225.98  6617.5  225.98  7315.1  267.24  7726.5  271.88  8172.4  266.67
#Mann= 11 ,-1 , 0
  1942.8     .16       0  2672.6     .12       0  2831.5     .16       0
  2907.9     .12       0  2939.5     .05       0  3913.3     .12       0
  5014.4     .07       0  5020.4     .12       0    5481     .05       0
  6135.4     .08       0  6191.8     .05       0
Bank Sta=4982.5,5041.5
XS Rating Curve= 0 ,0
Exp/Cntr=0.3,0.1

Type RM Length L Ch R = 1 ,44799   ,6262,6262,6262
BEGIN DESCRIPTION:
HURRICANE BAYOU 26.0
END DESCRIPTION:
XS GIS Cut Line= 3
      3777609.48     10479375.42      3776706.71     10481424.01
       3776446.3     10486840.66
#Sta/Elev= 30
  2540.4  248.45  2818.8  253.44  3121.1  244.47  3318.6  222.94  3615.2   205.7
  3657.2   200.6  3805.5  199.06  3864.6  199.01    4102  196.52    4280  190.76
  4282.8  190.26    4286  190.76  4561.5  198.26  4965.5  198.44  4995.5  191.84
  5030.9  198.52    6307  200.07  6887.6   201.4  6985.6  202.76  7138.5  204.89
  7474.3  216.88    7574  223.04  7672.1  233.14    7942   249.2  8319.4  266.04
  8739.8  265.08  9392.6  280.53    9399  280.61  9660.9  275.82   10202   287.2
#Mann= 16 ,-1 , 0
  2540.4     .05       0  3615.2     .12       0  3657.2     .16       0
  3805.5     .05       0    4102     .12       0    4280     .07       0
    4286     .12       0  6887.6     .05       0  6985.6      .1       0
  7138.5     .05       0  7474.3      .1       0    7574     .05       0
  7672.1      .1       0    7942     .16       0  9392.6     .05       0
    9399     .16       0
Bank Sta=3864.6,6307
XS Rating Curve= 0 ,0
Exp/Cntr=0.3,0.1

Type RM Length L Ch R = 1 ,38537   ,3435,3435,3435
BEGIN DESCRIPTION:
HURRICANE BAYOU 25.0
END DESCRIPTION:
XS GIS Cut Line= 6
      3776203.23     10477656.66      3775335.19     10479045.54
      3774918.52     10480417.07      3774918.52     10483715.68
      3776151.16     10485486.51      3776012.31      10487395.7
#Sta/Elev= 30
  -549.9  288.62  -373.7  267.29  -211.3  248.77    93.9  274.85   267.9  292.15
     546  287.19  1634.6  228.02  2105.2  225.73  2122.4  224.99  2583.3  207.94
    2593  207.65  2813.8  208.11  2824.5  208.23  3054.5  190.83  3481.5  187.06
  3484.2  186.56  3487.5  187.06  5004.5  187.92  5515.2  202.55  6005.7  223.38
  6182.8  241.17  6227.3  234.09  6271.6  250.54  6516.7  258.17  7264.1  266.08
  8067.2  277.98    8272  259.78  8456.8  281.84  8554.9  284.86  9891.8  307.68
#Mann= 19 ,-1 , 0
  -549.9     .05       0  -373.7     .16       0    93.9     .05       0
     546     .16       0  1634.6     .12       0  2105.2     .16       0
  2122.4     .07       0  2583.3     .12       0    2593     .07       0
  2813.8     .12       0  3481.5     .07       0  3487.5     .12       0
  5515.2     .16       0  6005.7     .05       0  6271.6     .16       0
  6516.7     .05       0  7264.1     .16       0  8456.8     .05       0
  8554.9     .16       0
Bank Sta=2824.5,6182.8
XS Rating Curve= 0 ,0
Exp/Cntr=0.3,0.1

Type RM Length L Ch R = 1 ,35102   ,819,819,819
BEGIN DESCRIPTION:
HURRICANE BAYOU 24.0
END DESCRIPTION:
XS GIS Cut Line= 3
      3771376.85     10479080.26      3773499.61     10483010.19
      3775838.67      10486840.7
#Sta/Elev= 30
   554.7  265.43     746  274.45  1107.8  280.34  1577.4  273.11  1970.7  267.84
  2202.6  269.13  2385.4  239.65  2836.5  217.54  3169.6  201.64  3978.3  192.35
  4963.7  193.32  4995.6  182.97  4998.3  182.47  5001.6  182.97  5050.3  192.84
  5194.7  191.06  5671.4  192.52    5973   195.1  6090.7   195.1  6325.3  198.16
  6501.2  202.62  6630.4   218.9    6834  249.11  7136.4   248.8  7566.7  280.17
    7739  275.31  8236.4  284.59  8419.2  263.01  8737.8  287.54  9509.5  302.45
#Mann= 20 ,-1 , 0
   554.7     .16       0     746     .05       0  1107.8     .16       0
  1577.4     .05       0  1970.7     .16       0  2836.5     .16       0
  3169.6     .16       0  3978.3     .16       0  4995.6     .07       0
  5001.6     .16       0  5194.7     .16       0  5671.4     .16       0
    5973     .16       0  6090.7     .16       0  6325.3     .16       0
  6501.2     .05       0  6630.4     .16       0    6834     .05       0
  7136.4      .1       0    7739     .16       0
Bank Sta=4963.7,5050.3
XS Rating Curve= 0 ,0
Exp/Cntr=0.3,0.1

Type RM Length L Ch R = 1 ,34283   ,1748,1748,1748
BEGIN DESCRIPTION:
HURRICANE BAYOU 23.0
END DESCRIPTION:
XS GIS Cut Line= 4
      3771306.48     10480045.44      3773454.92     10483940.84
      3774832.96     10485633.54      3774995.71     10486251.99
#Sta/Elev= 30
  1076.8  293.27  1257.3  291.46  1451.6  286.97  1699.4  284.07  1813.9  280.28
  2144.1  238.91    2420  229.45  2893.7   197.9  3191.3  199.58  3302.2  199.67
  4984.3  191.75  5019.1  182.79  5021.9  182.29  5025.1  182.79  5033.6   190.3
  5410.3  193.77  5487.8  194.49  6207.8  203.43  6330.4  203.24    6385  217.57
  6500.8  232.57  6601.6  227.85  6857.3  265.16  7042.6  244.99  7227.6  260.96
  7429.9  258.55  7708.1  261.79  7983.8  228.68  8207.3  272.34  8347.6  287.75
#Mann= 19 ,-1 , 0
  1076.8     .16       0  1257.3     .05       0  1451.6     .16       0
  1699.4     .05       0  1813.9     .16       0    2420     .16       0
  3191.3     .16       0  3302.2     .16       0  5019.1     .07       0
  5025.1     .16       0  5410.3     .16       0  5487.8     .16       0
  6207.8     .16       0  6330.4     .16       0    6385     .16       0
  6500.8     .16       0  7227.6      .1       0  7429.9     .16       0
  8207.3      .1       0
Bank Sta=4984.3,5033.6
XS Rating Curve= 0 ,0
Exp/Cntr=0.3,0.1

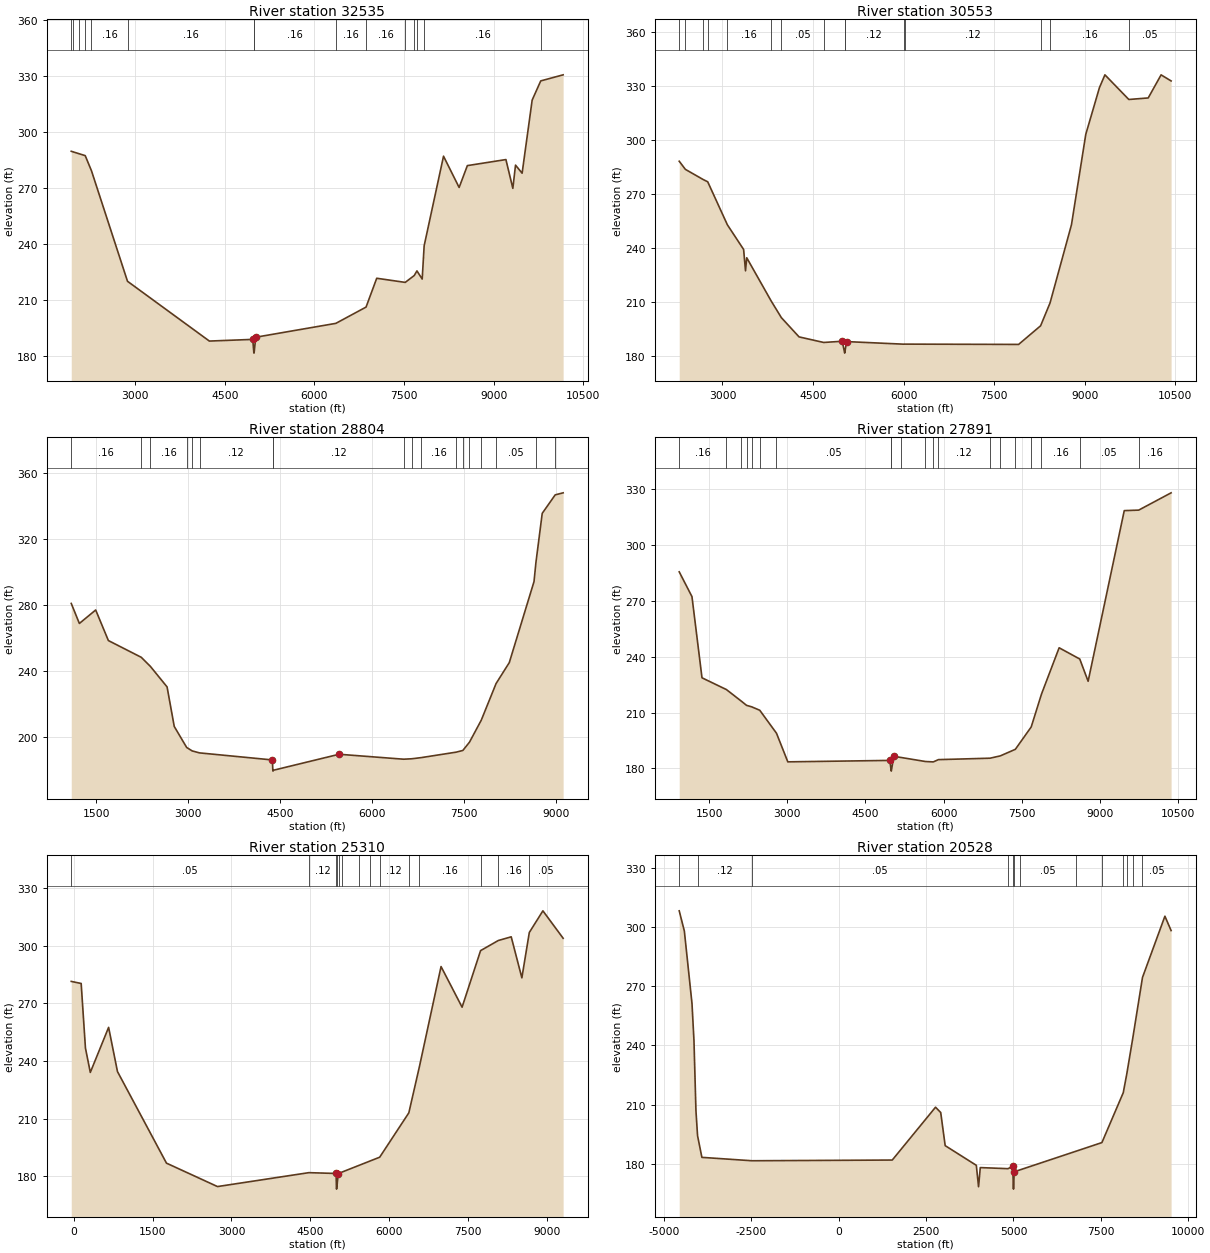
Type RM Length L Ch R = 1 ,32535   ,1982,1982,1982
BEGIN DESCRIPTION:
HURRICANE BAYOU 21.0
END DESCRIPTION:
XS GIS Cut Line= 3
      3771316.02     10480360.96      3772147.84     10482809.11
      3771627.01     10488434.14
#Sta/Elev= 30
  1928.8  289.79  1952.6  289.55  2057.6   288.5  2162.6  287.45  2267.6  279.31
  2870.3  220.14    4241  188.11  4967.4  189.01  4984.9  182.15  4987.7  181.65
  4990.9  182.15  5017.6  190.17  6358.7   197.6  6864.1  206.32  7042.7  221.76
  7519.6  219.55  7670.9  223.23    7716  225.71  7803.9  221.34  7836.7  239.16
    8161  287.16  8422.1   270.4  8560.2  282.11  9205.5  285.35  9321.4  269.93
  9366.2  282.38  9476.6  278.04  9644.8  317.22  9788.4  327.49 10163.5  330.75
#Mann= 15 ,-1 , 0
  1928.8     .05       0  1952.6      .1       0  2057.6     .16       0
  2162.6     .05       0  2267.6     .16       0  2870.3     .16       0
  4984.9     .07       0  4990.9     .16       0  6358.7     .16       0
  6864.1     .16       0  7519.6     .12       0  7670.9     .16       0
    7716     .05       0  7836.7     .16       0  9788.4     .05       0
Bank Sta=4967.4,5017.6
XS Rating Curve= 0 ,0
Exp/Cntr=0.3,0.1

Type RM Length L Ch R = 1 ,30553   ,1749,1749,1749
BEGIN DESCRIPTION:
HURRICANE BAYOU 20.0
END DESCRIPTION:
XS GIS Cut Line= 3
      3770064.51     10480430.62      3770585.34     10484684.11
      3771505.05     10488432.36
#Sta/Elev= 30
  2284.2  288.19  2386.2  283.67  2684.2  277.95    2756  276.76  3081.5  252.84
  3350.6  239.09  3381.9  227.21  3402.1  234.48  3805.9  210.49  3975.4  201.17
  4268.5  190.45  4676.6  187.35  4983.8  188.03  5021.1  181.92  5023.8  181.42
  5027.1  181.92  5054.3  187.84    5999   186.4  6022.8  186.43    7904  186.26
  8268.2  196.64  8424.5  209.35  8779.2  252.85    9016  303.15  9242.6  329.16
    9333  336.27  9728.7  322.55 10050.1  323.41 10263.1  336.25 10428.9  332.87
#Mann= 15 ,-1 , 0
  2284.2     .16       0  2386.2     .05       0  2684.2     .16       0
    2756     .05       0  3081.5     .16       0  3805.9     .12       0
  3975.4     .05       0  4676.6     .12       0  5021.1     .07       0
  5027.1     .12       0    5999     .07       0  6022.8     .12       0
  8268.2     .05       0  8424.5     .16       0  9728.7     .05       0
Bank Sta=4983.8,5054.3
XS Rating Curve= 0 ,0
Exp/Cntr=0.3,0.1

Type RM Length L Ch R = 1 ,28804   ,913,913,913
BEGIN DESCRIPTION:
HURRICANE BAYOU 19.0
END DESCRIPTION:
XS GIS Cut Line= 3
       3769804.1     10480413.26      3769283.26      10483885.5
      3771071.45     10488034.79
#Sta/Elev= 30
  1090.1  280.95  1222.5  268.83  1488.8  276.99  1696.1  258.48  2233.4  248.33
  2382.7   242.8  2654.3  230.41  2771.3  206.47  2974.6  193.73  3064.3  191.66
  3184.4  190.47  4373.4   186.2  4380.5  179.93  4383.2  179.43  4386.5  179.93
  5462.4  189.64  6515.1  186.65  6649.7  186.91  6804.6  187.62  7373.2  190.92
  7481.8  191.93  7590.4  196.96  7782.7  210.26    8025  232.48  8240.4  245.14
    8644   294.2    8675  305.69    8778   335.5  8989.8  346.69  9119.4  347.92
#Mann= 18 ,-1 , 0
  1090.1     .16       0  2233.4     .05       0  2382.7     .16       0
  2974.6     .12       0  3064.3     .05       0  3184.4     .12       0
  4380.5     .07       0  4386.5     .12       0  6515.1     .05       0
  6649.7      .1       0  6804.6     .16       0  7373.2     .05       0
  7481.8     .12       0  7590.4     .05       0  7782.7     .16       0
    8025     .05       0    8675     .16       0  8989.8     .05       0
Bank Sta=4373.4,5462.4
XS Rating Curve= 0 ,0
Exp/Cntr=0.3,0.1

Type RM Length L Ch R = 1 ,27891   ,2581,2581,2581
BEGIN DESCRIPTION:
HURRICANE BAYOU 18.0
END DESCRIPTION:
XS GIS Cut Line= 3
      3769456.87     10480413.27      3768363.12     10485343.83
      3767686.04     10489684.12
#Sta/Elev= 30
     926  285.54  1170.6  272.25  1363.3  228.67  1832.3  222.35  2118.6  216.13
  2218.2  213.89  2317.9  213.08  2472.3  211.25  2793.5  198.92  3010.8  183.56
  4968.9  184.33  4994.2  179.08  4996.9  178.58  5000.2  179.08  5045.9   186.5
  5182.8  185.91  5653.8  183.74  5804.2  183.53  5901.4  184.75  6893.6  185.52
  7091.1  186.77  7379.2  190.29  7683.4  202.28  7880.8  219.92  8219.6  244.78
  8615.8  238.75  8776.2  226.81  9469.8   318.4  9747.5  318.67 10369.2  327.95
#Mann= 20 ,-1 , 0
     926     .16       0  1832.3     .12       0  2118.6     .16       0
  2218.2     .05       0  2317.9     .16       0  2472.3     .05       0
  2793.5     .05       0  4994.2     .03       0  5000.2     .05       0
  5182.8     .12       0  5653.8     .12       0  5804.2     .05       0
  5901.4     .12       0  6893.6      .1       0  7091.1     .12       0
  7379.2     .16       0  7683.4     .05       0  7880.8     .16       0
  8615.8     .05       0  9747.5     .16       0
Bank Sta=4968.9,5045.9
XS Rating Curve= 0 ,0
Exp/Cntr=0.3,0.1

Type RM Length L Ch R = 1 ,25310   ,4782,4782,4782
BEGIN DESCRIPTION:
HURRICANE BAYOU 16.0
END DESCRIPTION:
XS GIS Cut Line= 2
      3769231.17      10480413.3      3765446.48     10488972.26
#Sta/Elev= 30
   -48.1  281.49   140.5  280.42   221.8   246.8   314.5  234.12   662.6  257.57
   831.1  234.57  1763.5   186.9  2734.4  174.71    4472  181.95  4991.1  181.53
    4997  173.88  4999.8  173.38    5003  173.88  5032.3  181.48  5048.6  181.66
  5103.7  182.26  5433.5  185.82    5636  188.01  5819.8  189.99  6374.5  213.09
  6575.7  237.11  6987.6  289.22  7387.7  268.08  7739.6  297.52    8076  302.77
  8322.2   304.7    8525  283.36  8666.5  306.95  8925.3  318.23  9310.3  303.95
#Mann= 14 ,-1 , 0
   -48.1     .05       0    4472     .12       0    4997     .07       0
    5003     .12       0  5048.6     .05       0  5103.7     .12       0
  5433.5     .07       0    5636     .05       0  5819.8     .12       0
  6374.5     .05       0  6575.7     .16       0  7739.6     .05       0
    8076     .16       0  8666.5     .05       0
Bank Sta=4991.1,5032.3
XS Rating Curve= 0 ,0
Exp/Cntr=0.3,0.1

Type RM Length L Ch R = 1 ,20528   ,5122,5122,5122
BEGIN DESCRIPTION:
HURRICANE BAYOU 15.0
END DESCRIPTION:
XS GIS Cut Line= 3
      3772058.21     10475892.11      3765624.83     10482814.87
      3765990.36     10487426.85
#Sta/Elev= 30
 -4566.5  308.17   -4420  297.97 -4200.7  261.19 -4144.5  242.45 -4087.8   206.9
 -4041.7  194.26 -3917.8  183.29   -2484  181.57  1530.7  181.93  2768.8   208.7
  2917.3     206  3044.8  189.23    3936  179.26  4000.1  168.41  4049.4  178.11
  4843.2  177.56  4979.7  178.79  4996.7   167.7  4999.5   167.2  5002.7   167.7
  5019.8  175.97  5187.7  176.96  6797.1  186.45  7530.4  190.78  8141.4  216.05
  8240.2  225.35  8408.8  243.14  8691.5  274.42  9333.3  305.45  9510.5  298.17
#Mann= 13 ,-1 , 0
 -4566.5     .16       0 -4041.7     .12       0   -2484     .05       0
  4843.2     .12       0  4996.7     .07       0  5002.7     .12       0
  5187.7     .05       0  6797.1     .12       0  7530.4     .05       0
  8141.4     .08       0  8240.2     .05       0  8408.8     .16       0
  8691.5     .05       0
Bank Sta=4979.7,5019.8
XS Rating Curve= 0 ,0
Exp/Cntr=0.3,0.1

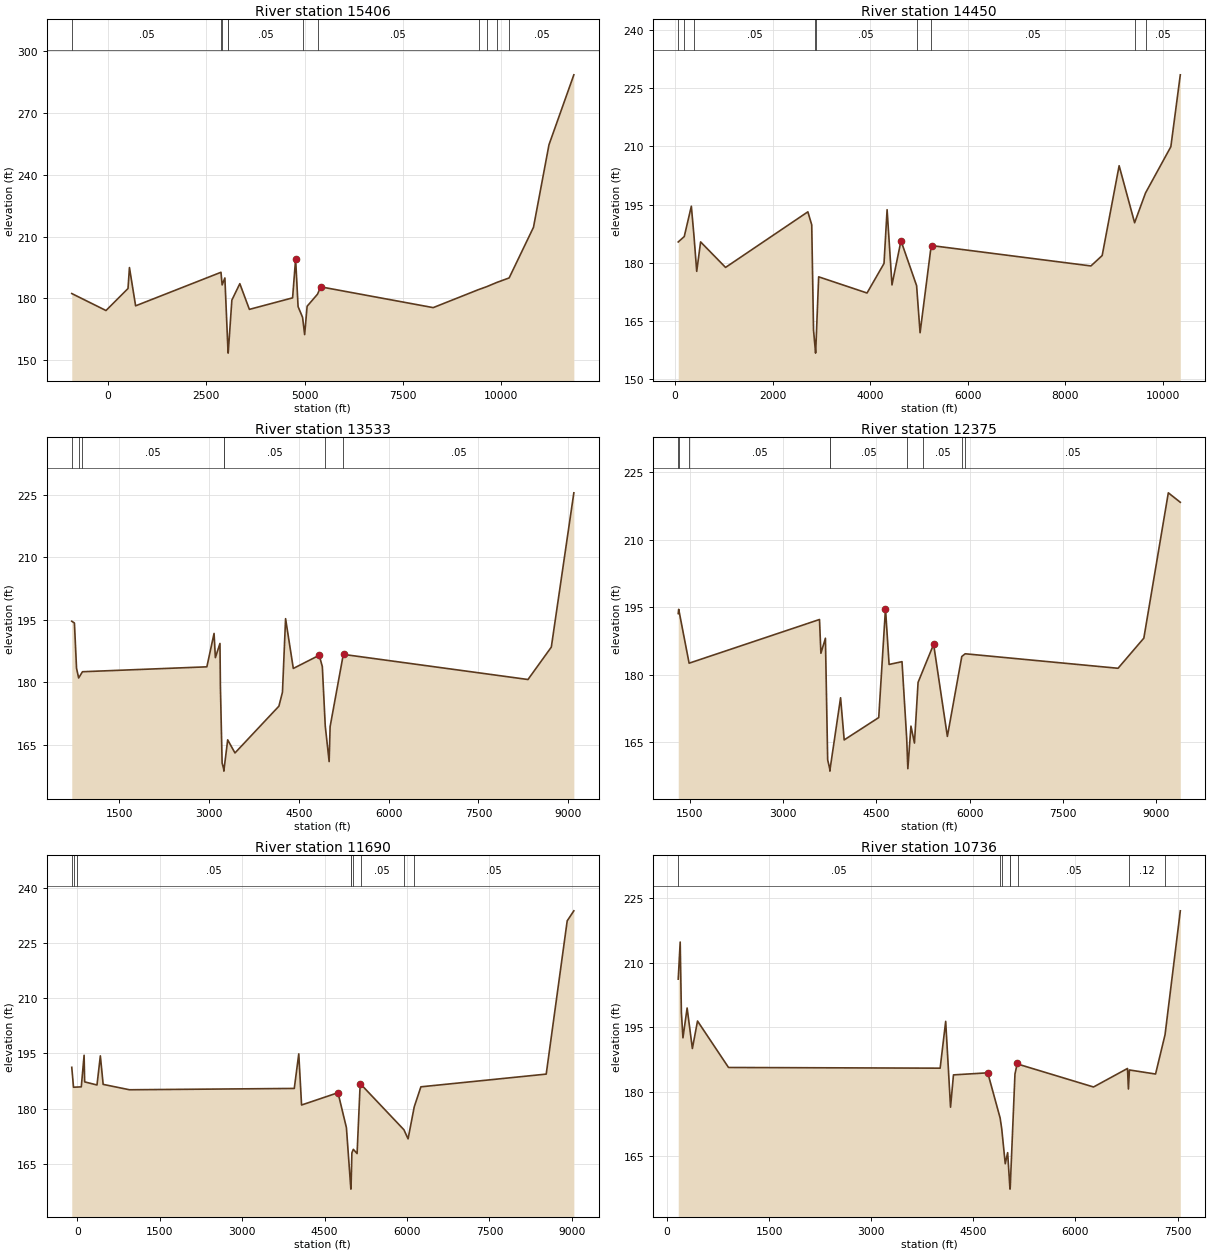
Type RM Length L Ch R = 1 ,15406   ,956,956,956
BEGIN DESCRIPTION:
HURRICANE BAYOU 13.0
END DESCRIPTION:
XS GIS Cut Line= 4
      3762183.02     10474825.07      3764099.61     10480460.19
      3765599.61     10485460.19      3765829.65      10487035.5
#Sta/Elev= 30
  -916.9  182.31   -46.5  174.06   512.9  184.75   549.5  194.91   706.4  176.34
  2876.7  192.63  2906.2  186.49  2975.5  189.88    3056  153.88  3058.7  153.38
    3062  153.88  3153.1  179.12  3355.8   187.1  3598.7  174.62  4697.2  180.21
  4773.9  199.11  4836.6  175.96  4950.7  170.78  5003.5  162.37  5066.6  176.14
  5331.1  182.01  5411.1  185.56  8271.7  175.47  9424.8  184.22  9635.9  185.67
  9884.7  187.66 10202.5  189.89 10821.3  214.47 11215.5  254.54 11847.4  288.49
#Mann= 11 ,-1 , 0
  -916.9     .05       0  2876.7     .08       0  2906.2     .05       0
    3056     .07       0    3062     .05       0  4950.7     .12       0
  5331.1     .05       0  9424.8     .12       0  9635.9     .05       0
  9884.7     .12       0 10202.5     .05       0
Bank Sta=4773.9,5411.1
XS Rating Curve= 0 ,0
Exp/Cntr=0.3,0.1

Type RM Length L Ch R = 1 ,14450   ,917,917,917
BEGIN DESCRIPTION:
HURRICANE BAYOU 12.0
END DESCRIPTION:
XS GIS Cut Line= 3
      3761999.46     10476510.92      3763549.61     10481160.19
      3765549.59     10486160.15
#Sta/Elev= 30
      68  185.33   191.2  186.72   336.6  194.56   392.2  186.65   446.7  177.73
   526.3  185.34  1037.5  178.75  2723.6  193.11  2802.9  189.75  2839.8  162.57
  2878.7  157.11  2881.5  156.61  2884.7  157.11    2945  176.32  3935.8  172.14
  4283.7  179.76  4346.9  193.66  4447.2  174.24  4631.6  185.63  4951.4  174.04
  5022.7  161.87  5236.4     183  5259.7  184.39  8523.1  179.13  8753.3  181.82
  9100.6  205.02  9417.7  190.29  9641.2  197.98 10160.2  209.93   10354   228.5
#Mann= 9 ,-1 , 0
      68     .05       0   191.2     .08       0   392.2     .05       0
  2878.7     .07       0  2884.7     .05       0  4951.4     .12       0
  5236.4     .05       0  9417.7     .12       0  9641.2     .05       0
Bank Sta=4631.6,5259.7
XS Rating Curve= 0 ,0
Exp/Cntr=0.3,0.1

Type RM Length L Ch R = 1 ,13533   ,1158,1158,1158
BEGIN DESCRIPTION:
HURRICANE BAYOU 11.0
END DESCRIPTION:
XS GIS Cut Line= 3
      3761065.34     10477657.47      3762799.61     10481560.19
      3764799.63     10485160.22
#Sta/Elev= 30
   704.6  194.66     749  194.24   784.2  183.35   819.8  181.02   883.2  182.52
  2961.8   183.7  3082.2  191.73  3104.1  185.91  3180.7  189.32  3188.1  179.06
  3216.8  160.57  3243.3  159.12  3246.1  158.62  3249.3  159.12  3309.8  166.14
  3431.6  162.99  4165.5  174.24    4225   177.6    4277  195.28  4406.3  183.31
  4839.2  186.48  4891.2  183.75  4939.9   169.5    5005  160.91  5021.1  169.31
  5241.8   186.7  5254.4  186.67  8327.1  180.65  8717.2  188.44  9093.6  225.54
#Mann= 7 ,-1 , 0
   704.6     .05       0   819.8     .08       0   883.2     .05       0
  3243.3     .07       0  3249.3     .05       0  4939.9     .12       0
  5241.8     .05       0
Bank Sta=4839.2,5254.4
XS Rating Curve= 0 ,0
Exp/Cntr=0.3,0.1

Type RM Length L Ch R = 1 ,12375   ,685,685,685
BEGIN DESCRIPTION:
HURRICANE BAYOU 10.0
END DESCRIPTION:
XS GIS Cut Line= 3
      3759848.38     10478759.92      3761862.26     10481746.01
      3764549.61      10485310.2
#Sta/Elev= 30
  1317.9  193.58  1325.4  194.52  1492.7  182.56  3587.2  192.26  3609.9  184.76
  3682.3   188.1  3718.5   161.1  3751.7   159.1  3754.4   158.6  3757.7   159.1
  3925.9  174.89  3983.9  165.53  4538.7  170.49  4647.2  194.69  4705.4  182.28
  4912.6   182.9  4987.7  165.93  5006.4  159.14  5056.4  168.59  5112.7  164.83
  5170.9   178.3  5251.1  181.03  5420.7  186.75  5641.4  166.31    5873  184.05
  5928.1  184.65  8383.1  181.43  8797.4  188.12  9190.8  220.38  9383.4  218.28
#Mann= 9 ,-1 , 0
  1317.9     .05       0  1325.4     .08       0  1492.7     .05       0
  3751.7     .07       0  3757.7     .05       0  4987.7     .12       0
  5251.1     .05       0    5873     .12       0  5928.1     .05       0
Bank Sta=4647.2,5420.7
XS Rating Curve= 0 ,0
Exp/Cntr=0.3,0.1

Type RM Length L Ch R = 1 ,11690   ,954,954,954
BEGIN DESCRIPTION:
HURRICANE BAYOU 9.0
END DESCRIPTION:
XS GIS Cut Line= 3
      3756599.63     10481360.19      3761599.61     10482360.19
      3764299.62      10485360.2
#Sta/Elev= 30
     -99  191.24   -67.3  185.84    -8.9  185.88    74.3  185.94   125.3  194.52
   135.5  187.29   359.9  186.45   421.1  194.35   472.1  186.61   951.4  185.15
  3949.6  185.51  4031.2  194.89  4082.2  181.01    4745  184.35    4898  174.87
  4976.6  158.68  4979.4  158.18  4982.6  158.68  4997.5     168  5023.9  168.99
  5092.3  167.83  5148.4  186.76  5156.6   186.7  5945.3  174.28  6019.9  171.82
  6131.8  180.49  6253.1  185.95  8533.4   189.4  8915.4  231.01  9036.1  233.72
#Mann= 9 ,-1 , 0
     -99     .05       0   -67.3      .1       0    -8.9     .05       0
  4976.6     .03       0  4982.6     .05       0  5023.9     .12       0
  5156.6     .05       0  5945.3     .12       0  6131.8     .05       0
Bank Sta=4745,5148.4
XS Rating Curve= 0 ,0
Exp/Cntr=0.3,0.1

Type RM Length L Ch R = 1 ,10736   ,0,0,0
BEGIN DESCRIPTION:
HURRICANE BAYOU 8.0
END DESCRIPTION:
XS GIS Cut Line= 3
      3756341.41     10481746.01      3760669.51     10482574.15
      3762499.63     10484910.22
#Sta/Elev= 30
   166.5  206.19   195.2   214.8   212.9  198.42   235.9  192.56     297  199.48
   374.2  190.07   449.7  196.46     905  185.67  4013.2  185.51  4094.7  196.38
    4166  176.45    4209  183.95  4712.6  184.43  4894.8  173.91  4917.9  171.42
  4969.4  163.32  5004.7  165.89  5036.9  157.92  5039.7  157.42  5042.9  157.92
  5112.2  184.15  5147.5  186.72  5149.7  186.48  6265.9  181.14  6764.9  185.44
  6778.5  180.67  6793.2  185.09  7177.2  184.15  7316.4  193.27  7540.7  222.05
#Mann= 8 ,-1 , 0
   166.5     .05       0  4894.8     .07       0  4917.9     .12       0
  5036.9     .07       0  5042.9     .12       0  5149.7     .05       0
  6793.2     .12       0  7316.4     .05       0
Bank Sta=4712.6,5147.5
XS Rating Curve= 0 ,0
Exp/Cntr=0.3,0.1

Chan Stop Cuts=-1
Use User Specified Reach Order=0
Composite Channel Slope=5