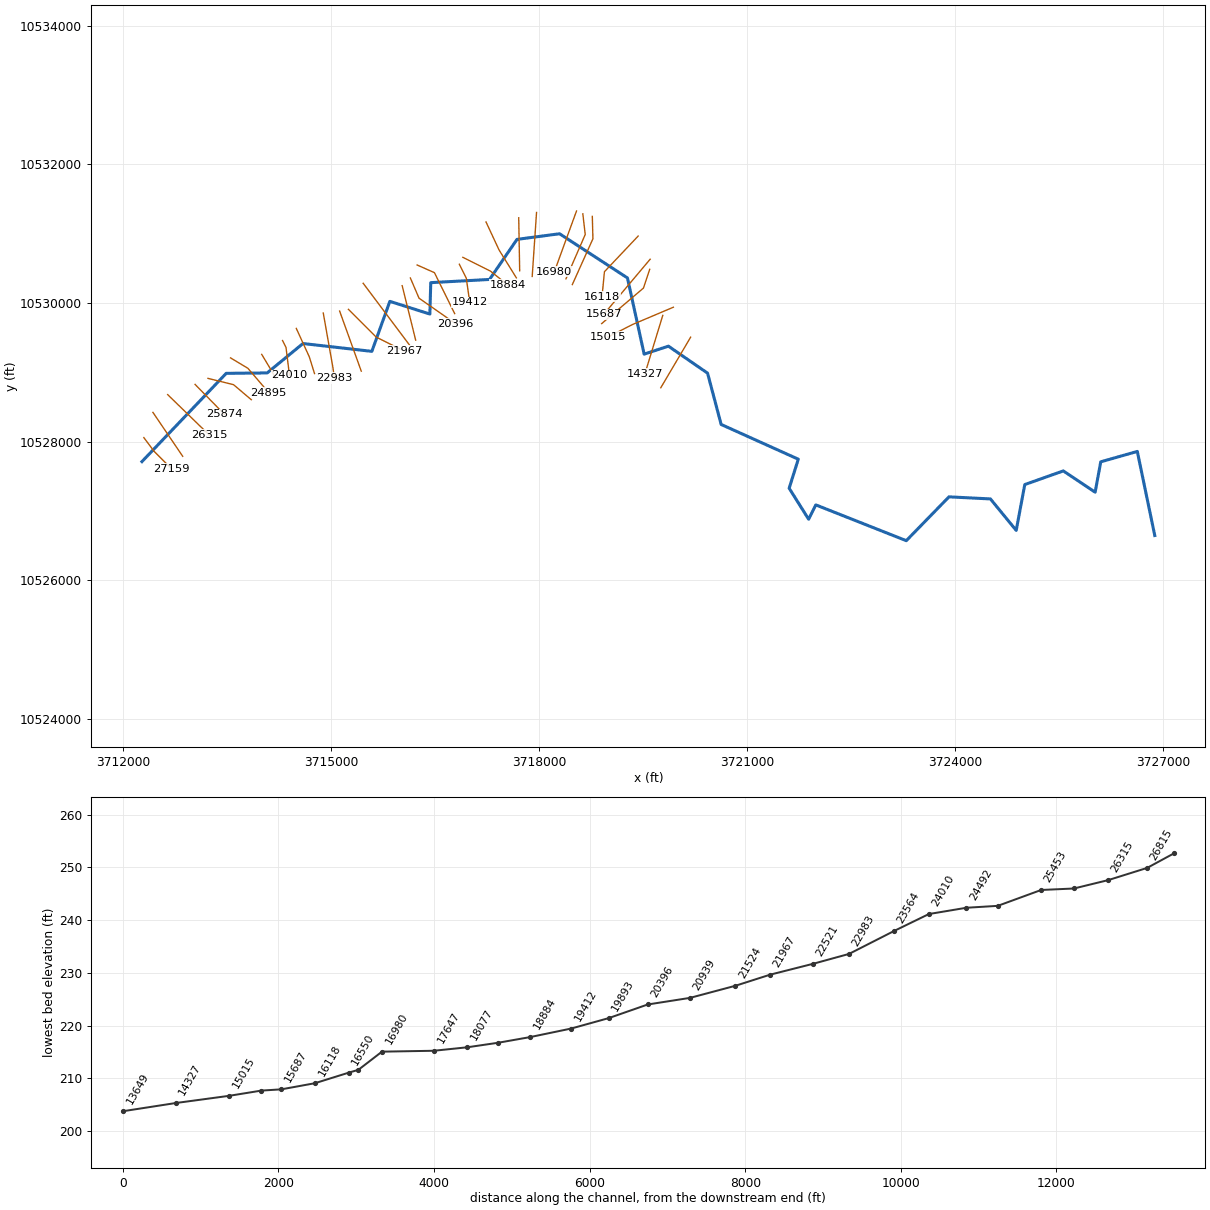
--- KINNON CREEK.prj (project) ---

Proj Title=KINNON CREEK Base Level Engineering
Current Plan=p01
Default Exp/Contr=0.3,0.1
English Units
Geom File=g01
Flow File=f01
Plan File=p01
Y Axis Title=Elevation
X Axis Title(PF)=Main Channel Distance
X Axis Title(XS)=Station
BEGIN DESCRIPTION:
KINNON CREEK
END DESCRIPTION:
DSS Export Rating Curves= 0
DSS Export Rating Curve Sorted= 0
DSS Export Volume Flow Curves= 0
DXF OffsetX= 0
DXF OffsetY= 0
DXF ScaleX= 1
DXF ScaleY= 10

--- KINNON CREEK.p01 (plan) ---

Plan Title=Multiple Run
Short Identifier=Multiple
Geom File=g01
Flow File=f01
Subcritical Flow
K Sum by GR= 0
Std Step Tol= 0.01
Critical Tol= 0.01
Num of Std Step Trials= 20
Max Error Tol= 0.3
Flow Tol Ratio= 0.001
Split Flow NTrial= 30
Split Flow Tol= 0.02
Split Flow Ratio= 0.02
Log Output Level= 0
Friction Slope Method= 1
Unsteady Friction Slope Method= 2
Unsteady Bridges Friction Slope Method= 1
Parabolic Critical Depth
Global Vel Dist=  1 , 1 , 1
Global Log Level= 0
CheckData=True
Encroach Param= -1, 0, 0, 0
BEGIN DESCRIPTION:
Multiple Run
END DESCRIPTION:

--- KINNON CREEK.f01 (steady flow) ---

Flow Title=Multiple
Program Version=4.10
Number of Profiles= 7
Profile Names=10-year,25-year,50-year,1pct_min,100-year,1pct_plu,500-year
River Rch & RM=KINNON CREEK,Reach-1         ,27159
     966    1358    1692    1549    2095    2833    3225
River Rch & RM=KINNON CREEK,Reach-1         ,19412
    1128    1594    1994    1831    2476    3348    3833
River Rch & RM=KINNON CREEK,Reach-1         ,16118
    1269    1794    2243    2056    2781    3761    4295
Boundary for River Rch & Prof#=KINNON CREEK,Reach-1         , 1
Up Type= 0
Dn Type= 3
Dn Slope=0.0038
Boundary for River Rch & Prof#=KINNON CREEK,Reach-1         , 2
Up Type= 0
Dn Type= 3
Dn Slope=0.0038
Boundary for River Rch & Prof#=KINNON CREEK,Reach-1         , 3
Up Type= 0
Dn Type= 3
Dn Slope=0.0038
Boundary for River Rch & Prof#=KINNON CREEK,Reach-1         , 4
Up Type= 0
Dn Type= 3
Dn Slope=0.0038
Boundary for River Rch & Prof#=KINNON CREEK,Reach-1         , 5
Up Type= 0
Dn Type= 3
Dn Slope=0.0038
Boundary for River Rch & Prof#=KINNON CREEK,Reach-1         , 6
Up Type= 0
Dn Type= 3
Dn Slope=0.0038
Boundary for River Rch & Prof#=KINNON CREEK,Reach-1         , 7
Up Type= 0
Dn Type= 3
Dn Slope=0.0038
DSS Import GetInterval= 0
DSS Import GetPeak= 0
DSS Import FillOption= 0

--- KINNON CREEK.g01 (geometry) ---

Geom Title=Existing Conditions
Program Version=4.10

River Reach=KINNON CREEK    ,Reach-1
Reach XY= 30
        3712272.       10527714.       3713487.5       10528987.
      3714078.25       10528993.      3714594.25       10529417.
      3715587.75       10529304.        3715847.       10530025.
       3716424.5       10529842.        3716437.       10530295.
       3717284.5       10530341.      3717680.75       10530919.
      3718294.75       10531000.      3719273.75       10530363.
       3719514.5       10529264.      3719864.25       10529379.
      3720428.75       10528990.        3720625.       10528250.
      3721737.25       10527749.      3721605.75       10527330.
       3721886.5       10526883.       3721989.5       10527090.
      3723294.75       10526574.       3723910.5       10527206.
      3724508.25       10527176.        3724880.       10526722.
       3725003.5       10527383.        3725559.       10527580.
      3726018.25       10527273.      3726099.25       10527711.
      3726626.25       10527861.       3726878.2     10526648.07

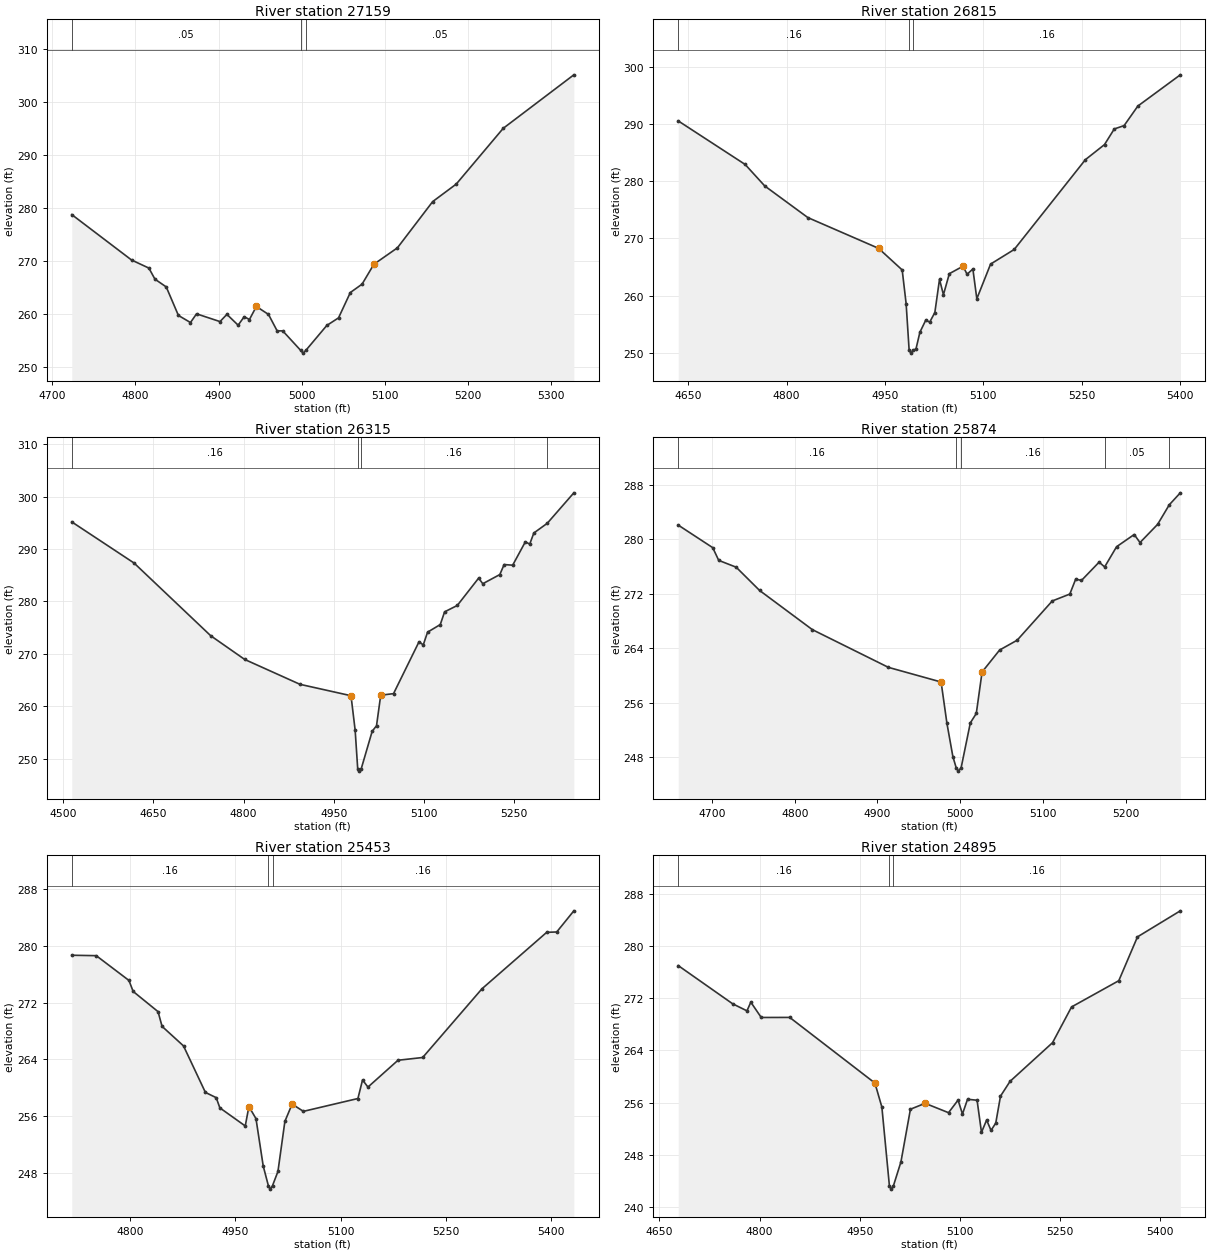
Type RM Length L Ch R = 1 ,27159   ,344,344,344
BEGIN DESCRIPTION:
KINNON CREEK 53.0
END DESCRIPTION:
XS GIS Cut Line= 3
      3712299.59     10528060.21      3712449.61     10527860.19
      3712699.62     10527610.18
#Sta/Elev= 30
  4723.6  278.78  4795.5  270.21  4816.3  268.69  4823.6   266.6  4837.2  265.13
  4851.8  259.76  4866.3  258.42  4873.6  260.06  4901.8   258.6  4910.1  259.96
  4923.6  257.92  4930.9  259.52  4937.2  258.99  4945.5  261.45  4960.1  259.95
  4970.5  256.85  4977.2  256.85  4998.9  253.15  5001.7  252.65  5004.9  253.15
  5030.2  257.87  5044.3   259.3  5058.5  264.08  5072.6  265.66  5086.8  269.41
  5115.1  272.51  5157.5  281.23  5185.8  284.53  5242.3  295.05  5327.2  305.14
#Mann= 3 ,-1 , 0
  4723.6     .05       0  4998.9    .035       0  5004.9     .05       0
Bank Sta=4945.5,5086.8
XS Rating Curve= 0 ,0
Exp/Cntr=0.3,0.1

Type RM Length L Ch R = 1 ,26815   ,500,500,500
BEGIN DESCRIPTION:
KINNON CREEK 52.0
END DESCRIPTION:
XS GIS Cut Line= 2
      3712430.42     10528424.06       3712860.1      10527790.4
#Sta/Elev= 30
  4634.8  290.61  4736.8  282.98  4766.7  279.21  4832.5  273.66  4940.3  268.27
  4976.3  264.48  4982.3  258.59  4986.9   250.4  4989.6   249.9  4992.9   250.4
  4997.3  250.62  5003.3  253.56  5012.2  255.67  5018.3  255.34  5026.1  257.02
  5033.2  262.83  5039.2  260.14  5048.2  263.83  5069.1  265.14  5075.2  263.73
  5084.1  264.64  5090.1  259.43  5111.1  265.51  5147.1  268.07  5255.7  283.82
  5284.8  286.46  5299.7   289.2  5314.7  289.79  5335.7  293.22  5400.4  298.69
#Mann= 3 ,-1 , 0
  4634.8     .16       0  4986.9     .07       0  4992.9     .16       0
Bank Sta=4940.3,5069.1
XS Rating Curve= 0 ,0
Exp/Cntr=0.3,0.1

Type RM Length L Ch R = 1 ,26315   ,441,441,441
BEGIN DESCRIPTION:
KINNON CREEK 51.0
END DESCRIPTION:
XS GIS Cut Line= 2
      3712643.09     10528680.14        3713242.     10528098.59
#Sta/Elev= 30
  4514.4  295.19    4618  287.33  4745.4  273.45  4801.9  268.92  4893.8  264.17
  4978.7  261.99  4985.6  255.38  4989.8  248.09  4992.6  247.59  4995.8  248.09
  5013.9   255.2  5021.1  256.26  5028.1  262.09  5049.4  262.39  5091.8   272.3
  5098.8  271.69    5106  274.13  5127.1  275.58  5134.3  278.01  5155.4  279.23
  5190.9  284.45  5197.8  283.38  5226.1  285.13  5233.3  287.04  5247.5  286.92
  5268.6  291.39  5275.8  290.94  5282.7  293.07    5305  294.92  5349.2  300.74
#Mann= 4 ,-1 , 0
  4514.4     .16       0  4989.8     .07       0  4995.8     .16       0
    5305     .05       0
Bank Sta=4978.7,5028.1
XS Rating Curve= 0 ,0
Exp/Cntr=0.3,0.1

Type RM Length L Ch R = 1 ,25874   ,421,421,421
BEGIN DESCRIPTION:
KINNON CREEK 50.0
END DESCRIPTION:
XS GIS Cut Line= 2
      3713038.06     10528827.71      3713462.64     10528394.47
#Sta/Elev= 30
  4659.3  282.06    4701  278.75  4708.2  276.89  4729.3  275.89  4757.6  272.48
  4821.3  266.74  4913.2  261.21  4976.9  259.06  4983.9  253.03  4991.1  248.14
  4995.1   246.5  4997.8     246  5001.1   246.5  5012.2  253.07  5019.4  254.45
  5026.4  260.53  5047.6  263.75  5068.8  265.19  5111.2  270.94  5132.4  271.95
  5139.5  274.14  5146.5  273.95  5167.8  276.63  5174.5  275.93  5188.9  278.89
  5210.2  280.68  5217.2   279.5  5238.5  282.17  5252.6  285.04  5265.9  286.79
#Mann= 5 ,-1 , 0
  4659.3     .16       0  4995.1     .07       0  5001.1     .16       0
  5174.5     .05       0  5252.6     .16       0
Bank Sta=4976.9,5026.4
XS Rating Curve= 0 ,0
Exp/Cntr=0.3,0.1

Type RM Length L Ch R = 1 ,25453   ,558,558,558
BEGIN DESCRIPTION:
KINNON CREEK 49.0
END DESCRIPTION:
XS GIS Cut Line= 3
      3713224.64     10528914.54       3713593.6     10528823.39
      3713849.66     10528606.39
#Sta/Elev= 30
  4716.7  278.68  4751.6  278.62  4798.2  275.13  4804.2  273.58  4839.7  270.73
  4845.4  268.66    4876   265.9  4907.2  259.35  4922.6  258.61  4927.8  257.17
    4964  254.62  4969.2  257.36  4979.3  255.65  4989.6  248.98  4996.9  246.22
  4999.7  245.72  5002.9  246.22  5010.6  248.21  5020.5  255.27  5030.8   257.7
  5046.9  256.68  5124.6  258.49  5131.2  261.11  5138.9   260.1  5181.7  263.88
  5216.9  264.27  5301.4  273.95  5393.7  281.91    5408  281.96  5432.4  284.94
#Mann= 3 ,-1 , 0
  4716.7     .16       0  4996.9     .07       0  5002.9     .16       0
Bank Sta=4969.2,5030.8
XS Rating Curve= 0 ,0
Exp/Cntr=0.3,0.1

Type RM Length L Ch R = 1 ,24895   ,403,403,403
BEGIN DESCRIPTION:
KINNON CREEK 48.0
END DESCRIPTION:
XS GIS Cut Line= 3
      3713549.64     10529210.17      3713799.61     10529060.19
      3714099.62     10528710.18
#Sta/Elev= 30
  4678.1  277.04  4759.7  271.17  4781.1  270.09  4786.9  271.42  4802.5  269.07
  4845.2  269.08  4972.9     259  4983.3  255.31  4994.6  243.21  4997.3  242.71
  5000.6  243.21  5011.9   246.9  5026.1  254.98  5048.1  255.89  5083.2  254.45
  5097.5  256.38  5104.1  254.24  5111.7  256.51    5126  256.36  5132.6  251.43
  5140.3  253.32  5146.9  251.73    5154  252.85  5161.1  256.99  5175.4  259.26
  5239.1   265.2  5267.6  270.69  5338.4  274.72  5366.4  281.45  5430.6  285.45
#Mann= 3 ,-1 , 0
  4678.1     .16       0  4994.6     .07       0  5000.6     .16       0
Bank Sta=4972.9,5048.1
XS Rating Curve= 0 ,0
Exp/Cntr=0.3,0.1

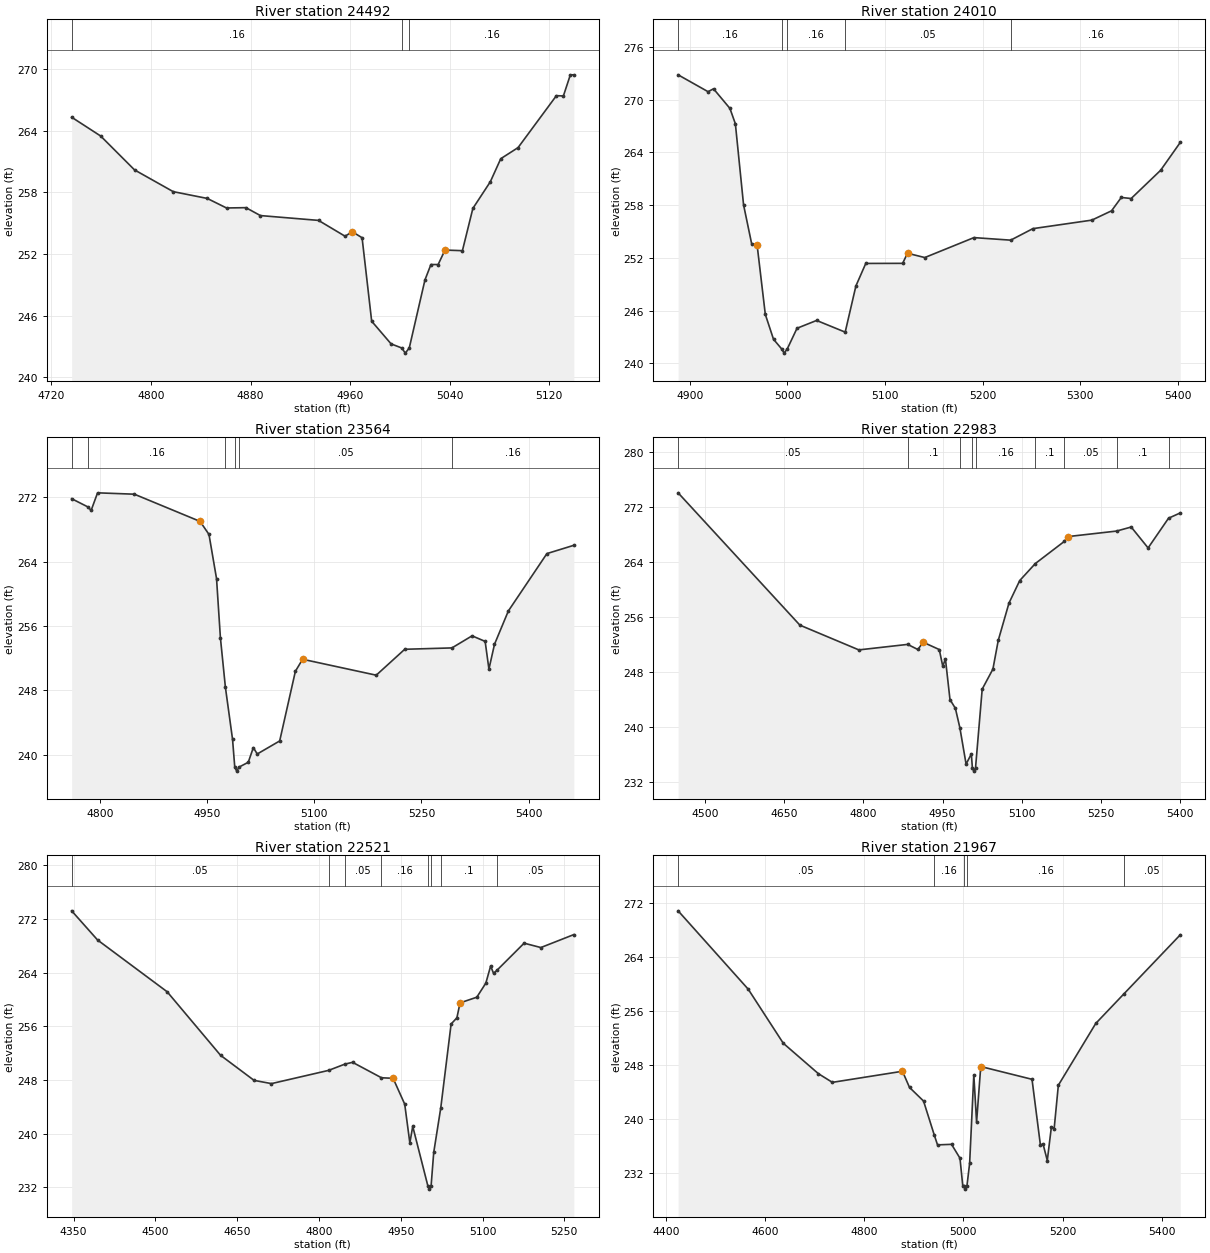
Type RM Length L Ch R = 1 ,24492   ,482,482,482
BEGIN DESCRIPTION:
KINNON CREEK 47.0
END DESCRIPTION:
XS GIS Cut Line= 3
       3713999.6      10529260.2      3714149.61     10529010.19
      3714199.62     10528910.16
#Sta/Elev= 30
  4736.3  265.33  4759.6   263.5  4786.8   260.2  4817.9  258.08  4845.2  257.42
  4860.7  256.49  4876.3  256.52  4887.9  255.75  4934.6  255.28  4955.9  253.74
  4961.8  254.17  4969.6  253.59  4977.3  245.46  4992.9  243.25  5001.5  242.85
  5004.3  242.35  5007.5  242.85  5020.1  249.48  5024.9  250.98  5030.7  250.98
  5036.2  252.39  5050.2  252.33  5058.6  256.45  5072.6  259.04    5081  261.29
  5094.9  262.37  5125.7  267.43  5131.3   267.4  5136.9  269.46  5139.7  269.46
#Mann= 3 ,-1 , 0
  4736.3     .16       0  5001.5     .07       0  5007.5     .16       0
Bank Sta=4961.8,5036.2
XS Rating Curve= 0 ,0
Exp/Cntr=0.3,0.1

Type RM Length L Ch R = 1 ,24010   ,446,446,446
BEGIN DESCRIPTION:
KINNON CREEK 46.0
END DESCRIPTION:
XS GIS Cut Line= 3
      3714299.62     10529460.17      3714349.61     10529360.19
      3714399.61     10528960.18
#Sta/Elev= 30
  4887.9  272.84  4918.6  270.92  4924.2  271.25    4941  269.02  4946.6  267.27
    4955  258.04  4963.3  253.61  4968.9  253.46  4977.3  245.57  4985.7  242.74
  4993.9  241.66  4996.6  241.16  4999.9  241.66  5009.8  243.99  5029.9  244.88
  5059.2  243.55  5070.2  248.81  5080.3  251.37  5118.1  251.38  5123.1  252.53
  5140.8  252.04  5191.2  254.31  5228.9  254.02  5251.6  255.33  5312.1   256.3
  5332.3  257.36  5342.3  258.88  5352.4  258.76  5382.6  261.97  5402.8  265.15
#Mann= 5 ,-1 , 0
  4887.9     .16       0  4993.9     .07       0  4999.9     .16       0
  5059.2     .05       0  5228.9     .16       0
Bank Sta=4968.9,5123.1
XS Rating Curve= 0 ,0
Exp/Cntr=0.3,0.1

Type RM Length L Ch R = 1 ,23564   ,581,581,581
BEGIN DESCRIPTION:
KINNON CREEK 45.0
END DESCRIPTION:
XS GIS Cut Line= 3
       3714498.1     10529635.05      3714685.61      10529225.3
       3714760.8     10528984.17
#Sta/Elev= 30
  4760.2  271.81  4782.9  270.79  4787.5  270.36  4796.5  272.54    4848  272.37
    4940  268.99  4952.5  267.37  4963.1  261.87  4968.5  254.53  4975.5  248.37
  4985.5  241.91  4988.6  238.46  4991.3  237.96  4994.6  238.46  5007.5  239.06
  5014.6  240.88  5020.1  240.09  5051.5  241.71  5073.5  250.37  5083.6  251.86
  5186.7  249.88  5226.6   253.1  5292.7  253.27  5320.9  254.77  5339.2  254.08
  5344.5  250.64  5352.3  253.72  5371.7  257.86  5425.7  264.99  5463.4  266.02
#Mann= 6 ,-1 , 0
  4760.2     .05       0  4782.9     .16       0  4975.5     .05       0
  4988.6     .03       0  4994.6     .05       0  5292.7     .16       0
Bank Sta=4940,5083.6
XS Rating Curve= 0 ,0
Exp/Cntr=0.3,0.1

Type RM Length L Ch R = 1 ,22983   ,462,462,462
BEGIN DESCRIPTION:
KINNON CREEK 44.0
END DESCRIPTION:
XS GIS Cut Line= 3
        3714887.     10529857.24      3715025.89     10529072.52
      3715046.72     10528919.75
#Sta/Elev= 30
  4449.2  274.05  4679.8  254.82  4791.5  251.22  4883.9  252.02  4903.2  251.28
  4913.4  252.33  4943.8  251.27  4950.4  248.86  4955.5  249.89  4964.1     244
  4974.3  242.73  4982.8  239.91  4994.6  234.62  5004.5  236.09  5006.5   234.1
  5009.3   233.6  5012.5   234.1  5025.1  245.52  5045.4  248.43  5055.5   252.6
  5075.8  258.02  5096.2   261.3  5125.7  263.77  5180.8     267  5187.5  267.69
  5279.5  268.49  5307.3  269.08  5339.3  266.04    5378  270.36  5400.3  271.13
#Mann= 9 ,-1 , 0
  4449.2     .05       0  4883.9      .1       0  4982.8     .16       0
  5006.5     .07       0  5012.5     .16       0  5125.7      .1       0
  5180.8     .05       0  5279.5      .1       0    5378     .16       0
Bank Sta=4913.4,5187.5
XS Rating Curve= 0 ,0
Exp/Cntr=0.3,0.1

Type RM Length L Ch R = 1 ,22521   ,554,554,554
BEGIN DESCRIPTION:
KINNON CREEK 43.0
END DESCRIPTION:
XS GIS Cut Line= 2
      3715123.11     10529885.02      3715435.11     10529018.37
#Sta/Elev= 30
  4346.4  273.19    4394  268.84  4521.6  261.13  4619.5  251.67    4681  247.93
  4712.9  247.45  4817.7  249.42  4847.8  250.36  4861.7  250.62  4914.7  248.32
    4936  248.24  4957.3  244.39  4966.7  238.61    4972  241.08  4999.7  232.23
  5002.5  231.73  5005.7  232.23  5010.5  237.19  5023.4  243.82  5042.4  256.33
    5053  257.25  5058.8  259.48  5089.5  260.32  5106.1  262.42  5114.9  264.97
  5120.2  263.88  5126.2  264.31  5176.3  268.37    5207  267.72  5267.5  269.65
#Mann= 8 ,-1 , 0
  4346.4     .05       0  4817.7      .1       0  4847.8     .05       0
  4914.7     .16       0  4999.7     .07       0  5005.7     .16       0
  5023.4      .1       0  5126.2     .05       0
Bank Sta=4936,5058.8
XS Rating Curve= 0 ,0
Exp/Cntr=0.3,0.1

Type RM Length L Ch R = 1 ,21967   ,443,443,443
BEGIN DESCRIPTION:
KINNON CREEK 42.0
END DESCRIPTION:
XS GIS Cut Line= 3
      3715249.62     10529910.17      3715649.61     10529510.19
      3716049.63     10529310.18
#Sta/Elev= 30
  4424.7  270.79  4566.1  259.21  4636.8  251.22  4707.5  246.73  4735.8  245.44
  4877.2  247.08  4891.4  244.69  4919.7  242.68  4941.3  237.67  4947.9   236.2
  4976.2  236.28  4993.2  234.23  4998.8  230.18  5001.3  230.16  5004.1  229.66
  5007.3  230.16  5012.7  233.48  5021.1  246.55  5026.7  239.57  5035.1  247.78
  5138.5  245.89  5155.3  236.25  5160.9  236.29  5169.3  233.89  5177.6  238.86
  5183.2  238.62  5191.6  245.01  5267.1  254.15  5323.9  258.52  5437.6  267.25
#Mann= 5 ,-1 , 0
  4424.7     .05       0  4941.3     .16       0  5001.3     .07       0
  5007.3     .16       0  5323.9     .05       0
Bank Sta=4877.2,5035.1
XS Rating Curve= 0 ,0
Exp/Cntr=0.3,0.1

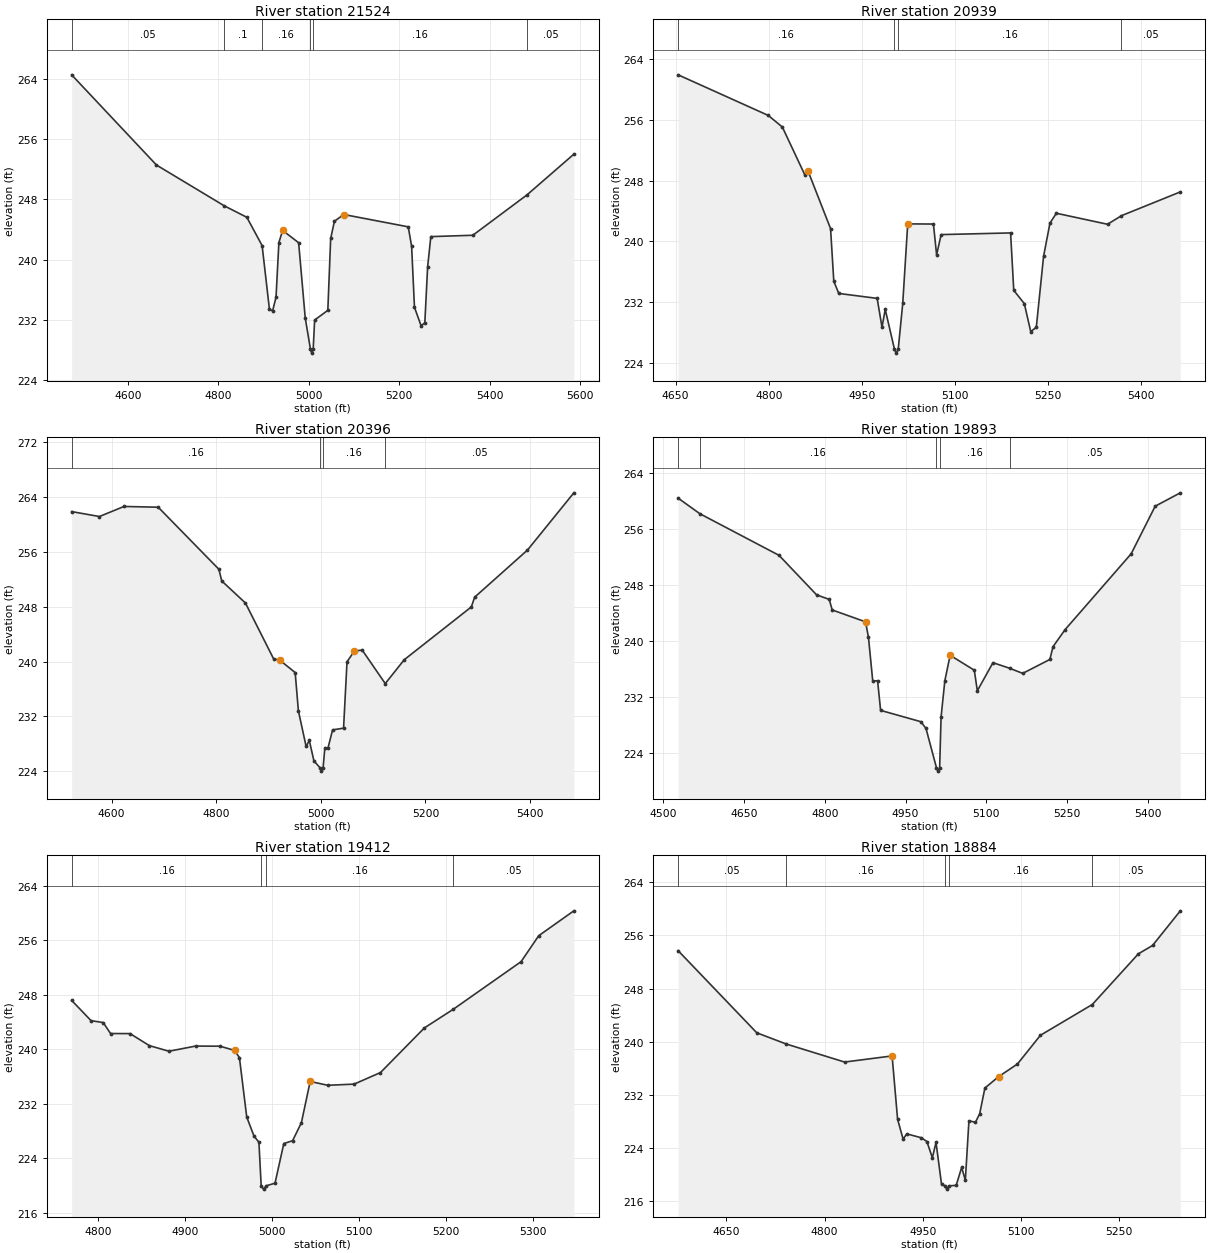
Type RM Length L Ch R = 1 ,21524   ,585,585,585
BEGIN DESCRIPTION:
KINNON CREEK 41.0
END DESCRIPTION:
XS GIS Cut Line= 2
      3715462.52     10530285.95      3716129.18     10529397.07
#Sta/Elev= 30
  4475.5  264.57  4663.1  252.58  4813.3  247.15  4863.1  245.63  4896.9  241.87
  4913.1   233.4  4920.2  233.19  4927.7  235.01    4934  242.27  4942.3  243.88
  4977.7  242.25  4992.3  232.25  5003.9  228.07  5006.6  227.57  5009.9  228.07
  5013.1  231.97  5042.3  233.26  5048.6  242.81  5056.9  245.11  5077.7     246
  5220.2  244.36  5227.7  241.77    5234  233.66  5248.6  231.22  5256.9   231.6
  5263.1  239.03  5270.2  243.06  5363.1  243.24    5483  248.61  5586.6  254.02
#Mann= 6 ,-1 , 0
  4475.5     .05       0  4813.3      .1       0  4896.9     .16       0
  5003.9     .07       0  5009.9     .16       0    5483     .05       0
Bank Sta=4942.3,5077.7
XS Rating Curve= 0 ,0
Exp/Cntr=0.3,0.1

Type RM Length L Ch R = 1 ,20939   ,543,543,543
BEGIN DESCRIPTION:
KINNON CREEK 40.0
END DESCRIPTION:
XS GIS Cut Line= 2
      3716025.03     10530251.17      3716219.46      10529466.5
#Sta/Elev= 30
  4654.2  261.92  4799.4  256.57    4822  255.04  4858.2  248.74  4863.4  249.24
  4899.6  241.67  4904.8  234.74  4912.8  233.13  4974.6  232.48  4982.4  228.68
  4987.6  231.02  5002.5  225.77  5005.2  225.27  5008.5  225.77  5015.8  231.82
  5023.8  242.29  5065.2  242.27  5070.3  238.21  5077.6  240.88  5189.4   241.1
  5194.5  233.54  5211.5  231.79  5221.8  228.11  5230.8  228.67  5242.5  238.02
  5252.8   242.4  5263.1  243.69  5345.5  242.24  5367.9  243.37  5462.6   246.5
#Mann= 4 ,-1 , 0
  4654.2     .16       0  5002.5     .07       0  5008.5     .16       0
  5367.9     .05       0
Bank Sta=4863.4,5023.8
XS Rating Curve= 0 ,0
Exp/Cntr=0.3,0.1

Type RM Length L Ch R = 1 ,20396   ,503,503,503
BEGIN DESCRIPTION:
KINNON CREEK 39.0
END DESCRIPTION:
XS GIS Cut Line= 3
      3716143.08     10530362.33      3716268.08     10530070.67
      3716795.23     10529703.05
#Sta/Elev= 30
  4523.6   261.9  4576.6  261.18  4623.7  262.65  4689.1  262.54  4805.1  253.48
  4810.5  251.78  4855.8  248.56  4909.8  240.39  4921.2  240.23  4950.9  238.41
    4957  232.84  4971.8  227.62  4977.9   228.5  4986.7  225.52  4998.3  224.52
    5001  224.02  5004.3  224.52  5007.6  227.41  5013.7  227.41  5022.4  230.04
  5043.4  230.29    5050  239.98  5064.3  241.57  5079.1  241.68  5123.1   236.8
  5159.4  240.28  5287.7  247.99  5293.9   249.4    5395  256.29  5483.6  264.64
#Mann= 4 ,-1 , 0
  4523.6     .16       0  4998.3     .07       0  5004.3     .16       0
  5123.1     .05       0
Bank Sta=4921.2,5064.3
XS Rating Curve= 0 ,0
Exp/Cntr=0.3,0.1

Type RM Length L Ch R = 1 ,19893   ,481,481,481
BEGIN DESCRIPTION:
KINNON CREEK 38.0
END DESCRIPTION:
XS GIS Cut Line= 3
      3716240.29     10530549.84       3716490.3     10530438.72
      3716781.97     10529848.44
#Sta/Elev= 30
  4527.9  260.47  4568.3  258.24  4715.2  252.29  4784.9  246.64  4808.3  245.99
  4813.9  244.48  4875.7  242.78  4881.2  240.55  4889.1  234.31  4898.1  234.36
  4903.7  230.12  4978.3   228.5  4987.9  227.54  5007.3  221.93    5010  221.43
  5013.3  221.93  5015.9  229.15  5022.9  234.35  5032.7     238  5077.6  235.86
  5083.2  232.92  5112.2  236.94  5143.2  236.14  5167.4  235.41  5217.8   237.4
  5223.7  239.23    5246  241.66  5368.7  252.51  5413.3  259.32  5459.9  261.23
#Mann= 5 ,-1 , 0
  4527.9     .05       0  4568.3     .16       0  5007.3     .07       0
  5013.3     .16       0  5143.2     .05       0
Bank Sta=4875.7,5032.7
XS Rating Curve= 0 ,0
Exp/Cntr=0.3,0.1

Type RM Length L Ch R = 1 ,19412   ,528,528,528
BEGIN DESCRIPTION:
KINNON CREEK 37.0
END DESCRIPTION:
XS GIS Cut Line= 3
      3716849.62     10530560.16      3716949.61     10530360.19
       3716999.6     10530010.22
#Sta/Elev= 30
  4769.9  247.18  4792.2   244.2  4806.2  243.92  4814.6  242.31    4837   242.3
  4859.3  240.53  4881.7  239.71  4912.4  240.47  4940.4  240.45  4957.1  239.83
  4962.7  238.77  4971.1  230.05  4979.5  227.24  4985.1  226.35  4987.7  219.96
  4990.4  219.46  4993.7  219.96  5003.6  220.33  5013.7  226.15  5023.8  226.57
  5033.9  229.21    5044  235.27  5064.2  234.71  5094.5  234.88  5124.8  236.58
  5175.3  243.14  5208.2  245.85  5286.4  252.87  5306.6  256.67    5347  260.33
#Mann= 4 ,-1 , 0
  4769.9     .16       0  4987.7     .07       0  4993.7     .16       0
  5208.2     .05       0
Bank Sta=4957.1,5044
XS Rating Curve= 0 ,0
Exp/Cntr=0.3,0.1

Type RM Length L Ch R = 1 ,18884   ,410,410,410
BEGIN DESCRIPTION:
KINNON CREEK 36.0
END DESCRIPTION:
XS GIS Cut Line= 3
      3716899.59      10530660.2      3717299.61     10530460.19
      3717549.62     10530260.18
#Sta/Elev= 30
  4576.2   253.7  4696.4  241.35  4741.2  239.67  4830.6  236.95  4903.2  237.87
  4911.6  228.33    4920  225.37  4925.6  226.15    4948  225.56  4956.4     225
  4964.7  222.55  4970.3  224.87  4978.7  218.59  4984.1  218.34  4986.8  217.84
  4990.1  218.34  5001.1   218.4  5009.5  221.11  5015.1  219.17  5020.6  228.12
  5030.6  227.89    5037  229.17    5045  233.04  5065.9  234.75  5094.7  236.65
  5129.9  240.98  5209.1   245.6  5279.6  253.23  5301.2  254.48  5343.6  259.69
#Mann= 5 ,-1 , 0
  4576.2     .05       0  4741.2     .16       0  4984.1     .07       0
  4990.1     .16       0  5209.1     .05       0
Bank Sta=4903.2,5065.9
XS Rating Curve= 0 ,0
Exp/Cntr=0.3,0.1

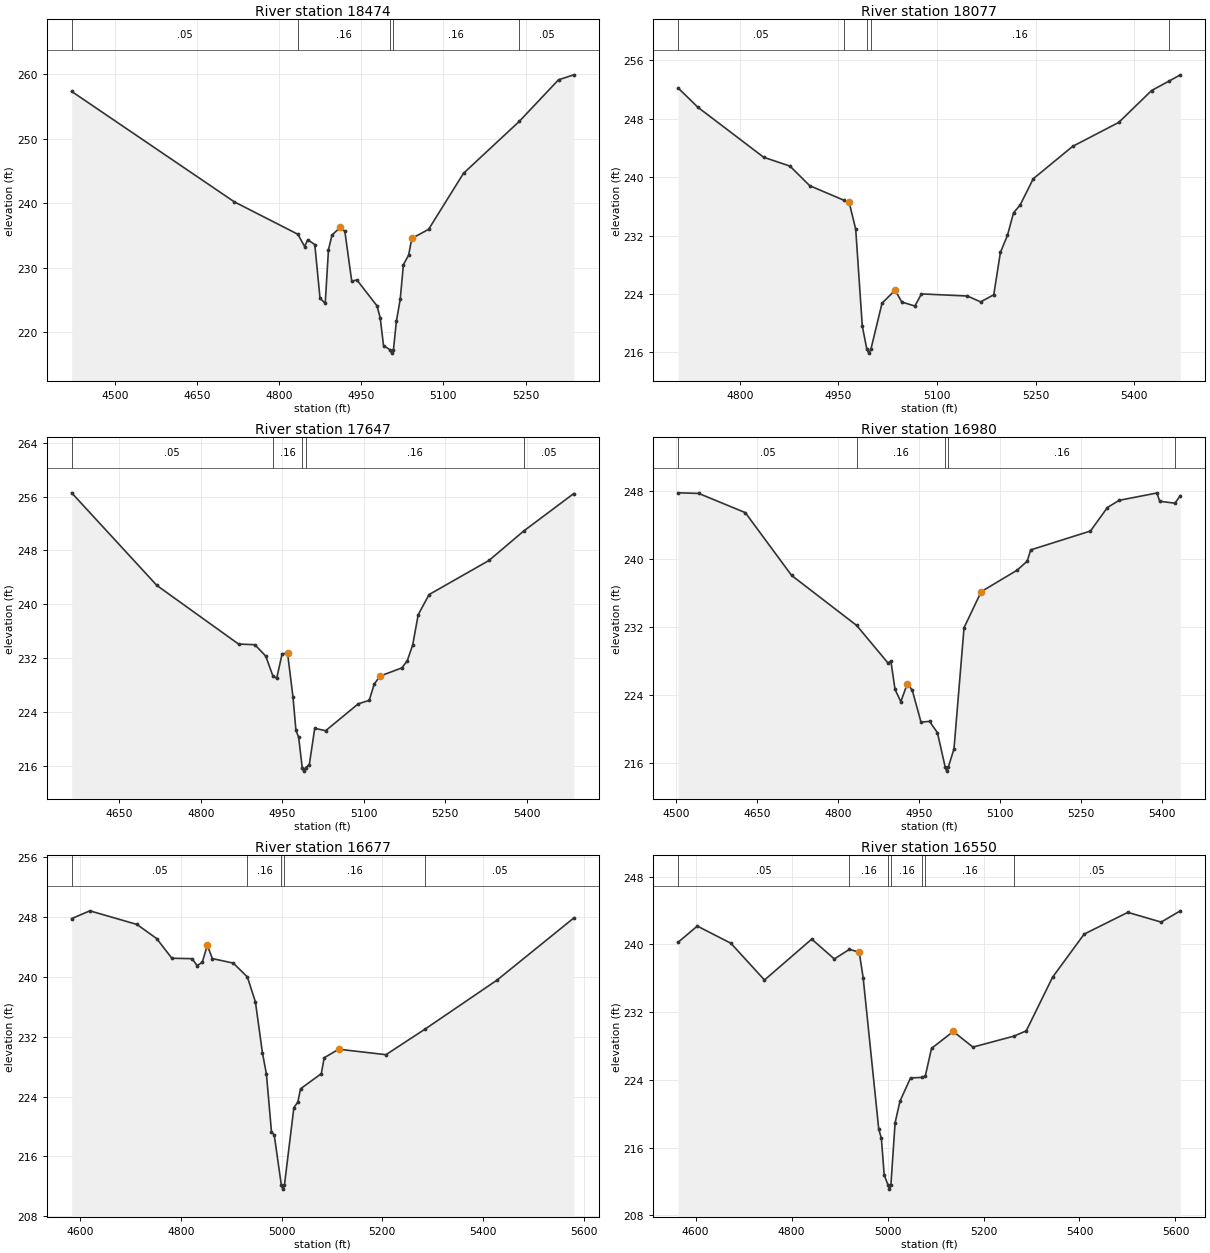
Type RM Length L Ch R = 1 ,18474   ,397,397,397
BEGIN DESCRIPTION:
KINNON CREEK 35.0
END DESCRIPTION:
XS GIS Cut Line= 3
      3717234.23     10531169.72      3717421.72     10530766.97
       3717671.4     10530364.71
#Sta/Elev= 30
  4420.6  257.34  4717.9  240.22  4833.9   235.2  4846.4  233.29  4851.9  234.35
  4864.9   233.6  4874.5  225.27    4884  224.49  4889.9   232.8  4896.4  235.07
  4911.1  236.25  4919.9  235.64  4932.4  227.93  4941.9  228.11  4978.5  224.11
  4984.4  222.26  4990.5  217.95  5002.6  217.27  5005.4  216.77  5008.6  217.27
  5014.1  221.76    5021   225.1  5026.9  230.49  5036.4  231.97  5042.2  234.55
  5072.9  235.96  5136.7  244.65  5238.4  252.68  5310.3  259.14  5338.3  259.91
#Mann= 5 ,-1 , 0
  4420.6     .05       0  4833.9     .16       0  5002.6     .07       0
  5008.6     .16       0  5238.4     .05       0
Bank Sta=4911.1,5042.2
XS Rating Curve= 0 ,0
Exp/Cntr=0.3,0.1

Type RM Length L Ch R = 1 ,18077   ,430,430,430
BEGIN DESCRIPTION:
KINNON CREEK 34.0
END DESCRIPTION:
XS GIS Cut Line= 2
      3717705.58     10531230.36      3717719.46     10530466.49
#Sta/Elev= 30
  4706.3  252.22  4736.5  249.57  4836.5  242.73  4876.5  241.52  4906.5  238.84
  4958.1  236.86  4966.5  236.57  4976.5  232.86  4986.5  219.61  4993.5  216.41
  4996.3  215.91  4999.5  216.41  5016.5  222.74  5036.5  224.54  5046.5  222.91
  5066.5  222.36  5076.5  224.02  5146.5  223.73  5166.5  222.93  5186.5   223.9
  5196.6   229.7  5207.4  232.05  5216.6  235.13  5226.6  236.19  5246.6  239.79
  5306.6  244.23  5376.6   247.5  5426.6  251.87  5452.9  253.15  5470.3  254.02
#Mann= 5 ,-1 , 0
  4706.3     .05       0  4958.1     .16       0  4993.5     .07       0
  4999.5     .16       0  5452.9     .05       0
Bank Sta=4966.5,5036.5
XS Rating Curve= 0 ,0
Exp/Cntr=0.3,0.1

Type RM Length L Ch R = 1 ,17647   ,667,667,667
BEGIN DESCRIPTION:
KINNON CREEK 33.0
END DESCRIPTION:
XS GIS Cut Line= 2
      3717962.52      10531306.8      3717900.09     10530384.21
#Sta/Elev= 30
  4562.2  256.55  4719.2   242.8  4869.5  234.11  4899.6  234.01  4919.6  232.32
  4932.6  229.41  4939.7  229.01  4949.7  232.63  4959.7  232.79  4969.7  226.29
  4975.2  221.31  4980.2  220.26  4986.8  215.75  4989.5  215.25  4992.8  215.75
  4999.8  216.22  5009.8   221.6  5029.9  221.25    5090  225.24  5110.1  225.75
  5119.4  228.18  5130.1  229.36  5170.2  230.57  5180.2  231.63  5190.2  233.99
  5200.3  238.45  5220.3  241.45  5330.6  246.51  5394.7  250.89  5486.9  256.45
#Mann= 5 ,-1 , 0
  4562.2     .05       0  4932.6     .16       0  4986.8     .07       0
  4992.8     .16       0  5394.7     .05       0
Bank Sta=4959.7,5130.1
XS Rating Curve= 0 ,0
Exp/Cntr=0.3,0.1

Type RM Length L Ch R = 1 ,16980   ,303,303,303
BEGIN DESCRIPTION:
KINNON CREEK 32.0
END DESCRIPTION:
XS GIS Cut Line= 2
      3718538.92     10531327.65      3718219.92     10530453.86
#Sta/Elev= 30
  4503.3   247.8  4541.5  247.73  4627.8  245.47  4713.5  238.09    4834  232.21
  4892.1  227.79  4897.4  228.02  4905.1  224.69  4915.8  223.24  4927.9  225.37
  4937.1  224.57  4953.2  220.84    4969  220.93  4983.7  219.59  4997.9  215.58
  5000.7  215.08  5003.9  215.58  5014.3  217.69  5032.9  231.94  5064.7  236.18
  5131.1   238.7    5150  239.77  5156.3  241.09  5267.1  243.31  5298.4  246.07
  5320.3  246.92  5390.1  247.78  5395.4  246.81  5423.5  246.58  5433.5  247.47
#Mann= 5 ,-1 , 0
  4503.3     .05       0    4834     .16       0  4997.9     .07       0
  5003.9     .16       0  5423.5     .05       0
Bank Sta=4927.9,5064.7
XS Rating Curve= 0 ,0
Exp/Cntr=0.3,0.1

Type RM Length L Ch R = 1 ,16677   ,127,127,127
BEGIN DESCRIPTION:
KINNON CREEK 31.0
END DESCRIPTION:
XS GIS Cut Line= 3
      3718630.05     10531287.82      3718664.78     10530989.19
      3718387.01     10530350.31
#Sta/Elev= 30
  4583.2  247.76  4619.3   248.8    4713  246.98    4752   245.1  4782.2  242.47
  4822.4  242.41  4832.5  241.47  4842.6  241.94  4852.6  244.19  4862.7  242.42
  4904.2  241.82  4932.2  239.97  4948.2  236.62    4962  229.88    4970     227
    4980  219.32  4985.5  218.87  4999.7  212.14  5002.5  211.64  5005.7  212.14
  5024.5  222.52  5032.4  223.27  5037.8  225.04    5079  227.06  5084.7  229.18
  5113.6  230.32  5207.4  229.59  5285.5  233.03    5428  239.55  5580.5  247.85
#Mann= 5 ,-1 , 0
  4583.2     .05       0  4932.2     .16       0  4999.7     .07       0
  5005.7     .16       0  5285.5     .05       0
Bank Sta=4852.6,5113.6
XS Rating Curve= 0 ,0
Exp/Cntr=0.3,0.1

Type RM Length L Ch R = 1 ,16550   ,432,432,432
BEGIN DESCRIPTION:
Mapping XS 64c3b347
END DESCRIPTION:
XS GIS Cut Line= 3
      3718767.04     10531250.13      3718775.72     10530927.21
      3718478.83     10530267.46
#Sta/Elev= 30
  4563.6  240.24  4603.6  242.15  4673.6  240.12  4743.6  235.78    4842  240.61
  4889.1  238.27  4920.3  239.39  4940.9  239.09  4949.2  236.06  4981.7  218.16
  4987.2  217.09    4993  212.77    5001  211.59  5003.7  211.09    5007  211.59
  5015.8  218.94  5025.9  221.47  5047.9  224.22  5072.1  224.28  5078.6  224.43
  5091.7  227.71    5137  229.71  5177.9  227.86  5263.6  229.16  5289.1  229.78
  5343.9  236.11  5409.7   241.2  5500.7  243.77  5570.2  242.62  5610.1  243.95
#Mann= 7 ,-1 , 0
  4563.6     .05       0  4920.3     .16       0    5001     .07       0
    5007     .16       0  5072.1     .12       0  5078.6     .16       0
  5263.6     .05       0
Bank Sta=4940.9,5137
XS Rating Curve= 0 ,0
Exp/Cntr=0.3,0.1

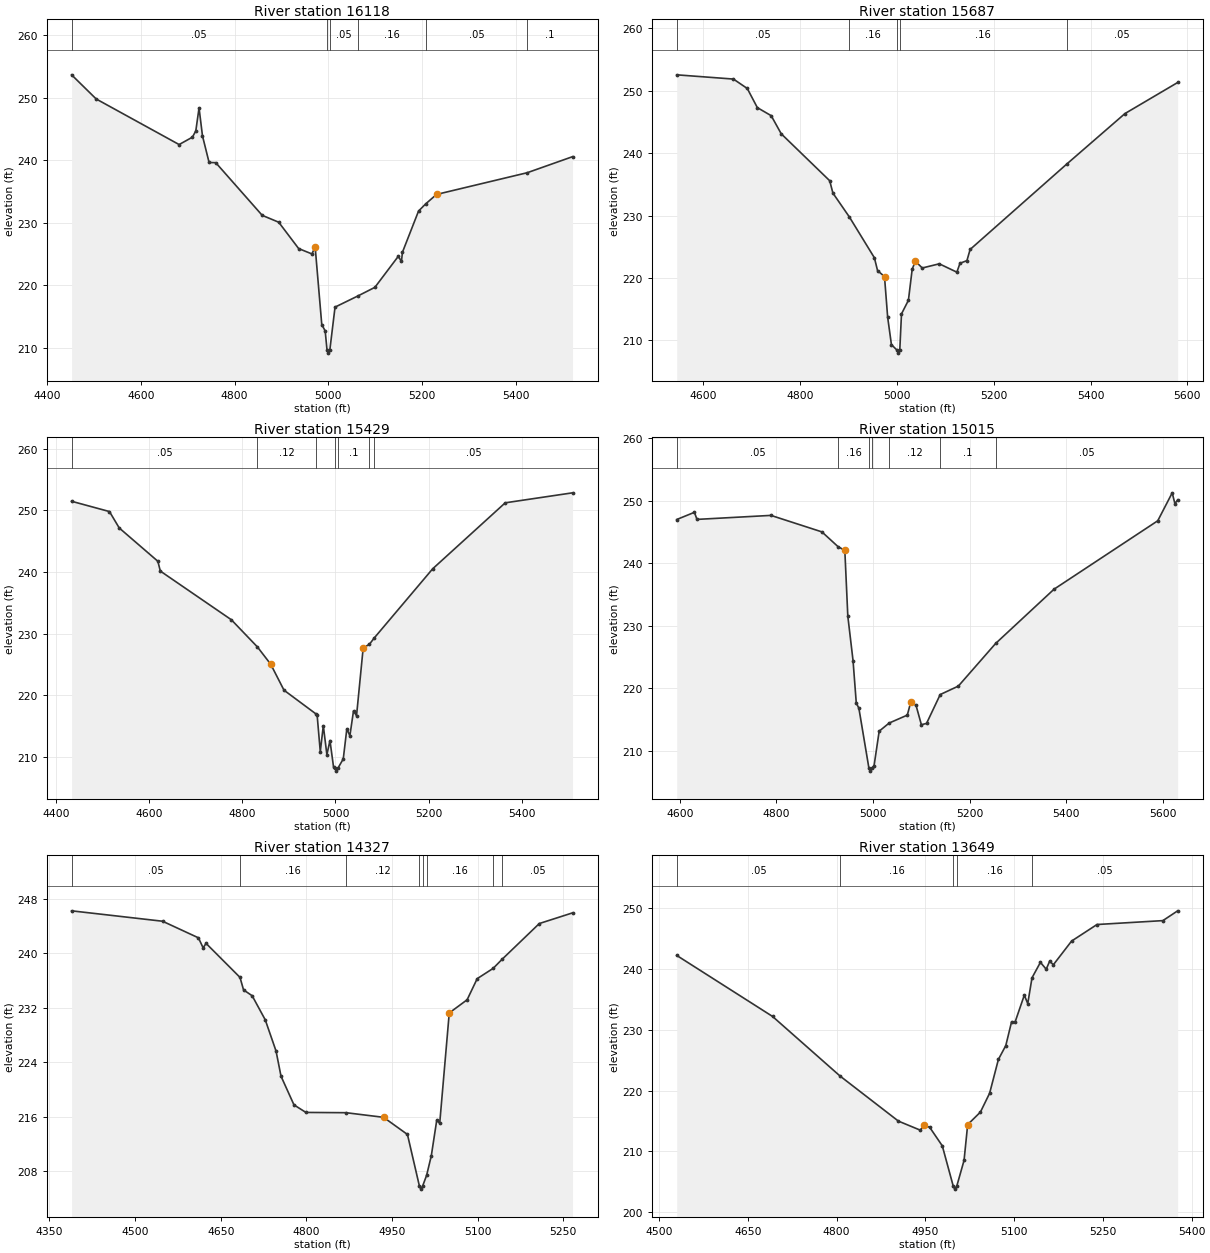
Type RM Length L Ch R = 1 ,16118   ,431,431,431
BEGIN DESCRIPTION:
KINNON CREEK 30.0
END DESCRIPTION:
XS GIS Cut Line= 3
      3719427.77     10530966.47      3718941.69     10530452.61
      3718907.14      10530093.3
#Sta/Elev= 30
  4452.3  253.68  4504.8  249.81  4681.6  242.51  4709.9  243.69  4717.2   244.7
  4724.1  248.38  4731.4  243.91  4745.5  239.64  4759.7  239.61  4858.8  231.17
    4894  230.07  4936.5  225.85  4964.8  224.99  4971.7  226.11  4985.8  213.68
  4993.1  212.65    4997   209.6  4999.7   209.1    5003   209.6  5014.1  216.47
    5064   218.3  5099.1  219.64  5148.9   224.6  5155.7   223.8  5157.9  225.27
  5192.2  231.86  5207.3     233  5230.5  234.52    5424     238  5520.6  240.57
#Mann= 6 ,-1 , 0
  4452.3     .05       0    4997    .035       0    5003     .05       0
    5064     .16       0  5207.3     .05       0    5424      .1       0
Bank Sta=4971.7,5230.5
XS Rating Curve= 0 ,0
Exp/Cntr=0.3,0.1

Type RM Length L Ch R = 1 ,15687   ,258,258,258
BEGIN DESCRIPTION:
KINNON CREEK 29.0
END DESCRIPTION:
XS GIS Cut Line= 2
      3719601.43     10530633.19      3718934.75     10529841.51
#Sta/Elev= 30
  4545.1  252.56  4662.3  251.88  4690.9  250.37  4711.7   247.3  4740.3  246.01
  4761.1   243.1  4861.2  235.58  4867.8   233.6    4902  229.75  4953.5  223.23
  4960.1  221.16  4974.4  220.22  4980.9  213.72  4988.7   209.3    5000  208.44
  5002.7  207.94    5006  208.44  5009.5  214.23  5023.8  216.41  5031.6  221.38
  5038.1  222.69  5052.4  221.59  5087.6  222.26  5123.9  220.92  5130.4  222.35
  5144.7  222.77  5151.3  224.56  5350.6  238.23  5471.2  246.35  5580.1  251.33
#Mann= 5 ,-1 , 0
  4545.1     .05       0    4902     .16       0    5000     .07       0
    5006     .16       0  5350.6     .05       0
Bank Sta=4974.4,5038.1
XS Rating Curve= 0 ,0
Exp/Cntr=0.3,0.1

Type RM Length L Ch R = 1 ,15429   ,414,414,414
BEGIN DESCRIPTION:
KINNON CREEK 28.0
END DESCRIPTION:
XS GIS Cut Line= 3
      3719594.48     10530487.37      3719504.19      10530216.5
      3718901.53     10529703.89
#Sta/Elev= 30
  4432.9  251.47  4514.3   249.8  4535.3  247.14  4618.3  241.74  4623.6  240.15
  4776.3  232.25  4832.2  227.85  4860.8  225.05  4889.4  220.83  4957.9  216.99
  4960.7  216.75  4967.4  210.84  4973.9  215.07  4981.6  210.37  4988.2  212.66
  4995.9  208.38  4999.5   208.2  5002.2   207.7  5005.5   208.2  5016.8  209.68
  5024.5  214.58    5031  213.42  5038.8  217.47  5045.3  216.68  5059.6  227.68
  5073.1  228.28  5083.5  229.31    5209  240.52  5364.9  251.22  5509.6  252.84
#Mann= 7 ,-1 , 0
  4432.9     .05       0  4832.2     .12       0  4957.9      .1       0
  4999.5     .07       0  5005.5      .1       0  5073.1     .16       0
  5083.5     .05       0
Bank Sta=4860.8,5059.6
XS Rating Curve= 0 ,0
Exp/Cntr=0.3,0.1

Type RM Length L Ch R = 1 ,15015   ,688,688,688
BEGIN DESCRIPTION:
KINNON CREEK 27.0
END DESCRIPTION:
XS GIS Cut Line= 3
      3719935.64     10529940.59      3719345.33     10529690.58
      3718992.86     10529510.88
#Sta/Elev= 30
  4593.8  246.96  4630.4  248.11  4635.8  246.98  4788.8  247.62  4894.3  244.98
  4927.8  242.61  4941.7  242.03  4947.9  231.49  4958.7   224.4  4965.4  217.61
  4970.8  216.77  4991.5  207.21  4994.3  206.71  4997.5  207.21  5002.2  207.57
  5012.8   213.1  5033.4   214.4    5071  215.67  5078.2  217.77    5089  217.25
  5100.1  214.14  5110.8  214.34  5139.1  218.96  5176.6  220.31  5253.9  227.14
  5374.6  235.81  5589.3  246.76  5619.2  251.23  5624.8  249.49  5630.5  250.11
#Mann= 7 ,-1 , 0
  4593.8     .05       0  4927.8     .16       0  4991.5     .07       0
  4997.5     .16       0  5033.4     .12       0  5139.1      .1       0
  5253.9     .05       0
Bank Sta=4941.7,5078.2
XS Rating Curve= 0 ,0
Exp/Cntr=0.3,0.1

Type RM Length L Ch R = 1 ,14327   ,678,678,678
BEGIN DESCRIPTION:
KINNON CREEK 26.0
END DESCRIPTION:
XS GIS Cut Line= 2
      3719782.84     10529822.54      3719526.33     10528983.68
#Sta/Elev= 30
  4388.9  246.27  4548.2  244.74    4611   242.3  4619.2  240.83  4624.4  241.48
  4683.8  236.48    4690  234.64  4705.1  233.78    4728  230.24  4746.9  225.65
  4755.6  221.95  4778.3  217.73  4799.2  216.62  4869.5  216.58  4935.2   215.9
    4977  213.38  4997.8  205.84  5000.5  205.34  5003.8  205.84  5010.6  207.38
  5018.8  210.26  5028.3  215.48  5033.5  215.03  5050.2  231.25  5081.5  233.19
  5099.1  236.29  5127.1  237.81  5142.7  239.14  5207.9   244.4  5266.1  245.97
#Mann= 8 ,-1 , 0
  4388.9     .05       0  4683.8     .16       0  4869.5     .12       0
  4997.8     .07       0  5003.8     .12       0  5010.6     .16       0
  5127.1      .1       0  5142.7     .05       0
Bank Sta=4935.2,5050.2
XS Rating Curve= 0 ,0
Exp/Cntr=0.3,0.1

Type RM Length L Ch R = 1 ,13649   ,419,419,419
BEGIN DESCRIPTION:
KINNON CREEK 25.0
END DESCRIPTION:
XS GIS Cut Line= 2
      3720184.77     10529508.21      3719754.41     10528779.38
#Sta/Elev= 30
    4530  242.21  4691.9  232.18    4806  222.38  4904.6  214.97  4941.6  213.48
  4947.5  214.25  4957.3  213.97  4978.7  210.91  4997.2  204.29  4999.9  203.79
  5003.2  204.29  5015.5  208.52  5021.6   214.4  5043.1  216.45  5058.7  219.56
  5073.5  225.11    5086  227.39  5095.8  231.31  5101.6  231.23  5117.3  235.68
  5123.1  234.29  5130.3  238.53  5144.5  241.07  5154.3  239.94  5160.1  241.26
  5166.4  240.68  5197.2  244.57  5240.1  247.29  5351.4  247.93  5376.4  249.54
#Mann= 5 ,-1 , 0
    4530     .05       0    4806     .16       0  4997.2     .07       0
  5003.2     .16       0  5130.3     .05       0
Bank Sta=4947.5,5021.6
XS Rating Curve= 0 ,0
Exp/Cntr=0.3,0.1