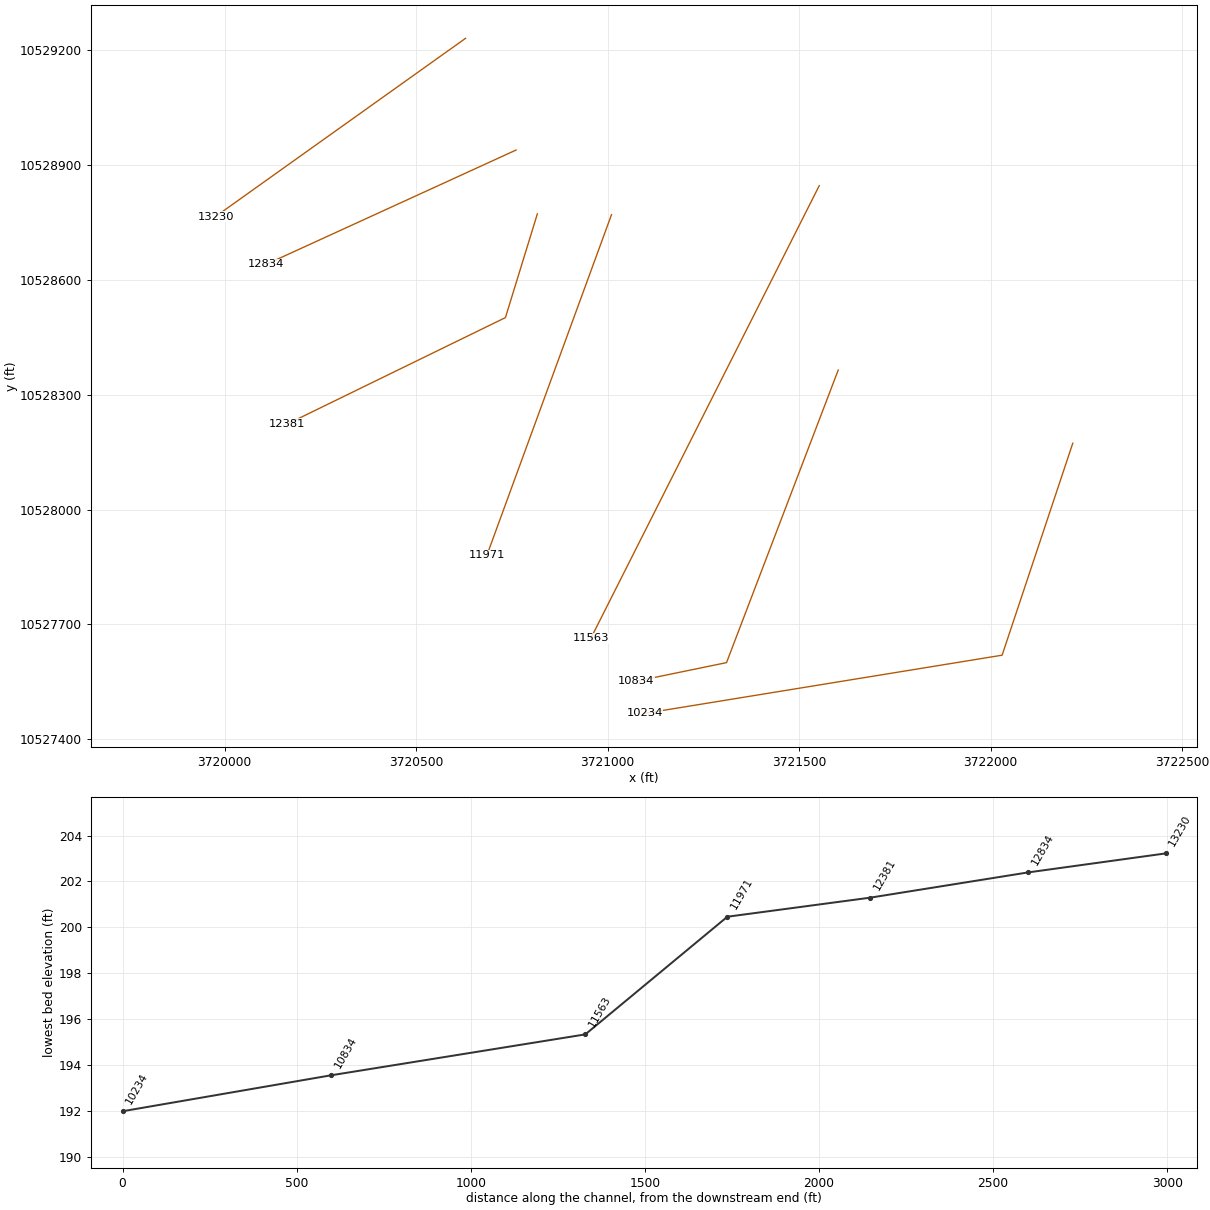
HEC-RAS study KINNON CREEK.prj: KINNON CREEK Base Level Engineering

--- KINNON CREEK.g01 (geometry) --- (continued)

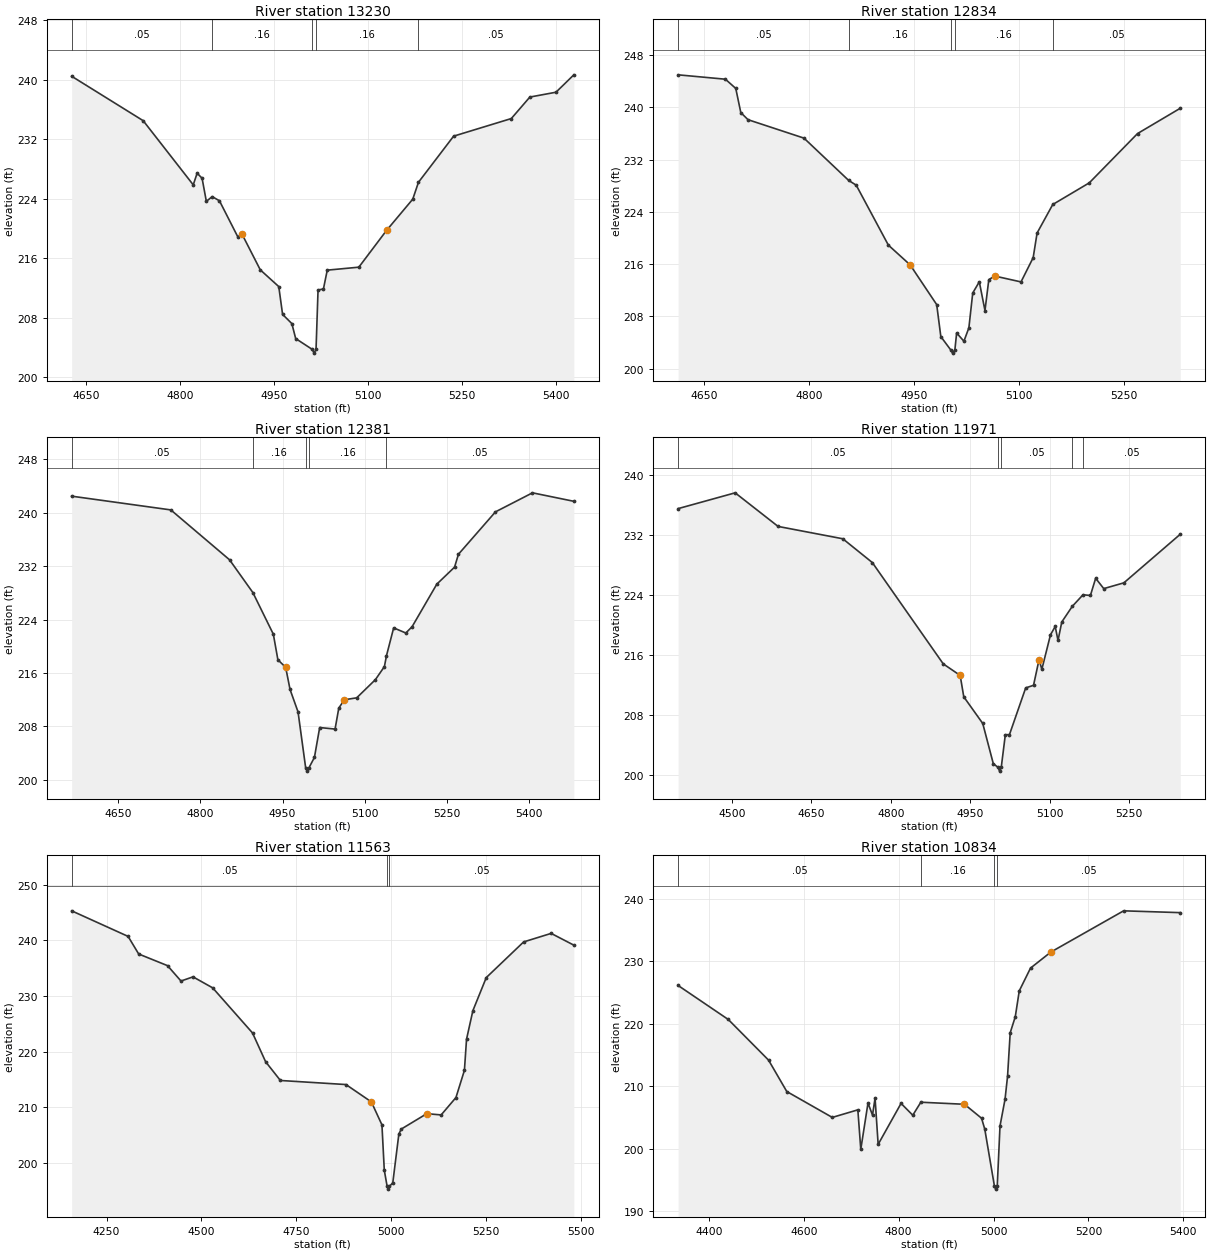
Type RM Length L Ch R = 1 ,13230   ,396,396,396
BEGIN DESCRIPTION:
KINNON CREEK 24.0
END DESCRIPTION:
XS GIS Cut Line= 2
      3720629.18     10529230.38      3719976.42     10528765.12
#Sta/Elev= 30
  4627.4  240.46  4741.6  234.48  4821.5  225.85  4827.7  227.42  4835.6  226.74
  4842.4  223.63  4851.7  224.27  4863.3  223.71  4892.8  218.83    4899  219.28
  4928.5  214.42    4958  212.17  4964.1  208.43  4978.9  207.19    4985  205.18
  5011.5  203.72  5014.3  203.22  5017.5  203.72  5020.7  211.71  5029.3  211.85
  5035.4  214.38  5085.8  214.78  5130.1  219.73  5171.9  223.93    5181   226.2
  5237.1   232.4  5329.2  234.77  5358.8  237.66  5400.5  238.31    5429  240.65
#Mann= 5 ,-1 , 0
  4627.4     .05       0  4851.7     .16       0  5011.5     .07       0
  5017.5     .16       0    5181     .05       0
Bank Sta=4899,5130.1
XS Rating Curve= 0 ,0
Exp/Cntr=0.3,0.1

Type RM Length L Ch R = 1 ,12834   ,453,453,453
BEGIN DESCRIPTION:
KINNON CREEK 23.0
END DESCRIPTION:
XS GIS Cut Line= 2
      3720761.11     10528938.71      3720108.37     10528640.12
#Sta/Elev= 30
  4613.1  244.95  4680.7  244.28  4695.5  242.87  4702.7  239.18    4713  238.09
    4793  235.27  4856.8  228.81  4867.7  228.07  4913.6  218.91  4944.7  215.89
  4982.7  209.81  4988.6  204.92  5002.7  202.89  5005.4  202.39  5008.7  202.89
  5011.2  205.47  5021.6  204.21  5028.7  206.26  5034.2  211.58  5043.6   213.3
  5051.7   208.9  5057.2  213.63  5065.6  214.18  5103.2  213.28  5120.6  216.99
  5126.2  220.76  5148.6  225.12  5200.8  228.43  5269.8  235.97  5330.9  239.84
#Mann= 5 ,-1 , 0
  4613.1     .05       0  4856.8     .16       0  5002.7     .07       0
  5008.7     .16       0  5148.6     .05       0
Bank Sta=4944.7,5065.6
XS Rating Curve= 0 ,0
Exp/Cntr=0.3,0.1

Type RM Length L Ch R = 1 ,12381   ,410,410,410
BEGIN DESCRIPTION:
KINNON CREEK 22.0
END DESCRIPTION:
XS GIS Cut Line= 3
       3720816.7     10528772.09      3720733.35     10528501.22
       3720163.9     10528223.44
#Sta/Elev= 30
  4564.8  242.48  4745.9  240.42  4853.1  232.95  4895.7  228.04  4933.1   221.8
  4941.4  217.97  4955.6  216.84  4963.6  213.52  4978.2  210.16  4992.1  201.79
  4994.9  201.29  4998.1  201.79  5008.1  203.34  5017.7  207.82  5045.8  207.59
  5052.6  210.73  5062.7  211.98  5085.3  212.27  5119.4  214.99  5135.9  216.95
  5139.7  218.59  5152.8  222.75    5175  221.98  5186.5  222.93  5231.6   229.3
    5264  231.85  5271.1  233.78  5338.7  240.13  5406.3  242.98  5481.8  241.71
#Mann= 5 ,-1 , 0
  4564.8     .05       0  4895.7     .16       0  4992.1     .07       0
  4998.1     .16       0  5139.7     .05       0
Bank Sta=4955.6,5062.7
XS Rating Curve= 0 ,0
Exp/Cntr=0.3,0.1

Type RM Length L Ch R = 1 ,11971   ,408,408,408
BEGIN DESCRIPTION:
KINNON CREEK 21.0
END DESCRIPTION:
XS GIS Cut Line= 2
      3721010.27      10528769.9      3720684.76     10527880.17
#Sta/Elev= 30
  4398.9  235.54  4506.5  237.65  4587.5  233.16  4709.6  231.51  4765.3  228.33
  4899.1  214.79    4931  213.25  4937.8  210.39  4973.6  206.83  4993.5  201.46
  5002.5  200.96  5005.3  200.46  5008.5  200.96  5016.2  205.32    5024  205.34
  5054.6  211.58  5069.4  211.93  5079.8  215.35  5085.1  214.07  5101.4  218.68
  5110.3  219.79  5115.6  217.92  5122.7  220.39  5142.5  222.48  5162.8  224.03
  5176.7  223.93  5186.6  226.23  5201.9  224.85  5239.8  225.62  5346.3  232.12
#Mann= 5 ,-1 , 0
  4398.9     .05       0  5002.5     .03       0  5008.5     .05       0
  5142.5     .16       0  5162.8     .05       0
Bank Sta=4931,5079.8
XS Rating Curve= 0 ,0
Exp/Cntr=0.3,0.1

Type RM Length L Ch R = 1 ,11563   ,729,729,729
BEGIN DESCRIPTION:
KINNON CREEK 20.0
END DESCRIPTION:
XS GIS Cut Line= 2
      3721552.78      10528845.8      3720956.51     10527664.11
#Sta/Elev= 30
    4158  245.28  4306.8  240.69  4334.7  237.53  4410.7  235.44  4446.2  232.68
  4477.9  233.43  4529.8  231.45  4634.7  223.36  4669.2   218.2  4708.2  214.83
    4881   214.1  4947.9  210.99  4975.8  206.87    4982  198.74  4989.5  195.83
  4992.3  195.33  4995.5  195.83  5004.4  196.46  5020.4  205.21  5026.8  206.11
    5094  208.87  5131.9  208.65  5170.9  211.77  5193.2  216.65  5198.8  222.24
  5215.5  227.36  5250.8   233.3  5349.3   239.7  5421.8  241.23  5481.6  239.12
#Mann= 3 ,-1 , 0
    4158     .05       0  4989.5     .03       0  4995.5     .05       0
Bank Sta=4947.9,5094
XS Rating Curve= 0 ,0
Exp/Cntr=0.3,0.1

Type RM Length L Ch R = 1 ,10834   ,600,600,600
BEGIN DESCRIPTION:
KINNON CREEK 19.0
END DESCRIPTION:
XS GIS Cut Line= 3
      3721602.28     10528364.19      3721310.61      10527600.3
      3721074.54      10527551.7
#Sta/Elev= 30
  4335.1  226.12  4440.9  220.68  4525.8  214.18  4564.2  209.16  4660.1  205.02
    4714  206.23  4720.2  199.91  4735.4  207.32  4744.9  205.39  4750.3   208.1
  4756.8  200.71  4805.1  207.26  4829.8  205.37  4846.8  207.45  4938.8  207.12
  4974.8  204.89  4981.6  203.14  5001.9  194.05  5004.6  193.55  5007.9  194.05
  5013.7  203.65  5024.3  207.92  5029.6  211.59  5035.2  218.56  5045.9  221.12
  5054.3  225.26    5078   228.9  5120.8  231.46  5274.3  238.06  5393.8  237.77
#Mann= 4 ,-1 , 0
  4335.1     .05       0  4846.8     .16       0  5001.9     .07       0
  5007.9     .05       0
Bank Sta=4938.8,5120.8
XS Rating Curve= 0 ,0
Exp/Cntr=0.3,0.1

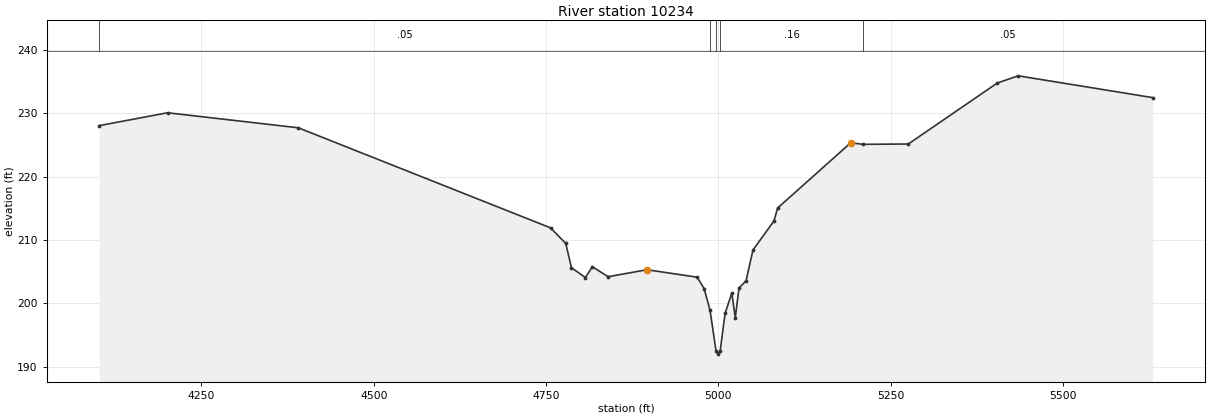
Type RM Length L Ch R = 1 ,10234   ,0,0,0
BEGIN DESCRIPTION:
KINNON CREEK 18.0
END DESCRIPTION:
XS GIS Cut Line= 3
       3722214.7     10528173.12      3722030.23     10527619.71
      3721097.05      10527467.8
#Sta/Elev= 30
  4101.7  228.04  4200.9  230.07  4390.6   227.7  4756.6  211.91  4778.7  209.45
    4787  205.61  4807.2  204.07  4817.4  205.77  4840.2   204.2  4896.6   205.3
  4969.4  204.12  4979.5  202.32  4988.1  198.89  4996.8  192.48  4999.5  191.98
  5002.8  192.48  5009.9  198.41  5019.7  201.61  5024.7  197.74  5030.1   202.4
  5040.3  203.54  5050.4  208.41  5080.8  212.99  5086.2  215.04  5192.3  225.34
  5209.7  225.09  5275.8  225.14    5405  234.77  5435.4   235.9  5630.5  232.46
#Mann= 5 ,-1 , 0
  4101.7     .05       0  4988.1     .16       0  4996.8     .07       0
  5002.8     .16       0  5209.7     .05       0
Bank Sta=4896.6,5192.3
XS Rating Curve= 0 ,0
Exp/Cntr=0.3,0.1

Chan Stop Cuts=-1
Use User Specified Reach Order=0
Composite Channel Slope=5