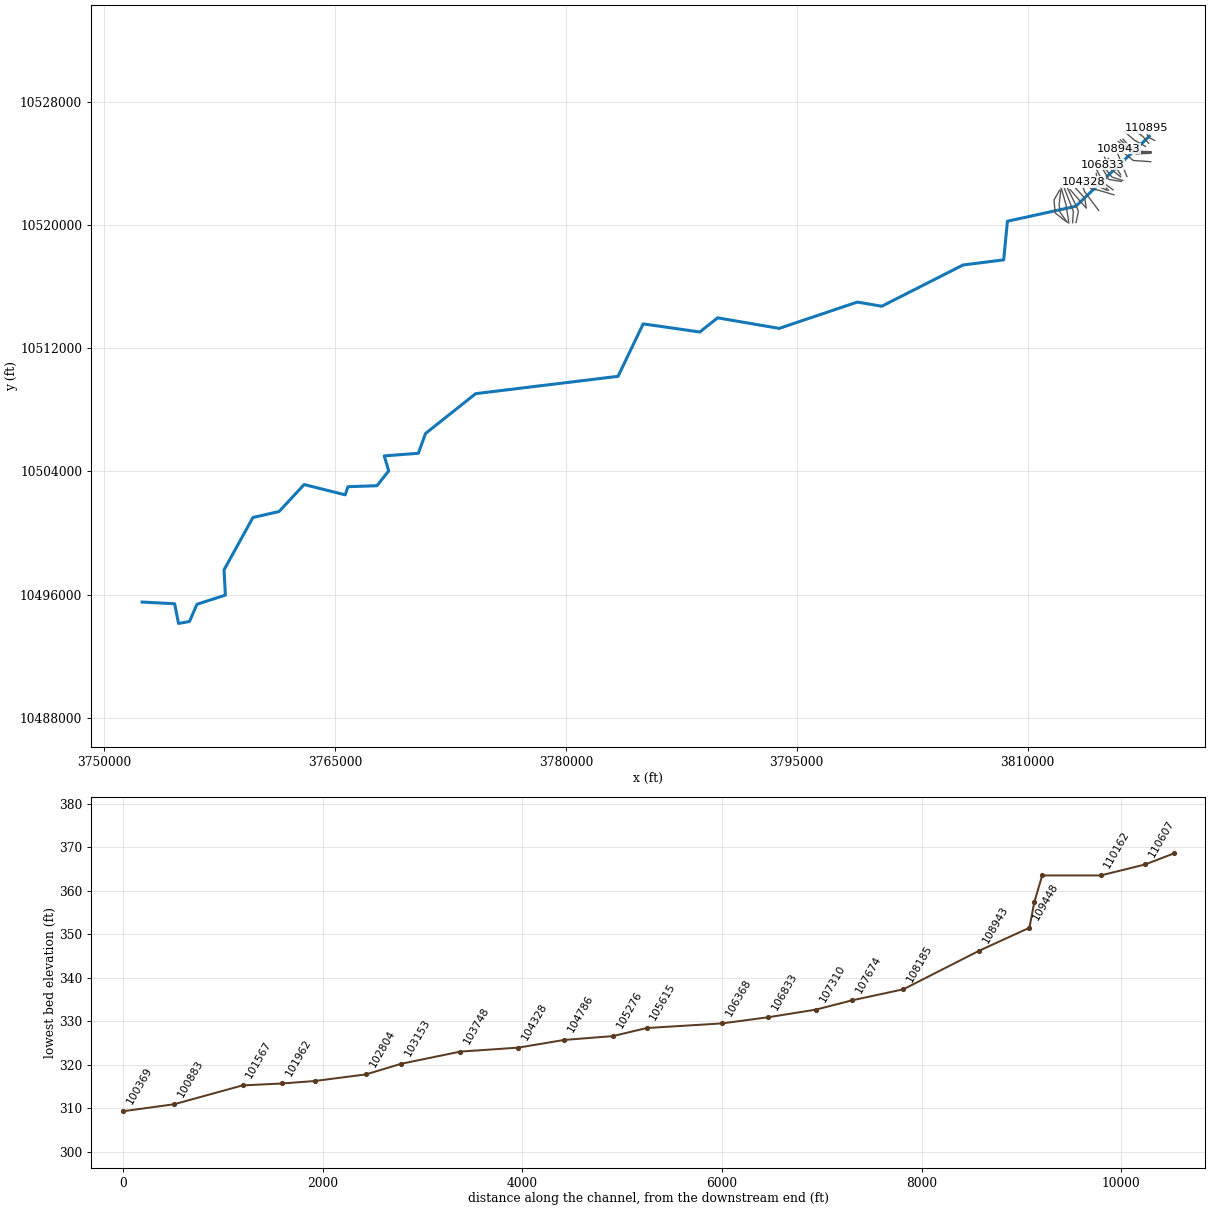
--- LITTLE ELKHART CREEK.prj (project) ---

Proj Title=LITTLE ELKHART CREEK Base Level Engineering
Current Plan=p01
Default Exp/Contr=0.3,0.1
English Units
Geom File=g01
Flow File=f01
Plan File=p01
Y Axis Title=Elevation
X Axis Title(PF)=Main Channel Distance
X Axis Title(XS)=Station
BEGIN DESCRIPTION:
LITTLE ELKHART CREEK
END DESCRIPTION:
DSS Export Rating Curves= 0
DSS Export Rating Curve Sorted= 0
DSS Export Volume Flow Curves= 0
DXF OffsetX= 0
DXF OffsetY= 0
DXF ScaleX= 1
DXF ScaleY= 10

--- LITTLE ELKHART CREEK.p01 (plan) ---

Plan Title=Multiple Run
Short Identifier=Multiple
Geom File=g01
Flow File=f01
Subcritical Flow
K Sum by GR= 0
Std Step Tol= 0.01
Critical Tol= 0.01
Num of Std Step Trials= 20
Max Error Tol= 0.3
Flow Tol Ratio= 0.001
Split Flow NTrial= 30
Split Flow Tol= 0.02
Split Flow Ratio= 0.02
Log Output Level= 0
Friction Slope Method= 1
Unsteady Friction Slope Method= 2
Unsteady Bridges Friction Slope Method= 1
Parabolic Critical Depth
Global Vel Dist=  1 , 1 , 1
Global Log Level= 0
CheckData=True
Encroach Param= -1, 0, 0, 0
BEGIN DESCRIPTION:
Multiple Run
END DESCRIPTION:

--- LITTLE ELKHART CREEK.f01 (steady flow) ---

Flow Title=Multiple
Program Version=4.10
Number of Profiles= 7
Profile Names=10-year,25-year,50-year,1pct_min,100-year,1pct_plu,500-year
River Rch & RM=LITTLE ELKHART C,Reach-1         ,110895
     786    1086    1339    1215    1643    2222    2480
River Rch & RM=LITTLE ELKHART C,Reach-1         ,108185
     989    1371    1694    1537    2078    2811    3138
River Rch & RM=LITTLE ELKHART C,Reach-1         ,99096
    1176    1640    2035    1851    2504    3386    3806
River Rch & RM=LITTLE ELKHART C,Reach-1         ,96848
    1898    2700    3393    3122    4222    5709    6564
River Rch & RM=LITTLE ELKHART C,Reach-1         ,96008
    1898    2700    3393    3122    4222    5709    6564
River Rch & RM=LITTLE ELKHART C,Reach-1         ,94023
    2917    4196    5314    4919    6653    8997   10472
River Rch & RM=LITTLE ELKHART C,Reach-1         ,91620
    2917    4196    5314    4919    6653    8997   10472
River Rch & RM=LITTLE ELKHART C,Reach-1         ,84199
    4176    6080    7763    7240    9791   13242   15638
River Rch & RM=LITTLE ELKHART C,Reach-1         ,82806
    4176    6080    7763    7240    9791   13242   15638
River Rch & RM=LITTLE ELKHART C,Reach-1         ,78553
    4248    6182    7891    7356    9948   13453   15874
River Rch & RM=LITTLE ELKHART C,Reach-1         ,76752
    4284    6220    7927    7376    9976   13491   15862
River Rch & RM=LITTLE ELKHART C,Reach-1         ,73852
    4789    6964    8884    8273   11188   15130   17811
River Rch & RM=LITTLE ELKHART C,Reach-1         ,71628
    4789    6964    8884    8273   11188   15130   17811
River Rch & RM=LITTLE ELKHART C,Reach-1         ,69363
    4789    6964    8884    8273   11188   15130   17811
River Rch & RM=LITTLE ELKHART C,Reach-1         ,68384
    4789    6964    8884    8273   11188   15130   17811
River Rch & RM=LITTLE ELKHART C,Reach-1         ,64791
    4983    7252    9255    8622   11660   15769   18577
River Rch & RM=LITTLE ELKHART C,Reach-1         ,63890
    5011    7270    9259    8605   11637   15738   18452
River Rch & RM=LITTLE ELKHART C,Reach-1         ,56964
    6100    8844   11260   10455   14139   19122   22371
River Rch & RM=LITTLE ELKHART C,Reach-1         ,54108
    6100    8844   11260   10455   14139   19122   22371
River Rch & RM=LITTLE ELKHART C,Reach-1         ,49406
    6100    8844   11260   10455   14139   19122   22371
River Rch & RM=LITTLE ELKHART C,Reach-1         ,44519
    6538    9536   12191   11367   15373   20790   24529
River Rch & RM=LITTLE ELKHART C,Reach-1         ,41752
    6622    9662   12354   11522   15582   21073   24872
River Rch & RM=LITTLE ELKHART C,Reach-1         ,40913
    6794    9897   12641   11774   15924   21535   25351
River Rch & RM=LITTLE ELKHART C,Reach-1         ,33113
    6885   10025   12801   11919   16119   21799   25642
River Rch & RM=LITTLE ELKHART C,Reach-1         ,32258
    6885   10025   12801   11919   16119   21799   25642
River Rch & RM=LITTLE ELKHART C,Reach-1         ,25672
    6899   10028   12789   11893   16083   21751   25519
River Rch & RM=LITTLE ELKHART C,Reach-1         ,17790
    6889   10002   12747   11844   16017   21662   25375
Boundary for River Rch & Prof#=LITTLE ELKHART C,Reach-1         , 1
Up Type= 0
Dn Type= 3
Dn Slope=0.003
Boundary for River Rch & Prof#=LITTLE ELKHART C,Reach-1         , 2
Up Type= 0
Dn Type= 3
Dn Slope=0.003
Boundary for River Rch & Prof#=LITTLE ELKHART C,Reach-1         , 3
Up Type= 0
Dn Type= 3
Dn Slope=0.003
Boundary for River Rch & Prof#=LITTLE ELKHART C,Reach-1         , 4
Up Type= 0
Dn Type= 3
Dn Slope=0.003
Boundary for River Rch & Prof#=LITTLE ELKHART C,Reach-1         , 5
Up Type= 0
Dn Type= 3
Dn Slope=0.003
Boundary for River Rch & Prof#=LITTLE ELKHART C,Reach-1         , 6
Up Type= 0
Dn Type= 3
Dn Slope=0.003
Boundary for River Rch & Prof#=LITTLE ELKHART C,Reach-1         , 7
Up Type= 0
Dn Type= 3
Dn Slope=0.003
DSS Import GetInterval= 0
DSS Import GetPeak= 0
DSS Import FillOption= 0

--- LITTLE ELKHART CREEK.g01 (geometry) ---

Geom Title=Existing Conditions
Program Version=4.10

River Reach=LITTLE ELKHART C,Reach-1
Reach XY= 30
      3817896.84      10525773.7       3813118.5       10521222.
       3808679.4     10520251.54      3808438.25       10517744.
      3805795.75       10517409.       3800519.5       10514731.
       3798931.5       10515001.      3793854.75       10513292.
       3789858.5       10513978.      3788699.75       10513057.
       3785023.5       10513585.      3783391.25       10510179.
       3774145.5       10509054.       3770887.5       10506467.
        3770423.       10505183.      3768206.75       10505010.
        3768497.       10504036.       3767732.5       10503075.
      3765850.75       10503011.      3765670.75       10502482.
      3763003.75       10503150.      3761375.25       10501398.
       3759679.5       10501010.      3757802.75       10497609.
        3757889.       10495970.        3756045.       10495374.
      3755557.25       10494258.      3754846.25       10494128.
        3754594.       10495409.      3752477.75       10495519.

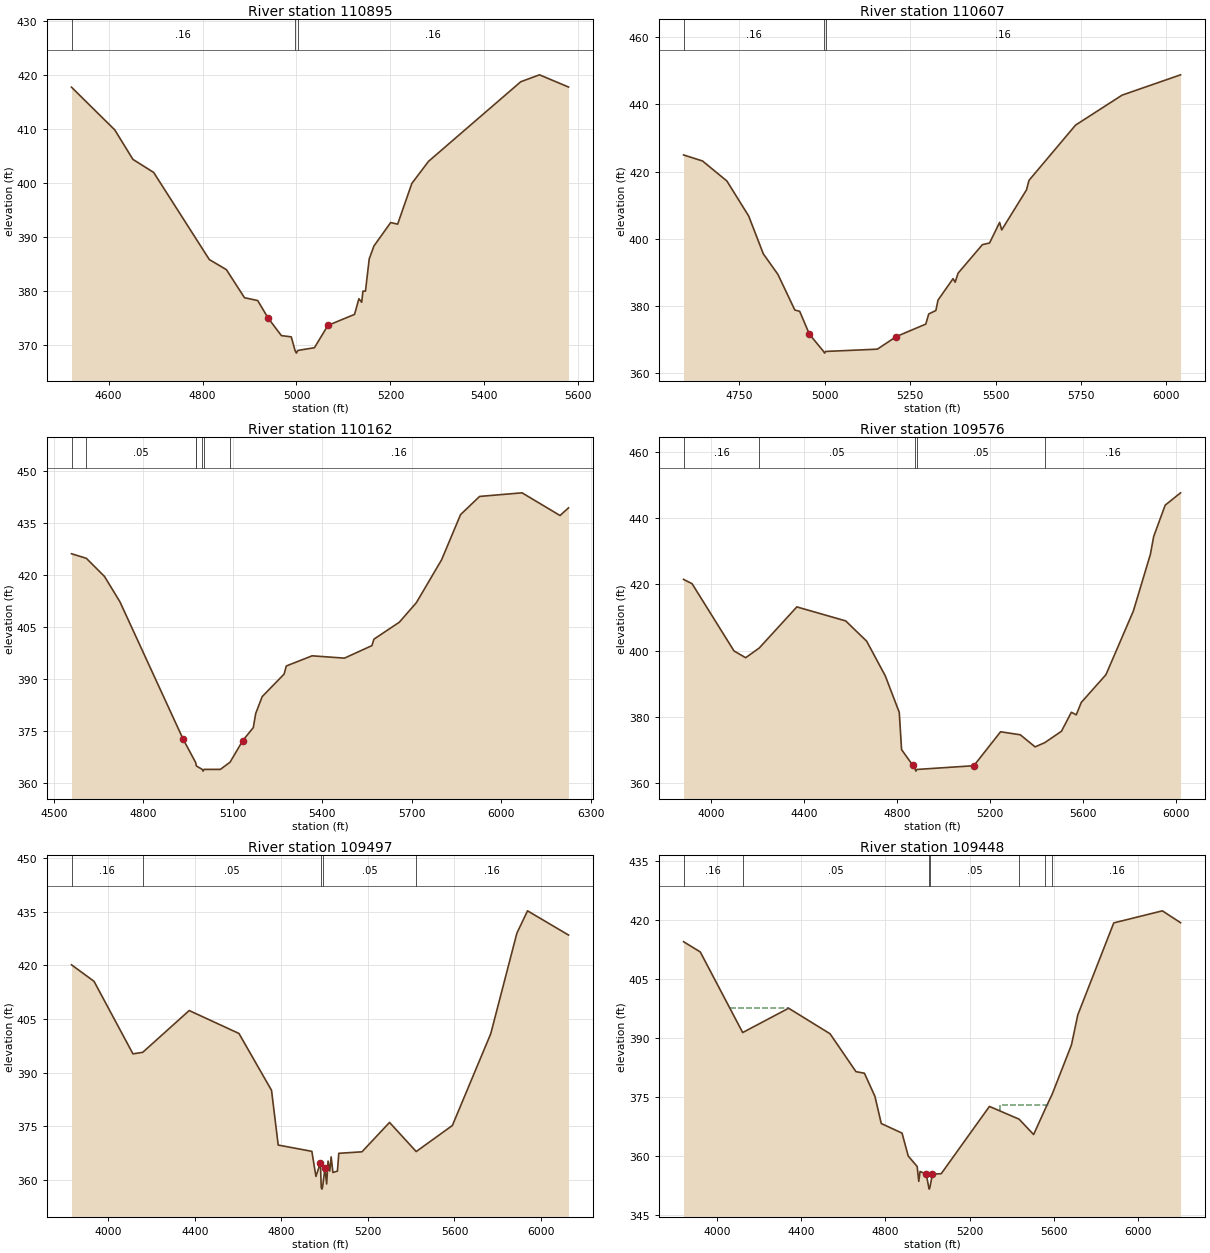
Type RM Length L Ch R = 1 ,110895  ,288,288,288
BEGIN DESCRIPTION:
LITTLE ELKHART CREEK 143.0
END DESCRIPTION:
XS GIS Cut Line= 5
      3818250.02     10525494.68      3817911.46     10525670.47
      3817798.61     10525802.85      3817761.72     10525859.28
      3817707.46     10526291.14
#Sta/Elev= 30
  4521.1  417.75  4613.2  409.85  4651.8   404.4    4696  401.98  4814.5  385.86
  4850.8     384  4889.4   378.8  4917.5  378.28  4939.5  375.06  4967.9  371.79
  4988.9  371.56    4997  369.05  4999.8  368.55    5003  369.05  5038.3  369.55
  5066.9  373.68  5123.7  375.72  5132.9  378.61  5138.9  377.96  5141.5  380.02
  5146.9  380.02  5154.9  385.99    5165  388.38  5200.6  392.71  5215.4  392.41
  5245.6  399.94  5281.1  404.03  5477.5  418.76  5517.3  420.04  5579.2  417.78
#Mann= 3 ,-1 , 0
  4521.1     .16       0    4997     .07       0    5003     .16       0
Bank Sta=4939.5,5066.9
XS Rating Curve= 0 ,0
Exp/Cntr=0.3,0.1

Type RM Length L Ch R = 1 ,110607  ,445,445,445
BEGIN DESCRIPTION:
LITTLE ELKHART CREEK 142.5
END DESCRIPTION:
XS GIS Cut Line= 3
      3817856.78     10525308.48      3817463.54     10525766.83
        3816774.     10526263.82
#Sta/Elev= 30
  4587.3  424.98  4642.8  423.18  4714.1  417.22  4777.8  406.81  4820.6  395.56
  4863.4  389.43  4912.8  378.83    4927  378.45  4955.6  371.61    4997  366.51
  4999.8  366.01    5003  366.51  5154.2  367.19    5210  370.95  5295.9  374.65
  5304.5  377.66  5325.4  378.69  5331.7  381.79  5375.7  388.17  5381.8  387.12
  5390.4   389.8  5461.6  398.29  5482.4  398.77  5511.9   404.9    5518  402.66
  5590.5  414.58  5597.8  417.41    5734  433.85  5870.2  442.77  6041.2  448.81
#Mann= 3 ,-1 , 0
  4587.3     .16       0    4997     .07       0    5003     .16       0
Bank Sta=4955.6,5210
XS Rating Curve= 0 ,0
Exp/Cntr=0.3,0.1

Type RM Length L Ch R = 1 ,110162  ,586,586,586
BEGIN DESCRIPTION:
LITTLE ELKHART CREEK 142.4
END DESCRIPTION:
XS GIS Cut Line= 3
      3817650.85       10525111.        3816926.       10525519.
      3816293.85     10526064.55
#Sta/Elev= 30
  4558.6  426.15  4608.4  424.83  4669.1  419.62  4720.7  412.35  4933.5  372.61
  4974.8  365.99  4977.5  364.97    4997  363.99  4999.8  363.49    5003  363.99
  5057.8  363.99  5090.3  366.07    5133   372.3  5168.2  376.04  5176.3   380.1
    5198  384.96  5271.5  391.46    5279   393.8  5365.6  396.73  5473.9  396.06
  5566.1  399.67  5572.7  401.52  5658.2  406.43  5715.3  412.07  5799.8  424.42
  5863.4  437.44  5927.2  442.67  6069.6  443.71  6196.9  437.17  6225.4  439.39
#Mann= 7 ,-1 , 0
  4558.6     .16       0  4608.4     .05       0  4974.8     .16       0
  4977.5     .05       0    4997    .035       0    5003     .05       0
  5090.3     .16       0
Bank Sta=4933.5,5133
XS Rating Curve= 0 ,0
Exp/Cntr=0.3,0.1

Type RM Length L Ch R = 1 ,109576  ,79,79,79
BEGIN DESCRIPTION:
LITTLE ELKHART CREEK 142.0
END DESCRIPTION:
XS GIS Cut Line= 4
      3818006.31      10524768.3      3817023.72     10524803.02
      3816787.61     10524931.49      3816186.88     10525580.83
#Sta/Elev= 30
  3881.9  421.53  3918.6  420.22  4098.7  399.88  4148.8  397.82  4207.2  400.75
  4368.9   413.2    4579  408.96  4669.1  402.82  4749.1  392.34  4809.2  381.28
  4819.2     370  4867.4  365.25  4878.2  363.99  4880.9  363.49  4884.2  363.99
  5129.9  365.13  5244.7   375.4  5329.7  374.49  5393.2  370.83  5434.8  372.11
  5506.6  375.57  5549.1  381.31  5570.1  380.53  5591.7  384.29  5697.7  392.68
  5815.7  411.98  5888.8  429.12  5902.9   434.5  5952.3  443.99  6018.5  447.73
#Mann= 5 ,-1 , 0
  3881.9     .16       0  4207.2     .05       0  4878.2     .03       0
  4884.2     .05       0  5434.8     .16       0
Bank Sta=4867.4,5129.9
XS Rating Curve= 0 ,0
Exp/Cntr=0.3,0.1

Type RM Length L Ch R = 1 ,109497  ,49,49,49
BEGIN DESCRIPTION:
Mapping XS 7f737d3b
END DESCRIPTION:
XS GIS Cut Line= 5
      3818023.68     10524716.21      3817120.94     10524716.21
      3816905.64     10524769.36      3816733.27     10524904.78
      3816013.98      10525531.6
#Sta/Elev= 30
  3829.4  420.17  3933.5  415.55  4113.5  395.24  4158.7  395.67  4373.5  407.37
  4603.5  400.95  4754.1  385.03    4785   369.7  4940.6  367.94  4959.3  360.92
  4980.1  364.71    4984  357.86  4986.8  357.36    4990  357.86  5000.9  363.18
    5009  358.81  5015.4  365.22  5023.4  362.43  5029.8  366.39  5037.9  362.02
  5058.7   362.4  5065.1  367.39  5172.3  367.81  5299.7  376.04  5422.9  367.88
  5590.2  375.18  5767.8  400.91  5888.4  429.03  5937.7  435.29  6127.2  428.51
#Mann= 5 ,-1 , 0
  3829.4     .16       0  4158.7     .05       0    4984    .035       0
    4990     .05       0  5422.9     .16       0
Bank Sta=4980.1,5000.9
XS Rating Curve= 0 ,0
Exp/Cntr=0.3,0.1

Type RM Length L Ch R = 1 ,109448  ,505,505,505
BEGIN DESCRIPTION:
LITTLE ELKHART CREEK 141.0
END DESCRIPTION:
XS GIS Cut Line= 4
      3817988.98     10524660.65      3817037.61     10524625.93
        3816739.     10524844.68      3815874.49     10525424.49
#Sta/Elev= 30
  3840.2   414.4  3919.6   411.8  4121.3   391.3  4339.9  397.48  4536.7  390.99
  4660.1  381.35  4700.1  380.96  4750.2  375.07  4780.2  368.17  4879.1  365.72
  4908.4   359.9  4950.9  357.24  4958.6  353.45  4964.8  355.97  4994.1  355.32
  5005.8  351.98  5008.5  351.48  5011.8  351.98  5023.5  355.31  5065.2   355.4
  5294.5  372.51  5435.7  369.27  5504.6  365.36  5561.1  372.02  5593.5   375.7
  5684.7  388.18  5714.7   395.8  5885.7  419.18  6116.8  422.25  6203.3  419.23
#Mann= 7 ,-1 , 0
  3840.2     .16       0  4121.3     .05       0  5005.8    .035       0
  5011.8     .05       0  5435.7     .16       0  5561.1     .05       0
  5593.5     .16       0
#XS Ineff= 2 ,-1
    4060  4339.9   397.5  5345.5  5576.6  372.82
Permanent Ineff=
       F       F
Bank Sta=4994.1,5023.5
XS Rating Curve= 0 ,0
Exp/Cntr=0.3,0.1

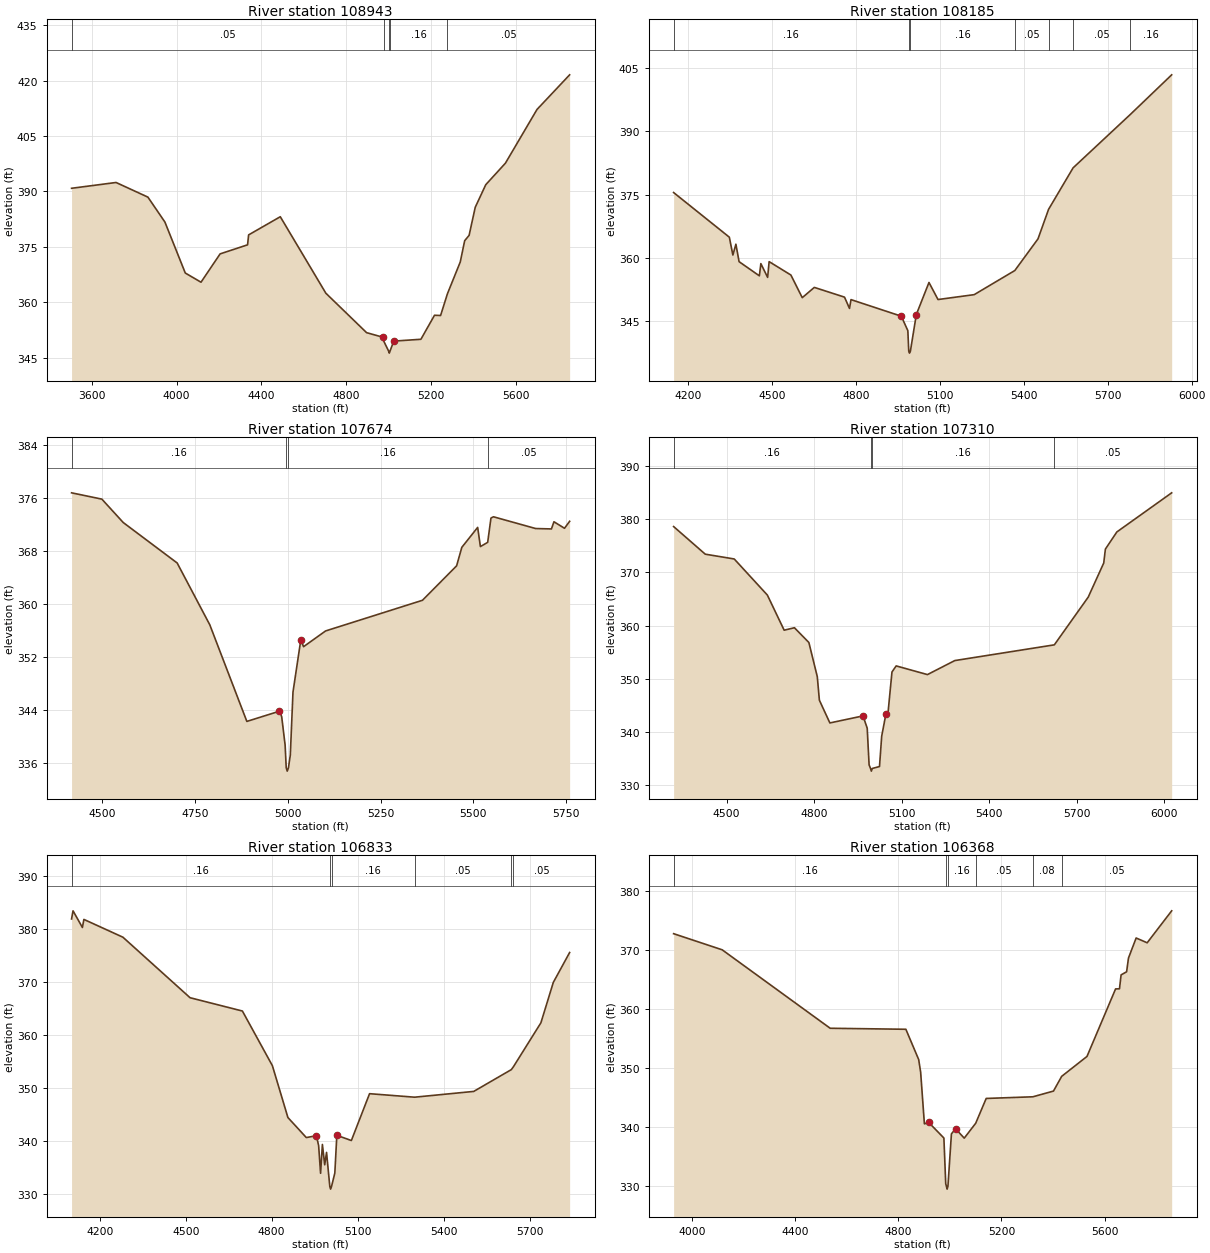
Type RM Length L Ch R = 1 ,108943  ,758,758,758
BEGIN DESCRIPTION:
LITTLE ELKHART CREEK 140.0
END DESCRIPTION:
XS GIS Cut Line= 3
      3817988.99     10524118.99      3816857.05     10524195.38
      3815905.65     10524952.33
#Sta/Elev= 30
  3504.4  390.82  3714.3  392.39  3864.6  388.43  3944.8  381.69    4041  367.88
  4115.2  365.39  4205.4  373.06  4334.9  375.51  4339.9   378.2  4489.3  383.12
  4704.4  362.41  4896.6  351.73  4975.1  350.47  4977.4  349.46  5000.9  346.69
  5003.7  346.19  5006.9  346.69  5024.7  349.44  5152.9  349.94    5217  356.44
  5245.8  356.38  5278.1  362.27  5338.5  370.85  5359.5  376.64  5380.3  378.07
  5409.2  385.66  5458.8  391.78  5551.7  397.62  5700.7  412.16  5854.7  421.54
#Mann= 5 ,-1 , 0
  3504.4     .05       0  4977.4     .16       0  5000.9     .07       0
  5006.9     .16       0  5278.1     .05       0
#XS Ineff= 1 ,-1
  3924.7  4489.3  383.12
Permanent Ineff=
       F
Bank Sta=4975.1,5024.7
XS Rating Curve= 0 ,0
Exp/Cntr=0.3,0.1

Type RM Length L Ch R = 1 ,108185  ,511,511,511
BEGIN DESCRIPTION:
LITTLE ELKHART CREEK 139.0
END DESCRIPTION:
XS GIS Cut Line= 2
      3816440.37     10523153.75      3815774.44     10524804.71
#Sta/Elev= 30
  4148.4  375.49  4347.5  364.89  4360.2  360.65    4371  363.22  4382.4  359.07
  4454.9  355.71  4460.2  358.61  4484.4  355.34  4489.8  359.08  4567.6   355.9
  4608.2  350.52  4651.3  352.96  4759.2  350.65    4777  347.97  4782.4  350.06
  4962.2  346.12  4985.6  342.68  4988.8  337.85  4991.5  337.35  4994.8  337.85
  5015.9  346.52  5061.1  354.13  5093.4  350.08  5222.8  351.24    5368  356.97
  5450.8  364.49  5488.6   371.5  5576.3  381.36  5780.5  394.02  5928.6  403.45
#Mann= 7 ,-1 , 0
  4148.4     .16       0  4988.8     .07       0  4994.8     .16       0
    5368     .05       0  5488.6     .16       0  5576.3     .05       0
  5780.5     .16       0
Bank Sta=4962.2,5015.9
XS Rating Curve= 0 ,0
Exp/Cntr=0.3,0.1

Type RM Length L Ch R = 1 ,107674  ,364,364,364
BEGIN DESCRIPTION:
LITTLE ELKHART CREEK 138.0
END DESCRIPTION:
XS GIS Cut Line= 3
       3816037.6     10523264.83      3815662.61     10523848.15
      3815226.06     10524326.28
#Sta/Elev= 30
  4418.2  376.76  4499.8  375.81  4557.2  372.29  4702.5  366.19  4790.4  356.87
  4890.1  342.32  4977.9  343.86  4983.9  343.04  4993.1  338.77  4996.1  335.33
  4998.8  334.83  5002.1  335.33  5007.1  337.25  5014.3  346.73  5035.4  354.62
  5042.8  353.58  5102.1  355.95  5362.9  360.57  5454.8  365.76  5468.9  368.55
  5511.5  371.55  5518.9  368.66  5538.5   369.3  5547.3  372.96  5554.1  373.15
  5667.6  371.38  5710.1  371.32  5716.9   372.4  5745.3  371.42  5759.1  372.47
#Mann= 4 ,-1 , 0
  4418.2     .16       0  4996.1     .07       0  5002.1     .16       0
  5538.5     .05       0
Bank Sta=4977.9,5035.4
XS Rating Curve= 0 ,0
Exp/Cntr=0.3,0.1

Type RM Length L Ch R = 1 ,107310  ,477,477,477
BEGIN DESCRIPTION:
LITTLE ELKHART CREEK 137.0
END DESCRIPTION:
XS GIS Cut Line= 3
      3816037.61     10523125.93      3815343.16     10523688.43
      3814982.66     10524416.38
#Sta/Elev= 30
  4318.8  378.57  4427.2  373.39  4526.4  372.49  4639.9  365.72  4697.4  359.13
  4732.6  359.59  4782.1  356.82  4810.9  350.41  4818.1  345.99    4854  341.73
  4967.6  343.05  4981.9  340.74  4988.4  333.85  4993.3  333.19  4996.1  332.69
  4999.3  333.19    5024  333.55  5031.5  339.24  5045.9  343.39  5052.3  343.13
  5066.7  351.28  5081.1  352.43  5188.2   350.8  5281.9  353.43  5622.8  356.38
  5738.9  365.33  5792.1  371.74  5797.7  374.34    5837  377.56  6024.8   384.9
#Mann= 4 ,-1 , 0
  4318.8     .16       0  4993.3     .07       0  4999.3     .16       0
  5622.8     .05       0
Bank Sta=4967.6,5045.9
XS Rating Curve= 0 ,0
Exp/Cntr=0.3,0.1

Type RM Length L Ch R = 1 ,106833  ,465,465,465
BEGIN DESCRIPTION:
LITTLE ELKHART CREEK 136.0
END DESCRIPTION:
XS GIS Cut Line= 3
      3816169.51     10522903.72      3815468.16     10523118.99
      3814849.63     10523910.16
#Sta/Elev= 30
  4101.8  381.93  4106.9  383.46  4139.6  380.32  4144.8  381.84    4281  378.48
  4515.3  367.06  4697.9  364.55  4802.5  354.24  4856.7  344.45  4920.9  340.67
  4956.2  341.02  4963.9  339.14  4970.7  333.93    4977  339.37  4985.1  335.53
  4991.5  337.87  5002.9  331.44  5005.7  330.94  5008.9  331.44  5020.4  333.97
  5027.4   341.1  5078.1  340.11  5141.6  348.95  5298.7  348.29  5505.1  349.38
  5636.2  353.49  5643.4  354.02  5739.4  362.32  5782.8  369.96  5839.7  375.59
#Mann= 6 ,-1 , 0
  4101.8     .16       0  5002.9     .07       0  5008.9     .16       0
  5298.7     .05       0  5636.2     .08       0  5643.4     .05       0
Bank Sta=4956.2,5027.4
XS Rating Curve= 0 ,0
Exp/Cntr=0.3,0.1

Type RM Length L Ch R = 1 ,106368  ,753,753,753
BEGIN DESCRIPTION:
LITTLE ELKHART CREEK 135.0
END DESCRIPTION:
XS GIS Cut Line= 4
      3816072.38     10522834.26      3815245.94     10522973.15
      3815072.33     10523306.49      3814704.43     10523924.28
#Sta/Elev= 30
  3927.7  372.76  4116.2  370.03  4535.3  356.75    4829  356.58  4878.8  351.45
  4886.4  349.31  4900.9  340.57  4917.4  340.82  4976.6  338.17  4983.7  330.44
  4986.3  330.02  4989.1  329.52  4992.3  330.02  5005.8  338.87  5021.7  339.74
  5055.6  338.15    5100  340.67  5140.8  344.87    5322  345.15  5401.9  346.12
  5433.7  348.61  5531.9  351.98  5642.9  363.41    5658  363.43  5664.3  365.79
  5685.7  366.31  5692.9  368.63  5722.7  372.03  5765.5  371.22  5860.6  376.63
#Mann= 6 ,-1 , 0
  3927.7     .16       0  4986.3     .07       0  4992.3     .16       0
    5100     .05       0    5322     .08       0  5433.7     .05       0
Bank Sta=4917.4,5021.7
XS Rating Curve= 0 ,0
Exp/Cntr=0.3,0.1

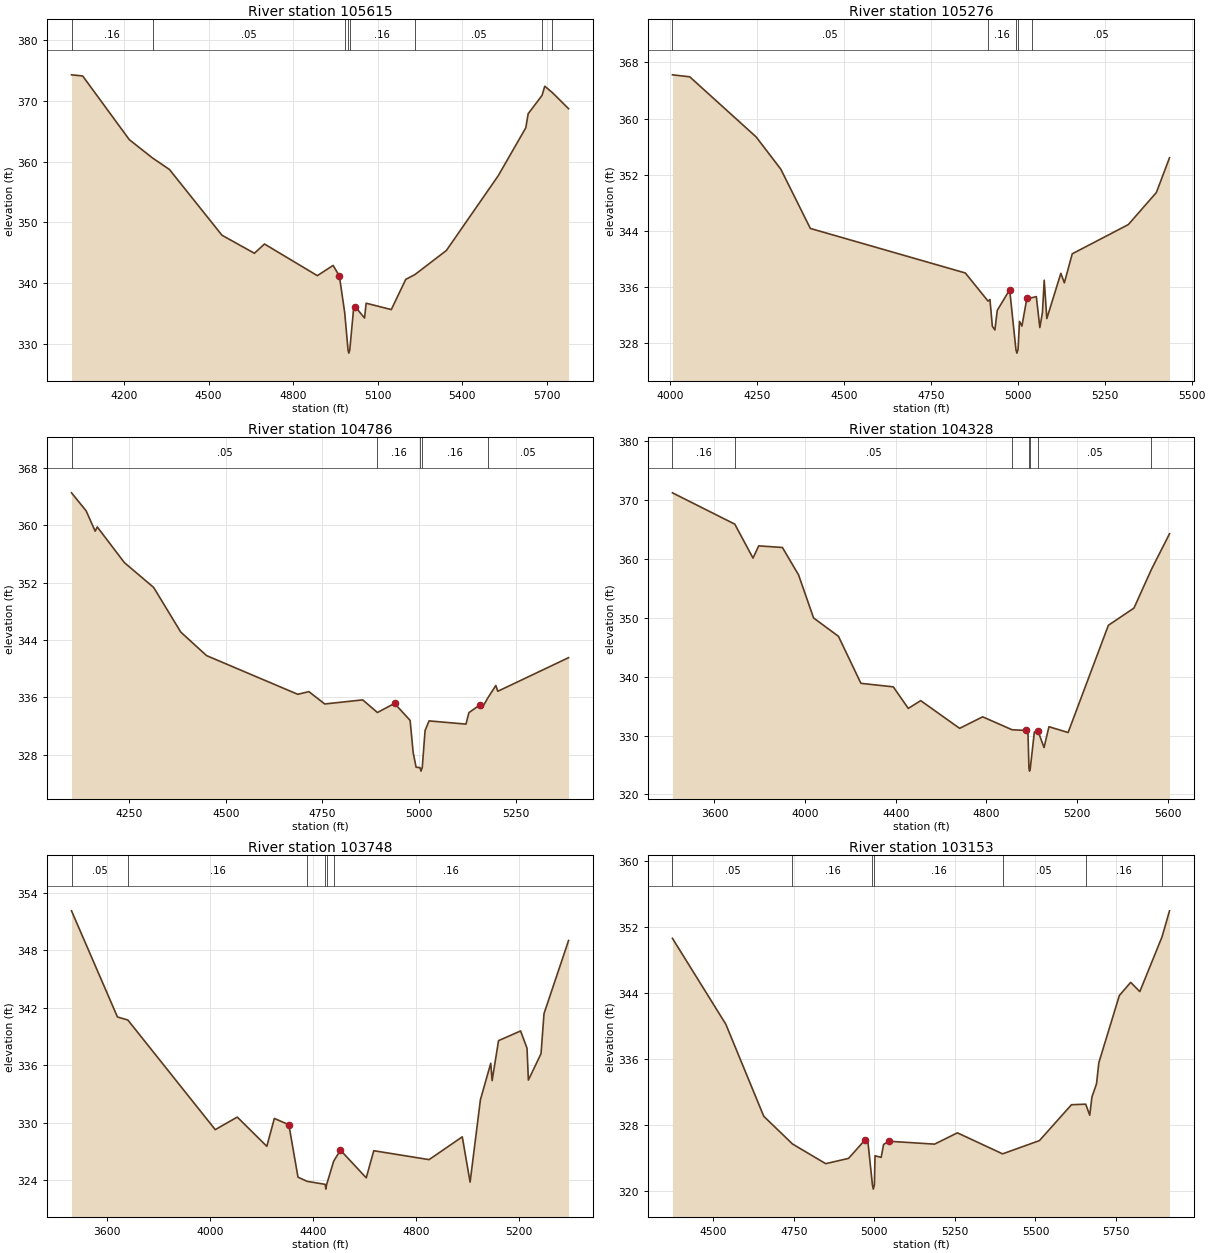
Type RM Length L Ch R = 1 ,105615  ,339,339,339
BEGIN DESCRIPTION:
LITTLE ELKHART CREEK 134.0
END DESCRIPTION:
XS GIS Cut Line= 3
      3815537.61      10522292.6      3814898.72     10522757.88
      3814461.41     10523625.55
#Sta/Elev= 30
  4014.3  374.34  4053.9  374.15  4219.2  363.65  4301.5  360.63  4361.4  358.74
  4547.6   347.9  4662.7  344.92  4698.3  346.45  4885.8  341.23  4941.6  342.92
  4963.9  341.16  4982.8  335.11  4994.6  328.96  4997.4  328.46  5000.6  328.96
  5014.1   335.7    5020  336.11  5053.1  334.25  5058.7  336.69  5147.9  335.64
  5199.2  340.62  5231.7  341.41  5343.1  345.38  5527.2  357.72  5624.7  365.61
  5633.1  367.93  5682.2  370.94  5691.9  372.46  5718.7  371.42  5776.3  368.76
#Mann= 8 ,-1 , 0
  4014.3     .16       0  4301.5     .05       0  4982.8     .16       0
  4994.6     .07       0  5000.6     .16       0  5231.7     .05       0
  5682.2     .08       0  5718.7     .05       0
Bank Sta=4963.9,5020
XS Rating Curve= 0 ,0
Exp/Cntr=0.3,0.1

Type RM Length L Ch R = 1 ,105276  ,490,490,490
BEGIN DESCRIPTION:
LITTLE ELKHART CREEK 133.0
END DESCRIPTION:
XS GIS Cut Line= 3
      3815249.62     10522260.17      3814499.61     10522960.19
      3814449.61     10523360.14
#Sta/Elev= 30
  4007.3  366.23  4056.9  365.95  4247.9  357.39  4318.8   352.8  4403.8  344.36
  4849.3  338.02  4914.6  334.02  4920.1  334.24    4927  330.43  4934.3  329.91
  4941.1   332.7  4976.8  335.63  4994.8  327.11  4997.6  326.61  5000.8  327.11
  5005.1  331.13    5012  330.46  5026.2  334.41  5042.4  334.52  5053.4  334.66
  5063.5  330.25    5071  332.39  5076.1  336.99  5083.6  331.53  5123.9  337.97
    5134  336.62  5156.7  340.75  5317.9  344.91  5398.6  349.48  5436.3  354.42
#Mann= 5 ,-1 , 0
  4007.3     .05       0  4914.6     .16       0  4994.8     .07       0
  5000.8     .16       0  5042.4     .05       0
Bank Sta=4976.8,5026.2
XS Rating Curve= 0 ,0
Exp/Cntr=0.3,0.1

Type RM Length L Ch R = 1 ,104786  ,458,458,458
BEGIN DESCRIPTION:
LITTLE ELKHART CREEK 132.0
END DESCRIPTION:
XS GIS Cut Line= 3
      3815149.57     10522260.21      3814349.61     10522610.19
       3814249.6     10523010.21
#Sta/Elev= 30
  4101.2  364.55    4139  362.04  4162.4   359.2  4167.8  359.79    4238  354.81
  4313.6  351.35  4383.8  345.12  4450.4  341.84  4686.3  336.44  4715.1  336.81
  4756.1  335.09  4854.3  335.66  4892.4   333.9  4936.6  335.17  4976.9   332.8
  4984.7  328.36  4992.4  326.26  5002.3  326.22    5005  325.72  5008.3  326.22
  5015.6  331.38  5025.9  332.73  5121.3  332.28    5129  333.88  5157.3  334.96
  5162.5  334.47  5177.6  335.91  5198.6  337.67  5203.7  336.86  5386.7  341.55
#Mann= 5 ,-1 , 0
  4101.2     .05       0  4892.4     .16       0  5002.3     .07       0
  5008.3     .16       0  5177.6     .05       0
Bank Sta=4936.6,5157.3
XS Rating Curve= 0 ,0
Exp/Cntr=0.3,0.1

Type RM Length L Ch R = 1 ,104328  ,580,580,580
BEGIN DESCRIPTION:
LITTLE ELKHART CREEK 131.0
END DESCRIPTION:
XS GIS Cut Line= 4
      3815600.14      10521966.2      3814579.27     10522271.77
      3814155.66     10522341.21      3813627.88     10522799.55
#Sta/Elev= 30
  3414.5  371.22  3689.7   365.9    3770  360.14  3795.3  362.21  3899.8  361.94
  3971.2  357.28  4037.4  349.97  4147.1  346.86  4246.4  338.87  4389.2  338.27
  4455.4  334.61  4510.2  335.93    4682  331.23  4783.8  333.18  4913.2  330.99
  4976.7  330.86  4983.6  330.63    4988  324.46  4990.7  323.96    4994  324.46
  5011.8  330.59  5026.1  330.85  5028.2  330.75  5054.6  327.96  5076.3   331.5
  5160.9  330.52  5338.5  348.72  5451.5  351.65  5528.7  358.23  5608.4  364.26
#Mann= 7 ,-1 , 0
  3414.5     .16       0  3689.7     .05       0  4913.2     .16       0
    4988     .07       0    4994     .16       0  5028.2     .05       0
  5528.7     .16       0
Bank Sta=4976.7,5026.1
XS Rating Curve= 0 ,0
Exp/Cntr=0.3,0.1

Type RM Length L Ch R = 1 ,103748  ,595,595,595
BEGIN DESCRIPTION:
LITTLE ELKHART CREEK 130.0
END DESCRIPTION:
XS GIS Cut Line= 3
       3814599.6      10520960.2      3813699.61     10522160.19
       3813549.6      10522560.2
#Sta/Elev= 30
  3463.9   352.1    3642  341.02  3682.4   340.7  4021.2  329.26  4106.6  330.57
  4221.2  327.52  4250.3  330.43  4306.6  329.77    4342   324.3  4377.7  323.86
  4447.3  323.55  4450.1  323.05  4453.3  323.55  4480.4  325.97  4506.6  327.12
  4606.6  324.23  4635.8  327.06  4850.3  326.13    4979  328.51  5009.3  323.78
  5049.3  332.38  5089.4  336.19  5094.7  334.38  5119.6  338.55  5205.1  339.56
    5230  337.76  5235.3  334.43  5284.3  337.19  5295.9  341.37  5391.1     349
#Mann= 6 ,-1 , 0
  3463.9     .05       0  3682.4     .16       0  4377.7     .05       0
  4447.3     .07       0  4453.3     .05       0  4480.4     .16       0
Bank Sta=4306.6,4506.6
XS Rating Curve= 0 ,0
Exp/Cntr=0.3,0.1

Type RM Length L Ch R = 1 ,103153  ,349,349,349
BEGIN DESCRIPTION:
LITTLE ELKHART CREEK 129.0
END DESCRIPTION:
XS GIS Cut Line= 3
       3813799.6     10521110.22      3813699.61     10521760.19
      3813099.61     10522410.19
#Sta/Elev= 30
  4373.7  350.67  4539.3  340.25    4657  329.08  4746.1  325.72  4849.2  323.33
    4920  323.97  4970.6  326.18  4980.7  325.79  4994.2  320.74  4996.9  320.24
  5000.2  320.74  5002.2  324.29  5021.2  324.09  5028.8  325.66  5045.2  326.05
    5187   325.7  5257.8  327.07    5398  324.52  5512.4  326.13  5611.7  330.48
  5655.9  330.55  5668.4  329.21  5675.2  331.42  5689.4  333.01  5696.7  335.59
  5760.2  343.73  5795.4  345.33  5823.8  344.21  5892.8  350.86  5915.9  354.01
#Mann= 7 ,-1 , 0
  4373.7     .05       0  4746.1     .16       0  4994.2     .07       0
  5000.2     .16       0    5398     .05       0  5655.9     .16       0
  5892.8     .05       0
Bank Sta=4970.6,5045.2
XS Rating Curve= 0 ,0
Exp/Cntr=0.3,0.1

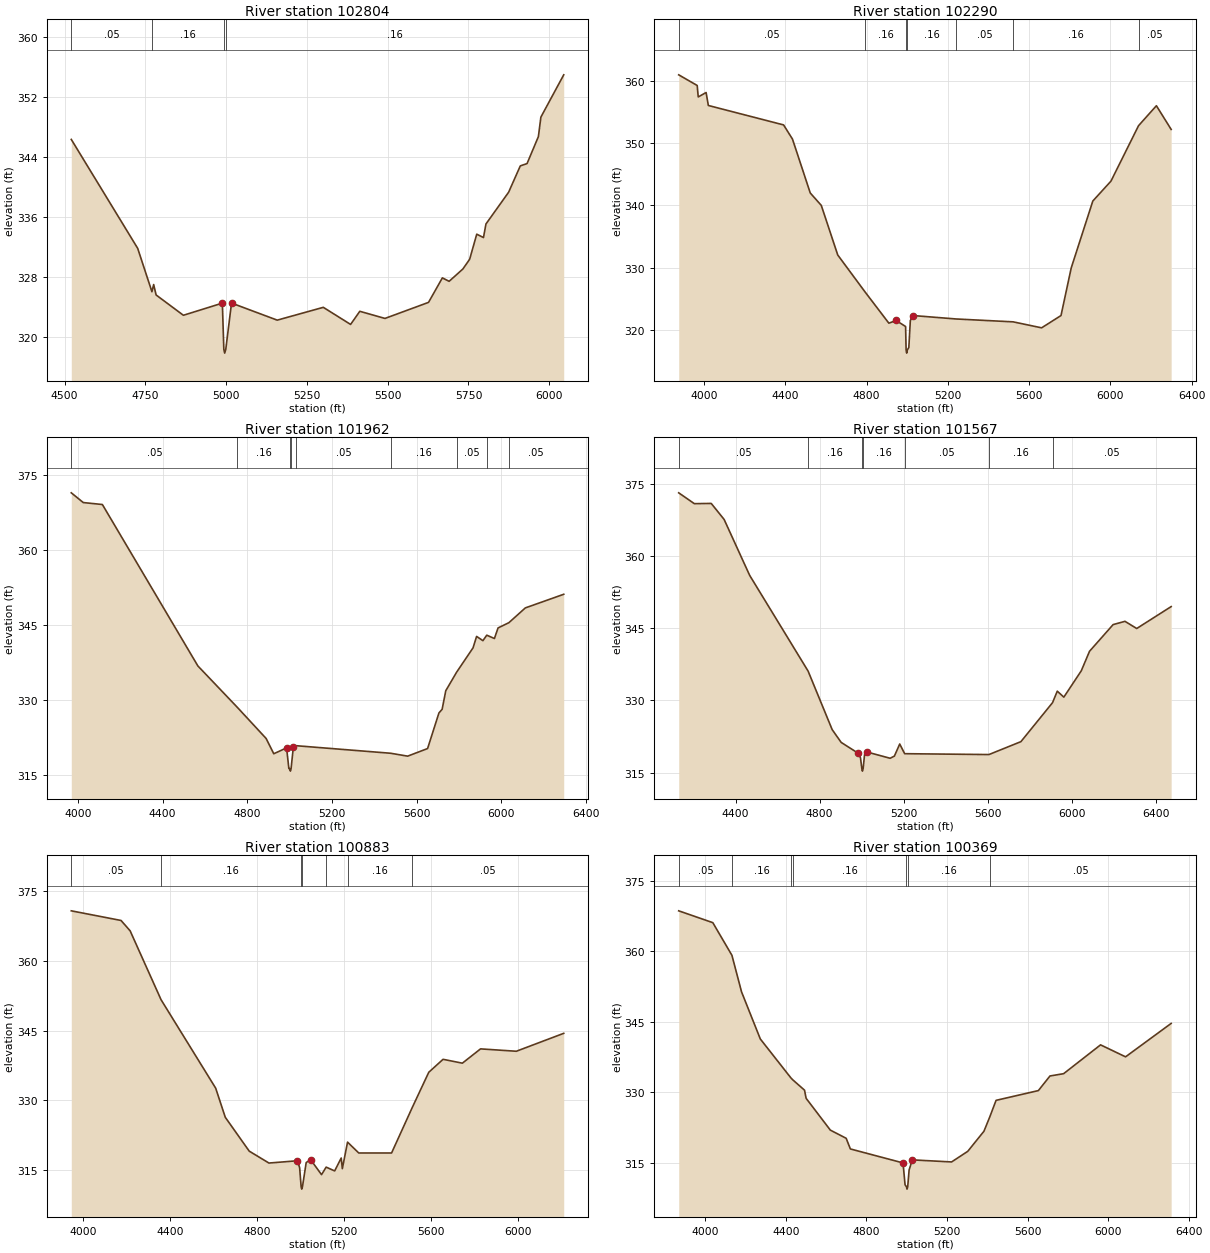
Type RM Length L Ch R = 1 ,102804  ,514,514,514
BEGIN DESCRIPTION:
LITTLE ELKHART CREEK 128.0
END DESCRIPTION:
XS GIS Cut Line= 3
      3813749.63     10521160.16      3813399.61     10521560.19
      3812749.62     10522310.18
#Sta/Elev= 30
  4520.9  346.33  4726.4   331.8  4770.5  326.01  4775.8  326.97  4783.4  325.58
  4867.8  322.87  4988.4  324.49    4993  318.32  4995.7  317.82    4999  318.32
  5016.8   324.5  5158.3  322.22  5300.8  323.93  5385.3  321.65  5413.8   323.4
  5491.7  322.45  5626.5  324.59  5669.3  327.86  5690.2   327.4  5732.9  329.05
  5753.8  330.35  5775.7  333.69  5796.5  333.24  5804.2  335.05  5874.4  339.29
  5910.5   342.8  5931.4  343.11  5966.5  346.71  5974.2  349.31  6044.9  354.95
#Mann= 4 ,-1 , 0
  4520.9     .05       0  4770.5     .16       0    4993     .07       0
    4999     .16       0
Bank Sta=4988.4,5016.8
XS Rating Curve= 0 ,0
Exp/Cntr=0.3,0.1

Type RM Length L Ch R = 1 ,102290  ,328,328,328
BEGIN DESCRIPTION:
LITTLE ELKHART CREEK 127.0
END DESCRIPTION:
XS GIS Cut Line= 4
      3813134.84     10520167.65      3813294.55     10520896.77
      3813030.66     10521493.99      3812572.33     10522410.66
#Sta/Elev= 30
  3874.9  360.97  3965.9  359.26    3971  357.42  4009.7  358.13  4020.8  356.05
  4391.2  352.93    4435  350.65  4522.4  342.01  4576.8  340.01  4657.8  332.05
    4792  326.13  4909.3  321.11  4945.2  321.54  4991.8  320.57  4994.3   316.8
    4997   316.3  5000.3   316.8  5007.7   317.2  5015.1  321.53  5029.6  322.33
  5241.2  321.78  5521.3  321.32  5661.3  320.36  5756.8  322.33  5807.1  329.97
  5913.4  340.71  6002.8  343.91  6138.6  352.81  6226.4  356.01  6299.1  352.21
#Mann= 7 ,-1 , 0
  3874.9     .05       0    4792     .16       0  4994.3     .07       0
  5000.3     .16       0  5241.2     .05       0  5521.3     .16       0
  6138.6     .05       0
Bank Sta=4945.2,5029.6
XS Rating Curve= 0 ,0
Exp/Cntr=0.3,0.1

Type RM Length L Ch R = 1 ,101962  ,395,395,395
BEGIN DESCRIPTION:
LITTLE ELKHART CREEK 126.0
END DESCRIPTION:
XS GIS Cut Line= 3
       3812912.6     10520153.68      3812961.22     10520896.77
      3812384.83     10522368.98
#Sta/Elev= 30
  3968.4  371.47    4025  369.52  4115.2  369.13  4566.2   336.8  4752.7   328.5
  4888.6  322.27  4924.7  319.21  4985.2  320.39    4996  316.24  5000.4  316.23
  5003.2  315.73  5006.4  316.23  5017.4  320.66  5030.6  320.82  5476.7  319.31
  5556.9  318.73  5651.1  320.25  5704.7  327.38  5719.8  328.11    5737  331.83
  5788.1  335.54  5865.8  340.42  5882.6  342.71  5912.4  341.86  5930.7  342.96
  5966.7  342.29    5984  344.41    6035  345.46  6112.8  348.42  6294.1  351.15
#Mann= 9 ,-1 , 0
  3968.4     .05       0  4752.7     .16       0  5000.4     .07       0
  5006.4     .16       0  5030.6     .05       0  5476.7     .16       0
  5788.1     .05       0  5930.7     .16       0    6035     .05       0
Bank Sta=4985.2,5017.4
XS Rating Curve= 0 ,0
Exp/Cntr=0.3,0.1

Type RM Length L Ch R = 1 ,101567  ,684,684,684
BEGIN DESCRIPTION:
LITTLE ELKHART CREEK 125.0
END DESCRIPTION:
XS GIS Cut Line= 3
      3812669.55     10520146.75      3812482.05     10521327.32
      3812169.55     10522431.48
#Sta/Elev= 30
  4129.6  373.07    4204  370.82  4284.3  370.87  4345.7  367.54  4467.2  355.93
  4745.3  336.05  4859.7  323.91  4902.6  321.25  4983.6     319  4994.3  318.09
  5000.9  315.79  5003.6  315.29  5006.9  315.79    5014  318.81  5024.1  319.27
  5135.5  317.96  5155.7  318.41  5181.1  320.92  5204.6  318.91  5605.5  318.73
  5757.7  321.41  5908.1   329.5  5930.7  331.89  5961.9  330.65  6044.9  336.12
  6084.1  340.17  6196.3  345.71  6252.9  346.39  6308.6   344.9  6472.5  349.45
#Mann= 7 ,-1 , 0
  4129.6     .05       0  4745.3     .16       0  5000.9     .07       0
  5006.9     .16       0  5204.6     .05       0  5605.5     .16       0
  5908.1     .05       0
Bank Sta=4983.6,5024.1
XS Rating Curve= 0 ,0
Exp/Cntr=0.3,0.1

Type RM Length L Ch R = 1 ,100883  ,514,514,514
BEGIN DESCRIPTION:
LITTLE ELKHART CREEK 124.0
END DESCRIPTION:
XS GIS Cut Line= 4
      3812572.31     10520174.57      3812100.11     10520827.32
      3812037.61     10521320.38      3812148.51     10522276.92
#Sta/Elev= 30
  3946.7  370.72  4175.6  368.65  4217.4  366.43  4359.8  351.63  4611.1  332.64
  4655.2  326.39  4765.3  319.13    4856  316.57  4987.1  317.06  4997.2   315.6
  5004.2  311.47    5007  310.97  5010.2  311.47  5027.4  316.67  5047.6  317.31
    5098  314.08  5119.3  315.69  5158.4  314.88  5188.6  317.65  5193.7  315.36
  5217.7  321.06  5269.3  318.73  5420.3  318.73  5515.1  328.46  5591.4  336.06
  5657.2  338.84  5745.9  338.01  5829.6  341.08  5994.1  340.57  6212.3  344.42
#Mann= 7 ,-1 , 0
  3946.7     .05       0  4359.8     .16       0  5004.2     .07       0
  5010.2     .16       0  5119.3     .05       0  5217.7     .16       0
  5515.1     .05       0
Bank Sta=4987.1,5047.6
XS Rating Curve= 0 ,0
Exp/Cntr=0.3,0.1

Type RM Length L Ch R = 1 ,100369  ,349,349,349
BEGIN DESCRIPTION:
LITTLE ELKHART CREEK 123.0
END DESCRIPTION:
XS GIS Cut Line= 4
       3812468.2      10520250.9      3811780.66      10520792.6
      3811704.27     10521625.93      3812064.99     10522264.12
#Sta/Elev= 30
  3867.8  368.64  4037.1  366.12    4132  359.17  4179.8  351.38  4272.9  341.35
  4425.3  333.03  4434.4  332.63  4492.5  330.44  4500.5   328.7  4620.7  321.93
  4699.3  320.19  4720.1  317.92  4981.7  314.94  4991.7  310.28  4998.8  309.86
  5001.5  309.36  5004.8  309.86  5011.8  313.43  5027.7  315.59  5222.7  315.15
    5303  317.41  5383.4  321.69  5411.8  324.68  5443.6  328.27  5653.7  330.35
  5711.2  333.46  5779.1  333.95  5962.4  340.09  6086.6  337.54    6313  344.66
#Mann= 7 ,-1 , 0
  3867.8     .05       0    4132     .16       0  4425.3     .05       0
  4434.4     .16       0  4998.8     .07       0  5004.8     .16       0
  5411.8     .05       0
Bank Sta=4981.7,5027.7
XS Rating Curve= 0 ,0
Exp/Cntr=0.3,0.1