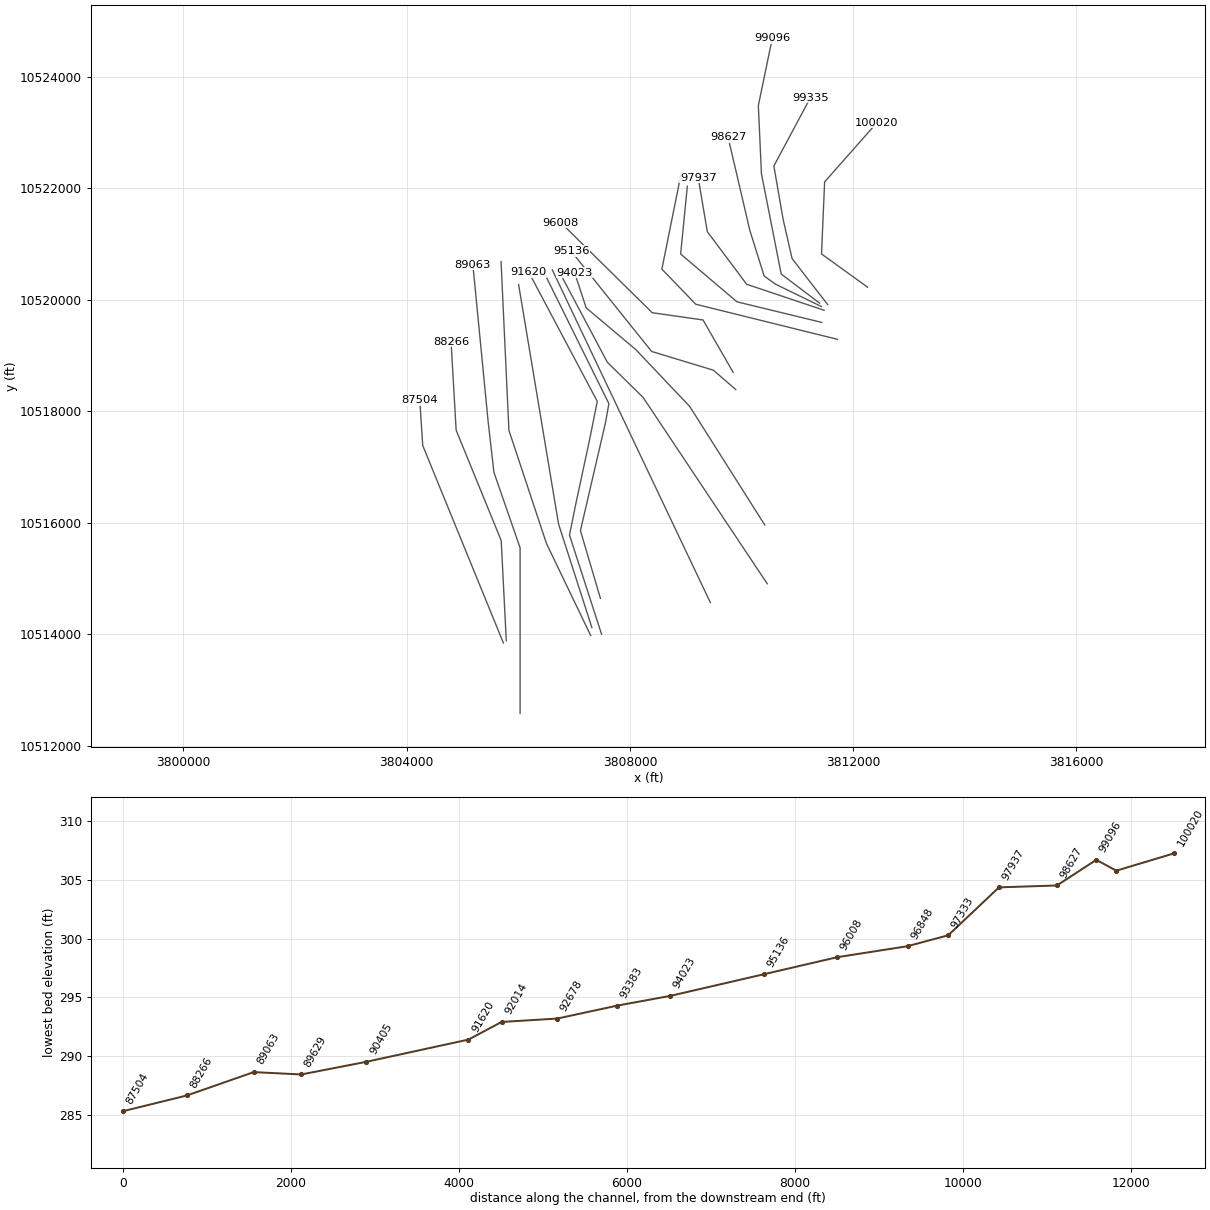
HEC-RAS study LITTLE ELKHART CREEK.prj: LITTLE ELKHART CREEK Base Level Engineering

--- LITTLE ELKHART CREEK.g01 (geometry) --- (continued)

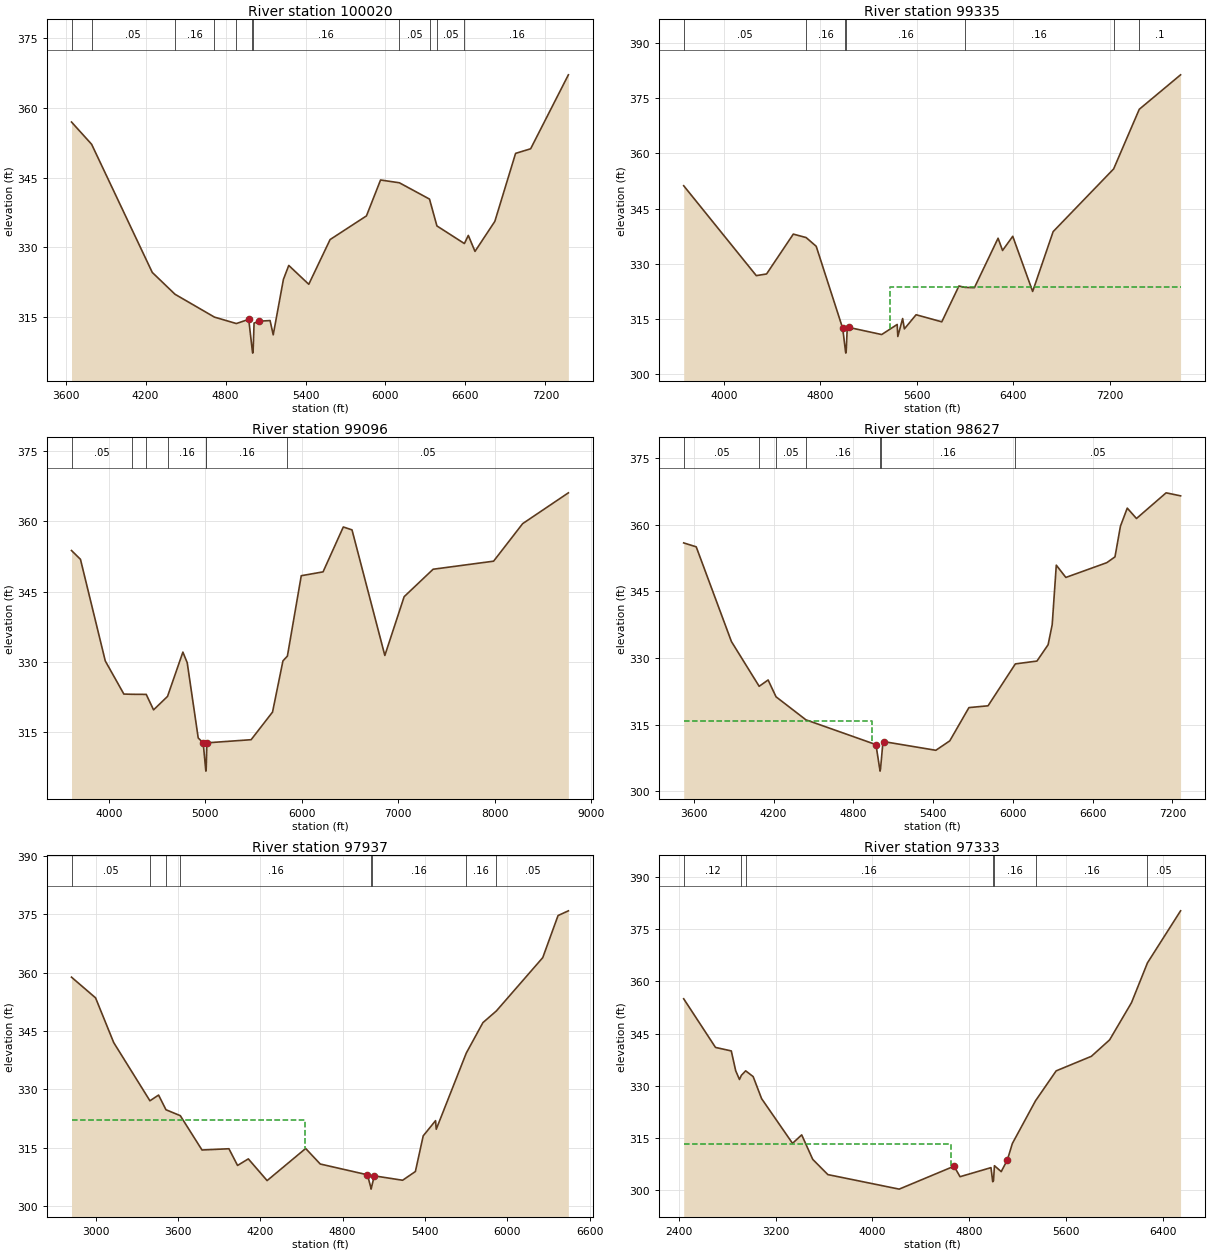
Type RM Length L Ch R = 1 ,100020  ,685,685,685
BEGIN DESCRIPTION:
LITTLE ELKHART CREEK 122.0
END DESCRIPTION:
XS GIS Cut Line= 4
      3812259.82     10520223.16      3811433.44     10520820.38
        3811489.     10522112.04      3812425.55     10523173.48
#Sta/Elev= 30
  3644.3  357.01  3795.2  352.22  4250.3  324.63  4420.5  319.94    4717  315.01
  4881.2  313.63    4974  314.53    5001  307.76  5003.8  307.26    5007  307.76
    5014  313.73  5054.1  314.14  5134.1  314.27  5157.8   311.2  5234.2  323.13
  5274.3  326.14  5424.4  322.08  5584.6  331.71  5857.2   336.8  5963.1  344.53
  6104.4  343.93  6330.3  340.42    6386  334.64    6592  330.85  6621.5   332.6
  6671.7  329.16  6820.6  335.63  6976.2  350.26  7089.1  351.25  7372.3  367.17
#Mann= 11 ,-1 , 0
  3644.3     .16       0  3795.2     .05       0  4420.5     .16       0
    4717     .05       0  4881.2     .16       0    5001     .07       0
    5007     .16       0  6104.4     .05       0  6330.3     .16       0
    6386     .05       0    6592     .16       0
Bank Sta=4974,5054.1
XS Rating Curve= 0 ,0
Exp/Cntr=0.3,0.1

Type RM Length L Ch R = 1 ,99335   ,239,239,239
BEGIN DESCRIPTION:
LITTLE ELKHART CREEK 121.0
END DESCRIPTION:
XS GIS Cut Line= 5
      3811544.55     10519910.66      3810905.66     10520737.04
      3810745.94     10521438.43      3810579.27     10522396.77
      3811232.03     10523618.95
#Sta/Elev= 30
  3665.4  351.19  4267.7  326.81  4352.8  327.26  4574.7  338.07  4681.3  337.13
  4764.7  334.77  4984.9  312.48  5007.6  306.29  5010.4  305.79  5013.6  306.29
  5020.9  311.77  5033.1  312.78    5308  310.83  5436.6  313.56  5441.7   310.3
  5481.8  315.17  5496.2  312.36  5593.5   316.2  5806.6  314.28  5948.7  323.99
  5999.5  323.62  6077.3  323.54  6273.5  336.95  6310.8  333.63  6395.3  337.48
  6560.4  322.51  6730.4  338.74  7232.3  355.75  7444.9  371.92  7787.6  381.27
#Mann= 7 ,-1 , 0
  3665.4     .05       0  4681.3     .16       0  5007.6     .07       0
  5013.6     .16       0  5999.5     .16       0  7232.3     .05       0
  7444.9      .1       0
#XS Ineff= 2 , 0
                            5375          323.78
Permanent Ineff=
       F       F
Bank Sta=4984.9,5033.1
XS Rating Curve= 0 ,0
Exp/Cntr=0.3,0.1

Type RM Length L Ch R = 1 ,99096   ,469,469,469
BEGIN DESCRIPTION:
LITTLE ELKHART CREEK 120.0
END DESCRIPTION:
XS GIS Cut Line= 5
      3811398.68     10519938.46      3810711.22     10520459.27
      3810357.05     10522257.88       3810301.5      10523480.1
      3810551.17     10524686.85
#Sta/Elev= 30
  3614.3  353.74  3707.2  351.86  3964.4   330.2  4157.1  323.14  4242.7  323.09
  4388.9  323.07    4465  319.77  4609.8  322.64    4769  332.08    4814  329.83
  4928.1  313.77  4979.5  312.75  5004.7  307.21  5007.4  306.71  5010.7  307.21
  5017.9  312.74  5476.5  313.41  5698.5   319.3  5806.4  330.21  5852.6  331.24
  5996.3  348.37  6222.3  349.19  6432.3  358.76  6522.4  358.14  6862.8  331.37
    7063   343.9  7363.3  349.75  7990.4  351.47  8291.7  359.47  8765.7  366.04
#Mann= 7 ,-1 , 0
  3614.3     .05       0  4242.7     .08       0  4388.9     .05       0
  4609.8     .16       0  5004.7     .07       0  5010.7     .16       0
  5852.6     .05       0
Bank Sta=4979.5,5017.9
XS Rating Curve= 0 ,0
Exp/Cntr=0.3,0.1

Type RM Length L Ch R = 1 ,98627   ,690,690,690
BEGIN DESCRIPTION:
LITTLE ELKHART CREEK 119.0
END DESCRIPTION:
XS GIS Cut Line= 5
      3811433.41     10519875.95      3810607.05     10520278.71
      3810405.66     10520424.54      3810148.72     10521243.99
      3809759.82      10522910.7
#Sta/Elev= 30
  3523.6  355.89  3617.8  355.01  3882.7  333.69  4091.4  323.62  4158.7  325.04
  4218.3  321.26  4442.9  316.08  4969.9   310.5  4998.4  305.03  5001.1  304.53
  5004.4  305.03  5022.3  310.95  5033.7  311.15  5420.6  309.22  5525.4  311.34
  5669.6  318.83  5813.4  319.23  6018.8  328.66  6181.2   329.3  6265.2  332.97
    6296   337.5  6326.8  350.88  6398.7  348.12  6706.8  351.44  6768.4  352.75
  6809.5  359.66  6860.8  363.72  6930.1  361.38  7153.1  367.16  7261.8  366.48
#Mann= 7 ,-1 , 0
  3523.6     .05       0  4091.4     .08       0  4218.3     .05       0
  4442.9     .16       0  4998.4     .07       0  5004.4     .16       0
  6018.8     .05       0
#XS Ineff= 2 , 0
         4938.64  315.77
Permanent Ineff=
       F       F
Bank Sta=4969.9,5033.7
XS Rating Curve= 0 ,0
Exp/Cntr=0.3,0.1

Type RM Length L Ch R = 1 ,97937   ,604,604,604
BEGIN DESCRIPTION:
LITTLE ELKHART CREEK 118.0
END DESCRIPTION:
XS GIS Cut Line= 4
      3811481.19     10519809.53      3810092.29     10520276.11
        3809387.     10521220.12      3809224.49     10522184.36
#Sta/Elev= 30
    2824  358.81  2999.3   353.5  3131.6  342.01  3395.6  327.06  3458.6  328.53
  3512.4  324.76  3616.9  323.24  3775.1  314.42  3971.3  314.74  4034.3  310.45
  4112.7  312.14  4249.7  306.56  4530.6  314.81  4636.9  310.82  4980.8  308.05
  5004.9  304.87  5007.6  304.37  5010.9  304.87  5030.7  307.78  5237.2  306.65
  5330.3  308.89  5387.3  318.05  5477.3  321.96  5482.4  319.75  5700.9  339.29
  5822.6  347.14  5920.7  350.14  6258.6  363.83  6370.2  374.64  6445.4  375.85
#Mann= 8 ,-1 , 0
    2824     .05       0  3395.6     .08       0  3512.4     .05       0
  3616.9     .16       0  5004.9     .07       0  5010.9     .16       0
  5700.9     .16       0  5920.7     .05       0
#XS Ineff= 2 , 0
         4527.27  322.13
Permanent Ineff=
       F       F
Bank Sta=4980.8,5030.7
XS Rating Curve= 0 ,0
Exp/Cntr=0.3,0.1

Type RM Length L Ch R = 1 ,97333   ,485,485,485
BEGIN DESCRIPTION:
LITTLE ELKHART CREEK 117.0
END DESCRIPTION:
XS GIS Cut Line= 4
      3811437.77     10519592.51      3809918.68     10519961.44
      3808909.57     10520818.64      3809028.92      10522033.9
#Sta/Elev= 30
  2440.8  355.01  2703.8  341.03  2834.3  340.02  2870.9  334.31    2902  331.81
  2917.5     333  2953.4   334.3  3015.2  332.64  3084.9  326.31  3340.7  313.45
  3416.5  315.89  3507.7  308.85  3632.6  304.47  4222.5  300.29  4676.3  306.88
  4725.7  303.86  4981.6  306.47  4995.9  302.42  5002.5   302.7  5010.2  307.02
  5066.2  305.32  5116.8  308.66  5158.4  313.41  5349.7  325.68  5520.6  334.29
    5812  338.48  5962.7  343.21  6143.5   353.9  6275.5  365.35  6549.2   380.3
#Mann= 7 ,-1 , 0
  2440.8     .12       0  2917.5     .08       0  2953.4     .16       0
  4995.9     .07       0  5002.5     .16       0  5349.7     .16       0
  6275.5     .05       0
#XS Ineff= 2 , 0
         4653.41  313.39
Permanent Ineff=
       F       F
Bank Sta=4676.3,5116.8
XS Rating Curve= 0 ,0
Exp/Cntr=0.3,0.1

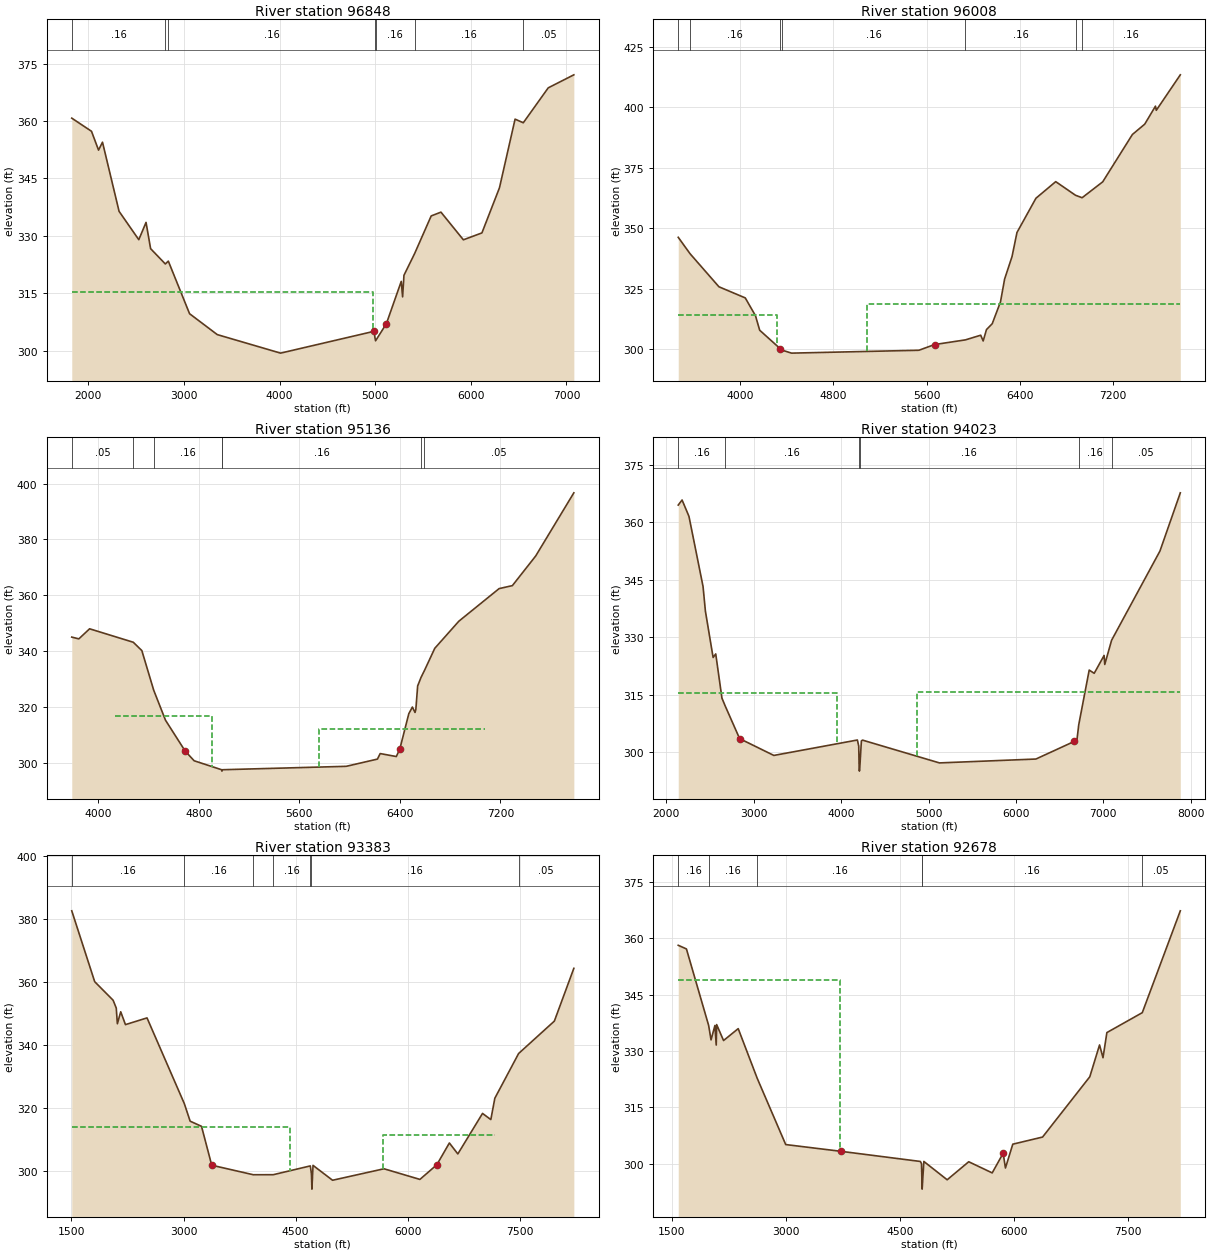
Type RM Length L Ch R = 1 ,96848   ,840,840,840
BEGIN DESCRIPTION:
LITTLE ELKHART CREEK 116.0
END DESCRIPTION:
XS GIS Cut Line= 4
      3811719.89     10519288.69      3809180.84     10519918.03
       3808573.2     10520547.37      3808920.43     10522272.68
#Sta/Elev= 30
  1826.8  360.76  2033.1  357.33  2106.8  352.41  2148.2  354.48  2321.6  336.41
  2527.7     329  2603.5  333.52  2651.3  326.66  2805.2  322.66  2836.7   323.4
  3058.7  309.66  3348.4   304.2  4010.4  299.36  4989.5  305.07  4996.7   303.5
  5003.7  302.58  5116.9  307.05  5272.5  318.11  5286.7  314.06  5300.8   319.7
  5412.2  325.37  5585.6  335.21  5687.6   336.2  5922.2  328.97    6116  330.77
  6299.6  342.56  6462.8   360.5  6548.7  359.55  6809.6  368.68  7077.4  372.08
#Mann= 7 ,-1 , 0
  1826.8     .16       0  2805.2     .08       0  2836.7     .16       0
  4996.7     .07       0  5003.7     .16       0  5412.2     .16       0
  6548.7     .05       0
#XS Ineff= 2 , 0
         4981.25  315.23
Permanent Ineff=
       F       F
Bank Sta=4989.5,5116.9
XS Rating Curve= 0 ,0
Exp/Cntr=0.3,0.1

Type RM Length L Ch R = 1 ,96008   ,872,872,872
BEGIN DESCRIPTION:
LITTLE ELKHART CREEK 115.0
END DESCRIPTION:
XS GIS Cut Line= 5
      3809850.63     10518695.74      3809441.25     10519408.05
      3809311.04     10519635.91      3808399.59     10519766.12
       3806761.1     10521382.91
#Sta/Elev= 30
  3469.8  346.25  3571.5  339.45  3819.1  325.81  4044.8  321.22  4132.4  313.86
  4168.5  307.87  4345.4  300.22  4361.2  299.64  4441.6  298.42  5533.9   299.6
  5668.3  301.96  5933.2  303.89  6064.3  305.82  6085.5  303.44  6113.8  308.14
  6163.2  310.57    6234  319.59  6269.4  329.02    6333  338.29  6375.4  348.24
  6538.1  362.38  6707.8  369.23  6877.5  363.61  6934.1  362.59  7110.8  369.15
  7365.4   388.7  7471.4  392.98  7563.4  400.41  7570.4  398.69  7776.4  413.34
#Mann= 7 ,-1 , 0
  3469.8     .05       0  3571.5     .16       0  4345.4     .07       0
  4361.2     .16       0  5933.2     .16       0  6877.5     .05       0
  6934.1     .16       0
#XS Ineff= 2 , 0
         4318.18  314.25 5085.23          318.86
Permanent Ineff=
       F       F
Bank Sta=4345.4,5668.3
XS Rating Curve= 0 ,0
Exp/Cntr=0.3,0.1

Type RM Length L Ch R = 1 ,95136   ,1113,1113,1113
BEGIN DESCRIPTION:
LITTLE ELKHART CREEK 114.0
END DESCRIPTION:
XS GIS Cut Line= 4
      3809896.95     10518388.11      3809495.51     10518735.31
      3808388.74     10519071.68      3806945.57     10520872.93
#Sta/Elev= 30
    3789  344.99  3845.3  344.36  3930.9  347.97  4278.5  343.15  4346.8  340.15
  4440.9  325.99    4535  315.21  4691.7  304.15    4763  300.68  4981.4  297.47
  4984.1  296.97  4987.4  297.47  5973.4  298.69  6221.5  301.28  6243.4  303.26
  6371.6   302.2  6399.2  304.81  6471.2  317.55  6499.7  319.93  6520.8  317.99
  6527.2  319.05  6541.6  327.49  6568.8  330.58    6596  333.05  6677.7  340.97
  6869.7   350.7  7189.8  362.37  7295.5  363.44  7481.1  374.07  7784.6  396.69
#Mann= 7 ,-1 , 0
    3789     .05       0  4278.5     .16       0  4440.9     .16       0
  4981.4     .07       0  4987.4     .16       0  6568.8     .16       0
    6596     .05       0
#XS Ineff= 2 ,-1
 4133.52 4903.41  316.65 5755.68 7073.86  311.94
Permanent Ineff=
       F       F
Bank Sta=4691.7,6399.2
XS Rating Curve= 0 ,0
Exp/Cntr=0.3,0.1

Type RM Length L Ch R = 1 ,94023   ,640,640,640
BEGIN DESCRIPTION:
LITTLE ELKHART CREEK 112.0
END DESCRIPTION:
XS GIS Cut Line= 5
      3810417.83      10515957.5      3809072.33     10518084.27
      3808106.62     10519104.23      3807216.86     10519852.93
      3807010.68     10520482.31
#Sta/Elev= 30
  2135.5  364.47  2179.5  365.79  2258.3  361.53  2419.4  343.26  2446.5  336.82
  2534.7  324.75  2564.7  325.68  2635.7  314.17  2671.2  312.21  2838.2   303.6
  3229.8  299.22    4186  303.24  4201.3  301.66  4206.5  295.63  4209.2  295.13
  4212.5  295.63  4231.8  303.02    4245  303.21  5125.2  297.27  6229.2  298.28
  6668.8  302.88  6697.4  302.98  6719.4  307.21  6839.2  321.47  6896.4  320.62
  7009.6  325.28  7017.3  322.93  7095.7  329.25  7648.9  352.49  7881.9  367.66
#Mann= 6 ,-1 , 0
  2135.5     .16       0  2671.2     .16       0  4206.5     .07       0
  4212.5     .16       0  6719.4     .16       0  7095.7     .05       0
#XS Ineff= 2 , 0
            3950  315.55 4867.05          315.63
Permanent Ineff=
       F       F
Bank Sta=2838.2,6668.8
XS Rating Curve= 0 ,0
Exp/Cntr=0.3,0.1

Type RM Length L Ch R = 1 ,93383   ,705,705,705
BEGIN DESCRIPTION:
LITTLE ELKHART CREEK 111.0
END DESCRIPTION:
XS GIS Cut Line= 4
      3810461.24     10514904.98      3808236.83     10518247.03
      3807596.63     10518876.37       3806750.3     10520471.38
#Sta/Elev= 30
  1504.5  382.48  1811.2  360.03  2057.6  354.15  2099.7  351.67  2114.7  346.69
  2159.4  350.49  2222.9  346.42  2511.5  348.55  3010.4  321.39  3088.5  315.82
  3240.6  314.19  3377.1  301.87  3933.1  298.85  4200.1  298.86  4696.5  301.65
  4711.5  299.07  4717.8  294.29  4732.6  301.82  4994.1   297.1  5682.1  300.74
  6162.9  297.37  6389.2  302.01    6557  308.91  6670.2  305.44  7000.7  318.28
  7111.7  316.33  7165.3  323.09  7483.8  337.27  7961.9  347.54  8222.5  364.26
#Mann= 7 ,-1 , 0
  1504.5     .16       0  3010.4     .16       0  3933.1     .16       0
  4200.1     .16       0  4696.5     .07       0  4711.5     .16       0
  7483.8     .05       0
#XS Ineff= 2 ,-1
  1504.5 4427.27  313.92 5663.64 7172.73  311.48
Permanent Ineff=
       F       F
Bank Sta=3377.1,6389.2
XS Rating Curve= 0 ,0
Exp/Cntr=0.3,0.1

Type RM Length L Ch R = 1 ,92678   ,664,664,664
BEGIN DESCRIPTION:
LITTLE ELKHART CREEK 110.0
END DESCRIPTION:
XS GIS Cut Line= 2
      3809441.24     10514568.67      3806609.53     10520535.87
#Sta/Elev= 30
  1584.9  358.15  1692.7  357.18  1985.1  336.79  2016.5  332.95  2067.5  336.79
  2084.7  331.58  2090.2  337.03  2181.1  332.78    2374  335.95  2624.1  322.71
  2998.9  305.07  3725.7  303.27  4770.7  300.57  4785.5  299.96  4793.2   293.2
  4793.7   293.2  4816.2  300.57  5122.8  295.69  5406.6  300.49  5715.3  297.52
  5859.2  302.75  5889.5  298.83    5986  305.17  6377.9  307.07  6999.2  323.13
  7127.5   331.6  7172.9   328.2  7223.9   334.9  7689.6   340.2  8189.9  367.33
#Mann= 6 ,-1 , 0
  1584.9     .16       0  1985.1     .16       0  2624.1     .16       0
  4793.2     .07       0  4793.7     .16       0  7689.6     .05       0
#XS Ineff= 2 , 0
         3719.16  348.78
Permanent Ineff=
       F       F
Bank Sta=3725.7,5859.2
XS Rating Curve= 0 ,0
Exp/Cntr=0.3,0.1

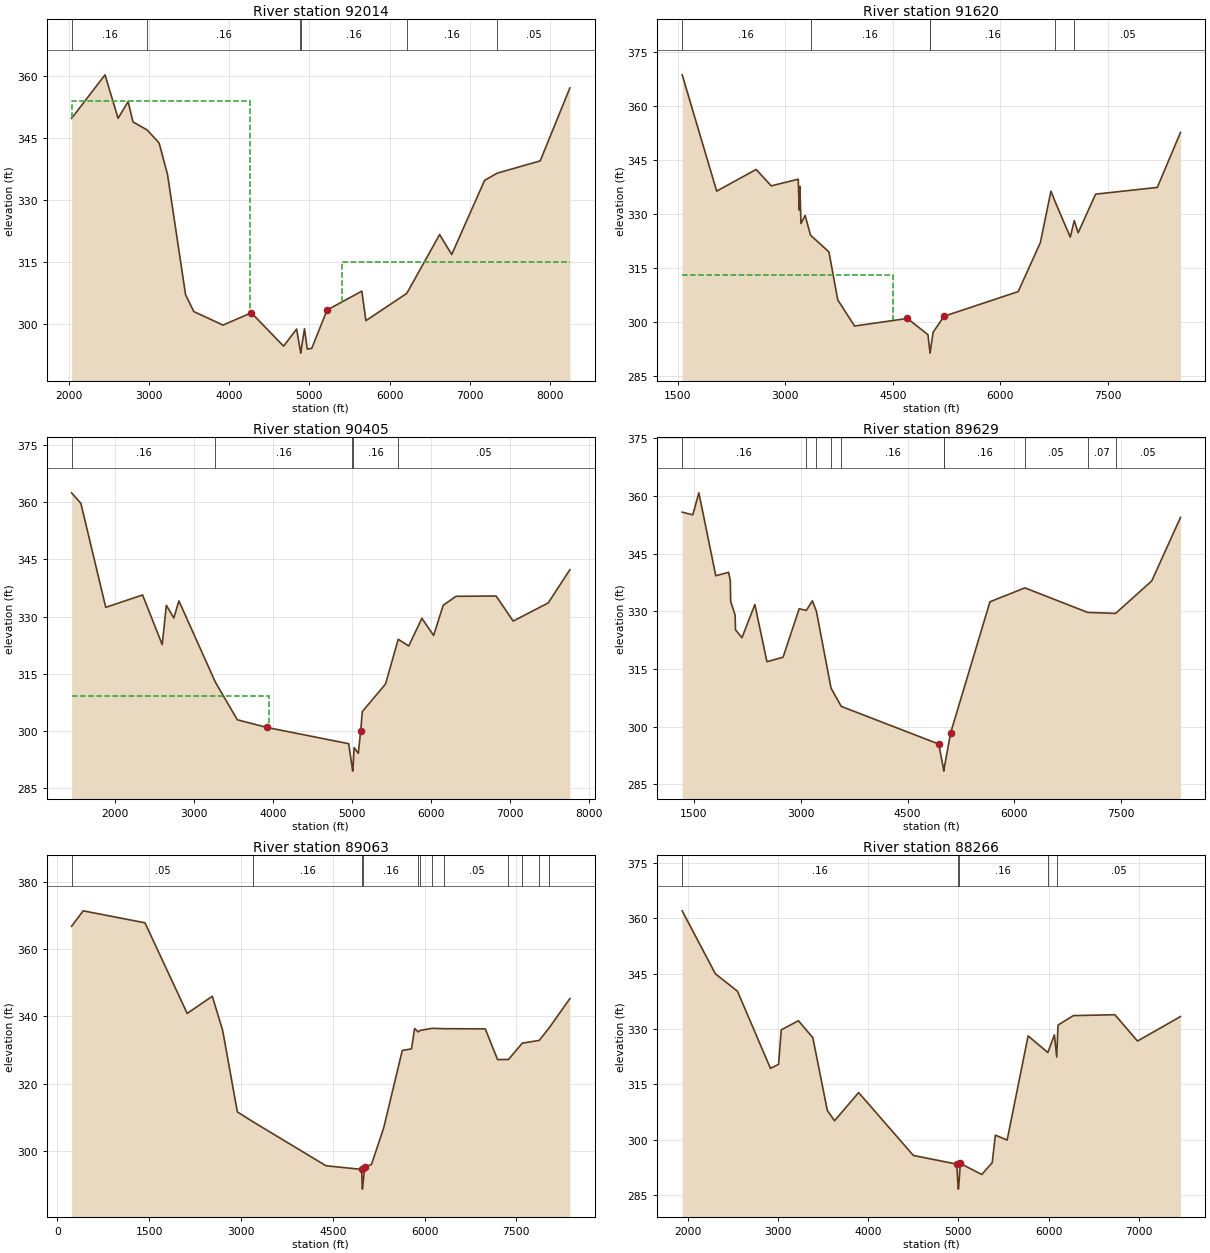
Type RM Length L Ch R = 1 ,92014   ,394,394,394
BEGIN DESCRIPTION:
LITTLE ELKHART CREEK 109.0
END DESCRIPTION:
XS GIS Cut Line= 5
      3807472.06     10514643.44        3807114.     10515858.68
      3807561.48     10517787.93      3807623.98     10518135.16
      3806464.42     10520482.06
#Sta/Elev= 30
  2032.9  349.81  2450.1  360.37  2613.3  349.84  2738.4  353.89    2799  348.96
  2976.1     347    3125  343.86  3230.2  336.21  3455.3  307.06    3558  302.99
  3922.3  299.71  4276.5  302.68  4678.3   294.6  4841.2  298.75  4888.6  293.41
  4891.3  292.91  4894.6  293.41  4939.4  298.82  4974.6  293.89  5029.8  294.07
    5221  303.35  5654.8  307.94  5705.6  300.78  6215.9   307.4  6625.4  321.65
  6776.4  316.82  7186.4  334.78  7343.5  336.53  7880.6  339.51  8250.8  357.19
#Mann= 6 ,-1 , 0
  2032.9     .16       0  2976.1     .16       0  4888.6     .07       0
  4894.6     .16       0  6215.9     .16       0  7343.5     .05       0
#XS Ineff= 2 , 0
         4255.25  354.05  5412.5          314.93
Permanent Ineff=
       F       F
Bank Sta=4276.5,5221
XS Rating Curve= 0 ,0
Exp/Cntr=0.3,0.1

Type RM Length L Ch R = 1 ,91620   ,1215,1215,1215
BEGIN DESCRIPTION:
LITTLE ELKHART CREEK 108.0
END DESCRIPTION:
XS GIS Cut Line= 6
      3807492.91     10513999.27      3806917.81     10515778.82
       3807033.7     10516350.43      3807276.76     10517482.38
      3807415.64     10518176.82      3806186.79     10520495.68
#Sta/Elev= 30
  1565.4  368.61  2046.1  336.35  2595.8  342.36  2806.5  337.81  3182.7  339.66
  3195.3   331.1  3205.8  337.66    3220  327.36  3278.8   329.6  3353.3  324.14
  3610.4  319.48  3732.9  306.19  3967.5  298.93  4703.8  301.03  4990.2  296.53
  5016.6  291.91  5019.4  291.41  5022.6  291.91  5061.8  297.18  5213.3  301.64
  6247.5  308.48  6556.3  322.07  6703.8  336.34  6758.5  333.59  6972.7   323.6
  7029.1  328.17  7082.7  324.79  7325.9  335.51    8186  337.38  8509.1  352.64
#Mann= 6 ,-1 , 0
  1565.4     .16       0  3353.3     .16       0  5016.6     .07       0
  5022.6     .16       0  6758.5     .16       0  7029.1     .05       0
#XS Ineff= 2 , 0
         4509.09  313.04
Permanent Ineff=
       F       F
Bank Sta=4703.8,5213.3
XS Rating Curve= 0 ,0
Exp/Cntr=0.3,0.1

Type RM Length L Ch R = 1 ,90405   ,776,776,776
BEGIN DESCRIPTION:
LITTLE ELKHART CREEK 107.0
END DESCRIPTION:
XS GIS Cut Line= 3
      3807319.28     10514118.68       3806722.5     10515974.13
      3806006.36       10520271.
#Sta/Elev= 30
  1448.5  362.43  1566.3  359.66  1880.8  332.43  2346.9  335.67  2595.1  322.67
  2647.6  332.95  2742.4  329.65  2806.6  334.12  3267.4  312.85  3545.6  302.97
  3920.7  300.96  4954.8  296.71  5002.5  290.02  5005.2  289.52  5008.5  290.02
  5023.9  295.68  5076.5  294.19  5106.9  300.07  5127.2  305.12  5421.2  312.34
  5581.8  324.06  5715.2  322.31  5880.6  329.57  6029.4  325.06  6151.1  332.98
  6313.3  335.32  6820.2   335.4  7036.3  328.83  7479.2  333.58  7753.7  342.29
#Mann= 5 ,-1 , 0
  1448.5     .16       0  3267.4     .16       0  5002.5     .07       0
  5008.5     .16       0  5581.8     .05       0
#XS Ineff= 2 , 0
         3947.16  309.17
Permanent Ineff=
       F       F
Bank Sta=3920.7,5106.9
XS Rating Curve= 0 ,0
Exp/Cntr=0.3,0.1

Type RM Length L Ch R = 1 ,89629   ,566,566,566
BEGIN DESCRIPTION:
LITTLE ELKHART CREEK 105.0
END DESCRIPTION:
XS GIS Cut Line= 4
      3807297.57     10513977.63      3806505.49     10515626.91
      3805832.75     10517655.99      3805691.69     10520683.29
#Sta/Elev= 30
  1335.2  355.79  1484.2   355.1  1569.2  360.82  1806.8  339.26  1987.9  340.14
  2010.6  337.98  2016.1  332.57  2078.5  328.99    2084  325.19  2174.6  323.15
  2355.7  331.77  2525.3   316.9  2751.8  318.06  2978.2  330.67  3077.9  330.23
  3163.9  332.73  3220.2     330  3425.5  310.01  3568.7  305.28  4938.2  295.48
  5005.6  288.94  5008.4  288.44  5011.6  288.94  5103.7   298.3  5657.1  332.48
  6147.6   336.1  7029.1  329.72  7421.3  329.46  7929.6  337.91  8333.1  354.42
#Mann= 10 ,-1 , 0
  1335.2     .16       0  3077.9     .05       0  3220.2     .16       0
  3425.5     .05       0  3568.7     .16       0  5005.6     .07       0
  5011.6     .16       0  6147.6     .05       0  7029.1     .07       0
  7421.3     .05       0
Bank Sta=4938.2,5103.7
XS Rating Curve= 0 ,0
Exp/Cntr=0.3,0.1

Type RM Length L Ch R = 1 ,89063   ,797,797,797
BEGIN DESCRIPTION:
LITTLE ELKHART CREEK 104.0
END DESCRIPTION:
XS GIS Cut Line= 5
      3806033.05     10512580.65      3806033.05     10515549.43
       3805564.3      10516903.6      3805460.13     10517815.06
      3805186.82     10520626.33
#Sta/Elev= 30
   231.8  366.76   421.3  371.35  1431.3  367.79  2121.3  340.86  2531.3  345.96
  2701.3  335.78  2941.3  311.59  3200.6  308.62    4390  295.58  4972.4  294.51
  4982.3  289.14    4985  288.64  4988.3  289.14  5022.7  295.21  5133.4  295.98
  5332.5  306.83  5636.5  329.86  5787.2  330.32  5837.5  336.37  5897.7  335.36
  5928.5  335.81  6124.9  336.43  6321.4  336.32  6992.9  336.27  7193.8  327.14
  7371.8  327.17  7598.1  332.03  7874.7  332.84  8040.4  336.65  8375.5  345.27
#Mann= 12 ,-1 , 0
   231.8     .05       0  3200.6     .16       0  4982.3     .03       0
  4988.3     .16       0  5897.7     .08       0  5928.5     .05       0
  6124.9     .08       0  6321.4     .05       0  7371.8     .16       0
  7598.1     .05       0  7874.7     .16       0  8040.4     .05       0
Bank Sta=4972.4,5022.7
XS Rating Curve= 0 ,0
Exp/Cntr=0.3,0.1

Type RM Length L Ch R = 1 ,88266   ,762,762,762
BEGIN DESCRIPTION:
LITTLE ELKHART CREEK 103.0
END DESCRIPTION:
XS GIS Cut Line= 4
      3805785.65      10513882.8      3805694.51     10515679.64
      3804887.22     10517658.81      3804796.13     10519246.27
#Sta/Elev= 30
  1936.6  362.01  2304.5  344.96  2549.6  340.24  2915.2  319.36  3005.4  320.44
  3035.4  329.78  3225.6  332.25  3385.8  327.65  3546.1  307.97  3626.2  305.16
  3893.6  312.79  4500.5  295.77  4981.8  293.42  4996.9  287.15  4999.7  286.65
  5002.9  287.15  5021.5   293.6  5259.1  290.62  5374.8  293.81  5410.3  301.27
  5540.6  299.93  5773.2  328.14  5992.2  323.64  6064.9  328.41  6090.3  322.41
    6105  331.08  6275.3  333.64    6736  333.87  6986.4  326.75  7463.3  333.38
#Mann= 5 ,-1 , 0
  1936.6     .16       0  4996.9     .03       0  5002.9     .16       0
  5992.2     .08       0  6090.3     .05       0
Bank Sta=4981.8,5021.5
XS Rating Curve= 0 ,0
Exp/Cntr=0.3,0.1

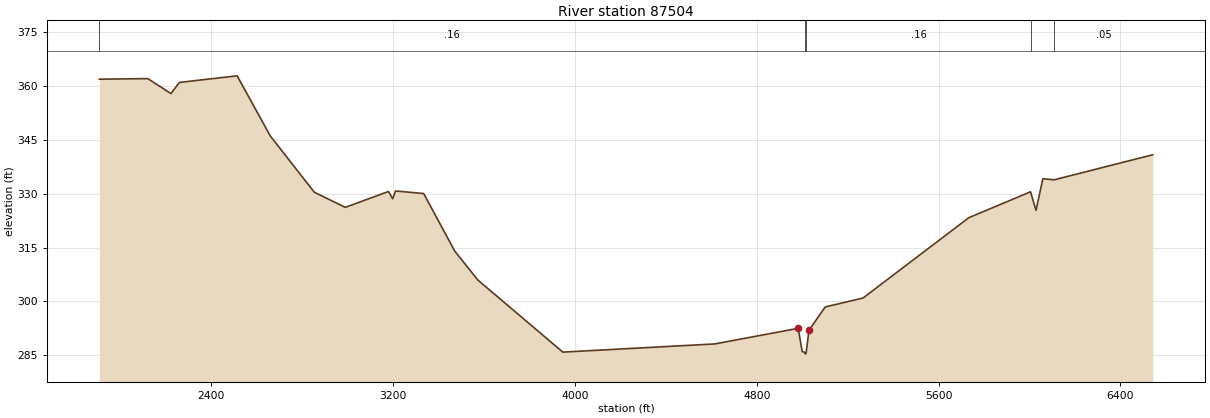
Type RM Length L Ch R = 1 ,87504   ,1011,1011,1011
BEGIN DESCRIPTION:
LITTLE ELKHART CREEK 101.0
END DESCRIPTION:
XS GIS Cut Line= 3
      3805733.59     10513843.67      3804288.26     10517385.37
      3804236.18     10518192.63
#Sta/Elev= 30
  1908.1  361.96  2121.4  362.12    2223  357.96  2260.8  361.06  2514.3   362.9
  2660.4  346.12  2853.8  330.45  2990.2  326.23    3180  330.65  3198.6  328.63
  3211.2   330.8    3335  330.08  3471.4  314.07  3572.9  305.99  3947.2  285.87
  4615.3  288.15  4982.5   292.5  5000.3     286  5011.9  285.81  5014.7  285.31
  5017.9  285.81  5029.8  291.93  5101.3  298.46  5267.7  300.95  5733.3  323.35
  6004.7  330.57  6028.8   325.4  6058.9  334.21  6108.6  333.91  6542.3  340.89
#Mann= 5 ,-1 , 0
  1908.1     .16       0  5011.9     .03       0  5017.9     .16       0
  6004.7     .08       0  6108.6     .05       0
Bank Sta=4982.5,5029.8
XS Rating Curve= 0 ,0
Exp/Cntr=0.3,0.1