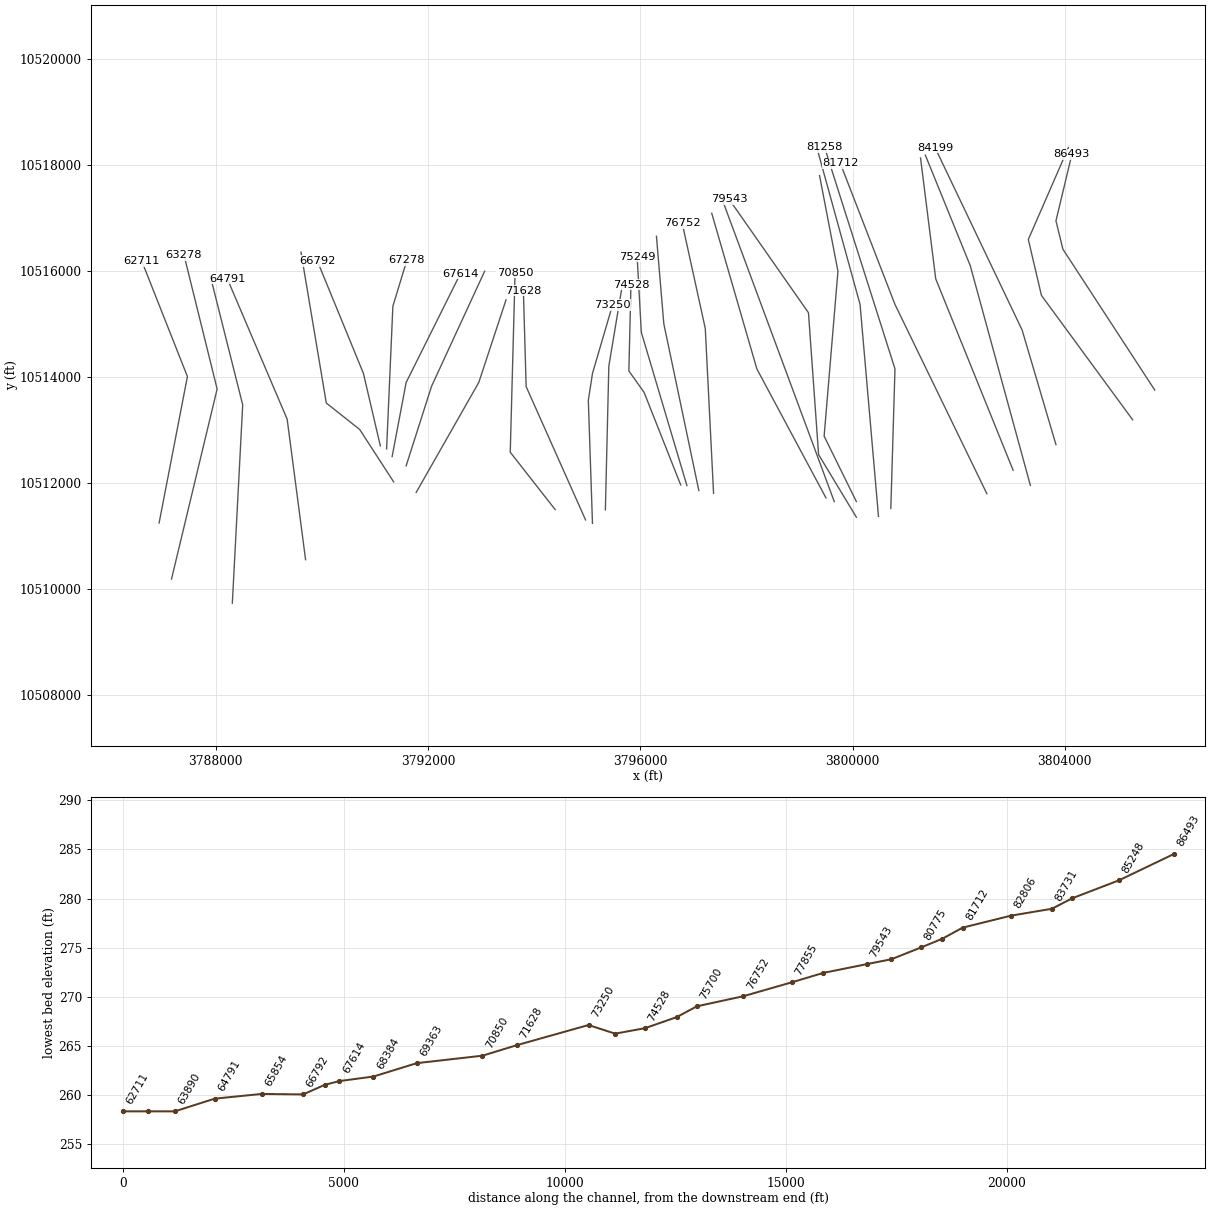
HEC-RAS study LITTLE ELKHART CREEK.prj: LITTLE ELKHART CREEK Base Level Engineering

--- LITTLE ELKHART CREEK.g01 (geometry) --- (continued)

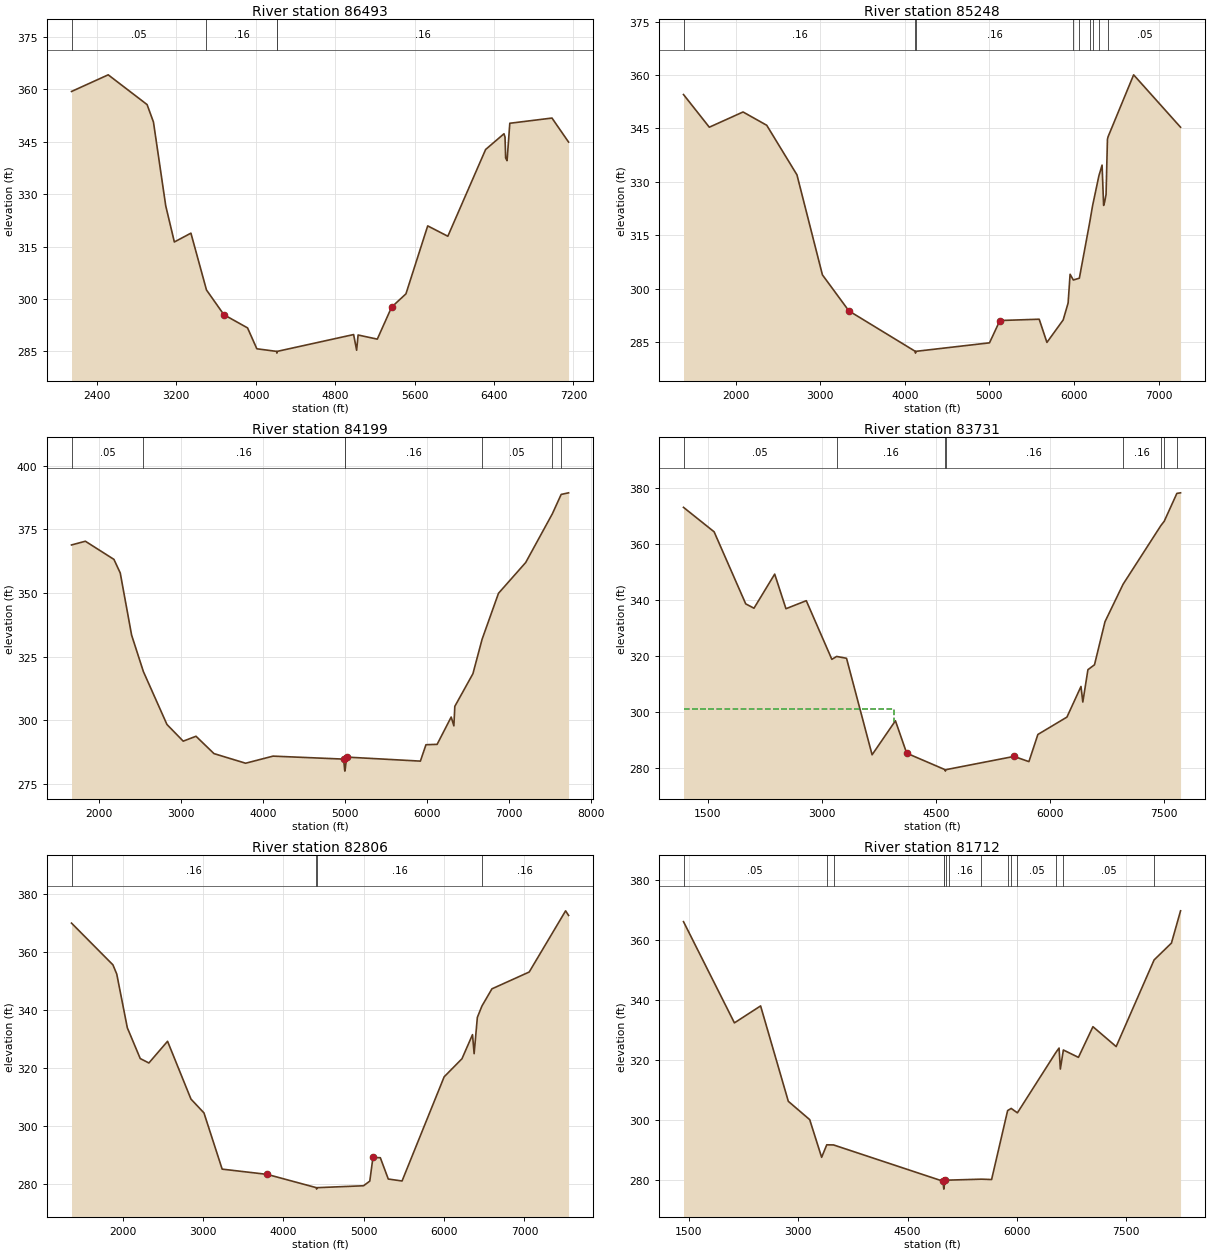
Type RM Length L Ch R = 1 ,86493   ,1245,1245,1245
BEGIN DESCRIPTION:
LITTLE ELKHART CREEK 100.0
END DESCRIPTION:
XS GIS Cut Line= 4
      3805694.48      10513752.6      3803962.74     10516408.81
      3803832.53     10516942.66        3804132.     10518192.62
#Sta/Elev= 30
  2144.7  359.34  2514.3   364.1  2905.8  355.59    2970  350.59  3093.7  326.62
  3180.4  316.31  3347.2  318.83    3504  302.58  3679.2  295.52  3917.6  291.74
  4011.1  285.77  4210.3  285.03    4213  284.53  4216.3  285.03  4985.7  289.84
    5016  285.36  5030.7  289.71  5224.1  288.53  5368.5  297.69  5512.6  301.48
  5731.8  320.91  5934.5  317.95    6315  342.75  6500.1  347.25  6510.4  346.29
  6516.7  340.33  6530.9  339.56  6558.7  350.25  6983.4  351.74  7150.4  344.87
#Mann= 4 ,-1 , 0
  2144.7     .05       0    3504     .16       0  4210.3     .03       0
  4216.3     .16       0
Bank Sta=3679.2,5368.5
XS Rating Curve= 0 ,0
Exp/Cntr=0.3,0.1

Type RM Length L Ch R = 1 ,85248   ,1049,1049,1049
BEGIN DESCRIPTION:
LITTLE ELKHART CREEK 99.0
END DESCRIPTION:
XS GIS Cut Line= 4
      3805277.83     10513192.68      3803559.09     10515536.41
       3803311.7      10516591.1      3804066.91     10518322.89
#Sta/Elev= 30
  1381.9  354.52  1687.2  345.34  2086.3  349.62  2366.4  345.88  2723.8  331.95
  3024.8  303.85  3338.2  293.72  4123.2  282.35  4125.9  281.85  4129.2  282.35
  5000.9  284.74  5124.2  291.01  5588.8  291.38  5680.3  284.86  5872.4  291.17
  5930.9  295.93  5954.3  304.01  5992.8   302.4  6063.9  302.91    6186  318.56
  6220.2  323.27  6294.9  331.67  6332.8  334.69  6350.8  323.35  6363.4  324.35
  6379.7  326.46  6396.1  341.95  6403.7  342.66  6705.9  360.06  7260.9  345.33
#Mann= 9 ,-1 , 0
  1381.9     .16       0  4123.2     .03       0  4129.2     .16       0
  5992.8     .16       0  6063.9     .05       0    6186     .08       0
  6220.2     .05       0  6294.9     .08       0  6403.7     .05       0
Bank Sta=3338.2,5124.2
XS Rating Curve= 0 ,0
Exp/Cntr=0.3,0.1

Type RM Length L Ch R = 1 ,84199   ,468,468,468
BEGIN DESCRIPTION:
LITTLE ELKHART CREEK 97.0
END DESCRIPTION:
XS GIS Cut Line= 3
      3803832.52     10512723.95      3803194.51     10514885.37
      3801554.25     10518322.09
#Sta/Elev= 30
  1668.2  368.86  1836.9  370.32  2185.5  363.19  2262.6  357.84    2401  333.46
  2544.6  319.14  2832.1  298.36  3030.2  291.81  3186.6  293.73  3405.5  286.92
  3791.3  283.14  4125.8  285.93  4987.4  284.76    4999  280.54  5001.7  280.04
    5005  280.54  5024.1  285.55  5922.7  283.97  5990.8  290.41  6126.9  290.56
  6298.4  301.28  6331.1  297.82  6342.7  305.48  6563.5   318.3  6675.1   331.8
  6875.1  349.87    7207  361.96  7532.8  381.14  7639.6   388.7  7729.9  389.33
#Mann= 7 ,-1 , 0
  1668.2     .05       0  2544.6     .16       0    4999     .03       0
    5005     .16       0  6675.1     .05       0  7532.8     .08       0
  7639.6      .1       0
Bank Sta=4987.4,5024.1
XS Rating Curve= 0 ,0
Exp/Cntr=0.3,0.1

Type RM Length L Ch R = 1 ,83731   ,925,925,925
BEGIN DESCRIPTION:
LITTLE ELKHART CREEK 96.0
END DESCRIPTION:
XS GIS Cut Line= 3
      3803350.75      10511955.7      3802217.95     10516096.31
      3801371.58     10518179.68
#Sta/Elev= 30
  1181.2  373.06  1584.2  364.33    2000  338.63  2108.6  337.08  2381.3  349.24
  2529.6   336.9    2797  339.76  3133.4  318.84  3197.1  319.87  3326.7  319.21
  3663.1  284.79  3970.2  296.93  4118.5  285.36  4624.9  279.46  4627.6  278.96
  4630.9  279.46  5531.4  284.21  5726.9  282.35  5845.1  292.04  6227.5  298.24
  6412.3  309.16  6436.4  303.61  6503.6  315.15  6589.9  316.89  6728.2  332.26
  6966.5  345.64  7465.6  366.64  7507.6  368.09  7674.1  378.04  7722.7  378.24
#Mann= 8 ,-1 , 0
  1181.2     .05       0  3197.1     .16       0  4624.9     .03       0
  4630.9     .16       0  6966.5     .16       0  7465.6      .1       0
  7507.6     .05       0  7674.1     .16       0
#XS Ineff= 2 , 0
         3955.11     301
Permanent Ineff=
       F       F
Bank Sta=4118.5,5531.4
XS Rating Curve= 0 ,0
Exp/Cntr=0.3,0.1

Type RM Length L Ch R = 1 ,82806   ,1094,1094,1094
BEGIN DESCRIPTION:
LITTLE ELKHART CREEK 95.0
END DESCRIPTION:
XS GIS Cut Line= 3
      3803025.25      10512242.1       3801566.9     10515848.91
      3801280.59      10518126.4
#Sta/Elev= 30
  1363.7  369.94  1879.4  355.55  1926.8  352.38  2058.2  333.88  2219.1  323.26
  2326.4  321.74  2558.9  329.22  2850.2   309.3    3012  304.53  3238.5  285.15
  3799.4  283.34  4411.2  278.76    4414  278.26  4417.2  278.76  4997.8  279.42
  5075.6  281.02  5115.3   289.2    5207  289.08  5305.9  281.74  5477.2  281.06
  6001.3  316.97    6223   323.2  6354.1  331.51  6374.2  324.95  6414.5  337.46
  6471.2  341.36  6595.9  347.29  7059.6  353.09  7512.7  374.18  7549.6   372.6
#Mann= 4 ,-1 , 0
  1363.7     .16       0  4411.2     .03       0  4417.2     .16       0
  6471.2     .16       0
Bank Sta=3799.4,5115.3
XS Rating Curve= 0 ,0
Exp/Cntr=0.3,0.1

Type RM Length L Ch R = 1 ,81712   ,454,454,454
BEGIN DESCRIPTION:
LITTLE ELKHART CREEK 94.0
END DESCRIPTION:
XS GIS Cut Line= 3
      3802530.46      10511799.4      3800798.67     10515367.14
      3799770.03     10518023.38
#Sta/Elev= 30
  1428.2  366.01  2126.2  332.34  2485.1  337.98    2865  306.25  3158.4  300.15
  3321.9  287.62  3391.9  291.78    3485  291.74  4985.9  279.67  4994.3  277.54
    4997  277.04  5000.3  277.54    5014  280.19  5023.1  280.16  5062.8  280.04
  5511.5  280.35  5651.9  280.23  5871.6  303.16  5920.4  303.89  6005.9  302.42
  6532.1  322.46  6576.9  323.97  6594.5  316.98  6635.8  323.32  6842.4  320.87
  7041.2  331.07  7359.7  324.46  7879.9  353.28  8117.4  358.88  8242.5  369.61
#Mann= 14 ,-1 , 0
  1428.2     .05       0  3391.9     .16       0    3485       0       0
  4994.3     .03       0  5000.3     .16       0  5023.1     .16       0
  5062.8     .16       0  5511.5     .16       0  5871.6     .05       0
  5920.4     .16       0  6005.9     .05       0  6532.1     .08       0
  6635.8     .05       0  7879.9     .16       0
Bank Sta=4985.9,5014
XS Rating Curve= 0 ,0
Exp/Cntr=0.5,0.3

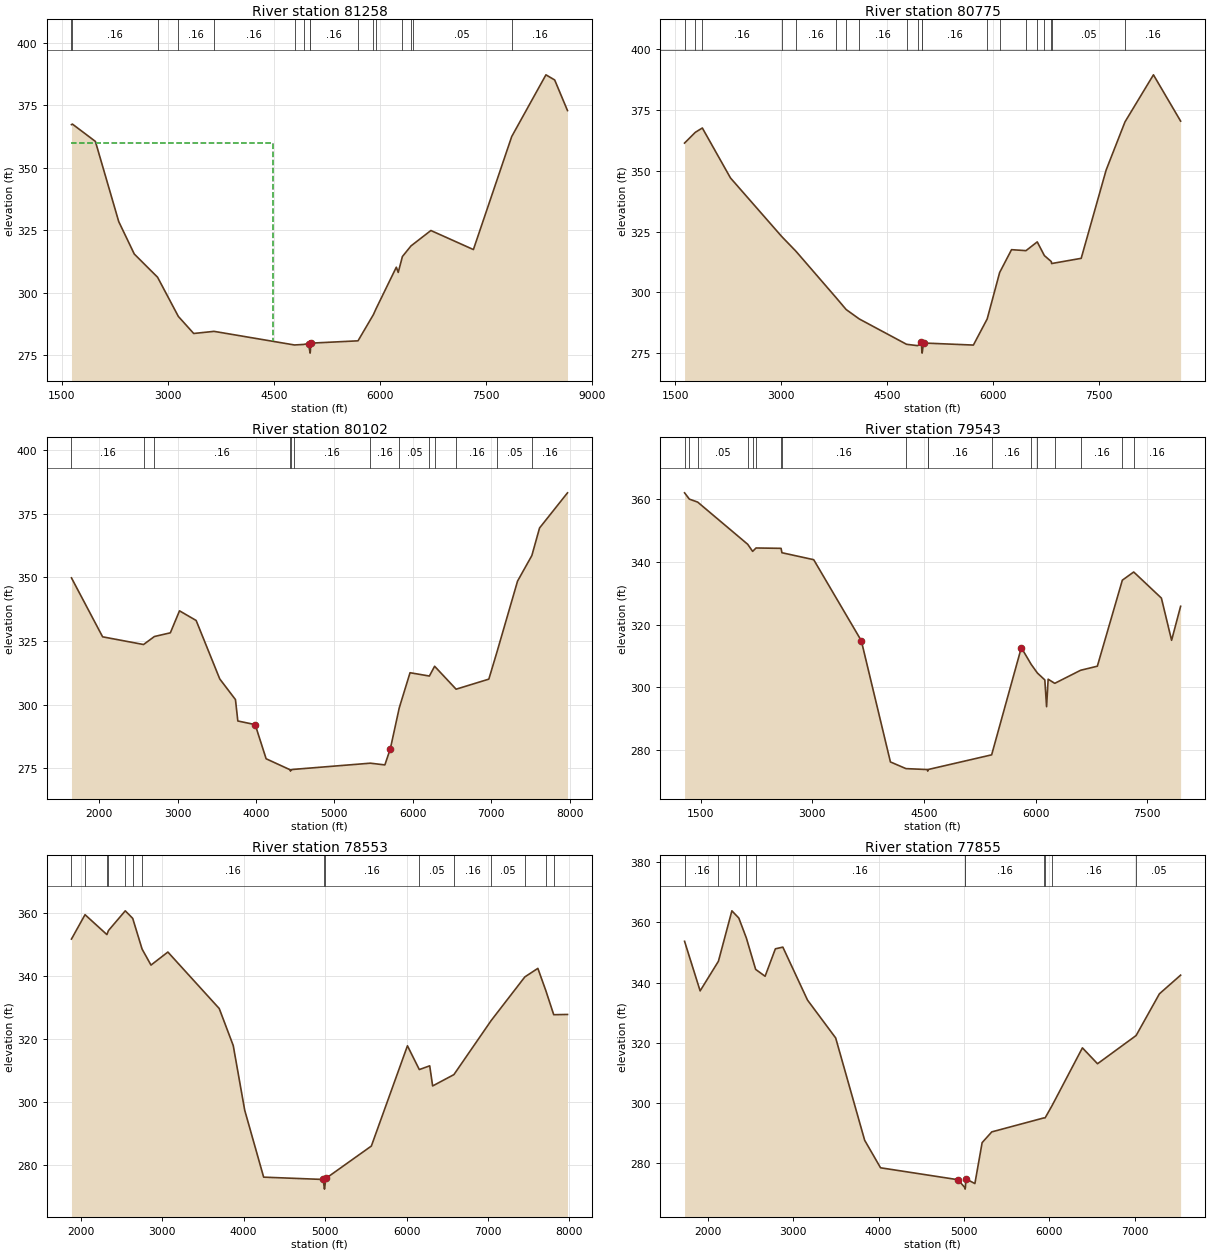
Type RM Length L Ch R = 1 ,81258   ,483,483,483
BEGIN DESCRIPTION:
LITTLE ELKHART CREEK 93.0
END DESCRIPTION:
XS GIS Cut Line= 3
       3800720.9     10511521.95      3800799.02      10514152.2
      3799470.91     10518331.85
#Sta/Elev= 30
  1637.8  367.36  1651.4  367.55  1976.2  360.63  2306.3  328.56  2526.4  315.57
  2856.1  306.28  3149.8   290.6  3366.8  283.78  3654.8  284.63    4793  279.18
  4922.8   279.4  4991.1  279.75  5010.8  276.42  5013.5  275.92  5016.8  276.42
  5022.6  279.91  5691.5  280.84  5908.7  291.31  5948.4  293.78  6233.3   310.3
  6260.3  308.22  6319.4  314.57  6441.8  318.85  6462.6  319.29  6722.2  324.98
  7323.7  317.36  7865.7  362.58  8349.7  387.27  8473.5  385.21  8654.8  372.97
#Mann= 16 ,-1 , 0
  1637.8      .1       0  1651.4     .16       0  2856.1     .05       0
  3149.8     .16       0  3654.8     .16       0    4793     .16       0
  4922.8     .16       0  5010.8     .07       0  5016.8     .16       0
  5691.5     .16       0  5908.7     .05       0  5948.4     .16       0
  6319.4     .05       0  6441.8     .08       0  6462.6     .05       0
  7865.7     .16       0
#XS Ineff= 2 , 0
         4483.28  359.87
Permanent Ineff=
       F       F
Bank Sta=4991.1,5022.6
XS Rating Curve= 0 ,0
Exp/Cntr=0.5,0.3

Type RM Length L Ch R = 1 ,80775   ,673,673,673
BEGIN DESCRIPTION:
LITTLE ELKHART CREEK 92.0
END DESCRIPTION:
XS GIS Cut Line= 3
      3800488.26     10511373.53      3800141.04     10515366.61
      3799342.51     10518265.59
#Sta/Elev= 30
  1633.5  361.38  1786.6  365.83  1884.8  367.58  2282.6  347.05  3006.6  322.99
  3208.4  316.92    3774  297.91  3918.2  292.96  4103.9  289.08  4772.8  278.66
  4929.6   278.1  4982.8  279.42  4989.8  275.53  4992.5  275.03  4995.8  275.53
  5012.9  279.19    5718  278.34  5913.2  289.09  6089.3  308.17  6257.3  317.56
  6461.9  317.16  6621.1  320.76  6721.8  315.13  6819.4  312.68  6824.6  311.86
  7242.5     314  7595.4   350.3  7861.9  370.09  8264.3  389.44  8648.6  370.42
#Mann= 20 ,-1 , 0
  1633.5     .16       0  1786.6     .05       0  1884.8     .16       0
  3006.6     .05       0  3208.4     .16       0    3774     .05       0
  3918.2     .16       0  4103.9     .16       0  4772.8     .16       0
  4929.6     .16       0  4989.8     .07       0  4995.8     .16       0
  5913.2     .16       0  6089.3     .05       0  6461.9     .16       0
  6621.1     .05       0  6721.8      .1       0  6819.4     .16       0
  6824.6     .05       0  7861.9     .16       0
Bank Sta=4982.8,5012.9
XS Rating Curve= 0 ,0
Exp/Cntr=0.5,0.3

Type RM Length L Ch R = 1 ,80102   ,559,559,559
BEGIN DESCRIPTION:
LITTLE ELKHART CREEK 91.0
END DESCRIPTION:
XS GIS Cut Line= 4
      3800071.58     10511651.35      3799463.95     10512883.97
      3799724.37     10515991.61      3799377.34     10517796.17
#Sta/Elev= 30
  1644.1  349.76  2041.5   326.6  2563.8  323.57    2702  326.71    2906  328.17
  3022.9  336.81  3235.3  333.02  3536.4  310.06  3737.1  301.93  3767.2  293.53
  3988.6   292.1  4128.4  278.69  4436.5  274.33  4439.3  273.83  4442.5  274.33
  4480.4  274.52    5459  276.95  5643.7  276.27    5714  282.68  5827.3  298.68
  5964.9  312.49  6211.9  311.19  6278.6  315.03  6552.8  306.02  6970.5  309.97
  7075.8  320.79  7337.1  348.49  7519.7  358.54  7617.7  369.35  7974.5  383.17
#Mann= 13 ,-1 , 0
  1644.1     .16       0  2563.8     .05       0    2702     .16       0
  4436.5     .07       0  4442.5     .16       0  4480.4     .16       0
    5459     .16       0  5827.3     .05       0  6211.9     .16       0
  6278.6      .1       0  6552.8     .16       0  7075.8     .05       0
  7519.7     .16       0
Bank Sta=3988.6,5714
XS Rating Curve= 0 ,0
Exp/Cntr=0.3,0.1

Type RM Length L Ch R = 1 ,79543   ,990,990,990
BEGIN DESCRIPTION:
LITTLE ELKHART CREEK 90.0
END DESCRIPTION:
XS GIS Cut Line= 4
       3800071.6     10511356.18      3799359.79     10512536.75
      3799168.81     10515210.36      3797675.98     10517345.45
#Sta/Elev= 30
  1285.4  362.02  1349.7  360.01  1461.7  359.06  2133.6  345.62  2199.9  343.36
  2245.6  344.44  2581.6  344.33  2593.6  342.93  3020.3  340.71  3659.9  314.89
  4050.9  276.26  4259.4  274.13  4549.2  273.83  4551.9  273.33  4555.2  273.83
  5410.8  278.52  5809.7  312.68  5942.4  307.34  6025.1  304.61  6125.4  302.39
  6148.9  293.86  6169.9  302.62    6259  301.31  6605.8  305.47  6830.9  306.77
  7166.7  334.18  7319.5  336.79  7691.6  328.47  7828.5  315.02  7949.6  325.86
#Mann= 18 ,-1 , 0
  1285.4     .05       0  1349.7     .16       0  1461.7     .05       0
  2133.6     .16       0  2199.9     .05       0  2245.6     .16       0
  2581.6     .05       0  2593.6     .16       0  4259.4     .16       0
  4549.2     .07       0  4555.2     .16       0  5410.8     .16       0
  5942.4     .05       0  6025.1     .16       0    6259     .05       0
  6605.8     .16       0  7166.7     .05       0  7319.5     .16       0
Bank Sta=3659.9,5809.7
XS Rating Curve= 0 ,0
Exp/Cntr=0.3,0.1

Type RM Length L Ch R = 1 ,78553   ,698,698,698
BEGIN DESCRIPTION:
LITTLE ELKHART CREEK 89.0
END DESCRIPTION:
XS GIS Cut Line= 2
      3799654.92     10511651.34      3797536.85     10517363.17
#Sta/Elev= 30
    1885   351.6  2051.4  359.32  2320.2  353.02  2339.4   354.3  2545.7  360.54
  2637.2  358.15  2752.1  348.44  2861.7  343.36    3069  347.49    3700   329.6
  3871.7  317.89  4012.9  297.39  4245.3  276.22  4976.7  275.49  4989.4  272.93
  4992.2  272.43  4995.4  272.93  5008.7  275.81    5568  286.07  6011.3  317.81
  6156.9  310.28  6284.8  311.47  6320.6   305.1  6581.6  308.68  7039.6  325.81
  7453.1  339.62  7612.9  342.32  7709.2   335.4  7807.8  327.65  7976.9  327.73
#Mann= 15 ,-1 , 0
    1885     .16       0  2051.4     .05       0  2320.2     .16       0
  2339.4     .05       0  2545.7     .16       0  2637.2     .05       0
  2752.1     .16       0  4989.4     .07       0  4995.4     .16       0
  6156.9     .05       0  6581.6     .16       0  7039.6     .05       0
  7453.1     .16       0  7709.2     .05       0  7807.8     .16       0
Bank Sta=4976.7,5008.7
XS Rating Curve= 0 ,0
Exp/Cntr=0.3,0.1

Type RM Length L Ch R = 1 ,77855   ,1103,1103,1103
BEGIN DESCRIPTION:
LITTLE ELKHART CREEK 87.0
END DESCRIPTION:
XS GIS Cut Line= 3
      3799498.69     10511720.74      3798196.59     10514151.33
      3797345.91      10517085.3
#Sta/Elev= 30
  1726.4  353.67  1908.7  337.23  2122.9  347.05  2280.8  363.78    2362  361.38
  2450.1  354.78  2559.2  344.36  2669.9  342.08  2790.2  351.18  2877.9  351.74
  3166.5   334.2  3496.9  321.62  3836.5   287.7  4022.6  278.57  4930.3  274.61
  5010.6  271.99  5013.4  271.49  5016.6  271.99    5024  274.89  5128.1  273.33
  5212.9  286.91    5326  290.47    5934  295.09  5950.8  295.11  6032.8  299.21
    6388  318.34    6565  313.07    7017  322.42  7290.3  336.26  7538.6  342.45
#Mann= 11 ,-1 , 0
  1726.4     .16       0  2122.9     .05       0    2362     .16       0
  2450.1     .05       0  2559.2     .16       0  5010.6     .07       0
  5016.6     .16       0    5934      .1       0  5950.8     .05       0
  6032.8     .16       0    7017     .05       0
Bank Sta=4930.3,5024
XS Rating Curve= 0 ,0
Exp/Cntr=0.3,0.1

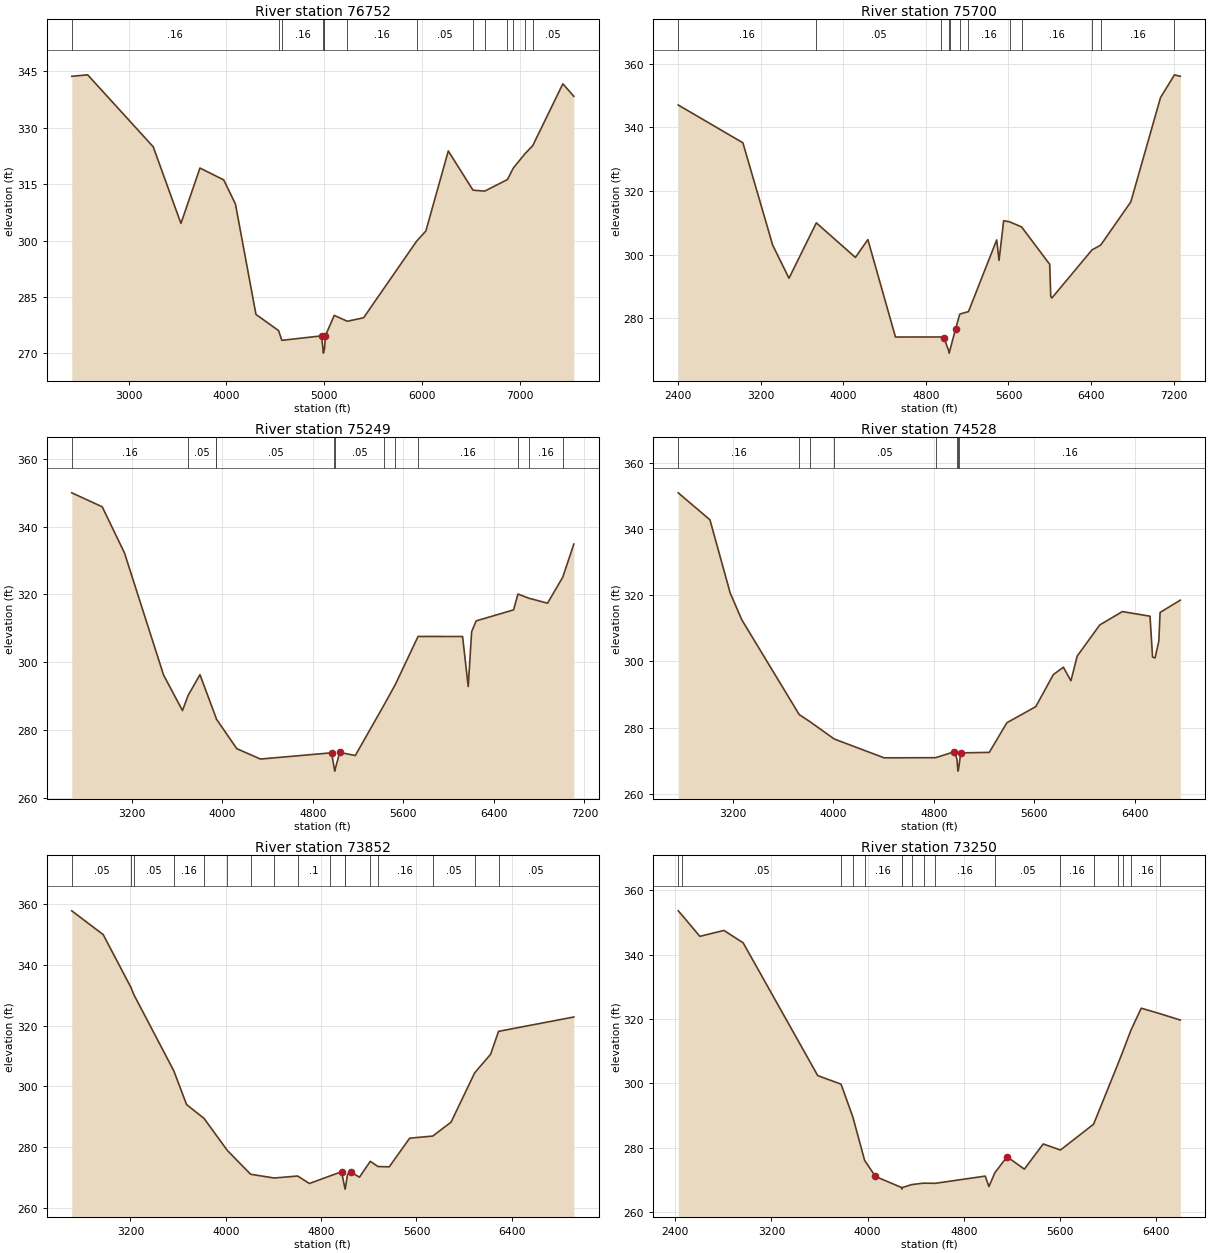
Type RM Length L Ch R = 1 ,76752   ,1052,1052,1052
BEGIN DESCRIPTION:
LITTLE ELKHART CREEK 86.0
END DESCRIPTION:
XS GIS Cut Line= 3
      3797380.62     10511807.55      3797224.37     10514915.22
      3796790.34     10516894.39
#Sta/Elev= 30
  2417.5  343.66  2580.3  344.05  3251.2  324.91  3534.7  304.55  3729.4  319.27
  3972.1  316.13  4092.3  309.72  4302.5  280.36  4533.9  276.06  4567.2  273.47
  4973.4  274.66  4990.4  270.57  4993.1  270.07  4996.4  270.57    5003  271.02
  5013.4  274.72  5103.5   280.1  5236.8  278.54  5403.9  279.47  5946.4  299.83
  6041.2  302.53  6270.5  323.81  6523.3  313.39  6643.6  313.14  6875.8  316.21
  6935.3  319.25  7054.5  323.05  7134.8  325.23  7442.8  341.66  7555.3  338.34
#Mann= 14 ,-1 , 0
  2417.5     .16       0  4533.9     .12       0  4567.2     .16       0
  4990.4     .07       0  4996.4     .16       0    5003      .1       0
  5236.8     .16       0  5946.4     .05       0  6523.3     .16       0
  6643.6     .05       0  6875.8     .16       0  6935.3     .05       0
  7054.5     .16       0  7134.8     .05       0
Bank Sta=4973.4,5013.4
XS Rating Curve= 0 ,0
Exp/Cntr=0.3,0.1

Type RM Length L Ch R = 1 ,75700   ,451,451,451
BEGIN DESCRIPTION:
LITTLE ELKHART CREEK 84.0
END DESCRIPTION:
XS GIS Cut Line= 3
      3797102.84     10511859.65      3796443.12     10515002.02
      3796304.23     10516651.31
#Sta/Elev= 30
  2399.7  347.04  3026.2  335.16  3315.3  302.97  3473.1  292.59  3738.1  309.99
  4116.9  299.12  4237.5  304.73  4505.2   274.1  4948.9  274.12  4975.5  273.84
  5023.3  269.54    5026  269.04  5029.3  269.54  5087.6  276.64  5128.4  281.31
  5212.7  282.09  5486.1  304.62  5508.8  298.18  5553.6  310.67  5610.5  310.32
  5727.3  308.72  6000.1  296.95  6010.2  286.92  6020.2  286.34  6410.2   301.5
  6493.8  302.98  6786.2  316.59  7073.9  349.38  7209.3  356.52  7265.7  356.05
#Mann= 12 ,-1 , 0
  2399.7     .16       0  3738.1     .05       0  4948.9     .16       0
  5023.3     .07       0  5029.3     .16       0  5128.4     .05       0
  5212.7     .16       0  5610.5     .05       0  5727.3     .16       0
  6410.2     .05       0  6493.8     .16       0  7209.3     .05       0
Bank Sta=4975.5,5087.6
XS Rating Curve= 0 ,0
Exp/Cntr=0.3,0.1

Type RM Length L Ch R = 1 ,75249   ,721,721,721
BEGIN DESCRIPTION:
LITTLE ELKHART CREEK 83.0
END DESCRIPTION:
XS GIS Cut Line= 3
       3796878.4      10511952.3      3796019.04     10514842.89
      3795940.92     10516262.11
#Sta/Elev= 30
  2669.3  349.95  2938.3  345.84  3135.1  332.25  3480.8  296.25  3647.8   285.8
  3697.9  290.29  3802.3  296.36  3943.6  283.72  3946.3  283.34  4127.7  274.57
  4336.7  271.51  4965.5  273.35  4990.5  268.45  4993.2  267.95  4996.5  268.45
  5037.1  273.46  5175.1  272.55  5427.5  287.37  5528.7  293.47  5729.7  307.63
  6122.9  307.62    6173  292.89    6203  309.02  6243.1  312.22  6573.6  315.46
  6612.2  320.13  6710.2  318.88    6874  317.44  7008.2  325.09  7106.3  334.85
#Mann= 12 ,-1 , 0
  2669.3     .16       0  3697.9     .05       0  3943.6     .16       0
  3946.3     .05       0  4990.5     .03       0  4996.5     .05       0
  5427.5     .16       0  5528.7     .05       0  5729.7     .16       0
  6612.2     .05       0  6710.2     .16       0  7008.2     .05       0
Bank Sta=4965.5,5037.1
XS Rating Curve= 0 ,0
Exp/Cntr=0.3,0.1

Type RM Length L Ch R = 1 ,74528   ,676,676,676
BEGIN DESCRIPTION:
LITTLE ELKHART CREEK 82.0
END DESCRIPTION:
XS GIS Cut Line= 4
      3796761.22     10511965.29      3796071.12     10513710.08
      3795784.66     10514113.72      3795823.72     10515741.29
#Sta/Elev= 30
  2763.4  350.91    3016  342.76  3177.3  320.65  3269.7  312.55  3727.3   283.9
  3810.5  281.82  4006.1  276.53  4403.2  270.84  4813.2  270.88  4963.4  272.68
  4983.8  270.44  4989.9  267.32  4992.7  266.82  4995.9  267.32  5013.8  272.33
  5241.2  272.49  5381.2  281.44  5611.3   286.3  5751.3  295.99  5831.3  298.22
  5891.3  294.12  5941.4  301.59  6121.4     311  6301.5  315.03  6521.5  313.63
  6541.5   301.3  6561.5  301.02  6591.5   306.1  6601.6  314.78  6762.7  318.47
#Mann= 8 ,-1 , 0
  2763.4     .16       0  3727.3     .05       0  3810.5     .16       0
  4006.1     .05       0  4813.2     .16       0  4983.8     .05       0
  4989.9     .07       0  4995.9     .16       0
Bank Sta=4963.4,5013.8
XS Rating Curve= 0 ,0
Exp/Cntr=0.3,0.1

Type RM Length L Ch R = 1 ,73852   ,602,602,602
BEGIN DESCRIPTION:
LITTLE ELKHART CREEK 81.0
END DESCRIPTION:
XS GIS Cut Line= 3
      3795341.95     10511496.56      3795407.06     10514204.87
      3795654.45      10515689.2
#Sta/Elev= 30
  2707.2   357.7  2970.9  349.89  3204.1  332.52  3227.7  330.21  3563.7  305.12
  3671.1  294.03  3817.1  289.51  4013.6  278.94  4208.6  271.14  4406.5  269.91
    4603  270.57  4701.4  268.11    4878  270.64  4971.5  271.95  4998.5  266.76
  5001.2  266.26  5004.5  266.76  5021.5  271.13  5051.5  271.84  5121.5  270.17
  5212.6  275.41  5277.5  273.68  5371.6  273.58  5543.3     283  5736.6  283.69
  5890.6  288.27    6089  304.48  6222.6  310.57  6289.2   318.1  6921.1  322.82
#Mann= 17 ,-1 , 0
  2707.2     .05       0  3204.1     .16       0  3227.7     .05       0
  3563.7     .16       0  3817.1      .1       0  4013.6     .16       0
  4208.6      .1       0  4406.5     .07       0    4603      .1       0
    4878     .16       0  4998.5     .07       0  5004.5     .16       0
  5212.6     .12       0  5277.5     .16       0  5736.6     .05       0
    6089     .16       0  6289.2     .05       0
Bank Sta=4971.5,5051.5
XS Rating Curve= 0 ,0
Exp/Cntr=0.3,0.1

Type RM Length L Ch R = 1 ,73250   ,1622,1622,1622
BEGIN DESCRIPTION:
LITTLE ELKHART CREEK 80.0
END DESCRIPTION:
XS GIS Cut Line= 4
       3795098.9     10511240.43      3795020.77     10513558.17
       3795098.9     10514065.98      3795476.51     10515355.07
#Sta/Elev= 30
    2425  353.66  2455.2  352.38  2604.9  345.73    2805  347.57  2965.1  343.71
  3585.4  302.43  3779.4  299.77  3877.4  289.54  3975.5  276.06  4065.7  271.07
  4282.8  267.64  4285.6  267.14  4288.8  267.64  4367.7  268.55  4465.7     269
  4563.7  268.95  4978.8  271.19  5009.2  267.93  5058.2   272.2  5159.9  277.22
  5303.9  273.35  5460.7  281.18  5604.4   279.3  5879.8  287.33  6086.6  306.45
  6122.1  309.84    6190  316.52  6276.2  323.39  6433.3  321.67  6601.1   319.7
#Mann= 17 ,-1 , 0
    2425     .16       0  2455.2     .05       0  3779.4     .16       0
  3877.4      .1       0  3975.5     .16       0  4282.8     .07       0
  4288.8     .16       0  4367.7      .1       0  4465.7     .07       0
  4563.7     .16       0  5058.2     .05       0  5604.4     .16       0
  5879.8     .05       0  6086.6     .16       0  6122.1     .05       0
    6190     .16       0  6433.3     .05       0
Bank Sta=4065.7,5159.9
XS Rating Curve= 0 ,0
Exp/Cntr=0.3,0.1

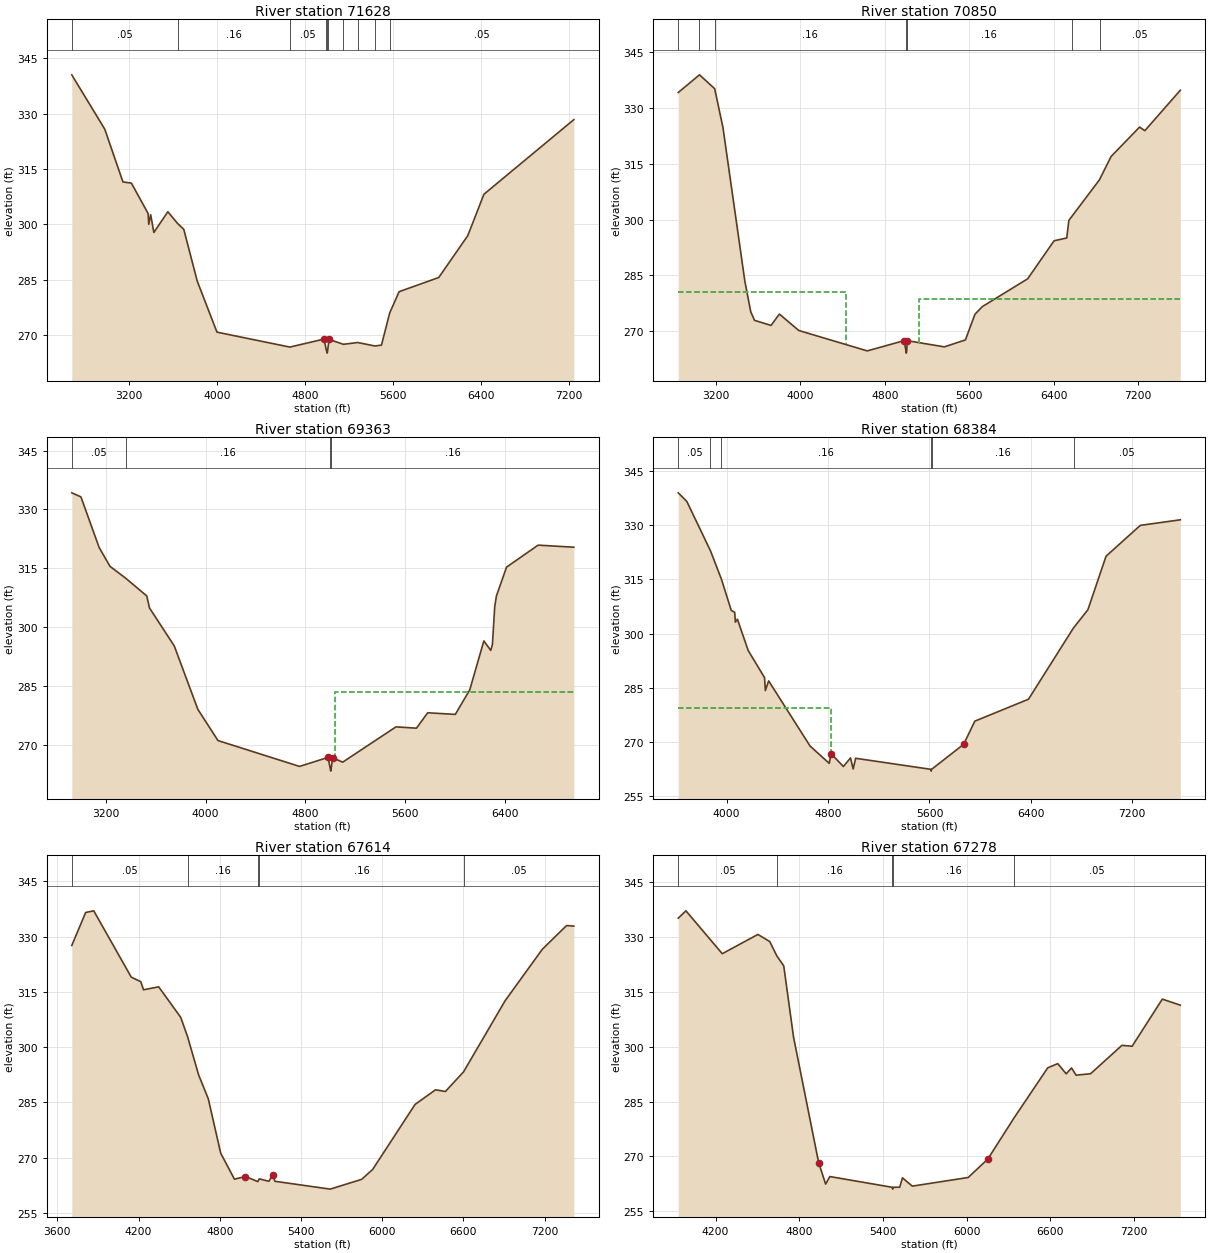
Type RM Length L Ch R = 1 ,71628   ,778,778,778
BEGIN DESCRIPTION:
LITTLE ELKHART CREEK 79.0
END DESCRIPTION:
XS GIS Cut Line= 3
      3794968.69     10511305.57       3793848.9     10513818.58
      3793796.86     10515626.83
#Sta/Elev= 30
  2681.7  340.57  2981.7  325.82  3146.6  311.51  3223.2  311.21  3375.3  302.95
  3380.8  300.03  3398.4  302.63  3427.3  297.82  3554.4  303.44  3642.7  300.26
  3699.2  298.66  3820.9  284.66  4000.5  270.78  4662.6  266.73    4973   268.9
  4993.8  265.85  4998.7  265.59  5001.5  265.09  5004.7  265.59  5018.6  268.82
  5148.9  267.48  5278.2  267.97  5435.5  267.03  5494.5  267.26  5568.8  275.93
  5654.6  281.75  6014.8   285.6  6278.6  296.95  6424.9  308.17  7241.9  328.42
#Mann= 10 ,-1 , 0
  2681.7     .05       0  3642.7     .16       0  4662.6     .05       0
  4993.8     .16       0  4998.7     .07       0  5004.7     .16       0
  5148.9     .05       0  5278.2     .16       0  5435.5     .12       0
  5568.8     .05       0
Bank Sta=4973,5018.6
XS Rating Curve= 0 ,0
Exp/Cntr=0.3,0.1

Type RM Length L Ch R = 1 ,70850   ,1487,1487,1487
BEGIN DESCRIPTION:
LITTLE ELKHART CREEK 78.0
END DESCRIPTION:
XS GIS Cut Line= 3
      3794395.74     10511500.91      3793549.42      10512581.6
      3793640.54     10515966.13
#Sta/Elev= 30
  2843.1  334.21  3044.5  338.97  3188.5  335.24  3267.2  324.74  3474.2  283.44
  3530.3  275.16  3566.2  272.85  3722.8  271.48  3801.5  274.54    3986  270.11
  4634.5  264.62  4984.6  267.39  5001.6  264.52  5004.4  264.02  5007.6  264.52
  5014.6  267.37  5364.7  265.71  5564.8  267.57  5654.9  274.47  5724.9  276.54
    6155  284.04  6405.1  294.28  6525.2  295.03  6545.2  299.77  6575.2   300.9
  6835.8  310.72  6945.3  316.97  7215.4   324.9  7265.4  323.93  7601.5  334.82
#Mann= 7 ,-1 , 0
  2843.1     .05       0  3044.5     .16       0  3188.5     .16       0
  5001.6     .03       0  5007.6     .16       0  6575.2     .16       0
  6835.8     .05       0
#XS Ineff= 2 , 0
         4430.68  280.43 5126.14          278.72
Permanent Ineff=
       F       F
Bank Sta=4984.6,5014.6
XS Rating Curve= 0 ,0
Exp/Cntr=0.3,0.1

Type RM Length L Ch R = 1 ,69363   ,979,979,979
BEGIN DESCRIPTION:
LITTLE ELKHART CREEK 77.0
END DESCRIPTION:
XS GIS Cut Line= 3
      3791776.86     10511823.81      3792957.41     10513898.44
      3793469.57     10515452.31
#Sta/Elev= 30
  2927.7  334.21  3001.2  333.17  3146.7   320.3  3234.2  315.46  3360.7  312.42
  3528.7  307.92  3550.3  304.88  3749.2  295.16    3938  279.01  4099.4  271.05
  4752.9  264.46  4981.4  266.76    5000  263.76  5002.8  263.26    5006  263.76
  5017.6   266.7  5098.1  265.54  5525.6  274.54  5689.7  274.21  5779.8  278.14
  6000.9  277.72  6116.8  283.99  6229.7  296.45  6285.2  294.04  6298.5  295.58
  6316.8  305.18  6330.3   307.9  6411.6  315.27  6664.3  320.87  6950.8  320.35
#Mann= 4 ,-1 , 0
  2927.7     .05       0  3360.7     .16       0    5000     .03       0
    5006     .16       0
#XS Ineff= 2 , 0
                         5037.91          283.46
Permanent Ineff=
       F       F
Bank Sta=4981.4,5017.6
XS Rating Curve= 0 ,0
Exp/Cntr=0.3,0.1

Type RM Length L Ch R = 1 ,68384   ,770,770,770
BEGIN DESCRIPTION:
LITTLE ELKHART CREEK 76.0
END DESCRIPTION:
XS GIS Cut Line= 3
      3791587.61     10512325.51      3792066.78     10513825.53
      3793066.78      10515992.2
#Sta/Elev= 30
  3618.1  338.99    3686   336.6  3872.6  322.92  3958.9  315.06  4036.6  306.41
  4063.5  305.92  4068.7  303.18  4084.9  303.98  4170.5  295.28  4299.2   287.8
  4305.4  284.22  4331.4   286.9  4658.4  268.84  4809.3  264.06  4824.6  266.71
  4921.1  263.18  4977.2  265.56  4998.2   262.5  5017.7  265.46    5611   262.4
  5613.8   261.9    5617   262.4  5869.8  269.33  5957.9  275.74  6381.3  281.82
  6736.5  301.57    6850   306.6  6993.2  321.43  7263.3  329.97  7579.1  331.52
#Mann= 6 ,-1 , 0
  3618.1     .05       0  3872.6     .16       0  3958.9     .16       0
    5611     .07       0    5617     .16       0  6736.5     .05       0
#XS Ineff= 2 , 0
         4821.02  279.32
Permanent Ineff=
       F       F
Bank Sta=4824.6,5869.8
XS Rating Curve= 0 ,0
Exp/Cntr=0.3,0.1

Type RM Length L Ch R = 1 ,67614   ,336,336,336
BEGIN DESCRIPTION:
LITTLE ELKHART CREEK 75.0
END DESCRIPTION:
XS GIS Cut Line= 3
      3791323.73     10512499.18      3791587.61     10513894.97
      3792608.46      10515943.6
#Sta/Elev= 30
  3706.2  327.59    3809  336.57  3868.7  337.01  4145.7     319  4216.1  317.77
  4236.4  315.57  4348.4  316.37  4511.2  308.09  4562.1   302.8  4643.5  292.45
  4714.8  285.98  4806.4  271.21  4908.1  264.14  4989.5  264.86  5081.1  263.48
  5091.3  264.23  5162.6  263.57  5190.6  265.26  5207.4  263.57  5615.7  261.44
  5847.6  264.09  5929.3  266.79  6242.6  284.44  6393.7  288.41  6466.5  287.95
  6600.8  293.29  6908.6  312.64  7182.8  326.58  7361.8  333.01  7415.6  332.87
#Mann= 5 ,-1 , 0
  3706.2     .05       0  4562.1     .16       0  5081.1     .07       0
  5091.3     .16       0  6600.8     .05       0
Bank Sta=4989.5,5190.6
XS Rating Curve= 0 ,0
Exp/Cntr=0.3,0.1

Type RM Length L Ch R = 1 ,67278   ,486,486,486
BEGIN DESCRIPTION:
LITTLE ELKHART CREEK 74.0
END DESCRIPTION:
XS GIS Cut Line= 3
      3791219.56       10512645.      3791337.61     10515332.47
      3791601.49     10516200.48
#Sta/Elev= 30
  3932.8  335.17    3988  337.18  4248.3  325.45  4503.6  330.72  4588.6  328.77
    4639  324.87  4688.7  322.14  4758.8  302.68    4939  268.28    4989  262.42
    5019  264.49  5466.5  261.55  5469.2  261.05  5472.5  261.55  5519.5  261.57
  5539.5  264.15  5609.6  261.87    6010  264.23  6150.1  269.23  6340.3  280.61
  6580.5  294.25    6652  295.38  6712.5  292.59  6750.6   294.2  6783.5  292.22
  6887.3  292.62  7111.7  300.38  7184.9  300.14  7401.2  313.03  7530.1  311.37
#Mann= 5 ,-1 , 0
  3932.8     .05       0    4639     .16       0  5466.5     .07       0
  5472.5     .16       0  6340.3     .05       0
Bank Sta=4939,6150.1
XS Rating Curve= 0 ,0
Exp/Cntr=0.3,0.1

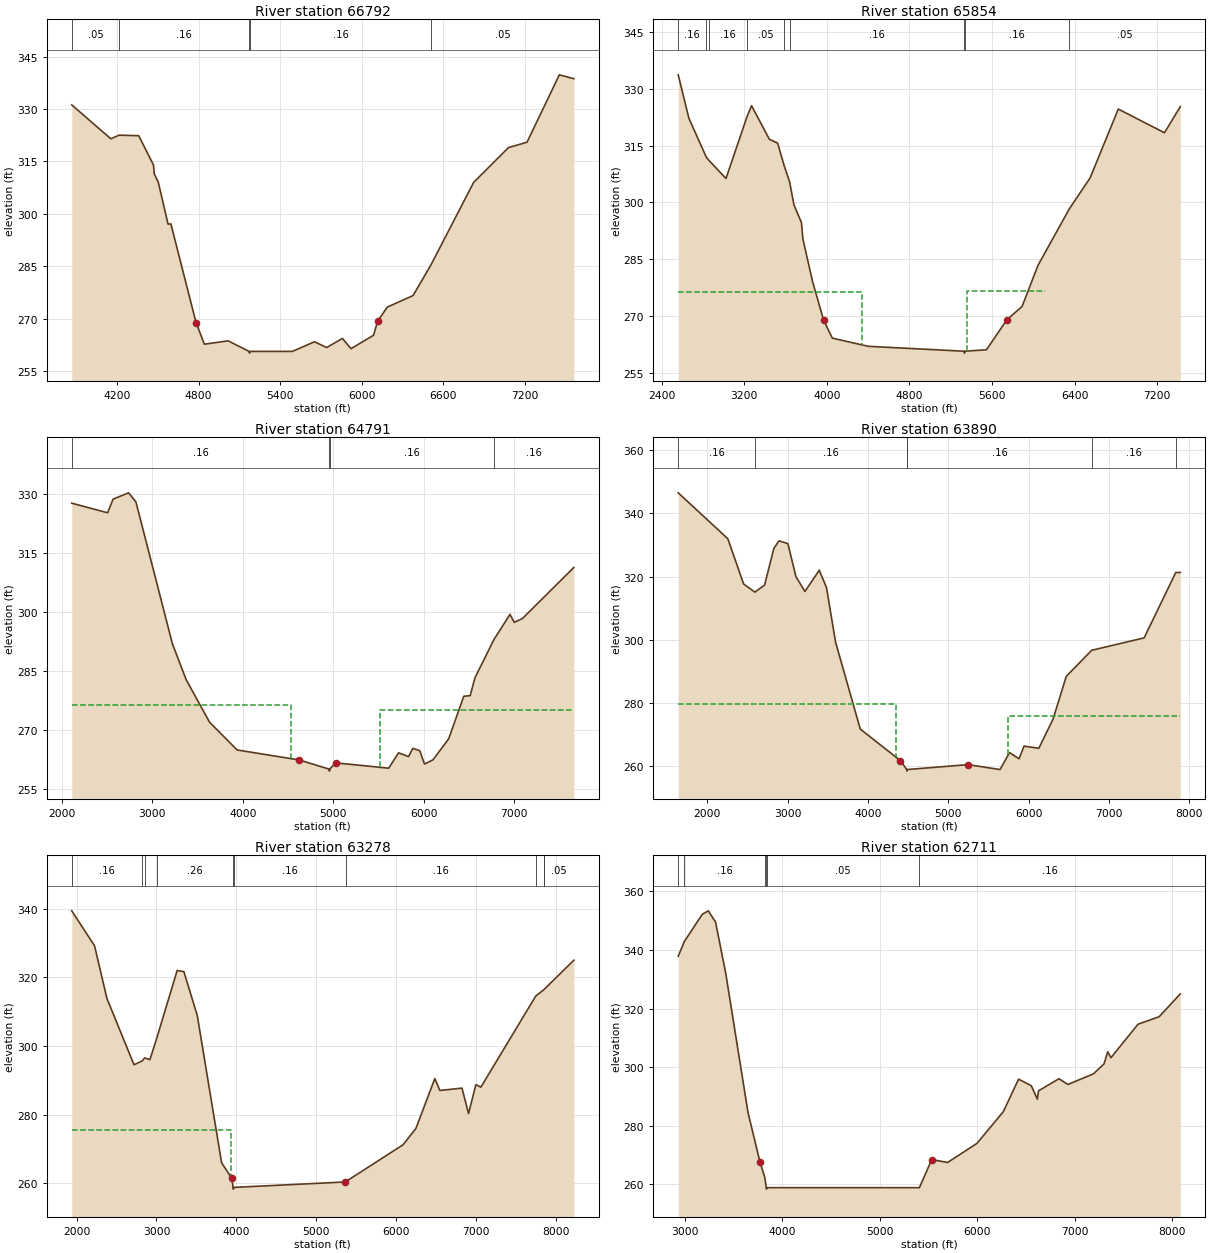
Type RM Length L Ch R = 1 ,66792   ,938,938,938
BEGIN DESCRIPTION:
LITTLE ELKHART CREEK 73.0
END DESCRIPTION:
XS GIS Cut Line= 3
      3791101.51      10512700.5      3790782.06     10514068.58
      3789914.62     10516185.14
#Sta/Elev= 30
  3867.4   331.2  4154.6  321.51  4216.2  322.54    4360  322.38  4468.6  313.97
  4473.8  311.48  4503.8  309.03  4575.6  297.04  4596.2  297.12  4781.7  268.78
  4842.6  262.64  5017.2   263.6  5171.7  260.58  5174.5  260.08  5177.7  260.58
  5490.2  260.58  5652.3  263.33  5742.2  261.68  5857.6  264.29  5920.9  261.36
  6086.5  265.19    6117  269.26  6187.9  273.27  6377.4  276.58  6508.2  285.31
  6823.1  309.02  7078.8  318.98  7215.4  320.52    7453  339.83  7559.7  338.72
#Mann= 5 ,-1 , 0
  3867.4     .05       0  4216.2     .16       0  5171.7     .07       0
  5177.7     .16       0  6508.2     .05       0
Bank Sta=4781.7,6117
XS Rating Curve= 0 ,0
Exp/Cntr=0.3,0.1

Type RM Length L Ch R = 1 ,65854   ,1063,1063,1063
BEGIN DESCRIPTION:
LITTLE ELKHART CREEK 72.0
END DESCRIPTION:
XS GIS Cut Line= 4
      3791352.83     10512022.11      3790712.61     10513009.56
      3790083.27     10513508.69      3789605.84      10516351.6
#Sta/Elev= 30
  2561.5   333.7  2664.5  322.23  2833.6  311.92    2859  311.07    3024   306.3
  3228.6  322.71  3271.7  325.53  3443.8  316.68  3524.6  315.64  3587.7  309.65
  3640.3  305.41  3682.5  299.29  3754.9  294.64  3768.8  290.33  3861.7  279.13
  3969.1  268.87    4054  264.09  4403.3  261.93    5331  260.63  5333.8  260.13
    5337  260.63    5547  261.02  5742.9   268.9  5891.7  272.46  6045.9  283.34
    6349  298.24  6550.8  306.45  6823.7  324.65  7270.8  318.38  7424.3   325.3
#Mann= 9 ,-1 , 0
  2561.5     .16       0  2833.6     .05       0    2859     .16       0
  3228.6     .05       0  3587.7     .16       0  3640.3     .16       0
    5331     .07       0    5337     .16       0    6349     .05       0
#XS Ineff= 2 ,-1
  2561.5 4342.05  276.22 5354.55 6114.77  276.52
Permanent Ineff=
       F       F
Bank Sta=3969.1,5742.9
XS Rating Curve= 0 ,0
Exp/Cntr=0.3,0.1

Type RM Length L Ch R = 1 ,64791   ,901,901,901
BEGIN DESCRIPTION:
LITTLE ELKHART CREEK 71.0
END DESCRIPTION:
XS GIS Cut Line= 3
      3789692.65     10510557.26      3789345.43     10513204.87
      3788216.96     10515852.42
#Sta/Elev= 30
  2109.9   327.6  2506.2  325.17  2566.7  328.64  2738.2  330.23  2818.9  327.92
  3222.3  291.92  3373.6  282.87  3631.8  272.09  3936.9  265.02  4624.2  262.48
  4954.6  260.15  4957.4  259.65  4960.6  260.15  5025.1  261.75  5612.1   260.4
  5720.7  264.29  5831.4  263.34  5878.7  265.41    5955  264.86  6007.7  261.45
  6101.3   262.5  6275.2  267.85  6441.9  278.64  6512.7  278.79  6565.4  283.31
  6776.1  293.05  6952.4  299.41  6999.6  297.38  7090.5  298.36  7658.2   311.3
#Mann= 4 ,-1 , 0
  2109.9     .16       0  4954.6     .07       0  4960.6     .16       0
  6776.1     .16       0
#XS Ineff= 2 , 0
         4536.36  276.36 5511.36          275.12
Permanent Ineff=
       F       F
Bank Sta=4624.2,5025.1
XS Rating Curve= 0 ,0
Exp/Cntr=0.3,0.1

Type RM Length L Ch R = 1 ,63890   ,612,612,612
BEGIN DESCRIPTION:
LITTLE ELKHART CREEK 70.0
END DESCRIPTION:
XS GIS Cut Line= 3
      3788312.44     10509736.98      3788507.75     10513473.96
      3787896.24     10515907.01
#Sta/Elev= 30
  1638.7  346.54  2256.4  331.99    2453  317.64  2593.2  315.08  2713.4  317.29
  2829.2  328.92  2893.6  331.34  3003.8  330.44  3103.9  320.01    3216  315.27
  3394.3  322.02  3484.4  316.53  3597.9  299.19    3905   271.7  4405.7  261.67
  4482.8  258.86  4485.5  258.36  4488.8  258.86  5246.8  260.42    5645  258.86
  5763.2  264.24  5881.5  262.28    5944  266.28  6128.3   265.6  6304.9  274.83
  6469.9   288.4  6786.4  296.65  7439.1  300.58  7833.3  321.31  7889.5  321.31
#Mann= 6 ,-1 , 0
  1638.7     .16       0  2593.2     .16       0  4482.8    .033       0
  4488.8     .16       0  6786.4     .16       0  7833.3     .05       0
#XS Ineff= 2 , 0
         4344.89   279.5 5748.86          275.89
Permanent Ineff=
       F       F
Bank Sta=4405.7,5246.8
XS Rating Curve= 0 ,0
Exp/Cntr=0.3,0.1

Type RM Length L Ch R = 1 ,63278   ,567,567,567
BEGIN DESCRIPTION:
LITTLE ELKHART CREEK 69.0
END DESCRIPTION:
XS GIS Cut Line= 3
      3787166.61     10510192.73      3788025.98     10513773.44
      3787400.98     10516299.48
#Sta/Elev= 30
  1940.4  339.41  2225.7  329.23    2380  313.92  2719.4  294.57  2821.1  295.69
  2853.7  296.57  2918.6  296.06  3007.8  302.59  3259.7  322.04  3343.7   321.7
  3511.2  308.94  3815.9  266.04  3941.9  261.58  3960.7  258.86  3963.5  258.36
  3966.7  258.86  5358.5  260.44  5376.6  260.64  6087.3  271.28  6247.8  276.01
  6484.8  290.56  6548.1  287.09  6824.7  287.78  6907.1  280.37  6998.6  288.77
  7061.7  288.07    7749  314.62  7846.3  316.38  7850.3  316.46    8225  325.03
#Mann= 10 ,-1 , 0
  1940.4     .16       0  2821.1     .05       0  2853.7     .16       0
  3007.8     .26       0  3960.7    .033       0  3966.7     .16       0
  5376.6     .16       0    7749     .05       0  7846.3     .16       0
  7850.3     .05       0
#XS Ineff= 2 , 0
         3936.36  275.67
Permanent Ineff=
       F       F
Bank Sta=3941.9,5358.5
XS Rating Curve= 0 ,0
Exp/Cntr=0.3,0.1

Type RM Length L Ch R = 1 ,62711   ,691,691,691
BEGIN DESCRIPTION:
LITTLE ELKHART CREEK 68.0
END DESCRIPTION:
XS GIS Cut Line= 3
      3786932.23     10511247.38      3787466.09     10514007.82
      3786606.72     10516182.28
#Sta/Elev= 30
    2934  337.88  2997.6  342.95  3181.3  352.23  3242.4  353.38    3317  349.51
  3420.6  332.19  3649.8   284.5  3772.1  267.67  3821.2  262.43  3837.1  258.86
  3839.8  258.36  3843.1  258.86  5407.6  258.86  5534.1  268.44  5697.1  267.46
  5997.6  273.97  6268.1   284.8    6425  295.91  6554.6  293.68    6617  289.11
  6629.8  291.93  6838.7  296.05  6930.9  294.09    7193  297.73  7301.2  301.11
  7339.5  305.27  7371.8  303.21    7650  314.67  7866.4  317.22  8083.7  325.02
#Mann= 6 ,-1 , 0
    2934     .05       0  2997.6     .16       0  3821.2     .05       0
  3837.1    .033       0  3843.1     .05       0  5407.6     .16       0
Bank Sta=3772.1,5534.1
XS Rating Curve= 0 ,0
Exp/Cntr=0.3,0.1