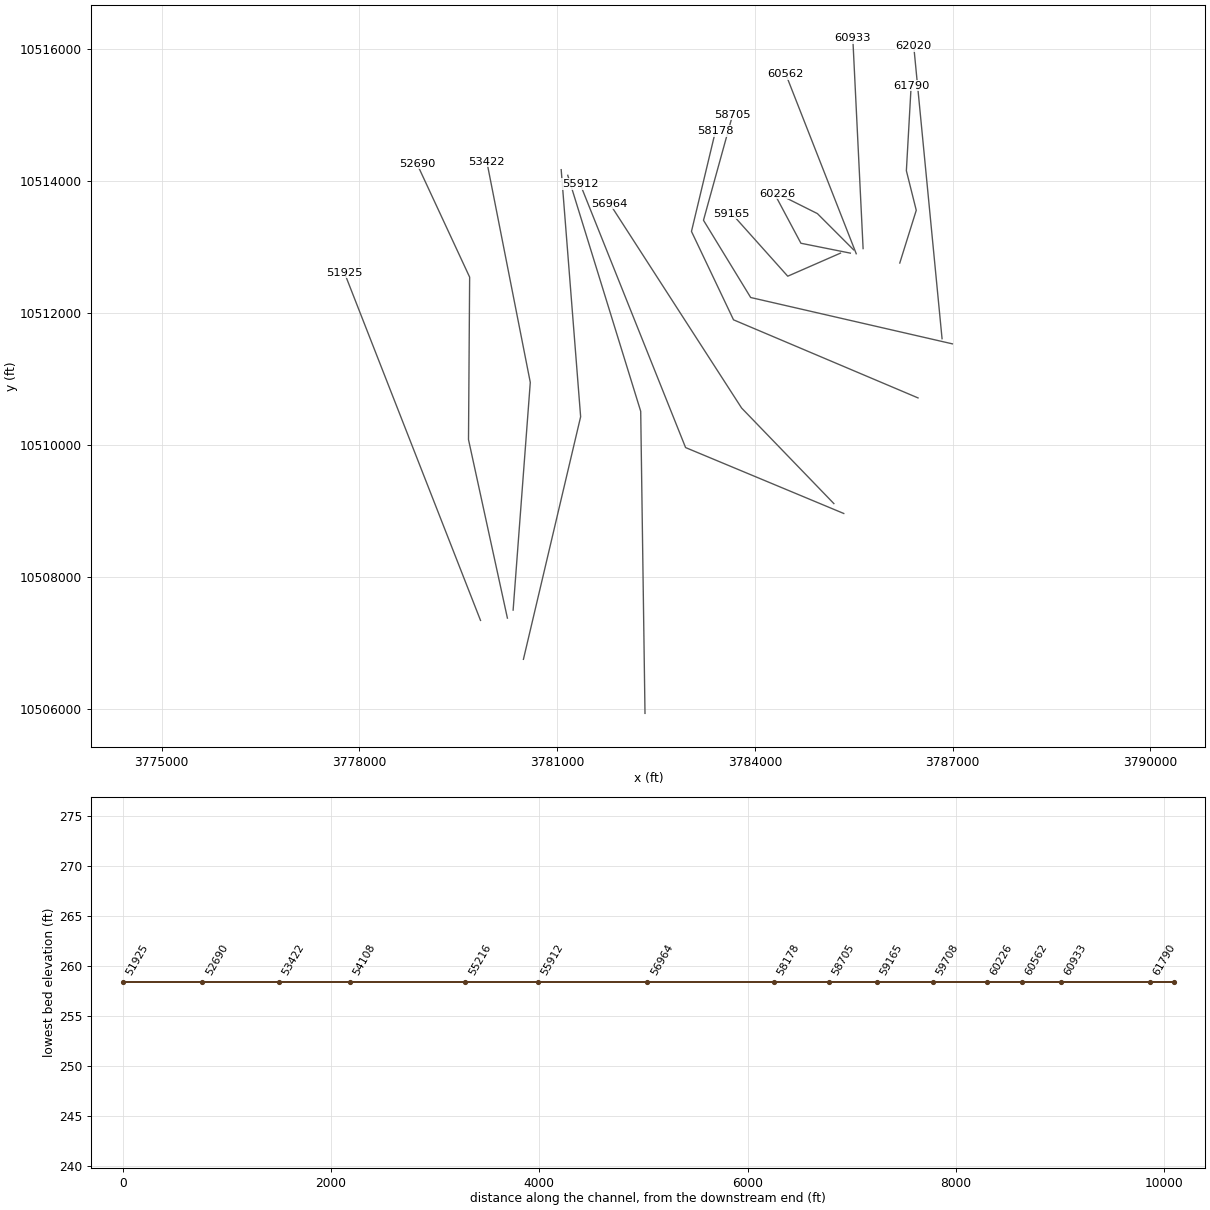
HEC-RAS study LITTLE ELKHART CREEK.prj: LITTLE ELKHART CREEK Base Level Engineering

--- LITTLE ELKHART CREEK.g01 (geometry) --- (continued)

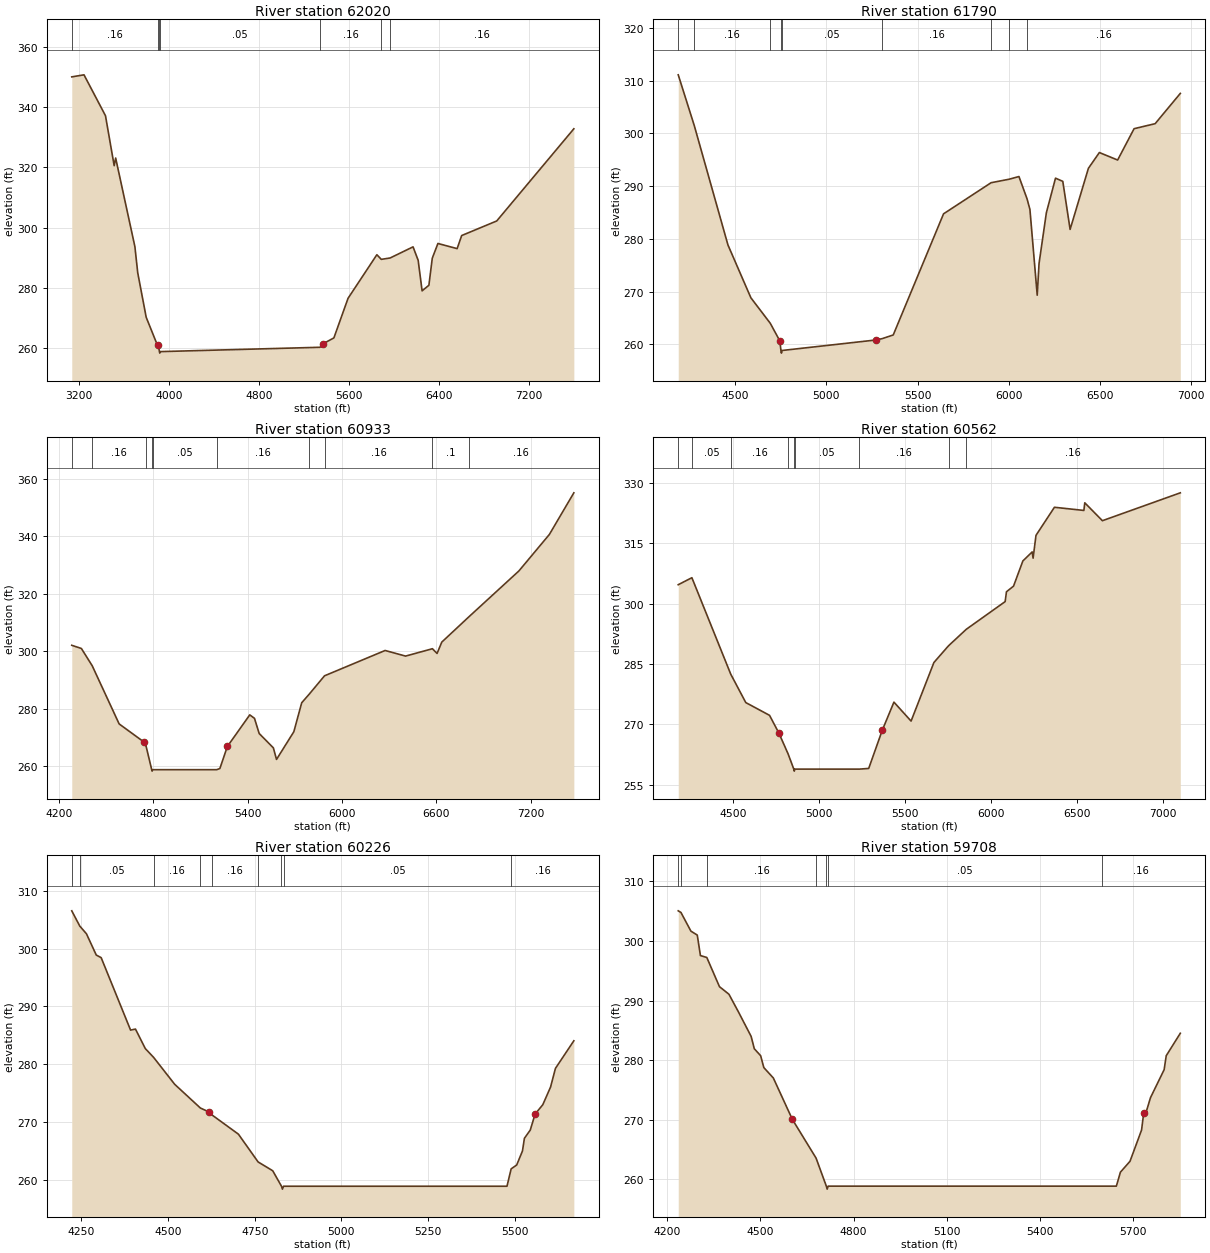
Type RM Length L Ch R = 1 ,62020   ,230,230,230
BEGIN DESCRIPTION:
LITTLE ELKHART CREEK 67.0
END DESCRIPTION:
XS GIS Cut Line= 2
      3786841.09     10511611.97      3786411.39     10516052.13
#Sta/Elev= 30
    3135  349.99  3243.7  350.67  3434.6   337.1  3511.8  320.54    3525  323.07
  3695.8   293.7  3721.1  285.01  3796.3  270.25  3896.8  260.91  3905.3  260.86
  3913.9  258.86  3916.6  258.36  3919.9  258.86  5341.6   260.3  5363.6  261.38
    5464  263.41  5589.8  276.55  5845.8     291  5885.1  289.46  5963.7  289.92
  6167.3  293.61  6212.7  289.15  6247.7  279.02    6308  280.87  6338.1  289.85
  6388.3  294.73  6559.1  293.02  6599.3  297.36  6910.8   302.2  7595.9  332.77
#Mann= 7 ,-1 , 0
    3135     .16       0  3905.3     .05       0  3913.9    .033       0
  3919.9     .05       0  5341.6     .16       0  5885.1     .05       0
  5963.7     .16       0
Bank Sta=3896.8,5363.6
XS Rating Curve= 0 ,0
Exp/Cntr=0.3,0.1

Type RM Length L Ch R = 1 ,61790   ,857,857,857
BEGIN DESCRIPTION:
LITTLE ELKHART CREEK 66.0
END DESCRIPTION:
XS GIS Cut Line= 4
      3786199.61     10512760.19      3786449.61     10513560.19
      3786299.61     10514160.19      3786372.34     10515453.13
#Sta/Elev= 30
  4188.4  311.11  4276.4  301.48  4460.8  278.87  4586.5  268.85    4693  264.01
  4745.2  260.67  4751.2  258.86  4753.9  258.36  4757.2  258.86  5273.9  260.86
  5306.4  261.11  5366.7   261.8  5642.4  284.76    5903  290.66  6001.5  291.32
  6055.7  291.83    6100  287.61  6115.8   285.6  6155.8  269.34  6165.8  275.34
  6205.9  284.96    6256  291.52    6296  290.92  6336.1  281.81  6436.3  293.39
  6496.4  296.38  6596.5  294.96  6686.7   300.9  6802.1  301.85    6940  307.59
#Mann= 9 ,-1 , 0
  4188.4     .05       0  4276.4     .16       0    4693     .05       0
  4751.2    .033       0  4757.2     .05       0  5306.4     .16       0
    5903     .08       0  6001.5     .05       0    6100     .16       0
Bank Sta=4745.2,5273.9
XS Rating Curve= 0 ,0
Exp/Cntr=0.3,0.1

Type RM Length L Ch R = 1 ,60933   ,371,371,371
BEGIN DESCRIPTION:
LITTLE ELKHART CREEK 65.0
END DESCRIPTION:
XS GIS Cut Line= 2
      3785643.17     10512979.21      3785486.92     10516169.29
#Sta/Elev= 30
  4281.3  302.09  4342.4  300.99  4411.6  294.96  4582.6  274.77  4742.8  268.39
  4754.7  266.88  4789.9  258.86  4792.6  258.36  4795.9  258.86    5203  258.86
  5223.4  259.26  5271.2  266.93  5413.6  277.91  5443.7   276.7  5473.5  271.44
  5563.8  266.44  5583.8  262.43    5694  272.06    5744  282.11  5791.3  285.07
  5889.3  291.49  6274.7  300.29  6404.8  298.34  6575.6   300.9  6605.1  299.25
  6635.1   303.2    6807  311.96  7125.7  327.93  7319.5  340.61  7475.2  355.08
#Mann= 10 ,-1 , 0
  4281.3     .05       0  4411.6     .16       0  4754.7     .05       0
  4789.9    .033       0  4795.9     .05       0    5203     .16       0
  5791.3     .05       0  5889.3     .16       0  6575.6      .1       0
    6807     .16       0
Bank Sta=4742.8,5271.2
XS Rating Curve= 0 ,0
Exp/Cntr=0.3,0.1

Type RM Length L Ch R = 1 ,60562   ,336,336,336
BEGIN DESCRIPTION:
LITTLE ELKHART CREEK 64.0
END DESCRIPTION:
XS GIS Cut Line= 2
      3785539.02     10512901.01      3784471.28     10515622.44
#Sta/Elev= 30
  4179.9   304.7  4259.4  306.44  4485.6  282.47  4573.2   275.4  4711.5  272.23
  4765.7  267.84  4819.2  262.69  4852.8  258.86  4855.5  258.36  4858.8  258.86
  5234.5  258.86    5289  259.03  5367.7  268.49  5435.8  275.51  5535.7   270.8
  5668.6  285.36  5753.7  289.52  5857.5  293.63  6083.4   300.5  6091.1  302.95
  6132.3  304.35  6186.5   310.6  6240.8  312.85  6246.1   311.3    6263  316.97
  6370.4  323.95  6541.8  323.16  6547.1  325.06  6649.7  320.61  7103.3  327.54
#Mann= 9 ,-1 , 0
  4179.9     .16       0  4259.4     .05       0  4485.6     .16       0
  4819.2     .05       0  4852.8    .033       0  4858.8     .05       0
  5234.5     .16       0  5753.7     .08       0  5857.5     .16       0
Bank Sta=4765.7,5367.7
XS Rating Curve= 0 ,0
Exp/Cntr=0.3,0.1

Type RM Length L Ch R = 1 ,60226   ,518,518,518
BEGIN DESCRIPTION:
LITTLE ELKHART CREEK 63.0
END DESCRIPTION:
XS GIS Cut Line= 3
      3785499.57     10512960.22      3784949.61     10513510.19
       3784349.6     10513810.19
#Sta/Elev= 30
    4222  306.56  4245.1  303.92  4264.4  302.58  4292.7   298.9  4306.8  298.45
  4391.7   285.9  4405.8  286.08  4434.1  282.71  4458.1  281.18  4518.9  276.52
  4593.2   272.4  4617.9  271.73  4625.6  271.25  4702.8  267.88  4759.6  263.07
  4801.8  261.54  4827.1  258.86  4829.8  258.36  4833.1  258.86  5477.7  258.86
  5489.7  261.87  5505.7  262.54  5522.4  264.97    5528  267.17  5544.8  268.58
  5558.8  271.35  5581.1  272.99  5603.5  276.05  5617.5  279.27  5670.6  284.05
#Mann= 9 ,-1 , 0
    4222     .16       0  4245.1     .05       0  4458.1     .16       0
  4593.2      .1       0  4625.6     .16       0  4759.6     .05       0
  4827.1    .033       0  4833.1     .05       0  5489.7     .16       0
Bank Sta=4617.9,5558.8
XS Rating Curve= 0 ,0
Exp/Cntr=0.3,0.1

Type RM Length L Ch R = 1 ,59708   ,543,543,543
BEGIN DESCRIPTION:
LITTLE ELKHART CREEK 62.0
END DESCRIPTION:
XS GIS Cut Line= 3
      3785449.59     10512910.19      3784699.61     10513060.19
      3784299.62     10513810.16
#Sta/Elev= 30
  4236.2  305.07  4244.9   304.8    4277  301.66  4297.4     301  4307.6  297.56
  4328.1  297.24  4368.8  292.34  4399.3  291.07  4429.9   288.1  4470.7  283.99
  4480.9  281.92  4501.3  280.75  4511.5  278.76  4542.1  277.01  4603.3  270.06
  4679.5  263.57  4712.5  258.86  4715.2  258.36  4718.5  258.86  5599.6  258.86
  5645.3  258.86  5658.4  261.21  5689.2  263.03  5726.4  268.28  5733.1  271.06
  5738.8  270.89  5755.1  273.71    5799  278.41  5805.7  280.75    5851  284.52
#Mann= 7 ,-1 , 0
  4236.2     .16       0  4244.9     .05       0  4328.1     .16       0
  4679.5     .05       0  4712.5    .033       0  4718.5     .05       0
  5599.6     .16       0
Bank Sta=4603.3,5733.1
XS Rating Curve= 0 ,0
Exp/Cntr=0.3,0.1

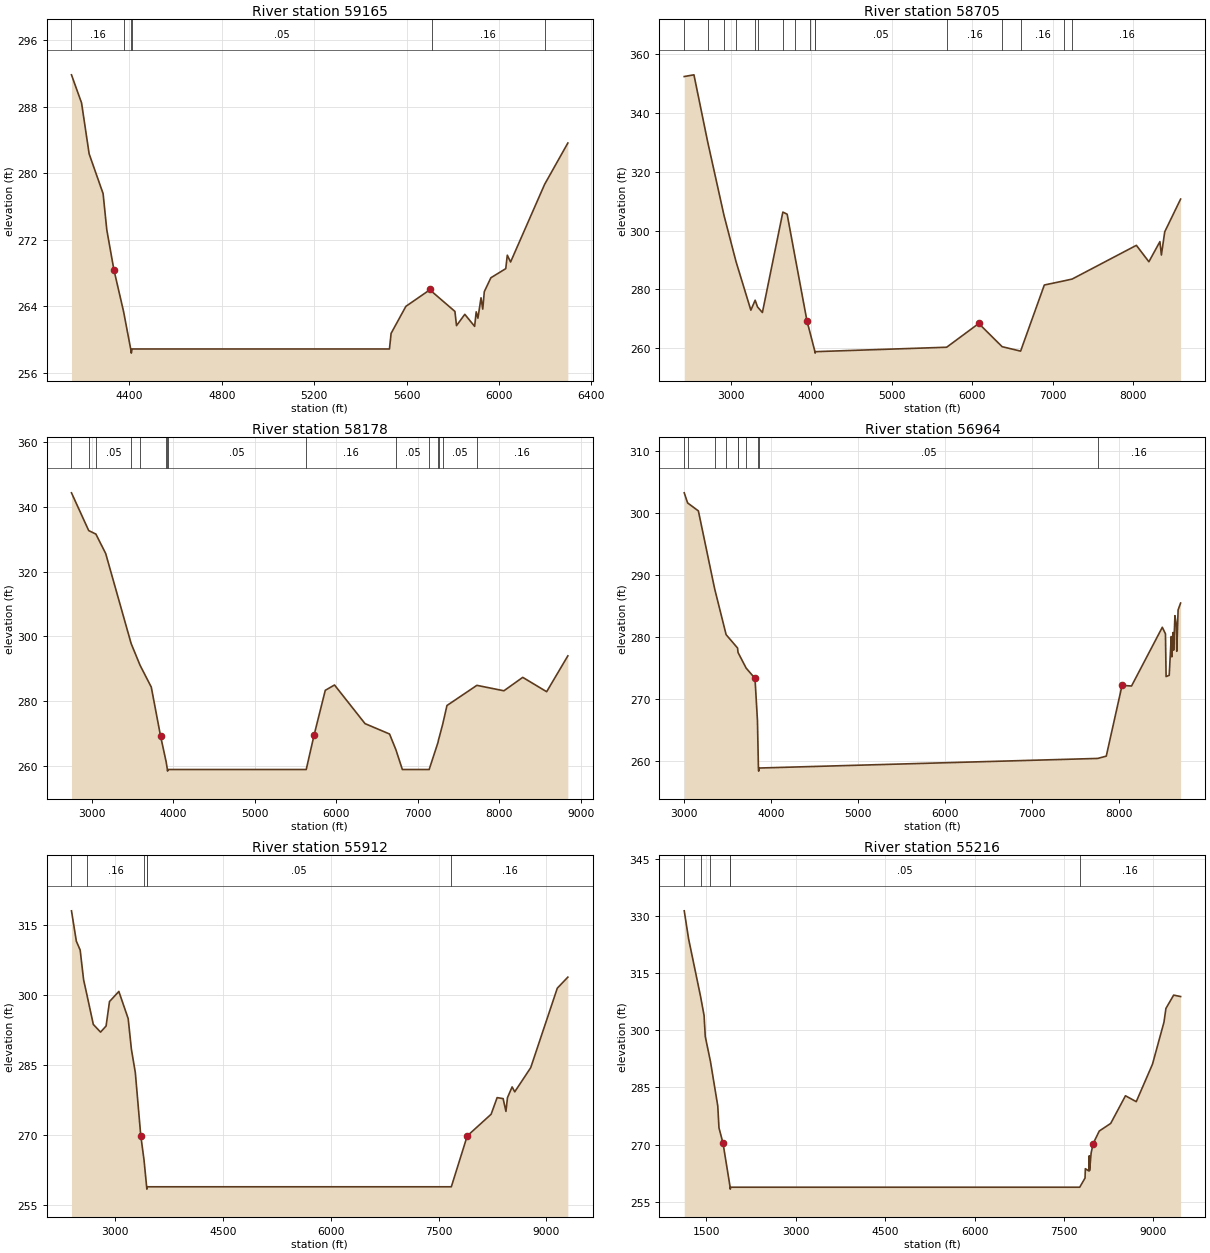
Type RM Length L Ch R = 1 ,59165   ,460,460,460
BEGIN DESCRIPTION:
LITTLE ELKHART CREEK 61.0
END DESCRIPTION:
XS GIS Cut Line= 3
      3785299.58     10512910.17      3784499.61     10512560.19
      3783649.63     10513510.16
#Sta/Elev= 30
  4149.8  291.86  4193.4  288.48  4226.2  282.35  4286.6  277.56  4302.6   273.2
  4333.4  268.39  4375.2  263.37    4406  258.86  4408.8  258.36    4412  258.86
  5525.8  258.86  5532.9  260.74  5596.8  263.99    5703  266.03  5708.9  265.78
  5809.1  263.38  5815.9  261.67  5851.8  263.03  5894.4  261.58  5901.1  263.33
  5908.6  262.57    5922  265.02  5929.5  263.66  5936.2  265.76  5964.6  267.43
    6029  268.53  6035.7  270.15  6049.9  269.33  6197.1  278.67  6297.7  283.65
#Mann= 6 ,-1 , 0
  4149.8     .16       0  4375.2     .05       0    4406    .033       0
    4412     .05       0  5708.9     .16       0  6197.1     .05       0
Bank Sta=4333.4,5703
XS Rating Curve= 0 ,0
Exp/Cntr=0.3,0.1

Type RM Length L Ch R = 1 ,58705   ,527,527,527
BEGIN DESCRIPTION:
LITTLE ELKHART CREEK 60.0
END DESCRIPTION:
XS GIS Cut Line= 4
      3786997.31     10511533.87      3783937.44     10512236.99
      3783221.29     10513408.86        3783664.     10515010.42
#Sta/Elev= 30
    2418  352.35  2538.8  352.93  2707.9  330.38  2912.5  305.19  3062.3  289.46
  3246.7  272.96  3300.4  276.34  3329.6  274.06  3390.4  272.16  3644.8  306.29
  3698.2  305.57  3792.4  291.67  3945.8  269.18  3983.3  265.29  4044.1  258.86
  4046.8  258.36  4050.1  258.86  5682.4  260.36  6081.9  268.43  6372.6  260.55
  6602.3  259.04  6897.4  281.51  7144.5  282.93  7243.7  283.53  8042.5  294.99
  8198.1  289.41  8335.2  296.25  8353.7   291.7  8395.2  299.58  8592.6   310.7
#Mann= 16 ,-1 , 0
    2418     .16       0  2707.9     .05       0  2912.5      .1       0
  3062.3     .16       0  3300.4     .05       0  3329.6     .16       0
  3644.8     .05       0  3792.4     .16       0  3983.3     .05       0
  4044.1    .033       0  4050.1     .05       0  5682.4     .16       0
  6372.6     .05       0  6602.3     .16       0  7144.5     .05       0
  7243.7     .16       0
Bank Sta=3945.8,6081.9
XS Rating Curve= 0 ,0
Exp/Cntr=0.3,0.1

Type RM Length L Ch R = 1 ,58178   ,1214,1214,1214
BEGIN DESCRIPTION:
LITTLE ELKHART CREEK 59.0
END DESCRIPTION:
XS GIS Cut Line= 4
      3786476.49     10510713.55      3783677.02     10511898.44
        3783039.     10513239.59      3783403.58       10514763.
#Sta/Elev= 30
    2751  344.43  2962.4  332.75  3050.8  331.67  3171.1  325.64  3483.2  297.82
  3592.3  291.12  3730.2  284.35  3844.4  269.19  3913.7  261.13  3927.6  258.86
  3930.3  258.36  3933.6  258.86  5631.7  258.86  5729.8  269.67  5865.6  283.35
  5979.1     285  6353.6  273.05  6654.4  269.84  6732.5  264.98  6811.6  258.86
  7140.4  258.86    7249  267.24  7255.4  268.01  7306.3  272.82  7358.9  278.65
  7726.1  284.89  8058.1  283.21  8288.9  287.36  8582.5  282.92  8842.5  294.01
#Mann= 15 ,-1 , 0
    2751     .16       0  2962.4      .1       0  3050.8     .05       0
  3483.2     .08       0  3592.3     .16       0  3913.7     .05       0
  3927.6    .033       0  3933.6     .05       0  5631.7     .16       0
  6732.5     .05       0  7140.4     .16       0    7249     .05       0
  7255.4     .16       0  7306.3     .05       0  7726.1     .16       0
Bank Sta=3844.4,5729.8
XS Rating Curve= 0 ,0
Exp/Cntr=0.3,0.1

Type RM Length L Ch R = 1 ,56964   ,1052,1052,1052
BEGIN DESCRIPTION:
LITTLE ELKHART CREEK 57.0
END DESCRIPTION:
XS GIS Cut Line= 3
      3785199.59     10509110.21      3783799.61     10510560.19
      3781799.61     10513660.18
#Sta/Elev= 30
  3000.3  303.28  3039.2  301.65    3163  300.36  3350.2  287.77  3481.7  280.39
  3613.2  278.23  3618.8  277.51  3712.3  274.98  3813.6  273.33  3841.9   266.5
    3853  258.86  3855.8  258.36    3859  258.86  7753.1  260.41  7850.7  260.78
  8032.2   272.2  8141.1   272.1  8494.8  281.58  8531.1  280.52  8538.4  273.62
  8574.1  273.83  8597.8  280.09  8603.7  276.81  8618.9  280.73  8624.8  277.89
    8640  283.45  8655.2  281.99  8661.1  277.71  8676.3  284.37    8705  285.49
#Mann= 10 ,-1 , 0
  3000.3     .05       0  3039.2     .16       0  3350.2     .05       0
  3481.7      .1       0  3613.2     .05       0  3618.8     .08       0
  3712.3     .05       0    3853    .033       0    3859     .05       0
  7753.1     .16       0
Bank Sta=3813.6,8032.2
XS Rating Curve= 0 ,0
Exp/Cntr=0.3,0.1

Type RM Length L Ch R = 1 ,55912   ,696,696,696
BEGIN DESCRIPTION:
LITTLE ELKHART CREEK 55.0
END DESCRIPTION:
XS GIS Cut Line= 3
       3785349.6     10508960.19      3782949.61     10509960.19
      3781349.62     10513960.17
#Sta/Elev= 30
  2391.6  317.99  2459.3  311.48  2512.4  309.59  2560.1  303.23    2605   300.1
  2695.5  293.65  2796.2     292  2873.1  293.31  2920.8  298.55  3050.8  300.72
  3180.8  294.89  3225.8   288.3  3279.9  283.35  3355.8  269.84  3400.8  264.65
  3437.8  258.86  3440.6  258.36  3443.8  258.86  7677.9  258.86  7899.6  269.76
  8232.1  274.41  8315.6  277.97  8399.1  277.75  8438.1  275.02  8459.6  277.97
  8524.3  280.26  8560.6  279.21  8782.7  284.38    9153  301.42  9299.7  303.78
#Mann= 6 ,-1 , 0
  2391.6     .05       0    2605     .16       0  3400.8     .05       0
  3437.8    .033       0  3443.8     .05       0  7677.9     .16       0
Bank Sta=3355.8,7899.6
XS Rating Curve= 0 ,0
Exp/Cntr=0.3,0.1

Type RM Length L Ch R = 1 ,55216   ,1108,1108,1108
BEGIN DESCRIPTION:
LITTLE ELKHART CREEK 54.0
END DESCRIPTION:
XS GIS Cut Line= 3
      3782333.91     10505927.18      3782268.81     10510510.51
      3781162.02     10514091.27
#Sta/Elev= 30
  1127.5  331.31  1200.5  323.98  1400.6  308.94  1460.5  303.89  1480.5  298.37
  1567.8  291.81  1690.6  280.15  1710.6  274.43    1779  270.36  1897.3  258.94
  1897.6  258.86  1900.3  258.36  1903.6  258.86  7765.8  258.86  7855.1  261.26
  7860.4  263.71  7919.4  263.13  7925.6  267.09  7930.9  263.22  7958.3  267.91
  7990.9  270.28    8094  273.59  8285.8  275.58  8533.9  282.83  8714.9  281.29
  8987.1   291.1  9180.1  302.12  9212.8  305.72  9342.9  309.22  9459.2  308.84
#Mann= 7 ,-1 , 0
  1127.5      .1       0  1400.6     .05       0  1567.8     .16       0
  1897.3     .05       0  1897.6    .033       0  1903.6     .05       0
  7765.8     .16       0
Bank Sta=1779,7990.9
XS Rating Curve= 0 ,0
Exp/Cntr=0.3,0.1

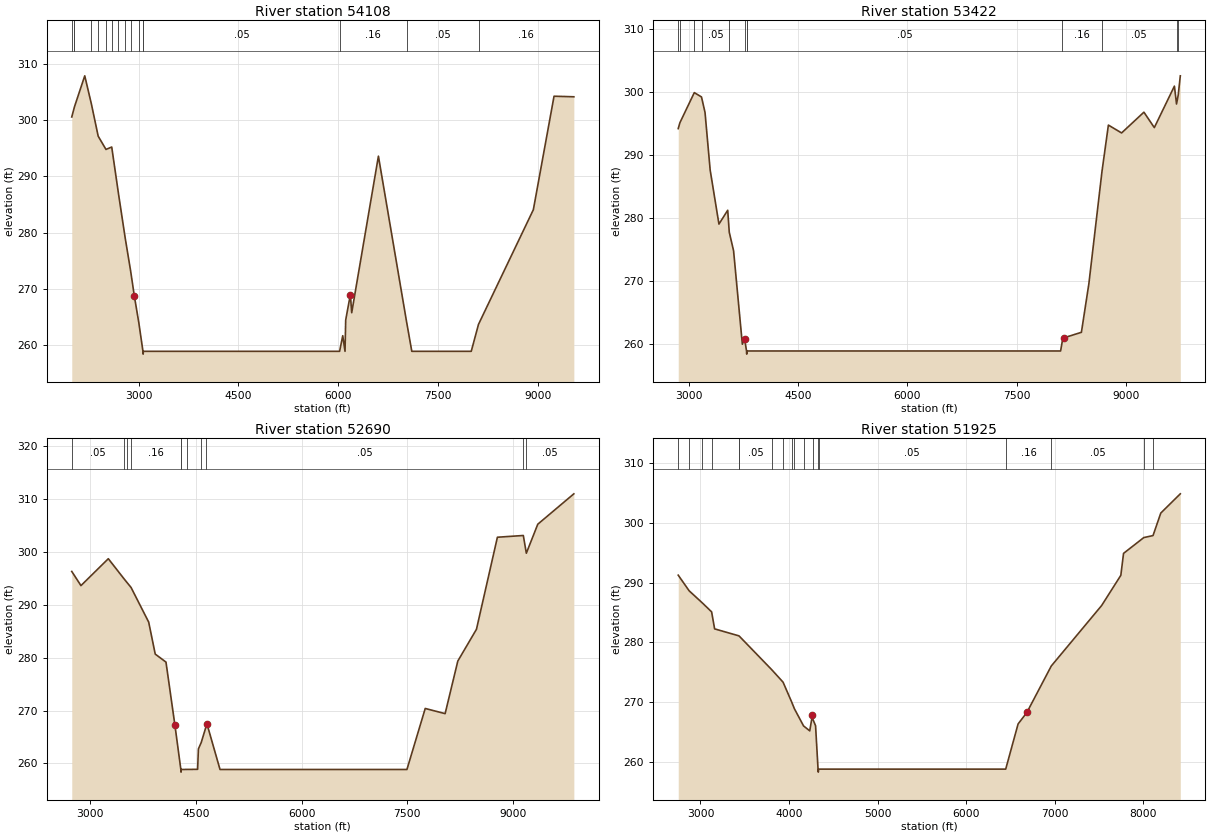
Type RM Length L Ch R = 1 ,54108   ,686,686,686
BEGIN DESCRIPTION:
LITTLE ELKHART CREEK 52.0
END DESCRIPTION:
XS GIS Cut Line= 3
       3780489.3     10506747.51      3781357.35     10510428.04
      3781062.32     10514176.64
#Sta/Elev= 30
  1997.1  300.57  2037.7  302.38    2038  302.39  2192.2  307.89  2292.1  302.87
  2393.9  297.15    2511  294.79  2597.3  295.22    2699   286.9  2800.8  278.94
  2881.5  273.15  2937.5  268.66  3004.2  263.95  3066.6  258.86  3069.4  258.36
  3072.6  258.86  6020.4  258.86  6067.5  261.64  6101.7  258.86  6111.8  264.42
    6182  268.97  6202.1  265.73  6603.3  293.59  7027.4  264.04  7104.8  258.86
  7997.6  258.86  8106.8  263.66  8930.5  284.06  9241.4  304.26  9538.8  304.16
#Mann= 16 ,-1 , 0
  1997.1     .05       0  2037.7      .1       0    2038     .05       0
  2292.1     .08       0  2393.9      .1       0    2511     .08       0
  2597.3     .05       0    2699     .16       0  2800.8     .05       0
  2881.5     .16       0  3004.2     .05       0  3066.6    .033       0
  3072.6     .05       0  6020.4     .16       0  7027.4     .05       0
  8106.8     .16       0
Bank Sta=2937.5,6182
XS Rating Curve= 0 ,0
Exp/Cntr=0.3,0.1

Type RM Length L Ch R = 1 ,53422   ,732,732,732
BEGIN DESCRIPTION:
LITTLE ELKHART CREEK 50.0
END DESCRIPTION:
XS GIS Cut Line= 3
      3780333.05     10507494.06      3780593.46     10510948.88
      3779933.74     10514299.53
#Sta/Elev= 30
  2858.9  294.21  2881.6  295.14    3079  299.93  3177.7  299.24  3226.1  296.77
  3296.3  287.64  3416.7  279.03  3536.9  281.23  3558.2  277.73  3617.2   274.8
  3737.5  259.93  3767.6  260.84  3769.7   260.7  3794.7  258.86  3797.4  258.36
  3800.7  258.86  8098.3  258.86  8121.9  260.44  8149.2  260.97  8383.3  261.83
  8485.6  269.55  8665.1  287.39  8753.1  294.77    8934  293.52  9239.8  296.82
  9382.5  294.37  9657.6  300.96  9686.7  298.12  9709.9  299.56  9738.5   302.6
#Mann= 12 ,-1 , 0
  2858.9     .08       0  2881.6     .05       0    3079     .08       0
  3177.7     .05       0  3558.2     .16       0  3769.7     .05       0
  3794.7    .033       0  3800.7     .05       0  8121.9     .16       0
  8665.1     .05       0  9686.7     .08       0  9709.9     .05       0
Bank Sta=3767.6,8149.2
XS Rating Curve= 0 ,0
Exp/Cntr=0.3,0.1

Type RM Length L Ch R = 1 ,52690   ,765,765,765
BEGIN DESCRIPTION:
LITTLE ELKHART CREEK 49.0
END DESCRIPTION:
XS GIS Cut Line= 4
      3780246.23      10507372.5      3779655.96     10510080.82
      3779673.32      10512546.1      3778874.69     10514264.88
#Sta/Elev= 30
  2735.3  296.31    2866  293.63  3254.6  298.72  3475.8  294.95  3521.8  294.19
  3577.3  293.29  3828.1  286.73  3921.1  280.68  4073.7  279.17  4200.1  267.29
    4285  258.86  4287.8  258.36    4291  258.86    4372  258.87  4523.1  258.89
  4534.3  262.75  4574.3  263.96  4648.2   267.2  4657.1  267.43  4841.3  258.86
  7496.6  258.86  7756.6   270.4  8039.2  269.42  8219.6  279.37  8484.3  285.37
    8782  302.78  9150.1  303.11  9192.9  299.76  9355.4  305.24  9867.8  310.99
#Mann= 11 ,-1 , 0
  2735.3     .05       0  3475.8     .16       0  3521.8     .05       0
  3577.3     .16       0    4285    .033       0    4291     .16       0
    4372     .05       0  4574.3     .16       0  4648.2     .05       0
  9150.1     .08       0  9192.9     .05       0
Bank Sta=4200.1,4657.1
XS Rating Curve= 0 ,0
Exp/Cntr=0.3,0.1

Type RM Length L Ch R = 1 ,51925   ,847,847,847
BEGIN DESCRIPTION:
LITTLE ELKHART CREEK 47.0
END DESCRIPTION:
XS GIS Cut Line= 2
      3779838.24     10507337.79      3777772.35     10512615.35
#Sta/Elev= 30
  2749.2  291.23  2872.6  288.62  3022.2  286.59    3126  285.11  3159.9  282.27
  3430.7  281.12  3437.4  281.07  3804.3  275.46  3932.7  273.37  4028.7   270.1
  4060.2  268.95    4164  266.07  4233.7  265.25  4264.3  267.93  4267.8  267.24
  4299.5  266.09  4327.4  258.86  4330.1  258.36  4333.4  258.86  6445.7  258.86
  6585.6   266.4  6684.9  268.32  6960.5  276.08  7528.9  286.17  7745.3  291.21
  7775.9  294.87  8004.8  297.51  8108.6  297.84  8196.4   301.6  8416.7  304.81
#Mann= 18 ,-1 , 0
  2749.2     .16       0  2872.6     .05       0  3022.2     .16       0
    3126     .05       0  3430.7     .16       0  3437.4     .05       0
  3804.3     .08       0  3932.7     .05       0  4028.7     .08       0
  4060.2      .1       0    4164     .16       0  4267.8     .05       0
  4327.4    .033       0  4333.4     .05       0  6445.7     .16       0
  6960.5     .05       0  8004.8     .08       0  8108.6     .05       0
Bank Sta=4264.3,6684.9
XS Rating Curve= 0 ,0
Exp/Cntr=0.3,0.1