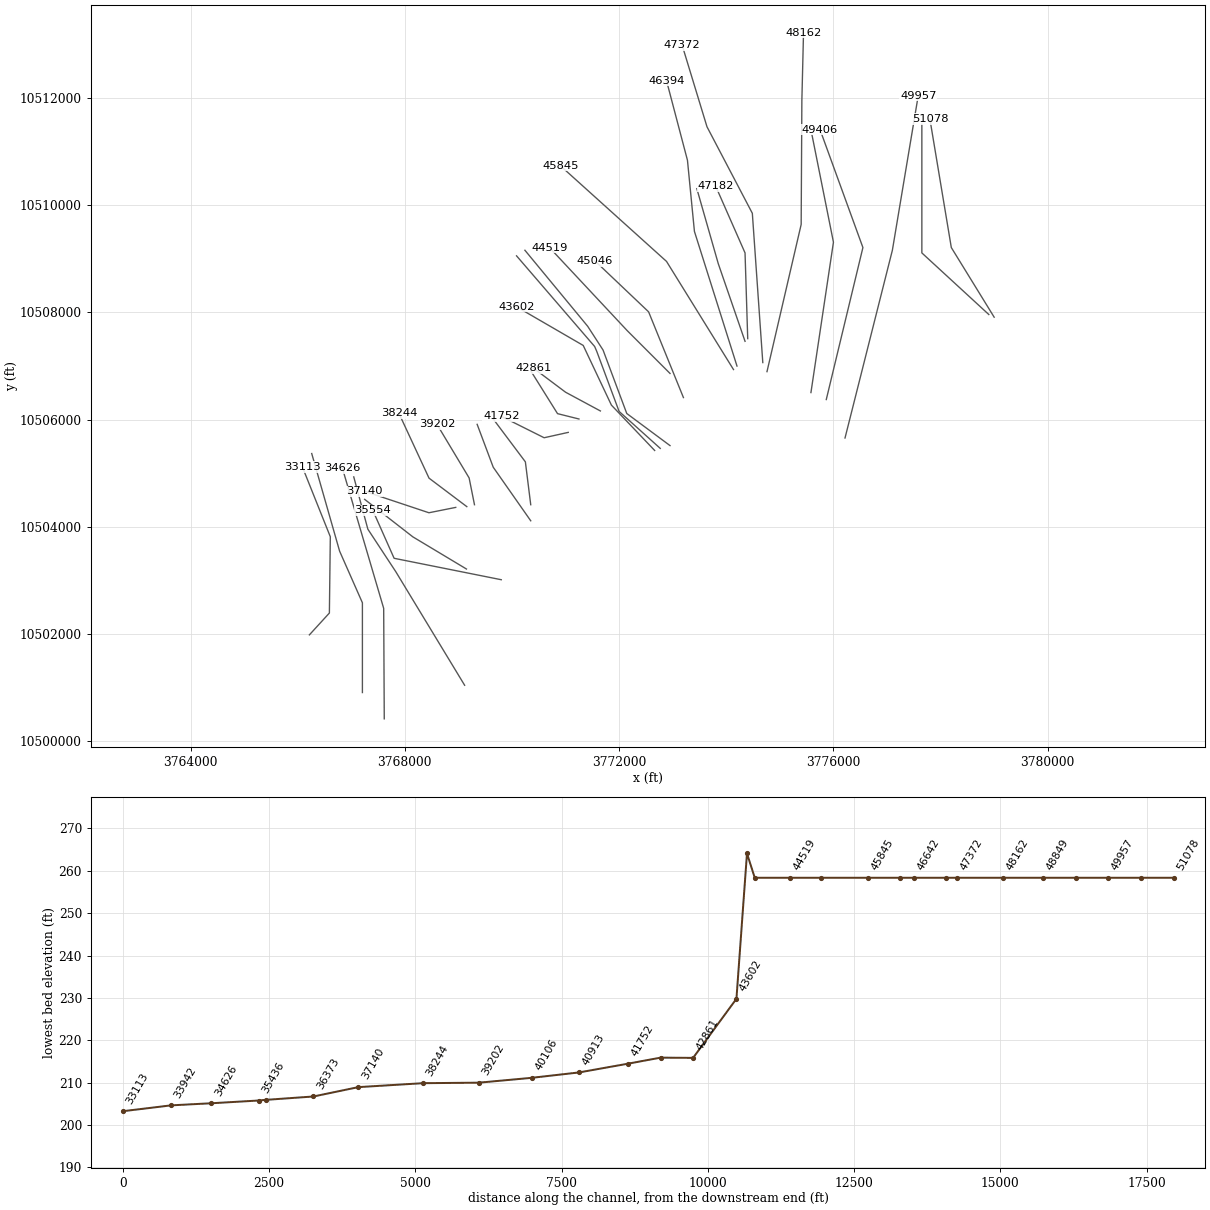
HEC-RAS study LITTLE ELKHART CREEK.prj: LITTLE ELKHART CREEK Base Level Engineering

--- LITTLE ELKHART CREEK.g01 (geometry) --- (continued)

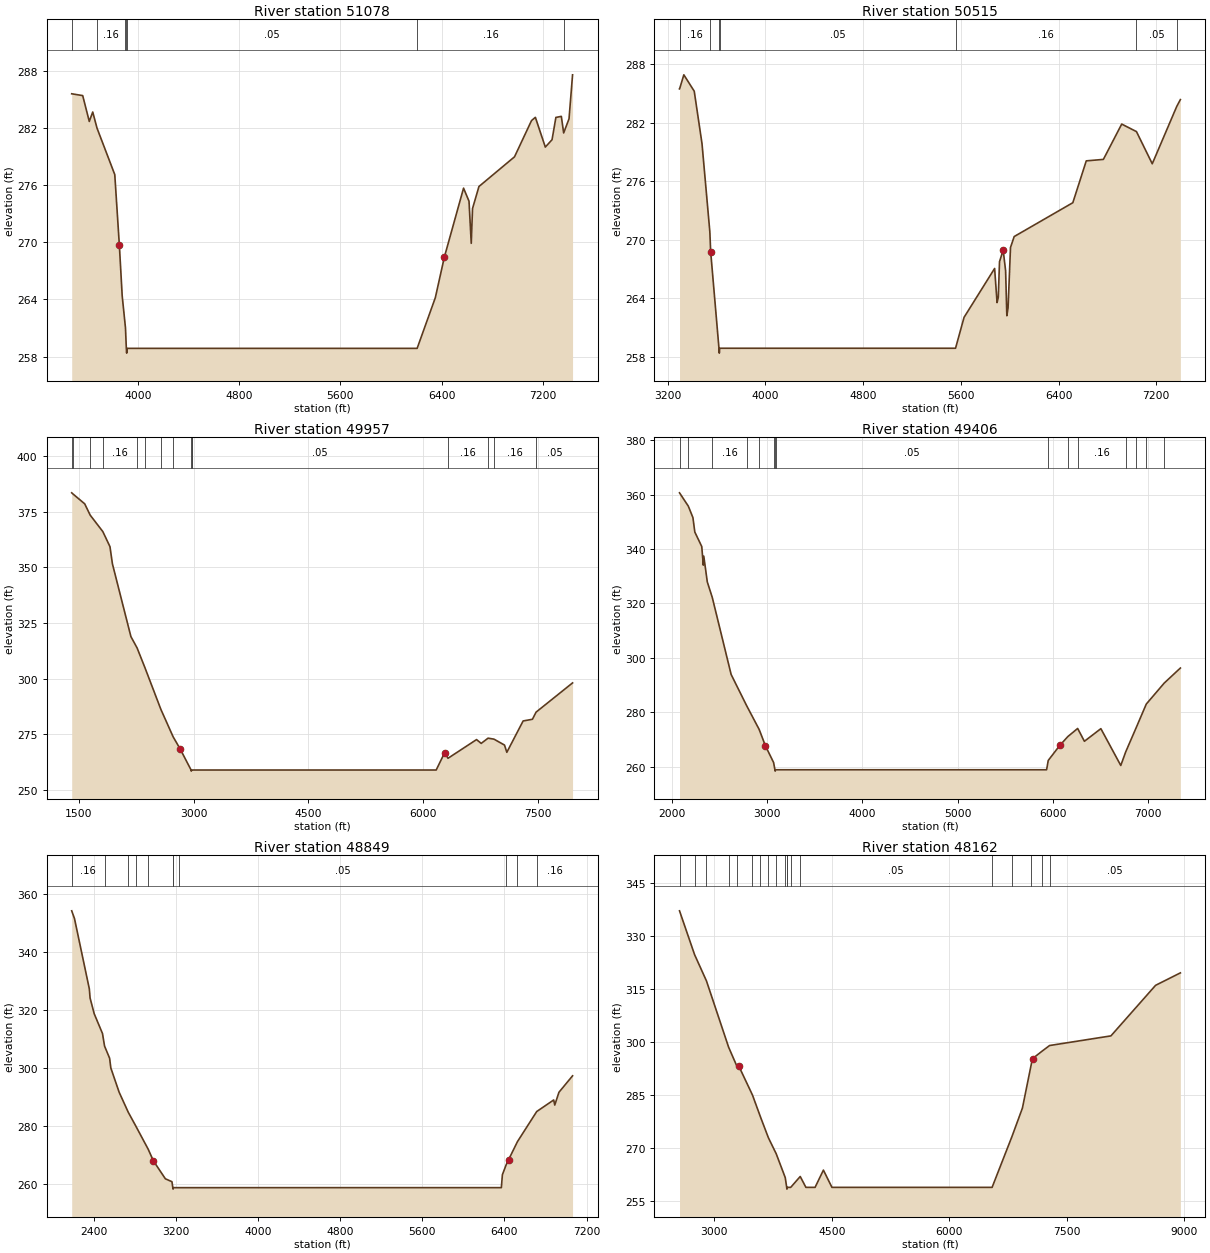
Type RM Length L Ch R = 1 ,51078   ,563,563,563
BEGIN DESCRIPTION:
LITTLE ELKHART CREEK 46.0
END DESCRIPTION:
XS GIS Cut Line= 3
      3778999.59     10507910.22      3778199.61     10509210.19
      3777799.61     10511610.19
#Sta/Elev= 30
  3476.6  285.57  3563.5  285.38  3615.6  282.67  3642.8  283.66  3676.7  281.97
  3817.1  277.09  3853.4  269.66  3875.8  264.36  3901.6  261.02  3908.4  258.86
  3911.1  258.36  3914.4  258.86  6207.4  258.86  6351.3  264.18  6422.3  268.42
  6574.4  275.67  6617.5   274.3  6635.2  269.88  6645.3  273.53    6696  275.84
  6977.4  278.96  7111.7  282.76  7142.1   283.1  7220.7  279.98  7273.9  280.75
  7304.3  283.09  7347.4   283.2  7365.7  281.46  7408.2  282.95  7436.1  287.56
#Mann= 7 ,-1 , 0
  3476.6     .05       0  3676.7     .16       0  3901.6     .05       0
  3908.4    .033       0  3914.4     .05       0  6207.4     .16       0
  7365.7     .08       0
Bank Sta=3853.4,6422.3
XS Rating Curve= 0 ,0
Exp/Cntr=0.3,0.1

Type RM Length L Ch R = 1 ,50515   ,558,558,558
BEGIN DESCRIPTION:
LITTLE ELKHART CREEK 45.0
END DESCRIPTION:
XS GIS Cut Line= 3
      3778899.61     10507960.19      3777649.61     10509110.19
      3777649.61     10511510.16
#Sta/Elev= 30
  3298.3  285.44  3298.7  285.44  3333.7  286.89  3418.8  285.21  3482.3  279.84
  3546.3  270.82  3553.2  268.77  3621.1  258.86  3623.9  258.36  3627.1  258.86
    5557  258.86  5626.8  262.03  5876.8  267.04  5896.8  263.54  5906.8  264.08
  5916.8  267.73  5946.8  268.92  5966.8   266.8  5976.8  262.19  5986.8  262.99
  6006.8  269.19  6036.8  270.31  6516.8  273.78  6626.8  278.07  6766.8  278.22
  6916.8  281.84  7037.5  281.07  7166.8  277.77  7366.8  283.64  7396.8  284.35
#Mann= 8 ,-1 , 0
  3298.3     .05       0  3298.7     .16       0  3546.3     .05       0
  3621.1    .033       0  3627.1     .05       0    5557     .16       0
  7037.5     .05       0  7366.8     .16       0
Bank Sta=3553.2,5946.8
XS Rating Curve= 0 ,0
Exp/Cntr=0.3,0.1

Type RM Length L Ch R = 1 ,49957   ,551,551,551
BEGIN DESCRIPTION:
LITTLE ELKHART CREEK 44.0
END DESCRIPTION:
XS GIS Cut Line= 3
      3776215.56     10505655.45      3777099.61     10509160.19
      3777582.46     10512046.97
#Sta/Elev= 30
  1407.5  383.57  1421.5  383.13  1577.4  378.61  1648.6  373.55  1814.2  366.12
  1907.4  359.34  1939.3  351.61  2180.6   318.9  2261.6  313.77  2363.8  304.91
  2572.5  286.11  2731.7  273.84  2825.3  268.25  2966.7  258.86  2969.4  258.36
  2972.7  258.86  2976.9  258.86  6167.7  258.86  6279.2  266.71  6322.1  264.14
  6694.9  272.55  6755.8  270.84  6845.4  273.19  6922.8  272.74  7059.9  270.09
  7090.4  266.83  7303.3  280.93  7424.9  281.69  7472.5  284.91  7948.9  298.05
#Mann= 15 ,-1 , 0
  1407.5     .08       0  1421.5     .16       0  1648.6     .05       0
  1814.2     .16       0  2261.6     .05       0  2363.8     .16       0
  2572.5     .05       0  2731.7     .16       0  2966.7    .033       0
  2972.7     .16       0  2976.9     .05       0  6322.1     .16       0
  6845.4     .05       0  6922.8     .16       0  7472.5     .05       0
Bank Sta=2825.3,6279.2
XS Rating Curve= 0 ,0
Exp/Cntr=0.3,0.1

Type RM Length L Ch R = 1 ,49406   ,557,557,557
BEGIN DESCRIPTION:
LITTLE ELKHART CREEK 43.0
END DESCRIPTION:
XS GIS Cut Line= 3
      3775865.96     10506373.17      3776549.61     10509210.19
       3775749.6     10511410.22
#Sta/Elev= 30
  2079.8  360.65  2172.3  355.75  2220.7  351.53  2240.5  346.23  2313.3  340.91
  2329.4  334.07  2334.6  337.38  2371.4  327.92  2423.9  322.18  2621.9  293.88
  2783.5   282.5  2916.5  273.66  2981.9  267.65  3067.7  261.53  3081.8  258.86
  3084.5  258.36  3087.8  258.86  5934.4  258.86  5951.5  262.28  6072.7   267.8
  6157.4  271.06  6260.4  274.04  6331.4  269.33  6504.3  273.97  6713.2  260.44
  6765.4  265.46  6878.2  274.59  6981.1  283.01  7169.9  290.74    7339  296.25
#Mann= 15 ,-1 , 0
  2079.8     .16       0  2172.3     .05       0  2423.9     .16       0
  2783.5     .05       0  2916.5     .16       0  3067.7     .05       0
  3081.8    .033       0  3087.8     .05       0  5951.5      .1       0
  6157.4     .05       0  6260.4     .16       0  6765.4     .05       0
  6878.2     .16       0  6981.1     .05       0  7169.9     .16       0
Bank Sta=2981.9,6072.7
XS Rating Curve= 0 ,0
Exp/Cntr=0.3,0.1

Type RM Length L Ch R = 1 ,48849   ,687,687,687
BEGIN DESCRIPTION:
LITTLE ELKHART CREEK 42.0
END DESCRIPTION:
XS GIS Cut Line= 3
       3775579.5     10506503.39      3775999.61     10509310.19
       3775599.6     10511310.21
#Sta/Elev= 30
  2185.8  354.05  2212.9  351.38  2357.5   327.2  2364.6  324.09    2405  318.65
  2485.7  311.86  2505.6  307.56  2554.9  303.37  2566.8  300.02  2647.7  291.68
  2736.5   284.8  2807.9  280.19    2931  272.06  2981.4  268.08  3098.1  261.91
  3162.2  260.91  3170.5  258.86  3173.2  258.36  3176.5  258.86  3230.4  258.86
    6370  258.87  6380.2  263.34  6416.6   266.7  6441.4  268.54  6526.8  274.69
  6714.5  285.04  6879.9  289.02  6890.1  287.27  6930.9  291.66  7063.5  297.32
#Mann= 11 ,-1 , 0
  2185.8     .16       0  2505.6     .05       0  2736.5     .16       0
  2807.9     .05       0    2931     .16       0  3170.5    .033       0
  3176.5     .16       0  3230.4     .05       0  6416.6     .16       0
  6526.8     .05       0  6714.5     .16       0
Bank Sta=2981.4,6441.4
XS Rating Curve= 0 ,0
Exp/Cntr=0.3,0.1

Type RM Length L Ch R = 1 ,48162   ,790,790,790
BEGIN DESCRIPTION:
LITTLE ELKHART CREEK 41.0
END DESCRIPTION:
XS GIS Cut Line= 4
      3774759.17     10506893.93      3775397.21     10509641.37
      3775410.23     10511959.08      3775440.98      10513216.9
#Sta/Elev= 30
  2554.5   337.2  2747.1  324.78  2898.4  317.36  3181.3  298.59  3294.8   292.8
  3310.4  293.27  3486.2  285.02  3587.8  278.85  3689.5  272.92  3789.3  268.38
  3904.9  261.62  3923.3  258.86  3926.1  258.36  3929.3  258.86  3974.7  258.86
    4096  261.94  4168.8  258.86  4285.6  258.86  4392.2  263.75  4501.2  258.86
  6546.5  258.86  6801.5  273.33  6933.9  281.33  7049.4     294  7063.9  295.34
  7182.2   297.4  7280.4  299.04    8064  301.77  8634.2  316.09    8951  319.62
#Mann= 19 ,-1 , 0
  2554.5     .16       0  2747.1     .05       0  2898.4     .16       0
  3181.3     .05       0  3294.8     .16       0  3486.2     .05       0
  3587.8     .08       0  3689.5     .05       0  3789.3     .16       0
  3904.9     .05       0  3923.3    .033       0  3929.3     .05       0
  3974.7     .16       0    4096     .05       0  6546.5     .16       0
  6801.5     .05       0  7049.4     .16       0  7182.2      .1       0
  7280.4     .05       0
Bank Sta=3310.4,7063.9
XS Rating Curve= 0 ,0
Exp/Cntr=0.3,0.1

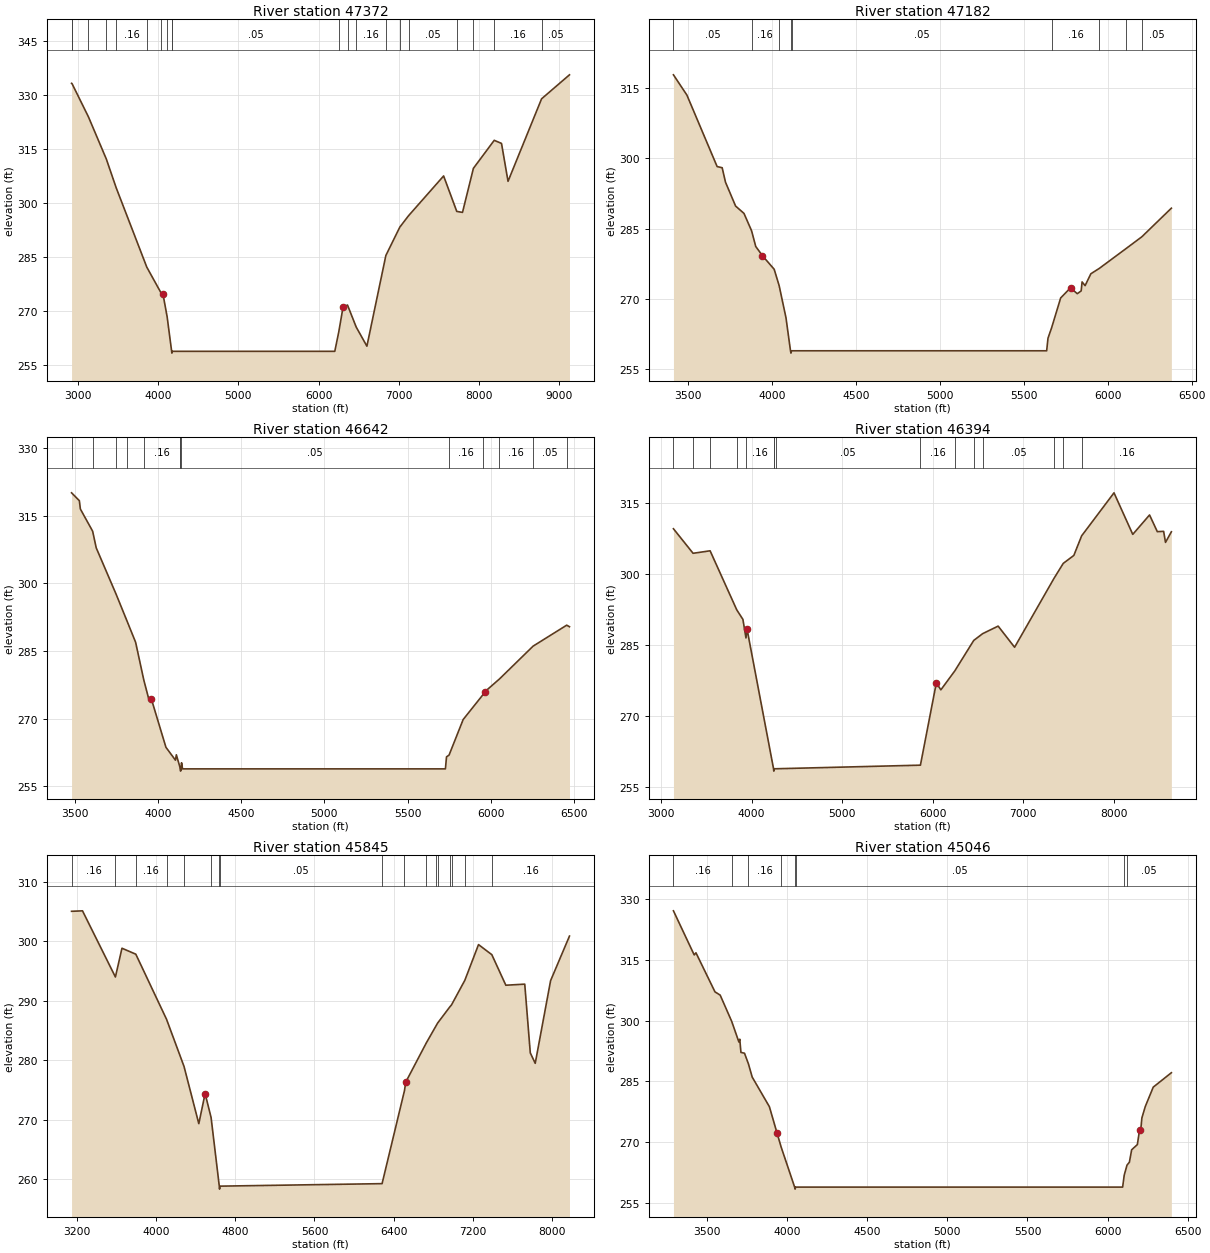
Type RM Length L Ch R = 1 ,47372   ,190,190,190
BEGIN DESCRIPTION:
LITTLE ELKHART CREEK 40.0
END DESCRIPTION:
XS GIS Cut Line= 4
      3774681.06     10507063.21      3774485.75      10509849.7
      3773639.39     10511464.29      3773177.14     10512982.48
#Sta/Elev= 30
  2922.5  333.25  2927.4  333.21  3132.9  323.94  3355.2  312.26    3479  304.23
    3860  282.22  4041.9   274.9  4062.3  274.66    4113  268.49  4169.5  258.86
  4172.3  258.36  4175.5  258.86  6201.9  258.86  6251.7  264.27  6304.5  271.08
  6360.3  271.71  6468.9  265.59    6602  260.29  6838.2  285.46  7011.9  293.33
  7120.5  296.49  7557.9  307.54  7721.6   297.7  7793.1  297.42  7928.9  309.66
  8188.4  317.43  8279.1  316.57  8360.3  306.05  8778.2  328.95  9125.8  335.61
#Mann= 20 ,-1 , 0
  2922.5     .16       0  2927.4     .05       0  3132.9     .16       0
  3355.2     .05       0    3479     .16       0    3860     .05       0
  4041.9     .16       0    4113     .05       0  4169.5    .033       0
  4175.5     .05       0  6251.7     .05       0  6360.3     .16       0
  6468.9     .16       0  6838.2     .05       0  7011.9     .16       0
  7120.5     .05       0  7721.6     .16       0  7928.9     .05       0
  8188.4     .16       0  8778.2     .05       0
Bank Sta=4062.3,6304.5
XS Rating Curve= 0 ,0
Exp/Cntr=0.3,0.1

Type RM Length L Ch R = 1 ,47182   ,540,540,540
BEGIN DESCRIPTION:
LITTLE ELKHART CREEK 39.0
END DESCRIPTION:
XS GIS Cut Line= 3
      3774399.61     10507510.15      3774349.61     10509110.19
       3773799.6     10510360.21
#Sta/Elev= 30
  3412.6  317.88  3492.7  313.55  3672.8  298.26  3702.8  298.01  3722.8  294.91
  3782.8  289.82  3832.8  288.24  3877.9  284.55  3902.9  281.17  3942.9  279.19
  4012.9  276.29  4042.6  272.75    4083  265.94    4110  258.86  4112.7  258.36
    4116  258.86  5636.2  258.86  5644.1  261.56  5665.4  263.75  5719.6  270.16
  5778.2  272.33  5818.4  271.07  5841.8  271.67  5847.2  273.59  5865.1  272.79
  5899.4  275.33  5950.5   276.5  6111.7  280.79  6203.2  283.24  6379.1  289.36
#Mann= 9 ,-1 , 0
  3412.6     .05       0  3877.9     .16       0  4042.6     .05       0
    4110    .033       0    4116     .05       0  5665.4     .16       0
  5950.5     .05       0  6111.7     .16       0  6203.2     .05       0
Bank Sta=3942.9,5778.2
XS Rating Curve= 0 ,0
Exp/Cntr=0.3,0.1

Type RM Length L Ch R = 1 ,46642   ,248,248,248
BEGIN DESCRIPTION:
LITTLE ELKHART CREEK 38.0
END DESCRIPTION:
XS GIS Cut Line= 3
      3774349.62     10507460.15      3773849.61     10508910.19
      3773449.62     10510310.15
#Sta/Elev= 30
  3482.3  320.06  3529.1  318.32  3535.2  316.47  3608.9  311.55  3630.4  307.86
  3750.2  297.55  3813.8  291.78  3867.1  286.91  3916.2  278.54  3947.8  274.08
  3960.7  274.46    4049  263.64  4106.2  260.79  4111.5  261.98  4132.4  259.33
  4134.4  258.86  4137.1  258.36  4140.4  258.86  4142.7  260.22  4148.7  258.86
  5727.2  258.86  5733.7  261.52  5749.1  261.92  5833.8   269.8  5951.7  275.26
  5962.5  275.91  6051.9   278.8  6253.7  286.07  6455.6  290.72  6472.1  290.37
#Mann= 13 ,-1 , 0
  3482.3     .05       0  3608.9     .16       0  3750.2      .1       0
  3813.8     .05       0  3916.2     .16       0  4132.4     .05       0
  4134.4    .033       0  4140.4     .05       0  5749.1     .16       0
  5951.7     .05       0  6051.9     .16       0  6253.7     .05       0
  6455.6     .08       0
Bank Sta=3960.7,5962.5
XS Rating Curve= 0 ,0
Exp/Cntr=0.3,0.1

Type RM Length L Ch R = 1 ,46394   ,549,549,549
BEGIN DESCRIPTION:
LITTLE ELKHART CREEK 37.0
END DESCRIPTION:
XS GIS Cut Line= 4
       3774199.3     10506998.12      3773405.02     10509511.16
      3773274.81     10510839.29      3772884.41     10512322.81
#Sta/Elev= 30
  3135.5  309.62  3352.5  304.43  3540.7  304.96  3835.6  292.46  3903.3  290.45
  3937.3  286.53  3948.9  288.42  4242.1  258.86  4244.8  258.36  4248.1  258.86
  4267.2  258.86  5865.6  259.62  6041.4  277.02  6091.6  275.55  6245.7  279.56
  6454.9     286  6553.1  287.43  6724.7  289.03  6906.6  284.56  7344.1  299.19
  7444.6   302.3  7561.5  303.98  7647.7  308.12  8005.5  317.22  8212.9  308.43
  8398.5  312.54  8484.3  309.01  8554.2  309.07  8574.8  306.74  8639.6  308.98
#Mann= 15 ,-1 , 0
  3135.5     .16       0  3352.5     .05       0  3540.7     .16       0
  3835.6     .05       0  3937.3     .16       0  4242.1    .033       0
  4248.1     .16       0  4267.2     .05       0  5865.6     .16       0
  6245.7     .05       0  6454.9     .16       0  6553.1     .05       0
  7344.1     .16       0  7444.6     .05       0  7647.7     .16       0
Bank Sta=3948.9,6041.4
XS Rating Curve= 0 ,0
Exp/Cntr=0.3,0.1

Type RM Length L Ch R = 1 ,45845   ,799,799,799
BEGIN DESCRIPTION:
LITTLE ELKHART CREEK 36.0
END DESCRIPTION:
XS GIS Cut Line= 3
      3774134.17     10506933.06      3772884.18     10508951.27
      3770905.01     10510735.13
#Sta/Elev= 30
  3142.2     305  3252.9  305.08  3585.9  293.97  3652.3   298.8  3792.4   297.8
  4103.1  286.88  4280.2  278.96  4429.8  269.35  4493.6   274.4    4554  270.39
  4637.1  258.86  4639.9  258.36  4643.1  258.86  6284.3  259.28    6511   274.9
    6524  276.33    6732  282.91  6831.3   285.8  6846.6  286.24  6969.2  288.94
  6987.1  289.29  7121.8  293.42  7260.2  299.41  7394.9  297.72  7536.7  292.59
    7728  292.77  7784.1  281.23  7834.1  279.48  7989.6  293.36  8180.6  300.84
#Mann= 17 ,-1 , 0
  3142.2     .16       0  3585.9     .05       0  3792.4     .16       0
  4103.1     .05       0  4280.2     .16       0    4554     .05       0
  4637.1    .033       0  4643.1     .05       0  6284.3     .16       0
    6511     .05       0    6732     .16       0  6831.3     .05       0
  6846.6     .16       0  6969.2      .1       0  6987.1     .16       0
  7121.8     .05       0  7394.9     .16       0
Bank Sta=4493.6,6524
XS Rating Curve= 0 ,0
Exp/Cntr=0.3,0.1

Type RM Length L Ch R = 1 ,45046   ,527,527,527
BEGIN DESCRIPTION:
LITTLE ELKHART CREEK 35.0
END DESCRIPTION:
XS GIS Cut Line= 3
      3773199.63     10506410.14      3772549.61     10508010.19
      3771549.57     10508960.22
#Sta/Elev= 30
  3291.5  327.15  3421.1  316.24  3431.9  316.78  3550.6  307.12    3583  306.32
  3655.2   299.8  3699.8  294.72  3705.2  295.42  3712.5  292.15  3734.7  291.96
  3759.5   289.3  3782.9  286.05    3890  278.74  3938.1  272.18  3963.1   268.8
  4047.6  258.86  4050.4  258.36  4053.6  258.86  6093.9  258.86  6103.7   261.8
  6121.1  264.29    6136  265.01  6150.1  268.08  6185.7  269.37  6199.8  273.05
  6206.7  272.96    6214  275.96  6235.1  278.77  6284.8  283.57  6397.9  287.13
#Mann= 8 ,-1 , 0
  3291.5     .16       0  3655.2     .05       0  3759.5     .16       0
  3963.1     .05       0  4047.6    .033       0  4053.6     .05       0
  6103.7     .08       0  6121.1     .05       0
Bank Sta=3938.1,6199.8
XS Rating Curve= 0 ,0
Exp/Cntr=0.3,0.1

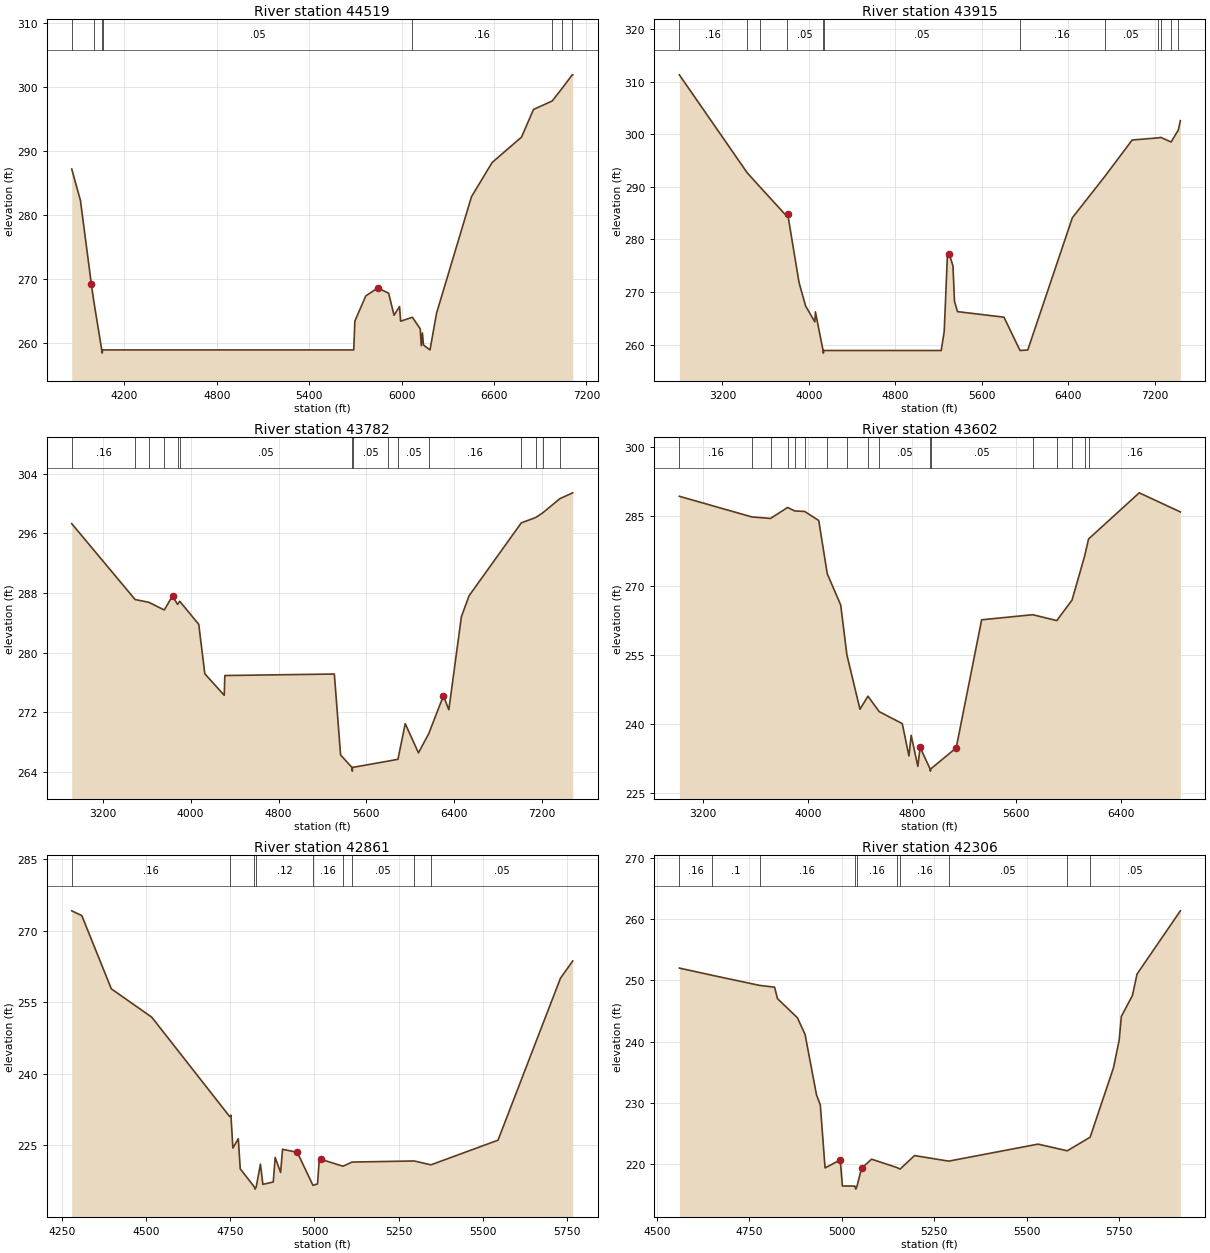
Type RM Length L Ch R = 1 ,44519   ,604,604,604
BEGIN DESCRIPTION:
LITTLE ELKHART CREEK 34.0
END DESCRIPTION:
XS GIS Cut Line= 3
      3772949.58     10506860.22      3772149.61     10507660.19
      3770699.63     10509210.17
#Sta/Elev= 30
  3857.4  287.14  3913.9  282.25  3984.6  269.21  4000.1  266.58  4052.4  258.86
  4055.1  258.36  4058.4  258.86    5689  258.86  5696.3  263.37  5767.1   267.3
  5844.8  268.55  5915.6  267.73  5950.8  264.28  5986.5  265.64  5993.3  263.35
  6069.9  263.96  6120.8  262.16  6127.7  259.52    6135  261.51  6141.8  259.63
  6184.3  258.86  6226.8   264.6  6453.5   282.8  6587.8  288.16  6778.8  292.13
  6856.5  296.45  6977.8  297.77  7042.3  299.75  7107.5  301.85  7111.2  301.86
#Mann= 8 ,-1 , 0
  3857.4     .16       0  4000.1     .05       0  4052.4    .033       0
  4058.4     .05       0  6069.9     .16       0  6977.8     .05       0
  7042.3     .16       0  7107.5     .05       0
Bank Sta=3984.6,5844.8
XS Rating Curve= 0 ,0
Exp/Cntr=0.3,0.1

Type RM Length L Ch R = 1 ,43915   ,133,133,133
BEGIN DESCRIPTION:
Mapping XS 3f138143
END DESCRIPTION:
XS GIS Cut Line= 5
       3772949.3     10505513.75        3772142.     10506112.72
      3771699.29     10507297.62      3771412.83     10507740.33
      3770240.95      10509159.6
#Sta/Elev= 30
  2800.6  311.27  3427.6  292.68  3543.9  290.03  3797.3  284.34  3804.2  284.74
  3908.6   271.8  3969.2  267.33  4054.8   264.3  4060.1   266.2  4131.1  258.86
  4133.8  258.36  4137.1  258.86  5224.7  258.86  5252.5  262.47    5282   276.9
  5297.2   277.3  5333.5  274.97  5347.7  268.21  5375.7  266.25  5805.6  265.19
  5954.3  258.86  6025.8  258.95  6438.8   284.1  6736.5  291.88  6992.5  298.88
  7229.8  299.28  7256.9  299.38  7353.2   298.5  7419.8  300.78  7438.6  302.56
#Mann= 12 ,-1 , 0
  2800.6     .16       0  3427.6     .05       0  3543.9     .16       0
  3797.3     .05       0  4131.1    .033       0  4137.1     .05       0
  5954.3     .16       0  6736.5     .05       0  7229.8     .16       0
  7256.9     .05       0  7353.2     .16       0  7419.8     .08       0
Bank Sta=3804.2,5297.2
XS Rating Curve= 0 ,0
Exp/Cntr=0.3,0.1

Type RM Length L Ch R = 1 ,43782   ,180,180,180
BEGIN DESCRIPTION:
LITTLE ELKHART CREEK 32.0
END DESCRIPTION:
XS GIS Cut Line= 5
      3772766.96     10505461.71      3771998.77     10506151.79
       3771582.1     10507271.58      3771543.04     10507362.72
      3770084.82      10509055.3
#Sta/Elev= 30
  2917.5   297.3  3494.7  287.12  3619.4  286.75  3760.2  285.72  3835.1  287.62
  3881.1  286.46    3901  286.89  4073.9  283.79  4129.3  277.16    4306  274.28
  4311.3  276.93  5308.2  277.13  5365.2  266.27  5468.6  264.61  5471.4  264.11
  5474.6  264.61  5800.1  265.46  5887.3   265.7  5953.5  270.48    6074  266.56
  6167.7  269.14  6301.1  274.21  6350.4  272.34  6464.5   284.8  6534.8  287.63
    7010   297.4  7140.9  298.12  7203.1  298.72  7361.6  300.65  7478.2  301.43
#Mann= 15 ,-1 , 0
  2917.5     .16       0  3494.7     .05       0  3619.4     .16       0
  3760.2     .05       0  3881.1      .1       0    3901     .05       0
  5468.6     .03       0  5474.6     .05       0  5800.1     .08       0
  5887.3     .05       0  6167.7     .16       0    7010     .05       0
  7140.9      .1       0  7203.1     .05       0  7361.6     .16       0
Bank Sta=3835.1,6301.1
XS Rating Curve= 0 ,0
Exp/Cntr=0.3,0.1

Type RM Length L Ch R = 1 ,43602   ,741,741,741
BEGIN DESCRIPTION:
Mapping XS 771b1ddf
END DESCRIPTION:
XS GIS Cut Line= 4
      3772662.82     10505422.63      3771855.54     10506268.97
      3771329.25     10507383.08      3770084.71     10508104.91
#Sta/Elev= 30
  3016.2  289.33  3573.1  284.85    3715  284.53  3845.8  286.91  3901.6  286.15
  3976.6  286.05  4084.8  284.08    4150  272.55  4253.1  265.78  4300.6  254.97
  4400.8   243.2  4461.7  246.04  4548.2  242.69    4725  240.09  4776.1  233.09
  4793.3  237.55  4844.4  230.82  4861.6  234.95    4938   230.3  4940.7   229.8
    4944   230.3  5138.3  234.83  5333.5  262.58  5724.8  263.68  5909.3  262.41
  6026.2  266.84  6122.2  276.32  6152.9  280.08  6541.5  290.08  6856.7  285.94
#Mann= 17 ,-1 , 0
  3016.2     .16       0  3573.1     .05       0    3715     .16       0
  3845.8     .05       0  3901.6      .1       0  3976.6     .05       0
    4150     .08       0  4300.6     .05       0  4461.7      .1       0
  4548.2     .05       0    4938     .03       0    4944     .05       0
  5724.8     .08       0  5909.3     .05       0  6026.2     .08       0
  6122.2     .05       0  6152.9     .16       0
Bank Sta=4861.6,5138.3
XS Rating Curve= 0 ,0
Exp/Cntr=0.3,0.1

Type RM Length L Ch R = 1 ,42861   ,555,555,555
BEGIN DESCRIPTION:
LITTLE ELKHART CREEK 31.0
END DESCRIPTION:
XS GIS Cut Line= 3
      3771649.63     10506160.18      3770999.61     10506510.19
      3770399.58     10506960.21
#Sta/Elev= 30
  4278.9  274.17  4308.9  273.17  4396.6  257.82  4516.6  251.89  4748.1  231.06
  4751.9  231.34  4757.6  224.46  4773.8  226.41  4779.5   220.1  4821.1  216.35
  4823.8  215.85  4827.1  216.35  4839.5  221.09  4846.8  216.85  4877.6  217.35
  4883.3  222.49  4899.5  219.34  4905.2   224.2    4949  223.56  4995.5  216.64
  5009.1  216.94  5014.3  222.07  5020.3  222.07  5084.7  220.65  5111.6  221.52
    5296  221.75  5346.1  220.94  5545.3  226.11  5730.7  260.04  5767.2  263.66
#Mann= 9 ,-1 , 0
  4278.9     .16       0  4748.1     .12       0  4821.1     .07       0
  4827.1     .12       0  4995.5     .16       0  5084.7     .07       0
  5111.6     .05       0    5296     .07       0  5346.1     .05       0
Bank Sta=4949,5020.3
XS Rating Curve= 0 ,0
Exp/Cntr=0.3,0.1

Type RM Length L Ch R = 1 ,42306   ,554,554,554
BEGIN DESCRIPTION:
LITTLE ELKHART CREEK 30.0
END DESCRIPTION:
XS GIS Cut Line= 3
      3771249.64     10506010.18      3770849.61     10506110.19
      3770349.63     10506910.15
#Sta/Elev= 30
  4560.3  252.01  4649.4  250.83  4777.5  249.18    4818  248.89  4825.8  247.02
  4879.9  243.89  4900.5  241.17  4931.4  231.31  4941.7  229.67  4954.6  219.37
  4995.6  220.68  5001.5  216.42  5035.1  216.41  5037.8  215.91  5041.1  216.41
  5053.4  219.33  5080.5   220.8  5148.8  219.44  5157.7  219.19  5196.7  221.39
  5289.1  220.48    5531  223.26  5609.9  222.17  5671.9  224.39    5735  235.72
  5750.4  240.23  5756.3  244.12  5786.3  247.53  5798.7  251.03    5916  261.36
#Mann= 10 ,-1 , 0
  4560.3     .16       0  4649.4      .1       0  4777.5     .16       0
  5035.1     .07       0  5041.1     .16       0  5148.8     .05       0
  5157.7     .16       0  5289.1     .05       0  5609.9     .16       0
  5671.9     .05       0
Bank Sta=4995.6,5053.4
XS Rating Curve= 0 ,0
Exp/Cntr=0.3,0.1

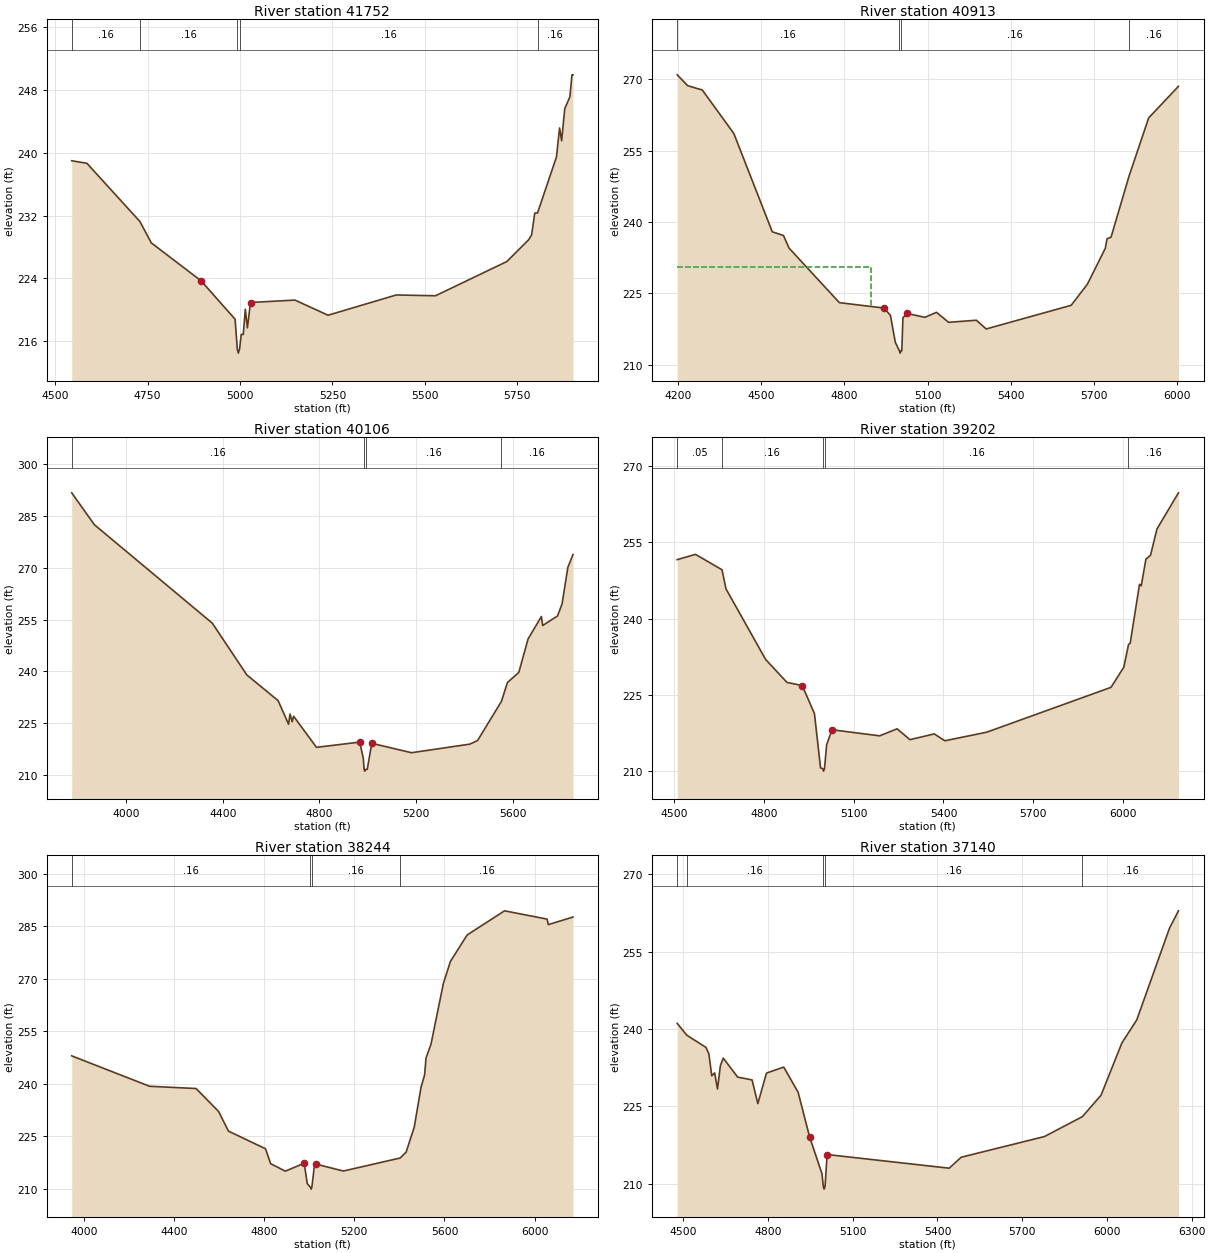
Type RM Length L Ch R = 1 ,41752   ,839,839,839
BEGIN DESCRIPTION:
LITTLE ELKHART CREEK 29.0
END DESCRIPTION:
XS GIS Cut Line= 3
      3771049.62     10505760.19      3770599.61     10505660.19
      3769799.62     10506060.18
#Sta/Elev= 30
    4545     239    4586  238.68  4729.4  231.26  4760.1  228.54  4894.6  223.71
  4986.8  218.81  4992.7  214.99  4995.5  214.49  4998.7  214.99  5003.4  216.87
  5008.8  216.87  5014.4  220.09    5020  217.71  5028.4  220.94  5148.5  221.25
    5238  219.32  5422.5   221.9  5528.7   221.8  5721.5  226.16  5780.2  228.92
  5788.6  229.56    5797  232.33  5804.6  232.36  5855.7  239.49  5864.1  243.18
  5869.7  241.55  5878.1  245.63    5892  247.15  5897.6  249.95  5900.4  249.95
#Mann= 5 ,-1 , 0
    4545     .16       0  4729.4     .16       0  4992.7     .03       0
  4998.7     .16       0  5804.6     .16       0
Bank Sta=4894.6,5028.4
XS Rating Curve= 0 ,0
Exp/Cntr=0.3,0.1

Type RM Length L Ch R = 1 ,40913   ,807,807,807
BEGIN DESCRIPTION:
LITTLE ELKHART CREEK 28.0
END DESCRIPTION:
XS GIS Cut Line= 3
      3770349.61     10504410.16      3770249.61     10505210.19
      3769649.58     10506010.22
#Sta/Elev= 30
  4197.2  270.94    4235  268.66  4287.9  267.74  4401.3  258.61  4539.9  237.93
  4580.2  237.16  4600.3  234.51  4781.7  223.03    4943   221.9  4965.7  220.35
  4983.3   214.7  4997.9  212.92  5000.7  212.42  5003.9  212.92  5006.6  212.92
  5010.7  219.86  5025.3  220.76  5089.9  219.95  5131.6     221  5175.3   218.9
  5275.3  219.34  5310.7   217.5    5617  222.48  5675.3  226.91  5739.9  234.45
  5746.2  236.46  5760.7  236.81  5825.3  249.61  5896.2  261.88  6003.5  268.52
#Mann= 4 ,-1 , 0
  4197.2     .16       0  4997.9     .07       0  5003.9     .16       0
  5825.3     .16       0
#XS Ineff= 2 , 0
         4894.89   230.5
Permanent Ineff=
       F       F
Bank Sta=4943,5025.3
XS Rating Curve= 0 ,0
Exp/Cntr=0.3,0.1

Type RM Length L Ch R = 1 ,40106   ,904,904,904
BEGIN DESCRIPTION:
LITTLE ELKHART CREEK 27.0
END DESCRIPTION:
XS GIS Cut Line= 3
      3770349.59     10504110.22      3769649.61     10505110.19
      3769349.62     10505910.17
#Sta/Elev= 30
  3774.4  291.72  3868.1  282.49  4356.4  253.98  4499.3     239  4628.8  231.55
    4672  224.73  4678.1  227.69  4686.8  225.43  4692.9  227.04  4787.5  218.04
  4966.7  219.55  4981.5  214.78  4984.6  211.65  4987.4  211.15  4990.6  211.65
  4997.7  211.66  5016.4   219.2    5181  216.48  5422.2  218.96  5454.3     220
  5553.1  231.33    5578   236.8  5625.1  239.73  5663.4  249.41  5718.6  255.91
  5723.9  253.31  5785.3  256.07    5804  259.52  5828.1  270.13  5849.4  273.85
#Mann= 4 ,-1 , 0
  3774.4     .16       0  4984.6     .07       0  4990.6     .16       0
  5553.1     .16       0
Bank Sta=4966.7,5016.4
XS Rating Curve= 0 ,0
Exp/Cntr=0.3,0.1

Type RM Length L Ch R = 1 ,39202   ,958,958,958
BEGIN DESCRIPTION:
LITTLE ELKHART CREEK 26.0
END DESCRIPTION:
XS GIS Cut Line= 3
      3769299.62     10504410.14      3769199.61     10504910.19
      3768599.63     10505910.16
#Sta/Elev= 30
  4509.6  251.59  4570.8  252.63  4659.5   249.6  4672.8  245.85  4805.4  231.96
  4876.8  227.44  4927.8  226.83  4968.6  221.31    4989  210.64  4996.2   210.5
  4998.9     210  5002.2   210.5  5009.3  215.17  5027.3  218.14  5186.7  216.94
    5245  218.32  5287.8  216.19  5369.4  217.32  5404.4  215.97  5544.3  217.65
  5960.3  226.48    6003  230.43  6018.6  234.86  6024.4  235.16  6055.5  246.73
  6061.3  246.44  6076.9  251.69  6092.4  252.46  6113.8  257.61  6185.7  264.73
#Mann= 5 ,-1 , 0
  4509.6     .05       0  4659.5     .16       0  4996.2     .07       0
  5002.2     .16       0  6018.6     .16       0
Bank Sta=4927.8,5027.3
XS Rating Curve= 0 ,0
Exp/Cntr=0.3,0.1

Type RM Length L Ch R = 1 ,38244   ,1104,1104,1104
BEGIN DESCRIPTION:
LITTLE ELKHART CREEK 25.0
END DESCRIPTION:
XS GIS Cut Line= 3
      3769156.55     10504374.47      3768451.26     10504906.16
      3767887.03     10506121.41
#Sta/Elev= 30
  3946.9  247.93  4292.2  239.25  4498.3  238.61  4598.3  232.05    4642  226.44
  4806.4  221.41  4829.3  217.14  4894.3  215.01  4977.9  217.28  4991.4  211.47
  5005.8  210.38  5008.6  209.88  5011.8  210.38    5022  216.01  5031.7     217
  5151.7  215.05  5403.7  218.77    5430  220.46    5466  227.59  5496.1     239
  5511.7  242.43  5518.2  247.32  5540.2  251.27  5595.3  268.64  5626.2  274.88
  5700.5  282.45  5866.3  289.35    6055  286.99  6060.5  285.41    6170  287.58
#Mann= 4 ,-1 , 0
  3946.9     .16       0  5005.8     .03       0  5011.8     .16       0
  5403.7     .16       0
Bank Sta=4977.9,5031.7
XS Rating Curve= 0 ,0
Exp/Cntr=0.3,0.1

Type RM Length L Ch R = 1 ,37140   ,767,767,767
BEGIN DESCRIPTION:
LITTLE ELKHART CREEK 24.0
END DESCRIPTION:
XS GIS Cut Line= 3
      3768949.66      10504360.2      3768449.61     10504260.19
      3767249.57      10504660.2
#Sta/Elev= 30
  4478.4  241.11  4512.8  238.79  4580.4  236.44  4590.6  235.18  4600.8  230.94
    4611   231.5  4621.2  228.38  4631.4   232.9  4641.6  234.36  4692.6  230.68
  4743.6  230.13    4764  225.54  4794.6  231.46  4855.8  232.62  4906.8  227.71
  4947.6  219.01    4991  211.96  4995.9  209.45  4998.6  208.95  5001.9  209.45
  5009.4  215.66  5441.6  213.01  5483.8  215.13  5778.9  219.15  5913.2  223.01
  5979.2  227.16    6053   237.3  6105.7  241.77  6221.6  259.56  6253.3  262.93
#Mann= 5 ,-1 , 0
  4478.4     .05       0  4512.8     .16       0  4995.9     .07       0
  5001.9     .16       0  5913.2     .16       0
Bank Sta=4947.6,5009.4
XS Rating Curve= 0 ,0
Exp/Cntr=0.3,0.1

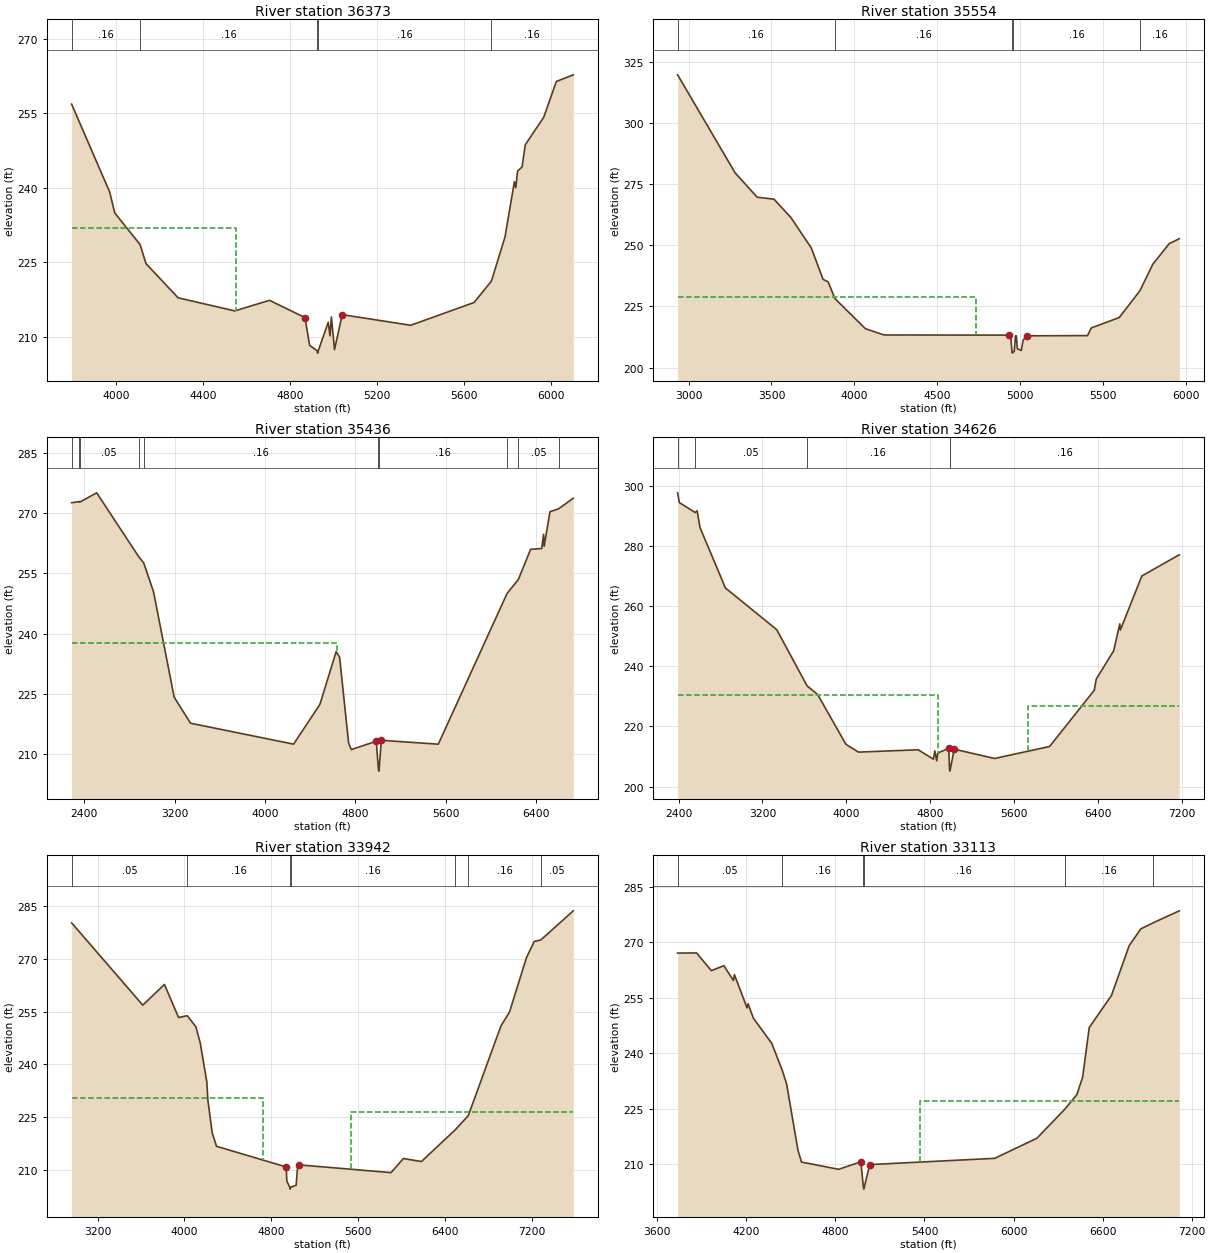
Type RM Length L Ch R = 1 ,36373   ,819,819,819
BEGIN DESCRIPTION:
LITTLE ELKHART CREEK 23.0
END DESCRIPTION:
XS GIS Cut Line= 3
      3769149.62     10503210.18      3768149.61     10503810.19
      3767249.59      10504510.2
#Sta/Elev= 30
  3796.7  256.81  3971.6  239.14    3995  234.93  4111.6  228.56  4138.8  224.73
  4286.5  217.86    4547  215.23  4706.3  217.36  4869.6  213.89    4891  208.31
  4924.9  207.24  4927.7  206.74  4930.9  207.24  4976.5  212.94  4984.6  210.21
    4991  214.01  5005.4  207.45  5040.7  214.48  5355.6  212.34    5647  216.92
  5726.6  221.21  5789.1  230.08  5832.5  241.21  5838.8  239.99    5847  243.33
  5867.8  244.19  5882.3  248.63  5967.3  254.17  6025.3  261.36  6103.1   262.7
#Mann= 5 ,-1 , 0
  3796.7     .16       0  4111.6     .16       0  4924.9     .03       0
  4930.9     .16       0  5726.6     .16       0
#XS Ineff= 2 , 0
          4551.7  231.89
Permanent Ineff=
       F       F
Bank Sta=4869.6,5040.7
XS Rating Curve= 0 ,0
Exp/Cntr=0.3,0.1

Type RM Length L Ch R = 1 ,35554   ,118,118,118
BEGIN DESCRIPTION:
LITTLE ELKHART CREEK 22.0
END DESCRIPTION:
XS GIS Cut Line= 3
      3769799.61     10503010.19      3767799.61     10503410.19
      3767399.61     10504310.19
#Sta/Elev= 30
    2934   319.7  3280.7  279.63  3413.3   269.7  3515.3  268.86  3617.3  261.35
  3739.6  248.98    3811   236.1  3841.6  235.06  3882.4  228.24    4066  215.94
  4178.2  213.36  4932.8   213.3    4943  212.08  4950.2  206.44    4953  205.94
  4956.2  206.44  4963.4  206.59  4971.1     213  4976.3     213  4982.5  207.73
  5005.8  207.01  5017.4  211.29    5040  213.02  5405.2   213.1  5428.4  216.24
  5596.7  220.49  5721.2  231.43  5799.1  242.28  5897.6  250.67  5958.5  252.71
#Mann= 5 ,-1 , 0
    2934     .16       0  3882.4     .16       0  4950.2     .03       0
  4956.2     .16       0  5721.2     .16       0
#XS Ineff= 2 , 0
         4731.25  228.84
Permanent Ineff=
       F       F
Bank Sta=4932.8,5040
XS Rating Curve= 0 ,0
Exp/Cntr=0.3,0.1

Type RM Length L Ch R = 1 ,35436   ,810,810,810
BEGIN DESCRIPTION:
Mapping XS 9b2ea722
END DESCRIPTION:
XS GIS Cut Line= 4
      3769115.76     10501040.48      3767831.96     10503158.51
      3767309.59     10503953.68      3767046.28     10504929.45
#Sta/Elev= 30
  2289.3  272.55  2358.4  272.84  2361.3  272.69  2511.1  275.01  2881.6  259.18
  2927.2  257.57    3014  250.41  3196.7  224.19  3341.4  217.71  4253.5   212.5
  4486.2  222.38  4629.7  235.49  4660.7   234.1  4740.2  212.79  4764.1  211.15
  4984.6  213.22  5004.3  206.29  5007.1  205.79  5010.3  206.29  5029.8  213.46
  5533.8  212.49  6141.7  249.94  6242.3  253.46  6350.7  260.96  6449.2  261.16
  6465.3   264.7  6470.5  261.69  6521.7  270.31    6598  271.03  6728.1  273.67
#Mann= 10 ,-1 , 0
  2289.3     .16       0  2358.4      .1       0  2361.3     .05       0
  2881.6     .16       0  2927.2     .16       0  5004.3     .03       0
  5010.3     .16       0  6141.7     .08       0  6242.3     .05       0
    6598     .16       0
#XS Ineff= 2 , 0
         4633.52  237.65
Permanent Ineff=
       F       F
Bank Sta=4984.6,5029.8
XS Rating Curve= 0 ,0
Exp/Cntr=0.3,0.1

Type RM Length L Ch R = 1 ,34626   ,684,684,684
BEGIN DESCRIPTION:
LITTLE ELKHART CREEK 21.0
END DESCRIPTION:
XS GIS Cut Line= 3
      3767615.75     10500413.92       3767604.9      10502475.6
      3766834.55     10505090.47
#Sta/Elev= 30
    2390  297.77  2406.3  294.53  2557.3  291.23  2576.3  291.78  2604.3  286.18
  2846.3   266.1  3336.3  252.22  3626.3  233.49  3726.3  230.66  3996.3  214.07
  4116.3  211.47  4685.8  212.25  4831.8  209.11  4844.7  211.87  4863.1   208.6
  4872.8  211.15  4977.7  212.76  4985.5  205.64  4988.2  205.14  4991.5  205.64
  5029.9  212.45  5415.6  209.35  5940.5  213.35  6366.5  232.06  6385.1  235.75
  6551.9  245.21  6610.3  254.17  6615.5  252.11  6820.7   270.1  7177.7  277.15
#Mann= 5 ,-1 , 0
    2390      .1       0  2557.3     .05       0  3626.3     .16       0
  4985.5     .07       0  4991.5     .16       0
#XS Ineff= 2 , 0
         4873.86  230.41 5729.55          226.91
Permanent Ineff=
       F       F
Bank Sta=4977.7,5029.9
XS Rating Curve= 0 ,0
Exp/Cntr=0.3,0.1

Type RM Length L Ch R = 1 ,33942   ,829,829,829
BEGIN DESCRIPTION:
Mapping XS c6e03e02
END DESCRIPTION:
XS GIS Cut Line= 4
      3767207.77      10500904.4      3767207.77     10502579.77
      3766782.42     10503543.31      3766261.74     10505365.67
#Sta/Elev= 30
  2959.8  280.15  3615.6  256.82  3815.6  262.68  3945.6  253.31  4025.6  253.83
  4105.6  250.66  4145.6  246.04  4205.6  235.12  4215.6  229.91  4255.6  220.62
  4295.6  216.79  4938.2  210.94  4943.6   206.9  4971.5  205.15  4974.2  204.65
  4977.5  205.15  5029.1  205.77  5042.4  210.84  5060.2  211.52  5903.8  209.33
    6018  213.33  6184.4  212.47  6496.4  221.49  6616.2   225.5  6917.8  250.97
  6995.8  254.84  7151.6  270.23  7224.4  274.89  7284.4  275.29  7583.7  283.56
#Mann= 7 ,-1 , 0
  2959.8     .05       0  4025.6     .16       0  4971.5     .07       0
  4977.5     .16       0  6496.4     .05       0  6616.2     .16       0
  7284.4     .05       0
#XS Ineff= 2 , 0
         4723.86  230.41 5531.82          226.41
Permanent Ineff=
       F       F
Bank Sta=4938.2,5060.2
XS Rating Curve= 0 ,0
Exp/Cntr=0.3,0.1

Type RM Length L Ch R = 1 ,33113   ,855,855,855
BEGIN DESCRIPTION:
LITTLE ELKHART CREEK 20.0
END DESCRIPTION:
XS GIS Cut Line= 4
       3766218.2     10501980.82      3766591.45     10502388.79
      3766608.81     10503812.41      3766087.96     10505114.53
#Sta/Elev= 30
  3737.1  267.13  3865.1  267.17  3964.3  262.36  4048.8  263.73    4113   259.7
  4119.7   261.3  4204.8   252.3  4211.6  253.42  4247.4  249.53  4371.5  242.68
  4441.5  235.47  4471.5  231.71  4547.9  213.76  4571.5  210.59  4821.5  208.62
  4971.5  210.65  4988.5  203.76  4991.3  203.26  5031.5   209.9  5872.9  211.59
  6157.1  217.02  6344.5  224.85  6426.4  228.82  6465.3  233.52  6509.9  246.99
  6659.2  255.64  6779.1  269.14  6857.2  273.68  6939.7   275.3  7116.2  278.56
#Mann= 6 ,-1 , 0
  3737.1     .05       0  4441.5     .16       0  4988.5     .07       0
  4991.3     .16       0  6344.5     .16       0  6939.7     .05       0
#XS Ineff= 2 , 0
                         5372.73          227.23
Permanent Ineff=
       F       F
Bank Sta=4971.5,5031.5
XS Rating Curve= 0 ,0
Exp/Cntr=0.3,0.1