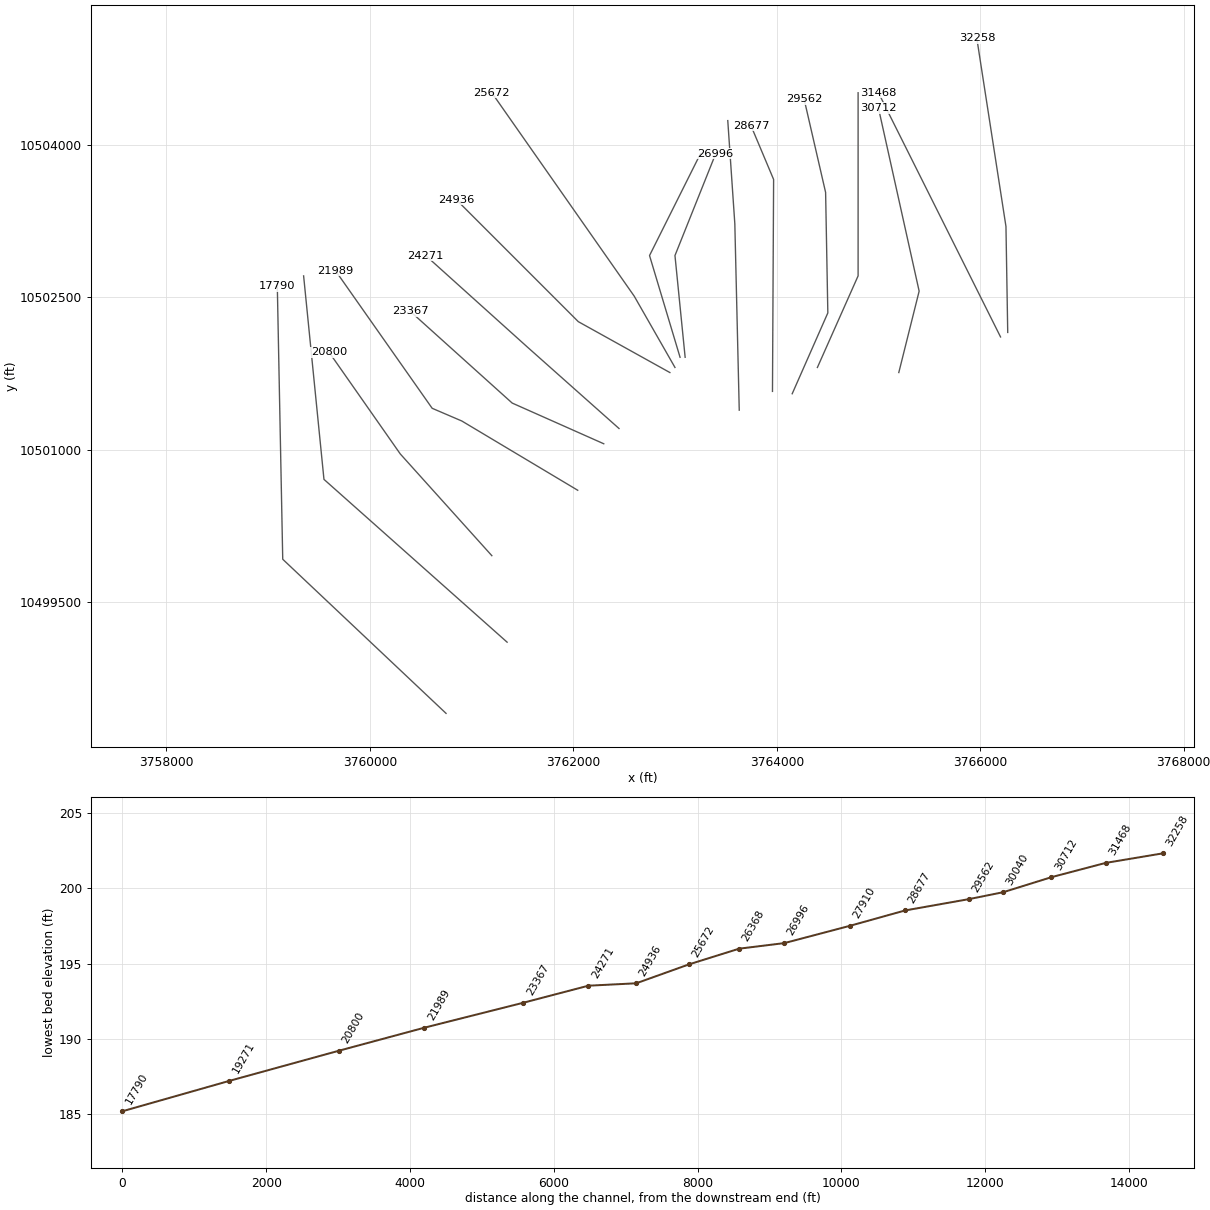
HEC-RAS study LITTLE ELKHART CREEK.prj: LITTLE ELKHART CREEK Base Level Engineering

--- LITTLE ELKHART CREEK.g01 (geometry) --- (continued)

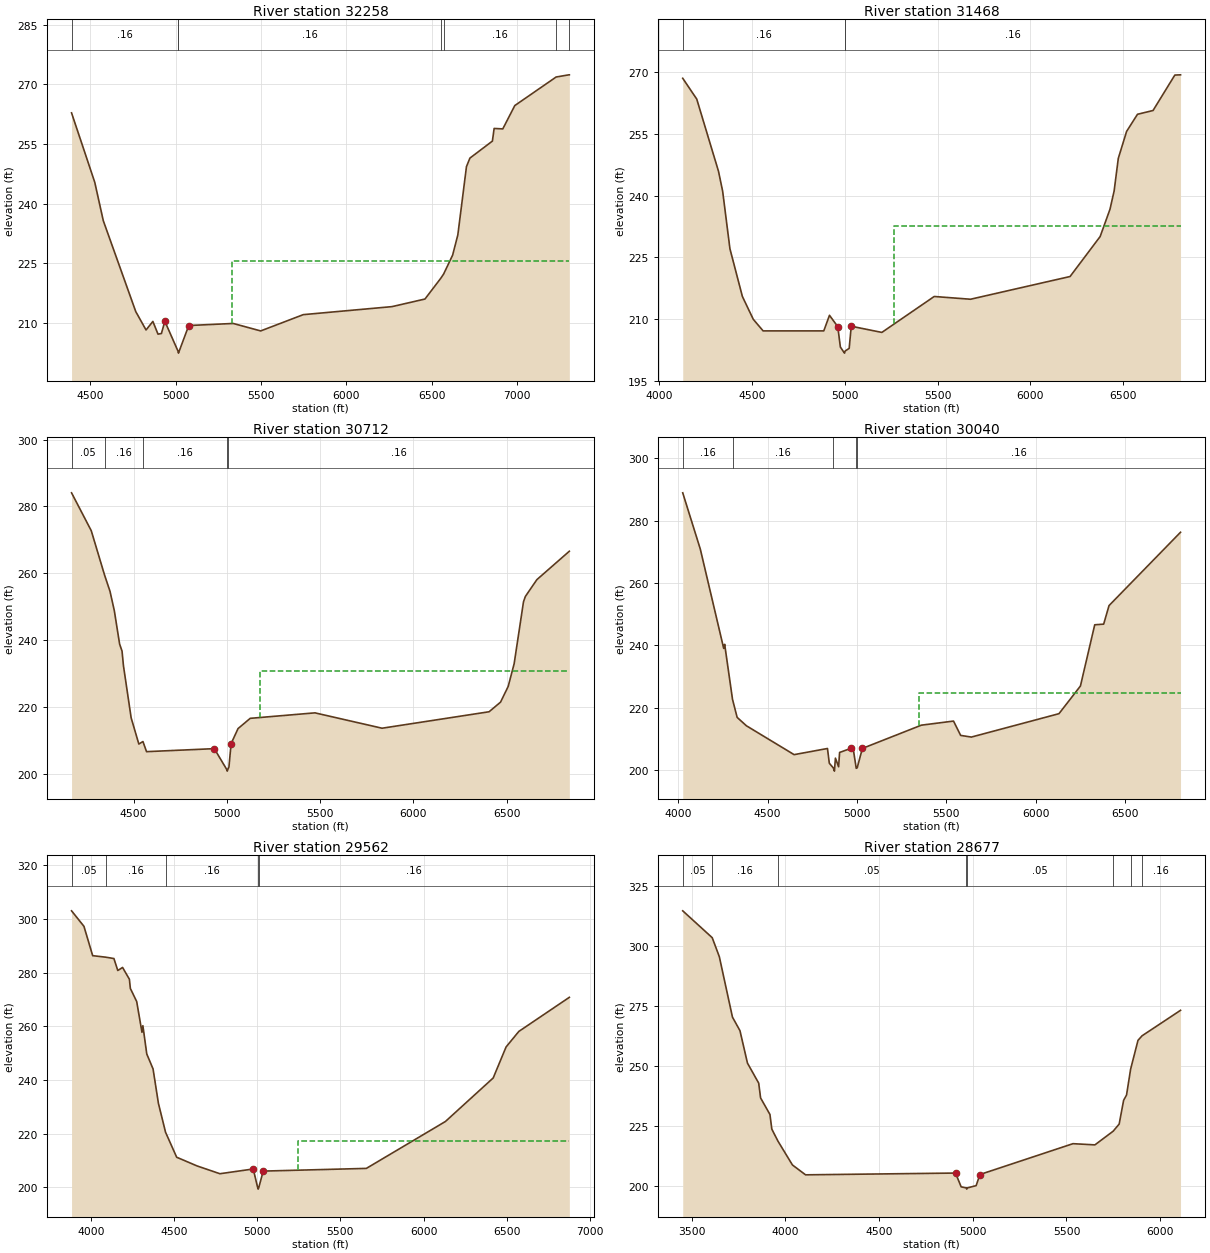
Type RM Length L Ch R = 1 ,32258   ,790,790,790
BEGIN DESCRIPTION:
Mapping XS 02633ef0
END DESCRIPTION:
XS GIS Cut Line= 3
      3766270.27     10502154.39      3766252.91     10503196.09
      3765966.44     10505045.09
#Sta/Elev= 30
  4391.5  262.83  4527.3  245.35  4577.3  235.67  4767.3  212.78  4827.4  208.16
  4867.4  210.31  4897.4  207.11  4917.4  207.27  4937.4  210.35  5014.4  202.83
  5017.1  202.33  5077.4  209.28  5337.4   209.8  5498.2  207.92  5747.5  212.02
  6266.8  214.04  6459.5  215.95  6550.6  221.09  6568.7  222.24  6621.4  227.01
  6651.8  232.08  6702.4  249.29  6722.6  251.44  6854.1  255.72  6864.3  258.91
  6914.9  258.79  6985.2  264.67  7227.1  271.86    7302  272.41  7304.4  272.41
#Mann= 7 ,-1 , 0
  4391.5     .16       0  5014.4     .07       0  5017.1     .16       0
  6550.6     .12       0  6568.7     .16       0  7227.1     .05       0
    7302     .16       0
#XS Ineff= 2 , 0
                         5328.41          225.53
Permanent Ineff=
       F       F
Bank Sta=4937.4,5077.4
XS Rating Curve= 0 ,0
Exp/Cntr=0.3,0.1

Type RM Length L Ch R = 1 ,31468   ,756,756,756
BEGIN DESCRIPTION:
LITTLE ELKHART CREEK 19.0
END DESCRIPTION:
XS GIS Cut Line= 3
      3766199.62     10502110.17      3765799.61     10502910.19
      3764999.61     10504510.19
#Sta/Elev= 30
  4126.6  268.57  4202.1  263.51  4319.5  245.93  4341.8  241.08    4381   227.1
  4448.1  215.49  4506.7  209.94  4559.9  207.11  4886.9  207.11  4917.6   210.9
  4962.3  208.15  4976.3  203.19  4998.4   201.7  4998.9   201.7  5001.7   202.2
  5023.8  202.86    5035  208.24  5199.9  206.74  5482.2  215.48  5677.9  214.81
  6214.5  220.34  6376.7  230.07  6429.8  236.72  6452.1  241.18  6474.5  249.09
  6519.2  255.64  6577.9  259.81  6661.8  260.73  6779.2  269.35  6809.9  269.41
#Mann= 3 ,-1 , 0
  4126.6     .16       0  4998.9     .07       0  5001.7     .16       0
#XS Ineff= 2 , 0
                         5263.07          232.64
Permanent Ineff=
       F       F
Bank Sta=4962.3,5035
XS Rating Curve= 0 ,0
Exp/Cntr=0.3,0.1

Type RM Length L Ch R = 1 ,30712   ,672,672,672
BEGIN DESCRIPTION:
LITTLE ELKHART CREEK 18.0
END DESCRIPTION:
XS GIS Cut Line= 3
      3765199.61     10501760.21      3765399.61     10502560.19
      3764999.61     10504360.18
#Sta/Elev= 30
  4167.2  284.09  4272.8  272.75  4344.3  259.44  4373.3   254.6  4396.5  248.79
  4424.9  238.79  4437.8  236.71  4445.5  232.28  4486.7   216.7  4527.9  208.86
  4549.9  209.61  4569.2  206.58  4932.5  207.48    4999  201.25  5001.8  200.75
    5005  201.25    5011  202.01  5022.5  208.98  5059.7  213.49    5125  216.56
    5472   218.2  5831.8   213.6  6405.5  218.53  6466.9  221.41  6507.9  226.12
  6539.9  232.94  6589.9  251.46  6600.1  253.07  6661.6  258.09  6835.7   266.6
#Mann= 5 ,-1 , 0
  4167.2     .05       0  4344.3     .16       0  4549.9     .16       0
    4999     .07       0    5005     .16       0
#XS Ineff= 2 , 0
                         5176.14          230.79
Permanent Ineff=
       F       F
Bank Sta=4932.5,5022.5
XS Rating Curve= 0 ,0
Exp/Cntr=0.3,0.1

Type RM Length L Ch R = 1 ,30040   ,478,478,478
BEGIN DESCRIPTION:
LITTLE ELKHART CREEK 17.0
END DESCRIPTION:
XS GIS Cut Line= 3
      3764399.59     10501810.15      3764799.61     10502710.19
      3764799.61     10504510.16
#Sta/Elev= 30
  4025.1  288.89  4123.6  270.83  4254.3  239.06  4259.7  240.37  4303.6  222.74
  4329.5  216.96  4381.5  214.27  4648.2  205.03  4834.9     207  4845.2  202.27
  4867.8  200.75  4873.7  199.75  4879.4  203.91  4897.2  201.15  4902.6  205.73
  4966.3  207.04  4977.9  207.27  4995.7  200.65  5001.1   200.8    5030  207.02
    5360  214.47    5540  215.78    5580  211.19    5640  210.66    6130  218.15
    6250  227.01    6330  246.62    6380  246.83    6410  252.77    6810  276.26
#Mann= 5 ,-1 , 0
  4025.1     .16       0  4303.6     .16       0  4867.8     .16       0
  4995.7     .07       0  5001.1     .16       0
#XS Ineff= 2 , 0
                          5348.3          224.76
Permanent Ineff=
       F       F
Bank Sta=4966.3,5030
XS Rating Curve= 0 ,0
Exp/Cntr=0.3,0.1

Type RM Length L Ch R = 1 ,29562   ,885,885,885
BEGIN DESCRIPTION:
LITTLE ELKHART CREEK 16.0
END DESCRIPTION:
XS GIS Cut Line= 4
      3764152.03     10501551.98      3764502.12      10502346.3
      3764480.26     10503530.44      3764269.37     10504446.17
#Sta/Elev= 30
  3884.3  303.05  3958.8  297.27  4011.3  286.33  4089.7  285.77  4138.9  285.26
  4162.2   280.8    4191  281.94    4232  277.53  4237.7  274.12  4275.8  269.24
  4307.6  257.77  4313.1  260.22  4336.4  249.68  4374.1  244.13  4406.4  231.28
  4449.4  220.48  4516.2  211.18  4638.2  207.95  4776.2  205.03  4976.3   206.8
  5003.3  199.79    5006  199.29  5009.3  199.79  5036.3  206.01  5656.4  207.02
  6131.4   224.5  6418.7  240.73  6496.1  252.29  6572.7  258.08  6876.4   270.8
#Mann= 5 ,-1 , 0
  3884.3     .05       0  4089.7     .16       0  4449.4     .16       0
  5003.3     .07       0  5009.3     .16       0
#XS Ineff= 2 , 0
                         5246.02          217.32
Permanent Ineff=
       F       F
Bank Sta=4976.3,5036.3
XS Rating Curve= 0 ,0
Exp/Cntr=0.3,0.1

Type RM Length L Ch R = 1 ,28677   ,767,767,767
BEGIN DESCRIPTION:
LITTLE ELKHART CREEK 15.0
END DESCRIPTION:
XS GIS Cut Line= 3
      3763958.04     10501574.91      3763969.15     10503658.21
      3763747.08     10504185.63
#Sta/Elev= 30
  3452.9  314.58  3610.2  303.38  3648.2  295.43  3718.2  270.25  3758.2  264.61
  3798.2  251.09  3858.2  242.72  3868.2  236.57  3918.2  229.66  3928.2  223.56
    3961  218.54  4038.2  208.61  4108.2   204.5  4908.2  205.24  4938.2  199.49
  4965.2  199.04    4968  198.54  4971.2  199.04  5018.2     200  5038.2  204.63
  5534.7  217.49  5651.7  216.99  5749.1  222.69  5781.2  225.67  5804.9  235.56
  5820.5  237.78  5842.3  248.57  5881.6  260.57  5903.3  262.47  6108.5  273.09
#Mann= 8 ,-1 , 0
  3452.9     .05       0  3610.2     .16       0    3961     .05       0
  4965.2     .03       0  4971.2     .05       0  5749.1     .16       0
  5842.3     .05       0  5903.3     .16       0
Bank Sta=4908.2,5038.2
XS Rating Curve= 0 ,0
Exp/Cntr=0.3,0.1

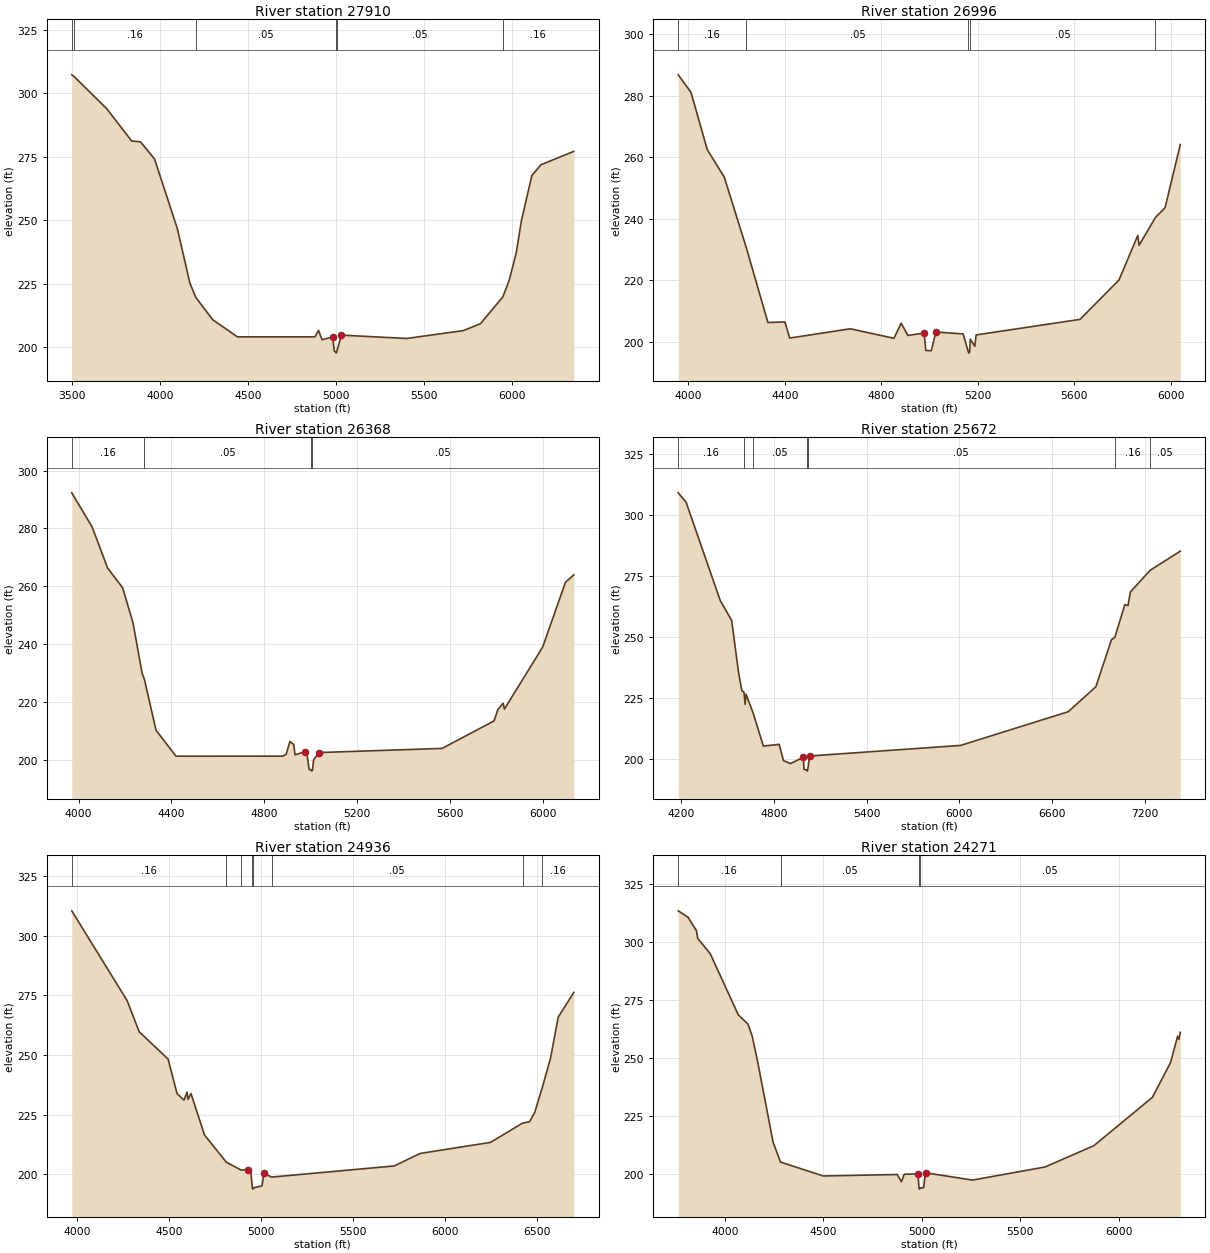
Type RM Length L Ch R = 1 ,27910   ,914,914,914
BEGIN DESCRIPTION:
LITTLE ELKHART CREEK 14.0
END DESCRIPTION:
XS GIS Cut Line= 3
      3763631.38     10501390.51      3763587.98     10503222.13
      3763518.62     10504236.43
#Sta/Elev= 30
  3499.4  307.37    3512  306.74  3699.1  293.91  3839.2  281.25  3889.2  280.93
  3969.2  274.13  4099.2  246.47  4169.3  225.21  4203.6  219.48  4299.3   210.7
  4439.3  203.95  4879.5  203.95  4899.5  206.47  4919.5  202.81  4979.5   203.9
  4989.5  198.26  4996.5  198.02  4999.2  197.52  5002.5  198.02  5029.5  204.62
  5399.8  203.31  5720.5   206.4  5818.2  209.13  5944.9  219.68  5981.1   226.2
  6021.2   237.1  6051.3  249.99  6110.1  267.61  6161.5  271.88  6348.2  277.16
#Mann= 6 ,-1 , 0
  3499.4     .05       0    3512     .16       0  4203.6     .05       0
  4996.5     .03       0  5002.5     .05       0  5944.9     .16       0
Bank Sta=4979.5,5029.5
XS Rating Curve= 0 ,0
Exp/Cntr=0.3,0.1

Type RM Length L Ch R = 1 ,26996   ,628,628,628
BEGIN DESCRIPTION:
LITTLE ELKHART CREEK 13.0
END DESCRIPTION:
XS GIS Cut Line= 3
      3763099.61     10501910.17      3762999.61     10502910.19
       3763399.6     10503910.16
#Sta/Elev= 30
  3957.7  286.78  4010.5   281.1  4078.3  262.45  4148.7  253.54  4240.3  230.53
  4329.6  206.33  4399.9   206.5    4420  201.26  4671.3  204.28  4852.2  201.18
  4882.3   206.1  4909.9  202.12  4977.5  202.88  4984.2  197.25  5007.1  197.15
    5026  203.23  5139.1  202.61  5160.3  196.87  5163.1  196.37  5166.3  196.87
  5168.7  200.91  5187.5   198.6  5192.9  202.28  5623.7  207.33  5785.3   220.1
  5863.4  234.61  5868.8   231.4  5936.4  240.43  5976.5  243.61  6039.7  264.14
#Mann= 5 ,-1 , 0
  3957.7     .16       0  4240.3     .05       0  5160.3     .03       0
  5166.3     .05       0  5936.4     .16       0
Bank Sta=4977.5,5026
XS Rating Curve= 0 ,0
Exp/Cntr=0.3,0.1

Type RM Length L Ch R = 1 ,26368   ,696,696,696
BEGIN DESCRIPTION:
LITTLE ELKHART CREEK 12.0
END DESCRIPTION:
XS GIS Cut Line= 3
       3763049.6     10501910.21      3762749.61     10502910.19
      3763249.59     10503910.15
#Sta/Elev= 30
  3970.9   292.3  4058.7  280.48  4124.9  266.34  4190.1   259.4  4234.5  247.33
  4273.6  229.94  4283.8  227.72  4333.7  210.15  4419.8  201.17  4879.2  201.18
    4894  201.84  4910.5   206.3    4927  205.18  4932.3  201.65  4973.1  202.66
  4983.6  201.89  4993.2  196.51  5001.5   196.5  5004.2     196  5007.5   196.5
  5012.3  199.97  5037.3  202.43  5565.5  203.86  5789.1  213.36  5805.9  217.31
  5828.3  219.48  5833.9  217.46  5998.8  238.94  6096.6  261.33  6132.9  263.93
#Mann= 4 ,-1 , 0
  3970.9     .16       0  4283.8     .05       0  5001.5     .03       0
  5007.5     .05       0
Bank Sta=4973.1,5037.3
XS Rating Curve= 0 ,0
Exp/Cntr=0.3,0.1

Type RM Length L Ch R = 1 ,25672   ,736,736,736
BEGIN DESCRIPTION:
LITTLE ELKHART CREEK 11.0
END DESCRIPTION:
XS GIS Cut Line= 3
      3762999.61     10501810.18      3762599.61     10502510.19
      3761199.64     10504510.15
#Sta/Elev= 30
  4181.1   308.9  4232.2  305.02  4452.5  264.84  4526.6  256.69  4570.5  235.71
  4592.1  227.96  4606.5  227.23  4613.7  222.31  4619.5  226.47    4665  218.86
  4731.8  205.21    4834  205.93  4861.4  199.29  4906.7  198.05  4990.4   200.6
  4994.7  195.68  5012.7  195.46  5015.4  194.96  5018.7  195.46  5030.5  201.16
    6007  205.48  6703.7  219.29  6882.4  229.51  6983.5  248.77  7005.1  249.72
  7069.9  263.14  7090.8  262.75  7105.6  268.31  7234.3  277.23  7428.6  285.02
#Mann= 7 ,-1 , 0
  4181.1     .16       0  4606.5     .12       0    4665     .05       0
  5012.7     .03       0  5018.7     .05       0  7005.1     .16       0
  7234.3     .05       0
Bank Sta=4990.4,5030.5
XS Rating Curve= 0 ,0
Exp/Cntr=0.3,0.1

Type RM Length L Ch R = 1 ,24936   ,665,665,665
BEGIN DESCRIPTION:
LITTLE ELKHART CREEK 10.0
END DESCRIPTION:
XS GIS Cut Line= 3
      3762949.63     10501760.18      3762049.61     10502260.19
      3760849.64     10503460.16
#Sta/Elev= 30
  3970.8  310.52  4271.7   272.8  4336.9  259.75  4493.6  248.33  4542.8  233.74
  4580.6  231.05  4596.6  234.43  4602.3  231.37  4618.3  233.81  4691.5  216.44
  4809.7  205.04  4890.4  201.71  4927.2  201.92  4943.2  200.97  4951.6   194.2
  4954.4   193.7  4957.6   194.2  5003.9  195.11  5014.5   200.3  5056.2  198.76
  5721.6  203.43  5863.1  208.68  6244.9  213.32  6418.8   221.4    6457  222.02
  6485.3  225.96  6526.1  236.39  6570.2  248.49  6612.6  265.91  6697.4  276.28
#Mann= 8 ,-1 , 0
  3970.8     .16       0  4809.7     .05       0  4890.4     .16       0
  4951.6     .07       0  4957.6     .16       0  5056.2     .05       0
  6418.8     .12       0  6526.1     .16       0
Bank Sta=4927.2,5014.5
XS Rating Curve= 0 ,0
Exp/Cntr=0.3,0.1

Type RM Length L Ch R = 1 ,24271   ,904,904,904
BEGIN DESCRIPTION:
LITTLE ELKHART CREEK 9.0
END DESCRIPTION:
XS GIS Cut Line= 3
      3762449.57     10501210.22      3761549.61     10502010.19
      3760549.59     10502910.21
#Sta/Elev= 30
  3762.8   313.3  3812.5  310.53  3855.2  304.78  3861.8  301.41  3925.4  294.84
  4067.6  268.56  4116.9  264.53  4137.8  259.57  4166.2  248.32  4244.4  213.76
  4282.1  205.19    4499   199.2  4874.5  199.83  4896.2  196.73  4910.5  199.95
  4980.7  200.08  4985.2  194.04    4988  193.54  4991.2  194.04  5009.1  194.16
  5016.6  199.55  5023.3  200.51  5257.3  197.43  5625.8  203.08  5873.2  212.22
  6170.6  233.04  6262.6  247.98  6298.4   259.3  6305.2  257.96  6312.3     261
#Mann= 4 ,-1 , 0
  3762.8     .16       0  4282.1     .05       0  4985.2     .03       0
  4991.2     .05       0
Bank Sta=4980.7,5023.3
XS Rating Curve= 0 ,0
Exp/Cntr=0.3,0.1

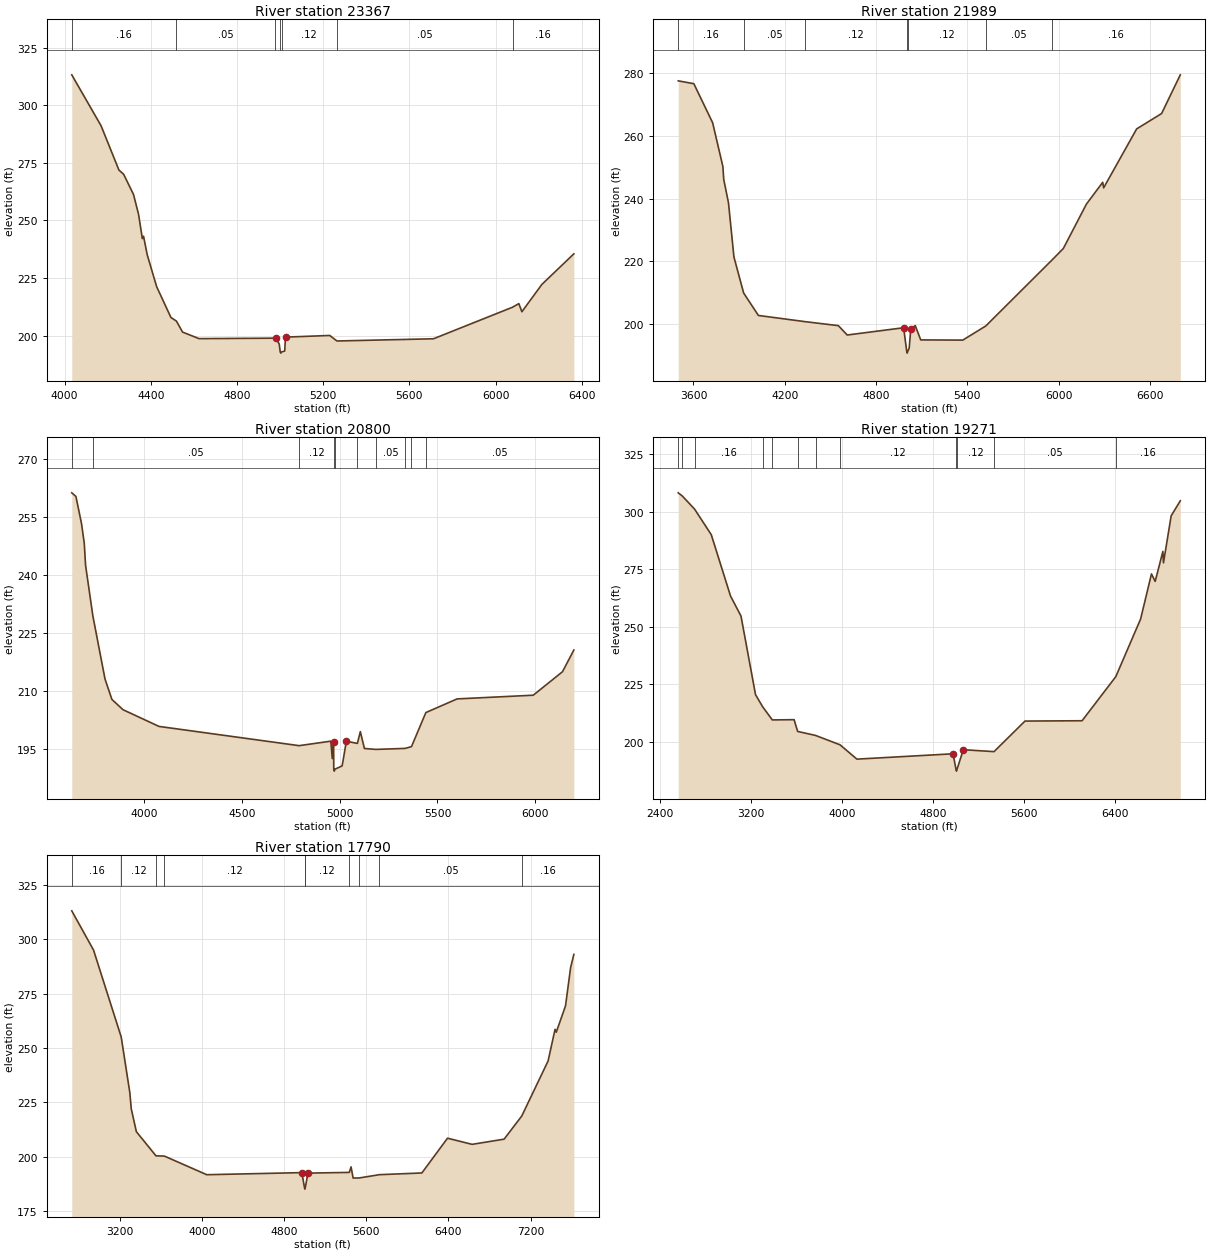
Type RM Length L Ch R = 1 ,23367   ,1378,1378,1378
BEGIN DESCRIPTION:
LITTLE ELKHART CREEK 8.0
END DESCRIPTION:
XS GIS Cut Line= 3
      3762299.62     10501060.18      3761399.61     10501460.19
      3760399.58     10502360.22
#Sta/Elev= 30
  4033.3  313.25  4169.4  291.12  4252.2  271.89  4274.1  270.08  4319.9  261.29
  4343.1  252.77  4360.9  242.16  4366.4  243.18  4383.5  235.13  4427.3  221.26
  4493.6  207.89    4519  206.32  4547.6  201.54  4624.2   198.7  4978.8  198.91
  4980.6   198.9  4996.3  196.32  5000.8  192.91  5003.6  192.41  5006.8  192.91
  5021.6  193.32  5025.3  199.36  5230.8  200.08    5264  197.68  5712.2  198.64
  6078.9  212.34  6108.3  213.91  6122.5  210.38  6215.2  222.24  6363.6  235.52
#Mann= 7 ,-1 , 0
  4033.3     .16       0    4519     .05       0  4978.8     .12       0
  5000.8     .07       0  5006.8     .12       0    5264     .05       0
  6078.9     .16       0
Bank Sta=4980.6,5025.3
XS Rating Curve= 0 ,0
Exp/Cntr=0.3,0.1

Type RM Length L Ch R = 1 ,21989   ,1189,1189,1189
BEGIN DESCRIPTION:
LITTLE ELKHART CREEK 7.0
END DESCRIPTION:
XS GIS Cut Line= 4
      3762043.72     10500603.19      3760904.82     10501283.76
      3760613.15     10501408.76      3759661.79     10502762.89
#Sta/Elev= 30
    3500  277.53  3602.6  276.62  3726.1  264.17  3793.3  250.24  3799.1   246.1
  3830.2  238.65  3865.9  221.41  3929.8  209.91  4026.7  202.76  4335.3  200.77
    4552  199.51  4610.4  196.52    4981  198.84  5001.6  191.25  5004.3  190.75
  5007.6  191.25  5017.4  192.32  5028.1   198.4  5057.2  199.54  5093.5  194.96
  5369.8   194.9    5521  199.41  5955.6  220.41  6030.3  224.09  6181.9  238.23
  6289.1  245.19  6295.2  243.42  6512.1  262.21    6676  267.11    6799  279.45
#Mann= 7 ,-1 , 0
    3500     .16       0  3929.8     .05       0  4335.3     .12       0
  5001.6     .07       0  5007.6     .12       0    5521     .05       0
  5955.6     .16       0
Bank Sta=4981,5028.1
XS Rating Curve= 0 ,0
Exp/Cntr=0.3,0.1

Type RM Length L Ch R = 1 ,20800   ,1529,1529,1529
BEGIN DESCRIPTION:
LITTLE ELKHART CREEK 6.0
END DESCRIPTION:
XS GIS Cut Line= 3
      3761199.58     10499960.22      3760299.61     10500960.19
       3759599.6     10501960.21
#Sta/Elev= 30
    3631  261.36  3652.3  260.42  3680.7  253.41  3694.9  248.28  3701.6  242.56
  3738.8  229.46    3801  213.08  3836.1  207.81  3892.9  205.14  4076.8  200.81
  4793.1  195.82    4955  196.99  4962.5  192.47  4969.2  196.74    4970  189.72
  4972.7  189.22    4976  189.72  5012.9  190.58  5034.3  196.96  5090.8  196.41
  5105.8  199.46  5126.7  195.09  5184.8  194.85  5334.5  195.11  5367.2  195.57
  5440.7   204.4  5600.2  207.94  5989.5   208.9    6139  214.99    6197  220.61
#Mann= 10 ,-1 , 0
    3631     .16       0  3738.8     .05       0  4793.1     .12       0
    4970     .07       0    4976     .12       0  5090.8     .07       0
  5184.8     .05       0  5334.5     .12       0  5367.2     .07       0
  5440.7     .05       0
Bank Sta=4969.2,5034.3
XS Rating Curve= 0 ,0
Exp/Cntr=0.3,0.1

Type RM Length L Ch R = 1 ,19271   ,1481,1481,1481
BEGIN DESCRIPTION:
LITTLE ELKHART CREEK 5.0
END DESCRIPTION:
XS GIS Cut Line= 3
      3761349.62     10499110.18      3759549.61     10500710.19
      3759349.61     10502710.18
#Sta/Elev= 30
  2556.8  308.29  2591.8  306.95    2700  301.25  2847.4   290.1  3017.1  263.38
  3109.1  254.68  3237.1  220.47  3299.6  215.22  3384.7  209.49  3576.6  209.59
  3607.7  204.48  3765.8  202.73  3980.7  198.66  4129.3  192.43  4975.2  194.75
  5002.3  187.71  5005.1  187.21  5008.3  187.71  5065.6  196.53  5335.8  195.69
  5608.3  208.99  6110.8  209.13  6407.6  228.33  6625.9  253.41  6721.3  273.01
    6754  269.77  6821.8  282.79  6826.9  277.83  6894.7  298.29  6975.1  304.83
#Mann= 12 ,-1 , 0
  2556.8     .16       0  2591.8      .1       0    2700     .16       0
  3299.6     .05       0  3384.7     .07       0  3607.7     .12       0
  3765.8     .05       0  3980.7     .12       0  5002.3     .07       0
  5008.3     .12       0  5335.8     .05       0  6407.6     .16       0
Bank Sta=4975.2,5065.6
XS Rating Curve= 0 ,0
Exp/Cntr=0.3,0.1

Type RM Length L Ch R = 1 ,17790   ,855,855,855
BEGIN DESCRIPTION:
LITTLE ELKHART CREEK 4.0
END DESCRIPTION:
XS GIS Cut Line= 3
      3760749.61     10498410.18      3759144.42     10499925.06
      3759091.03     10502611.28
#Sta/Elev= 30
  2727.9  313.03  2940.1  295.01  3209.7  255.11  3293.7  229.58  3307.8  222.08
  3357.6  211.58  3548.9  200.49  3630.4  200.38  4043.8  191.82  4970.2  192.78
  4997.2   185.7  4999.9   185.2  5003.2   185.7  5030.2  192.56    5433  192.88
  5450.3  195.42  5470.3  190.29  5531.1  190.34  5727.2  191.84  6140.4  192.62
  6390.5  208.59  6630.5  205.77    6942  208.15  7114.2  218.78  7370.7  244.05
  7438.7  258.61  7450.7  257.28  7540.7   269.4  7590.7  287.08  7621.8     293
#Mann= 10 ,-1 , 0
  2727.9     .16       0  3209.7     .12       0  3548.9     .16       0
  3630.4     .12       0  4997.2     .07       0  5003.2     .12       0
    5433     .05       0  5531.1     .16       0  5727.2     .05       0
  7114.2     .16       0
Bank Sta=4970.2,5030.2
XS Rating Curve= 0 ,0
Exp/Cntr=0.3,0.1