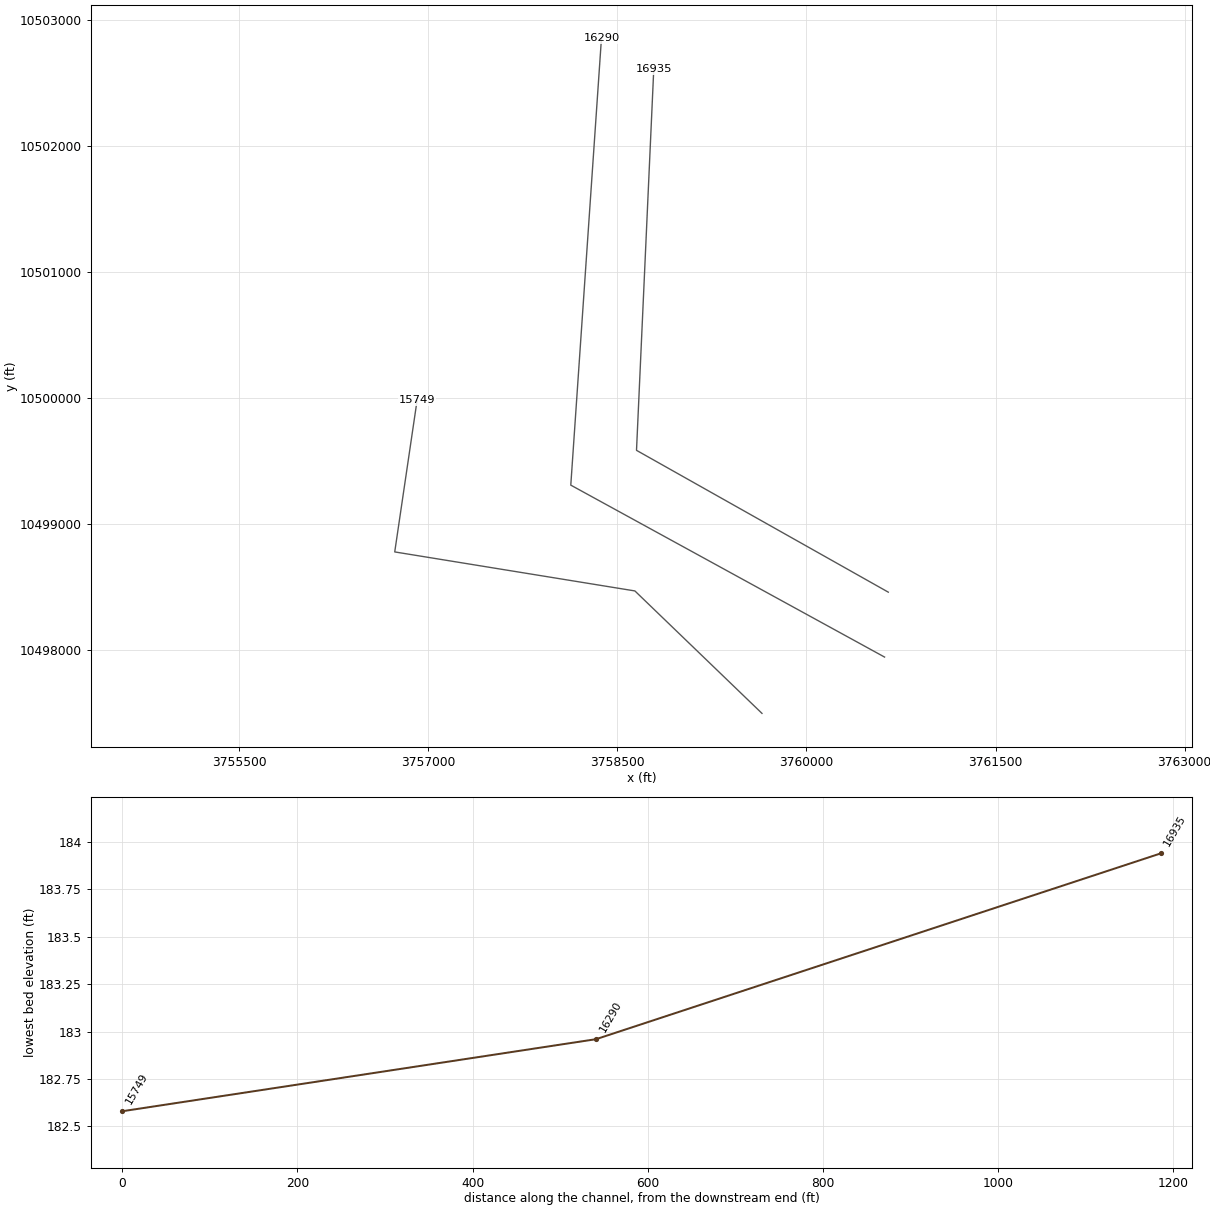
HEC-RAS study LITTLE ELKHART CREEK.prj: LITTLE ELKHART CREEK Base Level Engineering

--- LITTLE ELKHART CREEK.g01 (geometry) --- (continued)

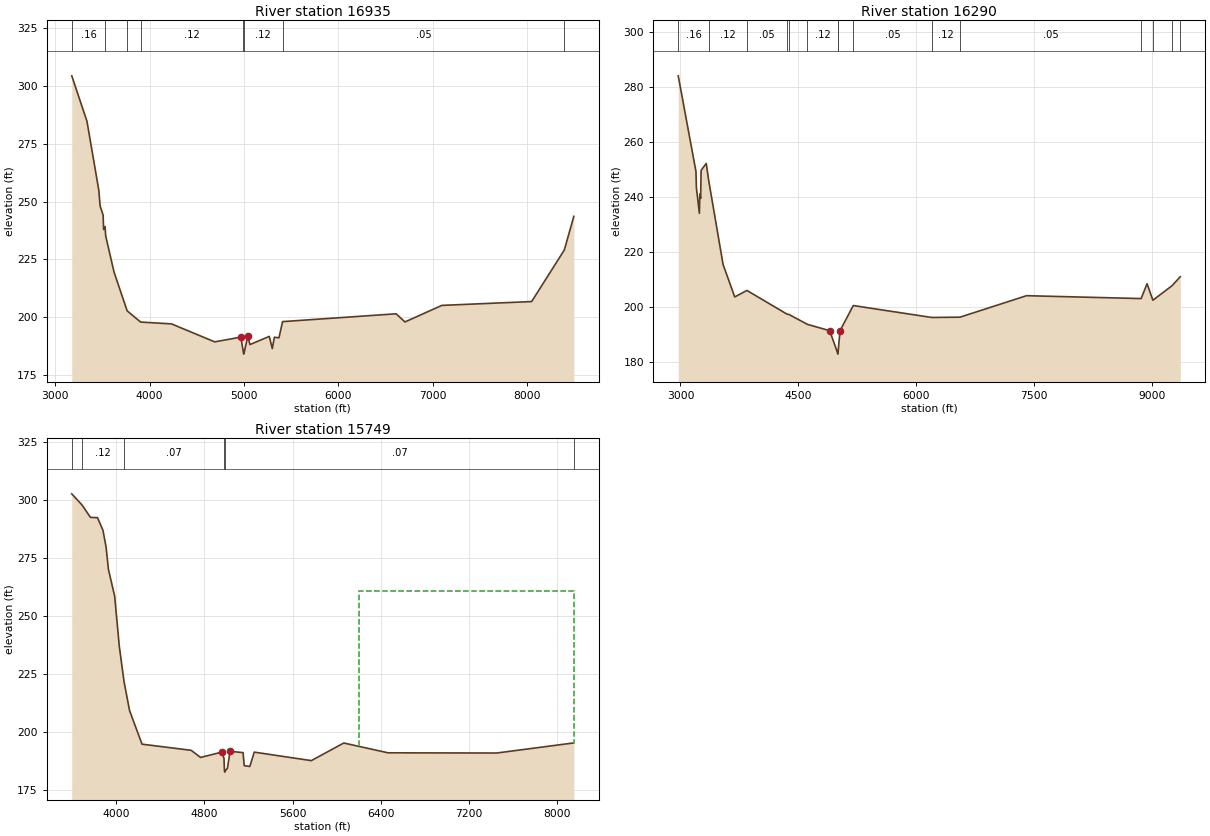
Type RM Length L Ch R = 1 ,16935   ,645,645,645
BEGIN DESCRIPTION:
LITTLE ELKHART CREEK 3.0
END DESCRIPTION:
XS GIS Cut Line= 3
      3760649.63     10498460.18      3758652.88     10499584.94
      3758789.67      10502606.5
#Sta/Elev= 30
  3176.9  304.48  3337.6  284.83  3463.9  254.79  3476.7  248.16  3508.6  244.21
  3514.3  237.91    3530  239.17    3536  235.16  3624.5  219.48  3763.5  202.67
  3906.5  197.83  4232.8  197.04  4690.5  189.25  4967.4  191.31  4995.3  184.44
  4998.1  183.94  5001.3  184.44  5041.6  191.78  5063.3  188.08  5268.5  191.62
  5300.2  186.33    5322  191.24  5371.1  191.03  5408.9  198.02  6611.3  201.41
  6705.2  197.88  7095.6  205.05  8046.5  206.71    8392     229  8493.3  243.63
#Mann= 8 ,-1 , 0
  3176.9     .16       0    3530     .12       0  3763.5     .16       0
  3906.5     .12       0  4995.3     .07       0  5001.3     .12       0
  5408.9     .05       0    8392     .16       0
Bank Sta=4967.4,5041.6
XS Rating Curve= 0 ,0
Exp/Cntr=0.3,0.1

Type RM Length L Ch R = 1 ,16290   ,541,541,541
BEGIN DESCRIPTION:
LITTLE ELKHART CREEK 2.0
END DESCRIPTION:
XS GIS Cut Line= 3
      3760620.05     10497945.54      3758131.73     10499309.01
      3758374.89     10502852.19
#Sta/Elev= 30
  2971.4  284.01  3196.9  249.31  3202.6  243.36  3240.5  234.07  3246.2  241.09
  3256.6  239.51  3262.3  249.68  3327.8   252.2  3357.9  246.21    3542  215.51
  3690.3  203.72  3845.5  206.08  4354.6   197.5  4379.5  197.38    4615  193.77
    4899  191.47  4998.6  183.46  5001.4  182.96  5004.6  183.46  5030.5  191.48
  5198.8   200.6    6197  196.27  6556.6  196.38  7403.7  204.18  8861.7  203.13
  8937.3  208.53  9011.2  202.54  9256.2  207.82  9354.8  210.94  9360.3  211.05
#Mann= 15 ,-1 , 0
  2971.4     .16       0  3357.9     .12       0  3845.5     .05       0
  4354.6     .16       0  4379.5     .05       0    4615     .12       0
  4998.6     .07       0  5004.6     .12       0  5198.8     .05       0
    6197     .12       0  6556.6     .05       0  8861.7     .16       0
  9011.2     .12       0  9256.2     .16       0  9354.8     .05       0
Bank Sta=4899,5030.5
XS Rating Curve= 0 ,0
Exp/Cntr=0.3,0.1

Type RM Length L Ch R = 1 ,15749   ,0,0,0
BEGIN DESCRIPTION:
LITTLE ELKHART CREEK 1.0
END DESCRIPTION:
XS GIS Cut Line= 4
      3759647.83     10497498.99        3758640.       10498470.
      3756735.56     10498779.34      3756912.93     10499981.92
#Sta/Elev= 30
  3600.5  302.79  3694.6   297.9  3769.8  292.62  3833.6  292.48    3883  287.03
  3911.3  279.84  3932.4  270.22    3989   258.6  4031.4   236.8  4073.9  221.71
  4123.5  209.25  4236.7  194.66    4682     192  4766.9  188.93  4958.1   191.2
  4979.2   188.6  4983.4  183.08  4986.6  182.58  4989.4  183.08  5010.5  184.25
  5034.1  191.59  5152.2     191  5162.5  185.37  5213.1  185.03  5253.7  191.22
  5770.4  187.55  6064.2  195.16  6465.6  190.927448.831 190.8328148.064195.2014
#Mann= 6 ,-1 , 0
  3600.5     .16       0  3694.6     .12       0  4073.9     .07       0
  4983.4     .05       0  4989.4     .07       08148.064     .05       0
#XS Ineff= 2 , 0
                         6200.31          260.63
Permanent Ineff=
       F       F
Bank Sta=4958.1,5034.1
XS Rating Curve= 0 ,0
Exp/Cntr=0.3,0.1

Chan Stop Cuts=-1
Use User Specified Reach Order=0
Composite Channel Slope=5