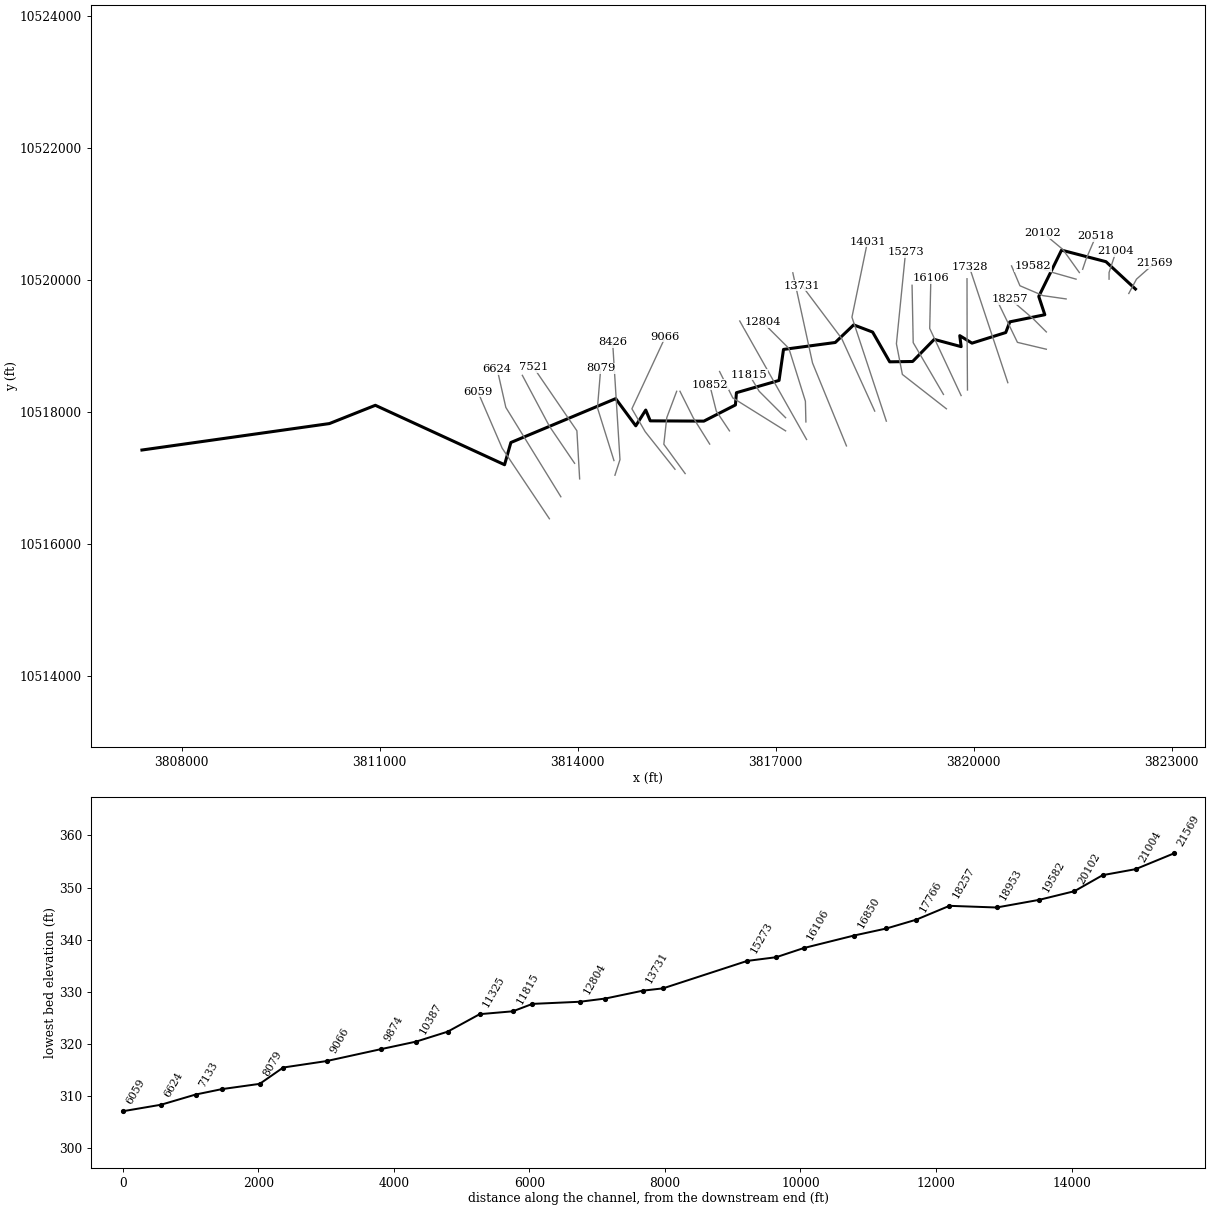
--- MAYES BRANCH.prj (project) ---

Proj Title=MAYES BRANCH Base Level Engineering
Current Plan=p01
Default Exp/Contr=0.3,0.1
English Units
Geom File=g01
Flow File=f01
Plan File=p01
Y Axis Title=Elevation
X Axis Title(PF)=Main Channel Distance
X Axis Title(XS)=Station
BEGIN DESCRIPTION:
MAYES BRANCH
END DESCRIPTION:
DSS Export Rating Curves= 0
DSS Export Rating Curve Sorted= 0
DSS Export Volume Flow Curves= 0
DXF OffsetX= 0
DXF OffsetY= 0
DXF ScaleX= 1
DXF ScaleY= 10

--- MAYES BRANCH.p01 (plan) ---

Plan Title=Multiple Run
Short Identifier=Multiple
Geom File=g01
Flow File=f01
Subcritical Flow
K Sum by GR= 0
Std Step Tol= 0.01
Critical Tol= 0.01
Num of Std Step Trials= 20
Max Error Tol= 0.3
Flow Tol Ratio= 0.001
Split Flow NTrial= 30
Split Flow Tol= 0.02
Split Flow Ratio= 0.02
Log Output Level= 0
Friction Slope Method= 1
Unsteady Friction Slope Method= 2
Unsteady Bridges Friction Slope Method= 1
Parabolic Critical Depth
Global Vel Dist=  1 , 1 , 1
Global Log Level= 0
CheckData=True
Encroach Param= -1, 0, 0, 0
BEGIN DESCRIPTION:
Multiple Run
END DESCRIPTION:

--- MAYES BRANCH.f01 (steady flow) ---

Flow Title=Multiple
Program Version=4.10
Number of Profiles= 7
Profile Names=10-year,25-year,50-year,1pct_min,100-year,1pct_plu,500-year
River Rch & RM=MAYES BRANCH,Reach-1         ,21569
    1039    1447    1793    1630    2205    2982    3348
River Rch & RM=MAYES BRANCH,Reach-1         ,14031
    1175    1637    2030    1845    2495    3374    3785
River Rch & RM=MAYES BRANCH,Reach-1         ,9066
    1444    2027    2524    2303    3114    4212    4761
River Rch & RM=MAYES BRANCH,Reach-1         ,3890
    1537    2161    2695    2461    3328    4501    5099
Boundary for River Rch & Prof#=MAYES BRANCH,Reach-1         , 1
Up Type= 0
Dn Type= 3
Dn Slope=0.003
Boundary for River Rch & Prof#=MAYES BRANCH,Reach-1         , 2
Up Type= 0
Dn Type= 3
Dn Slope=0.003
Boundary for River Rch & Prof#=MAYES BRANCH,Reach-1         , 3
Up Type= 0
Dn Type= 3
Dn Slope=0.003
Boundary for River Rch & Prof#=MAYES BRANCH,Reach-1         , 4
Up Type= 0
Dn Type= 3
Dn Slope=0.003
Boundary for River Rch & Prof#=MAYES BRANCH,Reach-1         , 5
Up Type= 0
Dn Type= 3
Dn Slope=0.003
Boundary for River Rch & Prof#=MAYES BRANCH,Reach-1         , 6
Up Type= 0
Dn Type= 3
Dn Slope=0.003
Boundary for River Rch & Prof#=MAYES BRANCH,Reach-1         , 7
Up Type= 0
Dn Type= 3
Dn Slope=0.003
DSS Import GetInterval= 0
DSS Import GetPeak= 0
DSS Import FillOption= 0

--- MAYES BRANCH.g01 (geometry) ---

Geom Title=Existing Conditions
Program Version=4.10

River Reach=MAYES BRANCH    ,Reach-1
Reach XY= 30
      3822449.61     10519860.19       3822002.5       10520275.
      3821329.75       10520450.      3820984.75       10519748.
       3821076.5       10519471.       3820546.5       10519363.
       3820484.5       10519201.      3819973.25       10519040.
      3819787.75       10519154.      3819809.25       10518987.
        3819401.       10519097.        3819074.       10518762.
       3818726.5       10518757.        3818468.       10519208.
        3818181.       10519317.        3817902.       10519050.
        3817118.       10518945.      3817050.75       10518475.
        3816405.       10518289.       3816389.5       10518103.
       3815911.5       10517858.       3815099.5       10517862.
        3815031.       10518026.        3814880.       10517787.
      3814575.75       10518199.      3812988.25       10517534.
      3812892.25       10517197.        3810935.       10518098.
      3810239.25       10517821.      3807399.25       10517420.

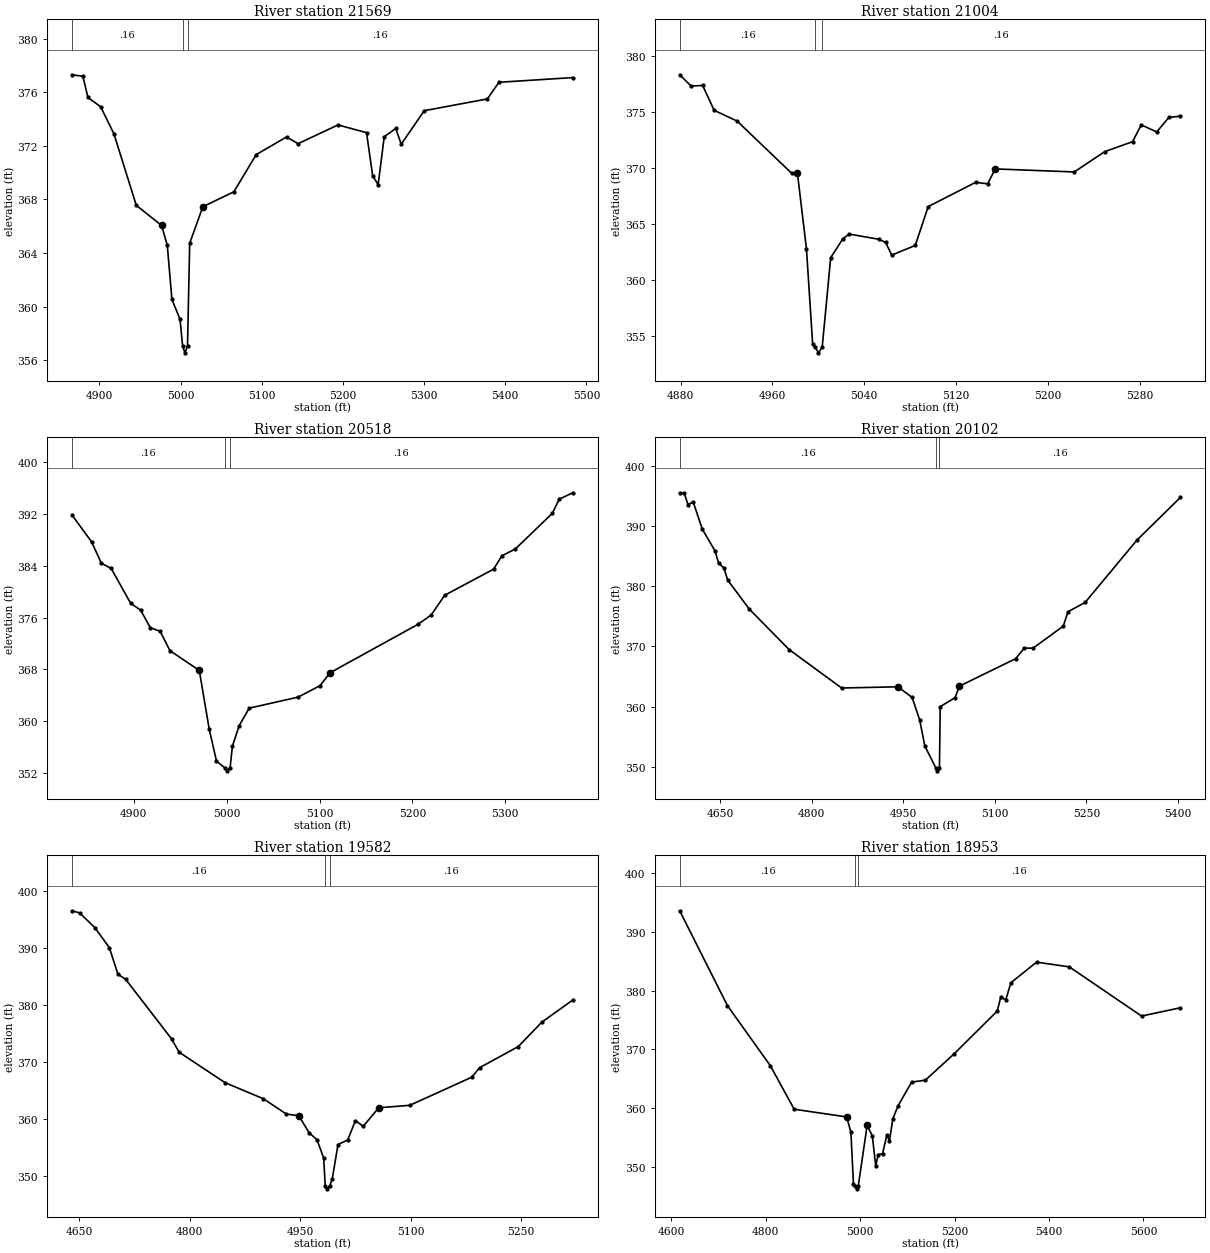
Type RM Length L Ch R = 1 ,21569   ,565,565,565
BEGIN DESCRIPTION:
MAYES BRANCH 38.0
END DESCRIPTION:
XS GIS Cut Line= 3
      3822348.54     10519792.89      3822464.87     10520009.91
       3822742.1     10520255.95
#Sta/Elev= 30
  4866.2   377.3  4879.6  377.19  4885.8  375.61  4901.5  374.91  4917.8   372.9
  4945.4  367.56  4976.6  366.06  4983.6  364.57  4989.3  360.54  4999.3  359.06
  5002.5  357.06  5005.3  356.56  5008.5  357.06  5011.2  364.73  5027.4  367.46
  5065.6  368.57  5093.2  371.35  5130.5  372.66  5144.7  372.16    5194  373.56
  5229.1  372.98  5236.7  369.75  5243.4  369.11  5250.9  372.68  5265.1   373.3
  5271.8  372.12  5300.2  374.62    5378   375.5  5392.2  376.74  5483.1  377.09
#Mann= 3 ,-1 , 0
  4866.2     .16       0  5002.5     .07       0  5008.5     .16       0
Bank Sta=4976.6,5027.4
XS Rating Curve= 0 ,0
Exp/Cntr=0.3,0.1

Type RM Length L Ch R = 1 ,21004   ,486,486,486
BEGIN DESCRIPTION:
MAYES BRANCH 37.0
END DESCRIPTION:
XS GIS Cut Line= 3
      3822049.61     10520010.18      3822049.61     10520110.19
      3822154.55     10520429.79
#Sta/Elev= 30
  4879.2  378.35  4889.2  377.34  4899.2   377.4  4909.2  375.18  4929.2  374.22
  4976.7  369.57  4981.8  369.57  4989.7   362.8  4995.1   354.3  4997.4  354.04
  5000.1  353.54  5003.4  354.04  5010.8  362.03  5021.3   363.7  5026.9  364.14
  5052.9  363.67  5058.7  363.39    5064  362.26  5084.5  363.12  5095.8  366.59
  5137.1  368.75  5147.6  368.62  5154.2  369.95  5223.1  369.68  5249.6  371.49
  5273.9  372.38  5281.5  373.88    5295  373.25  5305.5  374.54  5315.6  374.66
#Mann= 3 ,-1 , 0
  4879.2     .16       0  4997.4     .07       0  5003.4     .16       0
Bank Sta=4981.8,5154.2
XS Rating Curve= 0 ,0
Exp/Cntr=0.3,0.1

Type RM Length L Ch R = 1 ,20518   ,416,416,416
BEGIN DESCRIPTION:
MAYES BRANCH 36.0
END DESCRIPTION:
XS GIS Cut Line= 3
      3821649.61      10520160.2      3821699.61     10520310.19
      3821849.61      10520660.2
#Sta/Elev= 30
  4833.6  391.78  4854.7  387.65  4865.2  384.36  4875.8  383.55  4896.8  378.17
  4907.4  377.15  4917.9  374.44  4928.5  373.87    4939   370.9  4970.6  367.85
  4981.2  358.87  4989.1   353.9  4997.8  352.89  5000.5  352.39  5003.8  352.89
  5006.2  356.16  5013.5  359.34  5024.3  362.04  5076.9  363.74  5100.5   365.5
  5111.4   367.5  5205.7  374.93  5220.2  376.38  5234.7  379.43  5287.3  383.44
  5296.3   385.5  5310.8  386.56  5350.7  392.06    5358  394.22  5372.5  395.21
#Mann= 3 ,-1 , 0
  4833.6     .16       0  4997.8     .07       0  5003.8     .16       0
Bank Sta=4970.6,5111.4
XS Rating Curve= 0 ,0
Exp/Cntr=0.3,0.1

Type RM Length L Ch R = 1 ,20102   ,520,520,520
BEGIN DESCRIPTION:
MAYES BRANCH 35.0
END DESCRIPTION:
XS GIS Cut Line= 3
      3821599.59     10520110.22      3821349.61     10520460.19
       3821049.6     10520710.19
#Sta/Elev= 30
  4583.5  395.44  4590.8  395.51    4597  393.53  4605.6     394  4620.3  389.51
  4641.2  385.88  4647.4  383.79    4656  383.02  4662.1  381.01  4697.7  376.17
  4762.9  369.46  4848.9  363.08  4941.1  363.28  4964.4  361.52  4976.7  357.82
  4985.3  353.44  5003.2  349.82    5006  349.32  5009.2  349.82  5010.5  359.98
  5035.1   361.5  5041.6  363.37    5134  367.95  5148.3  369.71  5162.6   369.7
  5212.1  373.35  5219.9  375.75  5247.9  377.29  5333.1  387.67  5404.1  394.73
#Mann= 3 ,-1 , 0
  4583.5     .16       0  5003.2     .07       0  5009.2     .16       0
Bank Sta=4941.1,5041.6
XS Rating Curve= 0 ,0
Exp/Cntr=0.3,0.1

Type RM Length L Ch R = 1 ,19582   ,629,629,629
BEGIN DESCRIPTION:
MAYES BRANCH 34.0
END DESCRIPTION:
XS GIS Cut Line= 3
      3821549.65     10520010.18      3821199.61     10520110.19
      3820899.59      10520210.2
#Sta/Elev= 30
    4640   396.6  4650.4  396.22  4671.2  393.61  4690.7  390.12  4702.4  385.44
  4712.8  384.55  4775.2  374.07  4785.6   371.7    4848  366.34    4900  363.52
  4931.2  360.82  4948.1  360.53  4962.4  357.48  4972.8  356.32  4981.9  353.11
  4984.1  348.16  4986.9  347.66  4990.1  348.16  4993.6   349.4  5001.4  355.45
  5014.6  356.26  5025.1  359.67  5035.7  358.67  5056.8  361.93  5098.9  362.36
  5183.2  367.31  5193.8  368.98  5246.5  372.71  5278.1  376.97  5320.3  380.88
#Mann= 3 ,-1 , 0
    4640     .16       0  4984.1     .07       0  4990.1     .16       0
Bank Sta=4948.1,5056.8
XS Rating Curve= 0 ,0
Exp/Cntr=0.3,0.1

Type RM Length L Ch R = 1 ,18953   ,696,696,696
BEGIN DESCRIPTION:
MAYES BRANCH 33.0
END DESCRIPTION:
XS GIS Cut Line= 4
      3821399.64     10519710.18      3821049.61     10519760.19
      3820699.61     10519910.19      3820572.38     10520210.69
#Sta/Elev= 30
  4617.5  393.63  4718.5  377.46  4809.5   367.2    4860  359.77  4971.1  358.46
  4980.2  355.86  4985.6  346.95  4989.8  346.69  4992.6  346.19  4995.8  346.69
  5014.6  357.02  5025.5  355.25  5032.7  350.16  5038.2  352.02  5047.2  352.18
  5056.3  355.37  5061.8  354.37    5069   358.1  5079.9  360.34  5108.9   364.4
  5137.9  364.73  5199.6  369.28  5290.2  376.52  5297.5  378.84  5308.4  378.46
  5319.2  381.36  5373.6  384.87  5442.9  384.06  5595.9  375.67  5678.2  377.08
#Mann= 3 ,-1 , 0
  4617.5     .16       0  4989.8     .07       0  4995.8     .16       0
Bank Sta=4971.1,5014.6
XS Rating Curve= 0 ,0
Exp/Cntr=0.3,0.1

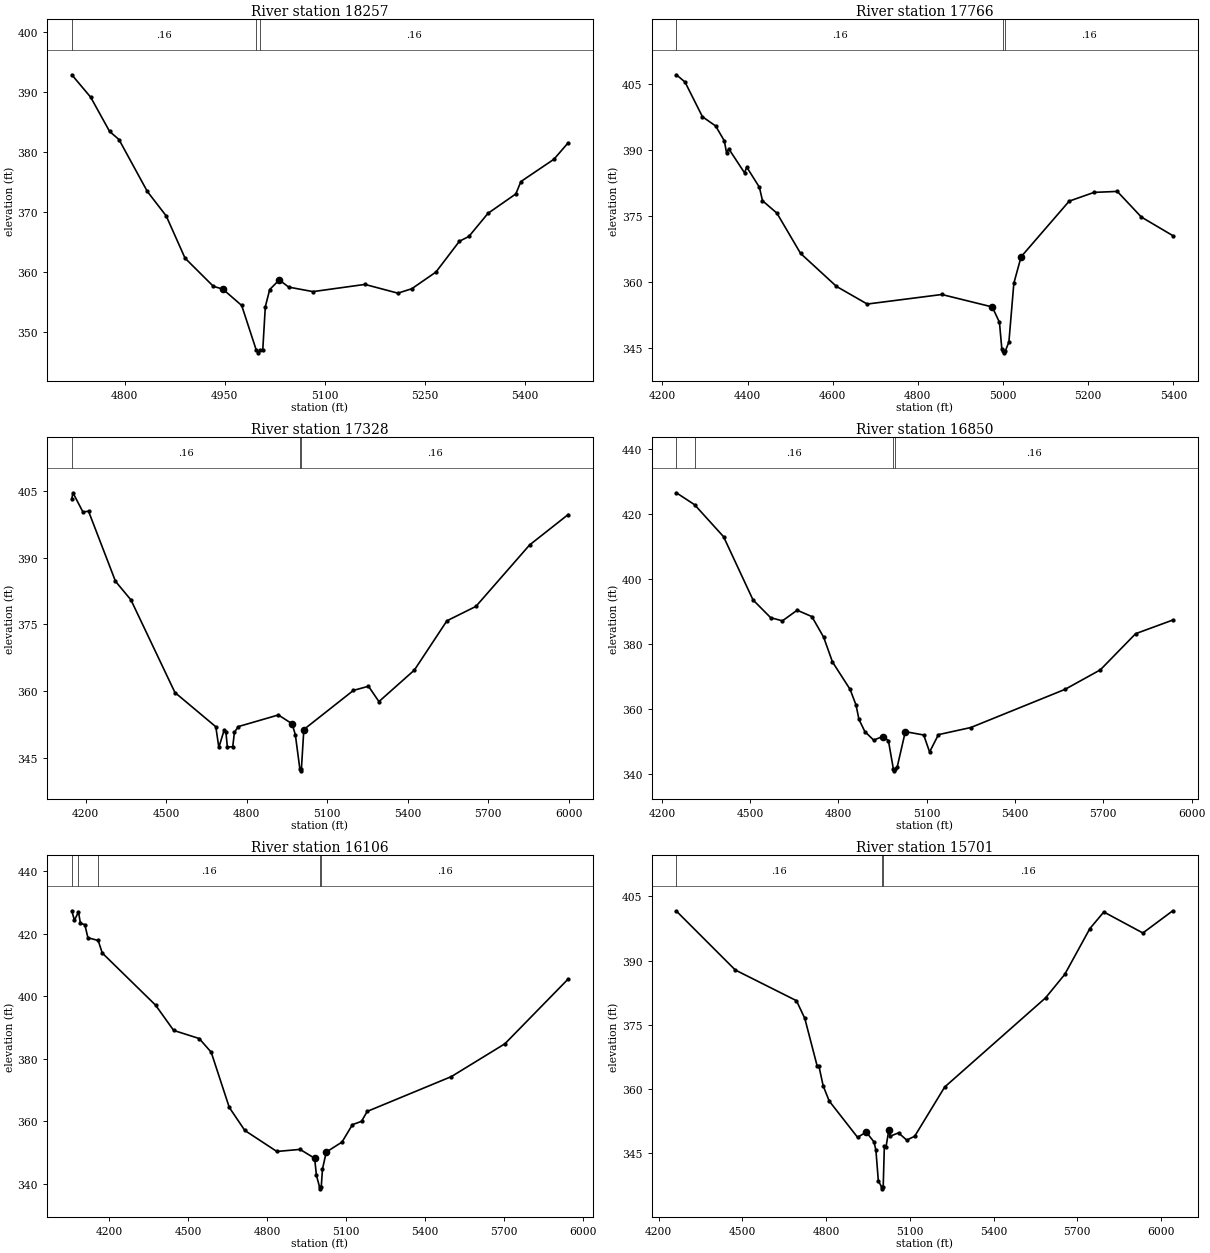
Type RM Length L Ch R = 1 ,18257   ,491,491,491
BEGIN DESCRIPTION:
MAYES BRANCH 32.0
END DESCRIPTION:
XS GIS Cut Line= 3
      3821099.63     10519210.16      3820899.61     10519410.19
      3820549.58     10519710.22
#Sta/Elev= 30
  4720.6  392.88  4748.9  389.14  4777.2  383.44  4791.3  382.08  4833.8  373.42
  4862.1  369.34  4890.3   362.3  4932.8   357.6  4946.9  357.14  4975.2  354.41
  4996.9  347.01  4999.7  346.51  5002.9  347.01  5006.8  347.01  5010.6  354.19
  5017.2  357.07  5031.5  358.67  5045.7  357.47    5082  356.72  5159.9  357.92
  5209.3  356.46  5230.1   357.2  5266.3  359.98  5301.5  365.12  5315.7  365.92
  5344.3  369.77    5386  373.01  5393.7  375.08  5443.1  378.79  5464.5  381.54
#Mann= 3 ,-1 , 0
  4720.6     .16       0  4996.9     .07       0  5002.9     .16       0
Bank Sta=4946.9,5031.5
XS Rating Curve= 0 ,0
Exp/Cntr=0.3,0.1

Type RM Length L Ch R = 1 ,17766   ,438,438,438
BEGIN DESCRIPTION:
MAYES BRANCH 31.0
END DESCRIPTION:
XS GIS Cut Line= 3
      3821099.26     10518947.83      3820661.74       10519052.
      3820349.86     10519696.56
#Sta/Elev= 30
  4232.8  407.05    4253  405.42  4294.1  397.51    4325  395.42  4345.5  392.03
  4350.8  389.22  4355.9  390.22  4392.9  384.76  4398.1  386.06  4427.8  381.49
  4435.1  378.42  4468.9  375.61  4524.5  366.45  4608.8  358.95  4681.1  354.94
  4856.2  357.11  4974.7  354.28  4991.6  350.79  4997.3  344.62  4999.8  344.35
  5002.6  343.85  5005.8  344.35  5013.8  346.33  5025.4  359.66  5042.4  365.68
  5155.4  378.33  5213.8  380.32  5268.3  380.54  5324.9  374.71  5398.6   370.5
#Mann= 3 ,-1 , 0
  4232.8     .16       0  4999.8     .07       0  5005.8     .16       0
Bank Sta=4974.7,5042.4
XS Rating Curve= 0 ,0
Exp/Cntr=0.3,0.1

Type RM Length L Ch R = 1 ,17328   ,478,478,478
BEGIN DESCRIPTION:
MAYES BRANCH 30.0
END DESCRIPTION:
XS GIS Cut Line= 2
       3820515.9     10518440.91      3819933.02     10520196.47
#Sta/Elev= 30
  4148.8  403.23  4153.1  404.53  4190.2  400.23  4211.2  400.39  4311.5  384.69
  4369.3  380.49  4533.2  359.73  4685.4  352.06  4696.8  347.42    4717   351.4
  4723.2   350.8  4728.5  347.47  4748.6   347.6  4754.9  350.85  4769.7   352.1
  4918.5   354.7  4969.9  352.72  4981.9  350.23  4998.5  342.67  5001.3  342.17
  5004.5  342.67  5013.5  351.44  5198.3  360.21  5254.4  361.14  5293.3   357.7
  5425.3  364.76  5546.7  375.82  5654.8  379.05    5855  392.84  5998.6  399.65
#Mann= 3 ,-1 , 0
  4148.8     .16       0  4998.5     .07       0  5004.5     .16       0
Bank Sta=4969.9,5013.5
XS Rating Curve= 0 ,0
Exp/Cntr=0.3,0.1

Type RM Length L Ch R = 1 ,16850   ,744,744,744
BEGIN DESCRIPTION:
MAYES BRANCH 29.0
END DESCRIPTION:
XS GIS Cut Line= 3
      3819904.79     10518329.77      3819899.61     10519110.19
      3819897.85     10520016.25
#Sta/Elev= 30
  4249.3  426.46  4311.3  422.78  4409.7  412.93  4509.7  393.47  4569.7  387.99
  4609.7  387.02  4659.7  390.29  4709.7  388.33  4749.7  381.98  4779.7  374.35
  4839.7  365.89  4859.7  361.09  4869.7  356.66  4889.7  352.92  4919.7  350.27
  4949.7  351.38  4969.7  350.16  4986.7  341.32  4989.5  340.82  4992.7  341.32
  4999.7  342.03  5027.2  352.89  5089.7  351.86  5109.7  346.62  5139.7  351.97
  5249.7  354.16  5569.7  365.91  5689.7  371.92  5809.7  383.06  5935.8  387.26
#Mann= 4 ,-1 , 0
  4249.3      .1       0  4311.3     .16       0  4986.7     .07       0
  4992.7     .16       0
Bank Sta=4949.7,5027.2
XS Rating Curve= 0 ,0
Exp/Cntr=0.3,0.1

Type RM Length L Ch R = 1 ,16106   ,405,405,405
BEGIN DESCRIPTION:
MAYES BRANCH 28.0
END DESCRIPTION:
XS GIS Cut Line= 3
      3819808.46     10518245.46      3819332.78     10519262.81
      3819350.14     10520023.25
#Sta/Elev= 30
  4059.1  427.31    4069  424.28  4084.5  426.92  4091.9  423.29  4108.5  422.89
  4120.2  418.69  4159.2  417.81  4174.7  413.81    4377  397.14  4445.6  389.06
  4542.5  386.47  4588.1  382.09  4656.7  364.44  4715.6  357.08  4837.1  350.36
  4925.4  351.02  4980.6  348.18  4987.5  342.69  4999.6  338.91  5002.4  338.41
  5005.6  338.91  5010.4  344.75  5024.7  350.16  5084.4  353.36  5124.1  358.94
  5158.5  359.98    5180  363.16  5499.6   374.3  5702.6  384.79  5942.8   405.5
#Mann= 5 ,-1 , 0
  4059.1     .16       0  4084.5      .1       0  4159.2     .16       0
  4999.6     .07       0  5005.6     .16       0
Bank Sta=4980.6,5024.7
XS Rating Curve= 0 ,0
Exp/Cntr=0.3,0.1

Type RM Length L Ch R = 1 ,15701   ,428,428,428
BEGIN DESCRIPTION:
MAYES BRANCH 27.0
END DESCRIPTION:
XS GIS Cut Line= 3
      3819541.09     10518262.85      3819082.78     10519047.53
      3819065.46     10519917.13
#Sta/Elev= 30
  4263.7  401.58  4474.8  387.81  4693.9  380.64  4723.9  376.49  4768.3  365.34
  4774.1  365.45  4789.8  360.72  4811.3  357.19    4913   348.7  4943.9  349.92
  4971.7  347.64  4978.6  345.73  4987.4  338.49  4998.8  337.16  5001.5  336.66
  5004.8  337.16  5008.9  346.59  5014.7  346.39  5024.6   350.3  5030.4  348.98
  5059.7  349.74  5089.1  348.05  5117.6  348.95  5225.1  360.46  5586.4  381.29
  5655.2  386.78  5745.2  397.48  5795.2  401.37  5935.2  396.46  6042.2  401.65
#Mann= 3 ,-1 , 0
  4263.7     .16       0  4998.8     .07       0  5004.8     .16       0
Bank Sta=4943.9,5024.6
XS Rating Curve= 0 ,0
Exp/Cntr=0.3,0.1

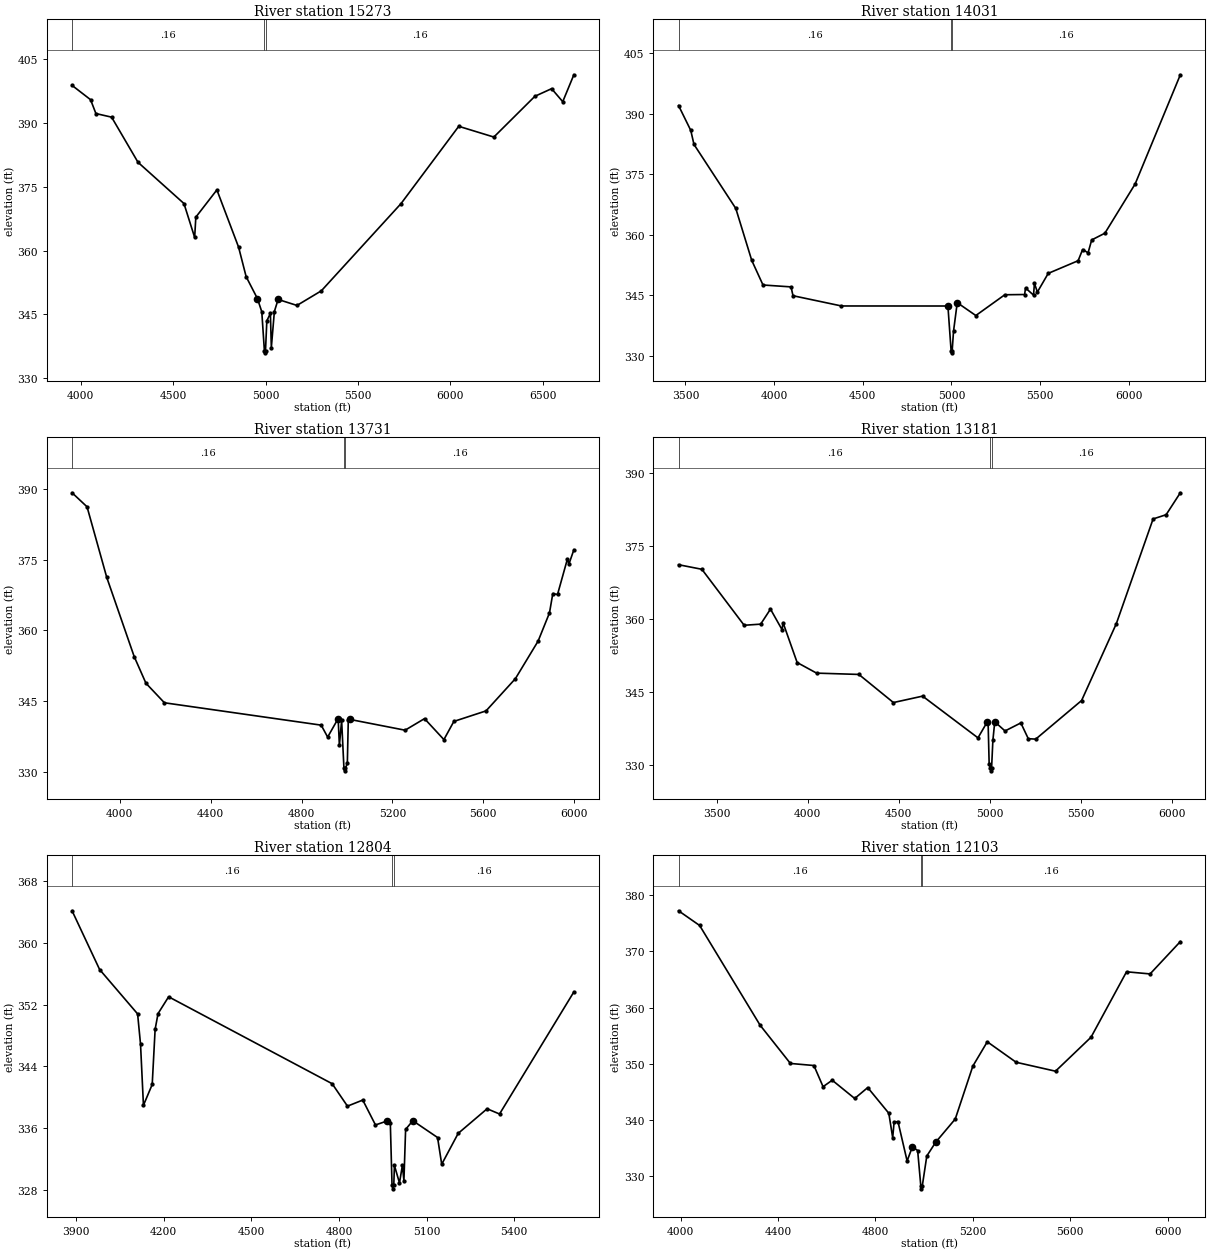
Type RM Length L Ch R = 1 ,15273   ,1242,1242,1242
BEGIN DESCRIPTION:
MAYES BRANCH 26.0
END DESCRIPTION:
XS GIS Cut Line= 4
      3819585.35     10518045.06      3818918.68     10518565.89
      3818828.41     10519031.17       3818967.3     10520420.09
#Sta/Elev= 30
  3952.9  398.86    4053   395.5  4081.9  392.24  4166.9  391.39  4309.8  380.77
  4558.5  371.07  4616.4   363.1  4622.7  367.87  4736.7  374.28  4854.2  360.81
    4895  353.87  4956.1  348.71  4979.7  345.61  4993.8  336.45  4996.6  335.95
  4999.8  336.45    5007  343.47  5026.3  345.24  5031.4   337.2  5047.8  345.67
  5068.1  348.51    5170   347.1    5302  350.54  5733.2  371.05  6045.7  389.24
  6235.7  386.71  6457.8   396.3  6548.2  398.09  6608.5  395.03  6668.7  401.36
#Mann= 3 ,-1 , 0
  3952.9     .16       0  4993.8     .07       0  4999.8     .16       0
Bank Sta=4956.1,5068.1
XS Rating Curve= 0 ,0
Exp/Cntr=0.3,0.1

Type RM Length L Ch R = 1 ,14031   ,300,300,300
BEGIN DESCRIPTION:
MAYES BRANCH 25.0
END DESCRIPTION:
XS GIS Cut Line= 3
      3818675.61      10517857.6      3818154.79     10519433.95
      3818390.91     10520579.82
#Sta/Elev= 30
  3460.9  392.01    3530  385.83  3547.9  382.37  3783.8  366.49  3873.8  353.61
  3937.3  347.51  4095.5  347.04  4106.5  344.85  4379.9  342.31  4980.2   342.3
  4998.2  331.19    5001  330.69  5004.2  331.19  5011.8  336.03  5032.8  343.13
  5137.6  339.94    5301  345.09  5412.8  345.15  5417.9  346.77  5463.1     345
  5468.2  347.91  5484.8  345.76    5546  350.39  5714.6  353.53    5740  356.31
  5770.7  355.49  5791.1  358.68  5865.5  360.35  6036.1  372.55    6291  399.63
#Mann= 3 ,-1 , 0
  3460.9     .16       0  4998.2     .07       0  5004.2     .16       0
Bank Sta=4980.2,5032.8
XS Rating Curve= 0 ,0
Exp/Cntr=0.3,0.1

Type RM Length L Ch R = 1 ,13731   ,550,550,550
BEGIN DESCRIPTION:
MAYES BRANCH 24.0
END DESCRIPTION:
XS GIS Cut Line= 3
      3818499.61     10518010.19      3817999.61     10519110.19
      3817399.61     10519910.19
#Sta/Elev= 30
  3790.1  389.15    3856  386.18  3942.8  371.21  4063.6  354.43  4115.2   348.8
  4196.5  344.66  4886.4  339.92  4914.9  337.39  4961.1  341.32  4966.5  335.62
  4976.4  340.91  4986.6  330.74  4989.4  330.24  4992.6  330.74  5001.5  331.81
  5005.7  340.98  5011.9  341.14  5255.7  338.85  5341.1   341.3  5426.5  336.86
  5470.3  340.71  5611.9  342.94  5741.1  349.77  5841.1  357.73  5891.1   363.7
  5905.7  367.79  5926.5   367.6  5970.3  375.16  5976.5  374.02  5998.4  377.07
#Mann= 3 ,-1 , 0
  3790.1     .16       0  4986.6     .07       0  4992.6     .16       0
Bank Sta=4961.1,5011.9
XS Rating Curve= 0 ,0
Exp/Cntr=0.3,0.1

Type RM Length L Ch R = 1 ,13181   ,377,377,377
BEGIN DESCRIPTION:
MAYES BRANCH 23.0
END DESCRIPTION:
XS GIS Cut Line= 3
      3818071.47     10517482.55      3817557.57      10518739.5
      3817259.22     10520106.37
#Sta/Elev= 30
  3290.5  371.12  3418.7  370.18    3651  358.67  3741.7   358.9  3795.7  361.99
  3859.3  357.76  3864.7  359.21  3942.2  351.01  4049.1  348.83  4281.4  348.56
  4471.1  342.78  4631.4   344.1  4935.7  335.52  4986.2  338.77  4991.3   338.8
  4997.2  330.11  5004.4  329.24  5007.1  328.74  5010.4  329.24  5017.6  334.99
  5027.9  338.83  5084.3  336.94  5171.2  338.59  5212.1  335.35    5253  335.26
  5505.1   343.2  5696.1  359.02  5897.9  380.53  5969.5   381.4  6047.5  385.91
#Mann= 3 ,-1 , 0
  3290.5     .16       0  5004.4     .07       0  5010.4     .16       0
Bank Sta=4986.2,5027.9
XS Rating Curve= 0 ,0
Exp/Cntr=0.3,0.1

Type RM Length L Ch R = 1 ,12804   ,701,701,701
BEGIN DESCRIPTION:
MAYES BRANCH 22.0
END DESCRIPTION:
XS GIS Cut Line= 4
      3817457.25      10517845.9      3817449.61     10518160.19
      3817199.61     10518960.19      3816799.62     10519360.17
#Sta/Elev= 30
  3885.9   364.2  3980.2  356.58  4110.3  350.82  4120.3   346.9  4130.3  338.96
  4160.3  341.66  4170.3  348.82  4180.3  350.86  4216.5  353.04  4776.5  341.76
  4828.9  338.85  4881.3  339.64  4924.8  336.41  4965.1  336.93  4975.6  336.71
  4981.5  328.62  4984.2  328.12  4987.5  328.62  4989.7  331.15    5007  328.89
    5017  331.16  5022.2  329.19    5028  335.83  5052.6  336.96  5137.4  334.78
  5151.6  331.31  5208.1  335.32  5307.1  338.51  5349.6  337.83  5604.1  353.67
#Mann= 3 ,-1 , 0
  3885.9     .16       0  4981.5     .07       0  4987.5     .16       0
Bank Sta=4965.1,5052.6
XS Rating Curve= 0 ,0
Exp/Cntr=0.3,0.1

Type RM Length L Ch R = 1 ,12103   ,288,288,288
BEGIN DESCRIPTION:
MAYES BRANCH 21.0
END DESCRIPTION:
XS GIS Cut Line= 2
      3817467.28      10517579.8      3816454.92     10519375.71
#Sta/Elev= 30
    3991  377.25  4077.7  374.63  4326.2  356.86  4450.6  350.05  4547.2  349.68
  4584.8  345.91  4622.4  347.06  4714.8  343.81  4768.3  345.75  4854.9  341.18
  4870.9  336.81  4876.6  339.59  4892.5   339.7  4930.1  332.68  4951.8  335.19
  4973.4  334.54  4986.4  328.21  4989.1  327.71  4992.4  328.21    5011  333.56
  5047.6  336.02  5127.9  340.15  5200.2  349.58  5259.5  353.91    5378  350.26
  5539.8  348.67  5685.7  354.72  5831.6  366.38  5928.4     366  6052.6  371.76
#Mann= 3 ,-1 , 0
    3991     .16       0  4986.4     .07       0  4992.4     .16       0
Bank Sta=4951.8,5047.6
XS Rating Curve= 0 ,0
Exp/Cntr=0.3,0.1

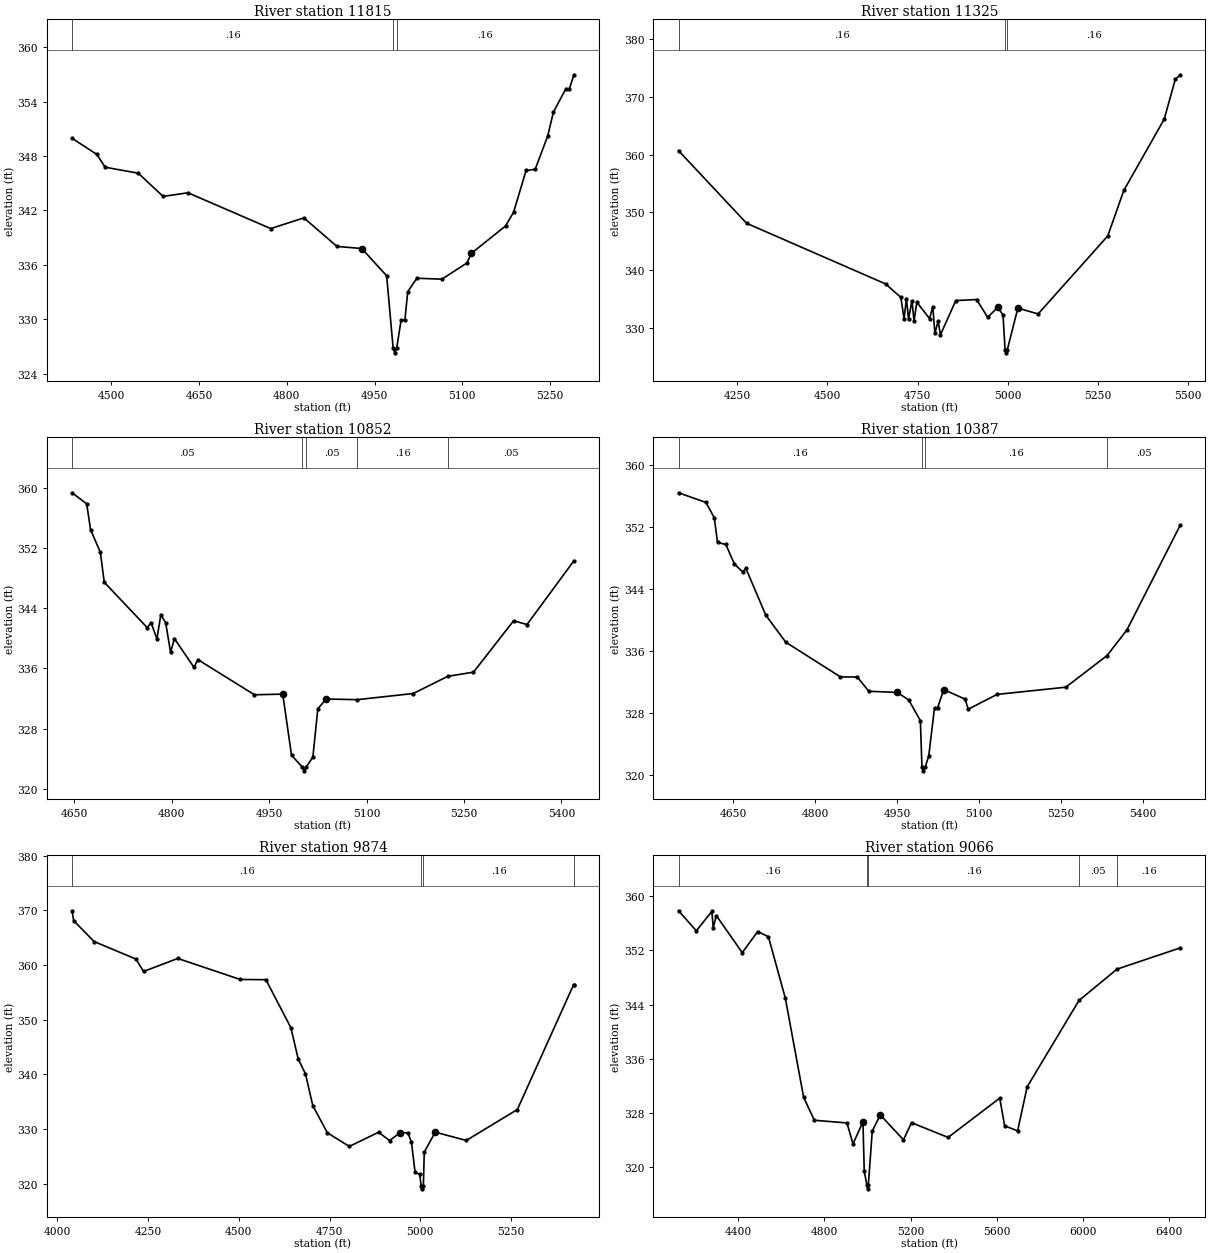
Type RM Length L Ch R = 1 ,11815   ,490,490,490
BEGIN DESCRIPTION:
MAYES BRANCH 20.0
END DESCRIPTION:
XS GIS Cut Line= 3
      3817149.59     10517910.21      3816749.61     10518310.19
      3816599.61     10518560.18
#Sta/Elev= 30
  4433.3  349.96  4475.7  348.18  4489.8  346.77  4546.4  346.11  4588.8  343.55
  4631.3  343.95  4772.7     340  4829.3  341.18  4885.8  338.03  4928.2   337.8
  4970.7  334.79  4981.8  326.79  4984.6  326.29  4987.8  326.79  4995.4  329.91
  5001.9  329.91  5006.7  333.04  5022.3  334.52    5065  334.42  5107.8   336.2
  5115.6  337.28  5173.9  340.29  5187.5   341.8  5208.9  346.41  5224.4  346.54
  5245.8  350.21  5255.5  352.84  5276.9  355.44  5282.7  355.39  5290.5  356.97
#Mann= 3 ,-1 , 0
  4433.3     .16       0  4981.8     .07       0  4987.8     .16       0
Bank Sta=4928.2,5115.6
XS Rating Curve= 0 ,0
Exp/Cntr=0.3,0.1

Type RM Length L Ch R = 1 ,11325   ,473,473,473
BEGIN DESCRIPTION:
MAYES BRANCH 19.0
END DESCRIPTION:
XS GIS Cut Line= 3
       3817149.6      10517710.2      3816349.61     10518210.19
      3816149.61     10518610.19
#Sta/Elev= 30
  4087.6  360.67  4276.3  348.12  4661.3  337.65  4703.7  335.32  4712.6  331.61
  4719.1  335.11    4725  331.61  4734.4  334.74  4740.3  331.27    4748  334.48
  4783.3  331.65  4792.2  333.72  4798.1   329.1  4806.9  331.23  4813.4  328.85
  4855.9  334.77  4913.6  334.95  4944.3  331.88    4972   333.6  4986.8  332.29
  4992.6  326.24  4995.4  325.74  4998.6  326.24    5028  333.47  5084.1  332.46
    5277  345.93  5321.7  353.81  5433.5  366.11  5464.2  372.98  5478.2  373.78
#Mann= 3 ,-1 , 0
  4087.6     .16       0  4992.6     .07       0  4998.6     .16       0
Bank Sta=4972,5028
XS Rating Curve= 0 ,0
Exp/Cntr=0.3,0.1

Type RM Length L Ch R = 1 ,10852   ,465,465,465
BEGIN DESCRIPTION:
MAYES BRANCH 18.0
END DESCRIPTION:
XS GIS Cut Line= 3
      3816299.61     10517710.18      3816099.61     10518010.19
       3815999.6     10518410.22
#Sta/Elev= 30
  4646.3  359.38  4668.8  357.91  4674.8  354.47  4689.9  351.45  4695.9  347.47
    4762  341.44    4768  342.09    4777  339.95    4783  343.13  4790.5  342.09
    4798  338.16    4804  339.97  4834.1  336.15  4840.1  337.18  4927.2   332.5
  4970.8  332.59  4984.3  324.46  5000.9  322.88  5003.6  322.38  5006.9  322.88
  5017.2   324.2  5024.9  330.65  5037.8  331.94  5085.4  331.85  5171.8  332.67
  5225.1  334.96  5264.6  335.51  5326.4  342.35    5347  341.85  5419.2  350.32
#Mann= 5 ,-1 , 0
  4646.3     .05       0  5000.9     .04       0  5006.9     .05       0
  5085.4     .16       0  5225.1     .05       0
Bank Sta=4970.8,5037.8
XS Rating Curve= 0 ,0
Exp/Cntr=0.3,0.1

Type RM Length L Ch R = 1 ,10387   ,513,513,513
BEGIN DESCRIPTION:
MAYES BRANCH 17.0
END DESCRIPTION:
XS GIS Cut Line= 3
      3815999.63     10517510.15      3815749.61     10517910.19
      3815549.59     10518310.23
#Sta/Elev= 30
  4549.4  356.45  4599.6   355.2  4614.9  353.21  4620.8  350.02  4636.1  349.76
  4651.5  347.26  4666.8  346.21  4672.7  346.68  4709.2  340.62  4745.8  337.12
    4846  332.63  4876.7  332.62  4897.9  330.77  4949.8  330.63    4971  329.65
  4992.3  326.97  4995.2  320.98  4997.9  320.48  5001.2  320.98  5007.6  322.38
  5018.2  328.64  5023.9  328.64  5035.1  330.99  5074.3  329.75  5079.8  328.45
  5132.9  330.37  5258.7   331.3  5334.3   335.4  5370.5   338.7  5468.4  352.28
#Mann= 4 ,-1 , 0
  4549.4     .16       0  4995.2     .07       0  5001.2     .16       0
  5334.3     .05       0
Bank Sta=4949.8,5035.1
XS Rating Curve= 0 ,0
Exp/Cntr=0.3,0.1

Type RM Length L Ch R = 1 ,9874    ,808,808,808
BEGIN DESCRIPTION:
MAYES BRANCH 16.0
END DESCRIPTION:
XS GIS Cut Line= 4
      3815628.04     10517062.92      3815305.12     10517507.37
      3815349.61     10517910.19      3815499.59     10518310.15
#Sta/Elev= 30
    4041  369.91  4045.3  368.11  4101.7  364.28  4216.9  361.08  4237.8  358.81
  4332.1  361.19  4503.7  357.35  4574.8   357.3  4643.5  348.53  4663.6  342.84
  4683.8  340.06  4703.9  334.27  4744.1  329.29  4804.5  326.81    4885   329.4
  4915.2  327.89  4945.2  329.34  4965.5  329.29  4975.5  327.64  4985.6  322.07
  4998.3  321.69  5002.4  319.55  5005.2  319.05  5008.4  319.55  5010.8  325.76
    5041  329.42  5126.5   327.9  5267.1  333.55    5422  356.37  5422.8  356.37
#Mann= 4 ,-1 , 0
    4041     .16       0  5002.4     .07       0  5008.4     .16       0
    5422     .05       0
Bank Sta=4945.2,5041
XS Rating Curve= 0 ,0
Exp/Cntr=0.3,0.1

Type RM Length L Ch R = 1 ,9066    ,640,640,640
BEGIN DESCRIPTION:
MAYES BRANCH 15.0
END DESCRIPTION:
XS GIS Cut Line= 4
      3815474.25     10517128.38      3815022.85     10517697.84
      3814821.46     10518045.06      3815328.39      10519135.3
#Sta/Elev= 30
  4122.5  357.86  4205.1   354.9  4277.2  357.76  4283.6  355.36    4298  357.15
  4418.3  351.67  4490.3  354.79    4540  354.02  4618.5  344.93  4703.4   330.3
  4753.1  326.89  4904.7  326.49  4932.8  323.39    4979  326.67    4985  319.33
  4997.8  317.25  5000.5  316.75  5003.8  317.25  5022.3   325.3  5059.5  327.68
  5167.2  323.99  5204.5  326.53  5374.3  324.35  5614.2  330.16  5637.1  326.06
  5697.3  325.32  5741.5  331.83  5982.3   344.6  6158.8  349.23  6452.9  352.38
#Mann= 5 ,-1 , 0
  4122.5     .16       0  4997.8     .07       0  5003.8     .16       0
  5982.3     .05       0  6158.8     .16       0
Bank Sta=4979,5059.5
XS Rating Curve= 0 ,0
Exp/Cntr=0.3,0.1

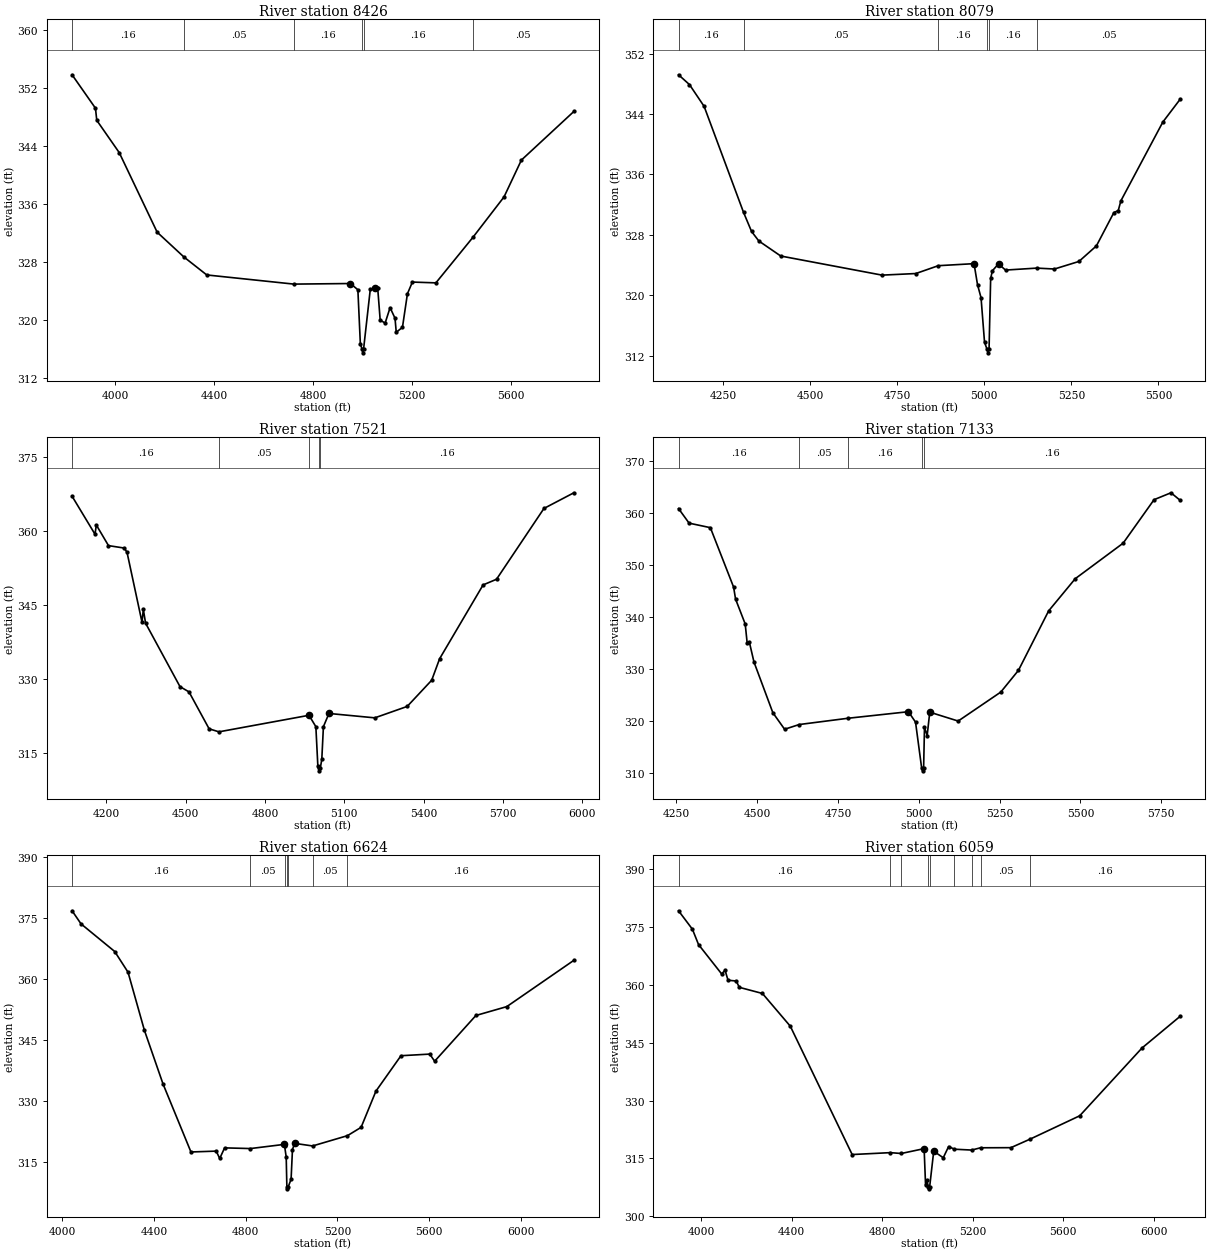
Type RM Length L Ch R = 1 ,8426    ,347,347,347
BEGIN DESCRIPTION:
MAYES BRANCH 14.0
END DESCRIPTION:
XS GIS Cut Line= 3
      3814564.52     10517038.13      3814640.91     10517274.23
      3814529.79     10519052.01
#Sta/Elev= 30
  3825.5  353.78  3920.1  349.18  3925.4  347.51  4016.2  343.07  4169.7  332.11
  4277.9   328.7  4370.2  326.23  4722.5  324.97  4951.3  325.05  4981.4  324.19
  4991.4  316.75  4998.4  316.01  5001.2  315.51  5004.4  316.01  5031.5  324.23
  5051.5  324.44  5061.5  324.46  5071.6  320.02  5091.6   319.6  5111.6  321.73
  5131.6  320.27  5136.6  318.34  5161.7  319.02  5181.8  323.64  5201.8  325.25
  5296.9  325.14  5446.5   331.4  5572.5  336.97  5642.7  342.04  5854.9  348.73
#Mann= 6 ,-1 , 0
  3825.5     .16       0  4277.9     .05       0  4722.5     .16       0
  4998.4     .07       0  5004.4     .16       0  5446.5     .05       0
Bank Sta=4951.3,5051.5
XS Rating Curve= 0 ,0
Exp/Cntr=0.3,0.1

Type RM Length L Ch R = 1 ,8079    ,558,558,558
BEGIN DESCRIPTION:
MAYES BRANCH 13.0
END DESCRIPTION:
XS GIS Cut Line= 3
      3814549.61     10517260.17      3814299.61     10518060.19
      3814349.61     10518660.24
#Sta/Elev= 30
  4122.6   349.2    4154   347.9    4196  345.02  4309.1  330.99  4332.2  328.45
  4353.1  327.19    4416   325.2  4706.7  322.67  4803.6  322.88  4868.2  323.92
  4970.8  324.19  4980.8   321.4  4990.9  319.68  5000.9  313.78  5007.9  312.88
  5010.7  312.38  5013.9  312.88  5018.5  322.24  5023.5  323.25    5041  324.16
  5061.1  323.34  5150.7   323.6  5201.6  323.48  5271.8  324.48    5322  326.54
  5372.2  330.96  5384.7  331.22  5392.3  332.51  5512.7  342.94  5562.9  345.99
#Mann= 6 ,-1 , 0
  4122.6     .16       0  4309.1     .05       0  4868.2     .16       0
  5007.9     .07       0  5013.9     .16       0  5150.7     .05       0
Bank Sta=4970.8,5041
XS Rating Curve= 0 ,0
Exp/Cntr=0.3,0.1

Type RM Length L Ch R = 1 ,7521    ,388,388,388
BEGIN DESCRIPTION:
MAYES BRANCH 12.0
END DESCRIPTION:
XS GIS Cut Line= 3
      3814029.79     10516982.57      3813988.13     10517711.73
      3813329.04     10518676.07
#Sta/Elev= 30
  4070.4  367.13  4157.2  359.41  4162.2  361.28  4208.2   357.1  4268.3   356.6
  4278.4  355.72    4335  341.55    4340  344.16  4348.5  341.35  4478.7  328.47
  4512.8   327.4  4588.9   319.9  4626.1  319.29  4966.7  322.65  4992.7  320.34
  5000.3  312.31  5003.4  311.87  5006.1  311.37  5009.4  311.87  5015.2  313.71
  5021.3  320.34  5042.3  323.02  5215.7  322.13  5338.3  324.45    5431  329.77
  5460.9  334.13  5625.4  349.12  5676.2  350.27  5855.7  364.65  5968.8  367.83
#Mann= 5 ,-1 , 0
  4070.4     .16       0  4626.1     .05       0  4966.7     .16       0
  5003.4     .07       0  5009.4     .16       0
Bank Sta=4966.7,5042.3
XS Rating Curve= 0 ,0
Exp/Cntr=0.3,0.1

Type RM Length L Ch R = 1 ,7133    ,509,509,509
BEGIN DESCRIPTION:
MAYES BRANCH 11.0
END DESCRIPTION:
XS GIS Cut Line= 3
      3813953.39      10517218.7      3813571.46     10517781.17
      3813161.76     10518551.96
#Sta/Elev= 30
  4256.3  360.85    4289  358.04  4354.8  357.17  4426.7  345.72  4432.8  343.41
  4462.6  338.62  4468.7  334.95  4475.7  335.06  4489.7   331.3  4548.2  321.52
  4584.5  318.34  4629.8  319.25    4781  320.46  4967.7  321.72  4989.7  319.71
  5008.7  310.83  5011.4  310.33  5014.7  310.83  5017.4  318.69  5025.7  317.13
  5033.7  321.63  5121.6  319.92  5253.5   325.5  5308.1  329.68  5401.6  341.14
  5483.9  347.34  5632.1  354.18  5727.8  362.56  5780.2  363.89  5809.1  362.41
#Mann= 5 ,-1 , 0
  4256.3     .16       0  4629.8     .05       0    4781     .16       0
  5008.7     .07       0  5014.7     .16       0
Bank Sta=4967.7,5033.7
XS Rating Curve= 0 ,0
Exp/Cntr=0.3,0.1

Type RM Length L Ch R = 1 ,6624    ,565,565,565
BEGIN DESCRIPTION:
MAYES BRANCH 10.0
END DESCRIPTION:
XS GIS Cut Line= 3
       3813745.1     10516711.69      3812911.74     10518065.89
      3812779.78     10518649.27
#Sta/Elev= 30
  4042.8  376.79    4082  373.56  4228.8  366.77  4286.8  361.68  4358.1  347.41
  4439.4  334.19  4561.2  317.45  4671.3  317.66  4686.7  315.85    4708  318.46
  4820.5  318.29  4968.6  319.32  4969.4  319.01  4976.6   316.2  4979.5  308.88
  4982.2  308.38  4985.5  308.88  4997.9  310.75  5003.9  318.04  5013.3  319.57
  5091.6  318.93  5243.6  321.46  5303.2  323.51  5367.9  332.42  5477.1  341.13
  5602.6  341.53  5623.9  339.77  5803.8  351.03  5938.5  353.21    6231   364.6
#Mann= 7 ,-1 , 0
  4042.8     .16       0  4820.5     .05       0  4969.4     .16       0
  4979.5     .07       0  4985.5     .16       0  5091.6     .05       0
  5243.6     .16       0
Bank Sta=4968.6,5013.3
XS Rating Curve= 0 ,0
Exp/Cntr=0.3,0.1

Type RM Length L Ch R = 1 ,6059    ,688,688,688
BEGIN DESCRIPTION:
MAYES BRANCH 9.0
END DESCRIPTION:
XS GIS Cut Line= 3
      3813571.48     10516378.37      3812856.18     10517447.84
      3812488.13     10518301.99
#Sta/Elev= 30
  3900.2  379.19  3961.5  374.41  3988.6  370.43  4090.6  362.83  4105.7  363.77
  4118.9  361.19    4155  360.99  4168.7  359.35  4270.8  357.76  4393.9  349.28
  4667.2  316.02    4836  316.51    4884  316.29  4985.1  317.55  4991.5  308.07
  4997.5  309.36  5003.5  307.63  5006.2  307.13  5009.5  307.63  5027.5  316.88
  5069.6  315.19  5093.4   318.1  5118.7   317.4  5195.3  317.18  5234.2  317.77
  5368.4   317.8    5455  320.06  5672.4  326.06  5947.5  343.62  6116.9  351.88
#Mann= 9 ,-1 , 0
  3900.2     .16       0    4836     .05       0    4884     .16       0
  5003.5     .07       0  5009.5     .16       0  5118.7     .05       0
  5195.3     .16       0  5234.2     .05       0    5455     .16       0
Bank Sta=4985.1,5027.5
XS Rating Curve= 0 ,0
Exp/Cntr=0.3,0.1