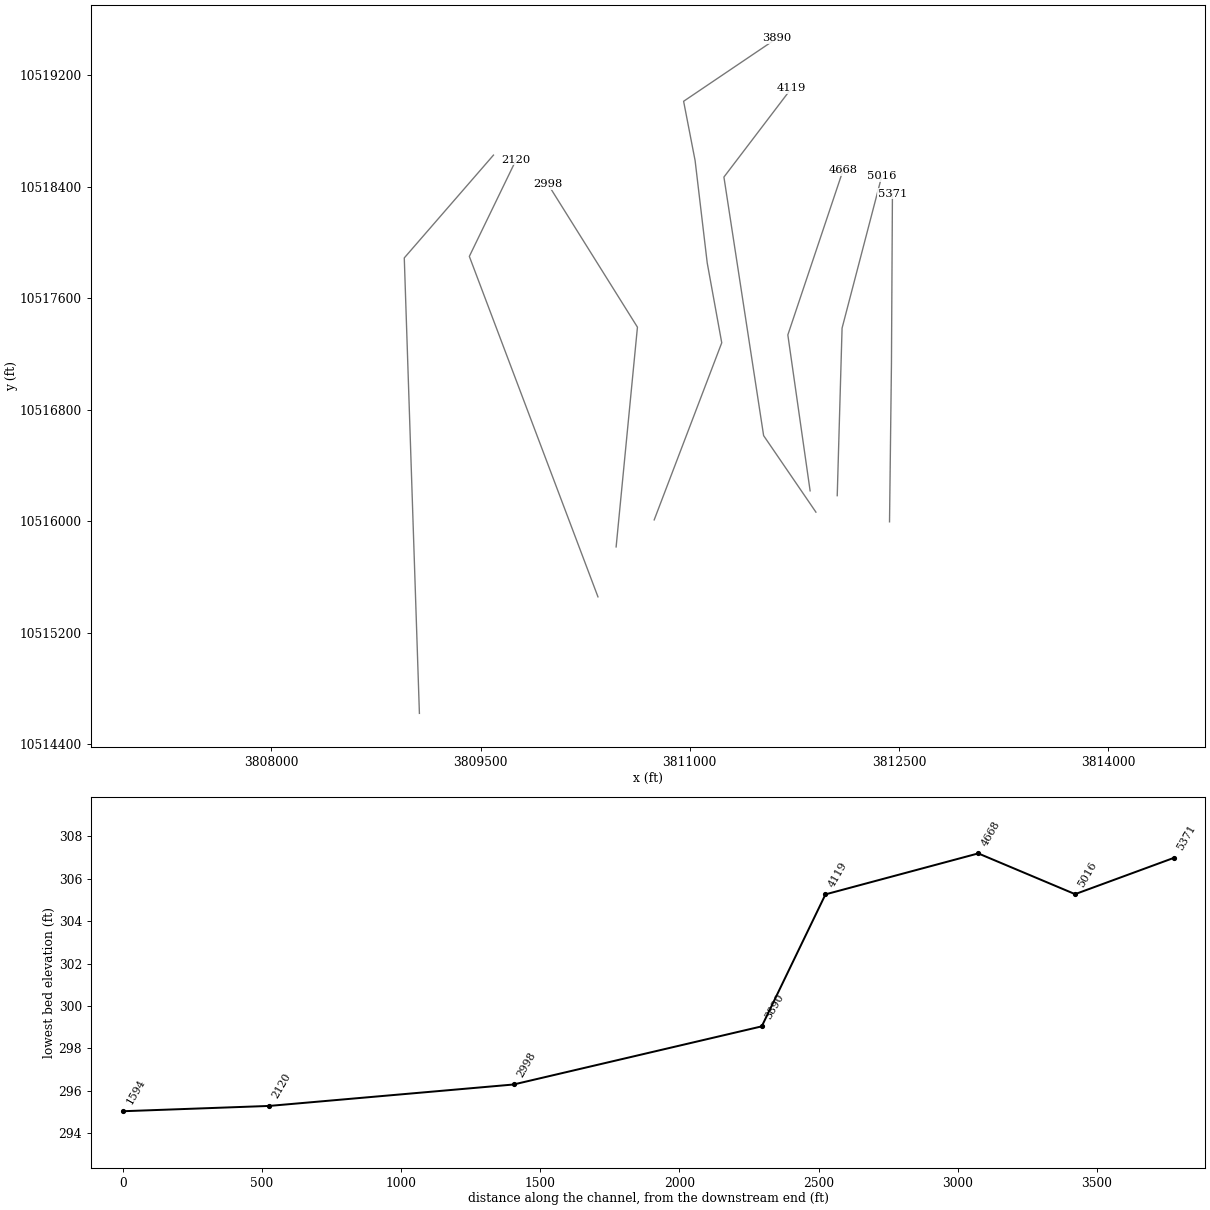
HEC-RAS study MAYES BRANCH.prj: MAYES BRANCH Base Level Engineering

--- MAYES BRANCH.g01 (geometry) --- (continued)

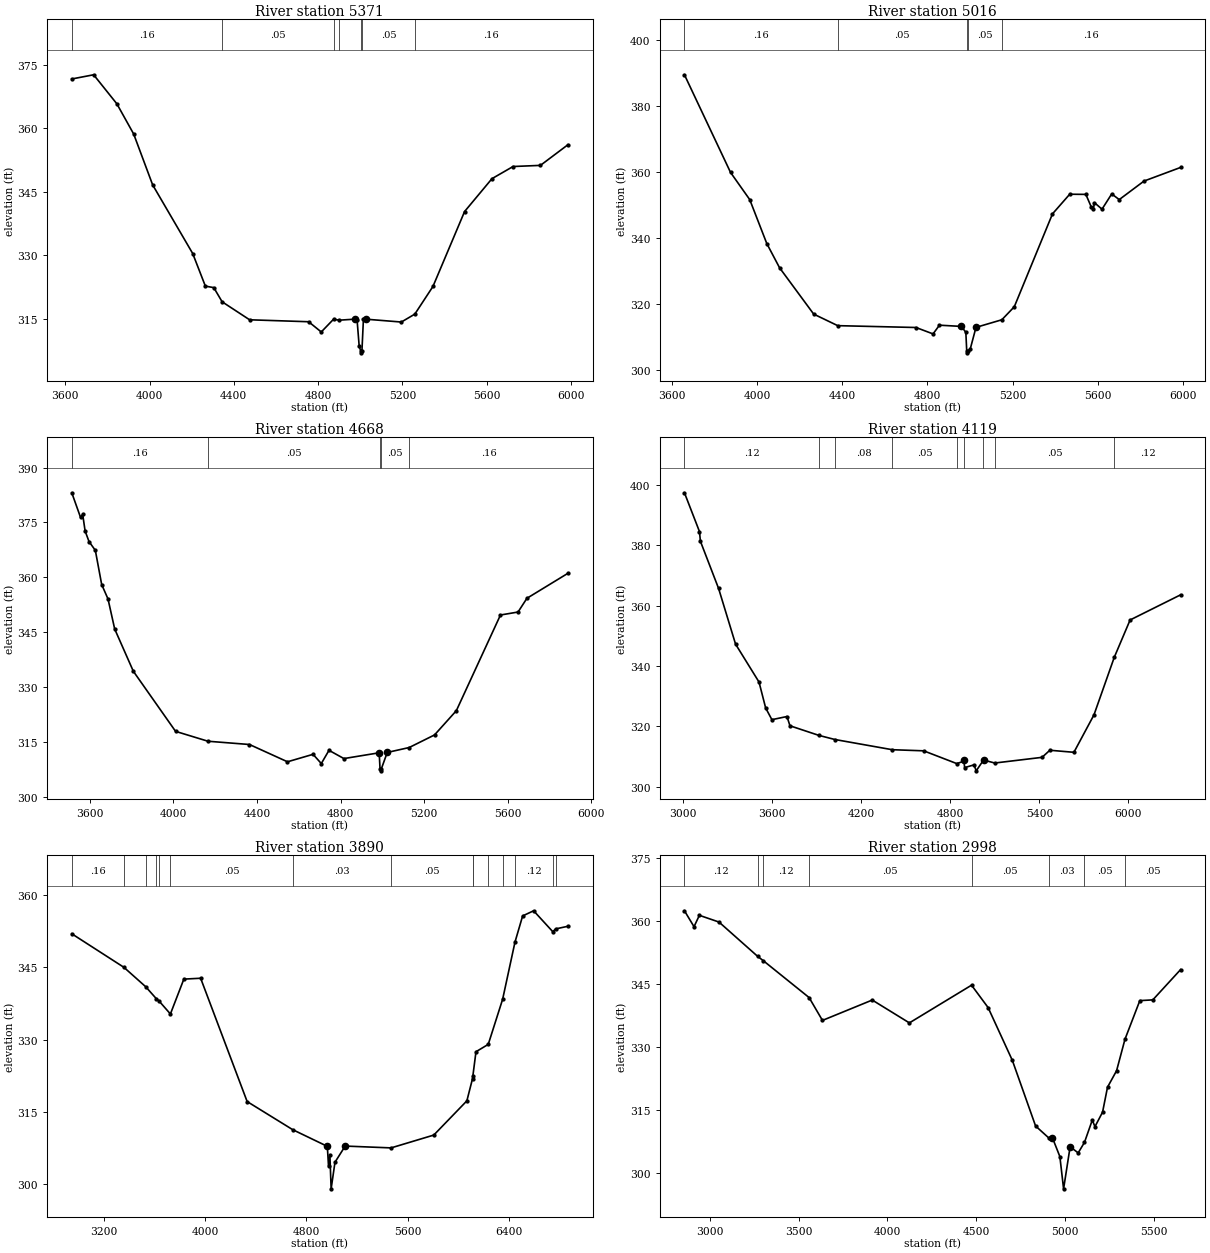
Type RM Length L Ch R = 1 ,5371    ,355,355,355
BEGIN DESCRIPTION:
MAYES BRANCH 8.0
END DESCRIPTION:
XS GIS Cut Line= 3
      3812432.57     10515996.46      3812446.46     10517135.34
      3812453.41     10518350.66
#Sta/Elev= 30
  3631.2   371.7  3734.9  372.69  3844.9  365.84  3924.9  358.69    4015  346.66
    4205  330.45    4265  322.75    4305  322.39  4344.6  319.04    4475  314.79
    4755  314.33    4815  311.91  4873.2  314.92  4900.4   314.7    4975  314.94
    4985  314.71    4995   308.5    5002  307.48  5004.8  306.98    5008  307.48
    5015   314.9    5025  314.94    5195  314.26  5258.9  316.13    5345  322.67
    5495  340.37    5625  348.14    5725  351.01    5855  351.28  5985.5  356.16
#Mann= 7 ,-1 , 0
  3631.2     .16       0  4344.6     .05       0  4873.2     .16       0
  4900.4     .05       0    5002     .03       0    5008     .05       0
  5258.9     .16       0
Bank Sta=4975,5025
XS Rating Curve= 0 ,0
Exp/Cntr=0.3,0.1

Type RM Length L Ch R = 1 ,5016    ,348,348,348
BEGIN DESCRIPTION:
MAYES BRANCH 7.0
END DESCRIPTION:
XS GIS Cut Line= 3
      3812057.57     10516183.96      3812092.29     10517385.34
      3812376.96      10518475.4
#Sta/Elev= 30
  3659.5  389.45  3875.8  359.89  3965.9  351.66  4045.9  338.36  4105.9  331.02
    4266     317  4378.8   313.5  4746.2  312.94  4826.2     311  4856.2  313.64
  4959.4  313.27  4980.1  311.47  4984.3  305.77    4987  305.27  4990.3  305.77
  5000.7  306.42  5027.7  312.98    5149  315.28  5207.5  319.22  5386.7  347.34
  5467.6  353.29  5543.3  353.24  5569.2  349.36  5578.6  348.84  5583.8  350.72
  5619.1  348.76  5664.7  353.38    5700  351.66  5816.2  357.27    5988   361.4
#Mann= 5 ,-1 , 0
  3659.5     .16       0  4378.8     .05       0  4984.3     .03       0
  4990.3     .05       0    5149     .16       0
Bank Sta=4959.4,5027.7
XS Rating Curve= 0 ,0
Exp/Cntr=0.3,0.1

Type RM Length L Ch R = 1 ,4668    ,549,549,549
BEGIN DESCRIPTION:
MAYES BRANCH 6.0
END DESCRIPTION:
XS GIS Cut Line= 3
      3811863.13     10516218.64      3811703.41     10517336.73
      3812098.89     10518516.26
#Sta/Elev= 30
  3514.3  383.11  3556.3  376.37  3566.4  377.23    3578  372.68  3596.7  369.79
    3627  367.38  3657.3  358.06  3687.6  354.11  3719.5  345.92  3808.8  334.37
  4010.8  317.97  4165.9  315.27  4364.4  314.38  4546.2  309.66  4668.5   311.7
  4707.9  309.18  4744.7  312.79  4816.1  310.54  4984.9  312.12  4988.9  307.69
  4991.6  307.19  4994.9  307.69  5023.4  312.21  5128.1  313.55  5249.5  316.99
    5354  323.62    5565  349.74  5649.1  350.55  5691.6   354.3  5887.8  361.13
#Mann= 5 ,-1 , 0
  3514.3     .16       0  4165.9     .05       0  4988.9     .03       0
  4994.9     .05       0  5128.1     .16       0
Bank Sta=4984.9,5023.4
XS Rating Curve= 0 ,0
Exp/Cntr=0.3,0.1

Type RM Length L Ch R = 1 ,4119    ,229,229,229
BEGIN DESCRIPTION:
MAYES BRANCH 5.0
END DESCRIPTION:
XS GIS Cut Line= 4
      3811904.78     10516065.91      3811529.79      10516614.5
      3811245.07     10518468.67      3811730.27     10519106.36
#Sta/Elev= 30
  3009.9  397.36  3111.2  384.49  3117.3  381.31  3239.9  365.66  3354.2  347.22
  3512.1  334.67  3556.8  326.09  3598.8  322.21  3700.4  323.25  3720.6  320.18
  3915.7     317    4023  315.64  4409.2  312.26  4621.1  311.89  4843.6  307.67
  4889.5   308.4  4891.8  308.89  4896.9  306.33  4960.2  307.24  4974.9  305.26
  5023.5  308.77  5028.5  308.78  5099.9  307.85  5418.4  309.73  5470.9  312.08
    5633   311.4  5768.2  323.81  5905.1   342.9  6011.4  355.23  6351.6  363.56
#Mann= 9 ,-1 , 0
  3009.9     .12       0  3915.7     .05       0    4023     .08       0
  4409.2     .05       0  4843.6     .08       0  4889.5     .07       0
  5023.5     .08       0  5099.9     .05       0  5905.1     .12       0
Bank Sta=4891.8,5028.5
XS Rating Curve= 0 ,0
Exp/Cntr=0.3,0.1

Type RM Length L Ch R = 1 ,3890    ,892,892,892
BEGIN DESCRIPTION:
MAYES BRANCH 4.0
END DESCRIPTION:
XS GIS Cut Line= 6
      3810745.09     10516010.37      3811229.45      10517280.3
      3811125.28     10517853.22      3811038.47     10518586.73
      3810956.01     10519012.07      3811624.37     10519463.44
#Sta/Elev= 30
  2946.4  351.93  3358.4  344.97  3529.9  340.96  3614.9  338.45  3637.5  337.94
  3725.5   335.3  3831.8  342.53  3964.4  342.71  4331.8  317.14  4691.7  311.31
  4965.4  307.85  4974.6   303.8  4985.6  306.05  4995.4  299.04  5025.8  304.56
  5106.4  307.91  5468.9  307.53  5806.4  310.19  6067.8  317.29  6112.4  321.89
  6115.1  322.43  6139.7  327.47  6236.7     329  6350.4  338.36  6447.9  350.21
  6508.3  355.63  6595.1   356.7  6746.3  352.37  6769.2  352.94  6866.3  353.49
#Mann= 15 ,-1 , 0
  2946.4     .16       0  3358.4     .05       0  3529.9     .08       0
  3614.9     .05       0  3637.5     .12       0  3725.5     .05       0
  4691.7     .03       0  5468.9     .05       0  6112.4     .05       0
  6115.1     .08       0  6236.7     .12       0  6350.4     .05       0
  6447.9     .12       0  6746.3     .05       0  6769.2     .16       0
Bank Sta=4965.4,5106.4
XS Rating Curve= 0 ,0
Exp/Cntr=0.3,0.1

Type RM Length L Ch R = 1 ,2998    ,878,878,878
BEGIN DESCRIPTION:
MAYES BRANCH 3.0
END DESCRIPTION:
XS GIS Cut Line= 3
      3810472.07      10515816.5      3810624.93     10517392.27
      3809982.31     10518419.21
#Sta/Elev= 30
  2857.6  362.37  2911.5  358.59  2941.7  361.29  3052.2  359.69  3269.9  351.54
  3301.7  350.51  3559.7  341.75  3634.9  336.32  3915.4  341.16  4124.5  335.73
  4474.6  344.69  4567.8  339.38  4704.5  326.82  4835.4  311.23  4908.5  308.44
  4929.7  308.49  4972.1  303.97  4993.1   296.3  5029.9   306.3  5075.3  304.84
  5110.7  307.34  5154.9  312.65  5169.7  311.07  5212.6  314.52  5240.5  320.45
  5291.6  324.37  5338.8  331.84  5422.5  341.02  5495.6   341.2  5652.2   348.4
#Mann= 8 ,-1 , 0
  2857.6     .12       0  3269.9     .05       0  3301.7     .12       0
  3559.7     .05       0  4474.6     .05       0  4908.5     .03       0
  5110.7     .05       0  5338.8     .05       0
Bank Sta=4929.7,5029.9
XS Rating Curve= 0 ,0
Exp/Cntr=0.3,0.1

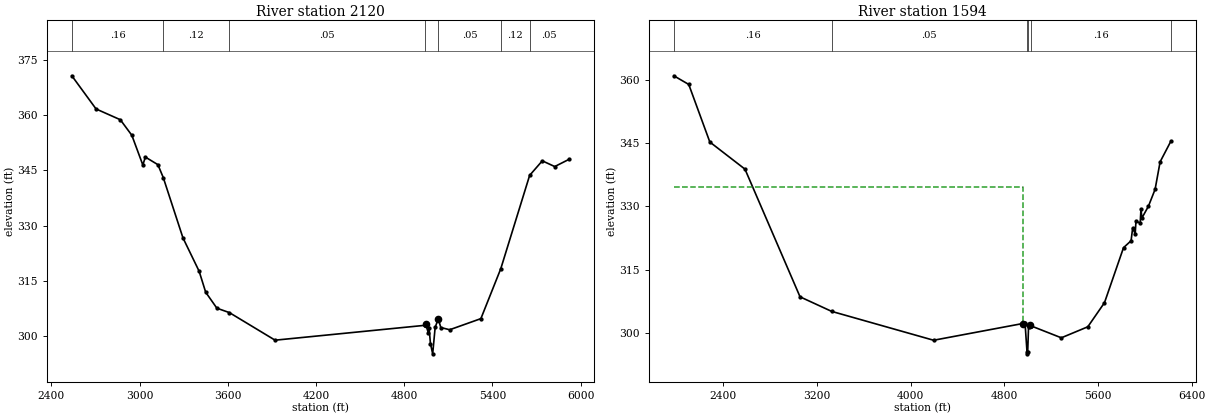
Type RM Length L Ch R = 1 ,2120    ,526,526,526
BEGIN DESCRIPTION:
MAYES BRANCH 2.0
END DESCRIPTION:
XS GIS Cut Line= 3
      3810341.85     10515458.44      3809419.55      10517899.8
      3809755.27      10518592.9
#Sta/Elev= 30
    2539  370.64  2703.8  361.65  2868.8  358.73  2947.1  354.52  3021.9  346.47
  3039.2  348.61  3124.4  346.55  3160.9  343.06  3294.8  326.72  3404.9  317.67
  3449.5  311.98  3525.6  307.66  3610.8  306.46  3921.5  298.99  4938.6  303.01
  4946.1  303.29  4963.4  301.01  4968.7  302.35  4978.1  298.08  4993.3  295.29
  5010.2  302.49  5031.6  304.76  5048.6  302.42    5109  301.82  5321.2  304.83
  5456.7  318.38  5652.8  343.65  5738.8  347.59  5823.5  346.04  5918.9  347.96
#Mann= 7 ,-1 , 0
    2539     .16       0  3160.9     .12       0  3610.8     .05       0
  4938.6     .03       0  5031.6     .05       0  5456.7     .12       0
  5652.8     .05       0
Bank Sta=4946.1,5031.6
XS Rating Curve= 0 ,0
Exp/Cntr=0.3,0.1

Type RM Length L Ch R = 1 ,1594    ,0,0,0
BEGIN DESCRIPTION:
MAYES BRANCH 1.0
END DESCRIPTION:
XS GIS Cut Line= 3
      3809061.48     10514622.89      3808952.97     10517888.95
      3809592.49     10518626.02
#Sta/Elev= 30
  1977.4  360.94  2104.8  358.89  2284.9  345.24    2585  338.81  3055.3  308.55
  3325.4   305.1  4195.9  298.26  4956.3  302.22  4976.4  302.43  4993.4  295.54
  4996.1  295.04  4999.4  295.54  5006.4  301.35  5016.4  301.97  5026.4  301.68
  5286.6  298.84  5512.7  301.45  5655.2  307.17  5817.6   320.2  5882.2  321.84
  5895.6  324.85  5917.3  323.49  5923.9  326.45  5960.1  326.04  5966.7  329.39
  5974.3  327.21  6030.3  330.02  6087.3  334.03  6130.1  340.54  6221.1  345.38
#Mann= 6 ,-1 , 0
  1977.4     .16       0  3325.4     .05       0  4993.4     .07       0
  4999.4     .05       0  5026.4     .16       0  6221.1     .05       0
#XS Ineff= 2 , 0
          4963.3  334.47
Permanent Ineff=
       F       F
Bank Sta=4956.3,5016.4
XS Rating Curve= 0 ,0
Exp/Cntr=0.3,0.1

Chan Stop Cuts=-1
Use User Specified Reach Order=0
Composite Channel Slope=5