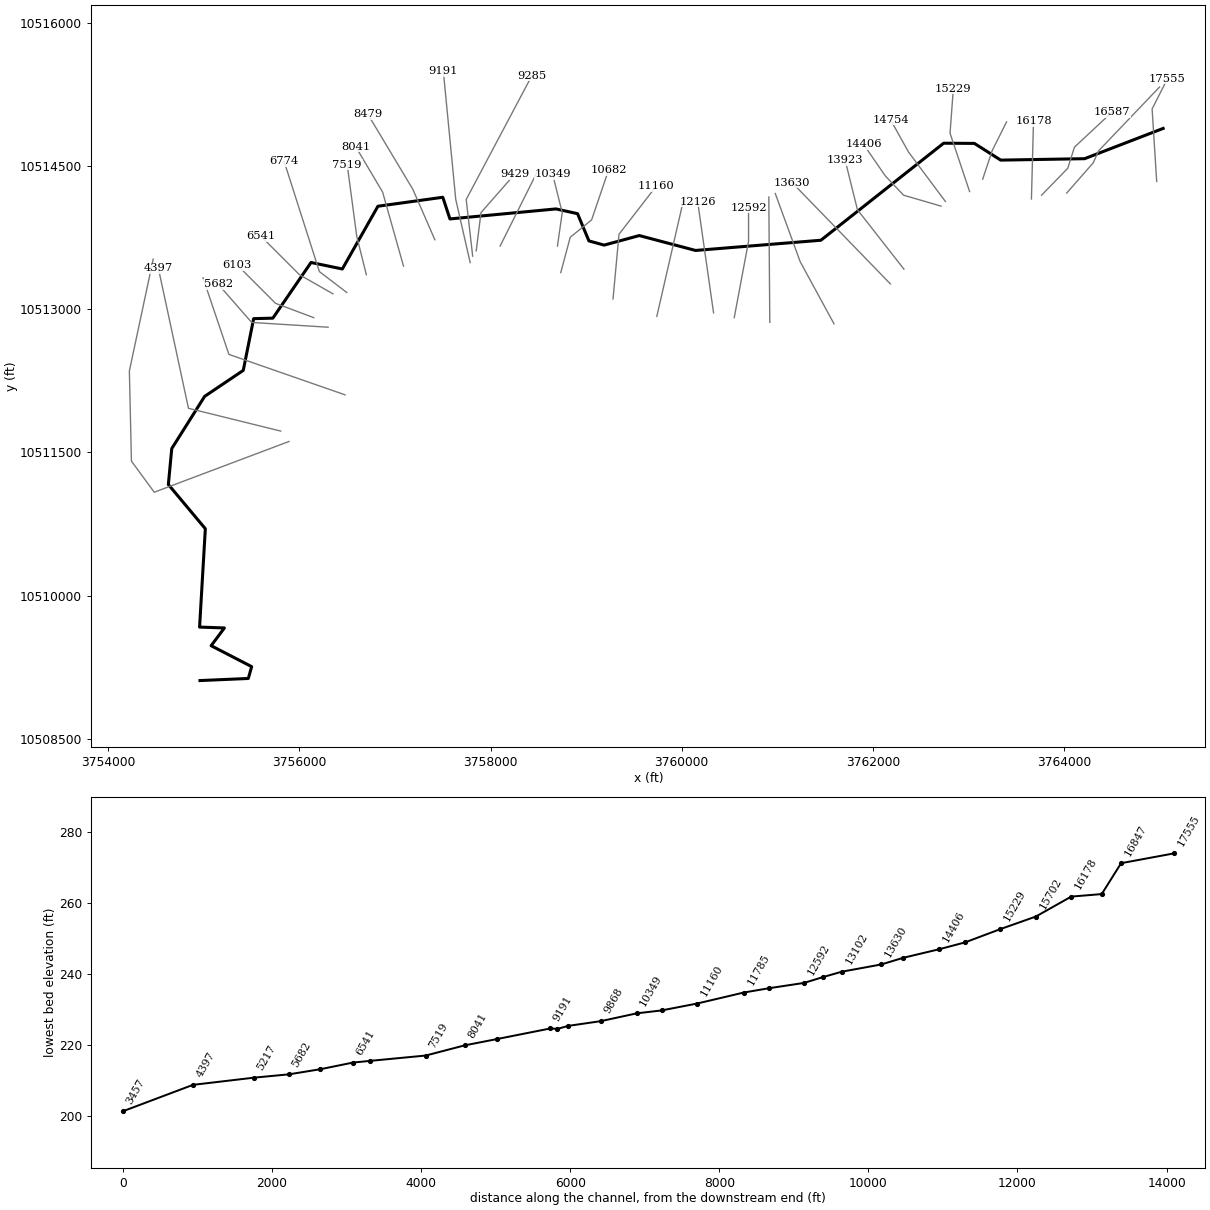
--- MERIWETHER BRANCH.prj (project) ---

Proj Title=MERIWETHER BRANCH Base Level Engineering
Current Plan=p01
Default Exp/Contr=0.3,0.1
English Units
Geom File=g01
Flow File=f01
Plan File=p01
BEGIN DESCRIPTION:
MERIWETHER BRANCH
END DESCRIPTION:

--- MERIWETHER BRANCH.p01 (plan) ---

Plan Title=Multiple Run
Short Identifier=Multiple
Geom File=g01
Flow File=f01
Subcritical Flow
K Sum by GR= 0
Std Step Tol= 0.01
Critical Tol= 0.01
Num of Std Step Trials= 20
Max Error Tol= 0.3
Flow Tol Ratio= 0.001
Split Flow NTrial= 30
Split Flow Tol= 0.02
Split Flow Ratio= 0.02
Log Output Level= 0
Friction Slope Method= 1
Unsteady Friction Slope Method= 2
Unsteady Bridges Friction Slope Method= 1
Parabolic Critical Depth
Global Vel Dist=  1 , 1 , 1
Global Log Level= 0
CheckData=True
Encroach Param= -1, 0, 0, 0
BEGIN DESCRIPTION:
Multiple Run
END DESCRIPTION:

--- MERIWETHER BRANCH.f01 (steady flow) ---

Flow Title=Multiple
Number of Profiles=7
Profile Names=10-year,25-year,50-year,1pct_min,100-year,1pct_plu,500-year
River Rch & RM= MERIWETHER BRANC,Reach-1,17555
     709     973    1193    1077    1456    1969    2174
River Rch & RM= MERIWETHER BRANC,Reach-1,14754
    1009    1407    1745    1588    2148    2905    3268
River Rch & RM= MERIWETHER BRANC,Reach-1,9429
    1210    1694    2105    1919    2595    3510    3960
Boundary for River Rch & Prof#=MERIWETHER BRANC,Reach-1,1
Up Type=0
Dn Type=3
Dn Slope=0.005
Boundary for River Rch & Prof#=MERIWETHER BRANC,Reach-1,2
Up Type=0
Dn Type=3
Dn Slope=0.005
Boundary for River Rch & Prof#=MERIWETHER BRANC,Reach-1,3
Up Type=0
Dn Type=3
Dn Slope=0.005
Boundary for River Rch & Prof#=MERIWETHER BRANC,Reach-1,4
Up Type=0
Dn Type=3
Dn Slope=0.005
Boundary for River Rch & Prof#=MERIWETHER BRANC,Reach-1,5
Up Type=0
Dn Type=3
Dn Slope=0.005
Boundary for River Rch & Prof#=MERIWETHER BRANC,Reach-1,6
Up Type=0
Dn Type=3
Dn Slope=0.005
Boundary for River Rch & Prof#=MERIWETHER BRANC,Reach-1,7
Up Type=0
Dn Type=3
Dn Slope=0.005

--- MERIWETHER BRANCH.g01 (geometry) ---

Geom Title=Existing Conditions

River Reach=MERIWETHER BRANC,Reach-1
Reach XY= 30
      3765038.25     10514892.00      3764216.50     10514575.00
      3763338.50     10514560.00      3763062.75     10514735.00
      3762741.00     10514737.00      3761456.75     10513721.00
      3760144.75     10513614.00      3759556.00     10513770.00
      3759188.50     10513670.00      3759029.00     10513714.00
      3758910.00     10513999.00      3758684.00     10514049.00
      3757574.50     10513944.00      3757500.00     10514171.00
      3756821.00     10514077.00      3756448.50     10513420.00
      3756120.75     10513488.00      3755721.25     10512905.00
      3755520.25     10512900.00      3755411.75     10512358.00
      3755007.50     10512086.00      3754663.25     10511539.00
      3754627.75     10511163.00      3755014.75     10510700.00
      3754954.50     10509670.00      3755214.25     10509661.00
      3755075.50     10509475.00      3755499.50     10509256.00
      3755464.50     10509132.00      3754958.75     10509110.00

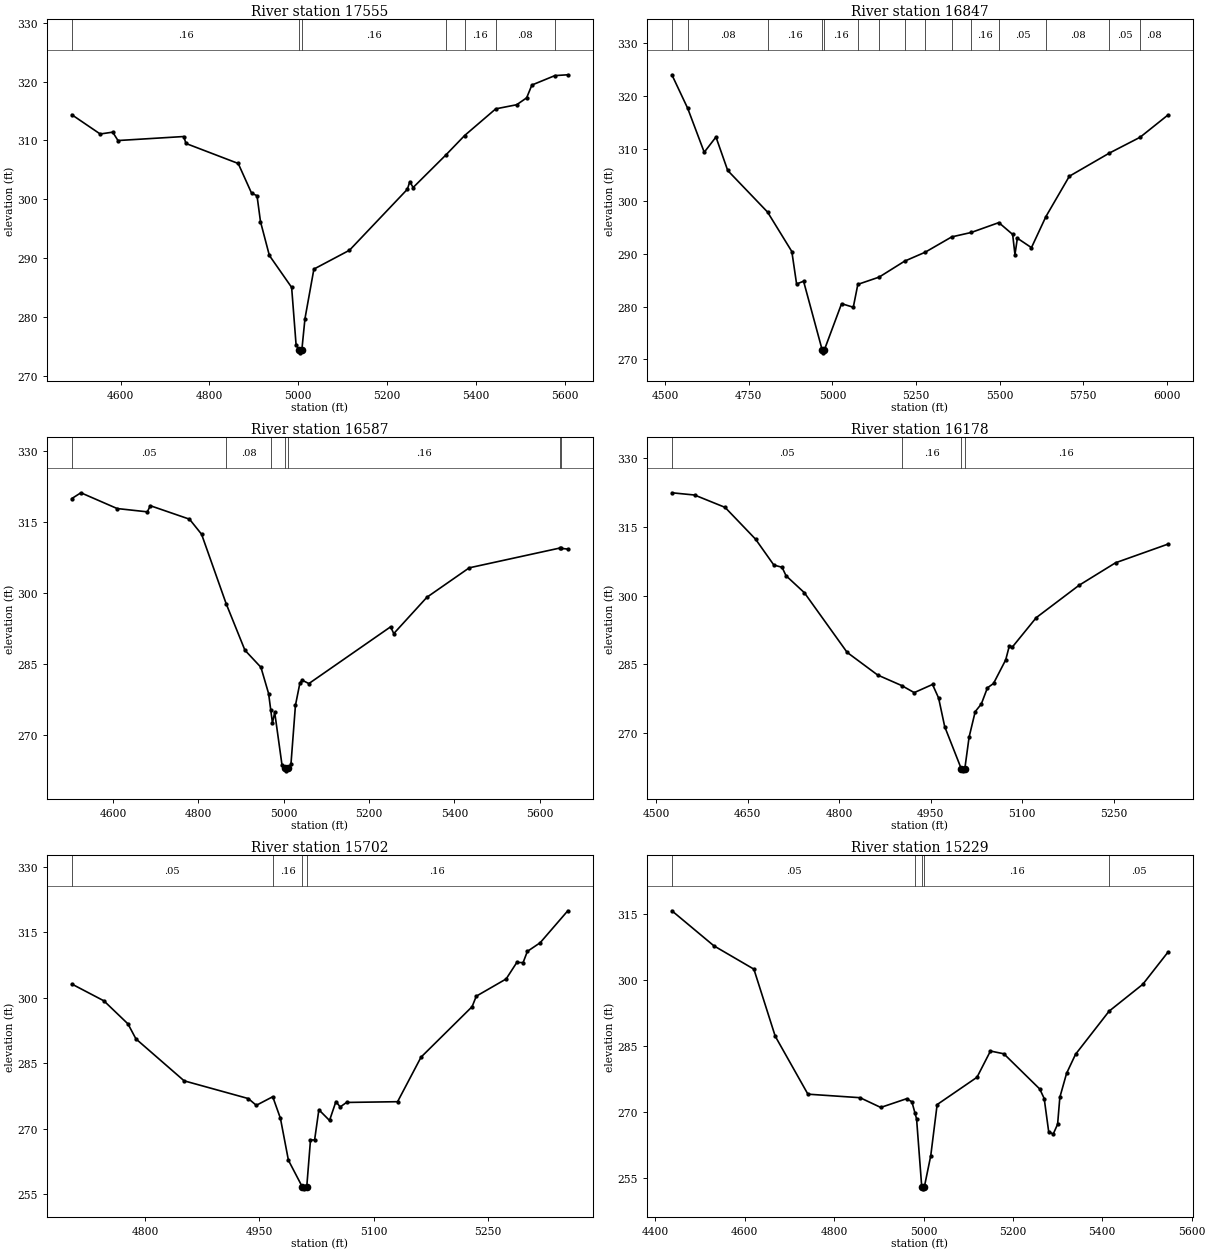
Type RM Length L Ch R = 1,17555,708,708,708
BEGIN DESCRIPTION:
MERIWETHER BRANCH 27.0
END DESCRIPTION:
XS GIS Cut Line= 3
      3764970.59     10514336.37      3764922.84     10515095.94
      3765083.44     10515412.80
#Sta/Elev= 30
  4490.3  314.37  4554.2  311.10  4582.4  311.41  4594.3  309.99  4742.3  310.67
  4747.3  309.49  4864.9  306.10  4894.9  301.07  4907.2  300.63  4915.0  296.24
  4935.0  290.50  4985.1  285.09  4995.1  275.36  5002.1  274.49  5004.9  273.99
  5008.1  274.49  5015.1  279.79  5035.2  288.19  5115.3  291.39  5245.6  301.73
  5251.0  303.02  5258.5  302.02  5332.2  307.54  5374.3  310.83  5444.4  315.36
  5491.6  316.06  5514.0  317.23  5525.8  319.40  5577.6  321.00  5606.6  321.14
#Mann=7,-1,0
  4490.3    0.16       0  5002.1    0.07       0  5008.1    0.16       0
  5332.2    0.05       0  5374.3    0.16       0  5444.4    0.08       0
  5577.6    0.05       0
Bank Sta=5002.1,5008.1
Exp/Cntr=0.3,0.1

Type RM Length L Ch R = 1,16847,260,260,260
BEGIN DESCRIPTION:
Mapping XS e8d6a67d
END DESCRIPTION:
XS GIS Cut Line= 4
      3764028.77     10514214.89      3764306.52     10514531.70
      3764362.95     10514657.57      3765000.63     10515325.61
#Sta/Elev= 30
  4519.9  323.99  4567.2  317.62  4616.6  309.29  4651.7  312.18  4686.8  305.83
  4805.8  297.95  4878.5  290.45  4892.7  284.29  4913.6  284.82  4969.4  271.73
  4972.2  271.23  4975.4  271.73  5027.2  280.56  5062.2  279.88  5075.8  284.22
  5139.5  285.60  5215.7  288.63  5277.1  290.32  5356.5  293.23  5414.8  294.07
  5497.3  295.94  5538.6  293.70  5545.5  289.87  5552.7  292.98  5594.8  291.19
  5638.1  297.09  5708.1  304.74  5827.7  309.13  5919.7  312.14  6002.7  316.35
#Mann=15,-1,0
  4519.9    0.05       0  4567.2    0.08       0  4805.8    0.16       0
  4969.4    0.07       0  4975.4    0.16       0  5075.8    0.05       0
  5139.5    0.16       0  5215.7    0.08       0  5277.1    0.16       0
  5356.5    0.08       0  5414.8    0.16       0  5497.3    0.05       0
  5638.1    0.08       0  5827.7    0.05       0  5919.7    0.08       0
Bank Sta=4969.4,4975.4
Exp/Cntr=0.3,0.1

Type RM Length L Ch R = 1,16587,409,409,409
BEGIN DESCRIPTION:
MERIWETHER BRANCH 26.0
END DESCRIPTION:
XS GIS Cut Line= 4
      3763766.39     10514193.17      3764039.81     10514474.41
      3764110.13     10514695.76      3764503.35     10515062.95
#Sta/Elev= 30
  4503.1  320.05  4524.5  321.27  4609.4  317.94  4680.2  317.24  4687.1  318.54
  4779.0  315.69  4807.3  312.51  4865.0  297.81  4908.9  288.00  4946.4  284.39
  4964.4  278.84  4969.3  275.46  4973.4  272.63  4978.7  274.86  4995.8  263.75
  5002.7  263.01  5005.4  262.51  5008.7  263.01  5016.8  263.93  5027.3  276.35
  5037.8  281.08  5043.2  281.66  5058.8  280.95  5250.4  292.95  5257.7  291.51
  5335.4  299.19  5434.6  305.41  5647.4  309.60  5649.5  309.53  5665.6  309.37
#Mann=7,-1,0
  4503.1    0.05       0  4865.0    0.08       0  4969.3    0.16       0
  5002.7    0.07       0  5008.7    0.16       0  5647.4    0.08       0
  5649.5    0.16       0
Bank Sta=5002.7,5008.7
Exp/Cntr=0.3,0.1

Type RM Length L Ch R = 1,16178,476,476,476
BEGIN DESCRIPTION:
MERIWETHER BRANCH 25.0
END DESCRIPTION:
XS GIS Cut Line= 2
      3763659.84     10514153.03      3763681.51     10514965.95
#Sta/Elev= 30
  4525.5  322.38  4562.7  321.89  4612.7  319.20  4662.7  312.27  4692.7  306.63
  4706.1  306.15  4712.7  304.30  4742.7  300.61  4812.8  287.61  4862.8  282.68
  4902.4  280.37  4922.8  278.84  4952.8  280.62  4962.8  277.66  4972.8  271.42
  4999.8  262.30  5002.6  261.80  5005.8  262.30  5012.8  269.16  5022.8  274.70
  5032.8  276.36  5042.8  279.88  5052.8  280.83  5072.8  285.98  5078.7  289.00
  5083.8  288.79  5122.9  295.18  5192.9  302.21  5252.9  307.13  5338.7  311.19
#Mann=4,-1,0
  4525.5    0.05       0  4902.4    0.16       0  4999.8    0.07       0
  5005.8    0.16       0
Bank Sta=4999.8,5005.8
Exp/Cntr=0.3,0.1

Type RM Length L Ch R = 1,15702,473,473,473
BEGIN DESCRIPTION:
MERIWETHER BRANCH 24.0
END DESCRIPTION:
XS GIS Cut Line= 3
      3763149.61     10514360.19      3763249.61     10514660.19
      3763399.59     10514960.16
#Sta/Elev= 30
  4703.6  303.17  4745.8  299.31  4777.4  294.02  4787.9  290.57  4851.2  280.95
  4935.5  276.88  4946.0  275.33  4967.6  277.30  4977.7  272.34  4988.2  262.72
  5006.3  256.66  5009.0  256.16  5012.3  256.66  5017.2  267.38  5022.6  267.38
  5028.2  274.31  5042.2  271.85  5050.6  276.19  5056.2  274.95  5064.5  275.99
  5131.6  276.16  5162.4  286.38  5229.5  297.97  5235.0  300.38  5274.2  304.33
  5288.2  308.11  5296.5  308.09  5302.1  310.66  5318.9  312.64  5355.2  319.98
#Mann=4,-1,0
  4703.6    0.05       0  4967.6    0.16       0  5006.3    0.07       0
  5012.3    0.16       0
Bank Sta=5006.3,5012.3
Exp/Cntr=0.3,0.1

Type RM Length L Ch R = 1,15229,475,475,475
BEGIN DESCRIPTION:
MERIWETHER BRANCH 23.0
END DESCRIPTION:
XS GIS Cut Line= 3
      3763012.83     10514230.94      3762807.97     10514842.03
      3762842.61     10515306.23
#Sta/Elev= 30
  4436.8  315.67  4530.9  307.72  4620.3  302.44  4668.0  287.25  4741.2  274.10
  4857.9  273.30  4904.2  271.09  4962.1  273.07  4973.9  272.37  4981.0  269.75
  4984.4  268.49  4995.9  253.14  4998.6  252.64  5001.9  253.14  5016.1  260.14
  5030.4  271.74  5119.6  277.93  5149.7  283.88  5179.7  283.25  5260.0  275.27
  5270.0  273.11  5280.0  265.61  5290.1  265.04  5300.0  267.29  5305.0  273.39
  5320.1  278.83  5340.2  283.15  5415.3  292.92  5490.6  299.00  5546.8  306.27
#Mann=5,-1,0
  4436.8    0.05       0  4981.0    0.16       0  4995.9    0.07       0
  5001.9    0.16       0  5415.3    0.05       0
Bank Sta=4995.9,5001.9
Exp/Cntr=0.3,0.1

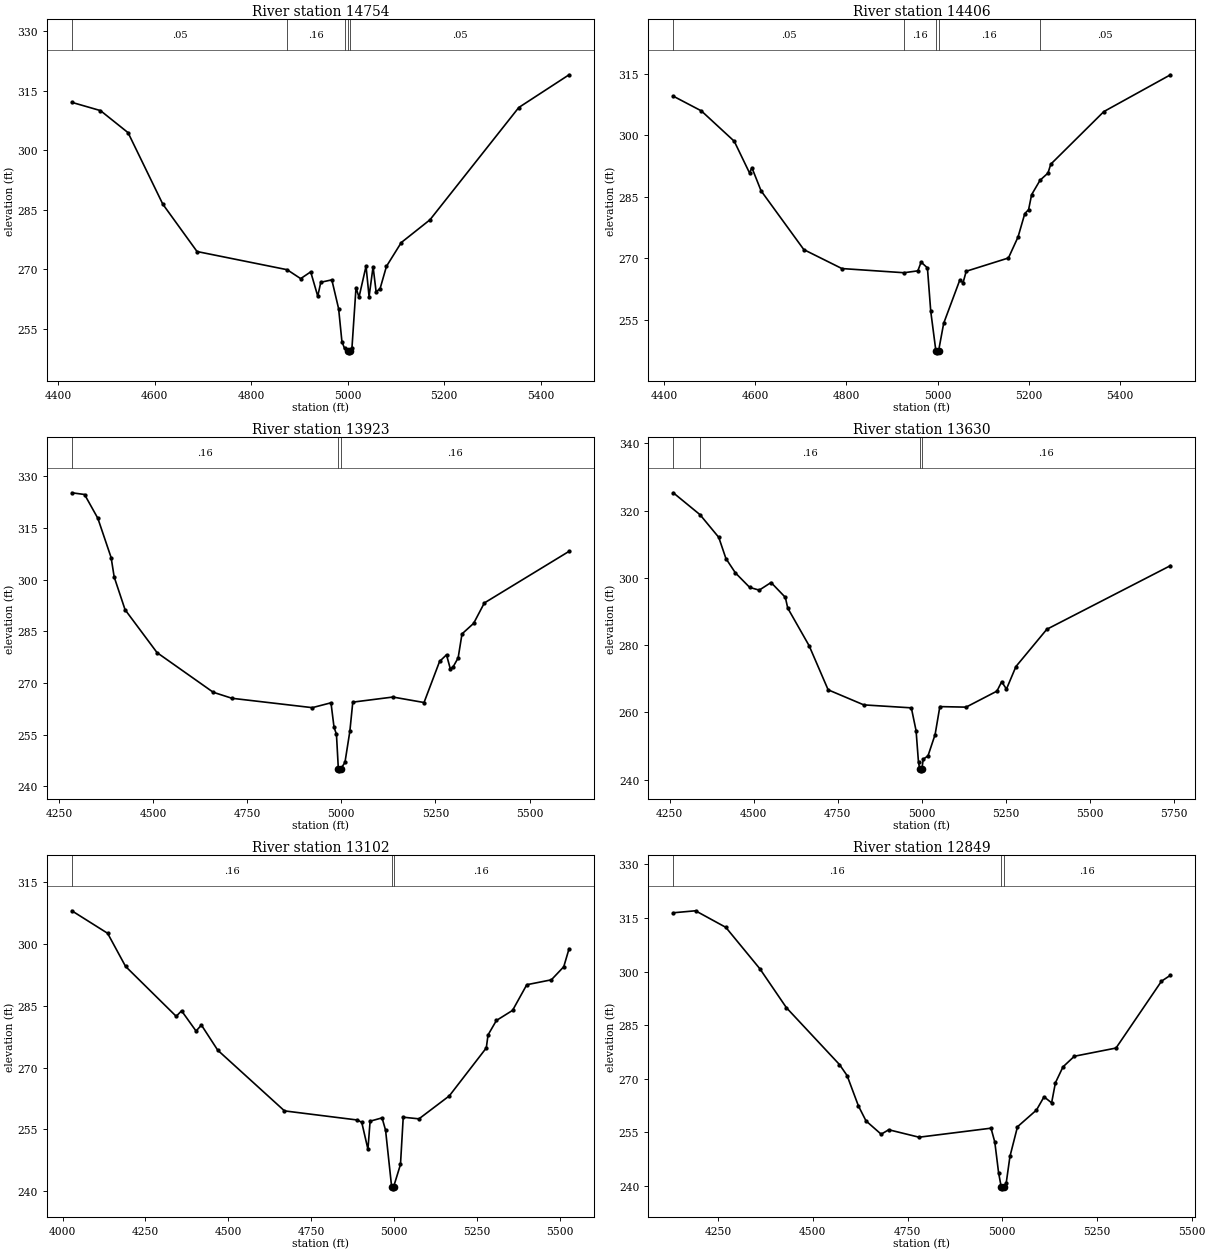
Type RM Length L Ch R = 1,14754,348,348,348
BEGIN DESCRIPTION:
MERIWETHER BRANCH 22.0
END DESCRIPTION:
XS GIS Cut Line= 3
      3762759.37     10514126.73      3762373.94     10514644.11
      3762186.46     10514980.88
#Sta/Elev= 30
  4428.2  312.03  4487.5  309.95  4544.7  304.39  4616.8  286.35  4687.7  274.42
  4874.4  269.84  4902.5  267.59  4923.3  269.29  4937.9  263.17  4944.2  266.67
  4967.1  267.28  4981.2  259.99  4988.0  251.72  4993.4  250.01  4999.6  249.38
  5002.3  248.88  5005.6  249.38  5008.8  250.10  5017.2  265.32  5023.4  262.89
  5038.0  270.73  5044.3  263.04  5052.6  270.60  5058.9  264.24  5067.2  265.10
  5080.3  270.68  5111.0  276.68  5170.5  282.42  5354.6  310.73  5458.8  318.98
#Mann=5,-1,0
  4428.2    0.05       0  4874.4    0.16       0  4993.4    0.05       0
  4999.6    0.03       0  5005.6    0.05       0
Bank Sta=4999.6,5005.6
Exp/Cntr=0.3,0.1

Type RM Length L Ch R = 1,14406,483,483,483
BEGIN DESCRIPTION:
MERIWETHER BRANCH 21.0
END DESCRIPTION:
XS GIS Cut Line= 4
      3762714.25     10514078.13      3762321.86     10514192.72
      3762130.89     10514394.11      3761902.47     10514726.35
#Sta/Elev= 30
  4420.5  309.58  4482.0  305.99  4554.1  298.58  4587.6  290.84  4592.8  292.12
  4612.9  286.48  4706.6  272.13  4790.0  267.51  4926.0  266.49  4956.4  266.95
  4963.6  269.08  4977.4  267.67  4984.7  257.05  4995.9  247.44  4998.6  246.94
  5001.9  247.44  5013.0  254.14  5048.2  264.66  5055.5  264.07  5062.4  266.85
  5154.9  270.09  5175.9  275.20  5190.8  280.93  5199.1  281.89  5205.7  285.54
  5224.2  289.06  5241.5  290.81  5247.7  292.98  5364.0  305.82  5510.0  314.80
#Mann=5,-1,0
  4420.5    0.05       0  4926.0    0.16       0  4995.9    0.07       0
  5001.9    0.16       0  5224.2    0.05       0
Bank Sta=4995.9,5001.9
Exp/Cntr=0.3,0.1

Type RM Length L Ch R = 1,13923,293,293,293
BEGIN DESCRIPTION:
MERIWETHER BRANCH 20.0
END DESCRIPTION:
XS GIS Cut Line= 3
      3762325.33     10513418.42      3761839.22     10514039.95
      3761711.02     10514556.22
#Sta/Elev= 30
  4284.0  325.19  4317.8  324.69  4353.1  317.78  4388.4  306.38  4396.5  300.76
  4425.4  291.27  4510.4  278.81  4659.6  267.32  4709.4  265.57  4922.8  262.85
  4972.5  264.26  4980.6  257.15  4987.0  255.15  4992.1  245.02  4994.9  244.52
  4998.1  245.02  5009.6  246.96  5022.6  255.98  5030.4  264.45  5137.0  265.93
  5219.7  264.34  5261.0  276.25  5279.4  278.19  5289.7  274.04  5297.2  274.74
  5310.3  277.27  5320.6  284.25  5351.5  287.31  5379.9  293.22  5605.0  308.20
#Mann=3,-1,0
  4284.0    0.16       0  4992.1    0.07       0  4998.1    0.16       0
Bank Sta=4992.1,4998.1
Exp/Cntr=0.3,0.1

Type RM Length L Ch R = 1,13630,528,528,528
BEGIN DESCRIPTION:
MERIWETHER BRANCH 19.0
END DESCRIPTION:
XS GIS Cut Line= 2
      3762184.13     10513263.24      3761154.63     10514325.25
#Sta/Elev= 30
  4260.8  325.33  4340.3  318.82  4396.1  312.08  4417.4  305.78  4445.7  301.50
  4488.2  297.19  4516.5  296.38  4551.7  298.65  4594.2  294.23  4601.3  291.04
  4664.9  279.86  4721.5  266.74  4827.6  262.26  4969.0  261.38  4983.1  254.58
  4990.3  245.13  4994.2  243.15  4997.0  242.65  5000.2  243.15  5004.4  246.10
  5018.6  247.12  5039.7  253.44  5053.8  261.75  5131.8  261.59  5223.6  266.35
  5237.8  269.16  5251.9  266.95  5280.2  273.67  5372.0  284.74  5739.9  303.67
#Mann=4,-1,0
  4260.8    0.05       0  4340.3    0.16       0  4994.2    0.07       0
  5000.2    0.16       0
Bank Sta=4994.2,5000.2
Exp/Cntr=0.3,0.1

Type RM Length L Ch R = 1,13102,253,253,253
BEGIN DESCRIPTION:
MERIWETHER BRANCH 18.0
END DESCRIPTION:
XS GIS Cut Line= 3
      3761593.74     10512845.83      3761239.57     10513496.89
      3760979.16     10514210.40
#Sta/Elev= 30
  4027.8  308.03  4135.8  302.57  4189.9  294.55  4342.8  282.44  4359.0  283.78
  4402.7  278.87  4418.9  280.32  4468.2  274.22  4669.6  259.51  4889.6  257.30
  4902.8  256.73  4921.5  250.21  4928.0  257.01  4964.1  257.82  4974.7  254.83
  4993.0  241.11  4995.8  240.61  4999.0  241.11  5019.7  246.52  5028.0  257.98
  5075.5  257.58  5167.1  263.15  5278.7  274.77  5284.0  277.93  5309.2  281.43
  5358.0  283.88  5400.9  290.10  5475.1  291.29  5512.5  294.46  5528.5  298.83
#Mann=3,-1,0
  4027.8    0.16       0  4993.0    0.07       0  4999.0    0.16       0
Bank Sta=4993,4999
Exp/Cntr=0.3,0.1

Type RM Length L Ch R = 1,12849,257,257,257
BEGIN DESCRIPTION:
Mapping XS faece4ab
END DESCRIPTION:
XS GIS Cut Line= 2
      3760921.86     10512861.44      3760911.44     10514174.00
#Sta/Elev= 30
  4131.5  316.46  4190.2  317.02  4270.2  312.38  4360.3  300.74  4430.3  289.84
  4570.3  273.92  4590.3  270.85  4620.3  262.32  4640.3  258.13  4680.3  254.40
  4700.3  255.65  4780.3  253.56  4970.3  256.09  4980.3  252.20  4990.3  243.61
  4997.3  239.59  5000.0  239.09  5003.3  239.59  5010.3  240.61  5020.3  248.18
  5040.2  256.49  5090.3  261.17  5110.3  264.88  5130.3  263.19  5140.3  268.81
  5160.3  273.27  5190.3  276.25  5300.3  278.55  5420.3  297.28  5444.1  298.96
#Mann=3,-1,0
  4131.5    0.16       0  4997.3    0.07       0  5003.3    0.16       0
Bank Sta=4997.3,5003.3
Exp/Cntr=0.3,0.1

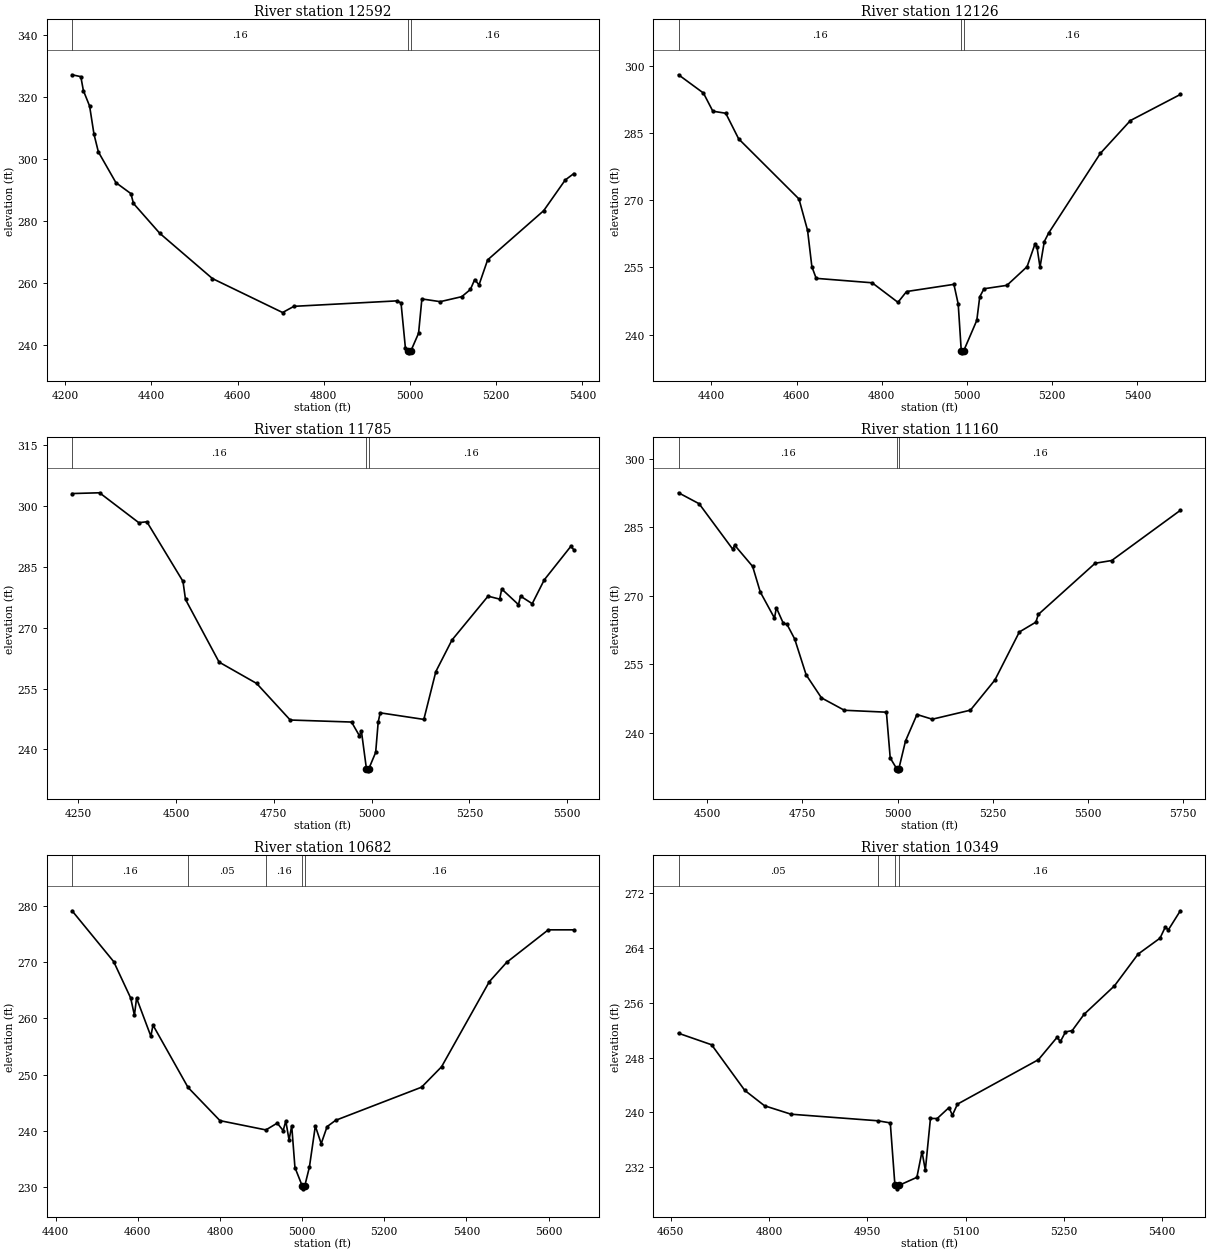
Type RM Length L Ch R = 1,12592,466,466,466
BEGIN DESCRIPTION:
MERIWETHER BRANCH 17.0
END DESCRIPTION:
XS GIS Cut Line= 3
      3760549.62     10512910.23      3760699.61     10513710.19
      3760699.61     10514060.18
#Sta/Elev= 30
  4216.1  327.29  4236.4  326.68  4242.3  322.20  4256.8  317.17  4266.9  308.11
  4277.1  302.36  4317.8  292.43  4352.6  288.88  4358.5  285.71  4419.5  276.06
  4541.6  261.44  4704.4  250.46  4730.7  252.46  4969.0  254.22  4979.1  253.58
  4989.3  238.95  4995.6  237.93  4998.4  237.43  5001.6  237.93  5019.8  243.76
  5027.5  254.85  5070.0  253.97  5120.0  255.58  5140.0  257.91  5150.0  261.11
  5160.0  259.39  5180.0  267.47  5310.0  283.37  5360.0  293.29  5380.0  295.37
#Mann=3,-1,0
  4216.1    0.16       0  4995.6    0.07       0  5001.6    0.16       0
Bank Sta=4995.6,5001.6
Exp/Cntr=0.3,0.1

Type RM Length L Ch R = 1,12126,341,341,341
BEGIN DESCRIPTION:
MERIWETHER BRANCH 16.0
END DESCRIPTION:
XS GIS Cut Line= 2
      3760333.31     10512960.47      3760166.79     10514126.14
#Sta/Elev= 30
  4323.1  297.95  4381.5  293.88  4403.6  289.83  4433.9  289.37  4464.2  283.66
  4605.7  270.26  4625.9  263.25  4636.0  255.15  4646.1  252.56  4777.4  251.57
  4838.0  247.21  4858.2  249.62  4969.3  251.22  4979.4  246.82  4986.5  236.45
  4989.3  235.95  4992.5  236.45  5023.0  243.19  5029.9  248.45  5040.0  250.24
  5093.7  251.00  5141.0  255.16  5159.3  260.16  5164.4  259.45  5171.3  255.04
  5181.4  260.76  5191.5  262.64  5312.8  280.41  5383.5  287.75  5500.6  293.56
#Mann=3,-1,0
  4323.1    0.16       0  4986.5    0.07       0  4992.5    0.16       0
Bank Sta=4986.5,4992.5
Exp/Cntr=0.3,0.1

Type RM Length L Ch R = 1,11785,625,625,625
BEGIN DESCRIPTION:
MERIWETHER BRANCH 15.0
END DESCRIPTION:
XS GIS Cut Line= 2
      3759739.56     10512923.94      3760026.02     10514173.94
#Sta/Elev= 30
  4234.6  303.03  4304.8  303.22  4405.2  295.85  4425.7  296.08  4518.0  281.40
  4524.5  276.94  4610.3  261.51  4706.3  256.25  4792.1  247.24  4948.9  246.74
  4968.9  243.37  4974.0  244.55  4986.9  235.22  4989.7  234.72  4992.9  235.22
  5010.5  239.26  5016.9  246.69  5022.0  249.01  5133.6  247.39  5164.3  259.18
  5205.4  266.93  5297.7  277.75  5327.5  277.02  5332.6  279.52  5375.5  275.66
  5380.7  277.76  5410.6  275.90  5441.3  281.76  5509.4  290.04  5517.0  289.16
#Mann=3,-1,0
  4234.6    0.16       0  4986.9    0.07       0  4992.9    0.16       0
Bank Sta=4986.9,4992.9
Exp/Cntr=0.3,0.1

Type RM Length L Ch R = 1,11160,478,478,478
BEGIN DESCRIPTION:
MERIWETHER BRANCH 14.0
END DESCRIPTION:
XS GIS Cut Line= 3
      3759281.24     10513106.30      3759343.73     10513783.35
      3759734.34     10514288.53
#Sta/Elev= 30
  4424.6  292.54  4478.7  290.14  4567.1  280.17  4572.1  281.06  4619.3  276.41
  4639.4  270.80  4676.7  265.08  4681.7  267.34  4699.7  263.98  4709.7  263.70
  4729.8  260.51  4759.9  252.65  4800.1  247.61  4860.3  244.89  4970.8  244.47
  4980.8  234.45  4997.6  232.12  5000.3  231.62  5003.6  232.12  5021.0  238.16
  5051.1  243.96  5091.3  242.93  5191.5  244.91  5255.8  251.51  5320.1  262.04
  5363.6  264.20  5369.9  265.88  5519.3  277.10  5562.8  277.70  5743.1  288.69
#Mann=3,-1,0
  4424.6    0.16       0  4997.6    0.07       0  5003.6    0.16       0
Bank Sta=4997.6,5003.6
Exp/Cntr=0.3,0.1

Type RM Length L Ch R = 1,10682,333,333,333
BEGIN DESCRIPTION:
MERIWETHER BRANCH 13.0
END DESCRIPTION:
XS GIS Cut Line= 4
      3758734.37     10513382.33      3758833.32     10513752.10
      3759057.28     10513934.39      3759234.34     10514455.17
#Sta/Elev= 30
  4440.0  279.13  4541.3  270.09  4582.7  263.61  4591.8  260.55  4597.0  263.60
  4631.8  256.82  4637.0  258.79  4722.3  247.71  4800.1  241.80  4911.9  240.15
  4939.5  241.36  4953.9  240.03  4960.3  241.74  4968.3  238.34  4974.7  240.90
  4982.6  233.46  5000.4  230.17  5003.2  229.67  5006.4  230.17  5017.8  233.54
  5032.2  240.84  5046.5  237.71  5060.9  240.74  5081.7  241.86  5290.8  247.75
  5339.5  251.38  5455.7  266.51  5497.9  269.95  5599.3  275.74  5661.6  275.74
#Mann=5,-1,0
  4440.0    0.16       0  4722.3    0.05       0  4911.9    0.16       0
  5000.4    0.07       0  5006.4    0.16       0
Bank Sta=5000.4,5006.4
Exp/Cntr=0.3,0.1

Type RM Length L Ch R = 1,10349,481,481,481
BEGIN DESCRIPTION:
MERIWETHER BRANCH 12.0
END DESCRIPTION:
XS GIS Cut Line= 3
      3758699.61     10513660.20      3758749.61     10514010.19
      3758649.60     10514410.24
#Sta/Elev= 30
  4661.9  251.57  4712.4  249.89  4762.9  243.24  4793.2  240.98  4833.6  239.75
  4966.1  238.79  4985.1  238.48  4992.2  229.35  4995.0  228.85  4998.2  229.35
  5025.7  230.53  5033.5  234.29  5038.6  231.57  5046.4  239.13  5056.7  239.12
  5074.7  240.72  5079.9  239.60  5087.6  241.22  5211.3  247.72  5239.6  250.97
  5244.8  250.37  5252.5  251.76  5262.8  251.97  5280.9  254.34  5327.3  258.50
  5363.3  263.13  5396.8  265.46  5404.6  267.03  5409.7  266.70  5427.8  269.46
#Mann=4,-1,0
  4661.9    0.05       0  4966.1    0.16       0  4992.2    0.07       0
  4998.2    0.16       0
Bank Sta=4992.2,4998.2
Exp/Cntr=0.3,0.1

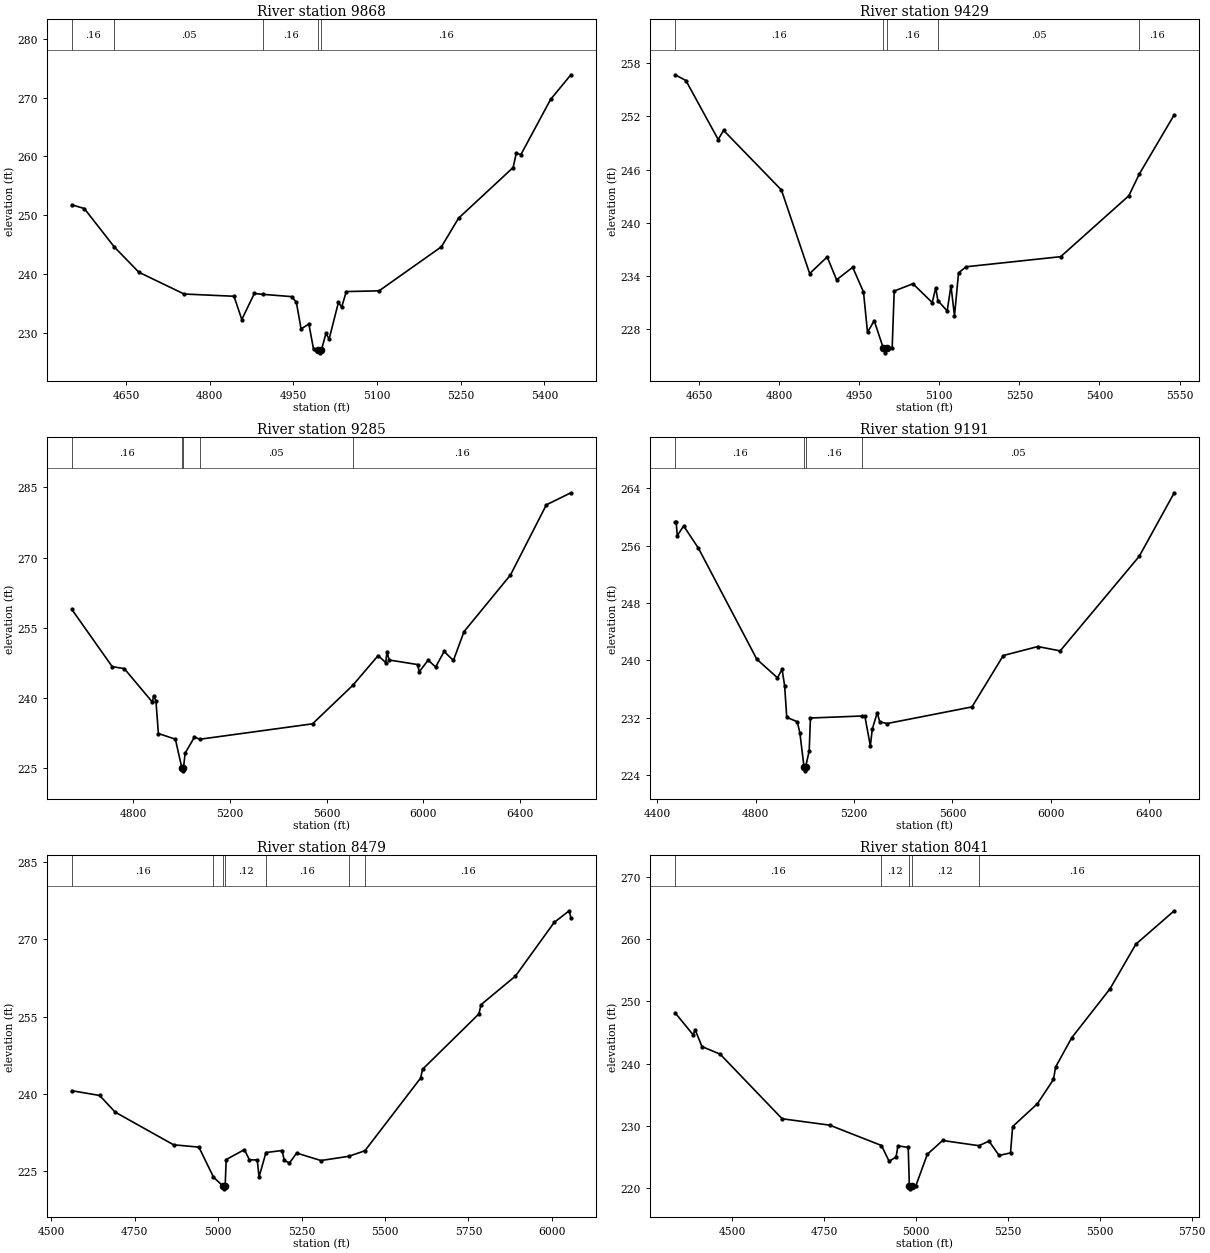
Type RM Length L Ch R = 1,9868,439,439,439
BEGIN DESCRIPTION:
MERIWETHER BRANCH 11.0
END DESCRIPTION:
XS GIS Cut Line= 3
      3758099.59     10513660.16      3758299.61     10514060.19
      3758499.63     10514460.23
#Sta/Elev= 30
  4552.8  251.80  4575.2  251.16  4629.0  244.63  4673.0  240.34  4754.1  236.64
  4843.5  236.26  4857.5  232.31  4879.9  236.73  4895.9  236.58  4946.9  236.20
  4955.3  235.24  4963.7  230.71  4977.7  231.54  4986.1  227.24  4994.2  227.15
  4997.0  226.65  5000.2  227.15  5008.4  229.96  5014.0  228.99  5030.8  235.27
  5036.4  234.39  5044.8  237.06  5103.5  237.18  5215.3  244.67  5246.0  249.52
  5343.8  258.13  5349.4  260.54  5357.8  260.33  5410.9  269.69  5447.3  273.88
#Mann=5,-1,0
  4552.8    0.16       0  4629.0    0.05       0  4895.9    0.16       0
  4994.2    0.07       0  5000.2    0.16       0
Bank Sta=4994.2,5000.2
Exp/Cntr=0.3,0.1

Type RM Length L Ch R = 1,9429,144,144,144
BEGIN DESCRIPTION:
MERIWETHER BRANCH 10.0
END DESCRIPTION:
XS GIS Cut Line= 3
      3757849.61     10513610.24      3757899.61     10514010.19
      3758249.63     10514410.21
#Sta/Elev= 30
  4605.4  256.71  4625.5  256.06  4686.0  249.40  4696.1  250.43  4804.4  243.70
  4857.3  234.26  4890.1  236.14  4907.7  233.56  4937.9  234.97  4958.1  232.18
  4965.6  227.64  4978.2  228.93  4995.4  225.81  4998.1  225.31  5001.4  225.81
  5011.8  225.84  5015.6  232.29  5050.7  233.11  5086.8  230.99  5093.4  232.66
  5097.4  231.21  5114.8  230.04  5121.9  232.88  5128.5  229.48  5136.1  234.34
  5150.4  235.03  5327.4  236.17  5455.0  243.05  5474.3  245.47  5540.0  252.19
#Mann=5,-1,0
  4605.4    0.16       0  4995.4    0.07       0  5001.4    0.16       0
  5097.4    0.05       0  5474.3    0.16       0
Bank Sta=4995.4,5001.4
Exp/Cntr=0.3,0.1

Type RM Length L Ch R = 1,9285,94,94,94
BEGIN DESCRIPTION:
Mapping XS b0b211f6
END DESCRIPTION:
XS GIS Cut Line= 3
      3757812.48     10513554.20      3757744.78     10514147.93
      3758432.27     10515444.80
#Sta/Elev= 30
  4545.9  258.93  4713.0  246.71  4763.3  246.27  4879.6  239.11  4884.6  240.49
  4894.1  239.37  4904.2  232.42  4974.6  231.21  5001.8  224.95  5004.6  224.45
  5007.8  224.95  5014.9  228.22  5053.4  231.66  5076.0  231.20  5542.2  234.49
  5708.5  242.70  5813.8  249.07  5844.9  247.57  5850.6  249.90  5859.1  248.12
  5976.9  247.15  5983.6  245.60  6020.8  248.10  6051.5  246.62  6086.8  249.94
  6125.1  248.02  6169.1  254.18  6361.4  266.28  6509.7  281.25  6611.3  283.83
#Mann=5,-1,0
  4545.9    0.16       0  5001.8    0.07       0  5007.8    0.16       0
  5076.0    0.05       0  5708.5    0.16       0
Bank Sta=5001.8,5007.8
Exp/Cntr=0.3,0.1

Type RM Length L Ch R = 1,9191,712,712,712
BEGIN DESCRIPTION:
MERIWETHER BRANCH 9.0
END DESCRIPTION:
XS GIS Cut Line= 3
      3757786.43     10513486.51      3757635.40     10514147.93
      3757505.19     10515491.69
#Sta/Elev= 30
  4473.0  259.27  4477.1  259.27  4481.6  257.39  4507.5  258.76  4567.5  255.65
  4805.0  240.16  4888.8  237.57  4907.6  238.75  4917.8  236.49  4926.7  232.05
  4969.1  231.45  4979.9  229.90  4996.9  225.09  4999.6  224.59  5002.9  225.09
  5017.8  227.37  5022.9  231.96  5232.6  232.24  5244.1  232.22  5266.3  228.07
  5274.3  230.42  5294.4  232.71  5304.4  231.42  5334.6  231.19  5679.6  233.51
  5806.8  240.68  5947.4  241.93  6037.8  241.32  6359.3  254.52  6501.5  263.38
#Mann=4,-1,0
  4473.0    0.16       0  4996.9    0.07       0  5002.9    0.16       0
  5232.6    0.05       0
Bank Sta=4996.9,5002.9
Exp/Cntr=0.3,0.1

Type RM Length L Ch R = 1,8479,438,438,438
BEGIN DESCRIPTION:
MERIWETHER BRANCH 8.0
END DESCRIPTION:
XS GIS Cut Line= 3
      3757416.66     10513726.04      3757187.48     10514252.10
      3756714.05     10515042.90
#Sta/Elev= 30
  4561.3  240.64  4644.6  239.72  4691.4  236.48  4866.3  230.15  4942.1  229.70
  4985.8  223.88  5014.8  222.11  5017.6  221.61  5020.8  222.11  5023.9  227.29
  5078.5  229.21  5093.5  227.24  5117.0  227.21  5122.4  223.92  5143.1  228.65
  5191.2  229.04  5198.0  227.14  5213.6  226.62  5235.0  228.55  5307.7  227.10
  5391.1  227.92  5439.5  228.99  5606.4  243.08  5612.3  244.80  5781.4  255.55
  5787.3  257.32  5890.5  262.86  6007.0  273.30  6051.8  275.54  6056.8  274.22
#Mann=7,-1,0
  4561.3    0.16       0  4985.8    0.12       0  5014.8    0.07       0
  5020.8    0.12       0  5143.1    0.16       0  5391.1    0.05       0
  5439.5    0.16       0
Bank Sta=5014.8,5020.8
Exp/Cntr=0.3,0.1

Type RM Length L Ch R = 1,8041,522,522,522
BEGIN DESCRIPTION:
MERIWETHER BRANCH 7.0
END DESCRIPTION:
XS GIS Cut Line= 3
      3757088.51     10513450.06      3756869.78     10514226.06
      3756588.51     10514700.05
#Sta/Elev= 30
  4345.2  248.17  4394.3  244.61  4399.5  245.46  4418.1  242.73  4467.5  241.51
  4636.2  231.10  4765.6  230.07  4906.4  226.79  4927.2  224.25  4946.0  224.94
  4951.2  226.73  4979.1  226.49  4982.2  220.31  4985.0  219.81  4988.2  220.31
  4999.9  220.31  5031.1  225.38  5072.6  227.60  5171.6  226.76  5198.8  227.51
  5226.1  225.19  5257.3  225.60  5263.1  229.84  5330.7  233.54  5374.2  237.44
  5380.0  239.44  5423.7  244.14  5528.2  252.06  5598.3  259.23  5702.6  264.61
#Mann=5,-1,0
  4345.2    0.16       0  4906.4    0.12       0  4982.2    0.07       0
  4988.2    0.12       0  5171.6    0.16       0
Bank Sta=4982.2,4988.2
Exp/Cntr=0.3,0.1

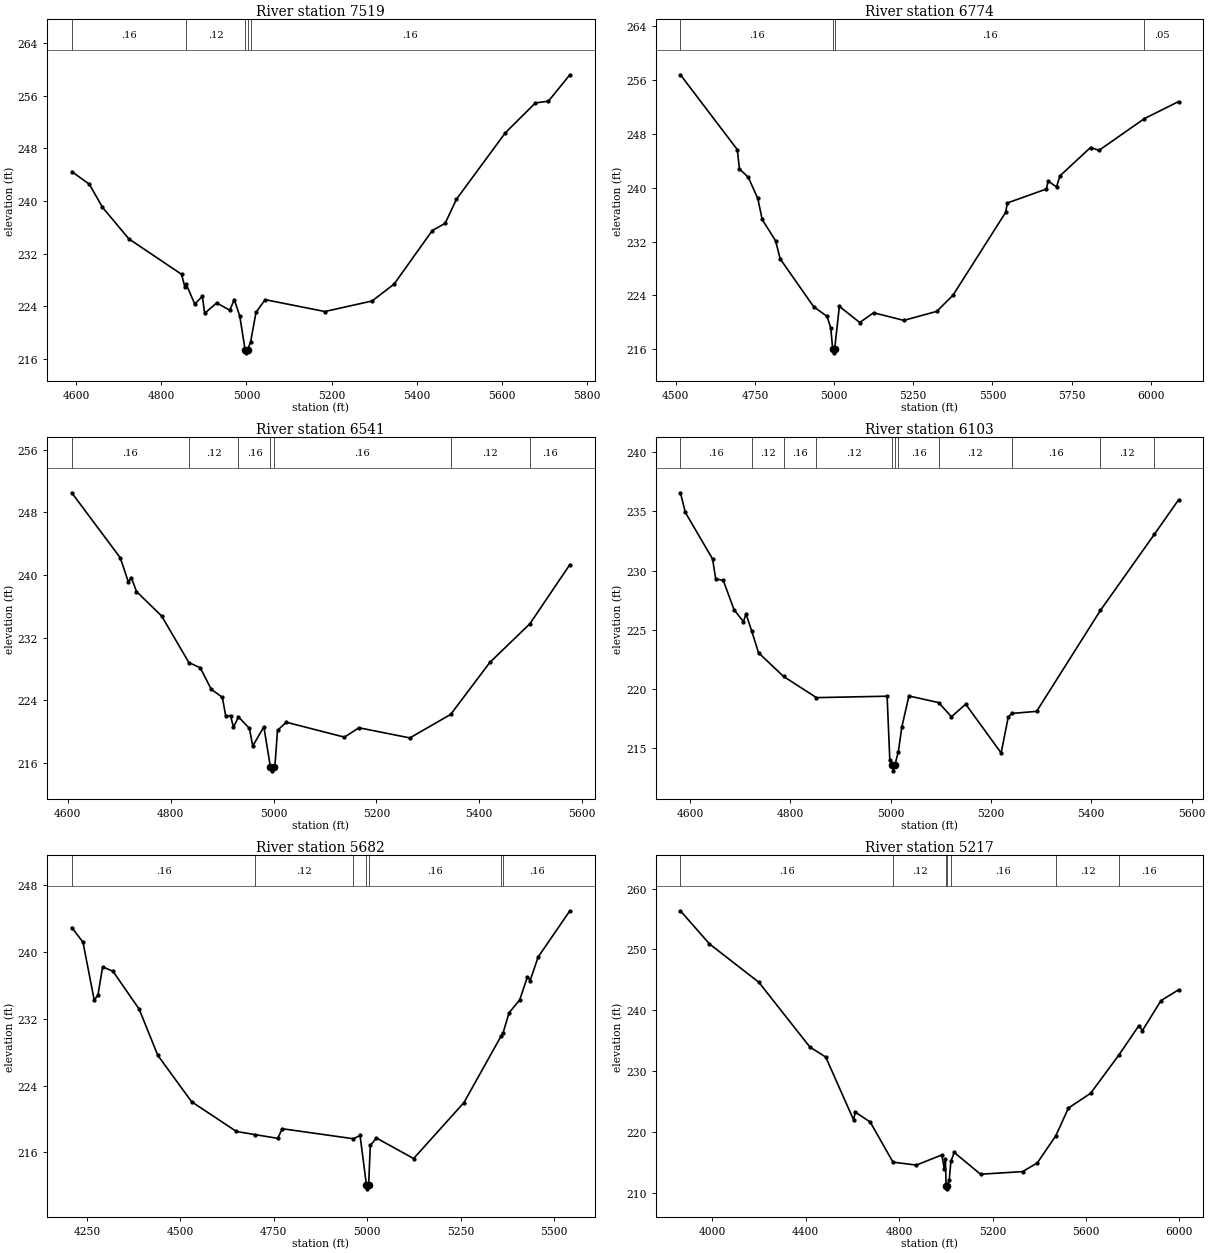
Type RM Length L Ch R = 1,7519,745,745,745
BEGIN DESCRIPTION:
MERIWETHER BRANCH 6.0
END DESCRIPTION:
XS GIS Cut Line= 3
      3756699.60     10513360.23      3756599.61     10513760.19
      3756499.61     10514510.19
#Sta/Elev= 30
  4590.0  244.49  4631.2  242.57  4662.1  239.06  4724.0  234.26  4847.6  228.88
  4855.4  226.95  4858.7  227.35  4878.6  224.36  4896.6  225.52  4901.8  222.94
  4930.1  224.53  4961.0  223.41  4971.3  225.04  4984.2  222.55  4996.7  217.44
  4999.4  216.94  5002.7  217.44  5009.5  218.52  5022.4  223.11  5043.9  225.02
  5183.9  223.22  5294.8  224.82  5346.5  227.39  5436.1  235.53  5466.3  236.63
  5492.8  240.29  5607.6  250.39  5678.2  254.93  5708.5  255.18  5758.9  259.20
#Mann=5,-1,0
  4590.0    0.16       0  4858.7    0.12       0  4996.7    0.07       0
  5002.7    0.12       0  5009.5    0.16       0
Bank Sta=4996.7,5002.7
Exp/Cntr=0.3,0.1

Type RM Length L Ch R = 1,6774,233,233,233
BEGIN DESCRIPTION:
MERIWETHER BRANCH 5.0
END DESCRIPTION:
XS GIS Cut Line= 3
      3756494.77     10513173.98      3756208.32     10513392.72
      3755839.13     10514547.10
#Sta/Elev= 30
  4514.9  256.81  4694.7  245.66  4701.0  242.81  4729.0  241.57  4759.1  238.41
  4773.0  235.28  4815.3  232.11  4829.8  229.42  4935.7  222.29  4977.7  220.87
  4989.7  219.08  4995.6  215.94  4998.4  215.44  5001.6  215.94  5016.6  222.36
  5080.9  219.95  5124.6  221.40  5220.1  220.27  5324.1  221.61  5375.6  224.03
  5541.7  236.35  5547.0  237.74  5670.4  239.82  5675.6  241.01  5702.1  240.12
  5713.0  241.77  5809.5  245.99  5836.4  245.57  5979.6  250.29  6087.3  252.82
#Mann=4,-1,0
  4514.9    0.16       0  4995.6    0.07       0  5001.6    0.16       0
  5979.6    0.05       0
Bank Sta=4995.6,5001.6
Exp/Cntr=0.3,0.1

Type RM Length L Ch R = 1,6541,438,438,438
BEGIN DESCRIPTION:
MERIWETHER BRANCH 4.0
END DESCRIPTION:
XS GIS Cut Line= 3
      3756349.58     10513160.20      3755999.61     10513360.19
      3755599.58     10513760.21
#Sta/Elev= 30
  4607.6  250.52  4701.9  242.21  4717.7  239.11  4723.5  239.67  4733.5  237.89
  4782.5  234.75  4835.4  228.80  4857.4  228.14  4878.9  225.39  4900.5  224.35
  4907.0  222.00  4916.4  222.00  4922.1  220.53  4931.9  221.85  4953.1  220.38
  4959.6  218.12  4981.2  220.58  4994.0  215.45  4996.8  214.95  5000.0  215.45
  5002.8  215.62  5007.8  220.13  5024.8  221.17  5138.0  219.26  5166.2  220.46
  5265.2  219.16  5344.6  222.17  5420.8  228.82  5498.6  233.76  5576.4  241.33
#Mann=7,-1,0
  4607.6    0.16       0  4835.4    0.12       0  4931.9    0.16       0
  4994.0    0.07       0  5000.0    0.16       0  5344.6    0.12       0
  5498.6    0.16       0
Bank Sta=4994,5000
Exp/Cntr=0.3,0.1

Type RM Length L Ch R = 1,6103,421,421,421
BEGIN DESCRIPTION:
MERIWETHER BRANCH 3.0
END DESCRIPTION:
XS GIS Cut Line= 3
      3756149.59     10512910.20      3755749.61     10513060.19
      3755349.58     10513460.22
#Sta/Elev= 30
  4581.0  236.58  4590.8  234.92  4645.1  230.98  4651.3  229.30  4666.4  229.17
  4687.8  226.70  4706.5  225.68  4711.8  226.33  4723.1  224.89  4736.7  223.05
  4786.6  221.05  4852.2  219.26  4993.0  219.38  4998.4  213.99  5002.5  213.57
  5005.3  213.07  5008.5  213.57  5015.4  214.69  5022.3  216.77  5036.5  219.40
  5095.7  218.84  5121.3  217.64  5149.6  218.71  5220.3  214.58  5234.4  217.60
  5241.0  217.92  5291.0  218.10  5418.1  226.63  5525.9  233.08  5573.9  235.98
#Mann=11,-1,0
  4581.0    0.16       0  4723.1    0.12       0  4786.6    0.16       0
  4852.2    0.12       0  5002.5    0.07       0  5008.5    0.12       0
  5015.4    0.16       0  5095.7    0.12       0  5241.0    0.16       0
  5418.1    0.12       0  5525.9    0.16       0
Bank Sta=5002.5,5008.5
Exp/Cntr=0.3,0.1

Type RM Length L Ch R = 1,5682,465,465,465
BEGIN DESCRIPTION:
MERIWETHER BRANCH 2.0
END DESCRIPTION:
XS GIS Cut Line= 3
      3756299.58     10512810.19      3755499.61     10512860.19
      3755149.63     10513260.16
#Sta/Elev= 30
  4209.6  242.93  4239.6  241.18  4269.7  234.24  4279.7  234.84  4292.2  238.22
  4319.8  237.70  4389.9  233.16  4440.0  227.61  4530.2  222.07  4650.4  218.50
  4701.0  218.12  4760.6  217.68  4773.2  218.83  4963.4  217.63  4981.1  218.03
  4998.1  212.13  5000.9  211.63  5004.1  212.13  5008.6  216.83  5024.9  217.72
  5124.5  215.26  5259.3  221.97  5358.7  229.94  5364.1  230.35  5379.9  232.72
  5408.3  234.26  5429.2  237.04  5436.3  236.58  5457.7  239.40  5542.6  244.94
#Mann=7,-1,0
  4209.6    0.16       0  4701.0    0.12       0  4963.4    0.16       0
  4998.1    0.07       0  5004.1    0.16       0  5358.7    0.12       0
  5364.1    0.16       0
Bank Sta=4998.1,5004.1
Exp/Cntr=0.3,0.1

Type RM Length L Ch R = 1,5217,820,820,820
BEGIN DESCRIPTION:
Mapping XS 57f418f2
END DESCRIPTION:
XS GIS Cut Line= 3
      3756476.69     10512102.20      3755261.40     10512525.38
      3754990.68     10513326.72
#Sta/Elev= 30
  3863.6  256.35  3987.6  250.92  4199.4  244.61  4418.2  233.97  4485.7  232.34
  4604.8  222.04  4612.3  223.29  4675.9  221.68  4773.8  215.08  4874.0  214.60
  4982.9  216.27  4993.0  214.01  4998.3  215.63  5001.1  211.20  5003.9  210.70
  5007.1  211.20  5014.7  212.22  5021.6  215.19  5035.9  216.68  5148.5  213.10
  5328.8  213.53  5391.7  214.96  5470.9  219.41  5525.0  223.97  5620.0  226.39
  5741.7  232.71  5826.8  237.51  5841.6  236.67  5921.2  241.61  5996.3  243.37
#Mann=7,-1,0
  3863.6    0.16       0  4773.8    0.12       0  5001.1    0.07       0
  5007.1    0.12       0  5021.6    0.16       0  5470.9    0.12       0
  5741.7    0.16       0
Bank Sta=5001.1,5007.1
Exp/Cntr=0.3,0.1

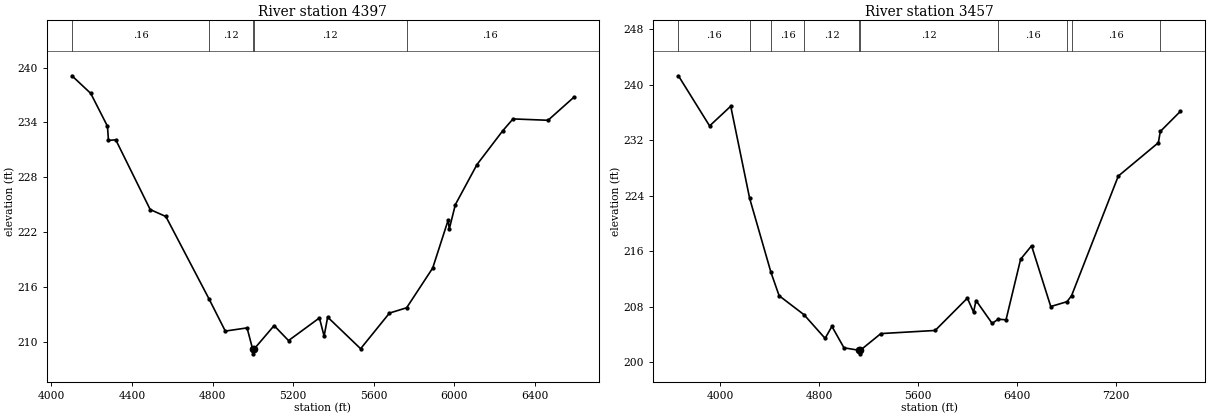
Type RM Length L Ch R = 1,4397,940,940,940
BEGIN DESCRIPTION:
Mapping XS dc38db15
END DESCRIPTION:
XS GIS Cut Line= 3
      3755803.92     10511722.43      3754838.22     10511961.15
      3754523.64     10513425.57
#Sta/Elev= 30
  4101.9  239.10  4195.3  237.17  4278.2  233.58  4283.3  232.03  4319.6  232.09
  4490.5  224.46  4568.3  223.70  4783.6  214.64  4863.5  211.16  4971.6  211.51
  4999.5  209.17  5002.3  208.67  5005.5  209.17  5105.9  211.76  5177.5  210.12
  5330.9  212.60  5354.2  210.61  5371.8  212.69  5535.5  209.23  5678.7  213.13
  5764.0  213.71  5893.5  218.06  5970.5  223.32  5975.7  222.32  6006.0  225.00
  6113.6  229.39  6241.2  233.08  6292.4  234.38  6466.3  234.23  6594.5  236.75
#Mann=5,-1,0
  4101.9    0.16       0  4783.6    0.12       0  4999.5    0.07       0
  5005.5    0.12       0  5764.0    0.16       0
Bank Sta=4999.5,5005.5
Exp/Cntr=0.3,0.1

Type RM Length L Ch R = 1,3457,0,0,0
BEGIN DESCRIPTION:
MERIWETHER BRANCH 1.0
END DESCRIPTION:
XS GIS Cut Line= 5
      3755890.70     10511613.91      3754480.15     10511082.24
      3754241.43     10511407.76      3754219.73     10512351.77
      3754469.30     10513523.64
#Sta/Elev= 30
  3664.7  241.31  3916.6  234.08  4087.2  236.92  4239.8  223.65  4412.4  212.95
  4478.0  209.60  4679.3  206.86  4849.3  203.45  4904.4  205.18  5001.7  202.09
  5126.9  201.72  5129.7  201.22  5132.9  201.72  5299.8  204.14  5738.3  204.59
  5998.3  209.25  6048.3  207.24  6068.3  208.91  6198.4  205.61  6246.8  206.21
  6310.6  206.13  6428.4  214.86  6516.8  216.80  6671.8  208.04  6803.0  208.74
  6839.5  209.59  7217.2  226.85  7540.9  231.66  7556.4  233.28  7718.2  236.17
#Mann=10,-1,0
  3664.7    0.16       0  4239.8    0.12       0  4412.4    0.16       0
  4679.3    0.12       0  5126.9    0.07       0  5132.9    0.12       0
  6246.8    0.16       0  6803.0    0.12       0  6839.5    0.16       0
  7556.4    0.05       0
Bank Sta=5126.9,5132.9
Exp/Cntr=0.3,0.1

Chan Stop Cuts=-1