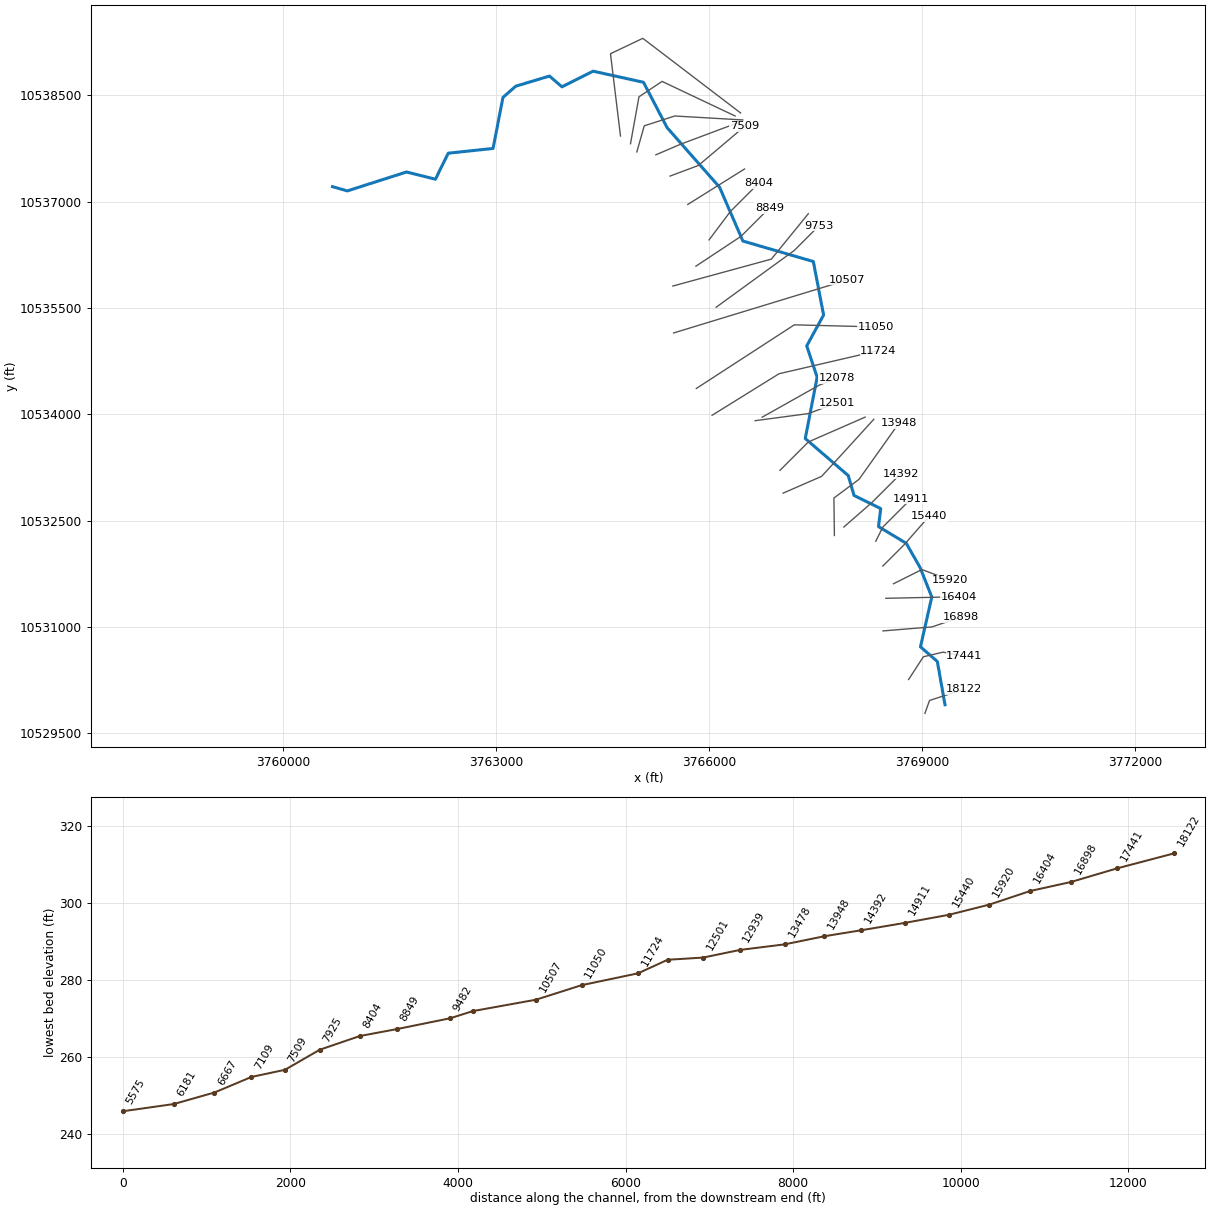
--- MURCHISON BRANCH.prj (project) ---

Proj Title=MURCHISON BRANCH Base Level Engineering
Current Plan=p01
Default Exp/Contr=0.3,0.1
English Units
Geom File=g01
Flow File=f01
Plan File=p01
Y Axis Title=Elevation
X Axis Title(PF)=Main Channel Distance
X Axis Title(XS)=Station
BEGIN DESCRIPTION:
MURCHISON BRANCH
END DESCRIPTION:
DSS Export Rating Curves= 0
DSS Export Rating Curve Sorted= 0
DSS Export Volume Flow Curves= 0
DXF OffsetX= 0
DXF OffsetY= 0
DXF ScaleX= 1
DXF ScaleY= 10

--- MURCHISON BRANCH.p01 (plan) ---

Plan Title=Multiple Run
Short Identifier=Multiple
Geom File=g01
Flow File=f01
Subcritical Flow
K Sum by GR= 0
Std Step Tol= 0.01
Critical Tol= 0.01
Num of Std Step Trials= 20
Max Error Tol= 0.3
Flow Tol Ratio= 0.001
Split Flow NTrial= 30
Split Flow Tol= 0.02
Split Flow Ratio= 0.02
Log Output Level= 0
Friction Slope Method= 1
Unsteady Friction Slope Method= 2
Unsteady Bridges Friction Slope Method= 1
Parabolic Critical Depth
Global Vel Dist=  1 , 1 , 1
Global Log Level= 0
CheckData=True
Encroach Param= -1, 0, 0, 0
BEGIN DESCRIPTION:
Multiple Run
END DESCRIPTION:

--- MURCHISON BRANCH.f01 (steady flow) ---

Flow Title=Multiple
Program Version=4.10
Number of Profiles= 7
Profile Names=10-year,25-year,50-year,1pct_min,100-year,1pct_plu,500-year
River Rch & RM=MURCHISON BRANCH,Reach-1         ,18122
     740    1020    1257    1139    1541    2083    2321
River Rch & RM=MURCHISON BRANCH,Reach-1         ,15440
    1046    1465    1824    1667    2255    3049    3458
River Rch & RM=MURCHISON BRANCH,Reach-1         ,13948
    1111    1555    1935    1767    2389    3231    3657
River Rch & RM=MURCHISON BRANCH,Reach-1         ,12501
    1342    1886    2353    2151    2908    3933    4464
River Rch & RM=MURCHISON BRANCH,Reach-1         ,8849
    1342    1886    2353    2151    2908    3933    4464
Boundary for River Rch & Prof#=MURCHISON BRANCH,Reach-1         , 1
Up Type= 0
Dn Type= 3
Dn Slope=0.006
Boundary for River Rch & Prof#=MURCHISON BRANCH,Reach-1         , 2
Up Type= 0
Dn Type= 3
Dn Slope=0.006
Boundary for River Rch & Prof#=MURCHISON BRANCH,Reach-1         , 3
Up Type= 0
Dn Type= 3
Dn Slope=0.006
Boundary for River Rch & Prof#=MURCHISON BRANCH,Reach-1         , 4
Up Type= 0
Dn Type= 3
Dn Slope=0.006
Boundary for River Rch & Prof#=MURCHISON BRANCH,Reach-1         , 5
Up Type= 0
Dn Type= 3
Dn Slope=0.006
Boundary for River Rch & Prof#=MURCHISON BRANCH,Reach-1         , 6
Up Type= 0
Dn Type= 3
Dn Slope=0.006
Boundary for River Rch & Prof#=MURCHISON BRANCH,Reach-1         , 7
Up Type= 0
Dn Type= 3
Dn Slope=0.006
DSS Import GetInterval= 0
DSS Import GetPeak= 0
DSS Import FillOption= 0

--- MURCHISON BRANCH.g01 (geometry) ---

Geom Title=Existing Conditions
Program Version=4.10

River Reach=MURCHISON BRANCH,Reach-1
Reach XY= 30
      3769325.07     10529903.72      3769217.25       10530514.
       3768979.5       10530720.      3769139.25       10531423.
        3768973.       10531841.       3768779.5       10532180.
      3768388.25       10532416.      3768419.25       10532670.
      3768042.75       10532856.      3767961.75       10533136.
      3767355.75       10533658.        3767523.       10534524.
      3767375.95     10534964.38        3767614.       10535400.
       3767469.5       10536155.      3766476.25       10536444.
       3766147.5       10537203.      3765407.75       10538044.
       3765075.5       10538683.       3764365.5       10538840.
        3763926.       10538619.       3763749.5       10538771.
       3763274.5       10538628.      3763094.25       10538470.
      3762954.75       10537750.        3762323.       10537683.
       3762142.5       10537316.        3761735.       10537418.
        3760900.       10537151.       3760691.5       10537211.

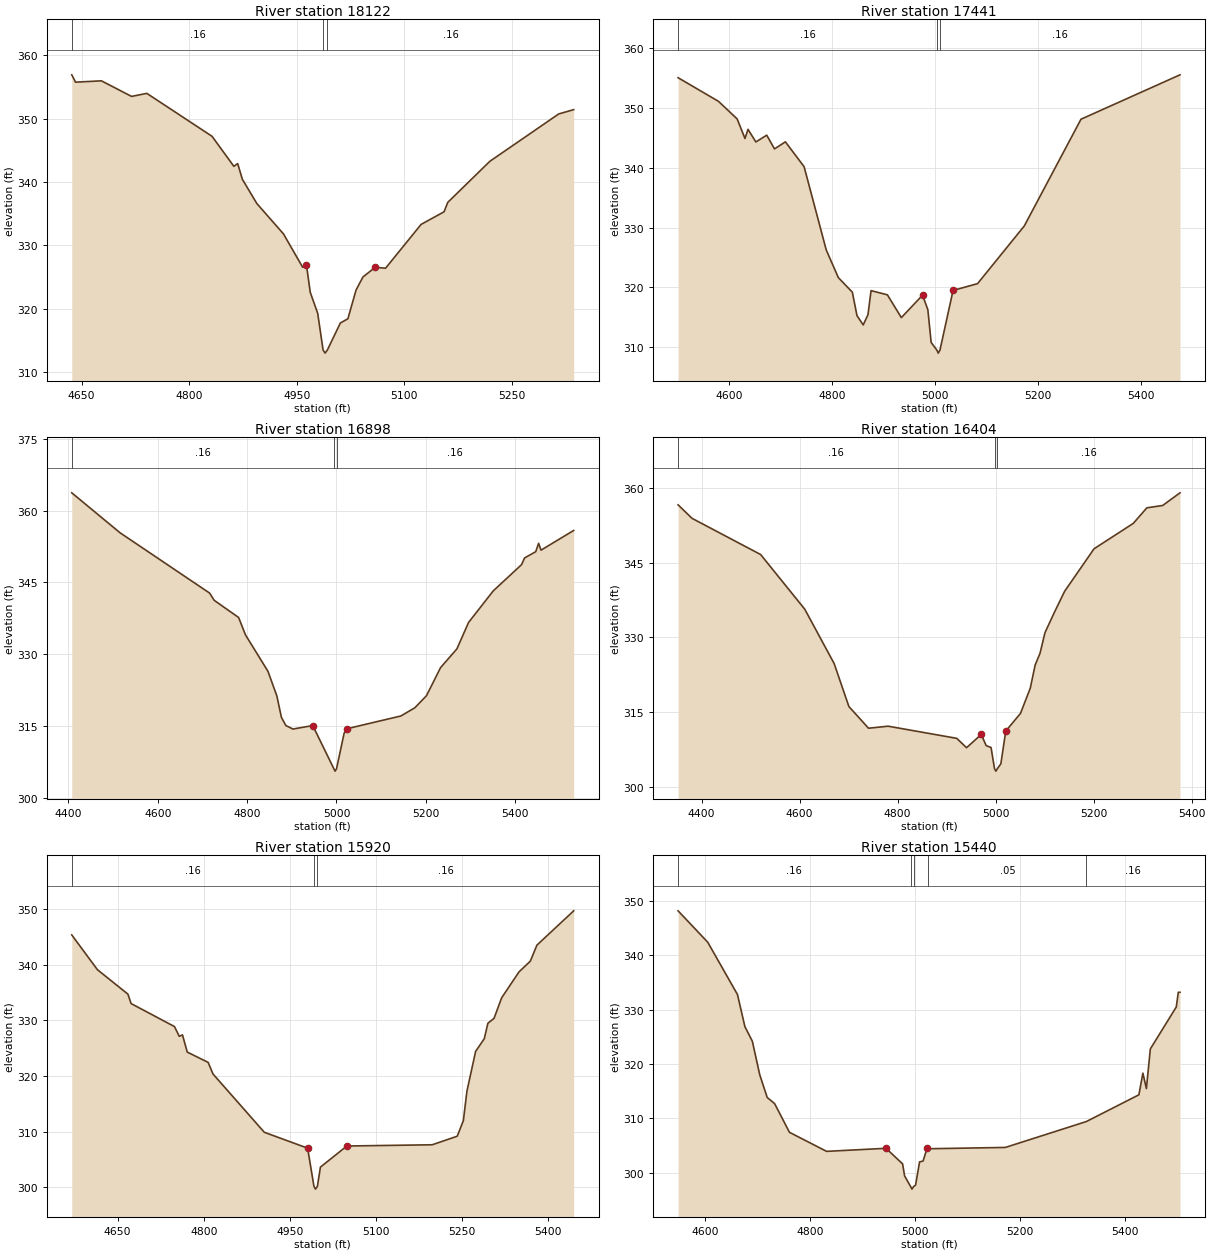
Type RM Length L Ch R = 1 ,18122   ,681,681,681
BEGIN DESCRIPTION:
MURCHISON BRANCH 25.0
END DESCRIPTION:
XS GIS Cut Line= 3
      3769042.33     10529781.62      3769107.43     10529963.89
      3769589.18     10530120.14
#Sta/Elev= 30
  4636.4  356.94  4641.7  355.78  4677.8  355.99  4719.8  353.53  4741.1  354.01
    4832  347.23  4862.5  342.48  4867.8  342.92  4874.3  340.44  4894.5  336.61
  4931.7   331.8  4958.4  326.54  4963.7   326.9    4969  322.58  4979.4  319.26
  4986.9  313.47  4989.7  312.97  4992.9  313.47    5011  317.73  5021.5   318.4
  5032.9  322.94  5042.5     325  5059.7  326.54    5074  326.38  5123.6  333.31
  5155.6   335.3  5160.8  336.79  5219.5  343.28  5315.5  350.76  5336.4  351.44
#Mann= 3 ,-1 , 0
  4636.4     .16       0  4986.9     .07       0  4992.9     .16       0
Bank Sta=4963.7,5059.7
XS Rating Curve= 0 ,0
Exp/Cntr=0.3,0.1

Type RM Length L Ch R = 1 ,17441   ,543,543,543
BEGIN DESCRIPTION:
MURCHISON BRANCH 24.0
END DESCRIPTION:
XS GIS Cut Line= 4
      3768812.26     10530258.99      3769020.62     10530580.21
       3769298.4     10530645.32      3769597.91     10530584.55
#Sta/Elev= 30
  4501.6  354.97    4580  351.03  4616.2   348.1  4631.4  344.84  4637.3  346.36
  4652.5  344.26  4673.6  345.39  4688.7   343.1  4709.8  344.28  4746.1  340.14
  4789.1  326.25  4812.6  321.64  4839.7  319.22  4848.7  315.31  4860.8  313.76
    4870  315.46    4876  319.48  4907.7  318.78  4934.8  314.98  4975.9  318.72
  4986.2   316.3  4992.6  310.84  5003.7  309.56  5006.4  309.06  5009.7  309.56
  5035.1  319.51  5082.6  320.64  5173.3  330.26  5283.3  348.05  5475.4  355.45
#Mann= 3 ,-1 , 0
  4501.6     .16       0  5003.7     .07       0  5009.7     .16       0
Bank Sta=4975.9,5035.1
XS Rating Curve= 0 ,0
Exp/Cntr=0.3,0.1

Type RM Length L Ch R = 1 ,16898   ,494,494,494
BEGIN DESCRIPTION:
MURCHISON BRANCH 23.0
END DESCRIPTION:
XS GIS Cut Line= 3
        3768452.     10530944.79      3769142.15     10531001.22
      3769550.11      10531140.1
#Sta/Elev= 30
  4407.5   363.7  4515.5  355.36  4716.1  342.75  4726.2  341.25  4780.9  337.66
  4796.4  334.01  4846.6  326.42  4866.6  321.25  4876.7  316.81  4886.7  315.08
  4902.5  314.35  4946.9  315.08  4994.1  306.06  4996.8  305.56  5000.1  306.06
  5017.1  313.49    5024  314.43  5144.1  317.08  5175.4   318.8  5201.5  321.33
  5232.9  327.18  5269.5   331.1  5295.6  336.62  5350.8  343.21  5414.2   348.7
    5421   350.1  5445.9   351.4  5452.4  353.16  5457.7  351.72  5530.9  355.84
#Mann= 3 ,-1 , 0
  4407.5     .16       0  4994.1     .07       0  5000.1     .16       0
Bank Sta=4946.9,5024
XS Rating Curve= 0 ,0
Exp/Cntr=0.3,0.1

Type RM Length L Ch R = 1 ,16404   ,484,484,484
BEGIN DESCRIPTION:
MURCHISON BRANCH 22.0
END DESCRIPTION:
XS GIS Cut Line= 2
      3768491.14     10531404.87      3769515.01     10531426.56
#Sta/Elev= 30
  4352.2  356.62  4380.7  353.91  4520.7  346.64  4610.7  335.67  4670.7  324.75
  4700.7  316.14  4740.8  311.78  4780.8  312.19  4920.8  309.75  4940.8  307.87
  4970.8  310.53  4980.8  308.29  4990.8  307.91  4997.8  303.67  5000.6  303.17
  5003.8  303.67  5010.8  304.65  5020.8  311.22  5050.8  314.75  5070.8  319.83
  5080.8  324.48  5090.8  326.86  5100.8  330.97  5120.8   335.2  5140.8  339.25
  5200.9   347.8  5280.9  352.89  5308.7  356.02  5340.9  356.49  5376.3  359.03
#Mann= 3 ,-1 , 0
  4352.2     .16       0  4997.8     .07       0  5003.8     .16       0
Bank Sta=4970.8,5020.8
XS Rating Curve= 0 ,0
Exp/Cntr=0.3,0.1

Type RM Length L Ch R = 1 ,15920   ,480,480,480
BEGIN DESCRIPTION:
MURCHISON BRANCH 21.0
END DESCRIPTION:
XS GIS Cut Line= 3
      3768599.61     10531610.19      3768999.61     10531810.19
      3769399.59     10531660.19
#Sta/Elev= 30
  4570.1  345.34  4614.8  339.09  4667.9   334.7  4673.5     333    4749  328.87
  4757.4  327.11    4763  327.37  4771.3  324.28  4807.7  322.43  4816.1  320.35
  4905.5  309.87    4981  307.01    4992  300.15  4994.7  299.65    4998  300.15
  5003.3  303.61  5049.4   307.4    5198  307.62  5241.6  309.16  5252.3  311.97
  5258.5  317.25  5273.6  324.39  5288.8   326.7    5295  329.46  5305.7  330.34
    5319  334.04  5349.3   338.7  5368.9  340.62  5380.4   343.5  5444.5  349.67
#Mann= 3 ,-1 , 0
  4570.1     .16       0    4992     .07       0    4998     .16       0
Bank Sta=4981,5049.4
XS Rating Curve= 0 ,0
Exp/Cntr=0.3,0.1

Type RM Length L Ch R = 1 ,15440   ,529,529,529
BEGIN DESCRIPTION:
MURCHISON BRANCH 20.0
END DESCRIPTION:
XS GIS Cut Line= 3
      3768449.64     10531860.22      3768749.61     10532160.19
      3769099.59     10532560.17
#Sta/Elev= 30
  4549.1  348.15  4605.6  342.38  4662.2  332.77  4676.3  326.88  4690.5  324.19
  4704.6  318.03  4718.8  313.85  4732.9  312.73  4761.2  307.45  4831.9  303.95
    4945  304.51  4976.6  301.65  4980.4  299.44  4991.7  297.51  4994.4  297.01
  4997.7  297.51  5001.3  297.74  5008.9  302.01  5015.6  302.17  5023.1  304.49
  5025.6  304.43  5172.2  304.67  5326.5  309.43  5426.5  314.34  5434.1  318.32
  5440.8  315.49  5448.3  322.77  5497.7  330.48  5501.5  333.18  5504.8  333.18
#Mann= 5 ,-1 , 0
  4549.1     .16       0  4991.7     .07       0  4997.7     .16       0
  5025.6     .05       0  5326.5     .16       0
Bank Sta=4945,5023.1
XS Rating Curve= 0 ,0
Exp/Cntr=0.3,0.1

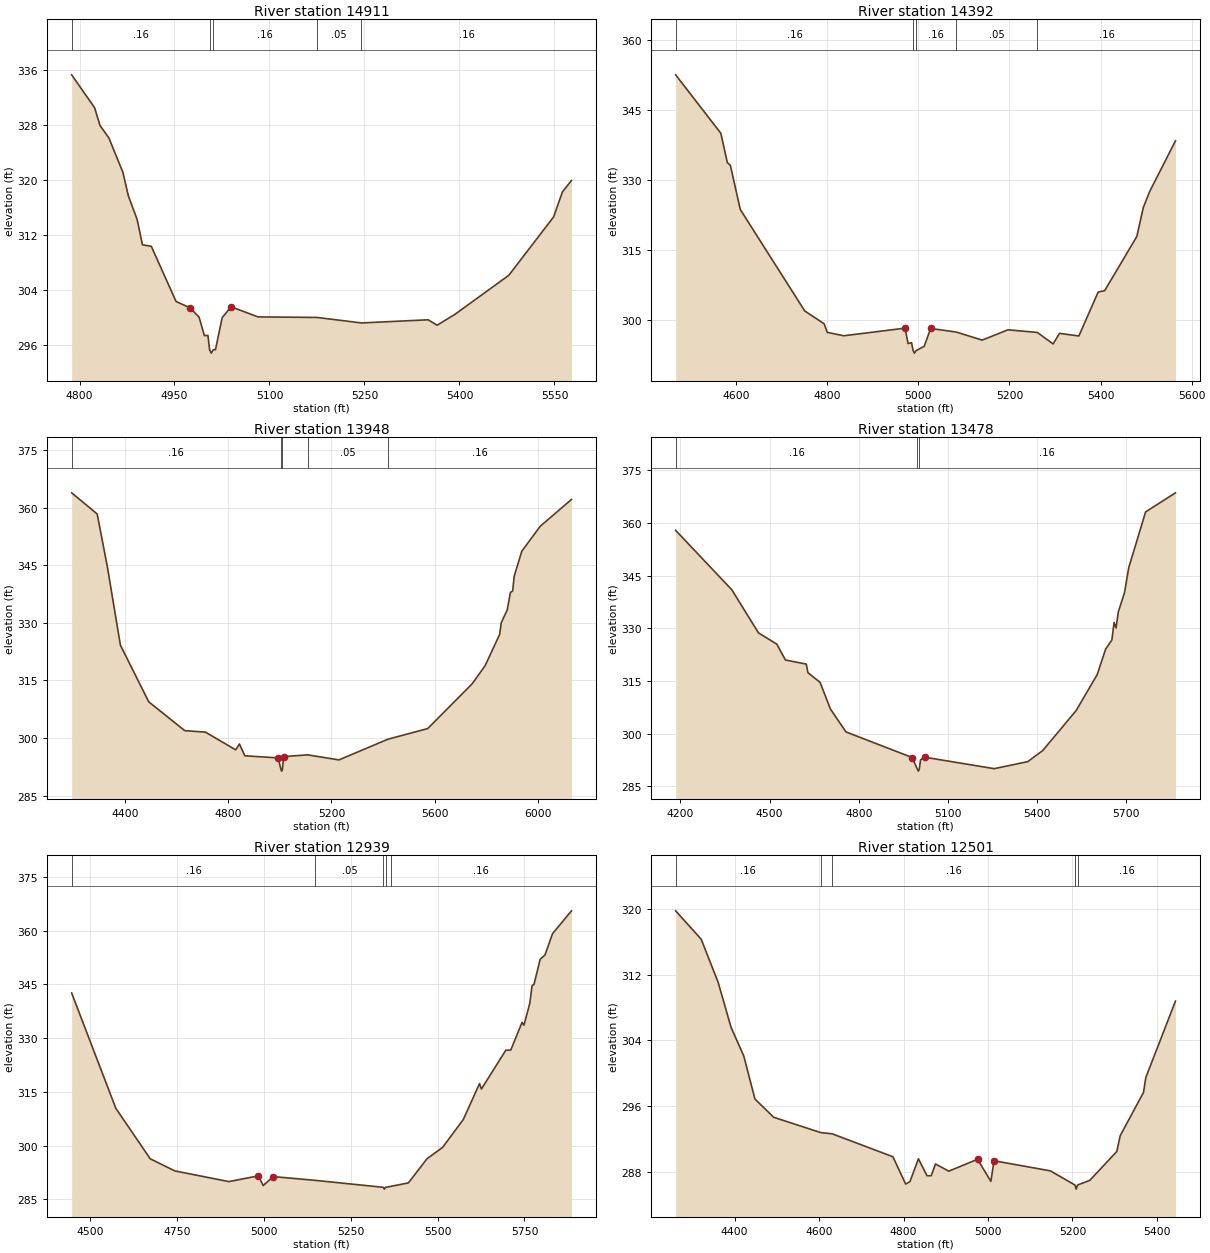
Type RM Length L Ch R = 1 ,14911   ,519,519,519
BEGIN DESCRIPTION:
MURCHISON BRANCH 19.0
END DESCRIPTION:
XS GIS Cut Line= 3
      3768349.62     10532210.21      3768449.61     10532410.19
      3768849.63     10532810.21
#Sta/Elev= 30
  4787.6  335.37  4823.9  330.58  4832.3  328.01  4846.3  326.21  4868.6  321.17
    4877  317.81    4891  314.33  4899.4  310.65  4913.4  310.42  4952.5   302.4
  4974.8  301.47  4988.8  300.12  4997.2  297.44  5002.8  297.46  5005.4  295.39
  5008.1  294.89  5011.4  295.39  5014.7  295.39  5025.3  300.06  5039.5  301.63
  5081.9  300.16  5175.1  300.08  5245.3  299.28  5350.6  299.74  5364.7  298.95
    5393  300.54  5477.9  306.21  5548.6  314.69  5562.7  318.36  5576.9     320
#Mann= 5 ,-1 , 0
  4787.6     .16       0  5005.4     .07       0  5011.4     .16       0
  5175.1     .05       0  5245.3     .16       0
Bank Sta=4974.8,5039.5
XS Rating Curve= 0 ,0
Exp/Cntr=0.3,0.1

Type RM Length L Ch R = 1 ,14392   ,444,444,444
BEGIN DESCRIPTION:
MURCHISON BRANCH 18.0
END DESCRIPTION:
XS GIS Cut Line= 3
      3767899.58     10532410.16      3768299.61     10532760.19
      3768699.58     10533160.16
#Sta/Elev= 30
  4467.3  352.62  4566.5   340.1  4580.8  333.81  4587.4  333.22  4609.2  323.76
  4750.7  302.02  4793.4  299.26    4800  297.43  4836.1   296.7  4970.9  298.33
  4977.5  295.03  4985.1  295.22  4988.7  293.48  4991.5  292.98  4994.7  293.48
    5013  294.46  5027.1  298.27  5083.5  297.49  5140.3  295.77  5196.8  297.98
  5261.3  297.41  5295.8  294.95    5310  297.22  5352.4  296.65  5394.8  306.07
    5409  306.36  5479.7  317.98  5493.8  324.16    5508  327.65  5564.5  338.48
#Mann= 5 ,-1 , 0
  4467.3     .16       0  4988.7     .07       0  4994.7     .16       0
  5083.5     .05       0  5261.3     .16       0
Bank Sta=4970.9,5027.1
XS Rating Curve= 0 ,0
Exp/Cntr=0.3,0.1

Type RM Length L Ch R = 1 ,13948   ,470,470,470
BEGIN DESCRIPTION:
MURCHISON BRANCH 17.0
END DESCRIPTION:
XS GIS Cut Line= 4
      3767766.28      10532291.1      3767759.34     10532818.93
       3768113.5     10533082.82      3768675.31     10533873.51
#Sta/Elev= 30
  4191.9  363.83    4291  358.32    4331  344.39    4381  324.21    4491  309.45
    4631  301.94    4711  301.56  4828.4  296.95    4843  298.47  4863.8   295.4
  4993.1  294.85  5003.9  291.91  5006.7  291.41  5009.9  291.91    5014  295.18
  5107.3  295.65    5229  294.33  5419.8  299.73  5573.4  302.48  5745.6   314.1
  5796.1  318.83  5852.6  326.97  5858.8  330.01    5882  333.35  5894.4  337.89
  5903.1  338.32  5909.2  342.15  5938.7  348.65  6010.1  355.13  6131.4  362.11
#Mann= 5 ,-1 , 0
  4191.9     .16       0  5003.9     .07       0  5009.9     .16       0
  5107.3     .05       0  5419.8     .16       0
Bank Sta=4993.1,5014
XS Rating Curve= 0 ,0
Exp/Cntr=0.3,0.1

Type RM Length L Ch R = 1 ,13478   ,539,539,539
BEGIN DESCRIPTION:
MURCHISON BRANCH 16.0
END DESCRIPTION:
XS GIS Cut Line= 4
      3767044.07     10532888.38      3767585.73     10533124.48
      3767905.17     10533471.71      3768321.83     10533930.03
#Sta/Elev= 30
  4183.9  357.87    4373  340.94  4462.7  328.67  4524.5  325.46  4553.4  320.95
  4623.6  319.78  4629.1  317.34  4669.9   314.6  4704.8     307  4757.2  300.47
  4979.7  293.19  4997.7  289.81  5000.5  289.31  5003.7  289.81  5008.1  292.54
  5022.3  293.27    5256  290.01  5368.8  292.01  5418.8  295.13  5531.7  306.55
  5602.6  316.81    5631  324.07  5651.9  326.62  5659.4  331.65  5666.1  330.08
  5673.6  334.64  5694.5  340.13  5708.7  347.24  5765.5  363.12    5866  368.55
#Mann= 3 ,-1 , 0
  4183.9     .16       0  4997.7     .07       0  5003.7     .16       0
Bank Sta=4979.7,5022.3
XS Rating Curve= 0 ,0
Exp/Cntr=0.3,0.1

Type RM Length L Ch R = 1 ,12939   ,438,438,438
BEGIN DESCRIPTION:
MURCHISON BRANCH 15.0
END DESCRIPTION:
XS GIS Cut Line= 3
      3766999.63     10533210.21      3767399.61     10533610.19
      3768199.64      10533960.2
#Sta/Elev= 30
  4446.4  342.61  4573.6   310.4  4672.6  296.31  4743.4  292.93  4898.9  289.94
  4983.8  291.54  4997.9  288.84  5026.5  291.34  5147.6  290.29  5343.9  288.34
  5346.7  287.84  5349.9  288.34  5366.2  288.63  5415.9  289.59  5469.3  296.32
  5514.2  299.49  5573.8  307.27  5620.6  317.32    5626  315.79  5696.2  326.63
  5710.6  326.68    5743   334.4  5748.4  333.62  5765.2  339.69  5771.8  344.66
  5777.3  344.97  5795.2  352.03  5808.9  353.21  5830.7  359.16  5885.3  365.55
#Mann= 5 ,-1 , 0
  4446.4     .16       0  5147.6     .05       0  5343.9     .07       0
  5349.9     .05       0  5366.2     .16       0
Bank Sta=4983.8,5026.5
XS Rating Curve= 0 ,0
Exp/Cntr=0.3,0.1

Type RM Length L Ch R = 1 ,12501   ,423,423,423
BEGIN DESCRIPTION:
MURCHISON BRANCH 14.0
END DESCRIPTION:
XS GIS Cut Line= 3
      3766649.56     10533910.18      3767399.61     10534010.19
      3767799.63     10534160.19
#Sta/Elev= 30
  4260.3  319.81  4320.9  316.34  4361.2  311.05  4391.5   305.6  4421.8  302.08
  4448.2  296.85  4492.4  294.63  4604.4  292.75    4631  292.61  4774.9  289.81
  4805.1  286.48  4815.2  286.78  4835.4  289.56  4855.6   287.5  4865.7  287.49
  4875.7  288.93  4907.3  288.05  4975.4   289.5  5006.9  286.81  5014.5  289.32
  5147.8  288.09  5206.2  286.36    5209  285.86  5212.2  286.36  5241.3  286.93
  5305.3  290.46  5313.4  292.39  5368.5  297.66  5373.9  299.47  5444.2   308.8
#Mann= 5 ,-1 , 0
  4260.3     .16       0  4604.4     .05       0    4631     .16       0
  5206.2     .07       0  5212.2     .16       0
Bank Sta=4975.4,5014.5
XS Rating Curve= 0 ,0
Exp/Cntr=0.3,0.1

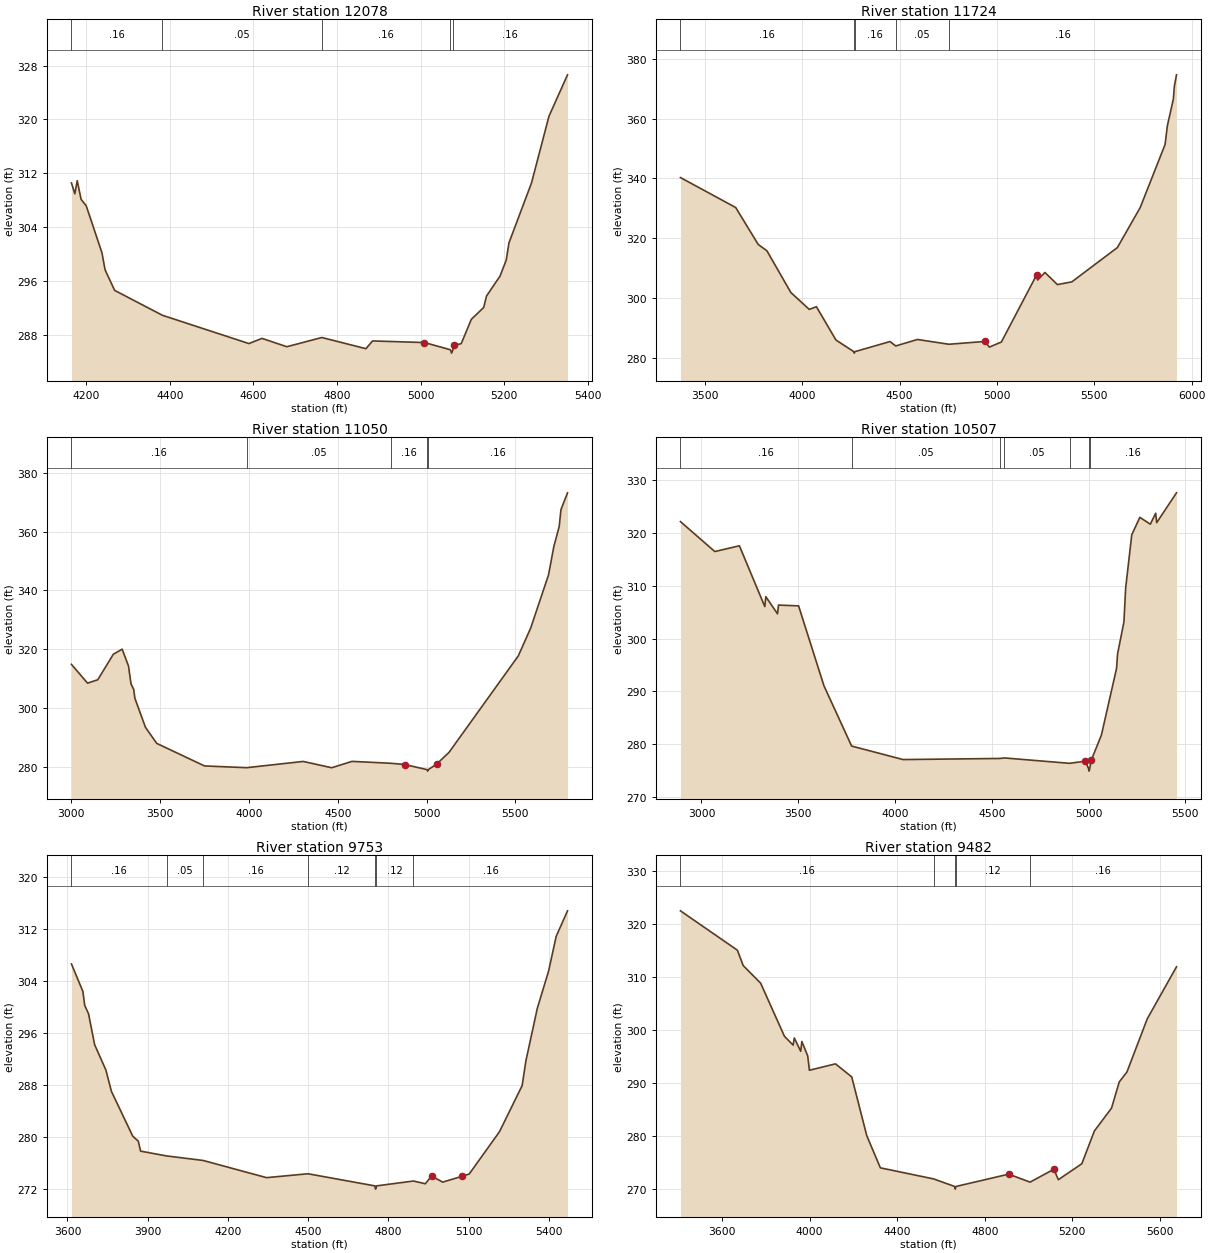
Type RM Length L Ch R = 1 ,12078   ,354,354,354
BEGIN DESCRIPTION:
MURCHISON BRANCH 13.0
END DESCRIPTION:
XS GIS Cut Line= 3
      3766749.57     10533960.16      3767549.61     10534410.19
      3767799.62     10534510.19
#Sta/Elev= 30
  4164.5  310.57  4172.5  308.95  4178.3   310.9  4187.5  308.14  4199.9  307.16
  4237.5  300.18  4244.9  297.67  4267.8  294.61  4382.2  290.91  4589.1  286.71
  4620.6  287.48  4679.9  286.24  4763.7  287.61  4869.2  285.95  4885.1   287.1
  5009.4  286.86  5071.5  285.79  5074.2  285.29  5077.5  285.79  5079.6  286.46
  5097.2  286.69  5121.5  290.31  5151.1  292.07  5157.8  293.77  5190.1  296.72
  5204.9  299.08  5211.7  301.69  5265.5  310.56  5307.3  320.47  5351.7  326.62
#Mann= 5 ,-1 , 0
  4164.5     .16       0  4382.2     .05       0  4763.7     .16       0
  5071.5     .07       0  5077.5     .16       0
Bank Sta=5009.4,5079.6
XS Rating Curve= 0 ,0
Exp/Cntr=0.3,0.1

Type RM Length L Ch R = 1 ,11724   ,674,674,674
BEGIN DESCRIPTION:
MURCHISON BRANCH 12.0
END DESCRIPTION:
XS GIS Cut Line= 3
      3766042.38     10533986.34      3766986.37     10534572.26
      3768385.39     10534897.61
#Sta/Elev= 30
  3374.9  340.31  3658.6  330.32  3774.3     318  3818.9  315.89    3942  301.96
  4036.5  296.34  4073.1  297.24  4173.5  286.13    4265  282.26  4267.7  281.76
    4271  282.26  4451.1  285.62  4480.3  284.15  4592.1  286.31  4753.4  284.72
  4938.1  285.65  4961.5  283.78  5023.1  285.47    5204  307.85  5209.2  306.12
  5246.6  308.66  5310.6  304.62  5384.7  305.52  5618.6  316.96  5735.9  330.31
  5863.7  351.34  5875.3  357.57  5906.1  366.46  5911.4   370.8  5922.3  374.57
#Mann= 5 ,-1 , 0
  3374.9     .16       0    4265     .07       0    4271     .16       0
  4480.3     .05       0  4753.4     .16       0
Bank Sta=4938.1,5204
XS Rating Curve= 0 ,0
Exp/Cntr=0.3,0.1

Type RM Length L Ch R = 1 ,11050   ,543,543,543
BEGIN DESCRIPTION:
MURCHISON BRANCH 11.0
END DESCRIPTION:
XS GIS Cut Line= 3
      3765820.25     10534364.74       3767201.5     10535262.08
      3768346.49     10535232.82
#Sta/Elev= 30
  3001.3  314.91  3091.9  308.54  3149.3  309.69  3236.9  318.35  3286.7  320.08
  3322.5  314.34  3336.5  308.31  3351.6  306.43  3358.3  303.42  3417.9  293.54
  3481.4  288.09  3750.3  280.43  3987.7  279.84  4305.9  281.96    4466  279.82
  4580.7  281.98  4798.1  281.34  4876.6  280.92  5003.7  279.17  5006.4  278.67
  5009.7  279.17  5056.7  281.03  5126.7  285.04  5516.8   317.8  5586.9  327.31
  5686.9   345.3  5716.9  354.94  5746.9  361.71  5756.9  367.45  5793.8  373.16
#Mann= 5 ,-1 , 0
  3001.3     .16       0  3987.7     .05       0  4798.1     .16       0
  5003.7     .07       0  5009.7     .16       0
Bank Sta=4876.6,5056.7
XS Rating Curve= 0 ,0
Exp/Cntr=0.3,0.1

Type RM Length L Ch R = 1 ,10507   ,754,754,754
BEGIN DESCRIPTION:
MURCHISON BRANCH 10.0
END DESCRIPTION:
XS GIS Cut Line= 2
       3765499.8     10535147.34      3767950.72     10535895.63
#Sta/Elev= 30
  2891.6  322.16  3069.1  316.49  3196.1  317.58  3327.4  306.06  3332.6  307.94
    3393   304.7  3398.2  306.35  3501.9   306.2  3633.1  291.05  3775.9  279.65
  4041.5  277.09  4543.4   277.3    4565   277.4  4901.6  276.38  4982.5  276.78
  4999.9   275.4  5002.6   274.9  5005.9   275.4  5013.9  276.97  5066.2  281.72
  5144.5  294.36  5149.8  297.11  5182.6  303.16  5191.6  309.61    5223  319.64
  5264.8  322.97    5319  321.67  5346.6  323.75  5351.8  321.96  5454.2  327.61
#Mann= 7 ,-1 , 0
  2891.6     .16       0  3775.9     .05       0  4543.4     .16       0
    4565     .05       0  4901.6     .16       0  4999.9     .07       0
  5005.9     .16       0
Bank Sta=4982.5,5013.9
XS Rating Curve= 0 ,0
Exp/Cntr=0.3,0.1

Type RM Length L Ch R = 1 ,9753    ,271,271,271
BEGIN DESCRIPTION:
MURCHISON BRANCH 9.0
END DESCRIPTION:
XS GIS Cut Line= 3
      3766099.61     10535510.19      3767199.61     10536310.19
      3767549.59     10536660.17
#Sta/Elev= 30
  3615.1  306.65    3658   302.4  3664.6  300.27  3678.9  298.98  3701.7  294.21
  3743.8   290.3  3764.6     287  3844.2   280.1  3865.1  279.32  3873.6  277.79
  3970.7  277.05  4107.5  276.35  4344.6   273.7  4499.6   274.3  4749.7  272.43
  4752.4  271.93  4755.7  272.43  4894.1  273.18  4938.5  272.76  4961.7  273.94
  5003.5  273.01  5074.2  273.89  5102.5  274.26  5215.7  280.78  5300.5  287.89
  5314.7  291.74  5357.1  299.79  5399.5  305.57  5427.8  310.91  5470.2  314.85
#Mann= 7 ,-1 , 0
  3615.1     .16       0  3970.7     .05       0  4107.5     .16       0
  4499.6     .12       0  4749.7     .07       0  4755.7     .12       0
  4894.1     .16       0
Bank Sta=4961.7,5074.2
XS Rating Curve= 0 ,0
Exp/Cntr=0.3,0.1

Type RM Length L Ch R = 1 ,9482    ,633,633,633
BEGIN DESCRIPTION:
MURCHISON BRANCH 8.0
END DESCRIPTION:
XS GIS Cut Line= 3
        3765489.     10535809.24      3766877.86     10536189.01
      3767398.67     10536829.17
#Sta/Elev= 30
  3410.5   322.5  3670.3  315.09  3697.3  312.18  3776.7  308.87  3885.4  298.86
  3925.1   297.2  3930.3  298.55  3959.6  296.04  3964.8  297.89  3991.7  295.16
  3999.3  292.47  4118.4  293.67  4192.6  291.21  4261.2  280.15  4323.4  274.08
  4567.1  271.99  4662.6  270.57  4665.3  270.07  4668.6  270.57  4909.2  272.89
    5007  271.39  5115.4  273.81  5136.2  271.85  5243.2  274.85  5300.7  281.03
    5379  285.34  5414.1  290.26  5449.3  292.14    5542  302.15  5675.6  311.96
#Mann= 5 ,-1 , 0
  3410.5     .16       0  4567.1     .12       0  4662.6     .07       0
  4668.6     .12       0    5007     .16       0
Bank Sta=4909.2,5115.4
XS Rating Curve= 0 ,0
Exp/Cntr=0.3,0.1

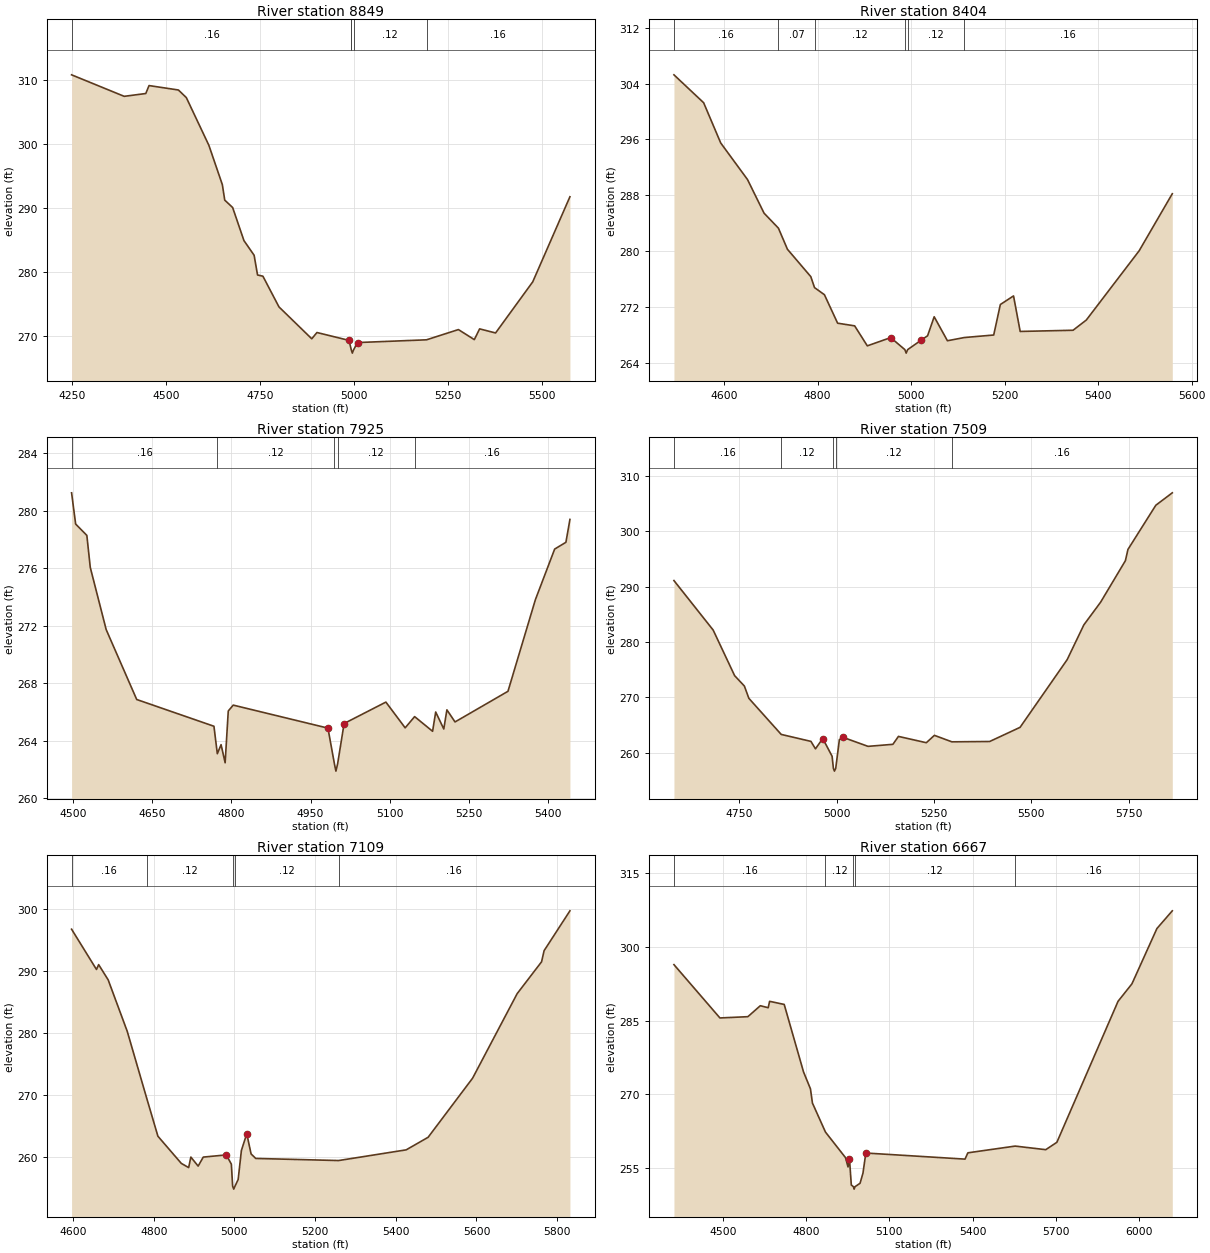
Type RM Length L Ch R = 1 ,8849    ,445,445,445
BEGIN DESCRIPTION:
MURCHISON BRANCH 7.0
END DESCRIPTION:
XS GIS Cut Line= 3
      3765814.85     10536089.74      3766449.61     10536510.19
      3766849.63     10536910.21
#Sta/Elev= 30
  4248.1  310.74  4388.2  307.38  4445.7  307.82  4454.4  309.06  4532.6  308.37
  4553.7  307.18  4613.7  299.73  4649.6  293.58    4656  291.16    4677  290.01
  4707.1  284.84  4734.2  282.55  4743.3  279.47  4757.6  279.28  4800.4  274.48
  4887.7   269.5  4901.5  270.48  4986.9  269.25  4992.7  267.83    4993  267.76
  4995.7  267.26    4999  267.76  5009.5  268.91  5193.3  269.34  5278.2  270.94
  5320.6  269.37  5334.7  271.05  5377.2  270.41  5476.2   278.4  5575.2  291.69
#Mann= 5 ,-1 , 0
  4248.1     .16       0  4992.7     .12       0    4993     .07       0
    4999     .12       0  5193.3     .16       0
Bank Sta=4986.9,5009.5
XS Rating Curve= 0 ,0
Exp/Cntr=0.3,0.1

Type RM Length L Ch R = 1 ,8404    ,479,479,479
BEGIN DESCRIPTION:
MURCHISON BRANCH 6.0
END DESCRIPTION:
XS GIS Cut Line= 3
      3765999.63     10536460.21      3766299.61     10536860.19
      3766699.64     10537260.22
#Sta/Elev= 30
  4492.9  305.24  4556.4  301.25  4592.9   295.5  4650.2  290.27  4685.6  285.46
  4716.3  283.32  4735.6   280.3  4785.6  276.38  4793.5  274.82  4814.7   273.8
  4842.9  269.73  4879.3  269.35  4906.4  266.49  4956.4  267.67  4986.7  265.95
  4989.5  265.45  4992.7  265.95  5021.2  267.29  5035.3  267.93  5049.4  270.65
  5077.7  267.22  5113.9  267.68  5176.7  268.04  5190.9   272.4  5219.1  273.63
  5233.3  268.55  5346.4  268.72  5374.7  270.18  5487.8  280.09  5558.6  288.24
#Mann= 6 ,-1 , 0
  4492.9     .16       0  4716.3     .07       0  4793.5     .12       0
  4986.7     .07       0  4992.7     .12       0  5113.9     .16       0
Bank Sta=4956.4,5021.2
XS Rating Curve= 0 ,0
Exp/Cntr=0.3,0.1

Type RM Length L Ch R = 1 ,7925    ,416,416,416
BEGIN DESCRIPTION:
MURCHISON BRANCH 5.0
END DESCRIPTION:
XS GIS Cut Line= 3
      3765699.58     10536960.17      3766099.61     10537210.19
      3766499.59     10537460.17
#Sta/Elev= 30
  4497.5  281.23  4505.2  279.06  4526.4  278.27  4532.9  276.04    4563  271.72
  4620.8  266.86    4767     265  4773.4  263.09  4780.5  263.72  4788.2  262.46
  4794.1  266.06  4803.5  266.47  4982.8  264.87  4995.1  262.38  4997.9  261.88
  5001.1  262.38  5013.4  265.19  5092.5  266.68    5129  264.89  5146.9  265.67
  5180.9  264.65  5186.8  265.99  5202.1  264.81    5208  266.14  5223.4   265.3
  5323.6  267.43  5375.5   273.8    5412  277.32  5433.3  277.79  5440.9  279.38
#Mann= 5 ,-1 , 0
  4497.5     .16       0  4773.4     .12       0  4995.1     .07       0
  5001.1     .12       0  5146.9     .16       0
Bank Sta=4982.8,5013.4
XS Rating Curve= 0 ,0
Exp/Cntr=0.3,0.1

Type RM Length L Ch R = 1 ,7509    ,400,400,400
BEGIN DESCRIPTION:
MURCHISON BRANCH 4.0
END DESCRIPTION:
XS GIS Cut Line= 3
      3765449.62     10537360.19      3765849.61     10537510.19
      3766499.64     10538060.22
#Sta/Elev= 30
  4582.9  291.12  4683.5  282.17  4738.6  273.92  4763.6  272.04  4775.1  269.82
  4858.1  263.29  4934.4  262.03    4946  260.68  4964.7  262.55  4988.7  259.34
    4992  257.15  4994.7  256.65    4998  257.15  5007.4  262.36  5017.2  262.75
  5080.9  261.13  5144.7   261.5  5158.9  262.93  5230.4  261.79  5251.2  263.12
  5295.9  261.95    5393  262.01    5471  264.57  5591.8  276.81  5634.7  283.11
  5677.6   287.2  5741.3  294.72  5747.8  296.75  5819.3  304.74  5861.6  306.99
#Mann= 5 ,-1 , 0
  4582.9     .16       0  4858.1     .12       0    4992     .07       0
    4998     .12       0  5295.9     .16       0
Bank Sta=4964.7,5017.2
XS Rating Curve= 0 ,0
Exp/Cntr=0.3,0.1

Type RM Length L Ch R = 1 ,7109    ,442,442,442
BEGIN DESCRIPTION:
MURCHISON BRANCH 3.0
END DESCRIPTION:
XS GIS Cut Line= 3
      3765249.57     10537660.17      3765599.61     10537810.19
      3766399.58     10538110.18
#Sta/Elev= 30
  4596.5  296.81  4658.2   290.3  4663.6  291.08  4687.2  288.62  4734.4  280.31
    4783  269.42  4810.5  263.34  4868.5  258.95  4886.7  258.27  4892.1  259.97
  4910.2  258.51  4922.9  259.97    4980  260.32  4992.5  258.83  4995.7  255.29
  4998.4  254.79  5001.7  255.29  5009.4  256.35  5017.4  261.04  5030.7  263.74
  5041.4  260.48    5053  259.75  5258.4  259.41  5425.9  261.14  5480.2  263.17
  5590.5  272.73  5700.9  286.39  5761.4  291.54  5767.7  293.34  5831.7  299.78
#Mann= 5 ,-1 , 0
  4596.5     .16       0    4783     .12       0  4995.7     .07       0
  5001.7     .12       0  5258.4     .16       0
Bank Sta=4980,5030.7
XS Rating Curve= 0 ,0
Exp/Cntr=0.3,0.1

Type RM Length L Ch R = 1 ,6667    ,486,486,486
BEGIN DESCRIPTION:
MURCHISON BRANCH 2.0
END DESCRIPTION:
XS GIS Cut Line= 4
      3764981.55     10537700.85      3765085.73     10538068.93
      3765516.28     10538207.82      3766474.64     10538152.26
#Sta/Elev= 30
  4324.2  296.38  4489.8  285.54  4590.5   285.8  4635.3  288.03  4663.6  287.62
  4668.8  288.92  4721.3  288.29  4790.9  274.57  4815.9  271.12    4823  268.24
  4869.9  262.34    4942  257.15  4951.2  255.25  4956.4   256.9    4963  251.58
  4970.5  251.24  4973.2  250.74  4976.5  251.24  4994.5  251.93    5005  253.99
  5015.3  258.08  5372.6  256.84  5382.8  258.12  5553.2  259.49  5663.3  258.76
  5703.4  260.26  5923.7  288.92  5973.8  292.48  6063.7  303.72  6119.1  307.32
#Mann= 5 ,-1 , 0
  4324.2     .16       0  4869.9     .12       0  4970.5     .07       0
  4976.5     .12       0  5553.2     .16       0
Bank Sta=4956.4,5015.3
XS Rating Curve= 0 ,0
Exp/Cntr=0.3,0.1

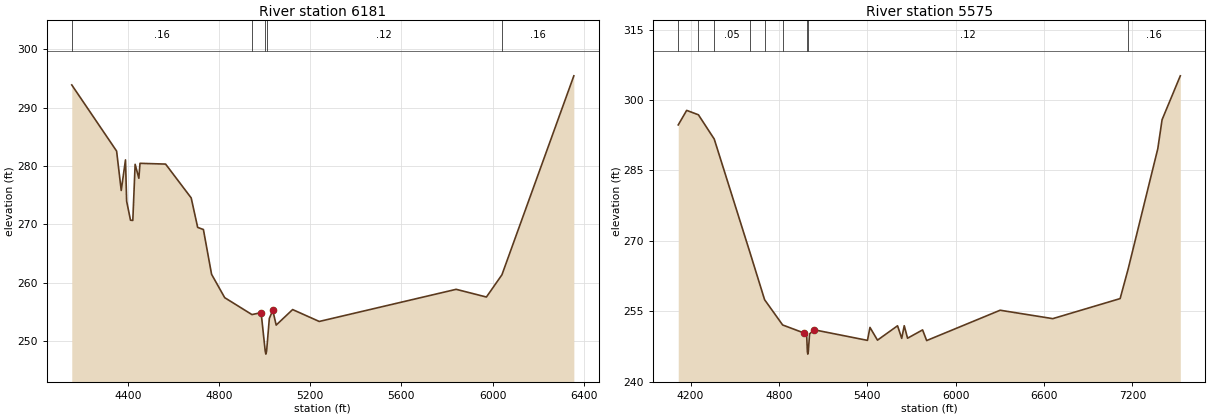
Type RM Length L Ch R = 1 ,6181    ,606,606,606
BEGIN DESCRIPTION:
Mapping XS a9215ed1
END DESCRIPTION:
XS GIS Cut Line= 4
      3764892.18     10537816.61      3765011.54     10538478.51
      3765337.06     10538695.52      3766366.24     10538208.02
#Sta/Elev= 30
    4154  293.89  4350.7  282.55    4371   275.8  4389.7  281.04  4394.7  273.96
  4411.7   270.7  4421.8  270.66    4432  280.28  4448.3  277.89  4453.4  280.45
  4565.6  280.32  4677.9  274.52  4706.3  269.47  4731.5   269.1  4767.3  261.43
  4824.9  257.42  4944.4  254.52  4984.7  254.85  5002.7  248.24  5005.5  247.74
  5008.7  248.24  5020.7  253.86  5035.8  255.24  5050.8  252.72  5122.9  255.38
  5239.6  253.34  5840.3  258.85  5973.1  257.53  6041.1  261.34  6356.6  295.45
#Mann= 5 ,-1 , 0
    4154     .16       0  4944.4     .12       0  5002.7     .07       0
  5008.7     .12       0  6041.1     .16       0
Bank Sta=4984.7,5035.8
XS Rating Curve= 0 ,0
Exp/Cntr=0.3,0.1

Type RM Length L Ch R = 1 ,5575    ,0,0,0
BEGIN DESCRIPTION:
MURCHISON BRANCH 1.0
END DESCRIPTION:
XS GIS Cut Line= 4
      3764751.12     10537925.14      3764610.07     10539086.15
       3765065.8     10539303.16      3766443.83     10538250.65
#Sta/Elev= 30
  4116.6   294.7  4173.9   297.8  4253.6  296.86    4361  291.69  4604.4  267.43
  4702.8  257.47  4825.5  252.08  4967.9   250.4    4988  250.25  4993.4  246.37
  4996.1  245.87  4999.4  246.37  5008.2  250.16  5038.4  251.06  5401.1   248.8
  5418.2  251.56  5469.2  248.85  5605.4  251.91  5633.7  249.23  5650.8  251.92
  5673.3  249.26  5775.4  251.03    5803  248.76  6301.8  255.22  6659.2  253.43
  7116.3   257.7  7170.7  263.99    7372  289.62  7401.1  295.81  7524.9  305.16
#Mann= 9 ,-1 , 0
  4116.6     .05       0  4253.6     .16       0    4361     .05       0
  4604.4     .12       0  4702.8     .16       0  4825.5     .12       0
  4993.4     .07       0  4999.4     .12       0  7170.7     .16       0
Bank Sta=4967.9,5038.4
XS Rating Curve= 0 ,0
Exp/Cntr=0.3,0.1

Chan Stop Cuts=-1
Use User Specified Reach Order=0
Composite Channel Slope=5