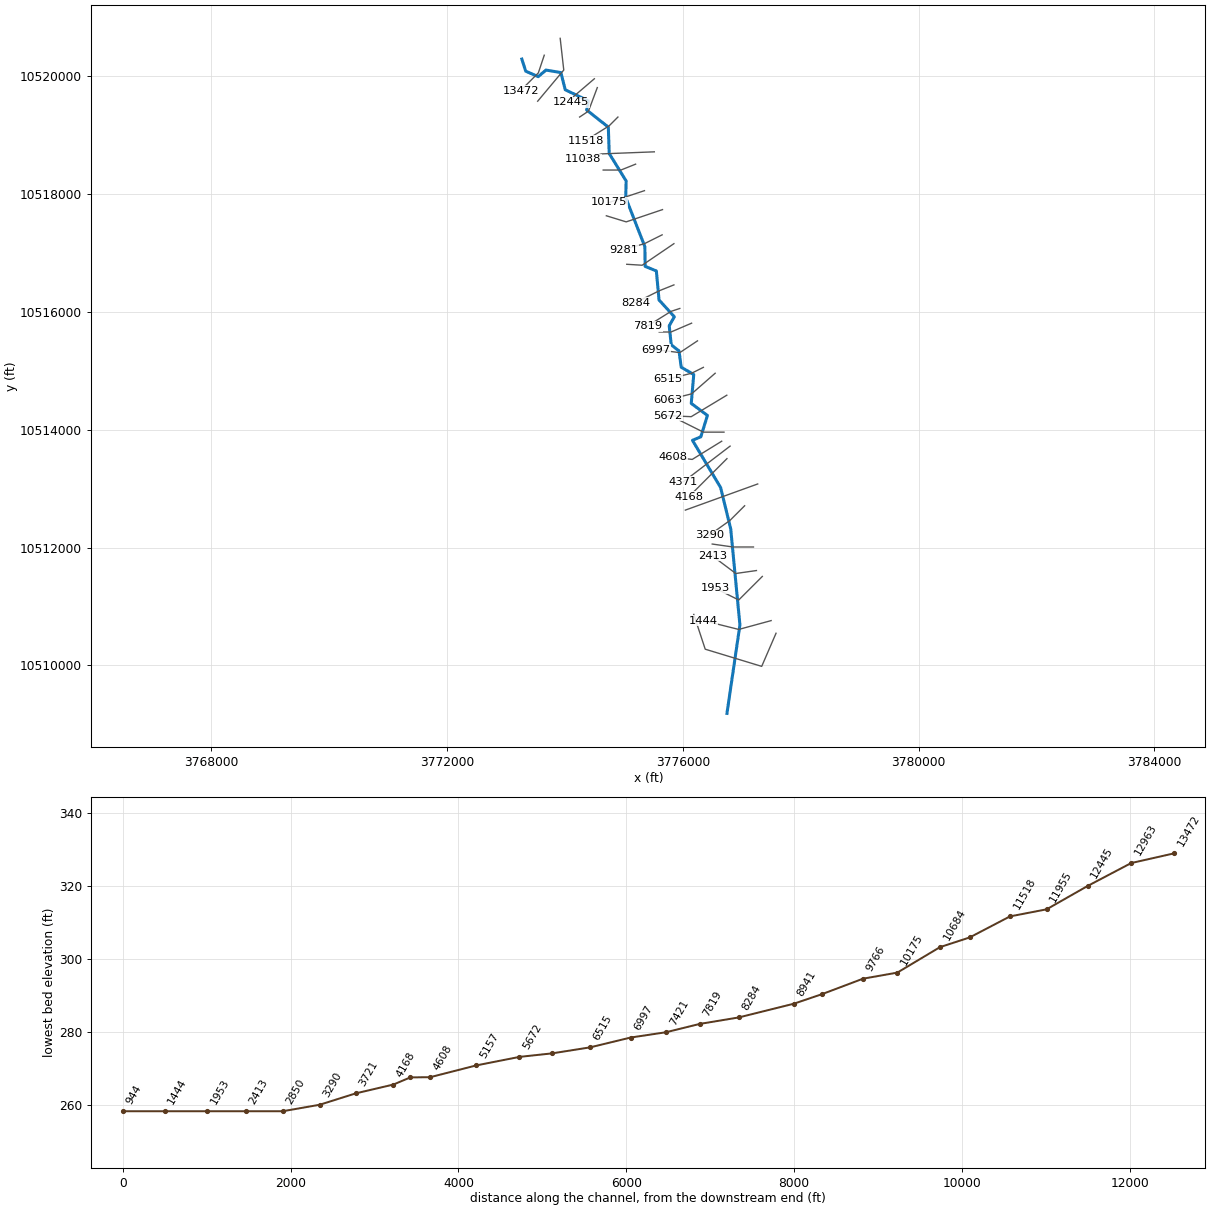
--- NEALY BRANCH.prj (project) ---

Proj Title=NEALY BRANCH Base Level Engineering
Current Plan=p01
Default Exp/Contr=0.3,0.1
English Units
Geom File=g01
Flow File=f01
Plan File=p01
BEGIN DESCRIPTION:
NEALY BRANCH
END DESCRIPTION:

--- NEALY BRANCH.p01 (plan) ---

Plan Title=Multiple Run
Short Identifier=Multiple
Geom File=g01
Flow File=f01
Subcritical Flow
K Sum by GR= 0
Std Step Tol= 0.01
Critical Tol= 0.01
Num of Std Step Trials= 20
Max Error Tol= 0.3
Flow Tol Ratio= 0.001
Split Flow NTrial= 30
Split Flow Tol= 0.02
Split Flow Ratio= 0.02
Log Output Level= 0
Friction Slope Method= 1
Unsteady Friction Slope Method= 2
Unsteady Bridges Friction Slope Method= 1
Parabolic Critical Depth
Global Vel Dist=  1 , 1 , 1
Global Log Level= 0
CheckData=True
Encroach Param= -1, 0, 0, 0
BEGIN DESCRIPTION:
Multiple Run
END DESCRIPTION:

--- NEALY BRANCH.f01 (steady flow) ---

Flow Title=Multiple
Number of Profiles=7
Profile Names=10-year,25-year,50-year,1pct_min,100-year,1pct_plu,500-year
River Rch & RM= NEALY BRANCH,Reach-1,13472
     662     904    1107     997    1348    1824    2007
River Rch & RM= NEALY BRANCH,Reach-1,12445
     902    1244    1533    1386    1874    2535    2813
Boundary for River Rch & Prof#=NEALY BRANCH,Reach-1,1
Up Type=0
Dn Type=3
Dn Slope=0.005
Boundary for River Rch & Prof#=NEALY BRANCH,Reach-1,2
Up Type=0
Dn Type=3
Dn Slope=0.005
Boundary for River Rch & Prof#=NEALY BRANCH,Reach-1,3
Up Type=0
Dn Type=3
Dn Slope=0.005
Boundary for River Rch & Prof#=NEALY BRANCH,Reach-1,4
Up Type=0
Dn Type=3
Dn Slope=0.005
Boundary for River Rch & Prof#=NEALY BRANCH,Reach-1,5
Up Type=0
Dn Type=3
Dn Slope=0.005
Boundary for River Rch & Prof#=NEALY BRANCH,Reach-1,6
Up Type=0
Dn Type=3
Dn Slope=0.005
Boundary for River Rch & Prof#=NEALY BRANCH,Reach-1,7
Up Type=0
Dn Type=3
Dn Slope=0.005

--- NEALY BRANCH.g01 (geometry) ---

Geom Title=Existing Conditions

River Reach=NEALY BRANCH,Reach-1
Reach XY= 30
      3773269.25     10520295.00      3773334.75     10520089.00
      3773547.00     10519996.00      3773679.25     10520108.00
      3773932.00     10520065.00      3774006.00     10519773.00
      3774401.25     10519584.00      3774368.75     10519430.00
      3774736.75     10519139.00      3774752.00     10518691.00
      3775038.75     10518225.00      3775032.25     10517941.00
      3775356.75     10517109.00      3775361.50     10516775.00
      3775551.75     10516697.00      3775597.25     10516204.00
      3775856.75     10515919.00      3775769.75     10515765.00
      3775804.75     10515442.00      3775936.25     10515339.00
      3775973.00     10515062.00      3776186.25     10514939.00
      3776143.75     10514448.00      3776418.25     10514243.00
      3776306.00     10513881.00      3776164.25     10513821.00
      3776641.50     10513021.00      3776813.25     10512318.00
      3776969.50     10510686.00      3776749.50     10509185.00

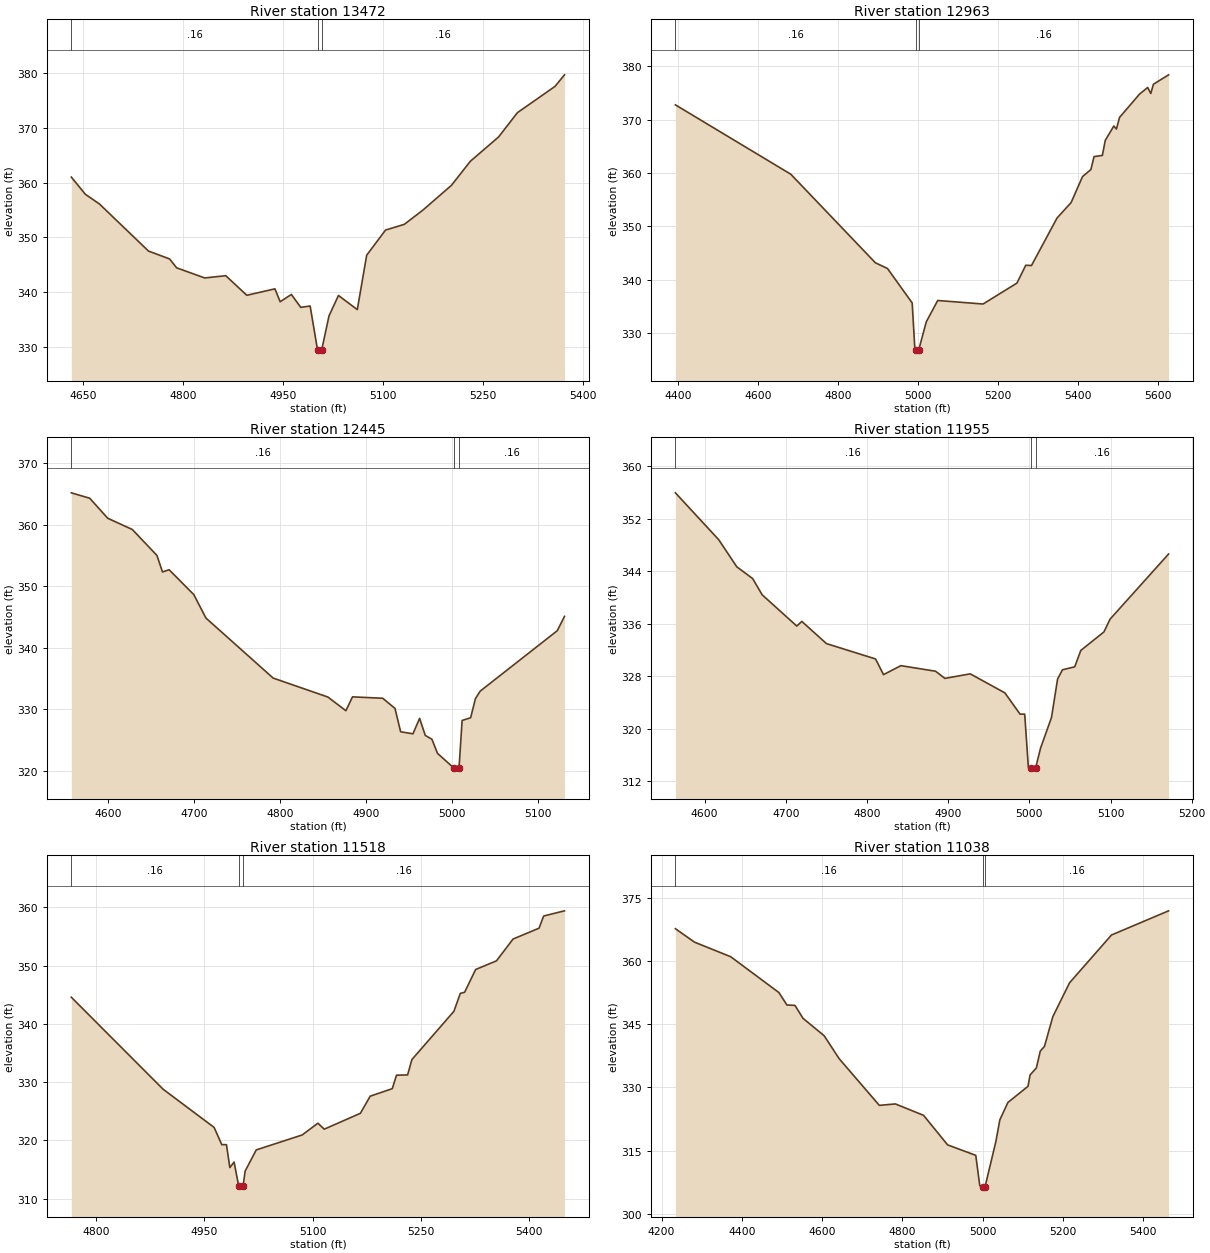
Type RM Length L Ch R = 1,13472,509,509,509
BEGIN DESCRIPTION:
NEALY BRANCH 28.0
END DESCRIPTION:
XS GIS Cut Line= 3
      3773649.61     10520360.18      3773549.61     10520060.19
      3773249.60     10519760.18
#Sta/Elev= 30
  4632.0  361.03  4653.1  357.89  4674.2  356.12  4747.9  347.51  4779.6  346.07
  4790.1  344.45  4832.3  342.60  4863.9  343.01  4895.5  339.43  4937.7  340.61
  4945.6  338.25  4962.4  339.58  4976.5  337.23  4990.6  337.47  5001.8  329.36
  5004.5  328.86  5007.8  329.36  5018.9  335.66  5033.1  339.40  5061.4  336.81
  5075.5  346.76  5103.8  351.35  5132.1  352.40  5160.4  355.05  5202.8  359.53
  5231.1  363.92  5273.5  368.36  5301.8  372.80  5358.3  377.61  5372.5  379.72
#Mann=3,-1,0
  4632.0    0.16       0  5001.8    0.07       0  5007.8    0.16       0
Bank Sta=5001.8,5007.8
Exp/Cntr=0.3,0.1

Type RM Length L Ch R = 1,12963,518,518,518
BEGIN DESCRIPTION:
NEALY BRANCH 27.0
END DESCRIPTION:
XS GIS Cut Line= 3
      3773919.97     10520646.58      3773980.73     10520108.37
      3773538.04     10519578.88
#Sta/Elev= 30
  4393.7  372.78  4681.9  359.77  4893.2  343.16  4923.4  342.09  4985.1  335.63
  4991.6  327.22  4995.1  326.72  4997.9  326.22  5001.1  326.72  5020.3  332.09
  5048.9  336.09  5162.1  335.43  5246.7  339.35  5268.8  342.70  5283.1  342.65
  5346.9  351.56  5382.0  354.45  5410.6  359.33  5431.5  360.65  5439.3  363.07
  5460.1  363.30  5467.4  366.12  5488.7  368.81  5495.2  368.25  5503.0  370.42
  5552.5  374.76  5573.3  376.04  5581.1  374.91  5587.6  376.64  5625.5  378.41
#Mann=3,-1,0
  4393.7    0.16       0  4995.1    0.07       0  5001.1    0.16       0
Bank Sta=4995.1,5001.1
Exp/Cntr=0.3,0.1

Type RM Length L Ch R = 1,12445,490,490,490
BEGIN DESCRIPTION:
NEALY BRANCH 26.0
END DESCRIPTION:
XS GIS Cut Line= 3
      3774499.63     10519960.21      3774149.61     10519660.19
      3774099.61     10519560.20
#Sta/Elev= 30
  4557.6  365.16  4579.0  364.28  4599.9  361.03  4628.4  359.21  4657.0  355.00
  4663.5  352.31  4671.2  352.67  4699.8  348.64  4714.0  344.82  4792.0  335.08
  4855.6  332.00  4876.5  329.78  4884.2  332.03  4919.3  331.80  4933.5  330.16
  4940.1  326.36  4954.4  326.03  4962.1  328.54  4968.7  325.77  4976.4  325.15
  4982.9  322.86  5001.9  320.47  5004.6  319.97  5007.9  320.47  5011.5  328.20
  5021.4  328.64  5027.0  331.76  5032.6  332.97  5122.0  342.77  5130.4  345.10
#Mann=3,-1,0
  4557.6    0.16       0  5001.9    0.07       0  5007.9    0.16       0
Bank Sta=5001.9,5007.9
Exp/Cntr=0.3,0.1

Type RM Length L Ch R = 1,11955,437,437,437
BEGIN DESCRIPTION:
NEALY BRANCH 25.0
END DESCRIPTION:
XS GIS Cut Line= 3
      3774549.60     10519810.16      3774399.61     10519410.19
      3774249.65     10519310.22
#Sta/Elev= 30
  4564.1  355.97  4617.5  348.82  4639.7  344.70  4659.3  342.90  4670.9  340.44
  4713.6  335.67  4719.8  336.38  4750.1  333.00  4810.6  330.66  4820.4  328.27
  4841.8  329.64  4884.5  328.79  4896.0  327.70  4927.2  328.39  4969.9  325.49
  4988.6  322.25  4994.3  322.25  4998.8  314.16  5001.8  314.07  5004.5  313.57
  5007.8  314.07  5013.8  317.06  5027.3  321.75  5034.8  327.60  5040.8  329.01
  5055.9  329.46  5063.4  331.96  5091.9  334.78  5099.4  336.72  5171.5  346.65
#Mann=3,-1,0
  4564.1    0.16       0  5001.8    0.07       0  5007.8    0.16       0
Bank Sta=5001.8,5007.8
Exp/Cntr=0.3,0.1

Type RM Length L Ch R = 1,11518,480,480,480
BEGIN DESCRIPTION:
NEALY BRANCH 24.0
END DESCRIPTION:
XS GIS Cut Line= 3
      3774899.61     10519310.19      3774749.61     10519160.19
      3774349.64     10518910.21
#Sta/Elev= 30
  4765.6  344.56  4892.9  328.77  4963.6  322.22  4974.2  319.26  4980.7  319.26
  4985.4  315.33  4991.3  316.27  4997.7  312.13  5000.5  311.63  5003.7  312.13
  5006.6  314.72  5022.0  318.36  5085.6  320.92  5107.5  322.94  5116.3  321.92
  5166.4  324.64  5180.0  327.58  5210.6  328.87  5216.5  331.18  5231.9  331.23
  5237.8  333.86  5296.1  342.15  5305.0  345.23  5310.9  345.41  5326.2  349.32
  5355.1  350.81  5378.1  354.55  5414.1  356.41  5420.5  358.50  5449.4  359.39
#Mann=3,-1,0
  4765.6    0.16       0  4997.7    0.07       0  5003.7    0.16       0
Bank Sta=4997.7,5003.7
Exp/Cntr=0.3,0.1

Type RM Length L Ch R = 1,11038,354,354,354
BEGIN DESCRIPTION:
NEALY BRANCH 23.0
END DESCRIPTION:
XS GIS Cut Line= 3
      3775517.20     10518719.48      3774623.09     10518684.76
      3774303.22     10518589.66
#Sta/Elev= 30
  4234.6  367.63  4282.2  364.44  4372.3  360.99  4492.4  352.49  4512.4  349.54
  4532.4  349.45  4552.4  346.38  4605.2  342.25  4642.5  336.81  4742.6  325.74
  4782.6  326.08  4852.7  323.38  4912.7  316.37  4982.8  313.89  4992.8  306.69
  4999.8  306.38  5002.5  305.88  5005.8  306.38  5032.8  317.14  5042.8  322.31
  5062.8  326.42  5112.9  330.26  5118.1  332.95  5133.8  334.63  5143.5  338.61
  5153.9  339.72  5174.8  346.78  5216.5  354.81  5320.8  366.13  5463.1  371.87
#Mann=3,-1,0
  4234.6    0.16       0  4999.8    0.07       0  5005.8    0.16       0
Bank Sta=4999.8,5005.8
Exp/Cntr=0.3,0.1

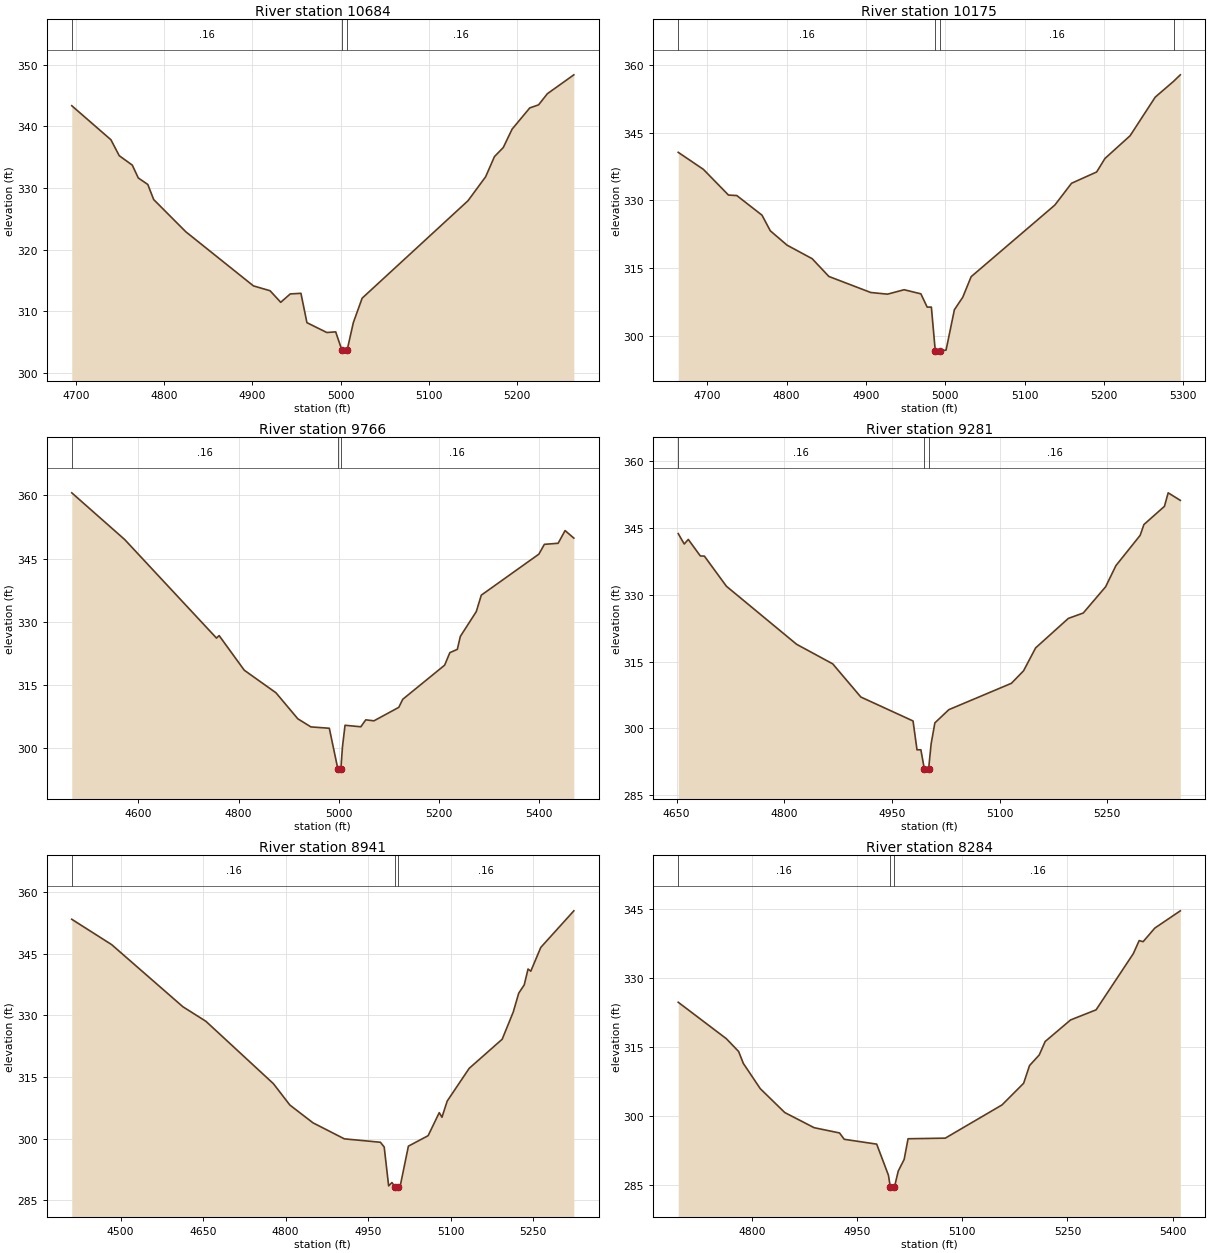
Type RM Length L Ch R = 1,10684,509,509,509
BEGIN DESCRIPTION:
NEALY BRANCH 22.0
END DESCRIPTION:
XS GIS Cut Line= 3
      3775199.60     10518510.18      3774949.61     10518410.19
      3774649.66     10518410.19
#Sta/Elev= 30
  4695.3  343.35  4739.7  337.83  4749.1  335.25  4763.9  333.72  4770.7  331.64
  4781.5  330.58  4788.2  328.13  4824.5  322.92  4901.3  314.13  4920.1  313.35
  4932.2  311.47  4943.0  312.83  4955.1  312.93  4961.9  308.17  4984.5  306.57
  4994.5  306.68  5001.5  303.73  5004.3  303.23  5007.5  303.73  5014.5  308.17
  5024.5  312.14  5144.5  327.94  5164.5  331.83  5174.5  335.10  5184.5  336.57
  5194.5  339.55  5214.5  342.99  5224.5  343.49  5234.5  345.30  5264.5  348.36
#Mann=3,-1,0
  4695.3    0.16       0  5001.5    0.07       0  5007.5    0.16       0
Bank Sta=5001.5,5007.5
Exp/Cntr=0.3,0.1

Type RM Length L Ch R = 1,10175,409,409,409
BEGIN DESCRIPTION:
NEALY BRANCH 21.0
END DESCRIPTION:
XS GIS Cut Line= 3
      3775349.65     10518060.20      3775049.61     10517960.19
      3774749.61     10517860.19
#Sta/Elev= 30
  4663.6  340.63  4695.3  336.87  4726.9  331.19  4737.4  331.08  4769.1  326.75
  4779.6  323.29  4800.7  320.12  4832.3  317.13  4853.4  313.20  4906.1  309.66
  4927.2  309.29  4948.2  310.27  4969.3  309.36  4977.2  306.43  4982.5  306.43
  4987.4  296.76  4990.2  296.26  4993.4  296.76  5001.0  296.93  5011.5  305.85
  5022.0  308.60  5032.6  313.15  5138.0  328.97  5159.1  333.80  5190.7  336.29
  5201.2  339.28  5232.9  344.31  5264.5  352.83  5287.6  356.32  5296.1  357.76
#Mann=4,-1,0
  4663.6    0.16       0  4987.4    0.07       0  4993.4    0.16       0
  5287.6    0.05       0
Bank Sta=4987.4,4993.4
Exp/Cntr=0.3,0.1

Type RM Length L Ch R = 1,9766,485,485,485
BEGIN DESCRIPTION:
NEALY BRANCH 20.0
END DESCRIPTION:
XS GIS Cut Line= 3
      3775656.06     10517738.58      3775039.76     10517530.25
      3774702.91     10517633.90
#Sta/Elev= 30
  4466.8  360.62  4572.5  349.54  4755.9  326.16  4761.2  326.75  4811.4  318.54
  4874.7  313.19  4918.4  307.01  4944.6  305.09  4981.3  304.77  4998.4  295.10
  5001.2  294.60  5004.4  295.10  5007.5  300.27  5012.7  305.48  5044.2  305.12
  5054.2  306.77  5070.4  306.53  5120.1  309.73  5128.0  311.64  5211.7  319.74
  5222.1  322.71  5237.0  323.48  5243.1  326.57  5274.9  332.44  5284.9  336.34
  5400.0  346.08  5410.9  348.40  5438.4  348.65  5452.3  351.66  5469.8  349.88
#Mann=3,-1,0
  4466.8    0.16       0  4998.4    0.07       0  5004.4    0.16       0
Bank Sta=4998.4,5004.4
Exp/Cntr=0.3,0.1

Type RM Length L Ch R = 1,9281,340,340,340
BEGIN DESCRIPTION:
NEALY BRANCH 19.0
END DESCRIPTION:
XS GIS Cut Line= 3
      3775649.63     10517310.20      3775349.61     10517160.19
      3774999.65     10517060.20
#Sta/Elev= 30
  4652.3  343.71  4660.7  341.38  4666.3  342.41  4683.1  338.70  4688.7  338.67
  4719.4  331.90  4817.2  318.87  4867.5  314.48  4906.7  307.03  4979.4  301.66
  4984.9  295.19  4990.3  295.19  4995.1  290.90  4997.9  290.40  5001.1  290.90
  5004.6  296.53  5009.8  301.23  5029.3  304.20  5116.4  310.11  5133.3  312.91
  5150.2  318.07  5195.7  324.68  5216.5  325.89  5247.7  331.79  5262.0  336.53
  5295.8  343.34  5301.0  345.75  5329.6  349.84  5334.8  352.87  5351.7  351.18
#Mann=3,-1,0
  4652.3    0.16       0  4995.1    0.07       0  5001.1    0.16       0
Bank Sta=4995.1,5001.1
Exp/Cntr=0.3,0.1

Type RM Length L Ch R = 1,8941,657,657,657
BEGIN DESCRIPTION:
NEALY BRANCH 18.0
END DESCRIPTION:
XS GIS Cut Line= 3
      3775849.60     10517160.18      3775310.83     10516794.11
      3775049.60     10516810.19
#Sta/Elev= 30
  4411.2  353.33  4483.7  347.17  4613.2  332.08  4655.2  328.53  4777.9  313.38
  4807.8  308.19  4849.8  303.87  4906.9  299.97  4972.5  299.14  4979.4  297.98
  4987.5  288.53  4993.5  289.35  4999.4  288.25  5002.2  287.75  5005.4  288.25
  5008.5  288.48  5023.4  298.19  5059.3  300.74  5079.5  306.33  5084.5  305.22
  5093.9  309.13  5133.9  317.09  5194.0  324.18  5214.1  330.79  5224.1  335.38
  5234.1  337.39  5241.0  341.24  5246.0  340.71  5264.2  346.49  5324.3  355.38
#Mann=3,-1,0
  4411.2    0.16       0  4999.4    0.07       0  5005.4    0.16       0
Bank Sta=4999.4,5005.4
Exp/Cntr=0.3,0.1

Type RM Length L Ch R = 1,8284,465,465,465
BEGIN DESCRIPTION:
NEALY BRANCH 17.0
END DESCRIPTION:
XS GIS Cut Line= 3
      3775849.61     10516460.19      3775599.61     10516360.19
      3775199.58     10516160.18
#Sta/Elev= 30
  4694.5  324.69  4763.2  316.75  4780.7  313.97  4787.4  311.38  4811.6  305.87
  4846.6  300.67  4888.4  297.38  4924.7  296.23  4931.4  294.85  4977.7  293.80
  4994.5  287.02  4997.1  284.50  4999.8  284.00  5003.1  284.50  5008.5  287.94
  5016.9  290.47  5022.5  294.97  5075.6  295.10  5156.6  302.34  5187.4  307.05
  5195.8  310.90  5209.7  313.22  5218.1  316.14  5254.4  320.84  5290.8  323.04
  5343.9  335.27  5352.3  338.12  5357.9  337.88  5374.6  340.84  5411.0  344.60
#Mann=3,-1,0
  4694.5    0.16       0  4997.1    0.07       0  5003.1    0.16       0
Bank Sta=4997.1,5003.1
Exp/Cntr=0.3,0.1

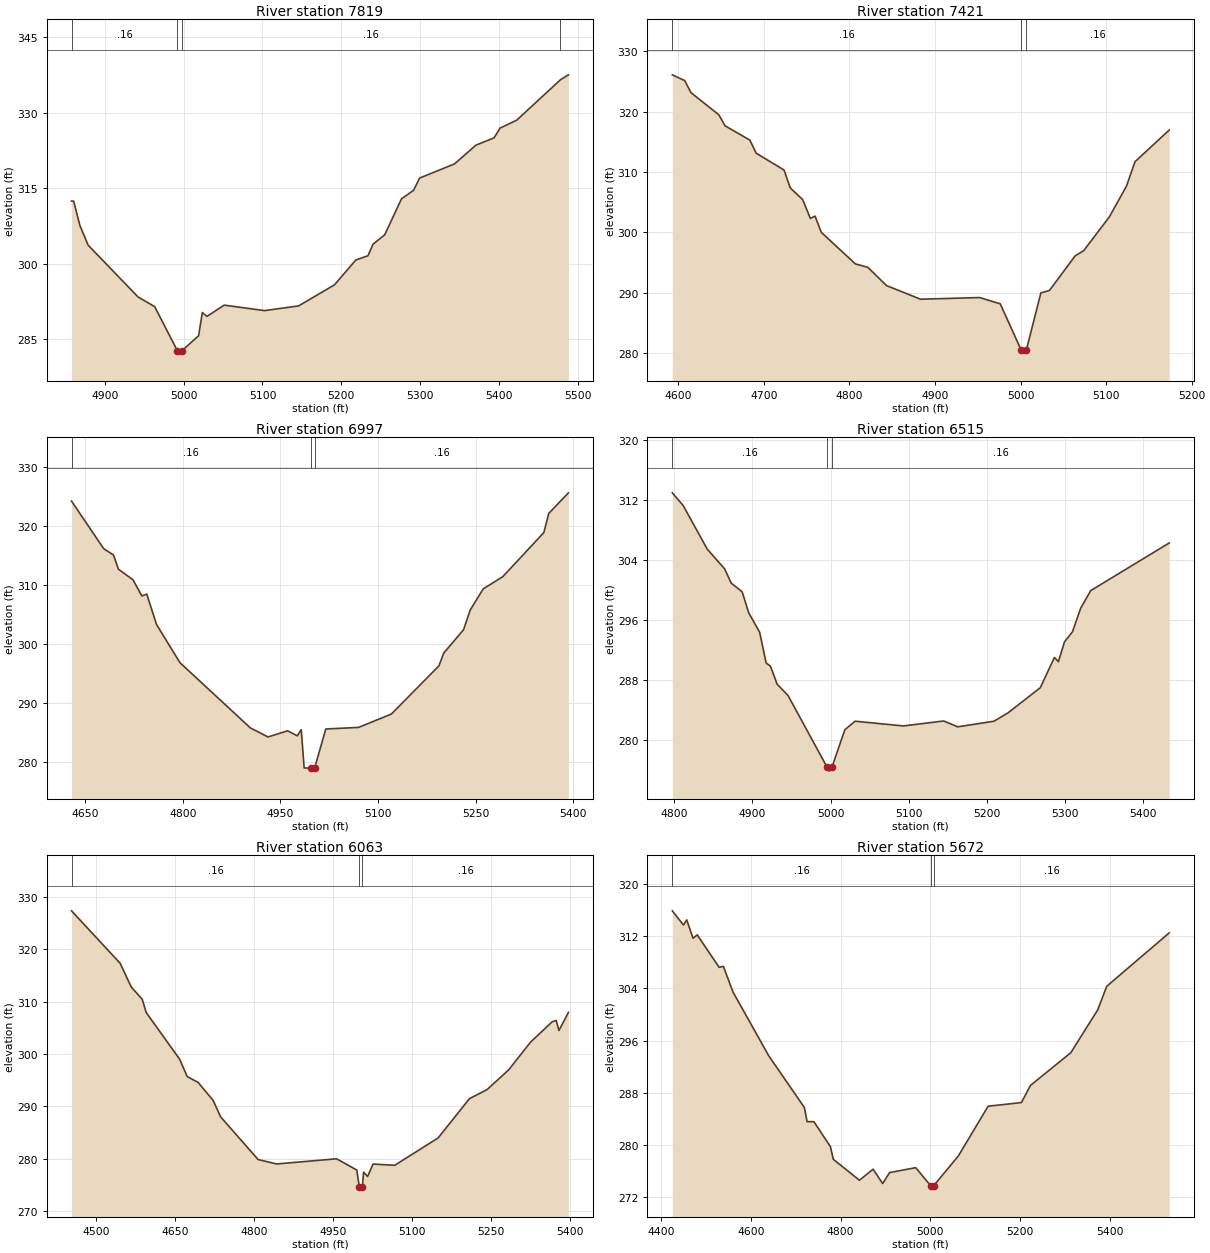
Type RM Length L Ch R = 1,7819,398,398,398
BEGIN DESCRIPTION:
NEALY BRANCH 16.0
END DESCRIPTION:
XS GIS Cut Line= 3
      3775949.63     10516060.20      3775799.61     10516010.19
      3775399.64     10515760.21
#Sta/Elev= 30
  4858.0  312.41  4860.7  312.41  4868.6  307.58  4879.1  303.66  4942.4  293.37
  4963.4  291.46  4992.1  282.73  4994.8  282.23  4998.1  282.73  5019.1  285.69
  5023.8  290.30  5029.7  289.52  5051.5  291.76  5102.8  290.67  5145.9  291.61
  5191.3  295.79  5218.4  300.73  5233.7  301.56  5240.2  303.86  5254.9  305.71
  5276.2  312.85  5291.5  314.55  5299.2  316.99  5343.4  319.79  5370.5  323.51
  5393.5  324.96  5401.2  326.91  5422.4  328.49  5477.7  336.50  5487.8  337.48
#Mann=4,-1,0
  4858.0    0.16       0  4992.1    0.07       0  4998.1    0.16       0
  5477.7    0.05       0
Bank Sta=4992.1,4998.1
Exp/Cntr=0.3,0.1

Type RM Length L Ch R = 1,7421,424,424,424
BEGIN DESCRIPTION:
NEALY BRANCH 15.0
END DESCRIPTION:
XS GIS Cut Line= 3
      3776149.65     10515810.21      3775799.61     10515660.19
      3775599.64     10515660.19
#Sta/Elev= 30
  4592.9  326.13  4607.4  325.18  4614.7  323.18  4647.3  319.50  4654.6  317.67
  4683.6  315.30  4690.9  313.14  4723.5  310.34  4730.8  307.37  4745.3  305.43
  4754.3  302.31  4759.8  302.69  4767.0  300.01  4806.9  294.77  4821.4  294.21
  4843.2  291.18  4883.1  288.91  4952.0  289.19  4976.2  288.15  5000.7  280.47
  5003.5  279.97  5006.7  280.47  5023.7  289.96  5033.7  290.36  5063.7  296.09
  5073.7  296.96  5103.7  302.56  5123.7  307.66  5133.7  311.72  5173.7  316.97
#Mann=3,-1,0
  4592.9    0.16       0  5000.7    0.07       0  5006.7    0.16       0
Bank Sta=5000.7,5006.7
Exp/Cntr=0.3,0.1

Type RM Length L Ch R = 1,6997,482,482,482
BEGIN DESCRIPTION:
NEALY BRANCH 14.0
END DESCRIPTION:
XS GIS Cut Line= 3
      3776249.57     10515510.16      3775949.61     10515310.19
      3775549.63     10515360.19
#Sta/Elev= 30
  4629.0  324.27  4678.5  316.20  4693.6  315.13  4701.1  312.73  4723.6  310.92
  4737.1  308.19  4744.6  308.51  4759.7  303.35  4795.7  296.88  4903.9  285.83
  4930.9  284.30  4961.0  285.34  4976.0  284.49  4982.0  285.54  4986.5  279.05
  4996.6  279.01  4999.3  278.51  5002.6  279.01  5019.7  285.65  5070.1  285.92
  5120.5  288.18  5193.6  296.35  5201.1  298.53  5231.4  302.46  5241.5  305.77
  5261.6  309.39  5291.8  311.47  5354.8  318.93  5362.4  322.18  5392.6  325.67
#Mann=3,-1,0
  4629.0    0.16       0  4996.6    0.07       0  5002.6    0.16       0
Bank Sta=4996.6,5002.6
Exp/Cntr=0.3,0.1

Type RM Length L Ch R = 1,6515,452,452,452
BEGIN DESCRIPTION:
NEALY BRANCH 13.0
END DESCRIPTION:
XS GIS Cut Line= 3
      3776349.57     10515060.17      3776149.61     10514960.19
      3775749.58     10514860.18
#Sta/Elev= 30
  4797.4  312.96  4811.3  311.27  4842.1  305.45  4864.4  302.81  4872.8  300.91
  4886.8  299.76  4895.2  296.95  4909.2  294.35  4917.5  290.26  4923.1  289.81
  4931.5  287.44  4945.5  285.92  4995.6  276.33  4998.3  275.83  5001.6  276.33
  5018.2  281.35  5031.3  282.49  5093.1  281.86  5144.7  282.52  5162.7  281.74
  5209.1  282.49  5227.1  283.61  5268.3  286.96  5286.4  290.99  5291.5  290.44
  5299.3  293.08  5309.6  294.44  5319.9  297.54  5332.8  299.91  5433.3  306.27
#Mann=3,-1,0
  4797.4    0.16       0  4995.6    0.07       0  5001.6    0.16       0
Bank Sta=4995.6,5001.6
Exp/Cntr=0.3,0.1

Type RM Length L Ch R = 1,6063,391,391,391
BEGIN DESCRIPTION:
NEALY BRANCH 12.0
END DESCRIPTION:
XS GIS Cut Line= 3
      3776549.60     10514960.18      3776149.61     10514610.19
      3775749.62     10514510.19
#Sta/Elev= 30
  4453.7  327.38  4546.2  317.34  4567.1  312.83  4588.0  310.48  4595.6  307.94
  4659.2  299.00  4673.4  295.71  4694.3  294.58  4722.8  291.13  4737.0  287.99
  4808.2  279.84  4843.3  279.00  4957.2  279.99  4995.5  277.84  5000.2  274.69
  5003.0  274.19  5006.2  274.69  5008.4  277.44  5016.1  276.61  5026.4  278.98
  5067.7  278.75  5150.1  283.98  5209.4  291.47  5242.9  293.21  5284.1  296.99
  5325.4  302.27  5366.6  306.17  5374.3  306.43  5379.5  304.51  5397.5  307.97
#Mann=3,-1,0
  4453.7    0.16       0  5000.2    0.07       0  5006.2    0.16       0
Bank Sta=5000.2,5006.2
Exp/Cntr=0.3,0.1

Type RM Length L Ch R = 1,5672,515,515,515
BEGIN DESCRIPTION:
NEALY BRANCH 11.0
END DESCRIPTION:
XS GIS Cut Line= 3
      3776747.19     10514587.27      3776142.99     10514222.67
      3775740.25     10514240.03
#Sta/Elev= 30
  4424.3  315.88  4449.2  313.71  4456.5  314.49  4470.5  311.68  4479.9  312.20
  4528.8  307.22  4538.3  307.37  4559.8  303.42  4639.4  293.67  4719.0  285.73
  4725.1  283.56  4740.3  283.56  4777.2  279.72  4783.5  277.80  4841.9  274.58
  4872.3  276.28  4893.7  274.08  4909.2  275.76  4967.4  276.51  5001.3  273.72
  5004.1  273.22  5007.3  273.72  5062.5  278.30  5129.0  285.93  5203.4  286.49
  5223.5  289.12  5313.5  294.13  5373.6  300.70  5393.6  304.31  5533.1  312.50
#Mann=3,-1,0
  4424.3    0.16       0  5001.3    0.07       0  5007.3    0.16       0
Bank Sta=5001.3,5007.3
Exp/Cntr=0.3,0.1

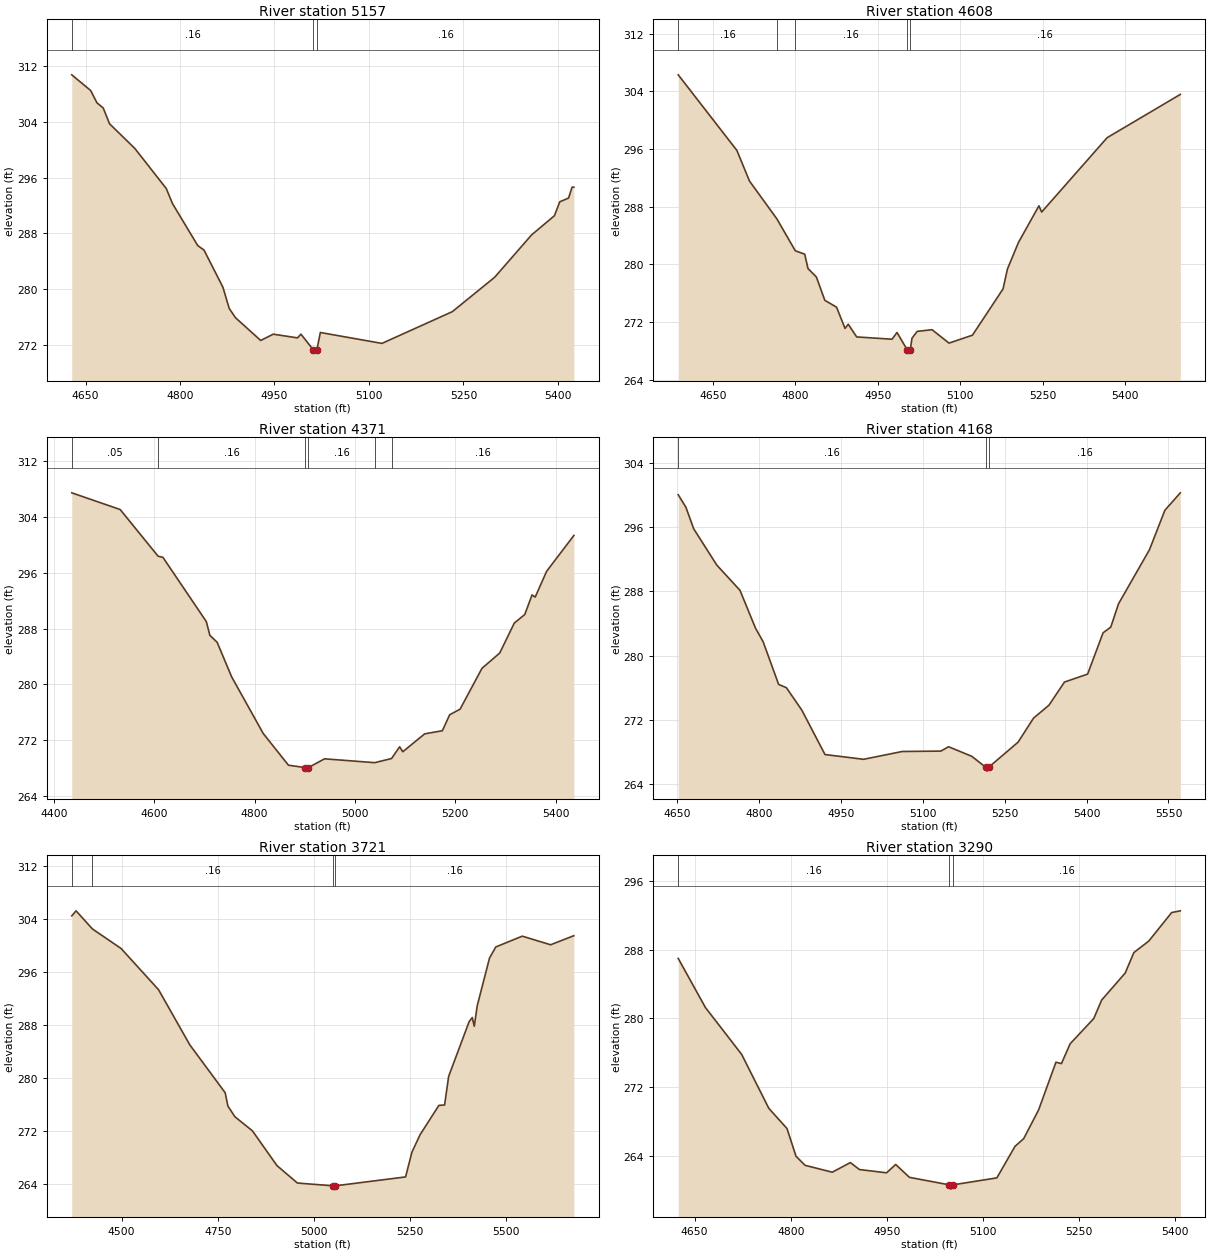
Type RM Length L Ch R = 1,5157,549,549,549
BEGIN DESCRIPTION:
NEALY BRANCH 10.0
END DESCRIPTION:
XS GIS Cut Line= 3
      3776699.58     10513960.19      3776349.61     10513960.19
      3775949.59     10514160.20
#Sta/Elev= 30
  4628.2  310.68  4658.2  308.44  4668.2  306.68  4678.2  305.93  4688.2  303.68
  4728.2  300.17  4778.2  294.43  4788.2  292.26  4828.2  286.27  4838.2  285.62
  4868.2  280.31  4878.2  277.28  4888.2  275.95  4928.2  272.70  4948.2  273.60
  4986.6  273.07  4992.1  273.60  5011.5  271.39  5014.3  270.89  5017.5  271.39
  5022.9  273.84  5120.7  272.28  5232.5  276.82  5299.6  281.73  5358.3  287.79
  5394.6  290.54  5403.0  292.52  5417.0  293.06  5422.6  294.62  5425.4  294.62
#Mann=3,-1,0
  4628.2    0.16       0  5011.5    0.07       0  5017.5    0.16       0
Bank Sta=5011.5,5017.5
Exp/Cntr=0.3,0.1

Type RM Length L Ch R = 1,4608,237,237,237
BEGIN DESCRIPTION:
NEALY BRANCH 9.0
END DESCRIPTION:
XS GIS Cut Line= 3
      3776660.36     10513806.01      3776160.35     10513496.97
      3775837.41     10513535.17
#Sta/Elev= 30
  4587.3  306.31  4694.0  295.81  4716.8  291.57  4766.6  286.32  4800.2  281.88
  4817.3  281.41  4823.3  279.41  4838.5  278.24  4853.9  275.00  4875.2  274.05
  4890.6  271.10  4896.5  271.68  4911.8  269.92  4976.1  269.60  4985.1  270.54
  5003.4  268.17  5006.2  267.67  5009.4  268.17  5012.3  269.73  5021.8  270.69
  5048.9  270.92  5079.7  269.06  5122.3  270.16  5178.0  276.59  5185.9  279.34
  5206.1  283.05  5243.2  288.12  5248.2  287.26  5367.2  297.58  5500.3  303.59
#Mann=5,-1,0
  4587.3    0.16       0  4766.6    0.05       0  4800.2    0.16       0
  5003.4    0.07       0  5009.4    0.16       0
Bank Sta=5003.4,5009.4
Exp/Cntr=0.3,0.1

Type RM Length L Ch R = 1,4371,203,203,203
BEGIN DESCRIPTION:
Mapping XS a3c33032
END DESCRIPTION:
XS GIS Cut Line= 2
      3776802.74     10513722.69      3776007.71     10513115.13
#Sta/Elev= 30
  4435.8  307.41  4532.3  305.02  4607.8  298.35  4617.5  298.18  4704.0  288.99
  4711.0  287.03  4725.5  286.04  4754.4  281.10  4817.3  273.00  4867.6  268.46
  4901.2  268.11  4904.0  267.61  4907.2  268.11  4939.6  269.37  5039.6  268.82
  5073.1  269.41  5089.2  271.09  5095.5  270.38  5139.1  272.94  5174.4  273.39
  5188.9  275.67  5209.7  276.47  5253.3  282.31  5288.7  284.50  5317.7  288.78
  5338.6  290.01  5353.1  292.81  5359.4  292.50  5382.1  296.18  5436.4  301.31
#Mann=6,-1,0
  4435.8    0.05       0  4607.8    0.16       0  4901.2    0.07       0
  4907.2    0.16       0  5039.6    0.05       0  5073.1    0.16       0
Bank Sta=4901.2,4907.2
Exp/Cntr=0.3,0.1

Type RM Length L Ch R = 1,4168,447,447,447
BEGIN DESCRIPTION:
NEALY BRANCH 8.0
END DESCRIPTION:
XS GIS Cut Line= 3
      3776749.60     10513510.18      3776499.61     10513260.19
      3776099.63     10512860.20
#Sta/Elev= 30
  4652.5  300.00  4666.6  298.44  4680.8  295.77  4723.2  291.25  4765.6  288.12
  4793.9  283.43  4808.0  281.72  4836.3  276.43  4850.5  276.02  4878.8  273.23
  4921.2  267.71  4991.9  267.12  5062.6  268.09  5133.3  268.14  5147.5  268.68
  5189.9  267.49  5215.2  266.15  5217.9  265.65  5221.2  266.15  5274.7  269.25
  5303.0  272.24  5331.3  273.85  5359.6  276.72  5402.0  277.71  5430.3  282.84
  5444.4  283.55  5458.6  286.45  5515.2  293.16  5543.4  298.07  5571.7  300.24
#Mann=3,-1,0
  4652.5    0.16       0  5215.2    0.07       0  5221.2    0.16       0
Bank Sta=5215.2,5221.2
Exp/Cntr=0.3,0.1

Type RM Length L Ch R = 1,3721,431,431,431
BEGIN DESCRIPTION:
NEALY BRANCH 7.0
END DESCRIPTION:
XS GIS Cut Line= 2
      3777271.50     10513080.32      3776043.41     10512636.27
#Sta/Elev= 30
  4370.3  304.46  4381.5  305.22  4424.0  302.49  4498.8  299.53  4596.1  293.32
  4677.4  285.00  4769.4  277.78  4776.4  275.78  4794.7  274.16  4840.2  272.04
  4904.0  266.80  4957.2  264.17  5049.9  263.75  5052.6  263.25  5055.9  263.75
  5238.6  265.09  5254.9  268.80  5276.2  271.45  5325.2  275.88  5340.0  275.94
  5350.6  280.26  5403.8  288.50  5411.9  289.13  5417.2  287.82  5425.0  290.93
  5456.9  298.10  5473.2  299.77  5542.0  301.40  5615.8  300.10  5676.2  301.47
#Mann=4,-1,0
  4370.3    0.05       0  4424.0    0.16       0  5049.9    0.07       0
  5055.9    0.16       0
Bank Sta=5049.9,5055.9
Exp/Cntr=0.3,0.1

Type RM Length L Ch R = 1,3290,440,440,440
BEGIN DESCRIPTION:
NEALY BRANCH 6.0
END DESCRIPTION:
XS GIS Cut Line= 3
      3777049.59     10512710.17      3776799.61     10512460.19
      3776449.64     10512210.21
#Sta/Elev= 30
  4624.4  286.98  4666.8  281.27  4723.4  275.81  4765.8  269.53  4794.1  267.19
  4808.2  263.96  4822.4  262.90  4864.8  262.10  4893.1  263.22  4907.2  262.41
  4949.6  262.03  4963.8  263.00  4985.3  261.50  5047.4  260.63  5050.2  260.13
  5053.4  260.63  5121.7  261.44  5150.0  265.11  5163.5  266.00  5186.8  269.34
  5213.9  274.90  5222.5  274.74  5236.0  277.04  5272.9  279.98  5285.2  282.13
  5322.0  285.28  5335.5  287.66  5358.9  289.01  5394.5  292.32  5408.0  292.52
#Mann=3,-1,0
  4624.4    0.16       0  5047.4    0.07       0  5053.4    0.16       0
Bank Sta=5047.4,5053.4
Exp/Cntr=0.3,0.1

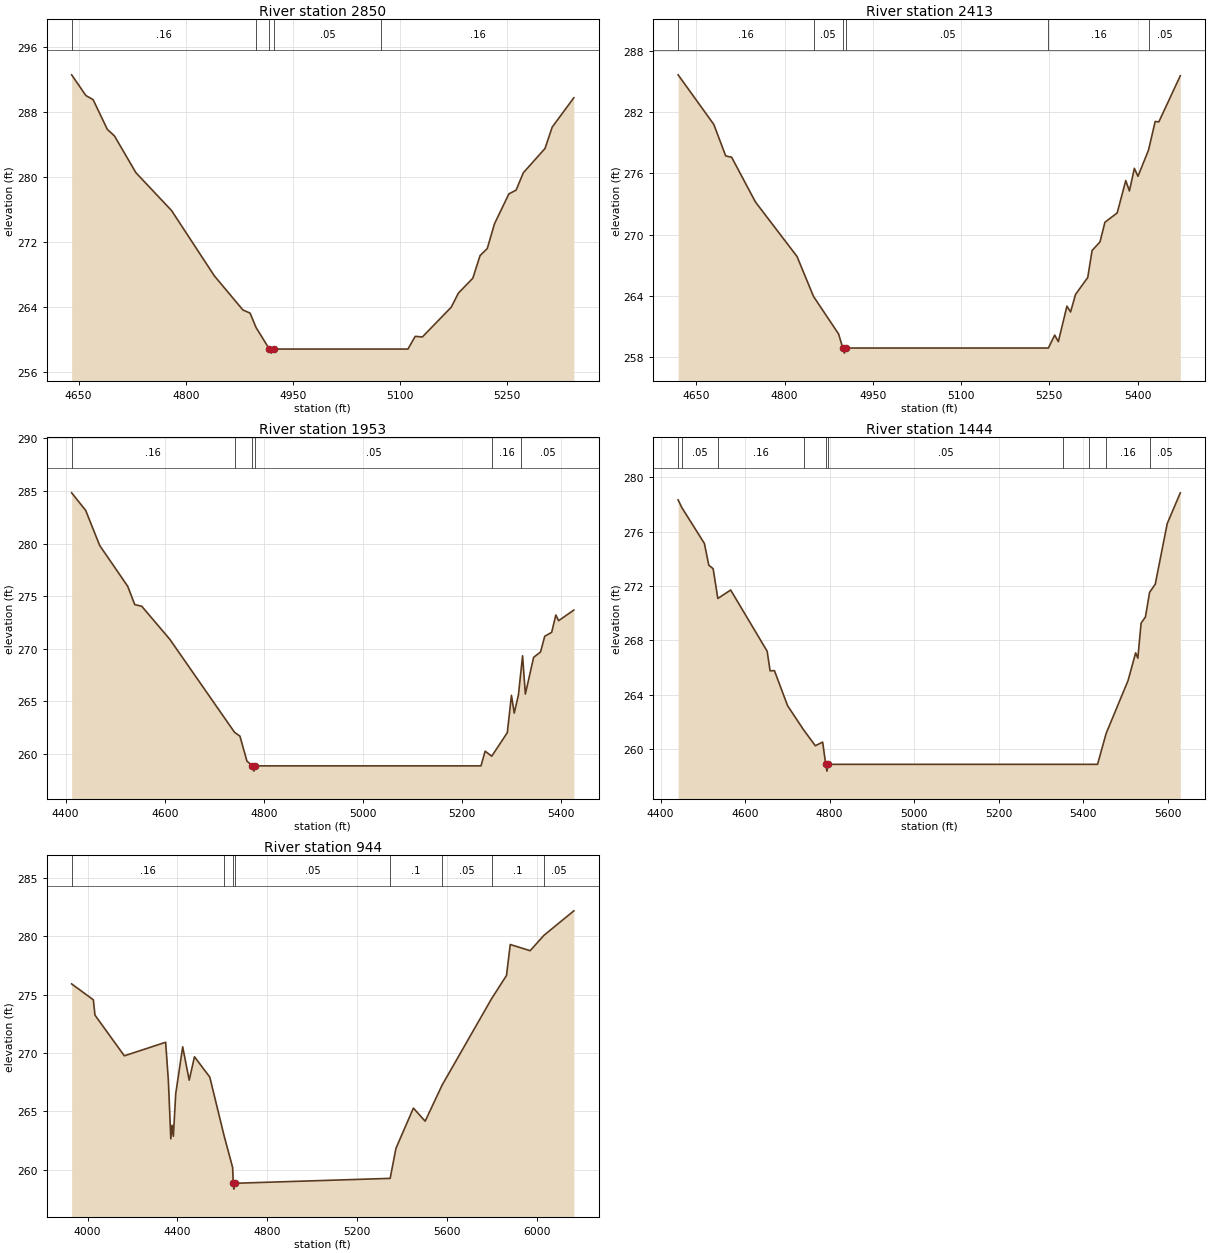
Type RM Length L Ch R = 1,2850,437,437,437
BEGIN DESCRIPTION:
NEALY BRANCH 5.0
END DESCRIPTION:
XS GIS Cut Line= 3
      3777199.62     10512010.19      3776849.61     10512010.19
      3776499.57     10512060.19
#Sta/Elev= 30
  4640.2  292.56  4660.2  290.01  4670.2  289.52  4690.2  285.86  4700.2  285.05
  4730.2  280.54  4780.2  275.88  4840.2  267.85  4880.2  263.66  4890.2  263.28
  4898.5  261.52  4917.2  258.86  4920.0  258.36  4923.2  258.86  5074.2  258.86
  5111.4  258.86  5121.5  260.42  5131.6  260.35  5172.0  264.00  5182.1  265.74
  5202.3  267.57  5212.4  270.35  5222.5  271.21  5232.6  274.25  5252.8  277.93
  5262.9  278.39  5273.0  280.52  5303.4  283.51  5313.5  286.14  5343.8  289.74
#Mann=5,-1,0
  4640.2    0.16       0  4898.5    0.05       0  4917.2   0.033       0
  4923.2    0.05       0  5074.2    0.16       0
Bank Sta=4917.2,4923.2
Exp/Cntr=0.3,0.1

Type RM Length L Ch R = 1,2413,460,460,460
BEGIN DESCRIPTION:
NEALY BRANCH 4.0
END DESCRIPTION:
XS GIS Cut Line= 3
      3777249.65     10511610.19      3776899.61     10511560.19
      3776499.61     10511860.19
#Sta/Elev= 30
  4619.1  285.68  4679.8  280.81  4700.0  277.72  4710.1  277.59  4750.5  273.20
  4821.2  267.85  4849.3  263.92  4891.9  260.24  4899.0  258.86  4901.7  258.36
  4905.0  258.86  5248.5  258.86  5259.2  260.13  5265.4  259.49  5280.0  262.97
  5286.2  262.40  5294.6  264.12  5315.4  265.79  5322.7  268.43  5336.2  269.28
  5344.6  271.21  5365.4  272.12  5380.0  275.30  5386.2  274.28  5394.6  276.50
  5400.8  275.72  5418.7  278.30  5430.0  281.10  5436.2  281.06  5472.7  285.59
#Mann=6,-1,0
  4619.1    0.16       0  4849.3    0.05       0  4899.0   0.033       0
  4905.0    0.05       0  5248.5    0.16       0  5418.7    0.05       0
Bank Sta=4899,4905
Exp/Cntr=0.3,0.1

Type RM Length L Ch R = 1,1953,509,509,509
BEGIN DESCRIPTION:
NEALY BRANCH 3.0
END DESCRIPTION:
XS GIS Cut Line= 3
      3777349.61     10511510.19      3776949.61     10511110.19
      3776549.61     10511310.19
#Sta/Elev= 30
  4412.3  284.83  4440.6  283.16  4468.9  279.82  4525.4  275.94  4539.6  274.20
  4553.7  274.04  4610.3  270.90  4740.9  262.05  4751.7  261.69  4765.9  259.31
  4777.0  258.86  4779.7  258.36  4783.0  258.86  5237.9  258.86  5246.3  260.26
  5259.6  259.78  5291.0  262.02  5299.4  265.57  5305.0  263.88  5313.4  265.60
  5319.1  268.13  5321.8  269.33  5327.4  265.69  5344.1  269.18  5358.1  269.70
  5366.5  271.19  5380.5  271.56  5388.9  273.21  5394.5  272.67  5425.2  273.68
#Mann=6,-1,0
  4412.3    0.16       0  4740.9    0.05       0  4777.0   0.033       0
  4783.0    0.05       0  5259.6    0.16       0  5319.1    0.05       0
Bank Sta=4777,4783
Exp/Cntr=0.3,0.1

Type RM Length L Ch R = 1,1444,500,500,500
BEGIN DESCRIPTION:
NEALY BRANCH 2.0
END DESCRIPTION:
XS GIS Cut Line= 3
      3777499.62     10510760.19      3776949.61     10510610.19
      3776349.58     10510760.20
#Sta/Elev= 30
  4441.4  278.34  4450.1  277.78  4503.6  275.13  4514.0  273.53  4524.3  273.27
  4535.4  271.08  4565.8  271.70  4652.2  267.19  4659.1  265.75  4669.4  265.76
  4700.5  263.18  4738.2  261.41  4766.2  260.23  4783.5  260.50  4790.8  258.86
  4793.6  258.36  4796.8  258.86  5351.6  258.86  5414.0  258.86  5434.1  258.86
  5454.4  261.13  5506.3  265.03  5524.3  267.07  5529.5  266.68  5537.2  269.26
  5547.5  269.72  5557.3  271.53  5570.7  272.13  5599.0  276.59  5630.0  278.86
#Mann=10,-1,0
  4441.4    0.16       0  4450.1    0.05       0  4535.4    0.16       0
  4738.2    0.05       0  4790.8   0.033       0  4796.8    0.05       0
  5351.6     0.1       0  5414.0    0.05       0  5454.4    0.16       0
  5557.3    0.05       0
Bank Sta=4790.8,4796.8
Exp/Cntr=0.3,0.1

Type RM Length L Ch R = 1,944,0,0,0
BEGIN DESCRIPTION:
NEALY BRANCH 1.0
END DESCRIPTION:
XS GIS Cut Line= 4
      3777582.22     10510545.57      3777339.17     10509983.08
      3776380.83     10510274.75      3776186.38     10510865.06
#Sta/Elev= 30
  3928.9  275.91  4025.5  274.55  4032.8  273.24  4163.5  269.76  4347.4  270.92
  4359.6  267.63  4370.5  262.66  4376.3  263.82  4381.8  262.88  4392.3  266.52
  4423.3  270.53  4452.3  267.68  4475.8  269.68  4544.0  267.94  4607.2  262.96
  4645.7  260.21  4648.4  258.86  4651.2  258.36  4654.4  258.86  5347.1  259.28
  5372.7  261.84  5450.6  265.29  5502.9  264.17  5578.5  267.26  5798.5  274.64
  5865.0  276.63  5881.8  279.28  5970.3  278.75  6031.5  280.06  6164.9  282.16
#Mann=8,-1,0
  3928.9    0.16       0  4607.2    0.05       0  4648.4   0.033       0
  4654.4    0.05       0  5347.1     0.1       0  5578.5    0.05       0
  5798.5     0.1       0  6031.5    0.05       0
Bank Sta=4648.4,4654.4
Exp/Cntr=0.3,0.1

Chan Stop Cuts=-1