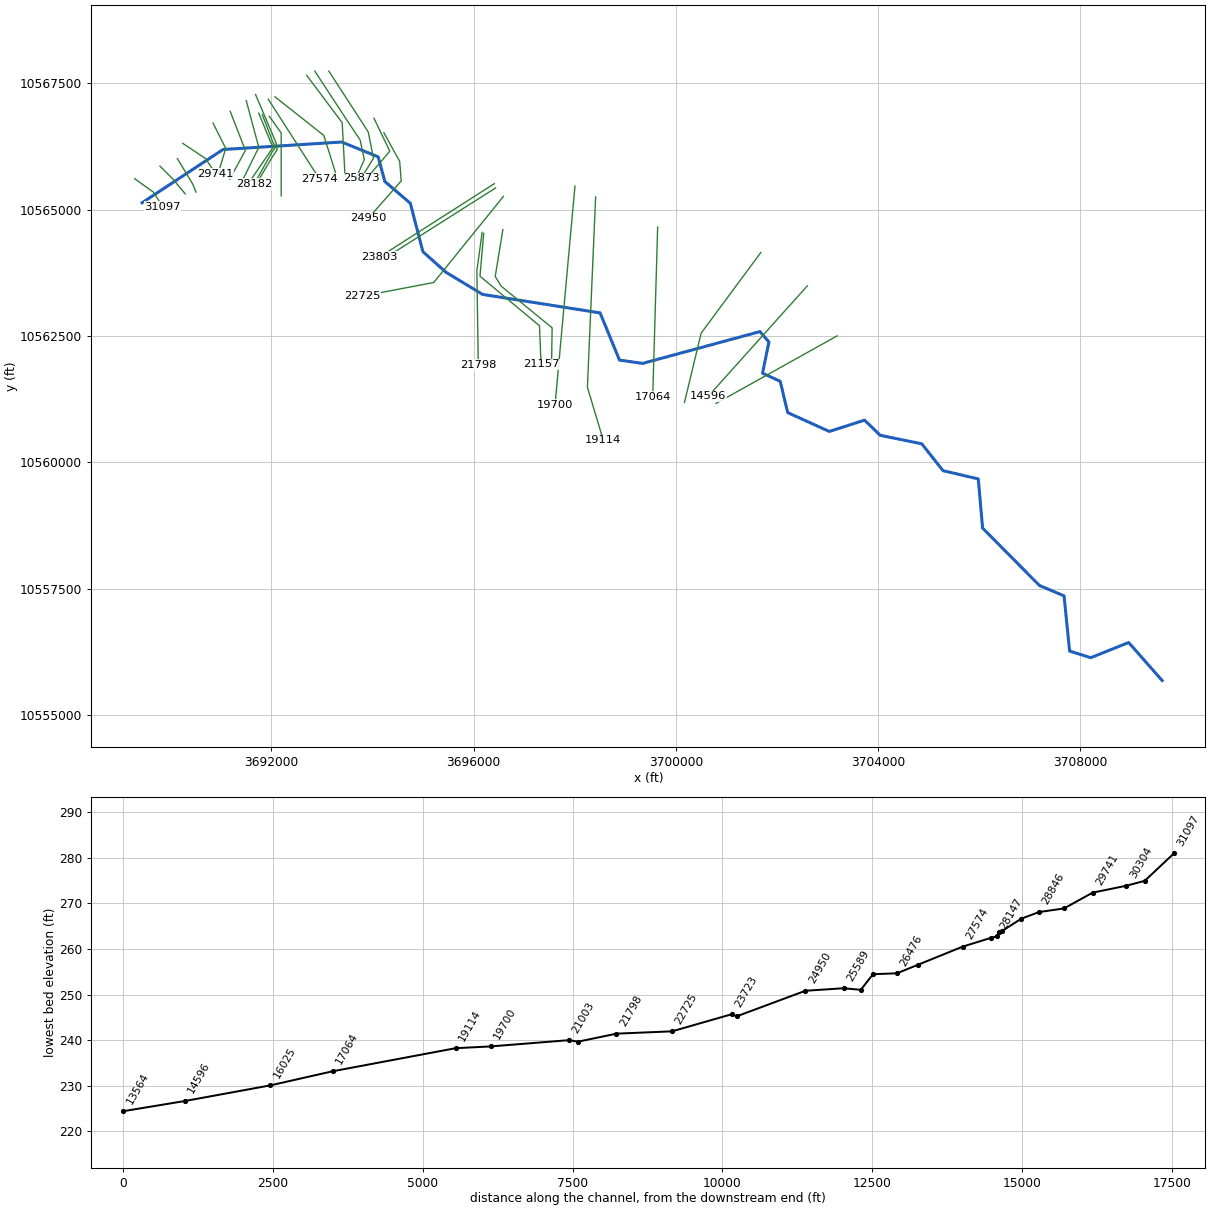
--- NORTHWEST FORK BOONS CR.prj (project) ---

Proj Title=NORTHWEST FORK BOONS CR Base Level Engineering
Current Plan=p01
Default Exp/Contr=0.3,0.1
English Units
Geom File=g01
Flow File=f01
Plan File=p01
Y Axis Title=Elevation
X Axis Title(PF)=Main Channel Distance
X Axis Title(XS)=Station
BEGIN DESCRIPTION:
NORTHWEST FORK BOONS CR
END DESCRIPTION:
DSS Export Rating Curves= 0
DSS Export Rating Curve Sorted= 0
DSS Export Volume Flow Curves= 0
DXF OffsetX= 0
DXF OffsetY= 0
DXF ScaleX= 1
DXF ScaleY= 10

--- NORTHWEST FORK BOONS CR.p01 (plan) ---

Plan Title=Multiple Run
Short Identifier=Multiple
Geom File=g01
Flow File=f01
Subcritical Flow
K Sum by GR= 0
Std Step Tol= 0.01
Critical Tol= 0.01
Num of Std Step Trials= 20
Max Error Tol= 0.3
Flow Tol Ratio= 0.001
Split Flow NTrial= 30
Split Flow Tol= 0.02
Split Flow Ratio= 0.02
Log Output Level= 0
Friction Slope Method= 1
Unsteady Friction Slope Method= 2
Unsteady Bridges Friction Slope Method= 1
Parabolic Critical Depth
Global Vel Dist=  1 , 1 , 1
Global Log Level= 0
CheckData=True
Encroach Param= -1, 0, 0, 0
BEGIN DESCRIPTION:
Multiple Run
END DESCRIPTION:

--- NORTHWEST FORK BOONS CR.f01 (steady flow) ---

Flow Title=Multiple
Program Version=4.10
Number of Profiles= 7
Profile Names=10-year,25-year,50-year,1pct_min,100-year,1pct_plu,500-year
River Rch & RM=NORTHWEST FORK B,Reach-1         ,31097
     516     698     847     757    1023    1384    1499
River Rch & RM=NORTHWEST FORK B,Reach-1         ,26476
     642     876    1070     961    1299    1757    1922
River Rch & RM=NORTHWEST FORK B,Reach-1         ,23803
    1548    2201    2765    2543    3439    4651    5350
River Rch & RM=NORTHWEST FORK B,Reach-1         ,21798
    2049    2941    3717    3437    4648    6286    7307
River Rch & RM=NORTHWEST FORK B,Reach-1         ,21157
    2049    2941    3717    3437    4648    6286    7307
River Rch & RM=NORTHWEST FORK B,Reach-1         ,17064
    2181    3128    3950    3647    4933    6671    7734
River Rch & RM=NORTHWEST FORK B,Reach-1         ,10136
    2300    3301    4170    3852    5209    7045    8172
River Rch & RM=NORTHWEST FORK B,Reach-1         ,7156
    2316    3314    4177    3849    5206    7040    8128
Boundary for River Rch & Prof#=NORTHWEST FORK B,Reach-1         , 1
Up Type= 0
Dn Type= 1
Dn Known WS=215.5
Boundary for River Rch & Prof#=NORTHWEST FORK B,Reach-1         , 2
Up Type= 0
Dn Type= 1
Dn Known WS=216.55
Boundary for River Rch & Prof#=NORTHWEST FORK B,Reach-1         , 3
Up Type= 0
Dn Type= 1
Dn Known WS=217.26
Boundary for River Rch & Prof#=NORTHWEST FORK B,Reach-1         , 4
Up Type= 0
Dn Type= 1
Dn Known WS=217.02
Boundary for River Rch & Prof#=NORTHWEST FORK B,Reach-1         , 5
Up Type= 0
Dn Type= 1
Dn Known WS=217.98
Boundary for River Rch & Prof#=NORTHWEST FORK B,Reach-1         , 6
Up Type= 0
Dn Type= 1
Dn Known WS=219.04
Boundary for River Rch & Prof#=NORTHWEST FORK B,Reach-1         , 7
Up Type= 0
Dn Type= 1
Dn Known WS=219.59
DSS Import GetInterval= 0
DSS Import GetPeak= 0
DSS Import FillOption= 0

--- NORTHWEST FORK BOONS CR.g01 (geometry) ---

Geom Title=Existing Conditions
Program Version=4.10

River Reach=NORTHWEST FORK B,Reach-1
Reach XY= 30
      3689446.99     10565134.46        3691047.       10566188.
      3693392.25       10566336.      3694113.75       10566043.
      3694246.25       10565554.      3694749.25       10565125.
      3694999.25       10564165.       3695458.5       10563756.
      3696179.25       10563321.        3698502.       10562955.
      3698885.25       10562022.      3699342.25       10561956.
      3701662.25       10562585.      3701839.75       10562380.
      3701713.75       10561762.       3702063.5       10561602.
      3702210.75       10560983.        3703034.       10560609.
       3703730.5       10560833.      3704041.25       10560533.
      3704862.25       10560365.      3705281.75       10559834.
       3705979.5       10559670.       3706064.5       10558698.
      3707189.75       10557561.      3707675.25       10557357.
        3707785.       10556265.        3708203.       10556133.
      3708952.25       10556434.        3709615.       10555681.

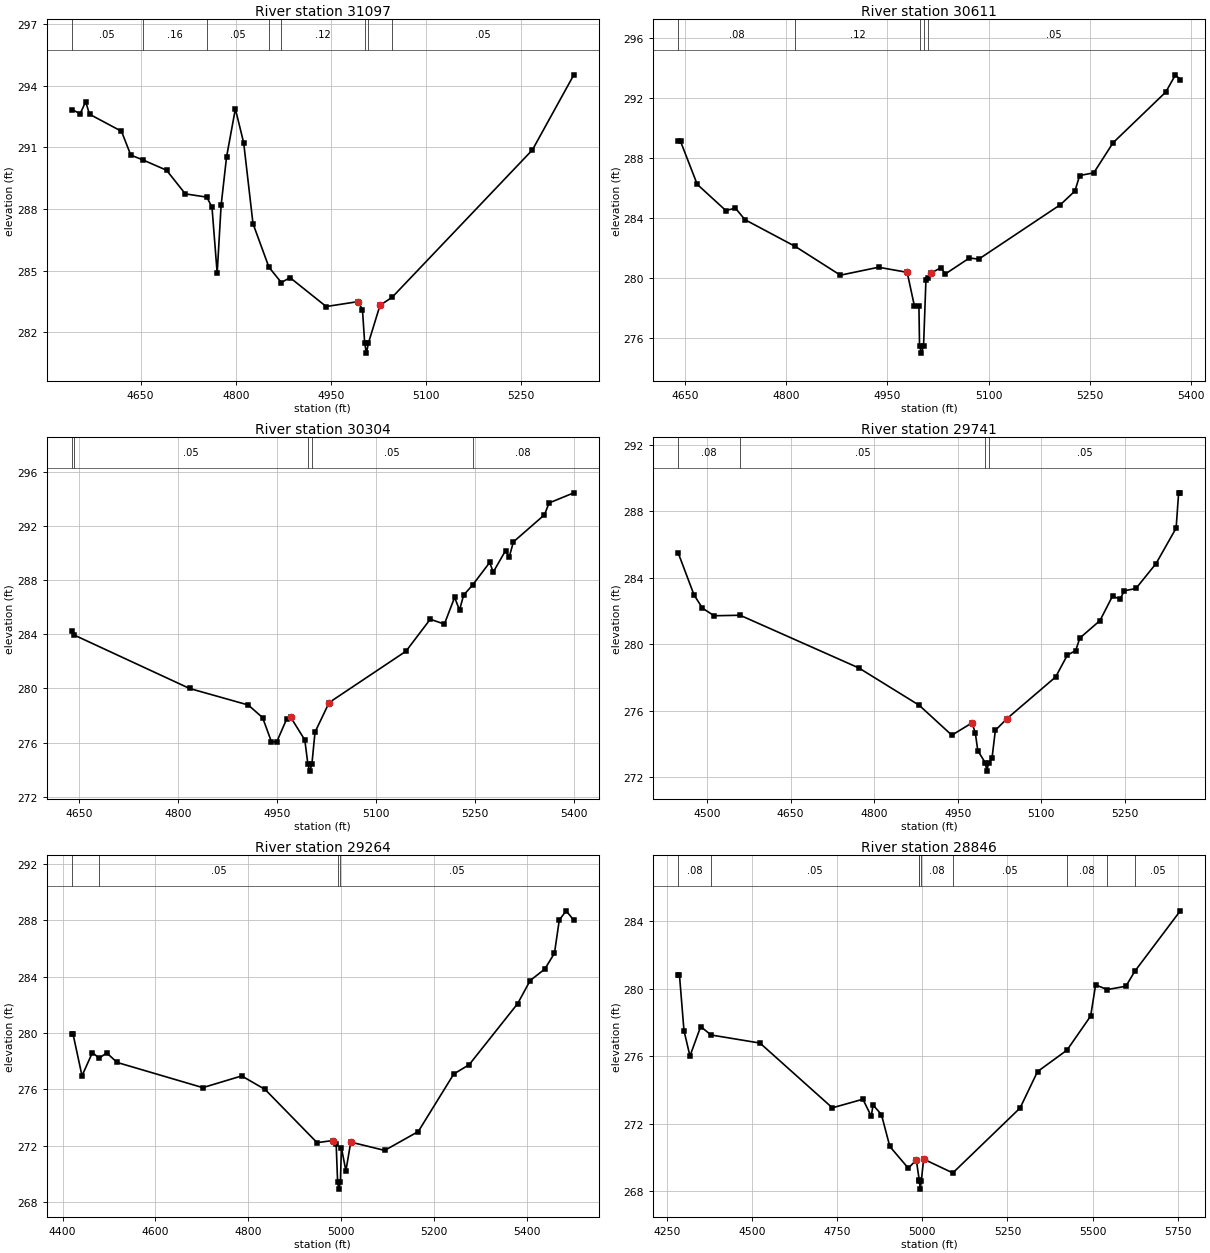
Type RM Length L Ch R = 1 ,31097   ,486,486,486
BEGIN DESCRIPTION:
NORTHWEST FORK BOONS CR 49.0
END DESCRIPTION:
XS GIS Cut Line= 3
      3689299.64     10565610.16      3689672.52     10565342.84
      3689849.58     10565060.23
#Sta/Elev= 30
  4541.2  292.85  4554.7  292.65  4563.3  293.23  4569.4  292.62  4619.8  291.79
  4634.5  290.63  4653.2   290.4    4691  289.89  4720.5  288.74  4754.5  288.58
  4762.6  288.09  4770.8  284.87    4777  288.18  4785.6  290.54  4799.5  292.88
  4812.6  291.23  4827.3  287.29  4852.4  285.17    4872  284.42  4885.7  284.66
  4942.8  283.25  4993.1  283.49    5000   283.1  5003.5  281.48  5006.2  280.98
  5009.5  281.48  5027.7  283.31  5046.8   283.7  5268.1  290.88  5333.5  294.54
#Mann= 8 ,-1 , 0
  4541.2     .05       0  4653.2     .16       0  4754.5     .05       0
  4852.4     .16       0    4872     .12       0  5003.5     .07       0
  5009.5     .12       0  5046.8     .05       0
Bank Sta=4993.1,5027.7
XS Rating Curve= 0 ,0
Exp/Cntr=0.3,0.1

Type RM Length L Ch R = 1 ,30611   ,307,307,307
BEGIN DESCRIPTION:
NORTHWEST FORK BOONS CR 48.0
END DESCRIPTION:
XS GIS Cut Line= 3
      3689799.59     10565860.21      3690049.61     10565610.19
      3690299.61     10565310.18
#Sta/Elev= 30
  4640.1  289.12  4643.7  289.12  4668.4  286.25  4710.8   284.5    4725  284.66
  4739.1  283.89  4813.7   282.1  4880.5  280.18  4937.1  280.71  4979.5  280.37
  4990.1  278.14  4996.9  278.14  4997.8  275.47  5000.6  274.97  5003.8  275.47
  5007.3  279.87  5009.9  280.02  5015.2  280.33  5029.5  280.68    5036  280.26
  5071.8  281.33  5085.5  281.25  5206.5  284.89    5228   285.8  5235.1  286.84
    5256  287.02  5284.6  289.03  5362.7  292.42    5377  293.57  5384.2  293.25
#Mann= 5 ,-1 , 0
  4640.1     .08       0  4813.7     .12       0  4997.8     .07       0
  5003.8     .12       0  5009.9     .05       0
Bank Sta=4979.5,5015.2
XS Rating Curve= 0 ,0
Exp/Cntr=0.3,0.1

Type RM Length L Ch R = 1 ,30304   ,563,563,563
BEGIN DESCRIPTION:
NORTHWEST FORK BOONS CR 47.0
END DESCRIPTION:
XS GIS Cut Line= 3
      3690142.92     10566009.47      3690446.75     10565505.97
      3690511.87     10565345.34
#Sta/Elev= 30
  4638.5  284.22  4641.6  283.95  4817.3  279.99  4906.3  278.77    4928  277.84
  4941.3  276.07  4949.3  276.03  4964.7  277.76  4970.7  277.86    4992  276.19
  4996.7  274.39  4999.5  273.89  5002.7  274.39  5007.5  276.77  5028.9  278.95
  5145.4  282.74  5182.2   285.1  5203.6  284.74  5219.1  286.71  5226.6  285.78
  5232.8  286.88  5246.5  287.63  5272.3  289.29  5277.7  288.58  5296.4  290.17
  5301.8  289.67  5308.3  290.81  5355.4  292.81  5362.3  293.68  5399.9  294.43
#Mann= 5 ,-1 , 0
  4638.5     .08       0  4641.6     .05       0  4996.7     .03       0
  5002.7     .05       0  5246.5     .08       0
Bank Sta=4970.7,5028.9
XS Rating Curve= 0 ,0
Exp/Cntr=0.3,0.1

Type RM Length L Ch R = 1 ,29741   ,477,477,477
BEGIN DESCRIPTION:
NORTHWEST FORK BOONS CR 46.0
END DESCRIPTION:
XS GIS Cut Line= 3
      3690249.58     10566310.21      3690699.61     10566010.19
      3690899.59     10565710.21
#Sta/Elev= 30
    4448   285.5  4476.6  282.96  4491.6  282.17  4512.6  281.71  4559.3  281.74
  4772.5  278.57  4880.7  276.33  4939.3  274.53  4975.4  275.27  4981.4  274.68
  4985.9   273.6  4999.4  272.87  5002.1  272.37  5005.4  272.87  5011.4  273.14
  5017.4  274.82  5038.4  275.53  5125.6  278.03  5146.6  279.34  5161.6  279.62
  5169.1  280.37  5205.2  281.42  5227.7  282.89  5241.3  282.71  5248.8  283.21
  5269.8  283.35  5305.9  284.85  5341.9  286.98  5346.4   289.1  5349.4   289.1
#Mann= 4 ,-1 , 0
    4448     .08       0  4559.3     .05       0  4999.4     .03       0
  5005.4     .05       0
Bank Sta=4975.4,5038.4
XS Rating Curve= 0 ,0
Exp/Cntr=0.3,0.1

Type RM Length L Ch R = 1 ,29264   ,418,418,418
BEGIN DESCRIPTION:
NORTHWEST FORK BOONS CR 45.0
END DESCRIPTION:
XS GIS Cut Line= 3
      3690849.62     10566710.17      3691099.61     10566210.19
      3690949.61      10565710.2
#Sta/Elev= 30
  4419.6  279.95  4422.4  279.95  4441.9  276.96  4464.3  278.61  4478.8  278.21
    4495  278.59  4517.4  277.91  4701.9  276.12  4785.7  276.95    4836  275.99
  4947.9  272.21  4981.2  272.36    4989  272.11  4992.1  269.41  4994.9  268.91
  4998.1  269.41  5000.3  271.85  5009.9  270.21  5020.4  272.25  5093.4  271.66
  5165.7     273  5242.2  277.09  5275.3  277.75  5379.7  282.09  5406.6  283.73
    5438  284.54  5458.9  285.67  5469.3  288.03  5484.1  288.68  5500.6  288.01
#Mann= 4 ,-1 , 0
  4419.6     .08       0  4478.8     .05       0  4992.1     .03       0
  4998.1     .05       0
Bank Sta=4981.2,5020.4
XS Rating Curve= 0 ,0
Exp/Cntr=0.3,0.1

Type RM Length L Ch R = 1 ,28846   ,293,293,293
BEGIN DESCRIPTION:
NORTHWEST FORK BOONS CR 44.0
END DESCRIPTION:
XS GIS Cut Line= 3
      3691188.93     10566942.63      3691488.42     10566170.03
      3691180.28     10565601.48
#Sta/Elev= 30
  4282.5  280.79  4286.5  280.79  4299.7  277.51  4317.3     276  4348.8  277.75
    4379  277.25    4523  276.77  4735.6  272.93  4825.3  273.44  4849.9  272.43
  4855.2   273.1  4879.8  272.53  4904.4  270.64  4958.8  269.35  4982.2  269.84
  4990.6  268.68  4991.1  268.61  4993.9  268.11  4997.1  268.61  5003.7  269.89
  5089.5  269.07  5287.1  272.92  5338.4  275.08  5424.9  276.35  5494.4  278.37
    5509  280.22  5543.2  279.94  5598.1  280.14  5623.9  281.02  5757.8  284.61
#Mann= 9 ,-1 , 0
  4282.5     .08       0    4379     .05       0  4990.6     .08       0
  4991.1     .07       0  4997.1     .08       0  5089.5     .05       0
  5424.9     .08       0  5543.2      .1       0  5623.9     .05       0
Bank Sta=4982.2,5003.7
XS Rating Curve= 0 ,0
Exp/Cntr=0.3,0.1

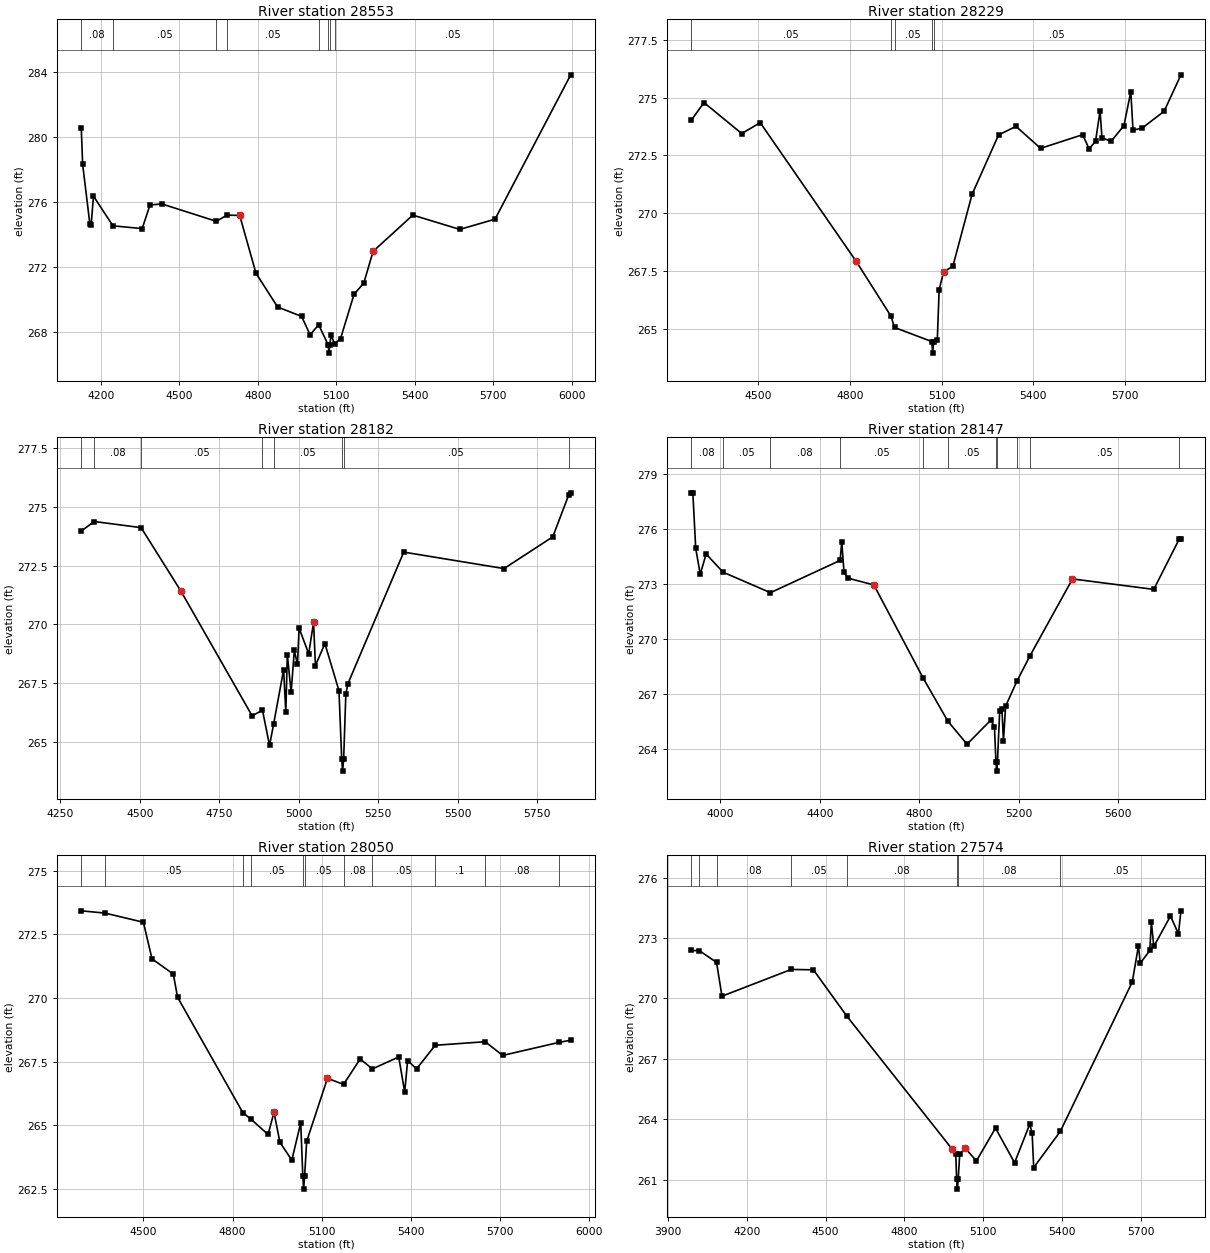
Type RM Length L Ch R = 1 ,28553   ,324,324,324
BEGIN DESCRIPTION:
NORTHWEST FORK BOONS CR 43.0
END DESCRIPTION:
XS GIS Cut Line= 3
      3691505.77     10567155.32      3691753.18      10566230.8
      3691349.53     10565410.48
#Sta/Elev= 30
  4125.3  280.54  4130.6  278.29    4158  274.65  4163.2  274.58    4172  276.34
  4246.4  274.51  4358.3  274.34  4387.9  275.79  4433.1  275.86  4641.5  274.79
  4682.9  275.17    4731  275.15  4793.1   271.6  4875.9  269.51  4967.9  268.93
  5000.2   267.8  5032.8  268.42  5069.6  267.17  5072.4  266.67  5075.6  267.17
  5080.1  267.78  5094.3  267.24  5116.5  267.56  5168.2  270.29  5205.6  270.99
  5241.1  272.94  5392.9  275.17  5572.6  274.29  5707.2  274.92  5996.6  283.81
#Mann= 8 ,-1 , 0
  4125.3     .08       0  4246.4     .05       0  4641.5     .08       0
  4682.9     .05       0  5032.8     .08       0  5069.6     .04       0
  5075.6     .08       0  5094.3     .05       0
Bank Sta=4731,5241.1
XS Rating Curve= 0 ,0
Exp/Cntr=0.3,0.1

Type RM Length L Ch R = 1 ,28229   ,47,47,47
BEGIN DESCRIPTION:
Mapping XS 4747ba40
END DESCRIPTION:
XS GIS Cut Line= 5
      3691752.29     10566907.92      3691999.71     10566308.92
      3692028.35     10566272.46      3692025.75     10566215.17
      3691546.76     10565514.91
#Sta/Elev= 30
  4282.5  274.04  4323.3  274.79  4446.7  273.45  4507.2  273.92    4821  267.92
  4934.7  265.55  4946.3  265.06  5068.2  264.45  5070.9  263.95  5074.2  264.45
  5086.1  264.51  5092.2   266.7  5107.1  267.48  5136.9   267.7  5199.8  270.82
  5286.5  273.39  5343.4  273.76    5424  272.81  5561.3   273.4  5582.4  272.79
  5603.4  273.11  5618.3  274.43  5624.4  273.27  5654.2  273.11  5696.2  273.79
  5718.8  275.26    5726   273.6  5755.2  273.68  5827.6  274.41  5882.7  275.99
#Mann= 5 ,-1 , 0
  4282.5     .05       0  4934.7     .08       0  4946.3     .05       0
  5068.2     .04       0  5074.2     .05       0
Bank Sta=4821,5107.1
XS Rating Curve= 0 ,0
Exp/Cntr=0.3,0.1

Type RM Length L Ch R = 1 ,28182   ,35,35,35
BEGIN DESCRIPTION:
Mapping XS c908c582
END DESCRIPTION:
XS GIS Cut Line= 6
      3691822.62     10566879.25      3692038.77     10566316.73
      3692070.02     10566277.67      3692077.83     10566222.98
      3692023.14     10566150.07      3691661.35     10565504.67
#Sta/Elev= 30
  4315.5  273.97  4356.7  274.37  4503.8  274.11  4629.1  271.41  4853.1  266.11
  4885.6  266.35  4907.8  264.85  4920.5  265.75  4952.1  268.07    4959  266.26
  4963.8  268.71  4975.7  267.11  4985.8  268.89  4995.7   268.3  5000.8  269.84
    5031  268.75  5046.3  270.08  5052.2  268.25    5082  269.18  5126.2  267.18
  5134.9  264.26  5137.6  263.76  5140.9  264.26  5147.8  267.02  5153.5  267.45
    5330  273.07  5645.6  272.37  5798.9  273.72  5848.7  275.49  5855.3  275.59
#Mann= 8 ,-1 , 0
  4315.5     .05       0  4356.7     .08       0  4503.8     .05       0
  4885.6     .08       0  4920.5     .05       0  5134.9     .04       0
  5140.9     .05       0  5848.7     .08       0
Bank Sta=4629.1,5046.3
XS Rating Curve= 0 ,0
Exp/Cntr=0.3,0.1

Type RM Length L Ch R = 1 ,28147   ,97,97,97
BEGIN DESCRIPTION:
NORTHWEST FORK BOONS CR 42.0
END DESCRIPTION:
XS GIS Cut Line= 5
       3691689.8     10567275.09      3692098.66     10566311.53
      3692116.89     10566183.92      3692015.33     10566030.28
      3691703.99     10565506.18
#Sta/Elev= 30
  3883.9  277.98  3889.3  277.98  3900.9  274.95  3919.1  273.54  3942.8  274.64
  4010.8  273.65  4201.6  272.53  4481.9  274.29  4488.6   275.3  4497.6  273.66
  4512.2  273.33  4617.8  272.95  4816.4  267.86  4914.8  265.53  4992.6  264.26
    5088  265.57  5102.9  265.22  5108.9  263.29  5111.7  262.79  5114.9  263.29
    5124  266.07  5133.1  266.17  5139.1  264.44  5147.9  266.34    5193  267.69
  5245.3  269.07  5416.9  273.28    5744  272.71  5846.1  275.45  5853.3  275.46
#Mann= 11 ,-1 , 0
  3883.9     .08       0  4010.8     .05       0  4201.6     .08       0
  4481.9     .05       0  4816.4     .08       0  4914.8     .05       0
  5108.9     .04       0  5114.9     .05       0    5193     .08       0
  5245.3     .05       0  5846.1     .08       0
Bank Sta=4617.8,5416.9
XS Rating Curve= 0 ,0
Exp/Cntr=0.3,0.1

Type RM Length L Ch R = 1 ,28050   ,476,476,476
BEGIN DESCRIPTION:
Mapping XS 3078161b
END DESCRIPTION:
XS GIS Cut Line= 3
        3691962.     10566844.03      3692196.41     10566515.87
      3692196.41     10565271.05
#Sta/Elev= 30
  4290.5  273.43  4370.7  273.34  4499.7  272.98  4528.7  271.54  4600.5  270.94
  4614.7  270.03  4834.5  265.49  4861.2  265.24  4919.5  264.63  4939.5   265.5
  4959.5  264.32  4999.5  263.62  5029.5  265.09  5036.5  262.98  5039.2  262.48
  5042.5  262.98  5049.5  264.36  5119.5  266.84  5173.7   266.6  5229.5   267.6
  5270.7  267.21  5359.5  267.68  5379.5   266.3  5389.5  267.54  5419.5  267.21
  5482.2  268.14  5650.5  268.28  5709.5  267.74  5897.6  268.25  5938.6  268.34
#Mann= 11 ,-1 , 0
  4290.5     .08       0  4370.7     .05       0  4834.5     .08       0
  4861.2     .05       0  5036.5     .04       0  5042.5     .05       0
  5173.7     .08       0  5270.7     .05       0  5482.2      .1       0
  5650.5     .08       0  5897.6     .05       0
Bank Sta=4939.5,5119.5
XS Rating Curve= 0 ,0
Exp/Cntr=0.3,0.1

Type RM Length L Ch R = 1 ,27574   ,749,749,749
BEGIN DESCRIPTION:
NORTHWEST FORK BOONS CR 41.0
END DESCRIPTION:
XS GIS Cut Line= 2
      3691941.54     10567182.19      3692947.68       10565614.
#Sta/Elev= 30
  3989.8  272.38  4019.9  272.37  4085.2  271.79  4105.8  270.11  4369.5  271.44
    4454  271.42  4580.6  269.13  4980.6  262.54  4995.8  262.29  4999.1  261.03
  5001.8  260.53  5005.1  261.03    5011  262.28  5032.1  262.56  5074.4  261.93
  5147.1  263.56  5219.8  261.84  5277.3  263.75  5286.5  263.33  5292.5   261.6
  5393.9   263.4  5667.8  270.82  5691.2  272.61  5698.2  271.75  5734.5  272.38
  5740.4   273.8  5749.7  272.58  5813.1  274.09  5843.5  273.21    5853  274.35
#Mann= 8 ,-1 , 0
  3989.8     .08       0  4019.9     .05       0  4085.2     .08       0
  4369.5     .05       0  4580.6     .08       0  4999.1     .07       0
  5005.1     .08       0  5393.9     .05       0
Bank Sta=4980.6,5032.1
XS Rating Curve= 0 ,0
Exp/Cntr=0.3,0.1

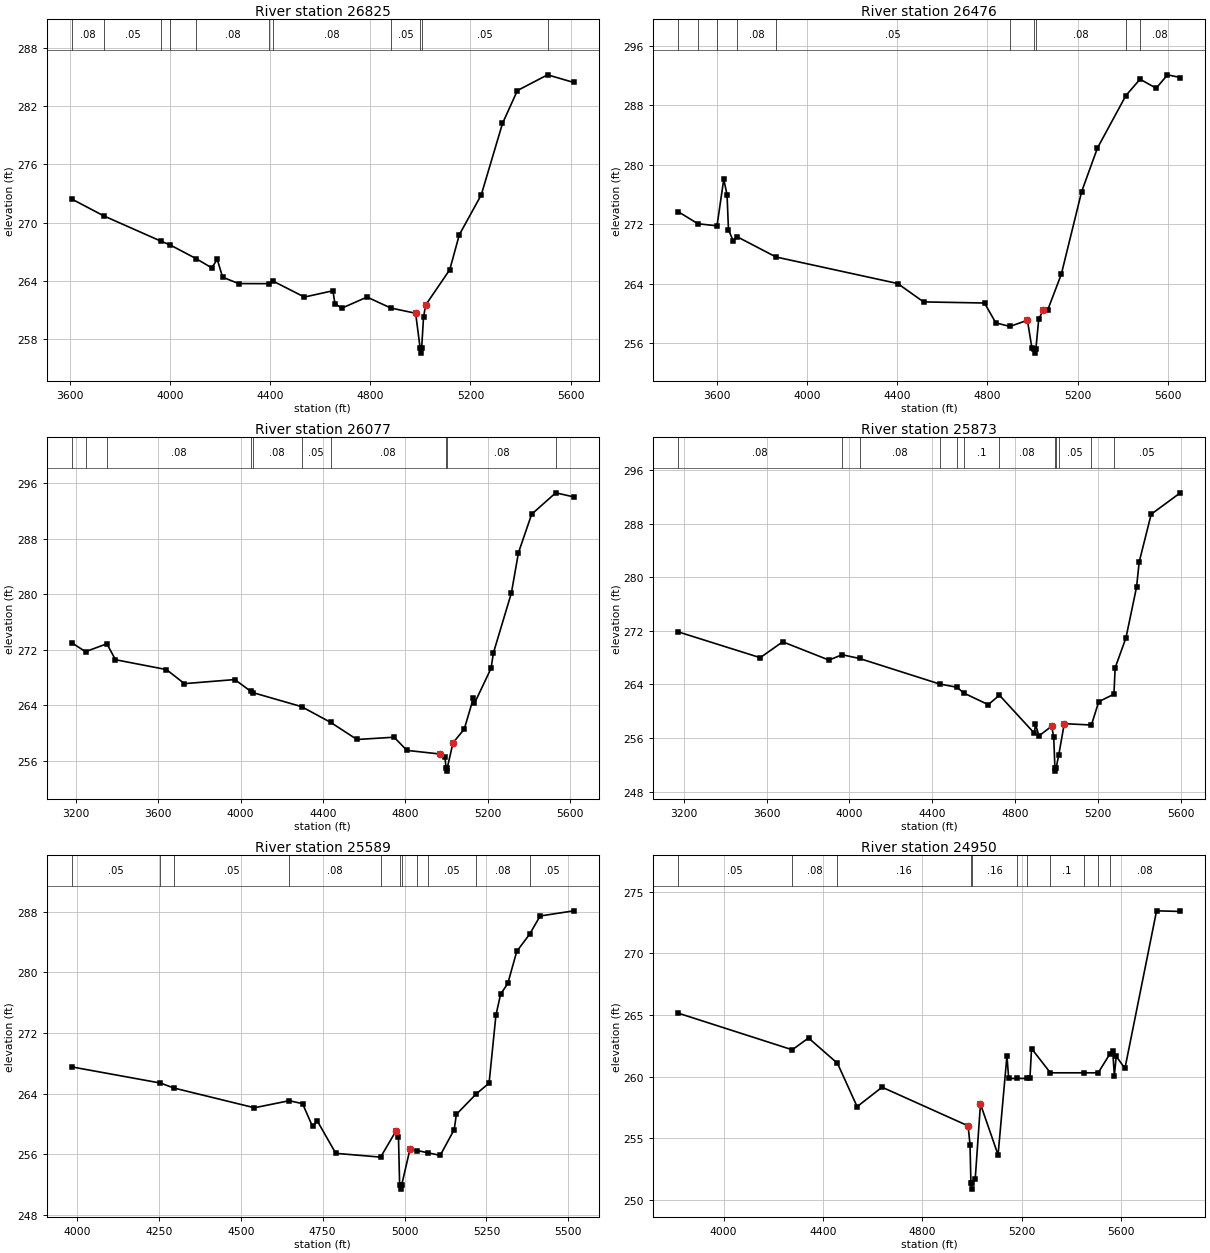
Type RM Length L Ch R = 1 ,26825   ,349,349,349
BEGIN DESCRIPTION:
NORTHWEST FORK BOONS CR 40.0
END DESCRIPTION:
XS GIS Cut Line= 3
      3692073.53     10567230.77      3693038.77     10566466.91
       3693271.4     10565727.35
#Sta/Elev= 30
  3606.9  272.43  3734.3   270.7  3964.6  268.07  3999.9   267.7  4104.2  266.28
  4166.6  265.33  4188.5  266.21  4209.9  264.37    4274  263.71  4395.4   263.7
  4410.2  263.98  4536.8  262.32  4650.6  262.97  4658.7  261.64  4685.9  261.17
  4786.9  262.32  4881.8  261.19  4981.1  260.65  4999.1  257.04  5001.9  256.54
  5005.1  257.04  5012.6  260.22  5020.9  261.49  5117.4  265.14  5155.7  268.75
  5243.2  272.85  5328.1  280.22  5387.6  283.61  5508.1  285.23  5613.1  284.44
#Mann= 11 ,-1 , 0
  3606.9     .08       0  3734.3     .05       0  3964.6      .1       0
  3999.9     .05       0  4104.2     .08       0  4395.4     .05       0
  4410.2     .08       0  4881.8     .05       0  4999.1     .04       0
  5005.1     .05       0  5508.1     .08       0
Bank Sta=4981.1,5020.9
XS Rating Curve= 0 ,0
Exp/Cntr=0.3,0.1

Type RM Length L Ch R = 1 ,26476   ,399,399,399
BEGIN DESCRIPTION:
Mapping XS adb6b337
END DESCRIPTION:
XS GIS Cut Line= 3
       3692701.6     10567654.77        3693403.     10566717.25
      3693458.47     10565663.47
#Sta/Elev= 30
  3429.5  273.71  3517.2  272.08  3601.9   271.8  3631.8  278.06  3646.4  275.98
  3652.7  271.28  3673.5  269.78  3691.3  270.33  3863.4  267.61  4402.9  264.04
  4517.5  261.57  4787.7  261.42  4837.7  258.75  4900.2  258.27  4977.9   259.1
    4998  255.33  5009.2  255.18    5012  254.68  5015.2  255.18    5028  259.24
    5048  260.47  5068.1   260.5  5128.2   265.3  5218.3  276.41  5288.4  282.27
  5414.4  289.32  5477.2  291.52  5548.7  290.31  5598.8  292.11  5655.6  291.75
#Mann= 10 ,-1 , 0
  3429.5      .1       0  3517.2     .15       0  3601.9      .1       0
  3691.3     .08       0  3863.4     .05       0  4900.2     .08       0
  5009.2     .07       0  5015.2     .08       0  5414.4      .1       0
  5477.2     .08       0
Bank Sta=4977.9,5048
XS Rating Curve= 0 ,0
Exp/Cntr=0.3,0.1

Type RM Length L Ch R = 1 ,26077   ,204,204,204
BEGIN DESCRIPTION:
NORTHWEST FORK BOONS CR 39.0
END DESCRIPTION:
XS GIS Cut Line= 5
      3692861.31     10567738.12      3693479.39     10566793.64
      3693757.17     10566376.98       3693840.5     10565988.09
      3693673.84     10565613.09
#Sta/Elev= 30
  3180.1  272.99  3247.5   271.7  3350.9  272.84  3392.9  270.54  3640.2  269.12
  3727.4  267.09  3971.9  267.68  4049.4  265.99  4059.4   265.8  4295.8  263.78
  4436.6  261.52    4565  259.04  4745.3  259.37  4807.3  257.47    4970  256.94
  4991.9  256.47  4997.6  254.98  5000.4  254.48  5003.6  254.98  5031.1  258.56
  5085.7  260.53    5130  264.99  5135.1  264.24    5216  269.31  5227.1   271.5
  5314.5  280.16  5348.9  285.97    5413  291.52  5529.8   294.6  5617.7  294.01
#Mann= 10 ,-1 , 0
  3180.1     .08       0  3247.5      .1       0  3350.9     .08       0
  4049.4     .05       0  4059.4     .08       0  4295.8     .05       0
  4436.6     .08       0  4997.6     .07       0  5003.6     .08       0
  5529.8      .1       0
Bank Sta=4970,5031.1
XS Rating Curve= 0 ,0
Exp/Cntr=0.3,0.1

Type RM Length L Ch R = 1 ,25873   ,284,284,284
BEGIN DESCRIPTION:
NORTHWEST FORK BOONS CR 38.0
END DESCRIPTION:
XS GIS Cut Line= 4
      3693139.09     10567738.12      3693916.89      10566536.7
      3694021.06     10566015.87      3693777.99       10565620.
#Sta/Elev= 30
  3172.1  271.86  3568.7     268  3677.5  270.37  3901.1  267.64  3964.6  268.44
  4048.8  267.88  4435.5  264.07  4519.6  263.58  4554.3  262.69  4671.1  260.98
  4724.7   262.4    4894   256.7  4899.1  258.06  4915.9  256.31  4977.1  257.76
  4987.3  256.15    4993  251.55  4995.7  251.05    4999  251.55  5011.6  253.47
  5038.3  258.14  5169.4  257.94  5204.9  261.43  5278.2  262.54  5284.2  266.49
  5336.3  270.96  5387.6  278.55  5400.2  282.29  5458.2  289.43    5599  292.63
#Mann= 12 ,-1 , 0
  3172.1     .08       0  3964.6     .05       0  4048.8     .08       0
  4435.5     .05       0  4519.6     .08       0  4554.3      .1       0
  4724.7     .08       0    4993     .07       0    4999     .08       0
  5011.6     .05       0  5169.4     .08       0  5278.2     .05       0
Bank Sta=4977.1,5038.3
XS Rating Curve= 0 ,0
Exp/Cntr=0.3,0.1

Type RM Length L Ch R = 1 ,25589   ,639,639,639
BEGIN DESCRIPTION:
NORTHWEST FORK BOONS CR 37.0
END DESCRIPTION:
XS GIS Cut Line= 3
      3694031.66     10566805.36      3694344.18     10566154.28
      3693817.54     10565537.27
#Sta/Elev= 30
  3983.6  267.52  4254.7  265.39  4295.9  264.73  4541.7  262.13    4648  263.06
  4688.7  262.67  4719.1  259.66  4733.4  260.41  4790.1  256.12    4927  255.62
  4974.1  259.08  4981.5  258.33  4985.1   251.9  4987.9   251.4  4991.1   251.9
  5016.7  256.68  5039.6  256.48  5072.7  256.18  5108.9  255.85  5151.7  259.25
  5158.3  261.26  5218.4  263.93  5258.2  265.38  5279.1  274.33  5293.3   277.1
  5315.3  278.52  5342.7  282.75    5382  285.02  5414.1  287.42    5517   288.1
#Mann= 11 ,-1 , 0
  3983.6     .05       0  4254.7     .08       0  4295.9     .05       0
    4648     .08       0    4927     .05       0  4985.1     .04       0
  4991.1     .05       0  5039.6     .12       0  5072.7     .05       0
  5218.4     .08       0    5382     .05       0
Bank Sta=4974.1,5016.7
XS Rating Curve= 0 ,0
Exp/Cntr=0.3,0.1

Type RM Length L Ch R = 1 ,24950   ,1147,1147,1147
BEGIN DESCRIPTION:
NORTHWEST FORK BOONS CR 36.0
END DESCRIPTION:
XS GIS Cut Line= 4
      3694227.01      10566519.7      3694539.49     10565952.02
       3694569.7     10565566.33      3693918.65     10564826.74
#Sta/Elev= 30
  3817.2  265.15  4276.4  262.17  4341.7  263.13  4458.3  261.07  4537.3  257.55
  4637.6  259.13  4983.8  255.99  4991.4  254.47  4995.1  251.35  4997.8  250.85
  5001.1  251.35  5012.3  251.66  5033.5  257.76  5104.3  253.63    5140  261.68
    5147  259.84  5179.4  259.84  5220.3  259.84  5232.4  259.84    5239  262.27
  5314.7   260.3    5450   260.3    5507   260.3  5553.7  261.82  5565.4  262.09
  5572.1  260.08  5579.6  261.64  5614.7  260.66  5741.9  273.46  5837.4  273.41
#Mann= 11 ,-1 , 0
  3817.2     .05       0  4276.4     .08       0  4458.3     .16       0
  4995.1     .04       0  5001.1     .16       0  5179.4      .1       0
  5220.3     .05       0  5314.7      .1       0    5450     .08       0
    5507     .05       0  5553.7     .08       0
Bank Sta=4983.8,5033.5
XS Rating Curve= 0 ,0
Exp/Cntr=0.3,0.1

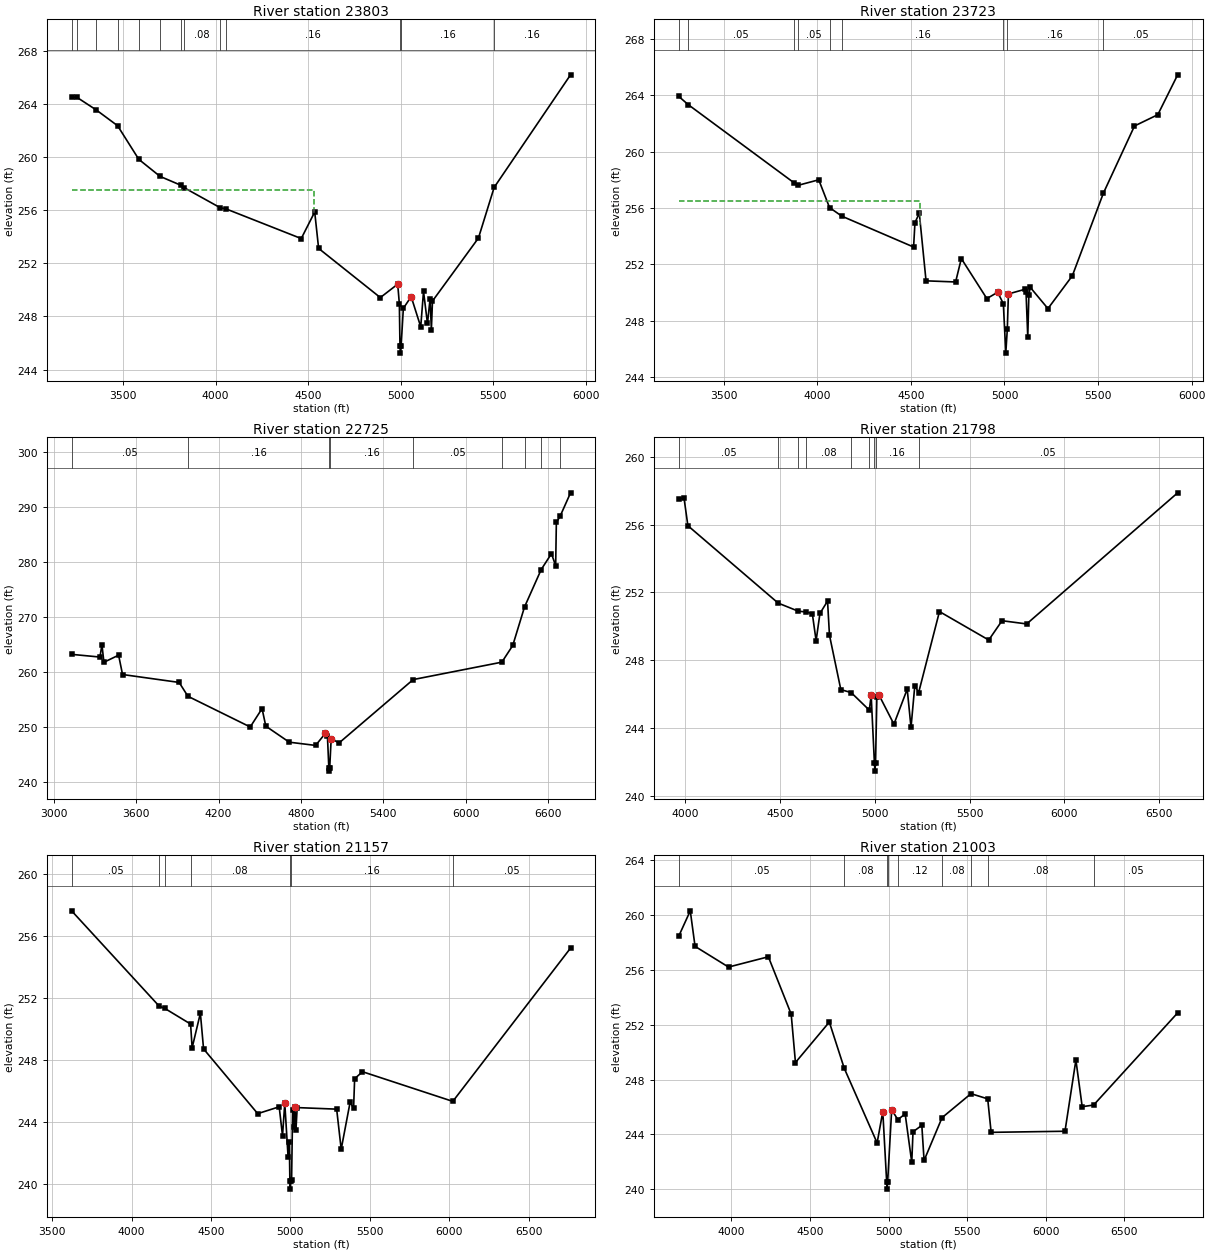
Type RM Length L Ch R = 1 ,23803   ,80,80,80
BEGIN DESCRIPTION:
Mapping XS eca36978
END DESCRIPTION:
XS GIS Cut Line= 2
      3696411.32     10565512.21      3694140.43     10564060.79
#Sta/Elev= 30
  3221.8  264.48    3249   264.5  3355.7  263.53  3470.2  262.35  3584.8  259.82
  3699.3  258.54  3813.8  257.86  3830.7  257.68  4024.6  256.18  4056.2  256.09
  4462.2  253.86  4534.9  255.86  4556.1  253.12  4889.4  249.42  4983.3  250.43
  4992.2  248.94  4995.5  245.74  4998.2  245.24  5001.5  245.74  5013.7  248.61
    5056  249.49  5107.6  247.22  5122.7  249.88    5144  247.47  5158.3  249.34
  5165.1  246.99  5171.1  249.16  5419.4   253.9  5504.3  257.71  5916.9  266.18
#Mann= 13 ,-1 , 0
  3221.8     .05       0    3249     .08       0  3355.7     .05       0
  3470.2     .08       0  3584.8     .05       0  3699.3     .08       0
  3813.8     .05       0  3830.7     .08       0  4024.6     .05       0
  4056.2     .16       0  4995.5     .07       0  5001.5     .16       0
  5504.3     .16       0
#XS Ineff= 2 , 0
         4532.39  257.48
Permanent Ineff=
       F       F
Bank Sta=4983.3,5056
XS Rating Curve= 0 ,0
Exp/Cntr=0.3,0.1

Type RM Length L Ch R = 1 ,23723   ,998,998,998
BEGIN DESCRIPTION:
NORTHWEST FORK BOONS CR 35.0
END DESCRIPTION:
XS GIS Cut Line= 2
      3696435.39     10565426.54      3694184.44     10563998.72
#Sta/Elev= 30
  3259.8  263.93    3310  263.35  3874.6  257.81  3895.1  257.61  4007.9  258.01
  4065.5  256.04  4131.1  255.43  4514.6  253.24  4521.9  254.97  4545.1  255.64
  4581.1  250.84  4739.1  250.76  4769.6  252.42    4906  249.58  4963.6  250.03
  4994.1  249.22  5007.2  245.71  5015.3  247.42  5021.2  249.91  5109.3  250.24
  5115.2  250.06  5124.6  246.85  5130.5  249.85  5137.7  250.38  5232.4  248.87
  5362.7   251.2  5528.5  257.06  5694.8  261.83  5819.3  262.63  5925.4  265.46
#Mann= 9 ,-1 , 0
  3259.8     .08       0    3310     .05       0  3874.6     .08       0
  3895.1     .05       0  4065.5     .07       0  4131.1     .16       0
  4994.1     .07       0  5015.3     .16       0  5528.5     .05       0
#XS Ineff= 2 , 0
         4551.14   256.5
Permanent Ineff=
       F       F
Bank Sta=4963.6,5021.2
XS Rating Curve= 0 ,0
Exp/Cntr=0.3,0.1

Type RM Length L Ch R = 1 ,22725   ,927,927,927
BEGIN DESCRIPTION:
NORTHWEST FORK BOONS CR 34.0
END DESCRIPTION:
XS GIS Cut Line= 3
      3696590.94      10565260.3      3695212.93     10563556.78
      3693793.05     10563285.81
#Sta/Elev= 30
  3128.7  263.21  3335.3  262.72  3349.7  264.98  3364.1  261.77  3471.2  263.06
  3499.9  259.54  3912.4   258.1  3976.4  255.58  4430.5  249.99  4516.8  253.33
  4544.1  250.14  4715.1  247.22    4907  246.63  4978.9  248.85  4993.3  248.35
  5003.7  242.45  5006.5  241.95  5009.7  242.45  5020.5  247.86    5078  247.08
  5618.4  258.62  6264.6  261.79  6344.1  264.83  6429.7  271.83  6551.5  278.66
  6626.3  281.55  6656.8  279.33  6661.9  287.23  6688.4  288.31  6765.3  292.62
#Mann= 9 ,-1 , 0
  3128.7     .05       0  3976.4     .16       0  5003.7     .07       0
  5009.7     .16       0  5618.4     .05       0  6264.6     .16       0
  6429.7     .05       0  6551.5     .08       0  6688.4     .05       0
Bank Sta=4978.9,5020.5
XS Rating Curve= 0 ,0
Exp/Cntr=0.3,0.1

Type RM Length L Ch R = 1 ,21798   ,641,641,641
BEGIN DESCRIPTION:
Mapping XS 01255c5a
END DESCRIPTION:
XS GIS Cut Line= 3
      3696169.56     10564547.99      3696065.39     10563787.56
      3696093.15      10561924.1
#Sta/Elev= 30
  3966.1  257.52  3994.2  257.55  4014.4  255.93  4490.5  251.36  4597.1  250.88
  4636.6  250.84  4670.6  250.74  4690.6  249.14  4710.8  250.75    4751  251.48
    4761  249.47    4821  246.25  4875.3  246.08  4971.2  245.04    4981  245.91
    4998  241.94  5000.8  241.44    5004  241.94    5011  245.79    5021  245.96
    5101  244.21  5171.1  246.28  5191.1  244.02  5211.1  246.49  5231.4  246.08
  5341.1  250.86  5601.1  249.18  5671.1  250.32  5801.1  250.13  6597.3  257.87
#Mann= 9 ,-1 , 0
  3966.1     .05       0  4490.5     .08       0  4597.1     .05       0
  4636.6     .08       0  4875.3     .16       0  4971.2     .16       0
    4998     .07       0    5004     .16       0  5231.4     .05       0
Bank Sta=4981,5021
XS Rating Curve= 0 ,0
Exp/Cntr=0.3,0.1

Type RM Length L Ch R = 1 ,21157   ,154,154,154
BEGIN DESCRIPTION:
Mapping XS 97c5f5a5
END DESCRIPTION:
XS GIS Cut Line= 4
      3696200.81     10564528.04      3696127.02     10563681.66
      3697303.24     10562700.75      3697334.49     10561940.34
#Sta/Elev= 30
  3622.4   257.6  4174.1  251.46  4208.7  251.32  4371.7  250.31  4381.4  248.78
  4433.3  251.01  4453.4  248.71  4794.4  244.54  4929.7  244.98  4950.6  243.12
  4964.9  245.21  4985.7  241.76  4993.5  242.74    4997  240.18  4999.8  239.68
    5003  240.18  5007.8  240.28  5014.3  244.79  5022.2   243.7  5028.7  244.94
  5035.3  243.51    5043  244.93  5291.6  244.83  5320.2  242.25  5376.2  245.27
  5398.3   244.9  5404.8  246.79  5454.3  247.24  6023.1  245.33  6764.6   255.2
#Mann= 7 ,-1 , 0
  3622.4     .05       0  4174.1     .08       0  4208.7     .05       0
  4371.7     .08       0    4997     .07       0    5003     .16       0
  6023.1     .05       0
Bank Sta=4964.9,5028.7
XS Rating Curve= 0 ,0
Exp/Cntr=0.3,0.1

Type RM Length L Ch R = 1 ,21003   ,1303,1303,1303
BEGIN DESCRIPTION:
Mapping XS a3338782
END DESCRIPTION:
XS GIS Cut Line= 5
      3696579.27     10564602.62      3696428.24     10563675.58
      3696548.03     10563482.87      3697553.24     10562659.96
      3697542.84     10561953.39
#Sta/Elev= 30
  3666.2  258.45  3739.6   260.3    3770  257.71  3982.7   256.2    4236  256.95
  4381.1  252.77  4408.3  249.24  4623.6  252.19  4718.5  248.82  4927.4  243.38
  4963.6  245.66  4988.3  240.51    4991  240.01  4994.3  240.51    5020   245.8
  5058.9  245.08  5105.8  245.49  5147.7  241.96  5155.6  244.19  5211.6  244.66
    5226   242.1  5340.3  245.22  5524.4  246.97  5630.5  246.59  5652.3  244.15
  6121.8  244.23  6191.2  249.42  6231.2  246.02  6303.8  246.14  6838.1  252.86
#Mann= 9 ,-1 , 0
  3666.2     .05       0  4718.5     .08       0  4988.3     .07       0
  4994.3     .08       0  5058.9     .12       0  5340.3     .08       0
  5524.4     .05       0  5630.5     .08       0  6303.8     .05       0
Bank Sta=4963.6,5020
XS Rating Curve= 0 ,0
Exp/Cntr=0.3,0.1

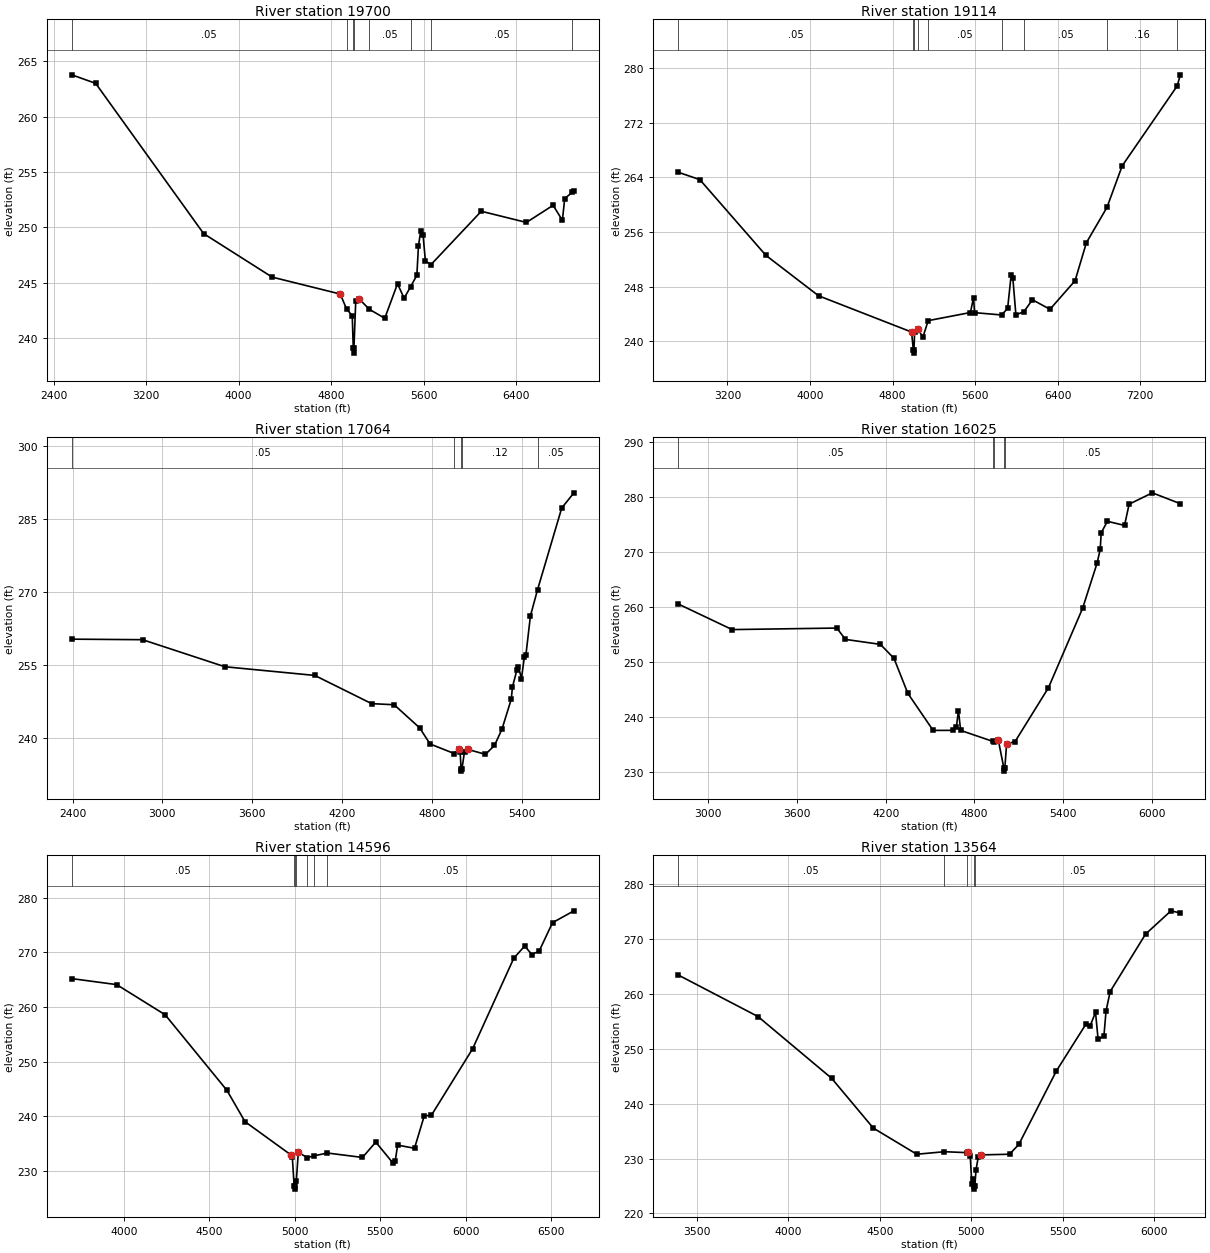
Type RM Length L Ch R = 1 ,19700   ,586,586,586
BEGIN DESCRIPTION:
NORTHWEST FORK BOONS CR 32.0
END DESCRIPTION:
XS GIS Cut Line= 2
      3698005.11     10565465.87      3697611.72     10561141.03
#Sta/Elev= 30
  2557.1  263.79  2763.6  263.02  3697.5  249.44  4289.9  245.51  4879.1  243.98
  4933.2  242.64  4982.8  242.02  4991.5  239.14  4994.3  238.64  4997.5  239.14
  5012.9  243.32    5043  243.53  5130.9   242.6  5263.9  241.79  5374.4  244.91
  5431.2   243.6  5488.1  244.65  5541.6  245.68  5555.1  248.28  5575.2  249.72
  5595.3   249.3  5615.4  246.97  5663.8  246.64  6098.8  251.46    6489  250.45
  6719.9     252  6800.2  250.64  6820.3  252.61  6884.5  253.16  6899.8  253.31
#Mann= 8 ,-1 , 0
  2557.1     .05       0  4933.2     .12       0  4991.5     .07       0
  4997.5     .12       0  5130.9     .05       0  5488.1     .08       0
  5663.8     .05       0  6884.5     .12       0
Bank Sta=4879.1,5043
XS Rating Curve= 0 ,0
Exp/Cntr=0.3,0.1

Type RM Length L Ch R = 1 ,19114   ,2050,2050,2050
BEGIN DESCRIPTION:
NORTHWEST FORK BOONS CR 29.0
END DESCRIPTION:
XS GIS Cut Line= 3
      3698413.88     10565249.45      3698251.12      10561484.3
      3698565.27     10560433.52
#Sta/Elev= 30
  2723.1  264.75  2932.6  263.67  3573.2  252.57  4083.6  246.65  4984.5  241.34
  5001.5  238.75  5004.2  238.25  5007.5  238.75  5014.5  241.31  5044.5  241.74
  5051.1  241.64  5094.6   240.6  5145.7  243.01    5555   244.2    5585  246.39
    5595  244.18  5856.5  243.84  5915.3   244.8  5949.2  249.66  5965.4  249.32
  5995.4  243.86    6073  244.32  6155.6  246.07  6325.7  244.67  6568.8  248.86
  6678.6  254.43  6878.2  259.61  7025.4  265.69  7558.2  277.39  7588.5  279.02
#Mann= 9 ,-1 , 0
  2723.1     .05       0  5001.5     .03       0  5007.5     .05       0
  5051.1     .07       0  5145.7     .05       0  5856.5     .08       0
    6073     .05       0  6878.2     .16       0  7558.2     .12       0
Bank Sta=4984.5,5044.5
XS Rating Curve= 0 ,0
Exp/Cntr=0.3,0.1

Type RM Length L Ch R = 1 ,17064   ,1039,1039,1039
BEGIN DESCRIPTION:
NORTHWEST FORK BOONS CR 28.0
END DESCRIPTION:
XS GIS Cut Line= 2
      3699640.01     10564652.72      3699542.36     10561299.84
#Sta/Elev= 30
  2394.8   260.3  2867.5  260.19  3417.8  254.63    4018  252.85  4398.2  247.05
  4548.2  246.83  4718.3  242.09  4788.3  238.77  4948.9  236.81  4978.4  237.64
  4989.1  237.07  4995.4  233.69  4998.2  233.19  5001.4  233.69  5018.4  237.21
  5038.4  237.67  5158.5  236.64  5218.5  238.46  5268.5   241.8  5330.9     248
  5338.6  250.48  5368.6     254  5378.6  254.68  5398.6  252.19  5418.6  256.73
  5428.6  257.08  5458.6  265.07    5506  270.44  5667.7  287.24  5749.1  290.36
#Mann= 5 ,-1 , 0
  2394.8     .05       0  4948.9     .12       0  4995.4     .07       0
  5001.4     .12       0    5506     .05       0
Bank Sta=4978.4,5038.4
XS Rating Curve= 0 ,0
Exp/Cntr=0.3,0.1

Type RM Length L Ch R = 1 ,16025   ,1429,1429,1429
BEGIN DESCRIPTION:
NORTHWEST FORK BOONS CR 22.0
END DESCRIPTION:
XS GIS Cut Line= 3
      3701679.94     10564150.67      3700499.39     10562553.45
      3700169.92     10561183.56
#Sta/Elev= 30
  2796.8  260.56  3161.6  255.89  3869.4  256.17  3927.9   254.1  4163.8   253.2
  4255.6  250.67  4349.6  244.27  4520.7  237.52  4656.4  237.53  4677.3  238.05
  4691.9  241.13  4706.5  237.52  4922.2  235.54  4929.7  235.38  4961.2  235.79
  4999.3   230.6    5002   230.1  5005.3   230.6  5017.5  235.07  5074.3  235.47
  5300.6  245.31  5531.2  259.76  5629.7  268.04  5650.3  270.52    5657  273.53
    5699  275.62  5814.8  274.87  5845.7  278.74  6002.9  280.81  6191.9  278.83
#Mann= 5 ,-1 , 0
  2796.8     .05       0  4922.2     .16       0  4929.7     .05       0
  4999.3     .03       0  5005.3     .05       0
Bank Sta=4961.2,5017.5
XS Rating Curve= 0 ,0
Exp/Cntr=0.3,0.1

Type RM Length L Ch R = 1 ,14596   ,1032,1032,1032
BEGIN DESCRIPTION:
NORTHWEST FORK BOONS CR 21.0
END DESCRIPTION:
XS GIS Cut Line= 2
      3702600.06     10563490.92      3700639.08     10561304.35
#Sta/Elev= 30
    3696   265.2  3958.8   264.1  4242.2  258.58  4603.2  244.76  4709.4  239.01
  4978.5  232.91    4986  232.56  4996.9  227.16  4999.7  226.66  5002.9  227.16
  5009.2  228.08  5021.1   233.4  5073.4  232.42    5110  232.74  5191.5  233.27
  5396.4  232.46  5474.2  235.27  5573.6  231.48  5587.8  231.78    5602  234.72
  5700.7  234.14  5757.5  240.05  5800.1  240.21  6040.8  252.36  6281.5  268.94
  6345.1  271.16  6387.7   269.6  6430.3  270.27    6508  275.44  6633.1  277.61
#Mann= 7 ,-1 , 0
    3696     .05       0  4996.9     .03       0  5002.9     .05       0
  5009.2     .16       0  5073.4     .12       0    5110     .16       0
  5191.5     .05       0
Bank Sta=4978.5,5021.1
XS Rating Curve= 0 ,0
Exp/Cntr=0.3,0.1

Type RM Length L Ch R = 1 ,13564   ,1493,1493,1493
BEGIN DESCRIPTION:
NORTHWEST FORK BOONS CR 20.0
END DESCRIPTION:
XS GIS Cut Line= 2
      3703190.36     10562501.37      3700795.09     10561164.88
#Sta/Elev= 30
  3398.6  263.46  3834.6  255.88  4236.7  244.63  4464.4  235.55  4701.7  230.78
  4852.9  231.24  4977.5  231.07  4979.7   231.2  4994.2   230.4  5002.6  225.44
  5010.2  226.25    5013  224.92  5015.7  224.42    5019  224.92  5025.5  227.93
  5037.7  230.25  5053.7  230.66  5208.8  230.78  5259.3  232.57    5465  245.99
  5627.3  254.57    5649  254.17  5678.3  256.66  5692.4  251.74  5724.1  252.29
  5735.8  256.89  5758.4  260.44  5951.8  270.91  6090.5  275.15  6141.5  274.75
#Mann= 5 ,-1 , 0
  3398.6     .05       0  4852.9     .12       0  4977.5     .05       0
    5013     .03       0    5019     .05       0
Bank Sta=4979.7,5053.7
XS Rating Curve= 0 ,0
Exp/Cntr=0.3,0.1