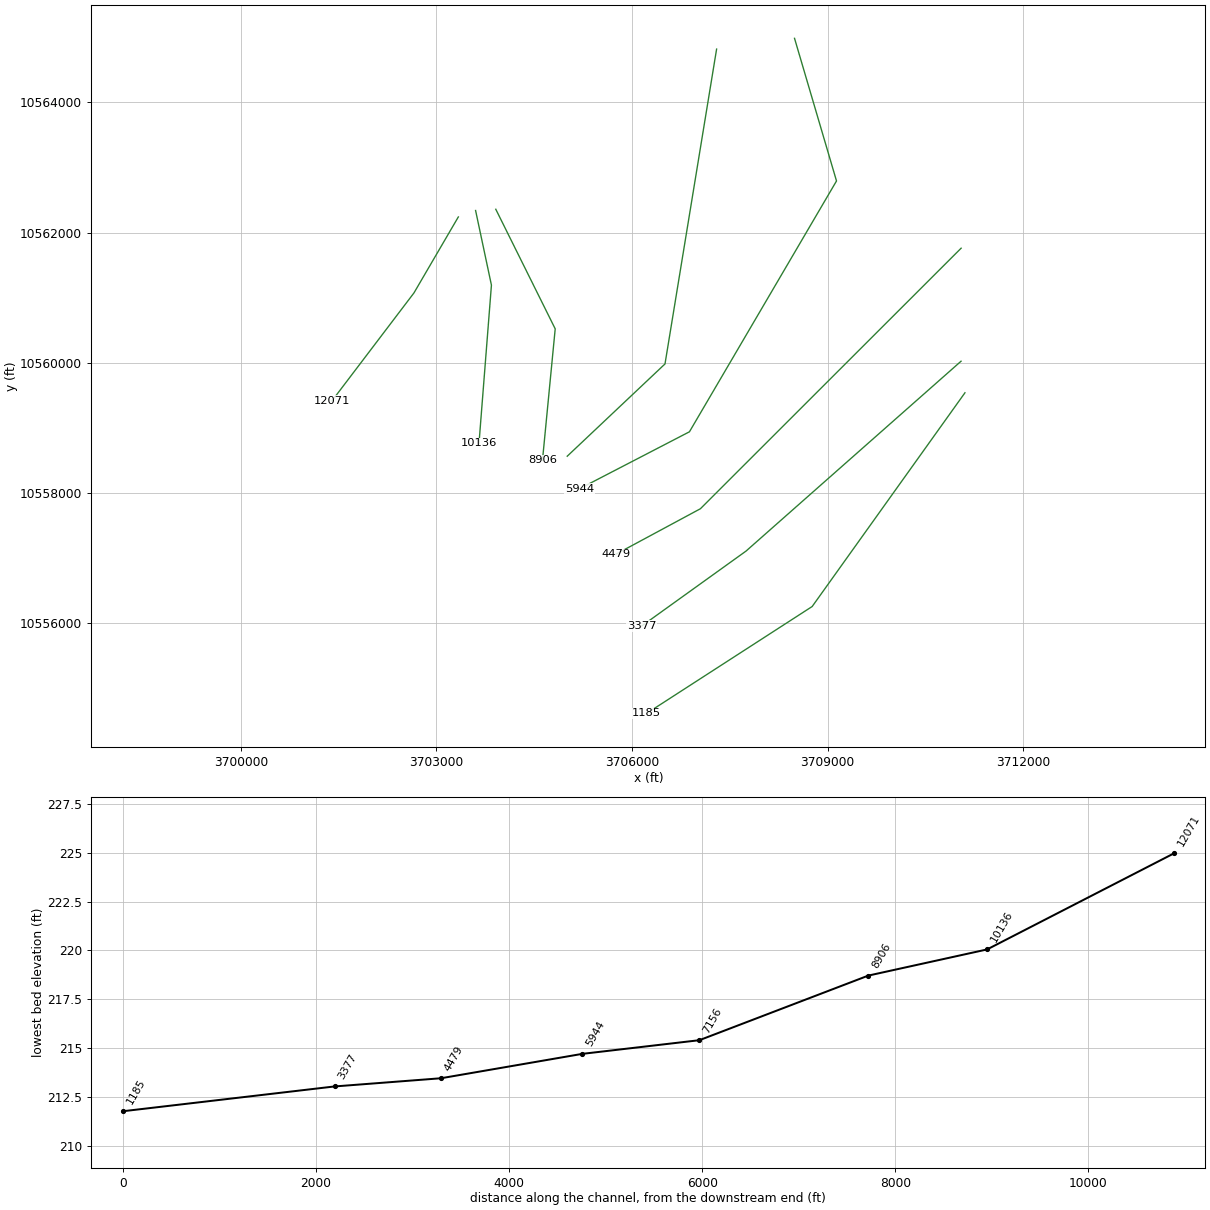
HEC-RAS study NORTHWEST FORK BOONS CR.prj: NORTHWEST FORK BOONS CR Base Level Engineering

--- NORTHWEST FORK BOONS CR.g01 (geometry) --- (continued)

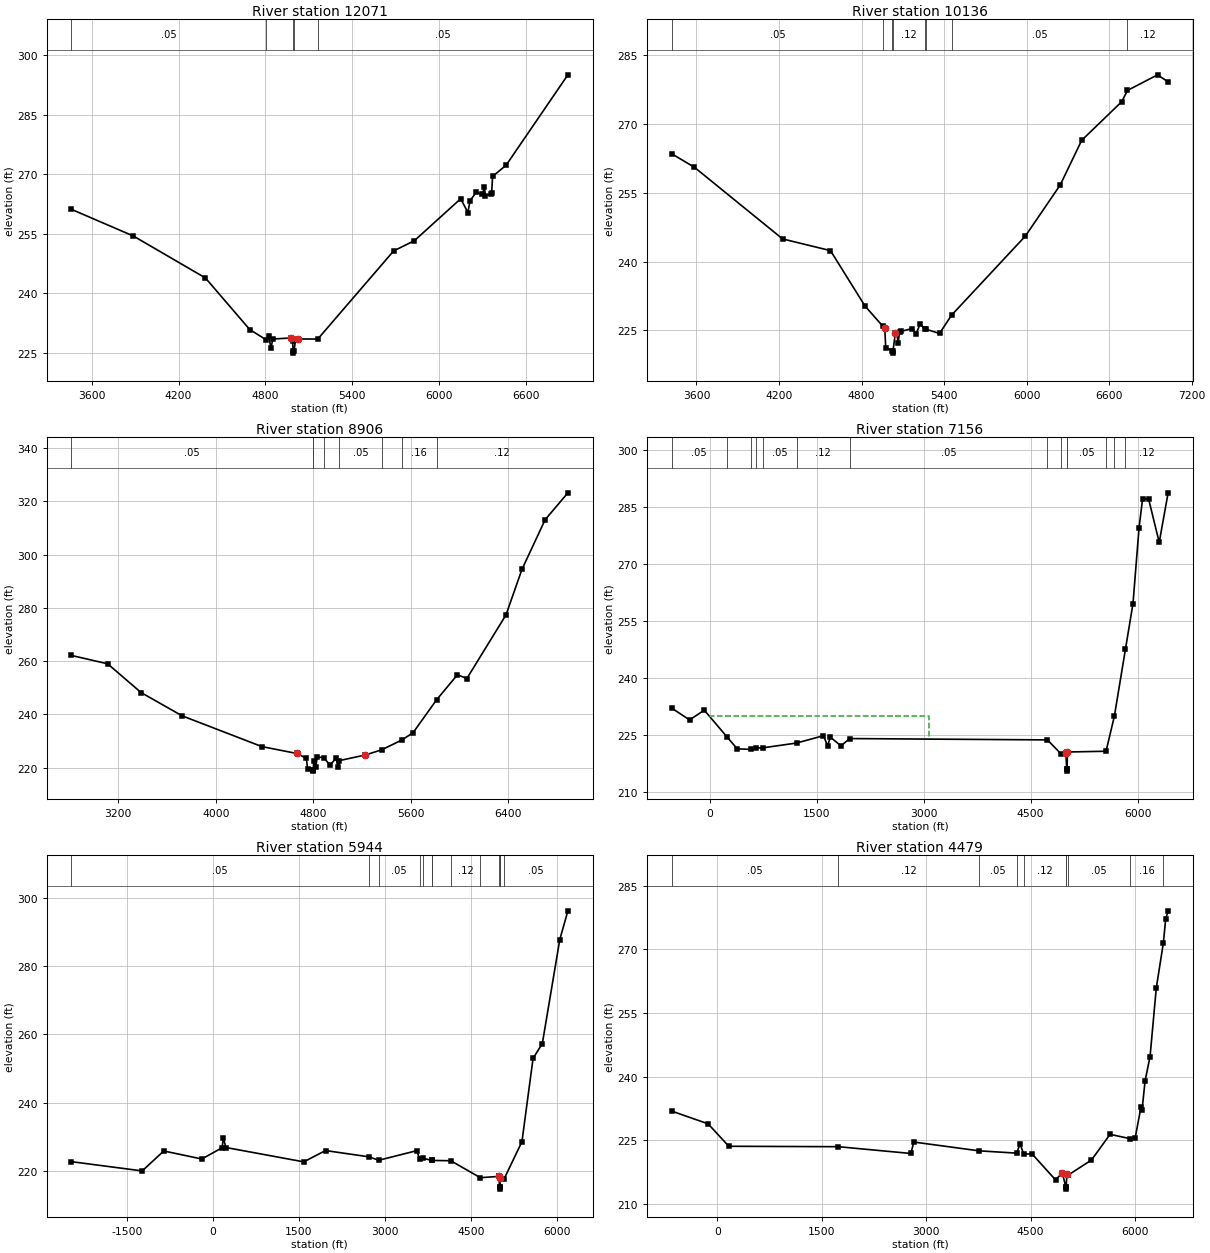
Type RM Length L Ch R = 1 ,12071   ,1935,1935,1935
BEGIN DESCRIPTION:
NORTHWEST FORK BOONS CR 16.0
END DESCRIPTION:
XS GIS Cut Line= 3
       3703336.2      10562240.1      3702654.77     10561072.55
      3701396.32     10559414.87
#Sta/Elev= 30
  3459.3   261.2  3887.6  254.48  4385.5  243.92  4692.4   230.9  4803.4  228.39
  4824.2  229.18  4838.7  226.19  4851.8  228.53  4980.2  228.79  4988.5  228.12
  4991.8  225.47  4994.5  224.97  4997.8  225.47  5009.3  228.34  5023.8  228.54
  5162.7  228.52  5687.3  250.73  5830.8  253.31  6151.1  263.88    6201  260.41
  6215.6  263.38    6258  265.48  6300.9  264.96  6315.4  266.89  6321.7  264.61
  6358.4  265.14  6365.3  265.43  6371.6  269.51  6465.2  272.33  6892.4  295.11
#Mann= 5 ,-1 , 0
  3459.3     .05       0  4803.4     .12       0  4991.8     .07       0
  4997.8     .12       0  5162.7     .05       0
Bank Sta=4980.2,5023.8
XS Rating Curve= 0 ,0
Exp/Cntr=0.3,0.1

Type RM Length L Ch R = 1 ,10136   ,1230,1230,1230
BEGIN DESCRIPTION:
NORTHWEST FORK BOONS CR 14.0
END DESCRIPTION:
XS GIS Cut Line= 3
      3703600.94     10562338.86        3703844.     10561192.99
      3703653.14     10558763.85
#Sta/Elev= 30
  3420.4  263.51  3585.2  260.57  4226.6  244.94  4574.2   242.4  4825.3  230.32
    4956  225.87  4968.9  225.55  4975.8  221.27  5022.9  220.55  5025.7  220.05
  5028.9  220.55    5046  224.44    5056  224.42    5066  222.32  5076.1  224.64
  5086.1  224.79  5166.3  225.39  5196.4  224.28    5227  226.44  5259.3  225.21
  5267.7  225.27    5367  224.34  5454.3  228.32  5991.1  245.58  6244.2  256.71
  6400.1  266.44    6691  274.86    6733  277.32  6951.8  280.72  7028.4  279.18
#Mann= 8 ,-1 , 0
  3420.4     .05       0    4956     .12       0  5022.9     .07       0
  5028.9     .12       0  5259.3     .16       0  5267.7     .12       0
  5454.3     .05       0    6733     .12       0
Bank Sta=4968.9,5046
XS Rating Curve= 0 ,0
Exp/Cntr=0.3,0.1

Type RM Length L Ch R = 1 ,8906    ,1750,1750,1750
BEGIN DESCRIPTION:
NORTHWEST FORK BOONS CR 12.0
END DESCRIPTION:
XS GIS Cut Line= 3
      3703910.84     10562357.93       3704822.3     10560521.99
      3704627.06     10558504.45
#Sta/Elev= 30
  2815.3  262.14  3112.4     259  3386.9  248.21    3723  239.49  4378.4  227.93
  4664.2  225.35  4744.2  223.55  4753.8  219.64  4795.6  219.21  4798.4  218.71
  4801.6  219.21  4804.2   222.4    4821  220.25  4833.6  223.96  4887.2  223.81
  4937.2  220.96  4987.4  223.46  5007.5   220.1  5015.3  222.66  5228.5  224.77
  5362.1   226.7  5528.8   230.4  5620.4  233.13  5813.5  245.47  5985.1  254.91
  6062.4  253.48  6383.9  277.39  6514.5  294.43  6705.1  313.11    6892   323.2
#Mann= 8 ,-1 , 0
  2815.3     .05       0  4795.6     .07       0  4801.6     .05       0
  4887.2     .12       0  5015.3     .05       0  5362.1     .12       0
  5528.8     .16       0  5813.5     .12       0
Bank Sta=4664.2,5228.5
XS Rating Curve= 0 ,0
Exp/Cntr=0.3,0.1

Type RM Length L Ch R = 1 ,7156    ,1212,1212,1212
BEGIN DESCRIPTION:
NORTHWEST FORK BOONS CR 9.0
END DESCRIPTION:
XS GIS Cut Line= 3
      3707298.43     10564816.68      3706506.77     10559983.36
      3705006.74     10558566.67
#Sta/Elev= 30
  -533.6     232  -283.8   228.9   -76.5  231.45     238   224.5     385  221.28
   576.4  221.13   642.1  221.48   745.2  221.54  1216.4   222.8  1594.7  224.74
    1651  222.09  1692.2  224.34    1840  222.06  1961.7  223.98  4734.4  223.63
  4929.1  219.89  4993.8  220.16  5004.9   215.9  5007.7   215.4  5010.9   215.9
  5015.2  220.44  5557.2  220.64  5673.9   229.9  5828.7   247.5  5934.8  259.54
  6019.7  279.51  6069.1   287.1    6154  287.12  6302.5  275.67  6427.4  288.73
#Mann= 14 ,-1 , 0
  -533.6     .05       0     238     .12       0   576.4     .05       0
   642.1     .12       0   745.2     .05       0  1216.4     .12       0
  1961.7     .05       0  4734.4     .12       0  4929.1     .05       0
  5004.9     .03       0  5010.9     .05       0  5557.2     .12       0
  5673.9     .16       0  5828.7     .12       0
#XS Ineff= 2 , 0
       0  3076.8     230               0
Permanent Ineff=
       F       F
Bank Sta=4993.8,5015.2
XS Rating Curve= 0 ,0
Exp/Cntr=0.3,0.1

Type RM Length L Ch R = 1 ,5944    ,1465,1465,1465
BEGIN DESCRIPTION:
NORTHWEST FORK BOONS CR 8.0
END DESCRIPTION:
XS GIS Cut Line= 4
      3708493.84     10564981.93      3709137.92     10562792.27
      3706881.77     10558941.69       3705194.4     10558066.76
#Sta/Elev= 30
   -2462  222.73 -1230.2  220.03  -854.9  225.86  -192.2  223.52     164  226.83
   179.7  229.74   228.5  226.88  1583.1  222.68  1962.3  225.99  2719.1  224.15
  2890.3  223.15  3554.9  225.97  3599.6  223.47  3653.5  223.75  3820.4  223.09
  3820.8  223.09    4144  223.01  4658.3  218.05    4980  218.42  4984.1  218.42
  4993.8   215.2  4996.5   214.7  4999.8   215.2  5006.6  218.06  5076.5  217.81
  5383.8  228.59  5577.3  252.96  5738.8   257.3    6043  287.74    6184  296.14
#Mann= 13 ,-1 , 0
   -2462     .05       0  2719.1     .08       0  2890.3     .05       0
  3599.6     .12       0  3653.5     .05       0  3820.4     .12       0
  3820.8     .05       0    4144     .12       0  4658.3     .05       0
    4980     .16       0  4993.8     .07       0  4999.8     .16       0
  5076.5     .05       0
Bank Sta=4984.1,5006.6
XS Rating Curve= 0 ,0
Exp/Cntr=0.3,0.1

Type RM Length L Ch R = 1 ,4479    ,1102,1102,1102
BEGIN DESCRIPTION:
NORTHWEST FORK BOONS CR 6.0
END DESCRIPTION:
XS GIS Cut Line= 3
       3711049.6     10561760.18      3707049.61     10557760.19
      3705749.64      10557060.2
#Sta/Elev= 30
  -657.3  231.86    -134  228.85   162.9  223.56  1737.8  223.46  2779.2  221.86
  2821.7  224.56    3756  222.49  4299.4  221.94    4349  224.14  4400.7  221.68
  4518.7   221.8  4858.1  215.63  4957.1  217.31  5004.7  213.95  5007.4  213.45
  5010.7  213.95  5022.3     217  5041.8  216.78  5374.3  220.31  5642.1  226.38
  5922.2  225.38  6003.1  225.57    6085  232.74  6101.2   232.1    6145     239
  6216.4  244.71  6305.7  260.87  6407.5  271.52  6440.3  277.07    6476  279.11
#Mann= 10 ,-1 , 0
  -657.3     .05       0  1737.8     .12       0    3756     .05       0
  4299.4     .16       0  4400.7     .12       0  5004.7     .07       0
  5010.7     .12       0  5041.8     .05       0  5922.2     .16       0
  6407.5     .05       0
Bank Sta=4957.1,5022.3
XS Rating Curve= 0 ,0
Exp/Cntr=0.3,0.1

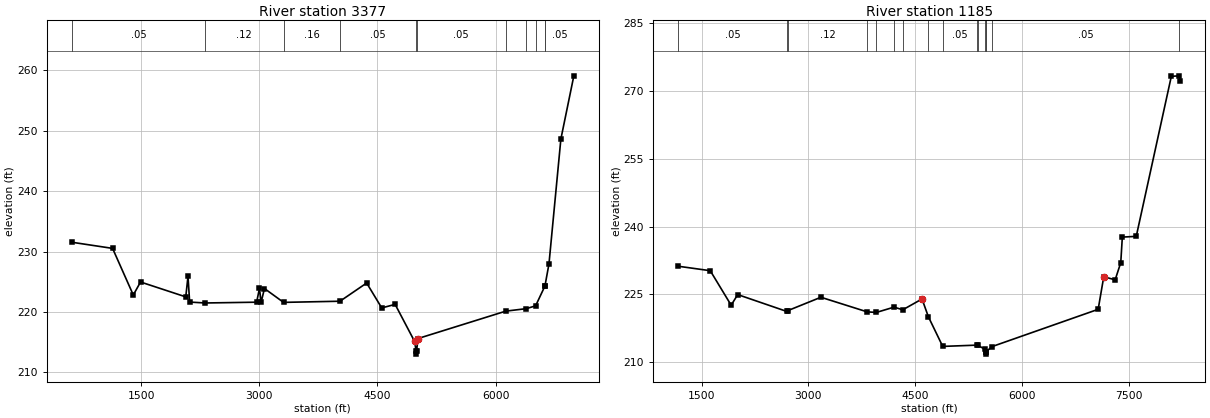
Type RM Length L Ch R = 1 ,3377    ,2192,2192,2192
BEGIN DESCRIPTION:
NORTHWEST FORK BOONS CR 4.0
END DESCRIPTION:
XS GIS Cut Line= 3
      3711048.45     10560025.04      3707749.61     10557110.19
      3706149.63     10555960.21
#Sta/Elev= 30
   619.6  231.54    1139  230.52  1401.7  222.81  1493.7  224.96  2067.6   222.5
    2096   225.9  2116.9  221.64  2313.9  221.49  2966.8  221.62  3002.8  223.89
  3023.7  221.61  3066.4  223.88  3308.4  221.59  4024.6  221.78    4363  224.79
  4554.5  220.67  4724.3  221.26  4971.9  215.12  4990.7  213.53  4993.5  213.03
  4996.7  213.53  5014.6  215.61  6128.4  220.14  6388.6  220.55  6507.1  221.02
  6622.6  224.22  6625.6  224.31  6676.6  227.96  6827.6  248.61  6992.1  259.06
#Mann= 11 ,-1 , 0
   619.6     .05       0  2313.9     .12       0  3308.4     .16       0
  4024.6     .05       0  4990.7     .03       0  4996.7     .05       0
  6128.4     .07       0  6388.6     .16       0  6507.1      .1       0
  6622.6     .16       0  6625.6     .05       0
Bank Sta=4971.9,5014.6
XS Rating Curve= 0 ,0
Exp/Cntr=0.3,0.1

Type RM Length L Ch R = 1 ,1185    ,829,829,829
BEGIN DESCRIPTION:
NORTHWEST FORK BOONS CR 1.0
END DESCRIPTION:
XS GIS Cut Line= 3
      3711108.32     10559540.64      3708764.58      10556259.4
      3706225.53     10554618.79
#Sta/Elev= 30
  1171.1  231.22  1622.5  230.23  1916.2  222.59  2008.4  224.94  2696.4  221.22
  2713.9   221.4  3177.1  224.35  3826.2  221.12  3956.1  220.99  4204.1  222.16
    4328  221.58  4597.7  223.97  4686.8  220.04  4888.5  213.47  5366.9  213.75
  5383.9  213.68  5486.8   212.8  5492.1  212.26  5494.8  211.76  5498.1  212.26
  5576.2   213.4  7072.4  221.68  7150.9  228.89  7311.2  228.21  7389.8  232.01
  7411.9  237.67  7607.5  237.83  8100.3  273.26  8210.3  273.37  8226.4  272.25
#Mann= 16 ,-1 , 0
  1171.1     .05       0  2696.4     .16       0  2713.9     .12       0
  3826.2     .16       0  3956.1     .12       0  4204.1     .16       0
    4328     .05       0  4686.8     .16       0  4888.5     .05       0
  5366.9     .12       0  5383.9     .07       0  5486.8     .12       0
  5492.1     .03       0  5498.1     .12       0  5576.2     .05       0
  8210.3     .08       0
Bank Sta=4597.7,7150.9
XS Rating Curve= 0 ,0
Exp/Cntr=0.3,0.1

Chan Stop Cuts=-1
Use User Specified Reach Order=0
Composite Channel Slope=5