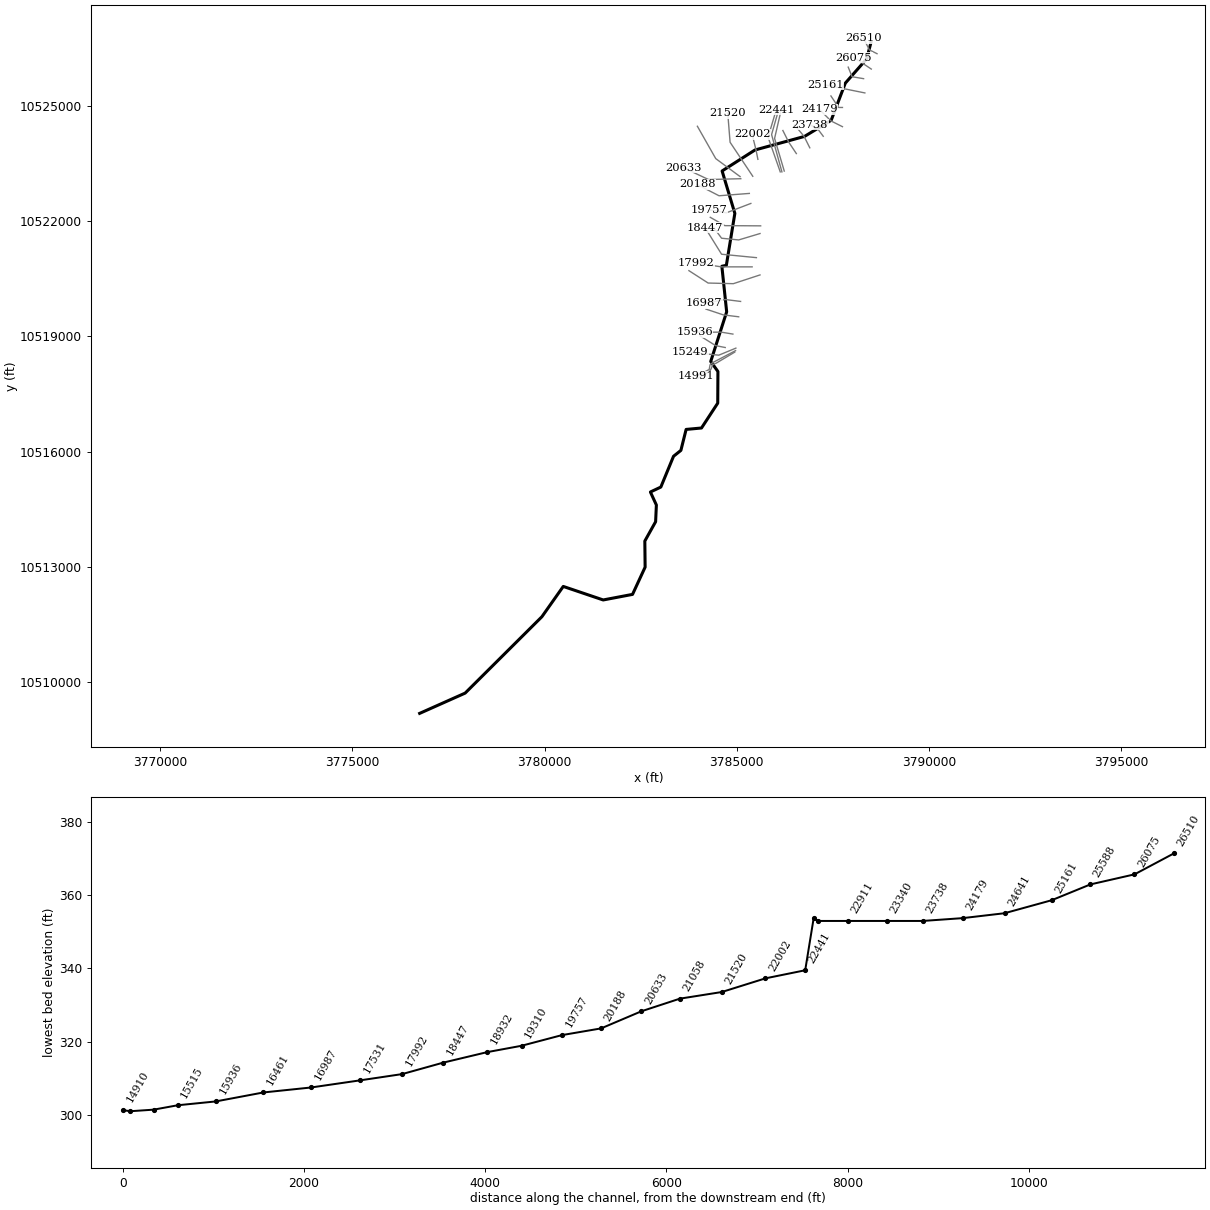
--- PENNINGTON BRANCH.prj (project) ---

Proj Title=PENNINGTON BRANCH Base Level Engineering
Current Plan=p01
Default Exp/Contr=0.3,0.1
English Units
Geom File=g01
Flow File=f01
Plan File=p01
Y Axis Title=Elevation
X Axis Title(PF)=Main Channel Distance
X Axis Title(XS)=Station
BEGIN DESCRIPTION:
PENNINGTON BRANCH
END DESCRIPTION:
DSS Export Rating Curves= 0
DSS Export Rating Curve Sorted= 0
DSS Export Volume Flow Curves= 0
DXF OffsetX= 0
DXF OffsetY= 0
DXF ScaleX= 1
DXF ScaleY= 10

--- PENNINGTON BRANCH.p01 (plan) ---

Plan Title=Multiple Run
Short Identifier=Multiple
Geom File=g01
Flow File=f01
Subcritical Flow
K Sum by GR= 0
Std Step Tol= 0.01
Critical Tol= 0.01
Num of Std Step Trials= 20
Max Error Tol= 0.3
Flow Tol Ratio= 0.001
Split Flow NTrial= 30
Split Flow Tol= 0.02
Split Flow Ratio= 0.02
Log Output Level= 0
Friction Slope Method= 1
Unsteady Friction Slope Method= 2
Unsteady Bridges Friction Slope Method= 1
Parabolic Critical Depth
Global Vel Dist=  1 , 1 , 1
Global Log Level= 0
CheckData=True
Encroach Param= -1, 0, 0, 0
BEGIN DESCRIPTION:
Multiple Run
END DESCRIPTION:

--- PENNINGTON BRANCH.f01 (steady flow) ---

Flow Title=Multiple
Program Version=4.10
Number of Profiles= 7
Profile Names=10-year,25-year,50-year,1pct_min,100-year,1pct_plu,500-year
River Rch & RM=PENNINGTON BRANC,Reach-1         ,26510
     585     789     958     856    1158    1566    1694
River Rch & RM=PENNINGTON BRANC,Reach-1         ,22002
     920    1271    1567    1418    1917    2593    2881
River Rch & RM=PENNINGTON BRANC,Reach-1         ,16987
    1065    1480    1831    1663    2249    3041    3403
River Rch & RM=PENNINGTON BRANC,Reach-1         ,14256
    1234    1720    2133    1939    2622    3545    3976
Boundary for River Rch & Prof#=PENNINGTON BRANC,Reach-1         , 1
Up Type= 0
Dn Type= 3
Dn Slope=0.0044
Boundary for River Rch & Prof#=PENNINGTON BRANC,Reach-1         , 2
Up Type= 0
Dn Type= 3
Dn Slope=0.0044
Boundary for River Rch & Prof#=PENNINGTON BRANC,Reach-1         , 3
Up Type= 0
Dn Type= 3
Dn Slope=0.0044
Boundary for River Rch & Prof#=PENNINGTON BRANC,Reach-1         , 4
Up Type= 0
Dn Type= 3
Dn Slope=0.0044
Boundary for River Rch & Prof#=PENNINGTON BRANC,Reach-1         , 5
Up Type= 0
Dn Type= 3
Dn Slope=0.0044
Boundary for River Rch & Prof#=PENNINGTON BRANC,Reach-1         , 6
Up Type= 0
Dn Type= 3
Dn Slope=0.0044
Boundary for River Rch & Prof#=PENNINGTON BRANC,Reach-1         , 7
Up Type= 0
Dn Type= 3
Dn Slope=0.0044
DSS Import GetInterval= 0
DSS Import GetPeak= 0
DSS Import FillOption= 0

--- PENNINGTON BRANCH.g01 (geometry) ---

Geom Title=Existing Conditions
Program Version=4.10

River Reach=PENNINGTON BRANC,Reach-1
Reach XY= 30
      3788492.49     10526655.96      3788379.25       10526225.
       3787823.5       10525593.       3787456.5       10524627.
       3786763.5       10524207.      3785473.25       10523853.
       3784618.5       10523307.        3784950.       10522203.
      3784728.75       10520850.        3784612.       10520826.
        3784737.       10519639.      3784322.25       10518347.
      3784509.75       10518086.      3784504.75       10517262.
      3784082.25       10516615.      3783682.25       10516578.
        3783546.       10516032.      3783354.75       10515879.
      3783024.25       10515077.      3782752.75       10514949.
      3782908.25       10514610.       3782888.5       10514175.
      3782607.75       10513672.       3782615.5       10512992.
        3782288.       10512283.      3781524.75       10512138.
      3780485.75       10512490.       3779929.5       10511701.
      3777933.25       10509713.       3776749.5       10509185.

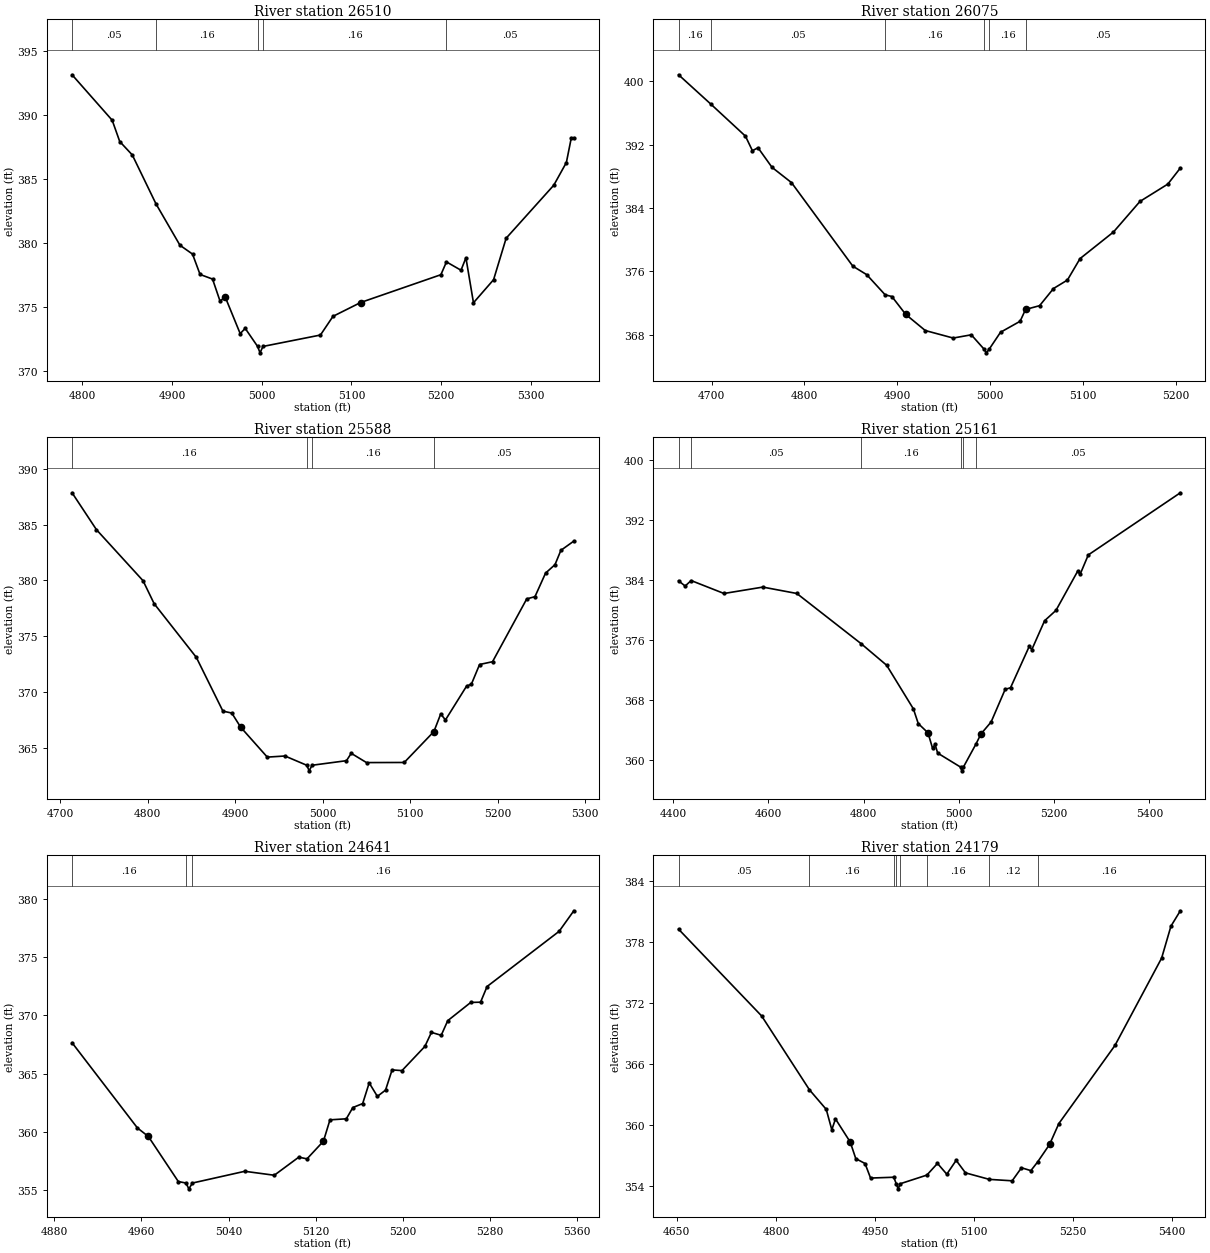
Type RM Length L Ch R = 1 ,26510   ,435,435,435
BEGIN DESCRIPTION:
PENNINGTON BRANCH 47.0
END DESCRIPTION:
XS GIS Cut Line= 3
      3788649.63     10526360.18      3788449.61     10526460.19
      3788299.63     10526760.16
#Sta/Elev= 30
  4788.7  393.13  4833.4  389.58  4841.8  387.92  4855.8  386.87  4882.2  383.05
  4908.9  379.82  4922.9  379.13  4931.3  377.54  4945.2  377.18  4953.6  375.45
  4959.2   375.8    4976  372.92  4981.6  373.33  4995.4  371.92  4998.1  371.42
  5001.4  371.92  5065.4  372.81  5079.4  374.27  5110.2  375.35  5199.6  377.52
  5205.8  378.52    5222  377.87  5227.5  378.84  5235.9  375.33  5258.3  377.13
  5272.3  380.37  5325.4  384.51  5339.4  386.28  5344.9  388.21  5347.7  388.21
#Mann= 5 ,-1 , 0
  4788.7     .05       0  4882.2     .16       0  4995.4     .07       0
  5001.4     .16       0  5205.8     .05       0
Bank Sta=4959.2,5110.2
XS Rating Curve= 0 ,0
Exp/Cntr=0.3,0.1

Type RM Length L Ch R = 1 ,26075   ,487,487,487
BEGIN DESCRIPTION:
PENNINGTON BRANCH 46.0
END DESCRIPTION:
XS GIS Cut Line= 3
      3788499.61     10525960.19      3788199.61     10526160.19
      3788049.64     10526260.17
#Sta/Elev= 30
  4664.3  400.84  4698.9  397.15  4736.4  393.08  4743.9  391.24  4749.9  391.62
    4765  389.14    4786  387.21  4852.1  376.65  4867.1  375.57    4887  373.02
  4894.2  372.81  4909.2  370.54  4930.2  368.51  4960.3  367.56  4979.8  367.97
  4993.3  366.19  4996.1  365.69  4999.3  366.19  5011.3  368.29  5032.4  369.68
  5038.4   371.2  5038.8  371.19  5053.4  371.65  5068.4  373.82  5083.4  374.89
    5097   377.6    5133  380.96  5161.6  384.83  5191.6  387.02  5205.1  389.05
#Mann= 6 ,-1 , 0
  4664.3     .16       0  4698.9     .05       0    4887     .16       0
  4993.3     .07       0  4999.3     .16       0  5038.8     .05       0
Bank Sta=4909.2,5038.4
XS Rating Curve= 0 ,0
Exp/Cntr=0.3,0.1

Type RM Length L Ch R = 1 ,25588   ,427,427,427
BEGIN DESCRIPTION:
PENNINGTON BRANCH 45.0
END DESCRIPTION:
XS GIS Cut Line= 3
      3788299.65     10525710.18      3787999.61     10525760.19
      3787899.62     10526010.16
#Sta/Elev= 30
  4713.6  387.86  4741.5  384.55  4794.7  379.98  4807.4  377.92  4855.6  373.11
    4886  368.29  4896.1  368.12  4906.3  366.85  4936.7  364.17  4956.9  364.27
  4981.8  363.44  4984.6  362.94  4987.8  363.44  5027.2  363.85  5032.6  364.51
  5050.1  363.68  5093.2  363.69  5127.1  366.46  5134.9  368.04  5140.3   367.5
  5164.5  370.54  5169.9   370.7  5179.3  372.47  5194.1  372.72  5233.2  378.35
  5242.6  378.55  5254.7  380.66  5265.5  381.42  5272.2   382.7    5287  383.53
#Mann= 4 ,-1 , 0
  4713.6     .16       0  4981.8     .07       0  4987.8     .16       0
  5127.1     .05       0
Bank Sta=4906.3,5127.1
XS Rating Curve= 0 ,0
Exp/Cntr=0.3,0.1

Type RM Length L Ch R = 1 ,25161   ,520,520,520
BEGIN DESCRIPTION:
PENNINGTON BRANCH 44.0
END DESCRIPTION:
XS GIS Cut Line= 2
      3788333.09      10525338.8      3787300.09     10525547.13
#Sta/Elev= 30
  4411.3  383.91  4425.1  383.21  4437.7  383.94  4506.7  382.22  4588.3  383.07
  4659.7  382.22  4795.1  375.52  4848.3  372.67  4904.5  366.86  4914.7  364.91
  4935.1  363.68  4944.8  361.61  4949.9  362.15  4955.5  360.98  5003.5  359.12
  5006.3  358.62  5009.5  359.12  5036.1  362.21  5046.4  363.53  5067.7  365.12
  5097.2  369.46  5108.5  369.68    5148  375.21  5153.1  374.74    5180  378.59
  5203.9  379.97  5249.6   385.2  5254.7  384.78  5271.8  387.35  5465.1  395.62
#Mann= 6 ,-1 , 0
  4411.3     .16       0  4437.7     .05       0  4795.1     .16       0
  5003.5     .07       0  5009.5     .16       0  5036.1     .05       0
Bank Sta=4935.1,5046.4
XS Rating Curve= 0 ,0
Exp/Cntr=0.3,0.1

Type RM Length L Ch R = 1 ,24641   ,462,462,462
BEGIN DESCRIPTION:
PENNINGTON BRANCH 43.0
END DESCRIPTION:
XS GIS Cut Line= 3
      3787749.56     10524960.19      3787649.61     10524960.19
      3787449.61     10525260.18
#Sta/Elev= 30
  4896.4  367.65  4956.4  360.31  4966.4  359.58  4993.9   355.7  5000.9  355.57
  5003.6  355.07  5006.9  355.57  5054.9  356.58    5082  356.24  5104.5   357.8
    5112  357.65  5127.1  359.17  5133.1  361.01  5148.1   361.1  5154.1  362.07
  5163.1  362.41  5169.1  364.19  5176.6  363.03  5184.1  363.57  5190.1  365.31
  5199.2  365.25  5220.2  367.33  5226.2  368.54  5235.2  368.29  5241.2  369.55
  5262.3  371.12  5271.3  371.14  5277.3  372.49  5343.4  377.24  5356.9  379.01
#Mann= 3 ,-1 , 0
  4896.4     .16       0  5000.9     .07       0  5006.9     .16       0
Bank Sta=4966.4,5127.1
XS Rating Curve= 0 ,0
Exp/Cntr=0.3,0.1

Type RM Length L Ch R = 1 ,24179   ,441,441,441
BEGIN DESCRIPTION:
PENNINGTON BRANCH 42.0
END DESCRIPTION:
XS GIS Cut Line= 3
       3787749.6     10524460.19      3787449.61     10524610.19
      3787149.59     10524910.21
#Sta/Elev= 30
  4652.6  379.25  4778.4  370.72  4850.8  363.46  4876.2  361.54  4884.6  359.54
  4890.2   360.6  4912.5  358.33  4920.9   356.7  4934.9  356.22  4943.3  354.79
  4978.4  354.87  4982.2  354.23    4985  353.73  4988.2  354.23  5028.5  355.08
  5044.6  356.23  5058.7  355.17  5072.9  356.53    5087   355.3  5123.1  354.66
  5157.7  354.52  5171.8   355.8    5186  355.52  5196.1  356.36  5214.3  358.09
  5228.4  360.15  5313.3  367.82    5384  376.41  5398.1  379.55  5412.3  381.06
#Mann= 8 ,-1 , 0
  4652.6     .05       0  4850.8     .16       0  4978.4     .12       0
  4982.2     .07       0  4988.2     .12       0  5028.5     .16       0
  5123.1     .12       0  5196.1     .16       0
Bank Sta=4912.5,5214.3
XS Rating Curve= 0 ,0
Exp/Cntr=0.3,0.1

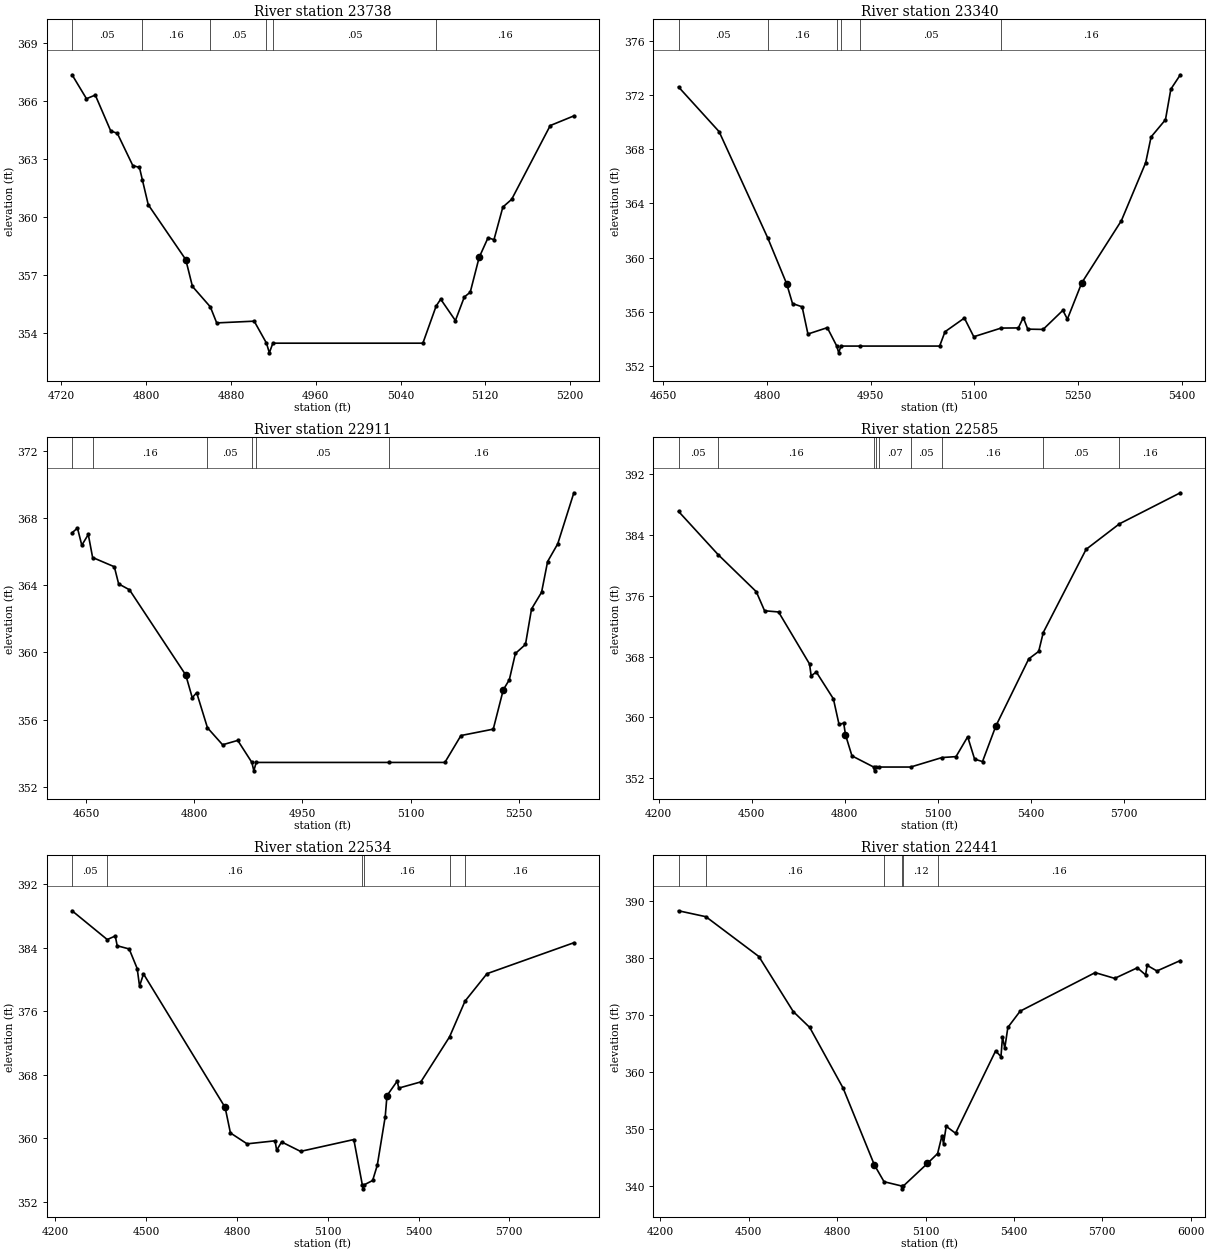
Type RM Length L Ch R = 1 ,23738   ,398,398,398
BEGIN DESCRIPTION:
PENNINGTON BRANCH 41.0
END DESCRIPTION:
XS GIS Cut Line= 3
      3787249.63     10524210.16      3787099.61     10524410.19
      3786899.65     10524510.17
#Sta/Elev= 30
    4730  367.36  4743.6  366.12  4751.9  366.31  4766.5  364.45  4772.7  364.33
  4787.3  362.66  4793.6  362.56  4796.3  361.93  4801.9  360.63  4837.3  357.79
  4843.6   356.4  4860.5  355.34  4866.5  354.51  4901.9   354.6  4913.5  353.46
  4916.2  352.96  4919.5  353.46  5061.1  353.46  5073.6  355.38  5077.9  355.74
  5091.8  354.63  5100.2  355.85  5105.8   356.1  5114.2   357.9  5122.6  358.92
  5128.2  358.82  5136.6  360.51  5144.9  360.91  5181.3  364.73  5203.6  365.23
#Mann= 6 ,-1 , 0
    4730     .05       0  4796.3     .16       0  4860.5     .05       0
  4913.5    .033       0  4919.5     .05       0  5073.6     .16       0
Bank Sta=4837.3,5114.2
XS Rating Curve= 0 ,0
Exp/Cntr=0.3,0.1

Type RM Length L Ch R = 1 ,23340   ,429,429,429
BEGIN DESCRIPTION:
PENNINGTON BRANCH 40.0
END DESCRIPTION:
XS GIS Cut Line= 3
      3786899.59     10523910.23      3786749.61     10524210.19
      3786499.59     10524510.21
#Sta/Elev= 30
  4672.2   372.6  4730.9   369.3  4801.4  361.43  4828.7  358.05  4837.1   356.6
    4851  356.36  4859.4  354.35  4887.4  354.82  4901.1  353.46  4903.9  352.96
  4907.1  353.46  4934.4  353.46  5049.9  353.46  5057.7  354.52  5085.7  355.53
  5099.3  354.15  5138.9  354.79  5163.8   354.8  5170.9  355.57  5177.4  354.71
  5199.6  354.69  5228.2   356.1  5234.7  355.45  5255.5  358.13  5312.8  362.72
    5348  367.01  5355.8  368.91  5376.6  370.18  5384.4  372.44  5398.1   373.5
#Mann= 6 ,-1 , 0
  4672.2     .05       0  4801.4     .16       0  4901.1    .033       0
  4907.1     .16       0  4934.4     .05       0  5138.9     .16       0
Bank Sta=4828.7,5255.5
XS Rating Curve= 0 ,0
Exp/Cntr=0.3,0.1

Type RM Length L Ch R = 1 ,22911   ,326,326,326
BEGIN DESCRIPTION:
PENNINGTON BRANCH 39.0
END DESCRIPTION:
XS GIS Cut Line= 3
       3786549.6      10523760.2      3786349.61     10524060.19
      3786199.59     10524360.23
#Sta/Elev= 30
  4630.4  367.12  4637.9   367.4  4643.9  366.38  4652.9  367.02  4658.9  365.65
    4689   365.1    4695  364.08    4710  363.73  4788.1  358.66  4797.1  357.31
  4803.2  357.61  4818.2  355.52  4839.2  354.51  4860.2  354.77  4879.8  353.46
  4882.5  352.96  4885.8  353.46  5069.9  353.46  5147.5  353.46  5169.8  355.06
  5214.6  355.44  5228.5  357.78  5236.9  358.38  5245.3  359.94  5259.3  360.48
  5267.7  362.59  5281.6  363.58    5290  365.41    5304  366.46  5326.4   369.5
#Mann= 6 ,-1 , 0
  4630.4     .05       0  4658.9     .16       0  4818.2     .05       0
  4879.8    .033       0  4885.8     .05       0  5069.9     .16       0
Bank Sta=4788.1,5228.5
XS Rating Curve= 0 ,0
Exp/Cntr=0.3,0.1

Type RM Length L Ch R = 1 ,22585   ,51,51,51
BEGIN DESCRIPTION:
Mapping XS 0946b067
END DESCRIPTION:
XS GIS Cut Line= 3
      3786235.52     10523304.37      3785983.79     10524155.04
      3786148.52     10524865.98
#Sta/Elev= 30
  4264.2  387.09  4391.4  381.42  4514.7  376.53  4541.4  374.02  4586.5  373.86
  4686.3  367.02  4691.5  365.47  4708.3  365.95  4763.2  362.43  4781.3  359.08
  4796.5  359.23  4802.1  357.71    4823  354.93    4893  353.46  4895.7  352.96
    4899  353.46  4910.9  353.46  5012.1  353.46  5113.3  354.71  5158.3  354.83
  5195.9  357.44  5218.2   354.5  5243.7  354.18  5286.4  358.83  5392.7  367.69
  5424.7  368.67  5439.4  371.15  5577.5   382.1  5684.7  385.45  5881.1  389.54
#Mann= 9 ,-1 , 0
  4264.2     .05       0  4391.4     .16       0    4893     .07       0
    4899     .16       0  4910.9     .07       0  5012.1     .05       0
  5113.3     .16       0  5439.4     .05       0  5684.7     .16       0
Bank Sta=4802.1,5286.4
XS Rating Curve= 0 ,0
Exp/Cntr=0.3,0.1

Type RM Length L Ch R = 1 ,22534   ,93,93,93
BEGIN DESCRIPTION:
PENNINGTON BRANCH 38.0
END DESCRIPTION:
XS GIS Cut Line= 3
      3786174.76     10523282.65      3785905.67     10524254.87
      3786083.62     10524879.86
#Sta/Elev= 30
  4254.8  388.62  4371.1     385  4397.5  385.45    4404  384.22  4443.5  383.82
  4470.1  381.35  4477.8  379.14  4490.9  380.68  4760.7  363.89  4778.2  360.68
  4833.3  359.31  4925.8  359.69    4931   358.5  4947.4  359.55    5010  358.36
  5186.1  359.85  5214.2  354.15    5217  353.65  5220.2  354.15  5248.3   354.7
  5263.6  356.61  5289.9  362.73  5295.7  365.37  5329.5   367.2  5334.7  366.32
  5407.6   367.1  5502.5  372.76  5553.7  377.26  5626.3  380.71  5913.4   384.6
#Mann= 6 ,-1 , 0
  4254.8     .05       0  4371.1     .16       0  5214.2     .07       0
  5220.2     .16       0  5502.5     .05       0  5553.7     .16       0
Bank Sta=4760.7,5295.7
XS Rating Curve= 0 ,0
Exp/Cntr=0.3,0.1

Type RM Length L Ch R = 1 ,22441   ,439,439,439
BEGIN DESCRIPTION:
Mapping XS 911d7e72
END DESCRIPTION:
XS GIS Cut Line= 3
      3786131.36     10523282.66      3785814.52     10524185.42
       3786027.2     10524901.57
#Sta/Elev= 30
  4261.3  388.26  4354.2  387.22  4534.2  380.23  4650.8  370.58  4706.8  367.79
  4820.1  357.15  4926.4  343.66  4959.1  340.73  5018.7  339.98  5021.5  339.48
  5024.7  339.98  5106.5  343.94  5140.9  345.67  5155.8  348.81  5161.1  347.41
  5170.1  350.46  5201.9  349.23  5337.8  363.67  5356.1  362.69  5361.3  366.11
  5369.1  364.18  5379.5   367.8  5421.2  370.65  5675.9  377.41  5742.3   376.4
  5819.2  378.26  5847.2  377.01  5852.4  378.69  5885.6   377.7  5965.1  379.53
#Mann= 6 ,-1 , 0
  4261.3     .05       0  4354.2     .16       0  4959.1     .12       0
  5018.7     .07       0  5024.7     .12       0  5140.9     .16       0
Bank Sta=4926.4,5106.5
XS Rating Curve= 0 ,0
Exp/Cntr=0.3,0.1

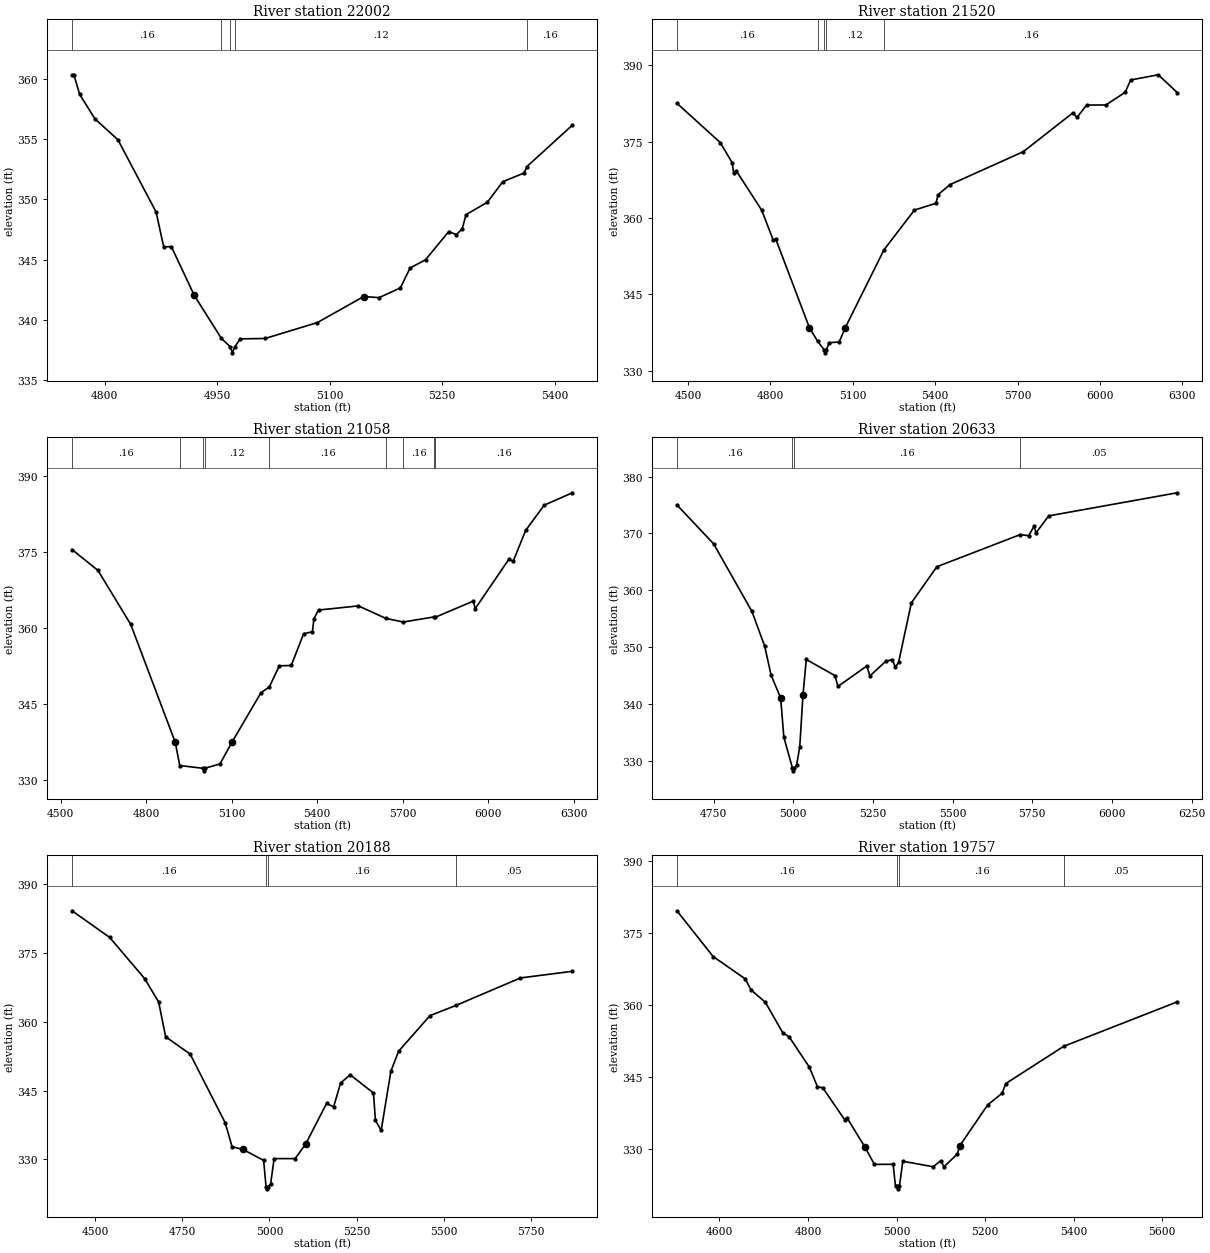
Type RM Length L Ch R = 1 ,22002   ,482,482,482
BEGIN DESCRIPTION:
PENNINGTON BRANCH 37.0
END DESCRIPTION:
XS GIS Cut Line= 3
       3785549.6     10523610.22      3785499.61     10523860.19
      3785399.62     10524260.16
#Sta/Elev= 30
  4756.5  360.34    4759  360.34  4766.7  358.72  4787.1  356.68  4817.7  354.95
  4868.6  348.96  4878.8  346.06    4889  346.08  4919.6  342.03  4955.8  338.46
  4967.6  337.77  4970.4  337.27  4973.6  337.77  4980.8  338.43    5014  338.46
  5083.6  339.78  5145.4  341.94    5166  341.85  5194.4  342.66  5207.3  344.31
  5227.9  344.99  5258.8  347.33  5269.1  347.08  5276.8  347.56    5282  348.74
  5310.3  349.76    5331  351.47  5359.3  352.19  5363.2  352.73  5423.7  356.16
#Mann= 5 ,-1 , 0
  4756.5     .16       0  4955.8     .12       0  4967.6     .07       0
  4973.6     .12       0  5363.2     .16       0
Bank Sta=4919.6,5145.4
XS Rating Curve= 0 ,0
Exp/Cntr=0.3,0.1

Type RM Length L Ch R = 1 ,21520   ,462,462,462
BEGIN DESCRIPTION:
PENNINGTON BRANCH 36.0
END DESCRIPTION:
XS GIS Cut Line= 3
      3785416.42     10523168.63      3784826.12     10524054.08
      3784765.36     10524809.26
#Sta/Elev= 30
  4459.4  382.57  4617.5  374.83  4660.3  370.92  4666.3  368.85  4675.3  369.32
  4768.4  361.53  4810.5  355.62  4819.5  355.87    4942  338.45  4971.8  335.81
  4996.8  334.03  4999.6  333.53  5002.8  334.03  5014.1  335.52  5050.2  335.66
  5071.9  338.41  5213.5  353.79  5324.3  361.58  5402.4  362.91  5410.7  364.62
  5453.5  366.57  5720.3  373.04  5900.9  380.67  5916.2  379.79  5951.1  382.21
  6021.3  382.23  6091.5  384.71  6111.6  387.14  6211.9  388.16  6281.2  384.66
#Mann= 5 ,-1 , 0
  4459.4     .16       0  4971.8     .12       0  4996.8     .07       0
  5002.8     .12       0  5213.5     .16       0
Bank Sta=4942,5071.9
XS Rating Curve= 0 ,0
Exp/Cntr=0.3,0.1

Type RM Length L Ch R = 1 ,21058   ,425,425,425
BEGIN DESCRIPTION:
PENNINGTON BRANCH 35.0
END DESCRIPTION:
XS GIS Cut Line= 3
      3785086.58     10523159.95      3784452.86     10523628.73
      3783975.43     10524470.74
#Sta/Elev= 30
  4539.1   375.4  4630.3  371.28  4745.1  360.64  4901.6  337.34  4917.3  332.77
  4998.8  332.22  5001.6  331.72  5004.8  332.22  5058.2  333.07    5102  337.51
  5202.2  347.13  5231.3  348.24    5267  352.45  5308.7  352.52    5352  358.78
  5382.7  359.17  5388.4  361.78  5404.3  363.46  5544.3  364.28  5640.3  361.82
  5701.6   361.1  5808.7  362.09    5812  361.99  5948.2  365.24  5953.9   363.7
  6072.2  373.47  6087.7  373.11  6131.4  379.18  6196.3  384.16  6295.3  386.61
#Mann= 9 ,-1 , 0
  4539.1     .16       0  4917.3     .12       0  4998.8     .07       0
  5004.8     .12       0  5231.3     .16       0  5640.3     .05       0
  5701.6     .16       0  5808.7     .05       0    5812     .16       0
Bank Sta=4901.6,5102
XS Rating Curve= 0 ,0
Exp/Cntr=0.3,0.1

Type RM Length L Ch R = 1 ,20633   ,445,445,445
BEGIN DESCRIPTION:
PENNINGTON BRANCH 34.0
END DESCRIPTION:
XS GIS Cut Line= 3
      3785104.96     10523105.82      3784266.05     10523083.59
      3783604.91     10523394.72
#Sta/Elev= 30
  4634.8  375.01  4750.2  368.15  4870.2  356.29  4910.3  350.17  4930.3  345.08
  4960.3  341.09  4970.3  334.19  4997.3  328.77    5000  328.27  5003.3  328.77
  5010.3  329.25  5020.3  332.51  5030.3  341.57  5040.7  347.84  5130.3  345.02
  5140.3  343.11  5230.4  346.69  5240.4  344.96  5290.4  347.53  5310.4  347.82
  5320.4  346.48  5330.4  347.35  5370.4  357.79  5450.4  364.14    5712  369.79
  5738.5   369.6  5755.7  371.29  5761.3  370.08  5801.3  373.08  6204.7  377.14
#Mann= 4 ,-1 , 0
  4634.8     .16       0  4997.3     .07       0  5003.3     .16       0
    5712     .05       0
Bank Sta=4960.3,5030.3
XS Rating Curve= 0 ,0
Exp/Cntr=0.3,0.1

Type RM Length L Ch R = 1 ,20188   ,431,431,431
BEGIN DESCRIPTION:
PENNINGTON BRANCH 33.0
END DESCRIPTION:
XS GIS Cut Line= 3
      3785327.19     10522722.48      3784538.28     10522661.37
      3783966.68     10522955.49
#Sta/Elev= 30
    4434   384.2  4541.9   378.4  4642.2  369.42  4682.3  364.32  4702.4  356.74
  4772.6  352.96  4872.9  338.03  4892.9  332.75    4923  332.22  4983.2  329.79
  4990.2  324.09    4993  323.59  4996.2  324.09  5003.3  324.67  5013.3  330.18
  5073.5  330.18  5103.6  333.34  5163.8  342.23  5183.8  341.44  5203.9  346.68
  5231.5  348.45    5298  344.48  5303.7   338.5  5320.2  336.32    5348  349.25
  5370.2  353.59  5459.9  361.34  5534.8  363.58  5719.3  369.56  5868.1  371.01
#Mann= 4 ,-1 , 0
    4434     .16       0  4990.2     .07       0  4996.2     .16       0
  5534.8     .05       0
Bank Sta=4923,5103.6
XS Rating Curve= 0 ,0
Exp/Cntr=0.3,0.1

Type RM Length L Ch R = 1 ,19757   ,447,447,447
BEGIN DESCRIPTION:
PENNINGTON BRANCH 32.0
END DESCRIPTION:
XS GIS Cut Line= 3
      3785366.07     10522461.38      3784727.16     10522216.93
      3784288.28      10522294.7
#Sta/Elev= 30
  4504.1  379.59    4586  370.07  4658.5  365.42  4671.6  363.12  4703.7  360.58
  4743.3   354.2  4757.3   353.4  4803.4  347.04  4821.5  342.98  4833.4  342.79
  4882.8  336.15  4888.2  336.52  4928.6  330.46    4950  326.85  4992.3  326.86
  4997.7  322.28  5000.5  322.26  5003.3  321.76  5006.5  322.26  5014.2   327.5
  5082.5  326.36  5099.9   327.6  5107.2  326.34  5137.2     329  5142.7  330.71
    5206  339.23  5238.5  341.65  5246.6  343.65  5377.5   351.4  5633.9  360.65
#Mann= 4 ,-1 , 0
  4504.1     .16       0  5000.5     .07       0  5006.5     .16       0
  5377.5     .05       0
Bank Sta=4928.6,5142.7
XS Rating Curve= 0 ,0
Exp/Cntr=0.3,0.1

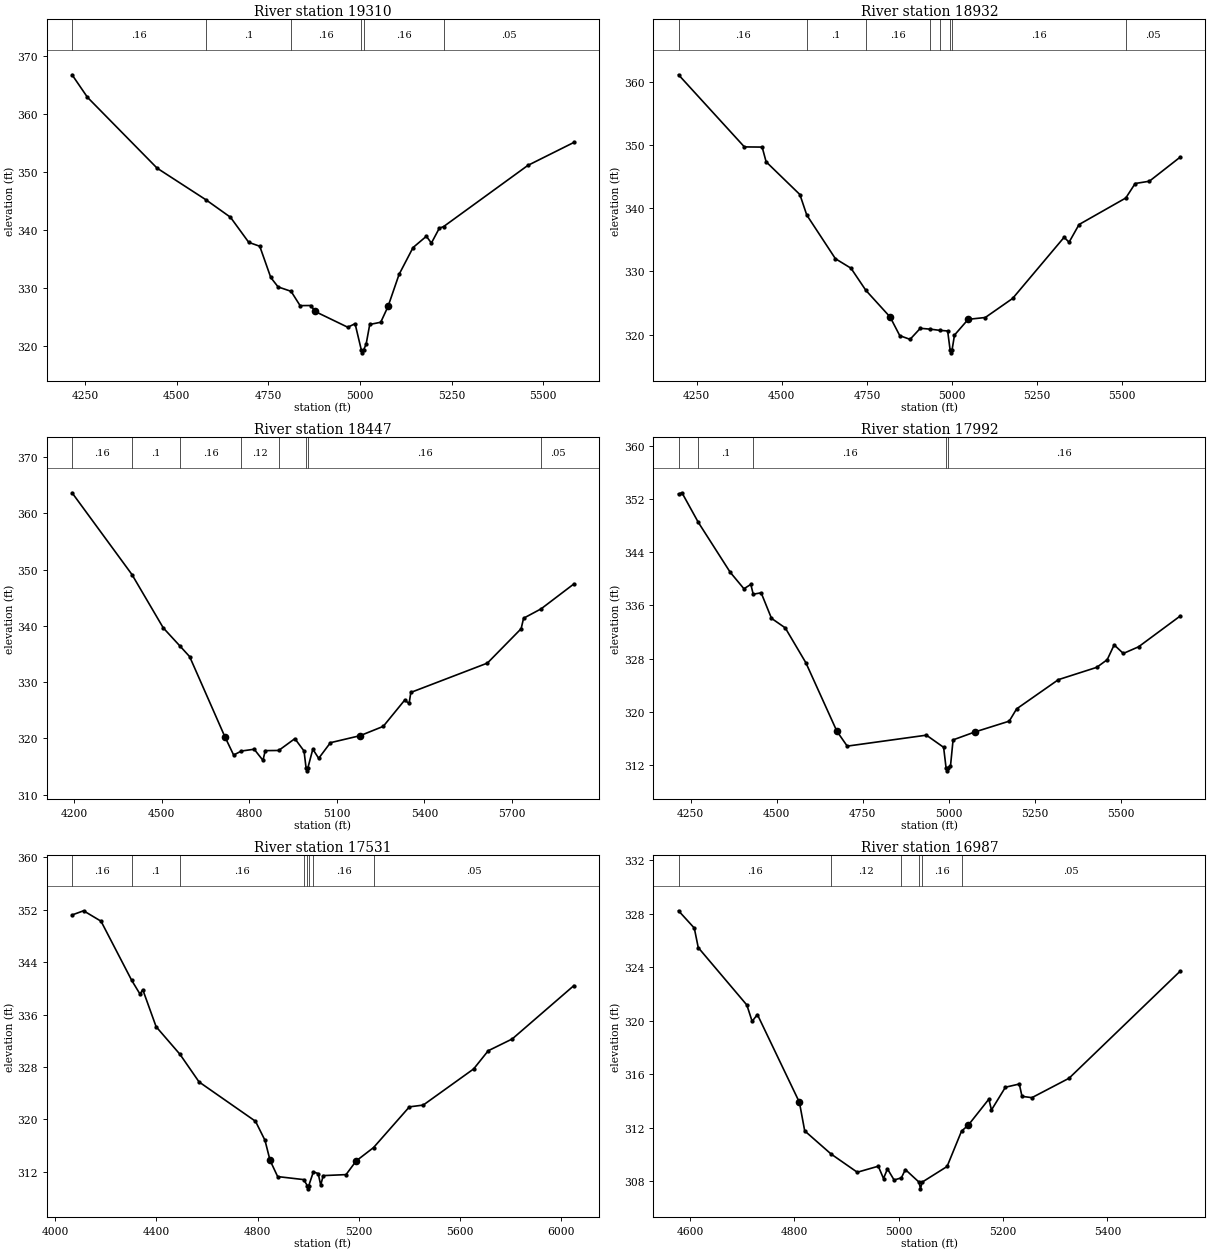
Type RM Length L Ch R = 1 ,19310   ,378,378,378
BEGIN DESCRIPTION:
PENNINGTON BRANCH 31.0
END DESCRIPTION:
XS GIS Cut Line= 3
      3785621.57     10521878.04      3784688.28     10521883.59
      3784310.51     10522100.25
#Sta/Elev= 30
  4214.7  366.84  4256.7  362.95  4446.7  350.72  4579.4  345.28  4646.7  342.25
  4696.7  337.91  4726.7  337.24  4756.7  331.85  4776.7  330.22  4812.1  329.46
  4836.7  326.99  4866.7  327.01  4876.7  326.01  4966.7  323.26  4986.7  323.87
  5003.7  319.34  5006.4  318.84  5009.7  319.34  5016.7  320.28  5026.7  323.74
  5056.7  324.12  5076.7  326.86  5106.7  332.38  5144.8  337.01  5181.1  338.96
  5194.9  337.79  5216.5  340.36  5228.1  340.63  5458.1   351.2  5583.5  355.16
#Mann= 6 ,-1 , 0
  4214.7     .16       0  4579.4      .1       0  4812.1     .16       0
  5003.7     .07       0  5009.7     .16       0  5228.1     .05       0
Bank Sta=4876.7,5076.7
XS Rating Curve= 0 ,0
Exp/Cntr=0.3,0.1

Type RM Length L Ch R = 1 ,18932   ,485,485,485
BEGIN DESCRIPTION:
PENNINGTON BRANCH 30.0
END DESCRIPTION:
XS GIS Cut Line= 4
      3785604.91     10521678.03      3785049.39     10521511.37
      3784604.94     10521555.81       3784338.9     10521916.08
#Sta/Elev= 30
  4196.5   361.1    4390  349.69  4442.2  349.66  4453.9  347.33  4553.1  342.15
  4573.3  338.91  4657.5     332  4703.2   330.5  4746.9     327  4818.2  322.78
  4846.6  319.83  4876.8  319.24  4906.9  320.99  4935.6  320.86  4965.3  320.66
  4987.3  320.57  4994.4  317.61  4997.1  317.11  5000.4  317.61  5007.4  319.92
  5047.6  322.41  5097.9   322.7  5178.3  325.72  5329.5  335.39  5344.1  334.61
  5373.4  337.41  5510.8  341.61  5538.3   343.9    5580  344.26    5671  348.09
#Mann= 8 ,-1 , 0
  4196.5     .16       0  4573.3      .1       0  4746.9     .16       0
  4935.6     .12       0  4965.3     .16       0  4994.4     .07       0
  5000.4     .16       0  5510.8     .05       0
Bank Sta=4818.2,5047.6
XS Rating Curve= 0 ,0
Exp/Cntr=0.3,0.1

Type RM Length L Ch R = 1 ,18447   ,455,455,455
BEGIN DESCRIPTION:
PENNINGTON BRANCH 29.0
END DESCRIPTION:
XS GIS Cut Line= 3
      3785510.49     10521050.26      3784604.94     10521139.15
      3784178.06     10521826.59
#Sta/Elev= 30
    4193  363.64  4398.1  349.12  4505.4  339.64  4563.4  336.37  4595.8  334.53
  4716.4  320.31  4746.5  317.05  4773.4  317.76  4816.9  318.08    4847   316.1
  4854.8  317.83  4900.9  317.86  4956.3  319.96  4987.7  317.76  4994.7  314.74
  4997.5  314.24  5000.7  314.74  5017.8  318.09  5037.9  316.46  5078.1  319.24
    5180  320.49  5259.1  322.14  5332.3  326.79  5347.7  326.22  5353.6  328.17
  5615.8  333.38  5731.5  339.49  5739.8  341.35  5799.9  343.02  5912.1  347.44
#Mann= 8 ,-1 , 0
    4193     .16       0  4398.1      .1       0  4563.4     .16       0
  4773.4     .12       0  4900.9     .16       0  4994.7     .07       0
  5000.7     .16       0  5799.9     .05       0
Bank Sta=4716.4,5180
XS Rating Curve= 0 ,0
Exp/Cntr=0.3,0.1

Type RM Length L Ch R = 1 ,17992   ,461,461,461
BEGIN DESCRIPTION:
PENNINGTON BRANCH 28.0
END DESCRIPTION:
XS GIS Cut Line= 3
       3785399.6     10520810.19      3784599.61     10520810.19
      3783949.65     10520910.18
#Sta/Elev= 30
  4214.7  352.78  4224.7  352.96  4272.1  348.51  4364.7     341  4404.7  338.51
  4424.7  339.17  4431.6  337.69  4454.7   337.9  4484.7  334.06  4524.7  332.62
  4584.7  327.36  4674.7  317.06  4704.7  314.82  4934.7  316.47  4984.7  314.64
  4991.7   311.6  4994.4   311.1  4997.7   311.6  5004.7  311.84  5012.2  315.76
  5075.4  316.95  5175.3  318.58  5196.8  320.43  5318.2  324.83  5429.5  326.68
  5459.9  327.83  5480.1  330.06  5506.7  328.77  5550.9  329.77  5672.3  334.42
#Mann= 5 ,-1 , 0
  4214.7     .16       0  4272.1      .1       0  4431.6     .16       0
  4991.7     .07       0  4997.7     .16       0
Bank Sta=4674.7,5075.4
XS Rating Curve= 0 ,0
Exp/Cntr=0.3,0.1

Type RM Length L Ch R = 1 ,17531   ,544,544,544
BEGIN DESCRIPTION:
PENNINGTON BRANCH 27.0
END DESCRIPTION:
XS GIS Cut Line= 4
      3785604.94     10520600.26       3784910.5     10520372.48
      3784254.94     10520389.15      3783754.98     10520711.35
#Sta/Elev= 30
  4067.6  351.19    4113  351.83  4181.9  350.24    4303  341.22  4335.8  339.12
  4346.8  339.79  4399.5  334.14  4493.8  329.92  4569.1  325.71  4791.9  319.71
  4829.3  316.81  4849.4  313.74  4879.4  311.27  4981.9  310.81  4996.4   309.9
  4999.1   309.4  5002.4   309.9  5020.4  311.99  5039.4  311.73  5049.4  309.98
  5059.4  311.42  5149.4  311.57  5189.5  313.66  5258.1   315.7  5399.5  321.91
  5454.2  322.18  5653.4   327.7  5710.8  330.47  5805.6  332.27    6049  340.41
#Mann= 8 ,-1 , 0
  4067.6     .16       0    4303      .1       0  4493.8     .16       0
  4981.9     .12       0  4996.4     .07       0  5002.4     .12       0
  5020.4     .16       0  5258.1     .05       0
Bank Sta=4849.4,5189.5
XS Rating Curve= 0 ,0
Exp/Cntr=0.3,0.1

Type RM Length L Ch R = 1 ,16987   ,526,526,526
BEGIN DESCRIPTION:
PENNINGTON BRANCH 26.0
END DESCRIPTION:
XS GIS Cut Line= 3
      3785099.62     10519910.19      3784699.61     10519960.19
      3784149.65      10519860.2
#Sta/Elev= 30
  4577.8  328.21    4608  326.92  4615.6  325.46  4708.8  321.17  4718.9  319.95
    4729  320.46  4809.6   313.9  4819.7  311.77  4870.3  310.04  4920.5  308.68
  4960.8  309.13  4970.8  308.21  4978.4  308.93  4991.1   308.1    5005  308.26
  5012.7  308.88  5038.9  307.94  5041.7  307.44  5044.9  307.94  5092.7  309.11
  5120.4  311.75  5133.4   312.2  5172.8  314.14  5177.8  313.33  5204.5  315.03
  5231.2  315.27  5236.3  314.35  5255.3  314.25  5326.5   315.7  5539.9  323.71
#Mann= 6 ,-1 , 0
  4577.8     .16       0  4870.3     .12       0    5005     .16       0
  5038.9     .07       0  5044.9     .16       0  5120.4     .05       0
Bank Sta=4809.6,5133.4
XS Rating Curve= 0 ,0
Exp/Cntr=0.3,0.1

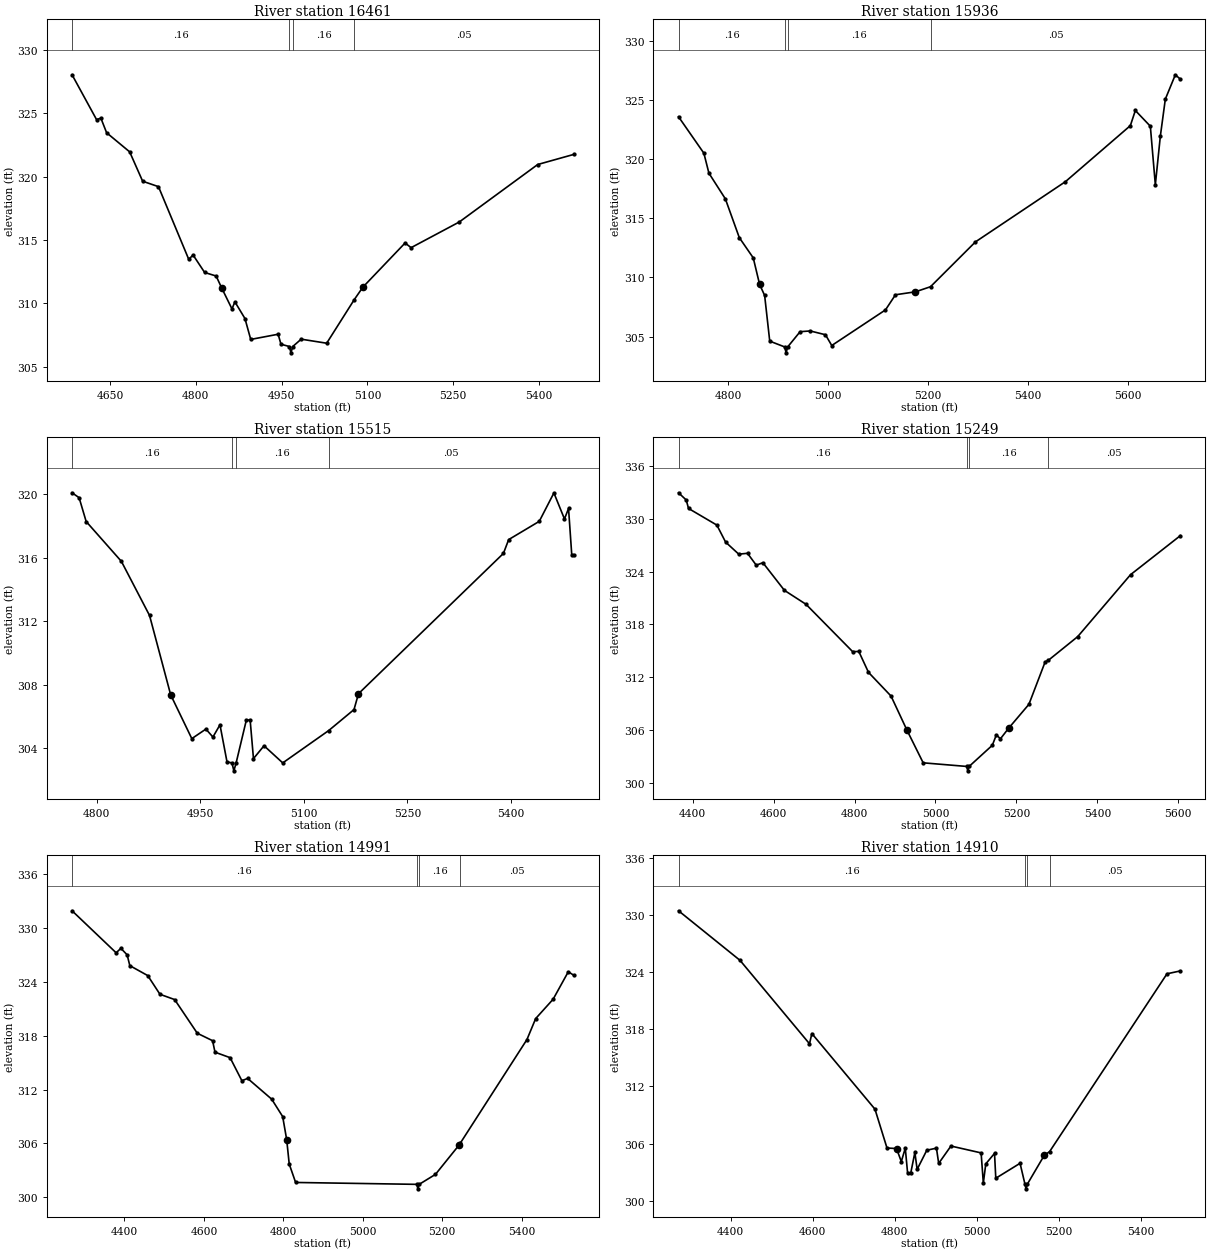
Type RM Length L Ch R = 1 ,16461   ,525,525,525
BEGIN DESCRIPTION:
PENNINGTON BRANCH 25.0
END DESCRIPTION:
XS GIS Cut Line= 3
      3785049.58     10519510.19      3784649.61     10519560.19
      3784199.63     10519710.18
#Sta/Elev= 30
  4583.6  328.05  4626.4  324.51    4634  324.62    4644  323.47  4684.3  321.96
    4707  319.64  4734.7  319.21  4787.6  313.47  4795.2  313.81  4815.4  312.43
  4835.5  312.15  4845.6  311.17  4863.2  309.55  4868.3  310.11  4885.9  308.79
    4896  307.14  4943.9  307.55  4948.9  306.76  4963.5  306.58  4966.3  306.08
  4969.5  306.58  4984.2  307.16  5028.8  306.84  5077.1  310.29  5092.1  311.27
  5165.9  314.76  5176.4  314.39  5260.7  316.42  5397.8  320.96    5461  321.76
#Mann= 4 ,-1 , 0
  4583.6     .16       0  4963.5     .07       0  4969.5     .16       0
  5077.1     .05       0
Bank Sta=4845.6,5092.1
XS Rating Curve= 0 ,0
Exp/Cntr=0.3,0.1

Type RM Length L Ch R = 1 ,15936   ,421,421,421
BEGIN DESCRIPTION:
PENNINGTON BRANCH 24.0
END DESCRIPTION:
XS GIS Cut Line= 3
      3784899.58     10519060.19      3784599.61     10519110.19
      3783899.62     10519110.19
#Sta/Elev= 30
  4700.8  323.59  4751.5  320.51  4761.6  318.82  4794.5  316.65  4822.4  313.37
  4850.3  311.66    4863  309.42  4873.1  308.48  4883.3  304.62  4913.2  304.13
    4916  303.63  4919.2  304.13  4944.1  305.42  4964.4  305.48  4994.8  305.16
  5007.4  304.25  5114.9  307.26  5134.9  308.54  5174.9  308.79    5205  309.22
  5294.9  313.01  5474.9   318.1  5604.9  322.84  5614.9  324.12  5644.9  322.79
  5654.9  317.84  5664.9  321.95  5674.9  325.08  5694.9  327.14  5704.9  326.77
#Mann= 4 ,-1 , 0
  4700.8     .16       0  4913.2     .07       0  4919.2     .16       0
    5205     .05       0
Bank Sta=4863,5174.9
XS Rating Curve= 0 ,0
Exp/Cntr=0.3,0.1

Type RM Length L Ch R = 1 ,15515   ,266,266,266
BEGIN DESCRIPTION:
PENNINGTON BRANCH 23.0
END DESCRIPTION:
XS GIS Cut Line= 3
      3784699.65     10518710.18      3784449.61     10518760.19
       3784049.6     10519010.19
#Sta/Elev= 30
  4764.4   320.1  4774.6  319.79  4784.8  318.29  4835.8  315.78  4876.6  312.37
  4907.2  307.37  4937.8  304.61  4958.2  305.21  4968.4  304.71  4978.6  305.48
  4988.8  303.14    4996  303.08  4998.7  302.58    5002  303.08  5016.8  305.78
  5022.3  305.78  5027.1  303.35  5042.4  304.16  5069.5  303.08  5136.1  305.12
  5172.7  306.44  5179.2  307.44  5389.1  316.28  5396.7  317.15    5441   318.3
  5462.2  320.09  5477.5  318.45  5483.4  319.11  5488.1  316.16  5491.1  316.16
#Mann= 4 ,-1 , 0
  4764.4     .16       0    4996     .07       0    5002     .16       0
  5136.1     .05       0
Bank Sta=4907.2,5179.2
XS Rating Curve= 0 ,0
Exp/Cntr=0.3,0.1

Type RM Length L Ch R = 1 ,15249   ,258,258,258
BEGIN DESCRIPTION:
Mapping XS d1f8f3f6
END DESCRIPTION:
XS GIS Cut Line= 3
      3784977.14     10518694.69      3784532.72     10518511.37
      3783777.21     10518583.59
#Sta/Elev= 30
  4365.2  332.95  4384.2  332.13  4389.9  331.17  4459.9  329.28  4481.5  327.35
    4514  325.98  4535.6  326.08  4557.2  324.73  4573.6  325.01  4626.8  321.87
  4680.1  320.29  4795.2  314.92  4810.6  314.93  4834.5  312.56  4890.2  309.87
  4929.4  306.01  4969.6  302.29  5077.1  301.88  5079.9  301.38  5083.1  301.88
  5140.4  304.28  5150.4  305.46  5160.5  305.02  5180.6  306.21  5230.8  308.93
    5271  313.76  5278.6  313.92  5351.4  316.62  5481.9  323.65  5604.9  328.08
#Mann= 4 ,-1 , 0
  4365.2     .16       0  5077.1     .07       0  5083.1     .16       0
  5278.6     .05       0
Bank Sta=4929.4,5180.6
XS Rating Curve= 0 ,0
Exp/Cntr=0.3,0.1

Type RM Length L Ch R = 1 ,14991   ,81,81,81
BEGIN DESCRIPTION:
Mapping XS 8f3a7713
END DESCRIPTION:
XS GIS Cut Line= 6
      3784968.46       10518629.      3784504.05     10518385.94
      3784378.18     10518320.84       3784304.4     10518260.08
      3784282.69     10518138.55      3783948.53     10517960.62
#Sta/Elev= 30
  4268.1  331.92  4379.1  327.24    4391  327.74  4406.8  327.01  4413.5  325.81
  4458.7   324.7  4489.4  322.62  4526.4  322.03  4583.4  318.28  4621.9  317.45
    4628  316.17    4666  315.56  4695.7  312.99  4710.1  313.25  4770.7  310.94
  4798.4     309  4808.5  306.43  4814.9  303.71    4831  301.66  5136.1  301.45
  5138.9  300.95  5142.1  301.45  5183.1  302.56  5243.4  305.87  5245.1     306
  5413.5  317.58  5435.4  319.91  5479.4  322.07  5517.6  325.13  5531.6  324.73
#Mann= 4 ,-1 , 0
  4268.1     .16       0  5136.1     .07       0  5142.1     .16       0
  5245.1     .05       0
Bank Sta=4808.5,5243.4
XS Rating Curve= 0 ,0
Exp/Cntr=0.3,0.1

Type RM Length L Ch R = 1 ,14910   ,64,64,64
BEGIN DESCRIPTION:
PENNINGTON BRANCH 22.0
END DESCRIPTION:
XS GIS Cut Line= 6
      3784946.74     10518589.93      3784464.99     10518303.48
      3784373.84     10518264.42      3784334.78     10518160.25
      3784295.72     10518090.81      3783974.57     10517899.85
#Sta/Elev= 30
  4272.5  330.43  4422.5  325.23    4592  316.48  4597.8  317.55  4751.7  309.62
  4781.1  305.54  4804.3  305.49    4816  304.12  4825.7  305.53  4831.3  302.93
  4838.8  302.87  4849.1  305.08  4854.6   303.3  4878.2  305.31  4901.7  305.53
  4907.2  303.93  4937.1  305.75  5010.7  305.03  5016.1  301.87  5022.1  303.88
  5043.4  304.98  5046.5  302.37  5105.7  303.94  5117.6  301.76  5120.3  301.26
  5123.6  301.76  5165.1   304.8  5177.7  305.16  5464.2  323.82  5496.7  324.12
#Mann= 4 ,-1 , 0
  4272.5     .16       0  5117.6     .07       0  5123.6     .16       0
  5177.7     .05       0
Bank Sta=4804.3,5165.1
XS Rating Curve= 0 ,0
Exp/Cntr=0.3,0.1