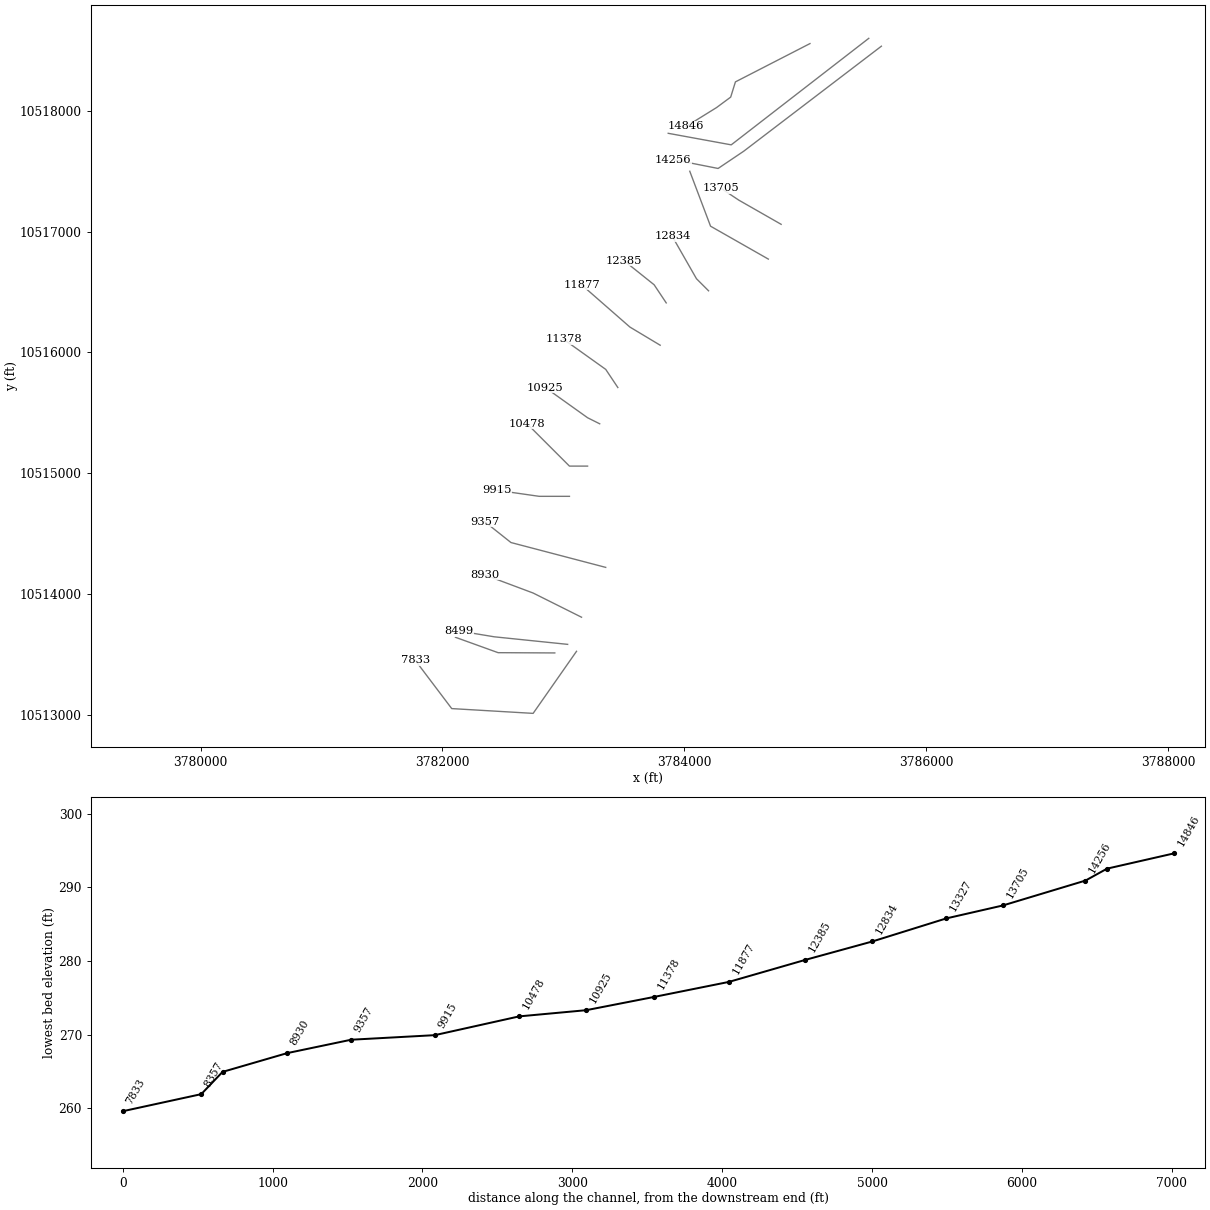
HEC-RAS study PENNINGTON BRANCH.prj: PENNINGTON BRANCH Base Level Engineering

--- PENNINGTON BRANCH.g01 (geometry) --- (continued)

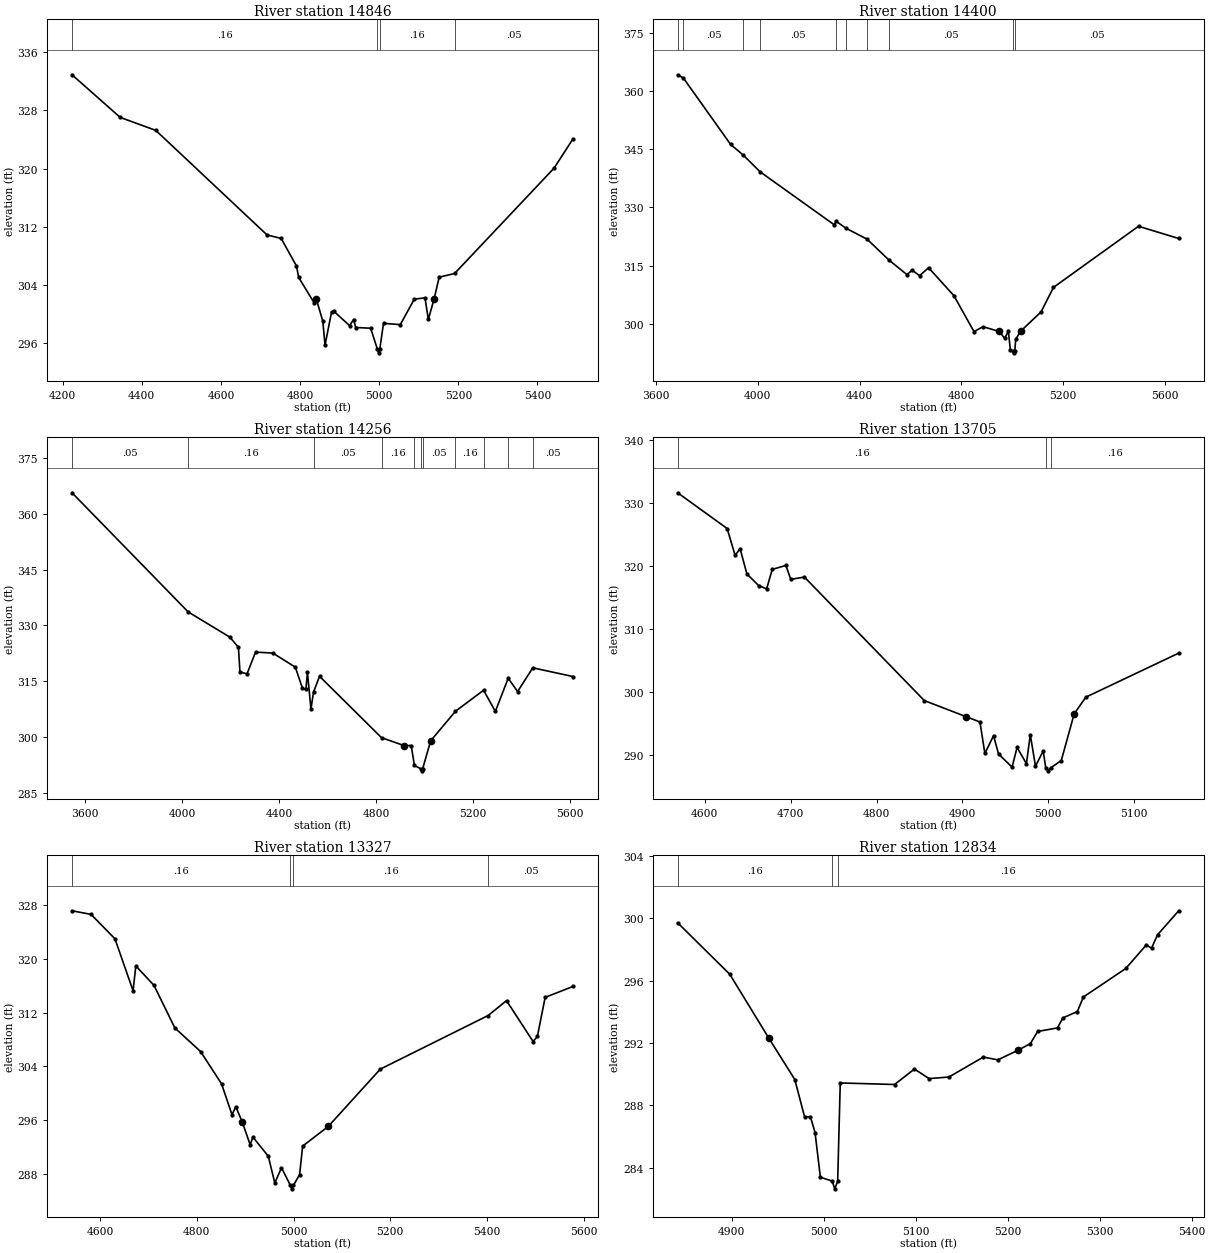
Type RM Length L Ch R = 1 ,14846   ,446,446,446
BEGIN DESCRIPTION:
Mapping XS 7e51ec78
END DESCRIPTION:
XS GIS Cut Line= 5
      3785037.88      10518555.2      3784421.58     10518238.37
      3784382.52     10518112.51      3784265.33      10518025.7
      3784014.08     10517869.75
#Sta/Elev= 30
  4223.7  332.91  4345.4  327.04  4435.4  325.25  4716.5  310.85  4752.2  310.37
    4791  306.57  4796.6  304.99  4835.3  301.52    4841  302.04  4857.5  298.97
  4863.1  295.66  4879.7  300.25  4885.3  300.34  4925.2  298.35  4935.3   299.2
  4940.6   298.1  4978.4     298  4995.5  295.11  4998.3  294.61  5001.5  295.11
  5010.9  298.67  5053.4   298.5  5088.8  302.01  5115.8  302.18  5124.2  299.21
  5138.9  302.06  5151.6  305.03  5190.6  305.54    5442  320.05    5490   324.1
#Mann= 4 ,-1 , 0
  4223.7     .16       0  4995.5     .07       0  5001.5     .16       0
  5190.6     .05       0
Bank Sta=4841,5138.9
XS Rating Curve= 0 ,0
Exp/Cntr=0.3,0.1

Type RM Length L Ch R = 1 ,14400   ,144,144,144
BEGIN DESCRIPTION:
PENNINGTON BRANCH 21.0
END DESCRIPTION:
XS GIS Cut Line= 3
      3785523.99      10518598.6      3784386.86     10517717.54
      3783866.06     10517813.02
#Sta/Elev= 30
  3685.4  364.18  3708.2  363.31  3893.4  346.23  3943.7  343.45  4009.2  339.18
  4299.8  325.56  4308.1  326.43  4346.2  324.65  4429.6  321.82  4514.7  316.48
  4585.9   312.7  4606.7  313.83  4635.7  312.41    4671  314.47  4770.6  307.25
  4849.3  298.01  4884.6  299.28  4948.9  298.04  4969.7  296.25  4984.2  298.09
  4992.4  293.23  5003.6  293.04  5006.3  292.54  5009.6  293.04  5013.2  296.09
    5034  298.19  5112.8  303.09  5161.5   309.4  5495.6  325.15  5653.4     322
#Mann= 10 ,-1 , 0
  3685.4     .16       0  3708.2     .05       0  3943.7     .16       0
  4009.2     .05       0  4308.1     .16       0  4346.2     .05       0
  4429.6     .16       0  4514.7     .05       0  5003.6     .04       0
  5009.6     .05       0
Bank Sta=4948.9,5034
XS Rating Curve= 0 ,0
Exp/Cntr=0.3,0.1

Type RM Length L Ch R = 1 ,14256   ,551,551,551
BEGIN DESCRIPTION:
PENNINGTON BRANCH 20.0
END DESCRIPTION:
XS GIS Cut Line= 4
      3785628.19     10518533.52      3784491.03     10517665.46
      3784278.35     10517522.23       3783905.1     10517596.01
#Sta/Elev= 30
  3545.7  365.66  4024.7  333.65    4197  326.85  4232.3  324.13  4238.6  317.54
  4267.7  316.97    4303  322.83  4374.2  322.58  4467.2  318.78  4496.3  313.15
  4510.8  312.79  4517.1   317.4  4531.6  307.51  4542.3  312.09    4567  316.33
  4822.9  299.83  4916.2   297.7  4945.2  297.72  4958.6  292.37  4986.4  291.42
  4989.1  290.92  4992.4  291.42  5025.4  298.97  5127.9  306.93    5244  312.58
  5292.6  306.89  5345.5  315.81  5384.3  312.23  5447.1  318.61  5613.2  316.26
#Mann= 11 ,-1 , 0
  3545.7     .05       0  4024.7     .16       0  4542.3     .05       0
  4822.9     .16       0  4958.6     .05       0  4986.4     .04       0
  4992.4     .05       0  5127.9     .16       0    5244     .05       0
  5345.5     .08       0  5447.1     .05       0
Bank Sta=4916.2,5025.4
XS Rating Curve= 0 ,0
Exp/Cntr=0.3,0.1

Type RM Length L Ch R = 1 ,13705   ,378,378,378
BEGIN DESCRIPTION:
PENNINGTON BRANCH 19.0
END DESCRIPTION:
XS GIS Cut Line= 3
      3784799.59      10517060.2      3784449.61     10517260.19
      3784299.59      10517360.2
#Sta/Elev= 30
  4568.4  331.67    4626     326  4635.3  321.74  4641.1  322.79    4649   318.8
  4662.7  316.94    4672  316.42  4678.5  319.51  4694.4  320.14  4700.1  317.93
    4716  318.29  4855.6  298.69  4904.6  296.12  4920.4  295.29  4926.1   290.3
  4936.2  293.12    4942  290.22  4957.8  288.12  4963.6  291.26  4974.5  288.68
    4979   293.3    4985  288.28    4994  290.68    4997  288.04  4999.8  287.54
    5003  288.04  5015.1  289.18  5030.1  296.58  5043.6  299.23  5151.8  306.22
#Mann= 3 ,-1 , 0
  4568.4     .16       0    4997     .07       0    5003     .16       0
Bank Sta=4904.6,5030.1
XS Rating Curve= 0 ,0
Exp/Cntr=0.3,0.1

Type RM Length L Ch R = 1 ,13327   ,493,493,493
BEGIN DESCRIPTION:
PENNINGTON BRANCH 18.0
END DESCRIPTION:
XS GIS Cut Line= 3
      3784693.81      10516772.5      3784216.05      10517044.7
      3784044.21     10517499.25
#Sta/Elev= 30
  4542.1  327.17  4581.5  326.63  4630.8     323  4668.3  315.27    4674  318.96
  4711.5  316.07  4754.7  309.73    4808  306.21  4851.2  301.41  4872.8  296.82
  4880.7     298  4894.4  295.66  4910.3  292.35  4916.1  293.48  4947.8  290.64
  4961.3  286.65  4975.1  288.92  4993.7  286.28  4996.5  285.78  4999.7  286.28
  5012.6  287.91  5018.8  292.14  5071.7  295.06  5179.4   303.6  5402.3  311.58
  5440.3  313.79  5495.3  307.71  5504.1  308.46  5520.2  314.28  5577.9  315.91
#Mann= 4 ,-1 , 0
  4542.1     .16       0  4993.7     .07       0  4999.7     .16       0
  5402.3     .05       0
Bank Sta=4894.4,5071.7
XS Rating Curve= 0 ,0
Exp/Cntr=0.3,0.1

Type RM Length L Ch R = 1 ,12834   ,449,449,449
BEGIN DESCRIPTION:
PENNINGTON BRANCH 17.0
END DESCRIPTION:
XS GIS Cut Line= 3
      3784199.61     10516510.19      3784099.61     10516610.19
      3783899.63     10516960.16
#Sta/Elev= 30
  4841.4  299.71    4898  296.41  4940.4  292.32  4968.7  289.66  4979.3  287.27
  4985.7  287.27  4990.7  286.26  4996.5  283.39  5009.3  283.15  5012.1  282.65
  5015.3  283.15  5018.1  289.44  5077.1  289.34  5098.7  290.33  5114.6  289.72
  5136.2  289.82  5173.6   291.1  5189.4  290.92    5211  291.53  5224.7  291.96
  5232.6  292.74  5254.2  292.97    5260  293.61  5275.8  294.02  5282.3  294.95
  5328.4  296.78  5350.7  298.29  5356.4  298.08  5362.9  298.94  5385.9  300.48
#Mann= 3 ,-1 , 0
  4841.4     .16       0  5009.3     .07       0  5015.3     .16       0
Bank Sta=4940.4,5211
XS Rating Curve= 0 ,0
Exp/Cntr=0.3,0.1

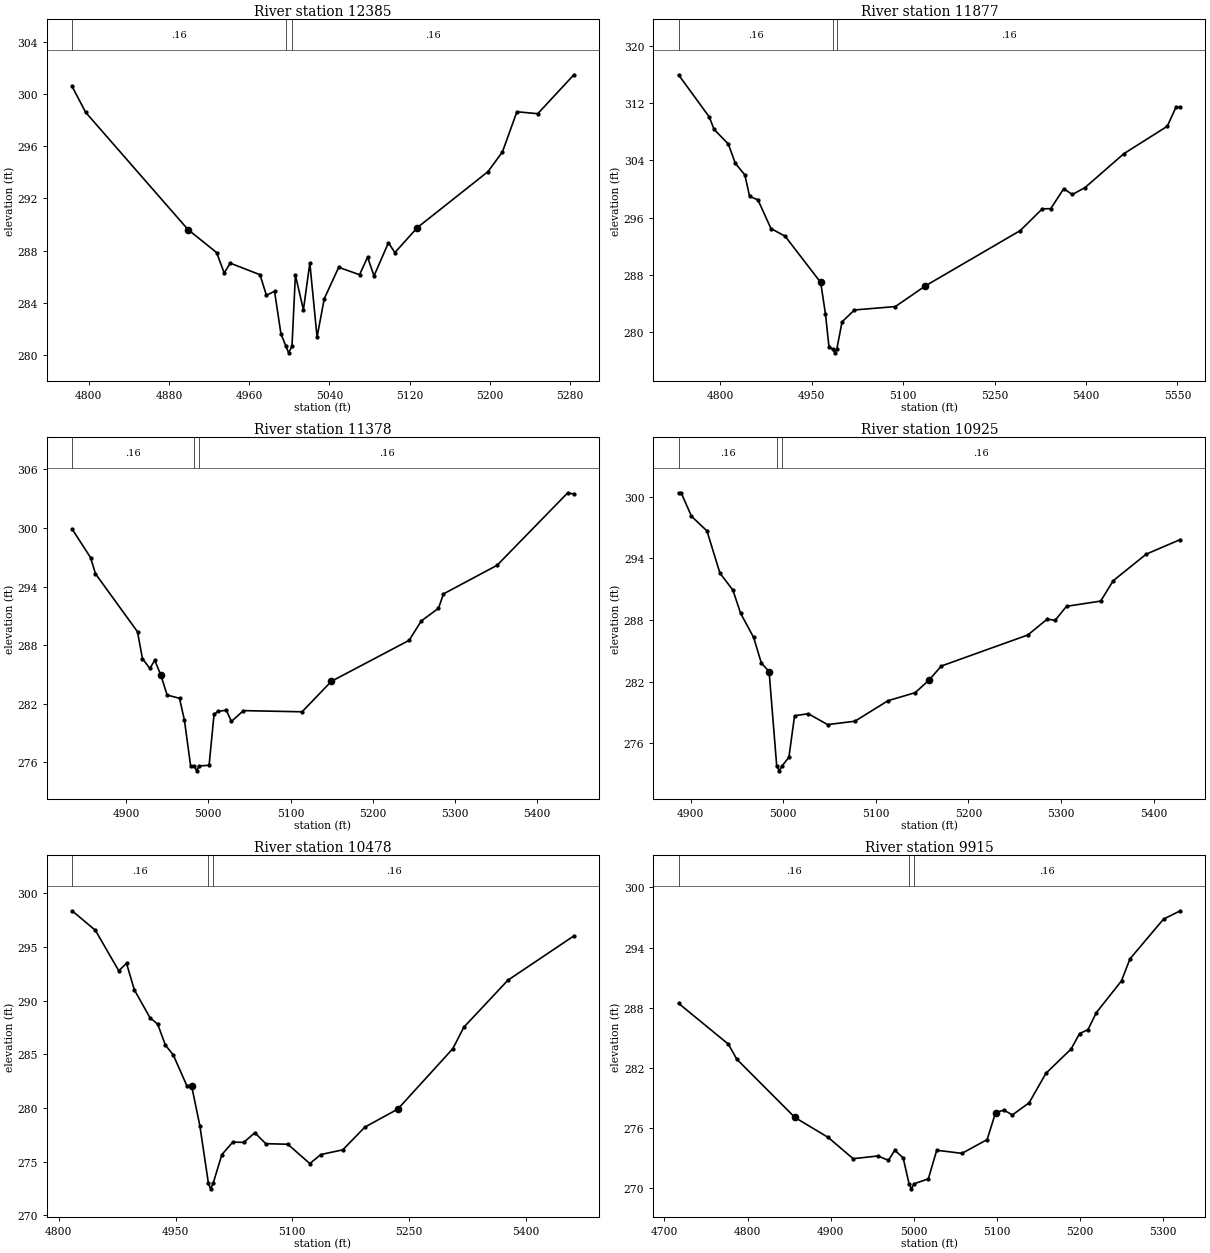
Type RM Length L Ch R = 1 ,12385   ,508,508,508
BEGIN DESCRIPTION:
PENNINGTON BRANCH 16.0
END DESCRIPTION:
XS GIS Cut Line= 3
      3783849.59     10516410.22      3783749.61     10516560.19
      3783499.61     10516760.19
#Sta/Elev= 30
  4783.4  300.61  4796.9  298.62    4899  289.61  4927.6  287.84  4935.1  286.27
  4941.1  287.03  4970.8  286.14  4977.2  284.56  4985.3  284.87  4991.7   281.6
  4996.7  280.64  4999.4  280.14  5002.7  280.64  5006.1  286.11  5014.1  283.44
  5020.5  287.04  5027.7  281.35  5034.9   284.3  5049.3  286.71  5070.1  286.14
  5078.1  287.49  5084.5  286.05  5098.9   288.6  5105.3  287.84  5127.7  289.76
  5198.2  294.06  5212.6  295.58    5227  298.66  5247.8  298.51  5283.8   301.5
#Mann= 3 ,-1 , 0
  4783.4     .16       0  4996.7     .07       0  5002.7     .16       0
Bank Sta=4899,5127.7
XS Rating Curve= 0 ,0
Exp/Cntr=0.3,0.1

Type RM Length L Ch R = 1 ,11877   ,499,499,499
BEGIN DESCRIPTION:
PENNINGTON BRANCH 15.0
END DESCRIPTION:
XS GIS Cut Line= 3
      3783799.61     10516060.19      3783549.61     10516210.19
      3783149.58     10516560.21
#Sta/Elev= 30
  4731.7  315.93  4782.2  310.04    4790  308.31  4813.3  306.29    4825  303.56
  4840.5  301.97  4848.3  298.96  4861.9   298.5  4883.3  294.49  4906.6  293.42
  4964.9  286.97  4972.7  282.58  4978.5  277.97  4985.3  277.66    4988  277.16
  4991.3  277.66  4999.9  281.48  5020.3  283.14  5087.3  283.61  5136.7   286.5
  5292.3  294.21  5328.4  297.24  5342.2  297.26  5363.5  300.04  5377.7  299.24
  5398.6  300.21  5462.2  304.93  5533.4  308.75  5547.6   311.4  5554.8  311.43
#Mann= 3 ,-1 , 0
  4731.7     .16       0  4985.3     .07       0  4991.3     .16       0
Bank Sta=4964.9,5136.7
XS Rating Curve= 0 ,0
Exp/Cntr=0.3,0.1

Type RM Length L Ch R = 1 ,11378   ,453,453,453
BEGIN DESCRIPTION:
PENNINGTON BRANCH 14.0
END DESCRIPTION:
XS GIS Cut Line= 3
      3783449.59     10515710.22      3783349.61     10515860.19
      3782999.58     10516110.21
#Sta/Elev= 30
  4834.2   299.9  4856.7  296.97  4862.7  295.31  4913.8  289.37  4919.8  286.62
  4928.8  285.61  4934.8  286.45  4942.3   284.9  4949.8  282.89  4964.9  282.55
  4970.9   280.3  4978.4  275.63  4982.9  275.62  4985.7  275.12  4988.9  275.62
  5000.9  275.69  5006.9   280.9  5011.4   281.2  5021.8  281.34    5028  280.18
  5042.7  281.29    5114  281.17  5149.6  284.29  5244.2  288.49    5259  290.48
  5279.9  291.77    5286  293.25  5351.2  296.18  5437.2  303.61  5444.6  303.47
#Mann= 3 ,-1 , 0
  4834.2     .16       0  4982.9     .07       0  4988.9     .16       0
Bank Sta=4942.3,5149.6
XS Rating Curve= 0 ,0
Exp/Cntr=0.3,0.1

Type RM Length L Ch R = 1 ,10925   ,447,447,447
BEGIN DESCRIPTION:
PENNINGTON BRANCH 13.0
END DESCRIPTION:
XS GIS Cut Line= 3
      3783299.61     10515410.19      3783199.61     10515460.19
      3782849.62     10515710.18
#Sta/Elev= 30
    4887  300.38  4889.8  300.38    4901  298.09  4917.7  296.67  4931.7  292.56
  4945.7  290.91  4954.1  288.64  4968.1   286.3  4976.4  283.82  4984.8  282.98
    4993  273.82  4995.8  273.32    4999  273.82  5006.2  274.64  5012.3  278.68
  5027.1  278.88    5048  277.82  5077.5  278.15  5113.1  280.14  5142.6  280.93
  5157.3  282.13  5170.8  283.52  5264.2  286.54  5285.1  288.08  5293.7  287.97
    5306  289.33  5342.9  289.84  5356.4  291.82  5392.1  294.41  5428.9  295.83
#Mann= 3 ,-1 , 0
    4887     .16       0    4993     .07       0    4999     .16       0
Bank Sta=4984.8,5157.3
XS Rating Curve= 0 ,0
Exp/Cntr=0.3,0.1

Type RM Length L Ch R = 1 ,10478   ,563,563,563
BEGIN DESCRIPTION:
PENNINGTON BRANCH 12.0
END DESCRIPTION:
XS GIS Cut Line= 3
      3783199.64     10515060.19      3783049.61     10515060.19
      3782699.61     10515410.19
#Sta/Elev= 30
    4817  298.35    4847  296.53    4877  292.77    4887  293.46    4897     291
    4917  288.42    4927   287.8    4937  285.85    4947  284.95  4964.5  282.08
  4970.6  282.08  4981.2  278.37  4992.3  272.98  4995.1  272.48  4998.3  272.98
  5009.5  275.66  5023.6  276.83  5037.7   276.8  5051.9   277.7    5066  276.68
  5094.3  276.63  5122.6  274.83  5136.7  275.67    5165  276.11  5193.3  278.22
  5235.7   279.9  5306.4  285.52  5320.6  287.52  5377.2  291.89    5462  296.01
#Mann= 3 ,-1 , 0
    4817     .16       0  4992.3     .07       0  4998.3     .16       0
Bank Sta=4970.6,5235.7
XS Rating Curve= 0 ,0
Exp/Cntr=0.3,0.1

Type RM Length L Ch R = 1 ,9915    ,558,558,558
BEGIN DESCRIPTION:
PENNINGTON BRANCH 11.0
END DESCRIPTION:
XS GIS Cut Line= 3
      3783049.63     10514810.19      3782799.61     10514810.19
      3782449.58     10514860.19
#Sta/Elev= 30
    4717  288.44    4777  284.36    4787  282.87    4857  277.05    4897  275.06
    4927  272.94    4957  273.21  4969.5  272.77  4977.1  273.78  4987.2  273.02
  4994.3  270.43  4997.1  269.93  5000.3  270.43  5017.5  270.93  5027.6  273.78
  5057.9  273.47  5088.2  274.84  5098.3  277.52  5108.4  277.79  5118.5   277.3
  5138.7  278.51  5158.9  281.45  5189.3  283.89  5199.4  285.42  5209.5  285.81
  5219.6  287.51  5249.9  290.69    5260  292.87  5300.4  296.84  5320.6  297.67
#Mann= 3 ,-1 , 0
    4717     .16       0  4994.3     .07       0  5000.3     .16       0
Bank Sta=4857,5098.3
XS Rating Curve= 0 ,0
Exp/Cntr=0.3,0.1

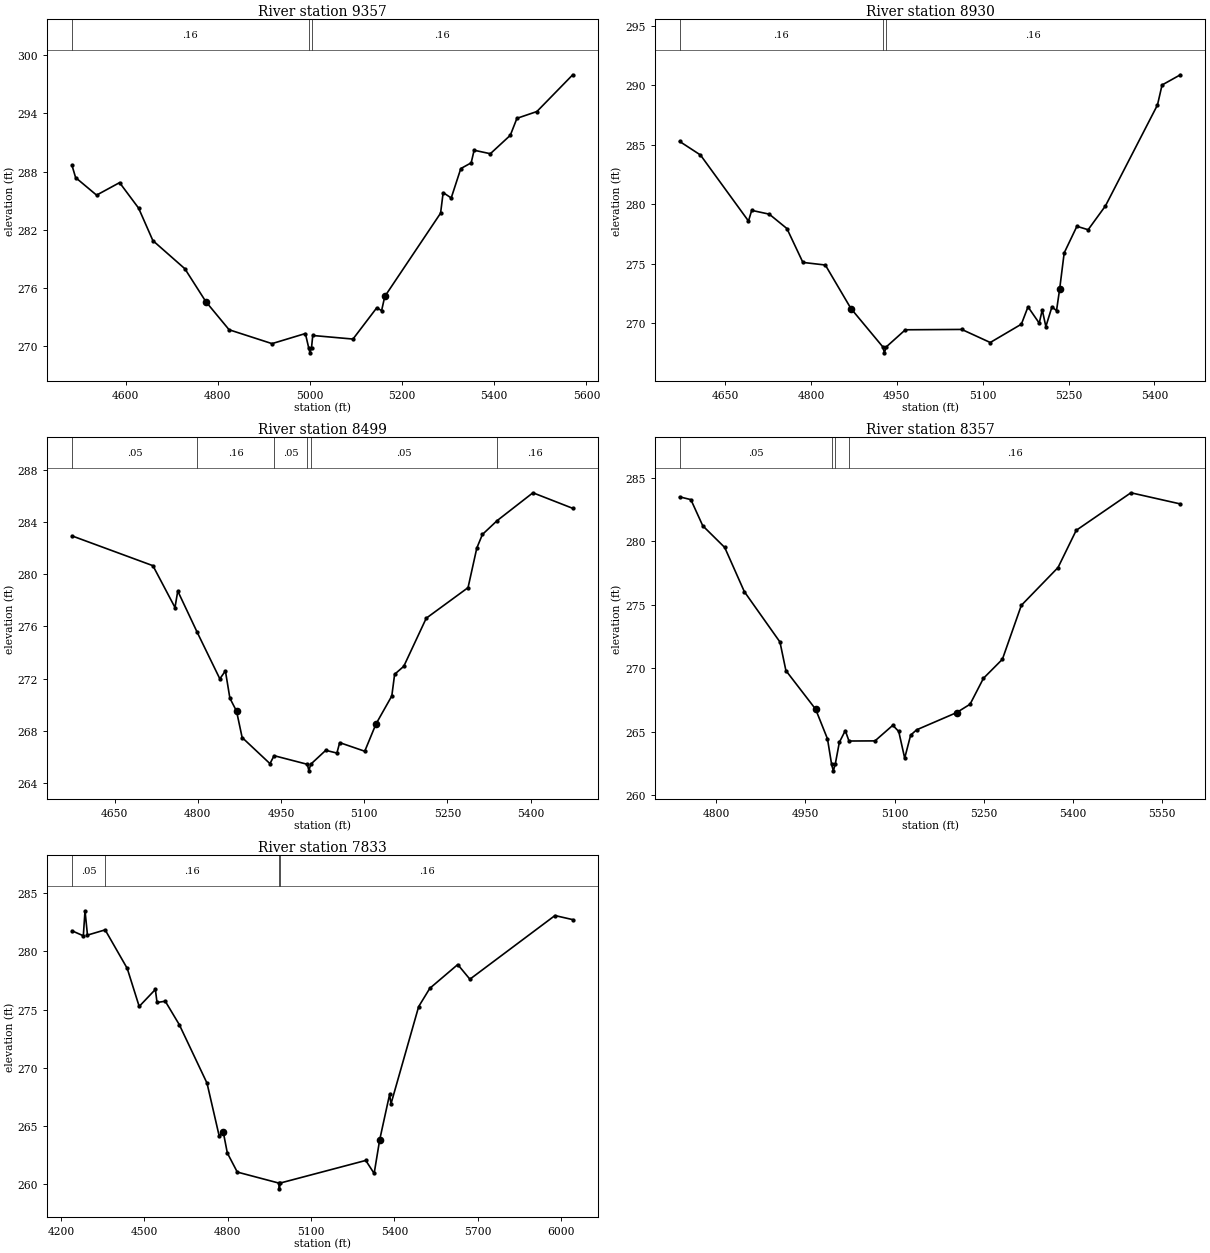
Type RM Length L Ch R = 1 ,9357    ,427,427,427
BEGIN DESCRIPTION:
PENNINGTON BRANCH 10.0
END DESCRIPTION:
XS GIS Cut Line= 3
      3783349.39     10514222.48      3782566.05     10514428.04
      3782349.41     10514600.24
#Sta/Elev= 30
  4483.6  288.63  4491.4  287.38  4536.9  285.57  4586.8  286.86  4628.1  284.23
  4659.1  280.88  4728.5  277.98    4774  274.59  4824.5  271.69  4917.6  270.26
    4990   271.3  4997.3  269.81    5000  269.31  5003.3  269.81    5006   271.1
  5093.3  270.73    5145  273.96  5155.4  273.66  5162.3  275.12  5283.4  283.71
    5289  285.83  5306.5  285.28  5327.3  288.31  5349.8   288.9  5356.2   290.2
  5391.4  289.84  5434.7  291.74  5449.1  293.49  5492.4  294.19  5570.2  297.98
#Mann= 3 ,-1 , 0
  4483.6     .16       0  4997.3     .07       0  5003.3     .16       0
Bank Sta=4774,5162.3
XS Rating Curve= 0 ,0
Exp/Cntr=0.3,0.1

Type RM Length L Ch R = 1 ,8930    ,431,431,431
BEGIN DESCRIPTION:
PENNINGTON BRANCH 9.0
END DESCRIPTION:
XS GIS Cut Line= 3
      3783149.61     10513810.19      3782749.61     10514010.19
      3782349.62     10514160.18
#Sta/Elev= 30
  4570.8  285.28  4607.1  284.14    4691  278.58  4696.6  279.48  4727.3  279.16
  4758.1  277.95    4786   275.1  4825.2  274.88  4869.9  271.22  4925.6  267.99
  4928.3  267.49  4931.6  267.99  4964.9  269.43  5063.4  269.46  5113.2  268.36
  5167.5   269.9  5179.1  271.36  5198.7  269.99    5204   271.1  5210.3   269.7
  5220.9  271.36  5228.9  271.04  5234.3  272.83  5242.3   275.9  5264.5  278.14
  5284.1  277.85  5314.4  279.86  5405.2  288.35  5413.2  290.03  5445.2  290.89
#Mann= 3 ,-1 , 0
  4570.8     .16       0  4925.6     .07       0  4931.6     .16       0
Bank Sta=4869.9,5234.3
XS Rating Curve= 0 ,0
Exp/Cntr=0.3,0.1

Type RM Length L Ch R = 1 ,8499    ,142,142,142
BEGIN DESCRIPTION:
PENNINGTON BRANCH 8.0
END DESCRIPTION:
XS GIS Cut Line= 3
      3783034.77     10513585.68      3782428.55     10513648.18
      3782138.93      10513696.1
#Sta/Elev= 30
  4573.1  282.92    4719  280.64  4758.8  277.44  4763.8   278.7    4799  275.53
  4839.7  271.98  4849.7  272.59  4857.8   270.5  4869.8  269.51  4879.9  267.49
  4930.1  265.49  4937.5   266.1  4997.5  265.44  5000.3  264.94  5003.5  265.44
  5030.7  266.51  5050.8   266.3  5055.8   267.1    5101  266.44  5121.2  268.52
  5149.8  270.67  5154.9  272.33  5171.4  272.94  5211.9  276.62  5287.3  278.96
  5303.1  281.99  5313.2  283.03  5339.8  284.09  5404.3  286.22  5476.1  285.03
#Mann= 6 ,-1 , 0
  4573.1     .05       0    4799     .16       0  4937.5     .05       0
  4997.5     .04       0  5003.5     .05       0  5339.8     .16       0
Bank Sta=4869.8,5121.2
XS Rating Curve= 0 ,0
Exp/Cntr=0.3,0.1

Type RM Length L Ch R = 1 ,8357    ,524,524,524
BEGIN DESCRIPTION:
Mapping XS bda36d46
END DESCRIPTION:
XS GIS Cut Line= 3
      3782928.55     10513514.84       3782459.8     10513516.93
      3782107.69     10513644.02
#Sta/Elev= 30
  4738.2  283.51  4757.1  283.29  4777.1  281.23  4814.1  279.52  4847.1  276.04
  4907.1  272.07  4917.1  269.82  4967.1  266.78  4987.1  264.44  4994.1  262.42
  4996.9  261.92  5000.1  262.42  5007.1  264.17  5017.1  265.09  5023.3  264.27
  5067.1  264.28  5097.1  265.51  5107.1  265.02  5117.1  262.92  5127.1  264.73
  5137.1  265.15  5204.6  266.51  5227.2  267.17  5249.7  269.21  5281.6  270.71
  5313.5  274.96  5375.3  277.94  5405.9  280.87    5498  283.83  5581.3  282.95
#Mann= 4 ,-1 , 0
  4738.2     .05       0  4994.1     .04       0  5000.1     .05       0
  5023.3     .16       0
Bank Sta=4967.1,5204.6
XS Rating Curve= 0 ,0
Exp/Cntr=0.3,0.1

Type RM Length L Ch R = 1 ,7833    ,1132,1132,1132
BEGIN DESCRIPTION:
PENNINGTON BRANCH 7.0
END DESCRIPTION:
XS GIS Cut Line= 4
      3783108.11     10513528.34      3782749.39     10513014.84
      3782076.47     10513054.43      3781774.52     10513454.25
#Sta/Elev= 30
  4239.8  281.77  4280.5  281.34  4286.6  283.49  4295.4   281.4    4359  281.85
  4438.4  278.54  4481.5  275.27  4539.6  276.73  4545.7  275.61  4575.3  275.72
  4625.9   273.7  4725.5  268.68    4769  264.17  4783.8   264.5  4798.6  262.68
  4834.4  261.04  4983.2   260.1  4985.9   259.6  4989.2   260.1  5296.7  262.04
  5326.8  260.92  5346.8  263.82  5382.4  267.71  5387.4   266.9    5487  275.26
  5527.1  276.83  5627.6  278.87  5671.3  277.61  5977.3  283.08  6041.3  282.73
#Mann= 4 ,-1 , 0
  4239.8     .05       0    4359     .16       0  4983.2     .07       0
  4989.2     .16       0
Bank Sta=4783.8,5346.8
XS Rating Curve= 0 ,0
Exp/Cntr=0.3,0.1

Chan Stop Cuts=-1
Use User Specified Reach Order=0
Composite Channel Slope=5