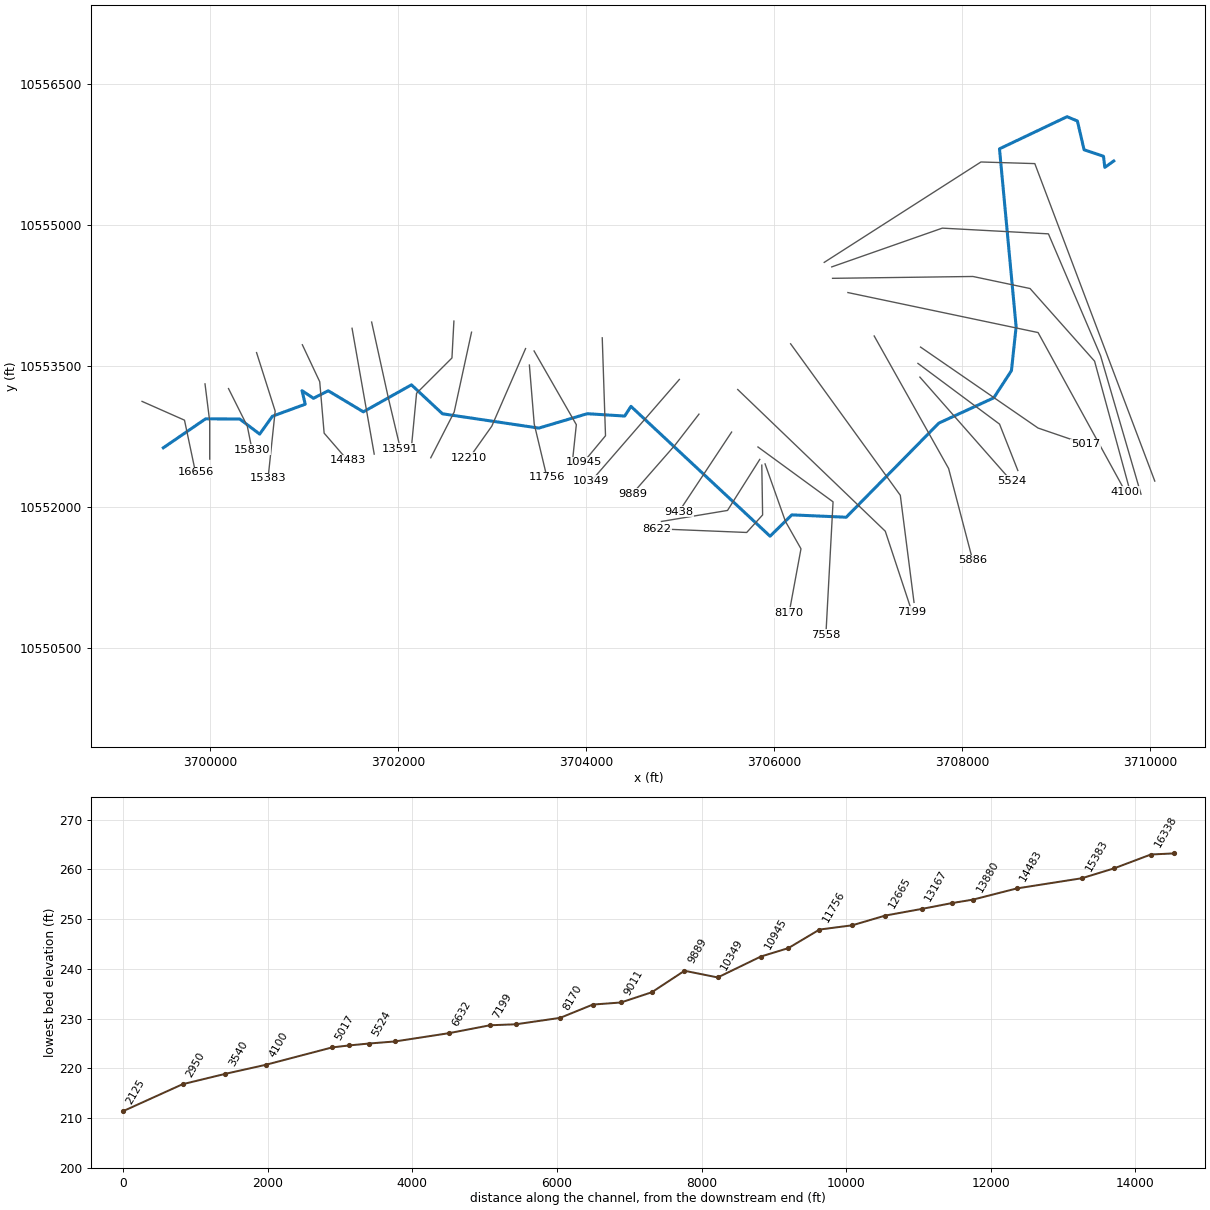
--- RINGGOLD CREEK.prj (project) ---

Proj Title=RINGGOLD CREEK Base Level Engineering
Current Plan=p01
Default Exp/Contr=0.3,0.1
English Units
Geom File=g01
Flow File=f01
Plan File=p01
Y Axis Title=Elevation
X Axis Title(PF)=Main Channel Distance
X Axis Title(XS)=Station
BEGIN DESCRIPTION:
RINGGOLD CREEK
END DESCRIPTION:
DSS File=dss
DSS Export Rating Curves= 0
DSS Export Rating Curve Sorted= 0
DSS Export Volume Flow Curves= 0
DXF OffsetX= 0
DXF OffsetY= 0
DXF ScaleX= 1
DXF ScaleY= 10

--- RINGGOLD CREEK.p01 (plan) ---

Plan Title=Multiple Run
Short Identifier=Multiple
Geom File=g01
Flow File=f01
Subcritical Flow
K Sum by GR= 0
Std Step Tol= 0.01
Critical Tol= 0.01
Num of Std Step Trials= 20
Max Error Tol= 0.3
Flow Tol Ratio= 0.001
Split Flow NTrial= 30
Split Flow Tol= 0.02
Split Flow Ratio= 0.02
Log Output Level= 0
Friction Slope Method= 1
Unsteady Friction Slope Method= 2
Unsteady Bridges Friction Slope Method= 1
Parabolic Critical Depth
Global Vel Dist=  1 , 1 , 1
Global Log Level= 0
CheckData=True
Encroach Param= -1, 0, 0, 0
BEGIN DESCRIPTION:
Multiple Run
END DESCRIPTION:

--- RINGGOLD CREEK.f01 (steady flow) ---

Flow Title=Multiple
Program Version=4.10
Number of Profiles= 7
Profile Names=10-year,25-year,50-year,1pct_min,100-year,1pct_plu,500-year
River Rch & RM=RINGGOLD CREEK,Reach-1         ,16656
     793    1091    1341    1210    1636    2212    2445
River Rch & RM=RINGGOLD CREEK,Reach-1         ,8170
    1296    1822    2271    2073    2803    3791    4295
Boundary for River Rch & Prof#=RINGGOLD CREEK,Reach-1         , 1
Up Type= 0
Dn Type= 1
Dn Known WS=215.5
Boundary for River Rch & Prof#=RINGGOLD CREEK,Reach-1         , 2
Up Type= 0
Dn Type= 1
Dn Known WS=216.55
Boundary for River Rch & Prof#=RINGGOLD CREEK,Reach-1         , 3
Up Type= 0
Dn Type= 1
Dn Known WS=217.26
Boundary for River Rch & Prof#=RINGGOLD CREEK,Reach-1         , 4
Up Type= 0
Dn Type= 1
Dn Known WS=217.02
Boundary for River Rch & Prof#=RINGGOLD CREEK,Reach-1         , 5
Up Type= 0
Dn Type= 1
Dn Known WS=217.98
Boundary for River Rch & Prof#=RINGGOLD CREEK,Reach-1         , 6
Up Type= 0
Dn Type= 1
Dn Known WS=219.04
Boundary for River Rch & Prof#=RINGGOLD CREEK,Reach-1         , 7
Up Type= 0
Dn Type= 1
Dn Known WS=219.59
DSS Import GetInterval= 0
DSS Import GetPeak= 0
DSS Import FillOption= 0

--- RINGGOLD CREEK.g01 (geometry) ---

Geom Title=Existing Conditions
Program Version=4.10

River Reach=RINGGOLD CREEK  ,Reach-1
Reach XY= 30
      3699506.29      10552630.4        3699955.       10552938.
      3700318.25       10552937.        3700531.       10552776.
      3700666.25       10552966.       3701015.5       10553094.
      3700981.25       10553238.      3701103.26     10553157.01
        3701260.       10553237.      3701633.75       10553013.
        3702145.       10553300.      3702475.25       10552992.
      3703499.75       10552840.      3704015.25       10552993.
      3704413.25       10552968.      3704479.75       10553071.
       3705959.5       10551690.      3706190.75       10551917.
       3706769.5       10551892.       3707754.5       10552893.
        3708339.       10553162.      3708526.75       10553451.
       3708576.4     10553917.62      3708399.61     10555810.19
      3709118.25       10556152.      3709228.15     10556106.11
      3709299.15     10555800.41      3709505.75     10555730.97
      3709519.64     10555612.91        3709615.       10555681.

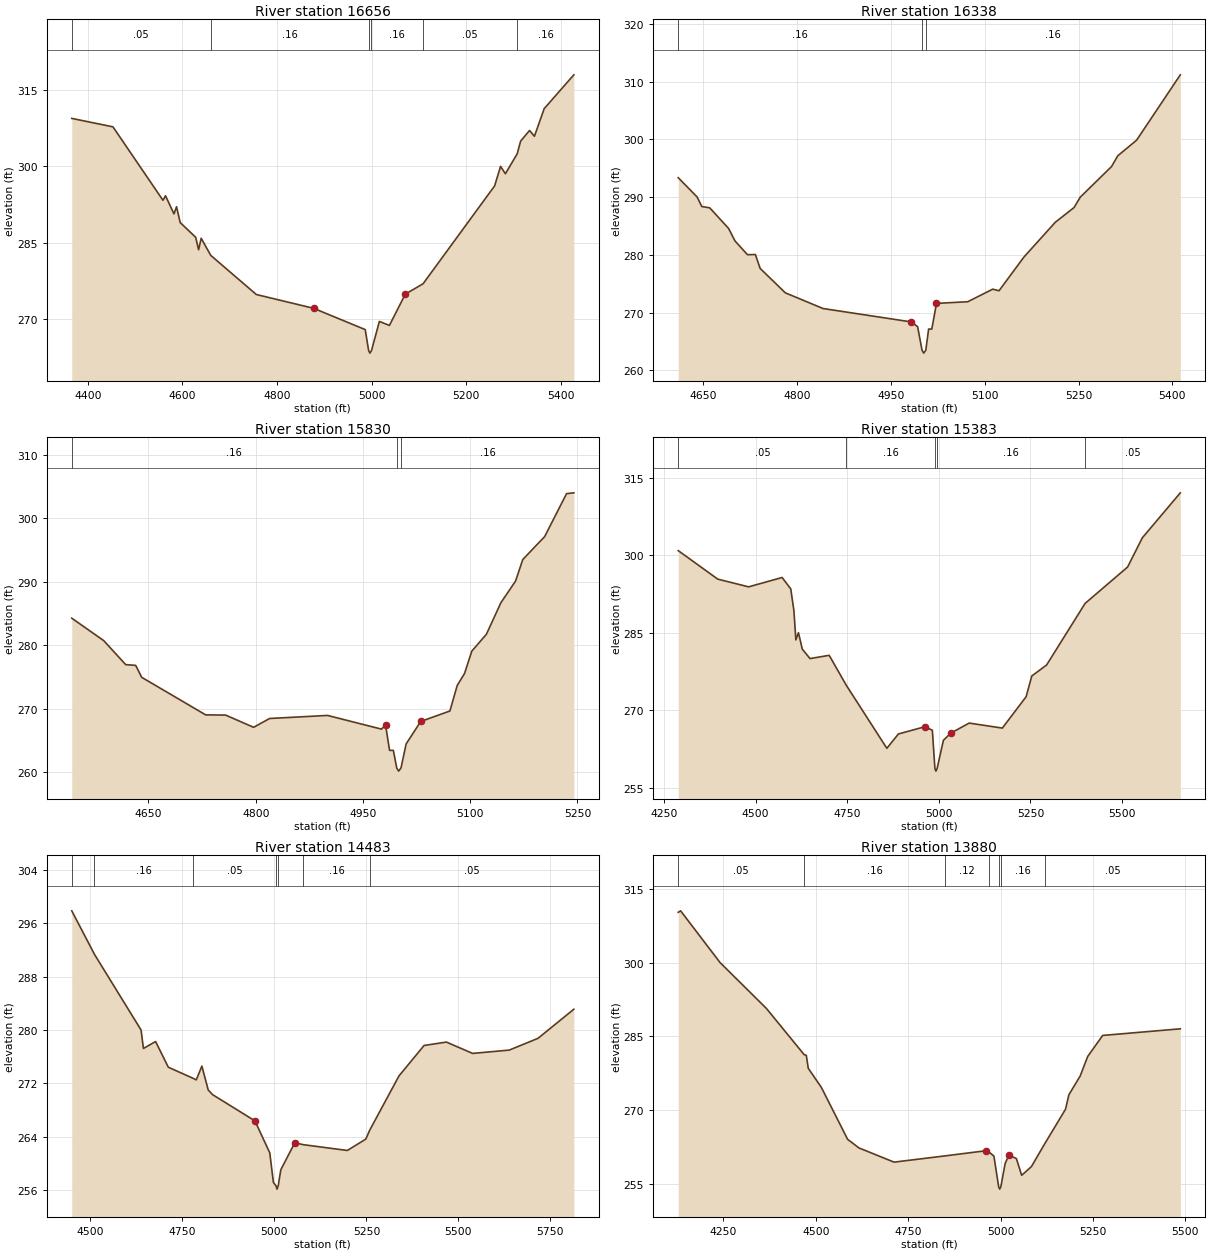
Type RM Length L Ch R = 1 ,16656   ,318,318,318
BEGIN DESCRIPTION:
RINGGOLD CREEK 27.0
END DESCRIPTION:
XS GIS Cut Line= 3
      3699279.98      10553123.9      3699731.37     10552924.24
      3699848.56     10552368.64
#Sta/Elev= 30
    4366  309.48  4453.1  307.81  4558.8  293.33  4564.2  294.22  4582.1  290.65
  4587.5  292.06  4595.2  288.94    4628  286.03  4634.1  283.57  4639.6  285.84
  4659.9  282.46  4756.1  274.75  4877.2  272.03  4986.4  267.83  4993.6  263.69
  4996.3  263.19  4999.6  263.69  5016.3  269.44  5037.5  268.65  5071.2  274.83
  5108.6  276.86    5260  296.18  5272.5  300.02  5282.7  298.56  5307.5  302.47
  5314.9     305  5333.8   307.1  5344.1  305.95  5364.7   311.4  5427.4  318.07
#Mann= 6 ,-1 , 0
    4366     .05       0  4659.9     .16       0  4993.6     .07       0
  4999.6     .16       0  5108.6     .05       0  5307.5     .16       0
Bank Sta=4877.2,5071.2
XS Rating Curve= 0 ,0
Exp/Cntr=0.3,0.1

Type RM Length L Ch R = 1 ,16338   ,508,508,508
BEGIN DESCRIPTION:
RINGGOLD CREEK 26.0
END DESCRIPTION:
XS GIS Cut Line= 3
      3699949.62     10553310.14      3699999.61     10552910.19
      3699999.61     10552510.15
#Sta/Elev= 30
  4609.6  293.38  4639.8  290.04  4647.3  288.38  4659.9  288.16  4690.2  284.58
  4700.3  282.43  4720.4  280.03    4733  280.06  4740.6  277.66  4780.9  273.42
  4841.3   270.7  4982.4  268.38  4992.5  267.56  4999.6  263.47  5002.3  262.97
  5005.6  263.47  5010.1  267.14  5015.2  267.14  5022.7  271.59  5072.7  271.88
  5112.7  274.06  5122.7  273.78  5162.7  279.64  5212.7  285.65  5242.7   288.2
  5252.7  290.01  5302.7  295.31  5312.7  297.18  5342.7  299.87  5412.7  311.21
#Mann= 3 ,-1 , 0
  4609.6     .16       0  4999.6     .07       0  5005.6     .16       0
Bank Sta=4982.4,5022.7
XS Rating Curve= 0 ,0
Exp/Cntr=0.3,0.1

Type RM Length L Ch R = 1 ,15830   ,447,447,447
BEGIN DESCRIPTION:
RINGGOLD CREEK 25.0
END DESCRIPTION:
XS GIS Cut Line= 3
      3700199.62     10553260.16      3700399.61     10552860.19
       3700449.6     10552610.22
#Sta/Elev= 30
  4542.8  284.27  4587.5  280.74  4618.2  276.96  4632.2  276.84  4640.6  274.96
    4730  269.05    4758  269.01  4797.1  267.09  4819.5  268.48  4900.5  268.96
    4976   266.8  4981.6  267.46  4987.2  263.46  4992.5  263.46  4997.2  260.69
  4999.9  260.19  5003.2  260.69  5010.4  264.48  5030.8  268.01  5071.6  269.66
  5081.8  273.68    5092  275.55  5102.2  279.08  5122.6  281.74    5143  286.73
  5163.4  290.11  5173.5  293.51  5204.1  297.12  5234.7  303.88  5244.9  304.01
#Mann= 3 ,-1 , 0
  4542.8     .16       0  4997.2     .07       0  5003.2     .16       0
Bank Sta=4981.6,5030.8
XS Rating Curve= 0 ,0
Exp/Cntr=0.3,0.1

Type RM Length L Ch R = 1 ,15383   ,900,900,900
BEGIN DESCRIPTION:
RINGGOLD CREEK 24.0
END DESCRIPTION:
XS GIS Cut Line= 3
      3700497.87     10553642.95      3700695.78      10553020.6
      3700620.25     10552307.04
#Sta/Elev= 30
  4288.7  300.93  4396.5  295.41  4480.8  293.91  4572.3  295.72  4595.9  293.51
  4604.5  289.28  4609.8  283.63  4616.9  285.02  4627.4  281.84  4648.4  280.01
  4700.8  280.64  4747.8   274.8  4858.2  262.62  4889.7   265.4  4962.3  266.81
  4982.4  266.12  4989.4   258.7  4992.2   258.2  4995.4   258.7  5012.6  264.18
  5032.7  265.56    5083  267.51  5173.5  266.54  5238.4  272.62  5253.9  276.64
  5294.1  278.75  5399.4   290.7  5515.4  297.75  5555.6  303.41  5659.3  312.13
#Mann= 5 ,-1 , 0
  4288.7     .05       0  4747.8     .16       0  4989.4     .07       0
  4995.4     .16       0  5399.4     .05       0
Bank Sta=4962.3,5032.7
XS Rating Curve= 0 ,0
Exp/Cntr=0.3,0.1

Type RM Length L Ch R = 1 ,14483   ,603,603,603
BEGIN DESCRIPTION:
RINGGOLD CREEK 23.0
END DESCRIPTION:
XS GIS Cut Line= 4
      3700984.82     10553726.37      3701169.74      10553333.1
      3701216.61     10552786.22      3701465.61     10552498.32
#Sta/Elev= 30
  4449.5   297.9  4511.2  291.37  4637.8  280.02  4644.2  277.25  4677.3  278.29
  4711.8  274.44  4779.7  272.76  4787.8  272.54    4803  274.61  4820.2  271.03
    4832  270.33  4947.2  266.39  4987.4   261.6  4997.4  257.15  5004.4  256.65
  5007.2  256.15  5010.4  256.65  5017.5  259.06  5055.4   263.1  5078.4  262.82
  5198.1  261.95  5248.3  263.65  5259.1     265  5338.6  273.14  5406.7   277.7
  5467.4  278.21  5538.5  276.51  5638.3  277.01  5716.2  278.77  5813.6  283.14
#Mann= 7 ,-1 , 0
  4449.5     .05       0  4511.2     .16       0  4779.7     .05       0
  5004.4     .03       0  5010.4     .05       0  5078.4     .16       0
  5259.1     .05       0
Bank Sta=4947.2,5055.4
XS Rating Curve= 0 ,0
Exp/Cntr=0.3,0.1

Type RM Length L Ch R = 1 ,13880   ,289,289,289
BEGIN DESCRIPTION:
RINGGOLD CREEK 22.0
END DESCRIPTION:
XS GIS Cut Line= 2
      3701513.49     10553901.66      3701749.27     10552563.27
#Sta/Elev= 30
  4127.6  310.22  4134.1  310.52  4240.8     300  4366.2  290.67  4468.3  281.28
  4474.3  281.11  4479.6  278.48  4514.9  274.62    4586  264.05  4616.5   262.3
  4711.7   259.4  4849.7  260.67  4961.7  261.73  4968.6  261.46    4982  260.65
  4994.9  254.41  4997.7  253.91  5000.9  254.41  5012.5  259.14  5022.6   260.8
  5042.9  260.13  5057.2  256.72  5083.6  258.49  5119.4  263.11  5175.8  270.15
  5185.1  273.12  5215.6  276.92  5235.9  280.89  5276.5  285.17  5486.6  286.52
#Mann= 7 ,-1 , 0
  4127.6     .05       0  4468.3     .16       0  4849.7     .12       0
  4968.6     .16       0  4994.9     .07       0  5000.9     .16       0
  5119.4     .05       0
Bank Sta=4961.7,5022.6
XS Rating Curve= 0 ,0
Exp/Cntr=0.3,0.1

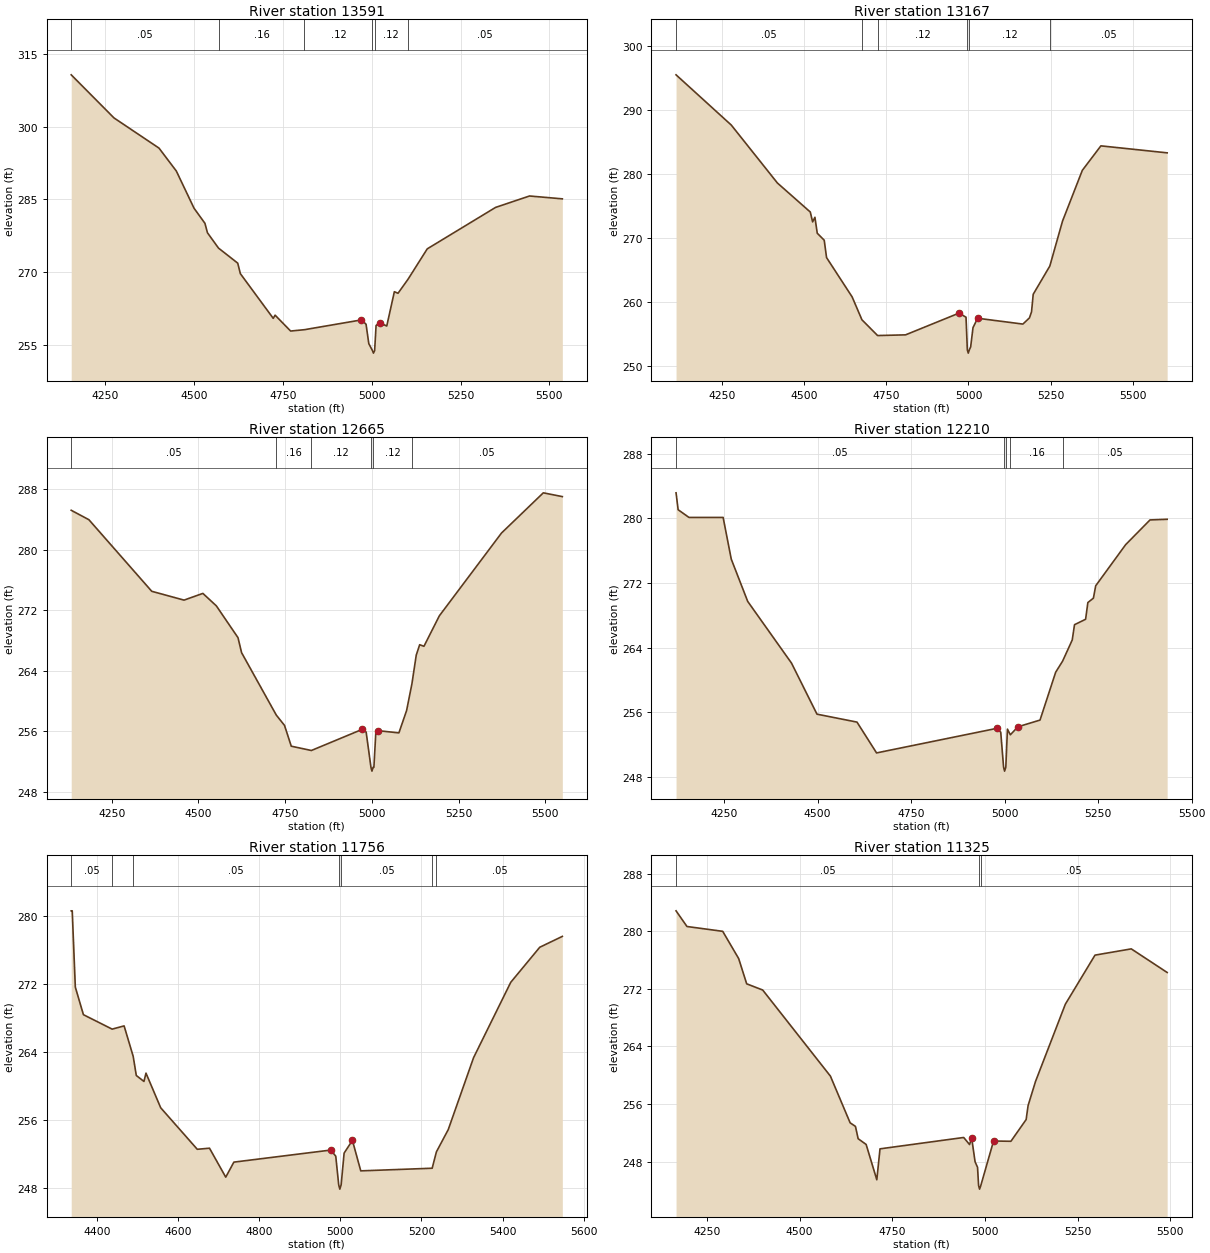
Type RM Length L Ch R = 1 ,13591   ,424,424,424
BEGIN DESCRIPTION:
RINGGOLD CREEK 21.0
END DESCRIPTION:
XS GIS Cut Line= 3
      3701721.82     10553967.63      3701899.61     10553160.19
      3702027.38     10552620.39
#Sta/Elev= 30
  4154.8  310.69  4275.1  301.79  4401.7  295.56  4450.5  290.82  4500.3  283.14
    4531  280.02    4538  278.08  4569.1  274.91  4623.2   271.8  4630.6  269.63
  4723.1   260.4  4728.3  261.06    4772  257.78  4810.9  258.06  4971.3  260.08
  4984.2  259.18  4991.9  255.19  5002.3  253.72    5005  253.22  5008.3  253.72
  5012.4  258.93  5022.7  259.48  5042.4  258.82  5063.8   265.9  5074.1  265.58
  5102.4  268.49  5156.3  274.75  5348.5  283.31    5444  285.67  5536.3  285.08
#Mann= 6 ,-1 , 0
  4154.8     .05       0  4569.1     .16       0  4810.9     .12       0
  5002.3     .07       0  5008.3     .12       0  5102.4     .05       0
Bank Sta=4971.3,5022.7
XS Rating Curve= 0 ,0
Exp/Cntr=0.3,0.1

Type RM Length L Ch R = 1 ,13167   ,502,502,502
BEGIN DESCRIPTION:
RINGGOLD CREEK 20.0
END DESCRIPTION:
XS GIS Cut Line= 4
      3702596.82     10553978.05      3702575.99      10553585.7
      3702199.61     10553210.19      3702145.62     10552643.22
#Sta/Elev= 30
  4110.4  295.44  4278.5   287.6  4418.7  278.57  4518.8  274.04  4525.9   272.5
  4532.9  273.22    4540  270.73  4561.2  269.64  4568.3  266.93  4646.1   260.8
  4675.9  257.23  4723.6  254.77  4808.7  254.88  4971.3  258.27  4992.6  257.63
  4996.6  252.53  4999.4  252.03  5002.6  252.53  5006.7     253  5013.8     256
  5027.9  257.47  5165.6  256.56  5185.6  257.53  5191.9  258.47    5197  261.21
  5247.5  265.61  5286.1  272.61  5346.4  280.54  5402.9  284.36  5604.5  283.27
#Mann= 6 ,-1 , 0
  4110.4     .05       0  4675.9     .16       0  4723.6     .12       0
  4996.6     .07       0  5002.6     .12       0  5247.5     .05       0
Bank Sta=4971.3,5027.9
XS Rating Curve= 0 ,0
Exp/Cntr=0.3,0.1

Type RM Length L Ch R = 1 ,12665   ,455,455,455
BEGIN DESCRIPTION:
RINGGOLD CREEK 19.0
END DESCRIPTION:
XS GIS Cut Line= 3
      3702784.33     10553860.04      3702599.61     10553010.19
      3702350.79     10552524.17
#Sta/Elev= 30
  4133.1  285.22  4184.1  283.97  4365.2   274.5  4458.3  273.33  4512.6  274.22
  4551.5  272.57  4613.9  268.36  4624.2  266.38  4724.2  258.12    4748  256.75
  4767.4     254  4825.4  253.43  4972.1  256.23  4983.3  255.87  4997.2   251.2
    5000   250.7  5003.2   251.2  5005.6   251.2  5011.1  255.75  5016.7  256.06
  5077.7  255.76  5099.9  258.72  5115.2  262.25  5127.7  266.05  5137.6  267.43
  5149.9  267.22  5194.4  271.26  5373.5  282.21    5494  287.53  5548.8  287.03
#Mann= 6 ,-1 , 0
  4133.1     .05       0  4724.2     .16       0  4825.4     .12       0
  4997.2     .07       0  5003.2     .12       0  5115.2     .05       0
Bank Sta=4972.1,5016.7
XS Rating Curve= 0 ,0
Exp/Cntr=0.3,0.1

Type RM Length L Ch R = 1 ,12210   ,454,454,454
BEGIN DESCRIPTION:
RINGGOLD CREEK 18.0
END DESCRIPTION:
XS GIS Cut Line= 3
      3703358.97     10553685.53      3702999.61     10552860.19
      3702761.04     10552523.77
#Sta/Elev= 30
  4121.9  283.15  4127.5  281.06  4156.4  280.11  4247.7  280.11  4269.5  274.95
  4313.4  269.73  4430.5   262.1  4498.6  255.79  4605.5  254.81  4657.8     251
  4978.5  254.03  4989.7  253.57  4997.3  249.25    5000  248.75  5003.3  249.25
  5007.6  253.94  5015.4  253.24  5035.6  254.23  5094.7  255.06  5136.5  260.97
  5155.2  262.36  5180.8  264.96  5186.9  266.85  5216.5  267.52  5222.6  269.59
  5237.4  270.13  5243.5  271.66  5323.5  276.74  5388.7   279.8  5434.5  279.88
#Mann= 5 ,-1 , 0
  4121.9     .05       0  4997.3     .03       0  5003.3     .05       0
  5015.4     .16       0  5155.2     .05       0
Bank Sta=4978.5,5035.6
XS Rating Curve= 0 ,0
Exp/Cntr=0.3,0.1

Type RM Length L Ch R = 1 ,11756   ,431,431,431
BEGIN DESCRIPTION:
RINGGOLD CREEK 17.0
END DESCRIPTION:
XS GIS Cut Line= 3
      3703399.61     10553510.22      3703450.99     10552884.09
      3703586.41     10552316.35
#Sta/Elev= 30
  4335.7  280.66  4338.2  280.66  4345.8  271.68  4365.8  268.43  4436.7  266.73
  4466.2  267.11  4488.6  263.53  4496.3  261.27  4515.2  260.57  4520.2  261.55
  4556.5  257.47  4646.8  252.58  4676.9  252.71    4717   249.3  4737.1  251.07
  4976.3  252.49  4988.5  251.77  4995.8  248.39  4998.5  247.89  5001.8  248.39
  5009.1  252.13  5029.6  253.63  5050.2  250.04  5226.4  250.35  5236.9  252.28
  5266.1   254.9  5328.6  263.37  5420.3  272.24  5491.9  276.37  5547.6  277.65
#Mann= 7 ,-1 , 0
  4335.7     .05       0  4436.7     .08       0  4488.6     .05       0
  4995.8     .03       0  5001.8     .05       0  5226.4     .16       0
  5236.9     .05       0
Bank Sta=4976.3,5029.6
XS Rating Curve= 0 ,0
Exp/Cntr=0.3,0.1

Type RM Length L Ch R = 1 ,11325   ,380,380,380
BEGIN DESCRIPTION:
RINGGOLD CREEK 16.0
END DESCRIPTION:
XS GIS Cut Line= 3
      3703449.61     10553660.19       3703898.9     10552876.28
      3703854.64     10552457.05
#Sta/Elev= 30
  4166.7  282.85  4196.2  280.67  4292.6     280  4335.7  276.21  4357.3   272.7
  4400.5  271.84  4583.2  259.87  4636.4  253.38  4650.8  252.88    4658  251.17
  4679.6  250.37  4708.4  245.46    4717  249.76  4942.8  251.34  4958.6  250.36
  4964.4  251.25  4973.5  247.97  4980.2  247.19    4983  244.66  4985.7  244.16
    4989  244.66  5023.4  250.85  5070.2  250.81  5111.3  253.83  5116.6  255.78
  5136.7  259.14  5217.1  269.87  5297.1  276.69    5395  277.56  5491.8  274.28
#Mann= 3 ,-1 , 0
  4166.7     .05       0    4983     .03       0    4989     .05       0
Bank Sta=4964.4,5023.4
XS Rating Curve= 0 ,0
Exp/Cntr=0.3,0.1

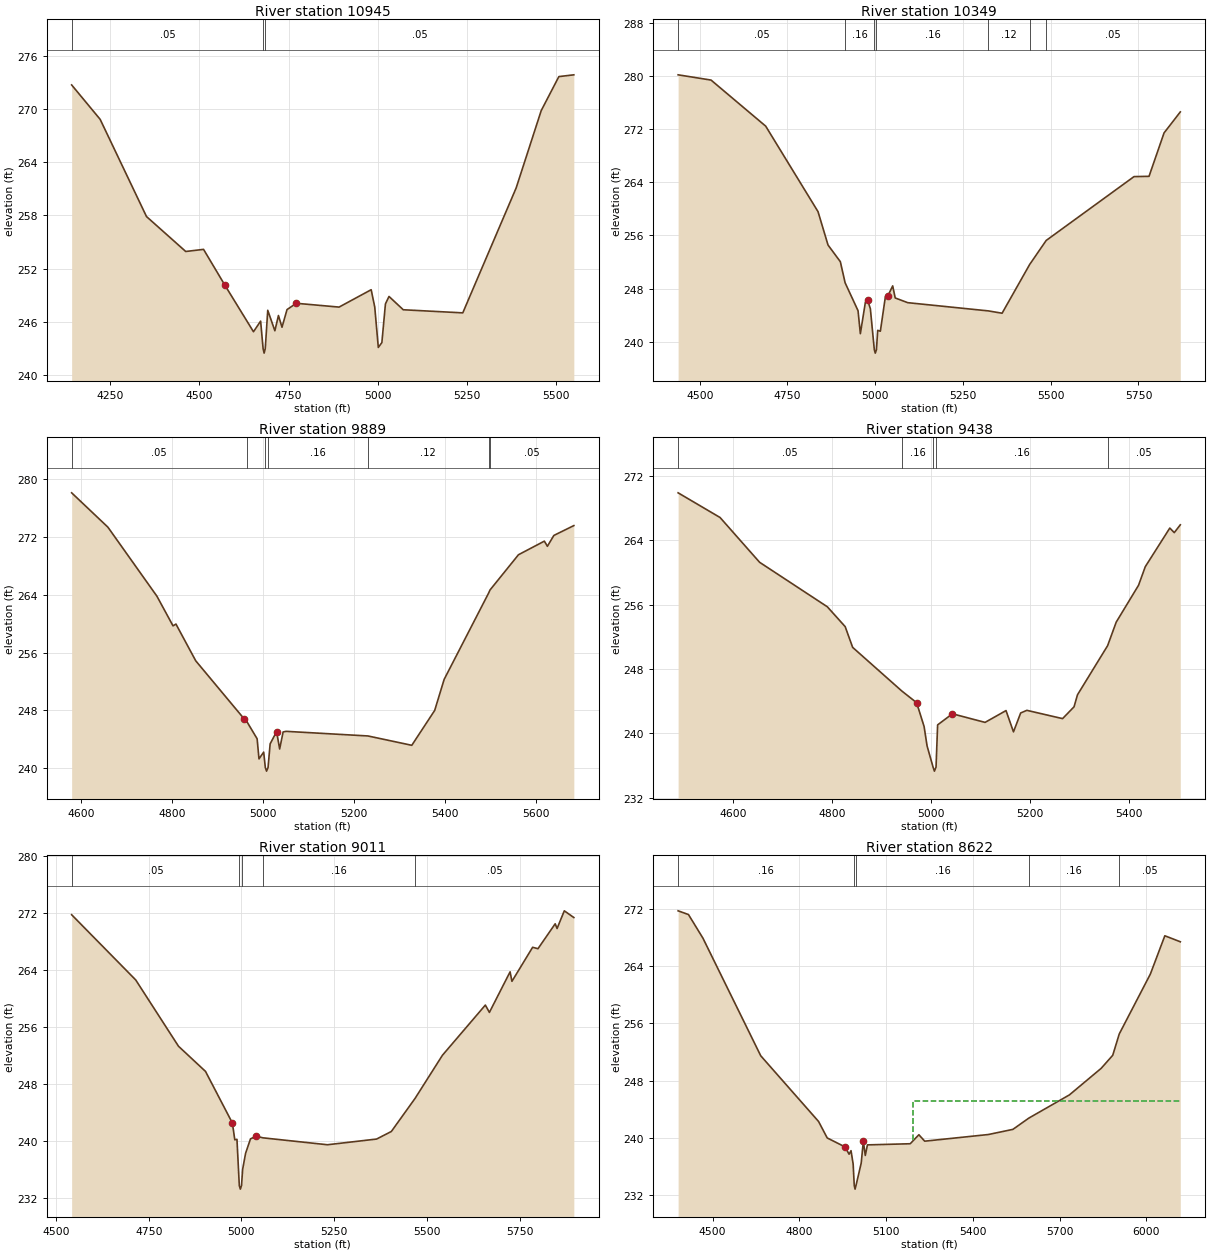
Type RM Length L Ch R = 1 ,10945   ,596,596,596
BEGIN DESCRIPTION:
RINGGOLD CREEK 15.0
END DESCRIPTION:
XS GIS Cut Line= 3
      3704174.51      10553800.1      3704209.23     10552758.44
      3703974.86     10552476.33
#Sta/Elev= 30
  4141.5  272.71  4221.5  268.83  4351.5  257.87  4461.6  253.93  4511.6  254.17
  4571.6  250.12  4651.7  244.88  4671.7  246.08  4678.7  242.97  4681.5  242.47
  4684.7  242.97  4691.7   247.3  4711.7  244.99  4721.7  246.71  4731.7  245.39
  4745.8  247.38  4771.8  248.09  4891.8  247.66  4981.9  249.62  4991.9  247.67
  5001.9  243.11  5011.9  243.66  5021.9  248.02  5031.9  248.86  5071.9  247.36
  5238.9  247.01  5388.7   261.1    5459  269.82  5508.5  273.65  5550.5  273.85
#Mann= 3 ,-1 , 0
  4141.5     .05       0  4678.7     .03       0  4684.7     .05       0
Bank Sta=4571.6,4771.8
XS Rating Curve= 0 ,0
Exp/Cntr=0.3,0.1

Type RM Length L Ch R = 1 ,10349   ,460,460,460
BEGIN DESCRIPTION:
RINGGOLD CREEK 14.0
END DESCRIPTION:
XS GIS Cut Line= 2
      3704994.83     10553357.42      3704057.33     10552276.68
#Sta/Elev= 30
  4438.5  280.19  4532.3   279.4    4688  272.46  4837.1  259.58  4865.6  254.55
  4900.7  252.04  4914.3  248.86  4951.1  244.66  4957.7   241.2    4972  245.93
  4978.6  246.22  4986.2  244.96  4997.5  238.77  5000.2  238.27  5003.5  238.77
  5007.1   241.7  5014.7  241.57    5029  246.77  5035.6  246.84  5049.8   248.4
    5057  246.58  5092.6  245.87  5322.4  244.63  5361.5  244.28    5440  251.62
  5487.1  255.24  5737.4  264.86  5780.1   264.9  5822.9  271.44  5869.2   274.6
#Mann= 7 ,-1 , 0
  4438.5     .05       0  4914.3     .16       0  4997.5     .07       0
  5003.5     .16       0  5322.4     .12       0    5440     .16       0
  5487.1     .05       0
Bank Sta=4978.6,5035.6
XS Rating Curve= 0 ,0
Exp/Cntr=0.3,0.1

Type RM Length L Ch R = 1 ,9889    ,451,451,451
BEGIN DESCRIPTION:
RINGGOLD CREEK 13.0
END DESCRIPTION:
XS GIS Cut Line= 3
      3705203.17      10552988.5      3704949.61     10552660.19
      3704495.71     10552142.14
#Sta/Elev= 30
  4580.1  278.08  4659.8  273.33  4767.5  263.79  4802.9  259.69  4809.3  259.94
  4852.8  254.86  4958.7  246.87  4965.3  246.44  4987.7  244.08  4991.8   241.3
  5002.1  242.24  5005.7  240.11  5008.4  239.61  5011.7  240.11  5016.3  243.38
  5030.5  245.07  5037.2  242.67  5044.8  245.02  5051.4  245.11  5231.3  244.47
  5327.6  243.18  5377.9     248  5398.7  252.29  5496.4  264.22  5499.5  264.65
    5562  269.52  5618.9   271.4  5625.6  270.69  5639.8  272.19  5683.7  273.55
#Mann= 7 ,-1 , 0
  4580.1     .05       0  4965.3     .16       0  5005.7     .07       0
  5011.7     .16       0  5231.3     .12       0  5496.4     .16       0
  5499.5     .05       0
Bank Sta=4958.7,5030.5
XS Rating Curve= 0 ,0
Exp/Cntr=0.3,0.1

Type RM Length L Ch R = 1 ,9438    ,427,427,427
BEGIN DESCRIPTION:
RINGGOLD CREEK 12.0
END DESCRIPTION:
XS GIS Cut Line= 2
      3705550.38     10552797.51      3704990.48     10551951.15
#Sta/Elev= 30
  4488.8  269.91  4573.6  266.84  4653.5  261.27  4790.3  255.74  4826.4  253.27
  4841.5  250.69  4941.1  245.25  4970.8  243.81  4985.9  240.84  4991.9  238.43
    5004   235.8  5006.7   235.3    5010   235.8  5013.2  241.05  5043.1  242.43
  5109.1  241.36  5151.4  242.83  5166.5  240.18    5181  242.53  5193.5  242.86
  5265.7  241.83  5288.9   243.3  5295.8  244.79  5356.7   250.9  5374.1  253.83
  5419.2  258.41  5432.8  260.72  5482.4  265.53  5491.4  264.96  5503.6  265.93
#Mann= 5 ,-1 , 0
  4488.8     .05       0  4941.1     .16       0    5004     .07       0
    5010     .16       0  5356.7     .05       0
Bank Sta=4970.8,5043.1
XS Rating Curve= 0 ,0
Exp/Cntr=0.3,0.1

Type RM Length L Ch R = 1 ,9011    ,389,389,389
BEGIN DESCRIPTION:
RINGGOLD CREEK 11.0
END DESCRIPTION:
XS GIS Cut Line= 3
      3705849.83     10552506.67      3705506.98     10551964.17
      3704804.23     10551847.05
#Sta/Elev= 30
  4542.2   271.7    4715  262.56  4830.3  253.27  4903.2  249.74  4975.7   242.5
  4982.1  240.16    4988  240.22  4994.3  233.74  4997.1  233.24  5000.3  233.74
  5003.3  236.02  5011.2  238.25  5024.4  240.28  5039.7  240.66    5058  240.43
    5232  239.46  5364.6  240.26  5404.3  241.32  5468.3  245.96    5542     252
  5657.8  259.04  5668.7  258.01  5724.5   263.7  5729.5  262.37  5785.3  267.14
  5799.7  266.94  5846.1  270.43  5851.2  269.77  5870.7  272.25  5896.4  271.31
#Mann= 5 ,-1 , 0
  4542.2     .05       0  4994.3     .03       0  5000.3     .05       0
    5058     .16       0  5468.3     .05       0
Bank Sta=4975.7,5039.7
XS Rating Curve= 0 ,0
Exp/Cntr=0.3,0.1

Type RM Length L Ch R = 1 ,8622    ,452,452,452
BEGIN DESCRIPTION:
RINGGOLD CREEK 10.0
END DESCRIPTION:
XS GIS Cut Line= 4
      3705871.56     10552445.95      3705880.24     10551916.43
      3705710.97      10551729.8      3704756.11     10551768.86
#Sta/Elev= 30
  4380.5  271.76  4416.3  271.24  4466.3  267.94  4666.3  251.48  4866.3  242.29
  4896.3  239.98  4957.7  238.73  4971.9  237.71  4978.6   238.2    4986  236.33
  4989.8  233.32  4992.6  232.82  4995.8  233.32  5013.8  236.45  5021.2   239.5
    5028  237.53  5035.4  239.01  5183.4  239.17  5213.4  240.43  5233.5  239.53
  5453.7  240.46  5538.6  241.18  5593.8  242.76  5733.9     246    5844  249.72
    5884  251.55  5906.5  254.53  6014.1  262.91  6064.2  268.27  6117.7  267.43
#Mann= 5 ,-1 , 0
  4380.5     .16       0  4989.8     .07       0  4995.8     .16       0
  5593.8     .16       0  5906.5     .05       0
#XS Ineff= 2 , 0
                         5194.32          245.21
Permanent Ineff=
       F       F
Bank Sta=4957.7,5021.2
XS Rating Curve= 0 ,0
Exp/Cntr=0.3,0.1

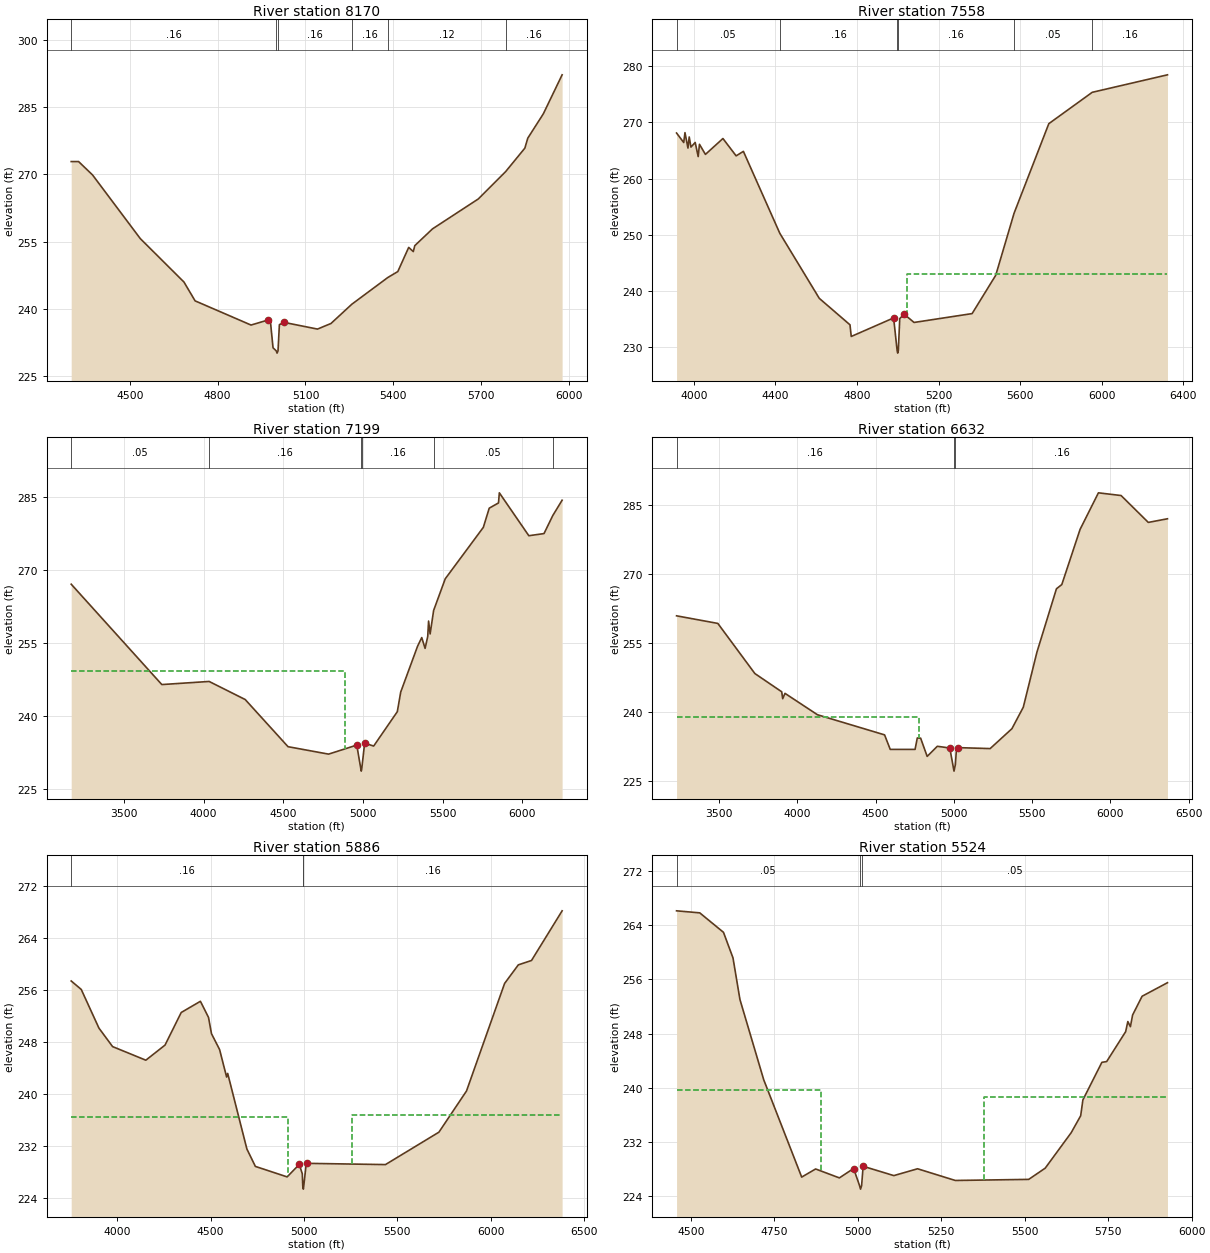
Type RM Length L Ch R = 1 ,8170    ,612,612,612
BEGIN DESCRIPTION:
RINGGOLD CREEK 9.0
END DESCRIPTION:
XS GIS Cut Line= 4
      3705906.27       10552459.      3706123.29     10551846.99
      3706288.23     10551556.19       3706162.4     10550874.98
#Sta/Elev= 30
    4300  272.85  4325.1  272.86    4373  269.86  4535.9  255.68    4685     246
  4723.1   241.8  4914.1  236.41  4973.4  237.56  4980.2  237.27  4989.2  231.34
  5000.2  230.65  5002.9  230.15  5006.2  230.65  5010.9  236.49  5026.2  237.01
  5141.1  235.51  5187.1  236.76  5258.3  241.05  5381.2  247.01  5415.3  248.33
  5452.5  253.72  5468.2  252.79  5473.3  254.11  5533.8  257.85  5690.2  264.52
  5783.1  270.58  5849.1  275.84  5859.2  278.08  5912.2  283.49  5976.4  292.19
#Mann= 6 ,-1 , 0
    4300     .16       0  5000.2     .07       0  5006.2     .16       0
  5258.3     .16       0  5381.2     .12       0  5783.1     .16       0
Bank Sta=4973.4,5026.2
XS Rating Curve= 0 ,0
Exp/Cntr=0.3,0.1

Type RM Length L Ch R = 1 ,7558    ,359,359,359
BEGIN DESCRIPTION:
RINGGOLD CREEK 8.0
END DESCRIPTION:
XS GIS Cut Line= 3
      3705830.73     10552639.11      3706629.37     10552055.75
      3706552.98     10550639.11
#Sta/Elev= 30
  3915.1  268.11  3950.2  266.42  3956.4  268.18    3971  265.43  3977.2  267.41
  3985.7   265.6  4006.5  266.43  4021.2  263.91  4027.4   266.1  4056.7   264.3
  4142.5  267.13  4207.3  264.04  4242.9  264.84  4421.4  250.24  4615.1  238.63
  4765.7  233.91  4771.9  231.83  4979.8  235.14  4996.8  229.36  4999.6  228.86
  5002.8  229.36  5009.8  235.02  5031.1  235.81  5079.9  234.33  5364.7  235.91
  5480.5  242.74  5570.6  253.82  5740.9  269.78  5953.8  275.37  6322.8  278.49
#Mann= 6 ,-1 , 0
  3915.1     .05       0  4421.4     .16       0  4996.8     .07       0
  5002.8     .16       0  5570.6     .05       0  5953.8     .16       0
#XS Ineff= 2 , 0
       0                 5044.32       0     243
Permanent Ineff=
       F       F
Bank Sta=4979.8,5031.1
XS Rating Curve= 0 ,0
Exp/Cntr=0.3,0.1

Type RM Length L Ch R = 1 ,7199    ,567,567,567
BEGIN DESCRIPTION:
RINGGOLD CREEK 7.0
END DESCRIPTION:
XS GIS Cut Line= 3
      3705615.52     10553250.16      3707184.93     10551743.25
      3707469.15     10550883.66
#Sta/Elev= 30
  3169.4  267.14  3738.1  246.48    4035  247.12  4261.4   243.4  4530.3  233.69
  4784.7  232.16  4961.7  234.02    4987  229.16  4989.8  228.66    4993  229.16
  5011.1  234.43  5067.7  233.82  5216.2   240.9  5237.5  244.94  5343.5  254.39
  5369.4  256.15  5390.5  253.93  5407.1  256.39  5412.3  259.55  5422.1   256.9
  5444.1  261.74  5516.9  268.25    5756  278.84    5793  282.79  5851.2  283.87
  5856.5  285.95  6041.6  277.12  6136.8  277.56  6191.9  281.27  6250.5  284.43
#Mann= 6 ,-1 , 0
  3169.4     .05       0    4035     .16       0    4987     .07       0
    4993     .16       0  5444.1     .05       0  6191.9     .16       0
#XS Ineff= 2 , 0
         4885.73  249.32
Permanent Ineff=
       F       F
Bank Sta=4961.7,5011.1
XS Rating Curve= 0 ,0
Exp/Cntr=0.3,0.1

Type RM Length L Ch R = 1 ,6632    ,746,746,746
BEGIN DESCRIPTION:
RINGGOLD CREEK 6.0, Ineff. added
END DESCRIPTION:
XS GIS Cut Line= 3
      3706178.01     10553736.27      3707344.65      10552125.2
      3707490.48     10550986.31
#Sta/Elev= 30
  3227.8  260.82  3491.6  259.17  3728.2  248.28  3899.9  244.31  3906.1  242.81
  3920.8  243.97    4128  239.33  4557.2  234.95  4593.4  231.79  4752.1  231.79
  4766.3  234.28  4787.7  234.23  4829.4  230.27  4894.4  232.47  4974.1  232.09
  5000.9  227.07  5009.6  228.47  5015.8  231.48  5024.3  232.18    5232  231.97
  5371.1  236.29  5443.8  240.97  5530.5  252.88  5655.5  266.69  5689.9  267.62
  5806.7  279.61  5923.9  287.55  6068.8  286.96  6242.7  281.12  6365.1  281.91
#Mann= 3 ,-1 , 0
  3227.8     .16       0  5000.9     .07       0  5009.6     .16       0
#XS Ineff= 2 , 0
         4777.84  238.92
Permanent Ineff=
       F       F
Bank Sta=4974.1,5024.3
XS Rating Curve= 0 ,0
Exp/Cntr=0.3,0.1

Type RM Length L Ch R = 1 ,5886    ,362,362,362
BEGIN DESCRIPTION:
RINGGOLD CREEK 5.0, Ineff. added
END DESCRIPTION:
XS GIS Cut Line= 3
      3707066.89      10553819.6      3707858.54     10552409.92
      3708115.06     10551432.38
#Sta/Elev= 30
  3754.4  257.39  3808.2  256.09  3902.8  250.15  3975.9  247.31  4153.8  245.22
  4256.5  247.54  4343.2  252.55  4445.9  254.27  4489.2   251.8  4505.2  249.29
  4548.5  246.86  4586.2  242.63  4591.9  243.19  4694.6  231.58  4740.1   228.9
  4910.1  227.29  4975.1  229.21  4991.1  227.78  4993.8  225.91  4996.6  225.41
  4997.1  225.41  5012.8  229.45  5018.5  229.37  5436.3  229.18  5722.4  234.16
  5870.1  240.49  6073.9  257.01  6147.5  259.87    6218  260.54  6381.8  268.17
#Mann= 3 ,-1 , 0
  3754.4     .16       0  4993.8     .07       0  4997.1     .16       0
#XS Ineff= 2 , 0
         4914.77  236.46 5255.68          236.77
Permanent Ineff=
       F       F
Bank Sta=4975.1,5018.5
XS Rating Curve= 0 ,0
Exp/Cntr=0.3,0.1

Type RM Length L Ch R = 1 ,5524    ,279,279,279
BEGIN DESCRIPTION:
RINGGOLD CREEK 4.0
END DESCRIPTION:
XS GIS Cut Line= 2
      3707552.97     10553382.16      3708524.93     10552278.28
#Sta/Elev= 30
  4456.7  266.14  4526.2  265.84  4597.3  262.96  4625.8  259.18  4646.6  253.03
  4717.8  241.17  4831.6  226.77  4873.4  227.97  4944.5  226.65  4987.2  228.04
  5005.1  225.49  5007.9  224.99  5011.1  225.49  5015.7  228.37  5107.7  226.99
  5178.8     228  5291.8  226.27  5511.8  226.43  5561.2  228.09    5639  233.33
  5667.5  235.84  5674.1  238.18    5731  243.74  5745.3  243.85  5802.2  248.27
  5808.8  249.77  5816.4  249.01  5823.1  250.74  5851.5  253.51  5927.5  255.51
#Mann= 3 ,-1 , 0
  4456.7     .05       0  5005.1     .03       0  5011.1     .05       0
#XS Ineff= 2 , 0
         4888.21  239.59 5379.23          238.59
Permanent Ineff=
       F       F
Bank Sta=4987.2,5015.7
XS Rating Curve= 0 ,0
Exp/Cntr=0.3,0.1

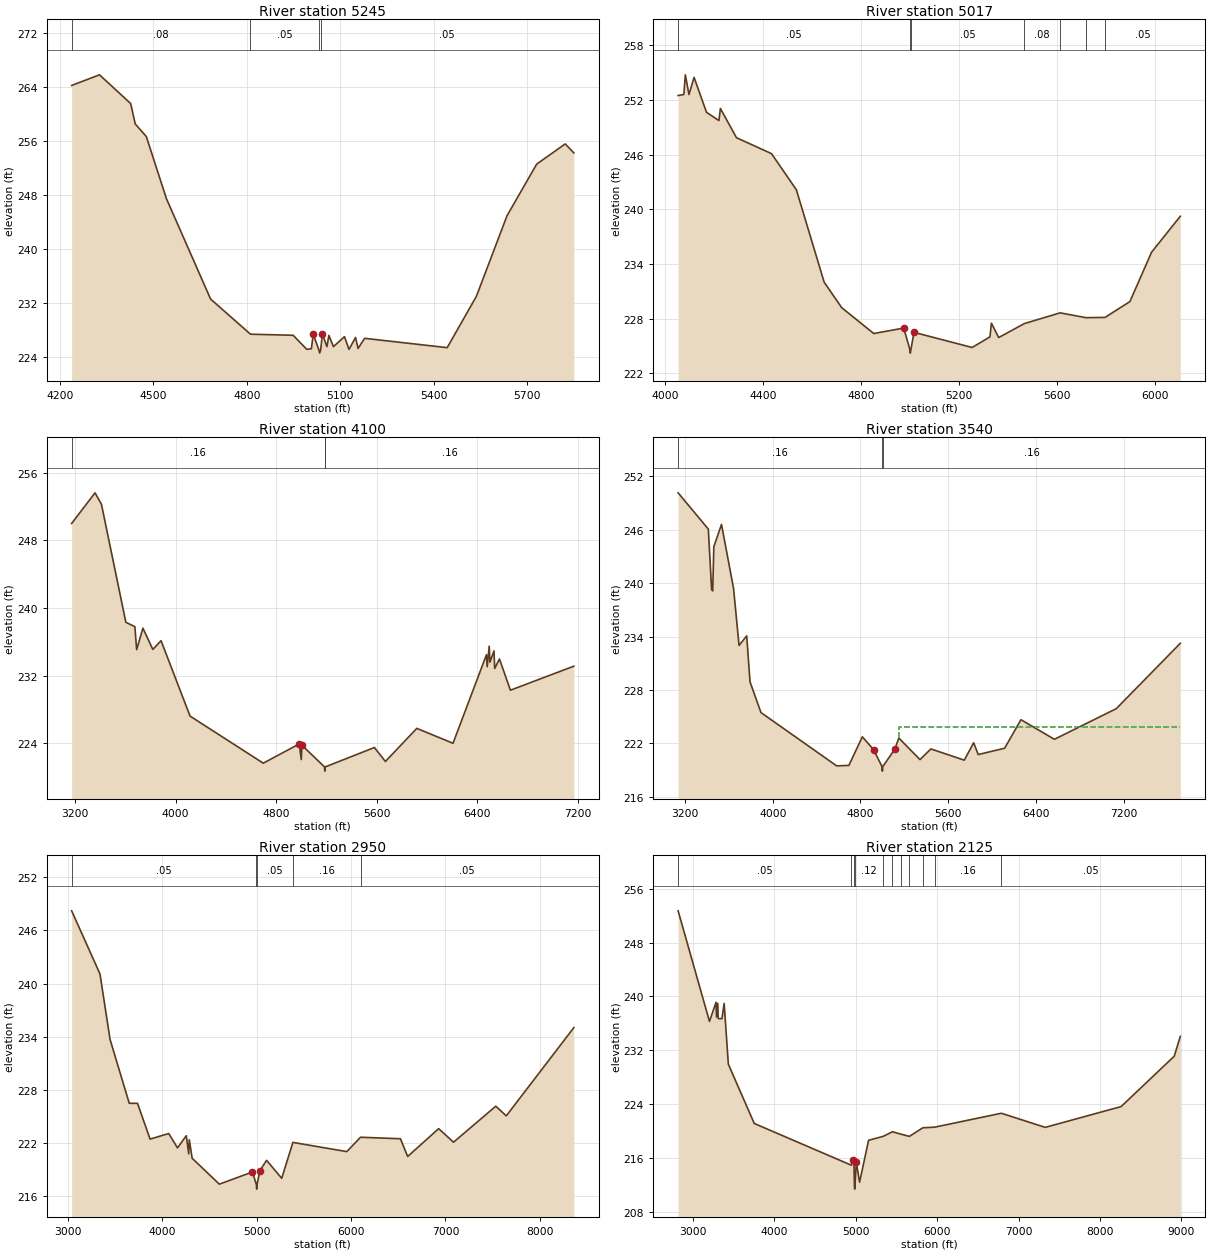
Type RM Length L Ch R = 1 ,5245    ,228,228,228
BEGIN DESCRIPTION:
RINGGOLD CREEK 3.0
END DESCRIPTION:
XS GIS Cut Line= 3
      3707532.12     10553527.99       3708400.2     10552882.14
      3708594.61     10552389.18
#Sta/Elev= 30
  4237.6   264.2    4327  265.77  4427.1  261.52  4441.7   258.5  4477.2  256.65
  4541.8  247.45  4683.6   232.6  4811.6   227.4  4948.5  227.24  4992.4  225.16
    5007  225.25  5013.2  227.37    5031   225.1  5033.8   224.6    5037   225.1
  5042.4  227.43    5057  225.56  5063.3  227.22  5077.9  225.56  5113.3  227.04
  5127.9  225.15  5148.8  226.92  5156.8  225.29    5178  226.79    5443  225.41
  5536.7     233  5635.1  244.93  5730.2  252.56  5821.9  255.55  5849.5  254.22
#Mann= 4 ,-1 , 0
  4237.6     .08       0  4811.6     .05       0    5031     .03       0
    5037     .05       0
Bank Sta=5013.2,5042.4
XS Rating Curve= 0 ,0
Exp/Cntr=0.3,0.1

Type RM Length L Ch R = 1 ,5017    ,917,917,917
BEGIN DESCRIPTION:
RINGGOLD CREEK 2.0, Ineff. added
END DESCRIPTION:
XS GIS Cut Line= 3
      3707559.89     10553701.61      3708809.93     10552840.48
      3709315.75     10552667.25
#Sta/Elev= 30
    4052  252.48  4075.4  252.59  4081.5  254.75  4096.4  252.59  4117.3  254.47
    4168  250.64  4218.8  249.73  4224.8  251.06  4290.5  247.85  4433.8   246.1
  4535.3  242.14  4648.9     232  4720.6   229.2  4851.8  226.36  4974.2  226.96
  4998.2  224.71    5001  224.21  5004.2  224.71  5016.1  226.49  5253.8  224.83
  5326.5  225.99  5332.6  227.49  5362.4  225.92    5467  227.45  5613.4  228.63
  5719.3   228.1  5797.2  228.13  5898.7  229.87  5987.3  235.29  6104.6  239.23
#Mann= 7 ,-1 , 0
    4052     .05       0  4998.2     .03       0  5004.2     .05       0
    5467     .08       0  5613.4     .05       0  5719.3     .08       0
  5797.2     .05       0
Bank Sta=4974.2,5016.1
XS Rating Curve= 0 ,0
Exp/Cntr=0.3,0.1

Type RM Length L Ch R = 1 ,4100    ,560,560,560
BEGIN DESCRIPTION:
Mapping XS cc6ffc26, Ineff. added
END DESCRIPTION:
XS GIS Cut Line= 3
      3706787.38     10554281.44      3708809.93      10553856.1
      3709738.27     10552164.25
#Sta/Elev= 30
  3173.2  249.98  3359.4   253.6  3410.5  252.24  3604.7   238.3  3676.2  237.79
  3690.5  235.07  3740.4  237.61  3819.3   235.1  3884.8  236.13  4115.6  227.22
  4698.1  221.66  4984.2  223.93  5000.5  222.09  5005.6  223.78  5185.6  221.22
  5188.3  220.72  5191.6  221.22  5582.8  223.51    5670  221.86  5920.2  225.77
  6208.3  224.01  6474.6  234.48  6480.3  233.06  6496.4  235.48  6502.1  233.59
  6534.3  234.92    6540  232.85  6577.9  233.97  6665.1  230.28  7169.8  233.12
#Mann= 3 ,-1 , 0
  3173.2     .16       0  5185.6     .03       0  5191.6     .16       0
Bank Sta=4984.2,5005.6
XS Rating Curve= 0 ,0
Exp/Cntr=0.3,0.1

Type RM Length L Ch R = 1 ,3540    ,590,590,590
BEGIN DESCRIPTION:
Mapping XS cdbe52a3
END DESCRIPTION:
XS GIS Cut Line= 5
      3706624.09     10554432.85       3708117.1     10554452.54
      3708724.77     10554324.34      3709410.81     10553552.02
      3709787.69     10552170.72
#Sta/Elev= 30
  3137.4  250.12  3412.9  246.05  3442.9  239.27    3453  239.12    3463  244.07
    3533  246.58    3643  239.39    3693     233    3763  234.07    3793  228.92
    3893  225.47    4583  219.49  4694.4  219.54  4817.1  222.75  4919.3  221.32
    4997   219.4  4999.8   218.9    5003   219.4  5113.5  221.37  5149.9  222.61
  5342.9  220.19  5442.4  221.39  5746.8  220.13  5832.1  222.08  5873.9  220.76
  6114.7  221.47  6263.6  224.67  6568.3  222.47  7133.1  225.91  7716.4  233.24
#Mann= 3 ,-1 , 0
  3137.4     .16       0    4997     .03       0    5003     .16       0
#XS Ineff= 2 , 0
                         5153.41          223.81
Permanent Ineff=
       F       F
Bank Sta=4919.3,5113.5
XS Rating Curve= 0 ,0
Exp/Cntr=0.3,0.1

Type RM Length L Ch R = 1 ,2950    ,825,825,825
BEGIN DESCRIPTION:
Mapping XS 0834e9d3
END DESCRIPTION:
XS GIS Cut Line= 5
       3706615.4     10554554.38      3707791.61      10554966.7
      3708920.08     10554905.94      3709474.73     10553608.98
      3709904.75     10552136.45
#Sta/Elev= 30
  3039.2   248.2  3339.5  241.08  3446.3  233.69  3649.6   226.5  3737.3  226.49
  3870.2  222.46  4067.8  223.09  4160.8  221.47  4253.9  222.84  4279.6   220.8
  4285.6   222.4  4316.2   220.3    4604  217.38  4954.6  218.75    4997  217.32
  4999.8  216.82    5003  217.32  5034.7  218.91  5104.8  220.07    5265  218.04
  5383.7  222.09  5954.9  221.05    6100  222.67  6523.3   222.5  6599.5   220.5
  6928.4  223.64  7085.4  222.11  7533.4  226.17  7644.6  225.08  8360.3  235.03
#Mann= 5 ,-1 , 0
  3039.2     .05       0    4997     .03       0    5003     .05       0
  5383.7     .16       0    6100     .05       0
Bank Sta=4954.6,5034.7
XS Rating Curve= 0 ,0
Exp/Cntr=0.3,0.1

Type RM Length L Ch R = 1 ,2125    ,0,0,0
BEGIN DESCRIPTION:
RINGGOLD CREEK 1.0, Ineff. added
END DESCRIPTION:
XS GIS Cut Line= 4
       3706535.6     10554602.61      3708202.29     10555670.34
       3708775.2     10555652.98      3710051.23     10552276.28
#Sta/Elev= 30
  2823.1  252.72  3207.9   236.3  3288.2  239.13  3294.1  236.95  3309.4  238.99
  3315.3  236.72  3360.9   236.7    3388  238.97  3439.6  229.94  3757.5  221.14
  4949.4  214.94  4968.6  215.77  4979.9  215.66  4986.9  211.89  4989.6  211.39
  4992.9  211.89  5009.9   215.4  5049.9  212.42    5160  218.64  5342.2  219.24
  5453.4  219.91  5556.8  219.56  5660.2  219.22  5826.4   220.5  5970.2  220.59
  6789.8  222.66  7327.7  220.56  8259.5  223.65  8910.9  231.13  8985.4  234.07
#Mann= 11 ,-1 , 0
  2823.1     .05       0  4949.4     .12       0  4986.9     .07       0
  4992.9     .12       0  5342.2     .05       0  5453.4     .12       0
  5556.8     .05       0  5660.2     .12       0  5826.4     .05       0
  5970.2     .16       0  6789.8     .05       0
Bank Sta=4968.6,5009.9
XS Rating Curve= 0 ,0
Exp/Cntr=0.3,0.1

Chan Stop Cuts=-1
Use User Specified Reach Order=0
Composite Channel Slope=5