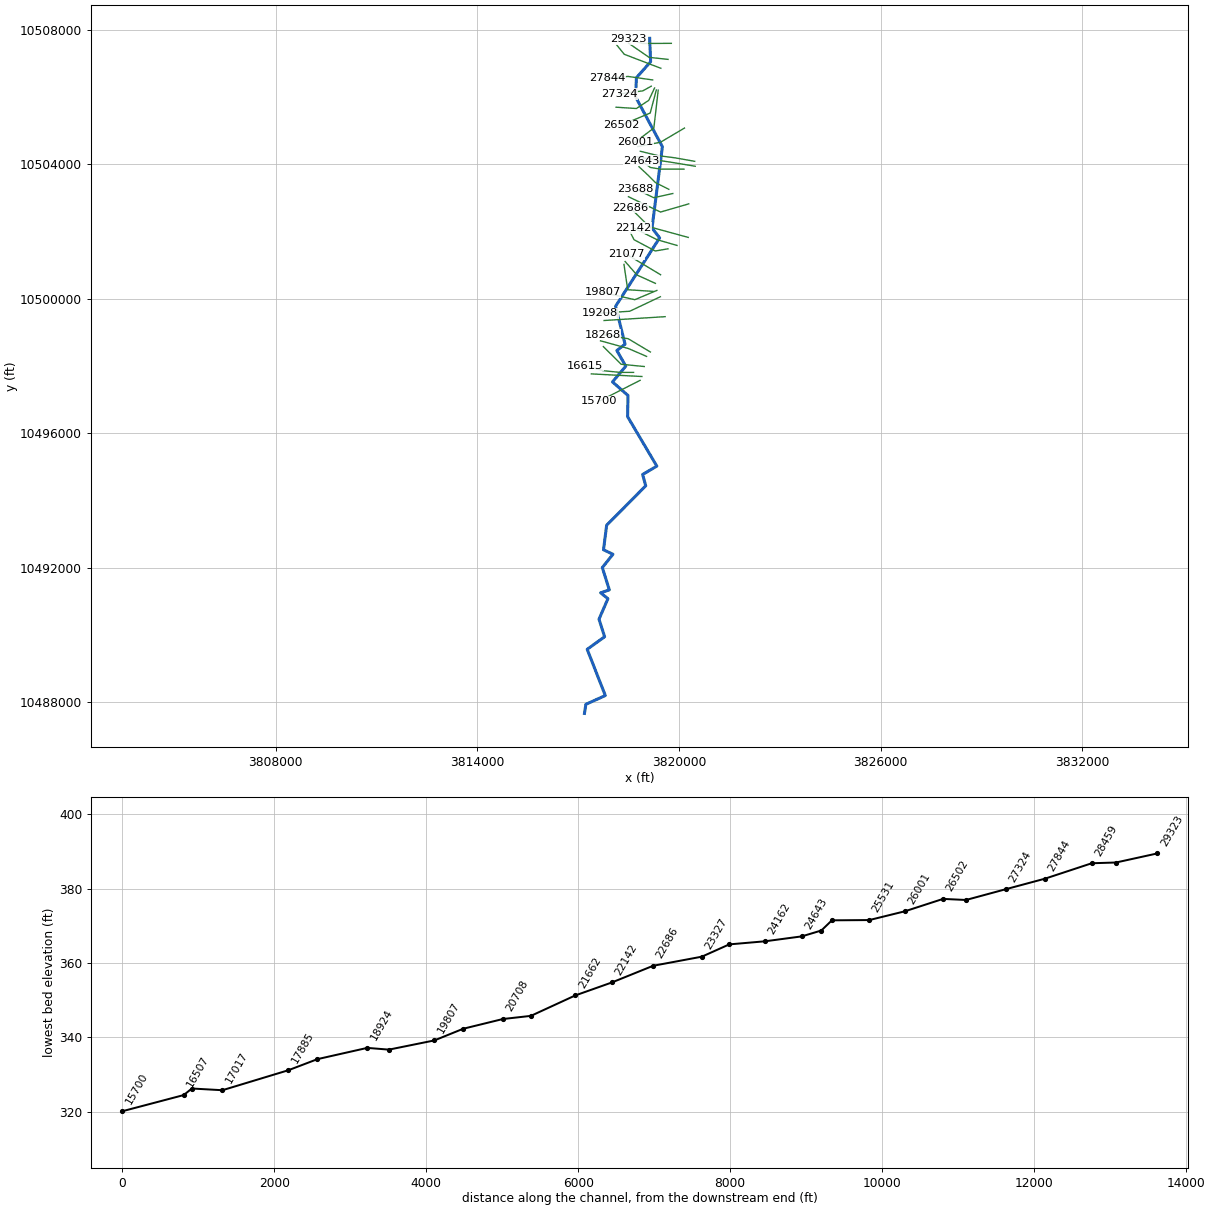
--- SANDS BRANCH.prj (project) ---

Proj Title=SANDS BRANCH Base Level Engineering
Current Plan=p01
Default Exp/Contr=0.3,0.1
English Units
Geom File=g01
Flow File=f01
Plan File=p01
Y Axis Title=Elevation
X Axis Title(PF)=Main Channel Distance
X Axis Title(XS)=Station
BEGIN DESCRIPTION:
SANDS BRANCH
END DESCRIPTION:
DSS Export Rating Curves= 0
DSS Export Rating Curve Sorted= 0
DSS Export Volume Flow Curves= 0
DXF OffsetX= 0
DXF OffsetY= 0
DXF ScaleX= 1
DXF ScaleY= 10

--- SANDS BRANCH.p01 (plan) ---

Plan Title=Multiple Run
Short Identifier=Multiple
Geom File=g01
Flow File=f01
Subcritical Flow
K Sum by GR= 0
Std Step Tol= 0.01
Critical Tol= 0.01
Num of Std Step Trials= 20
Max Error Tol= 0.3
Flow Tol Ratio= 0.001
Split Flow NTrial= 30
Split Flow Tol= 0.02
Split Flow Ratio= 0.02
Log Output Level= 0
Friction Slope Method= 1
Unsteady Friction Slope Method= 2
Unsteady Bridges Friction Slope Method= 1
Parabolic Critical Depth
Global Vel Dist=  1 , 1 , 1
Global Log Level= 0
CheckData=True
Encroach Param= -1, 0, 0, 0
BEGIN DESCRIPTION:
Multiple Run
END DESCRIPTION:

--- SANDS BRANCH.f01 (steady flow) ---

Flow Title=Multiple
Program Version=4.10
Number of Profiles= 7
Profile Names=10-year,25-year,50-year,1pct_min,100-year,1pct_plu,500-year
River Rch & RM=SANDS BRANCH,Reach-1         ,29323
     498     660     791     697     943    1275    1343
River Rch & RM=SANDS BRANCH,Reach-1         ,25531
     632     850    1028     913    1235    1670    1789
River Rch & RM=SANDS BRANCH,Reach-1         ,19807
     928    1271    1556    1397    1890    2556    2798
River Rch & RM=SANDS BRANCH,Reach-1         ,8469
    1670    2346    2924    2666    3606    4877    5509
Boundary for River Rch & Prof#=SANDS BRANCH,Reach-1         , 1
Up Type= 0
Dn Type= 3
Dn Slope=0.0032
Boundary for River Rch & Prof#=SANDS BRANCH,Reach-1         , 2
Up Type= 0
Dn Type= 3
Dn Slope=0.0032
Boundary for River Rch & Prof#=SANDS BRANCH,Reach-1         , 3
Up Type= 0
Dn Type= 3
Dn Slope=0.0032
Boundary for River Rch & Prof#=SANDS BRANCH,Reach-1         , 4
Up Type= 0
Dn Type= 3
Dn Slope=0.0032
Boundary for River Rch & Prof#=SANDS BRANCH,Reach-1         , 5
Up Type= 0
Dn Type= 3
Dn Slope=0.0032
Boundary for River Rch & Prof#=SANDS BRANCH,Reach-1         , 6
Up Type= 0
Dn Type= 3
Dn Slope=0.0032
Boundary for River Rch & Prof#=SANDS BRANCH,Reach-1         , 7
Up Type= 0
Dn Type= 3
Dn Slope=0.0032
DSS Import GetInterval= 0
DSS Import GetPeak= 0
DSS Import FillOption= 0

--- SANDS BRANCH.g01 (geometry) ---

Geom Title=Existing Conditions
Program Version=4.10

River Reach=SANDS BRANCH    ,Reach-1
Reach XY= 30
      3819129.58     10507753.93       3819157.5       10507056.
      3818735.25       10506583.        3818710.       10506011.
      3819507.75       10504528.       3819199.5       10502105.
      3819425.75       10501815.       3818114.5       10499778.
        3818397.       10498650.        3818152.       10498461.
      3818418.25       10497995.       3818023.5       10497526.
      3818483.75       10497123.      3818472.75       10496492.
        3819342.       10495020.      3818919.75       10494771.
        3819012.       10494434.        3817849.       10493261.
        3817756.       10492530.      3818036.25       10492396.
      3817720.25       10492000.      3817928.75       10491336.
       3817670.5       10491249.        3817887.       10491074.
      3817621.75       10490464.        3817789.       10489941.
      3817270.25       10489567.       3817809.5       10488191.
      3817230.25       10487930.        3817189.       10487660.

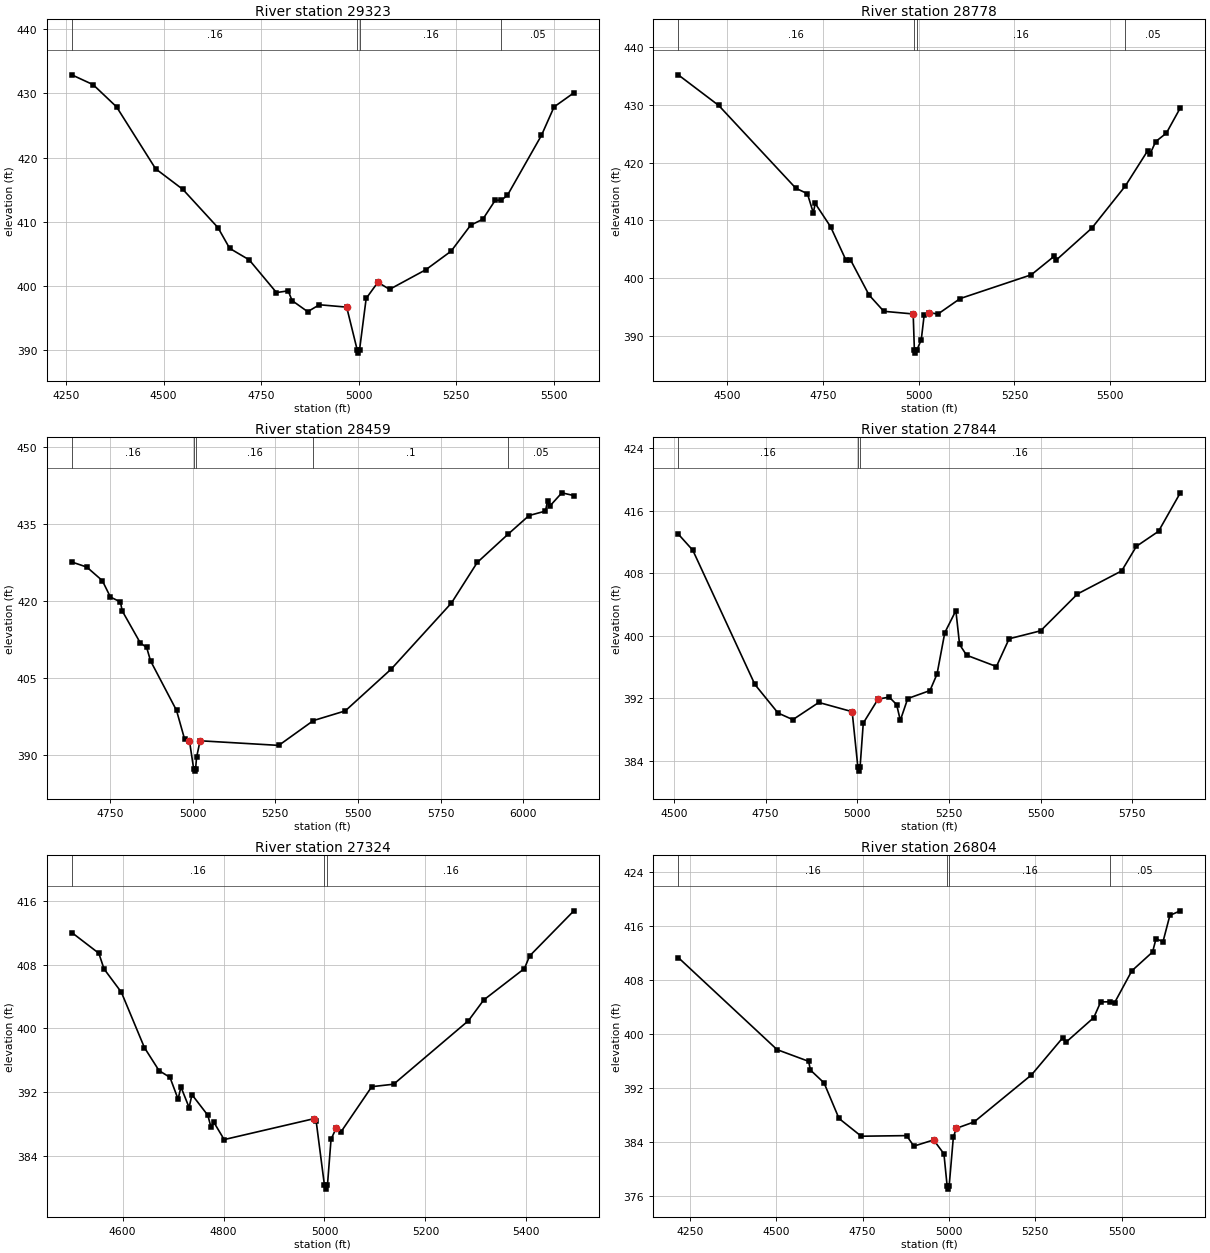
Type RM Length L Ch R = 1 ,29323   ,545,545,545
BEGIN DESCRIPTION:
SANDS BRANCH 52.0
END DESCRIPTION:
XS GIS Cut Line= 3
      3819774.46     10507604.85      3818919.47     10507600.51
      3818507.15     10507730.72
#Sta/Elev= 30
  4264.5  432.89  4319.4  431.35  4379.4  427.89  4479.4  418.25  4549.4  415.03
  4639.4  409.07  4669.4  405.84  4719.4  404.05  4789.4  398.95  4819.4  399.22
  4829.4   397.7  4869.4  395.97  4899.4  397.05  4969.4  396.68  4996.4  390.01
  4999.1  389.51  5002.4  390.01  5019.4  398.04  5049.4  400.55  5079.4  399.45
  5172.6  402.52  5237.3  405.41  5287.1  409.44  5318.6  410.39  5350.1  413.32
  5366.2  413.37  5381.5   414.1  5468.9  423.46  5501.2  427.89  5551.9  430.08
#Mann= 4 ,-1 , 0
  4264.5     .16       0  4996.4     .07       0  5002.4     .16       0
  5366.2     .05       0
Bank Sta=4969.4,5049.4
XS Rating Curve= 0 ,0
Exp/Cntr=0.3,0.1

Type RM Length L Ch R = 1 ,28778   ,319,319,319
BEGIN DESCRIPTION:
SANDS BRANCH 51.0
END DESCRIPTION:
XS GIS Cut Line= 3
       3819674.7     10507127.42      3819110.45     10507188.19
      3818499.65     10507610.16
#Sta/Elev= 30
  4372.8  435.17  4478.5  429.87  4679.7  415.56  4709.8  414.62  4725.2  411.31
  4730.2  412.93  4770.2  408.92  4810.4  403.13  4822.2  403.19  4870.7   397.1
  4909.1  394.29  4985.8  393.83  4988.9  387.56  4991.7  387.06  4994.9  387.56
  5006.8  389.34  5014.3  393.57  5027.7  394.04  5050.7  393.83  5108.2  396.49
  5293.8   400.6  5352.9  403.77    5359  403.15  5451.8  408.67  5539.3  415.96
  5597.6  422.05  5603.7  421.48  5618.5  423.63  5646.3  425.09  5682.7  429.46
#Mann= 4 ,-1 , 0
  4372.8     .16       0  4988.9     .07       0  4994.9     .16       0
  5539.3     .05       0
Bank Sta=4985.8,5027.7
XS Rating Curve= 0 ,0
Exp/Cntr=0.3,0.1

Type RM Length L Ch R = 1 ,28459   ,615,615,615
BEGIN DESCRIPTION:
SANDS BRANCH 50.0
END DESCRIPTION:
XS GIS Cut Line= 3
      3819462.01     10506862.67       3818372.6     10507279.33
      3818151.23     10507552.79
#Sta/Elev= 30
  4634.7  427.65  4680.1  426.66    4727  424.02  4751.7   420.8  4781.8  419.87
  4787.2  418.12  4841.9  411.87  4861.2  410.98  4872.8  408.38  4951.4  398.71
  4976.1  393.05  4990.6  392.76  5003.2  387.36  5005.9  386.86  5009.2  387.36
    5012  389.52  5022.7  392.78  5260.6  391.88  5365.3  396.72  5461.7  398.61
  5600.9  406.78  5782.9  419.66  5860.8  427.56  5954.8  433.12  6017.4  436.71
    6067  437.58  6073.4  439.54  6081.4  438.63  6116.6  441.14  6152.9  440.61
#Mann= 5 ,-1 , 0
  4634.7     .16       0  5003.2     .07       0  5009.2     .16       0
  5365.3      .1       0  5954.8     .05       0
Bank Sta=4990.6,5022.7
XS Rating Curve= 0 ,0
Exp/Cntr=0.3,0.1

Type RM Length L Ch R = 1 ,27844   ,520,520,520
BEGIN DESCRIPTION:
SANDS BRANCH 49.0
END DESCRIPTION:
XS GIS Cut Line= 3
      3819218.92     10506515.45      3818485.45     10506619.61
      3817860.43     10506563.19
#Sta/Elev= 30
  4512.1  413.02  4551.8  410.95    4721  393.79  4784.1  390.14  4824.5  389.29
  4895.2  391.49  4986.1  390.31  5001.7  383.21  5004.4  382.71  5007.7  383.21
  5016.4  388.85  5056.8  391.92  5087.1  392.17  5107.3  391.22  5117.4   389.2
  5137.6  391.99  5198.2  393.01  5217.4  395.11  5238.6  400.41  5268.8  403.23
  5278.9   398.9    5298  397.53  5379.3  396.08  5413.9  399.63  5499.8  400.65
  5600.2  405.36  5720.7  408.31  5760.8  411.45  5821.1  413.37  5880.5  418.29
#Mann= 3 ,-1 , 0
  4512.1     .16       0  5001.7     .07       0  5007.7     .16       0
Bank Sta=4986.1,5056.8
XS Rating Curve= 0 ,0
Exp/Cntr=0.3,0.1

Type RM Length L Ch R = 1 ,27324   ,520,520,520
BEGIN DESCRIPTION:
SANDS BRANCH 48.0
END DESCRIPTION:
XS GIS Cut Line= 3
      3819175.58     10506328.83      3818923.81     10506189.92
      3818222.62     10506099.03
#Sta/Elev= 30
  4499.4  412.01    4553  409.41  4563.3  407.45  4597.6  404.53  4643.3  397.59
  4672.2  394.71    4694  393.85    4710  391.13  4715.7  392.65  4731.8  390.08
  4737.5  391.69  4768.9  389.11  4775.3  387.59    4781  388.21  4801.3  386.06
  4978.5  388.67  4983.6  388.34  4999.9  380.35  5002.7  379.85  5005.9  380.35
    5013  386.09  5023.1  387.49  5033.2  387.07  5093.7  392.69    5137     393
  5285.3  400.97  5315.5  403.56  5396.2   407.5  5406.3  409.07    5494  414.73
#Mann= 3 ,-1 , 0
  4499.4     .16       0  4999.9     .07       0  5005.9     .16       0
Bank Sta=4978.5,5023.1
XS Rating Curve= 0 ,0
Exp/Cntr=0.3,0.1

Type RM Length L Ch R = 1 ,26804   ,302,302,302
BEGIN DESCRIPTION:
SANDS BRANCH 47.0
END DESCRIPTION:
XS GIS Cut Line= 4
      3819275.36      10506276.7      3819101.77     10505907.81
      3818732.84     10505664.75       3818129.5     10505703.82
#Sta/Elev= 30
  4215.8  411.29  4502.1  397.64  4593.3  395.91  4598.8  394.61  4638.1  392.71
  4681.4  387.44  4745.8  384.81  4877.1   384.9  4898.2  383.34  4955.4  384.26
  4985.3   382.2  4994.5  377.47  4997.3  376.97  5000.5  377.47  5012.6  384.68
  5021.3  385.98  5072.8  386.93  5238.9   393.9  5329.1  399.38  5339.1  398.75
  5419.3  402.39  5439.3  404.71  5466.7  404.73  5479.4  404.58  5529.5  409.32
  5589.6  412.11  5599.6  414.09  5619.7  413.62  5639.7  417.54  5669.9  418.21
#Mann= 4 ,-1 , 0
  4215.8     .16       0  4994.5     .07       0  5000.5     .16       0
  5466.7     .05       0
Bank Sta=4955.4,5021.3
XS Rating Curve= 0 ,0
Exp/Cntr=0.3,0.1

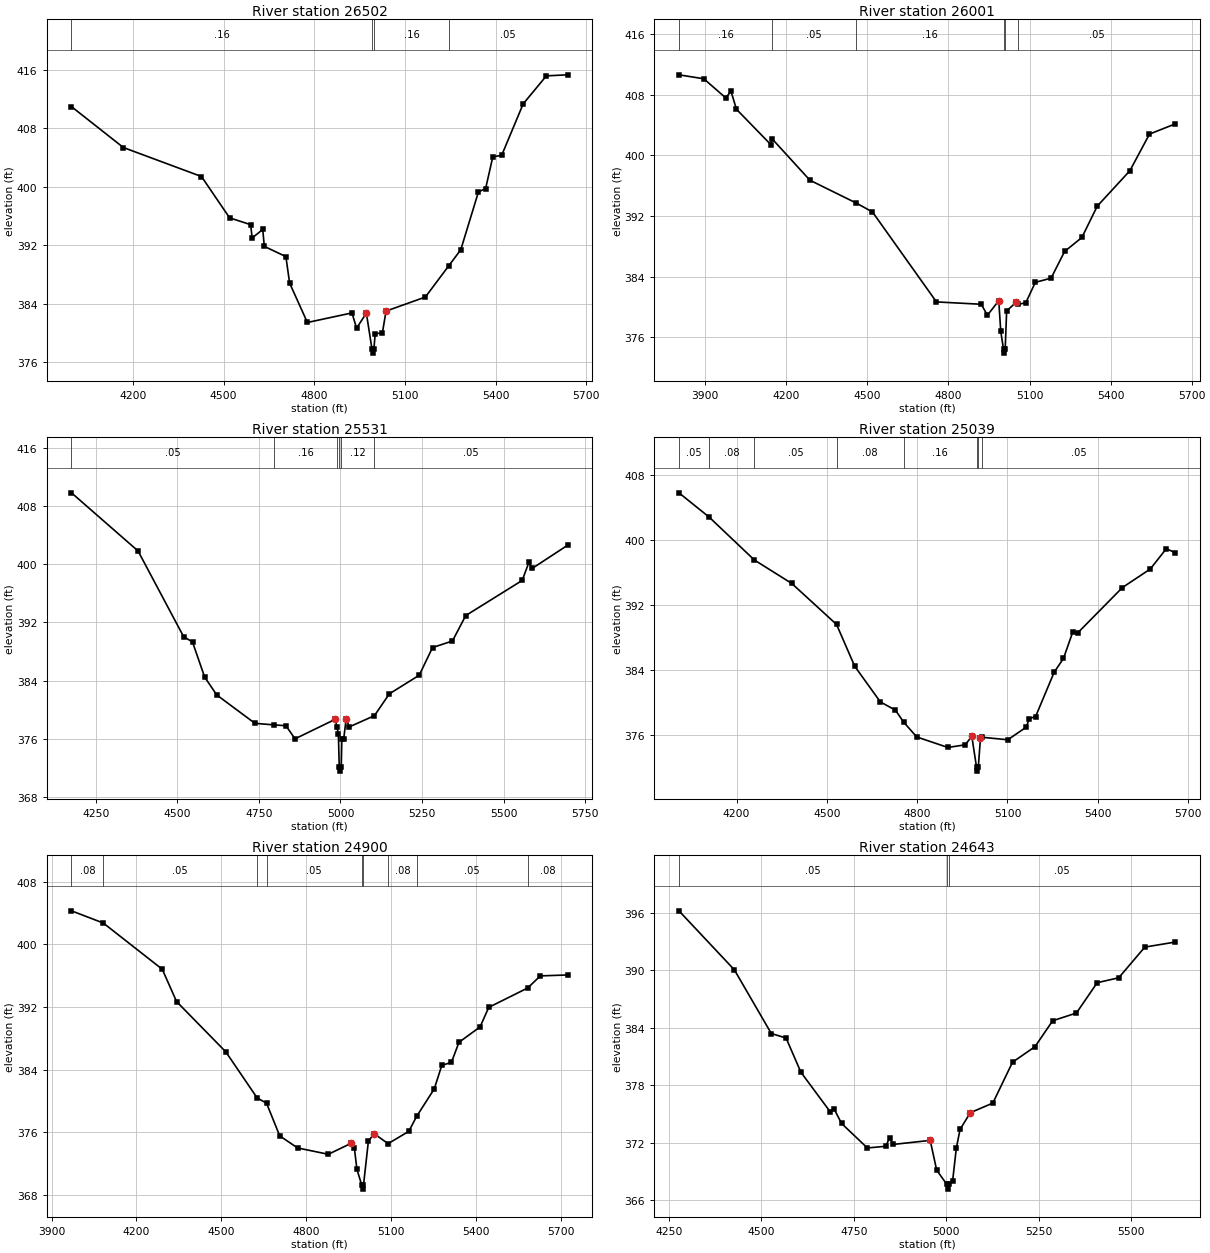
Type RM Length L Ch R = 1 ,26502   ,501,501,501
BEGIN DESCRIPTION:
SANDS BRANCH 46.0
END DESCRIPTION:
XS GIS Cut Line= 3
      3819327.45     10506215.94      3819145.17      10505530.2
      3818285.77     10505169.95
#Sta/Elev= 30
  3996.9  410.97  4168.6  405.38  4427.1  401.41  4520.2  395.76  4589.7  394.83
  4594.8  393.01  4629.8  394.17    4635  391.86  4706.4  390.46  4718.7  386.84
  4777.5  381.45  4925.1  382.76  4940.2  380.67  4972.7  382.73  4991.4  377.76
  4994.1  377.26  4997.4  377.76  5001.9  379.91  5025.7  380.03  5037.8  383.01
  5167.9  384.93    5246  389.24  5285.1   391.4  5343.5  399.31  5367.3  399.77
  5391.1  404.12  5420.3   404.3  5491.6  411.35  5568.3  415.18  5638.3  415.32
#Mann= 4 ,-1 , 0
  3996.9     .16       0  4991.4     .07       0  4997.4     .16       0
    5246     .05       0
Bank Sta=4972.7,5037.8
XS Rating Curve= 0 ,0
Exp/Cntr=0.3,0.1

Type RM Length L Ch R = 1 ,26001   ,470,470,470
BEGIN DESCRIPTION:
SANDS BRANCH 45.0
END DESCRIPTION:
XS GIS Cut Line= 3
      3819383.89     10506211.67      3819253.68     10505083.15
       3818694.2     10504662.46
#Sta/Elev= 30
  3802.4  410.61  3894.5  410.09  3975.3  407.58  3995.2  408.43  4015.3  406.07
  4143.1  401.39  4146.6   402.2  4287.1  396.72  4459.2   393.7  4518.6  392.54
  4755.5  380.68  4921.3  380.37  4944.1  378.92  4986.1  380.84  4993.5  376.79
  5003.9  374.43  5006.7  373.93  5009.9  374.43  5015.3   379.5  5050.7  380.63
  5058.6  380.37  5086.1  380.56  5121.5  383.26  5179.8  383.81  5229.8  387.33
  5293.8  389.17  5350.6   393.3  5471.4  397.97    5544   402.8  5638.4  404.13
#Mann= 6 ,-1 , 0
  3802.4     .16       0  4146.6     .05       0  4459.2     .16       0
  5003.9     .07       0  5009.9     .16       0  5058.6     .05       0
Bank Sta=4986.1,5050.7
XS Rating Curve= 0 ,0
Exp/Cntr=0.3,0.1

Type RM Length L Ch R = 1 ,25531   ,492,492,492
BEGIN DESCRIPTION:
SANDS BRANCH 44.0
END DESCRIPTION:
XS GIS Cut Line= 3
       3820165.1     10505083.13      3819449.61     10504660.19
      3818773.26     10504532.19
#Sta/Elev= 30
    4176  409.81  4379.9  401.82  4519.3  390.06  4546.8   389.3  4583.9  384.49
    4621  382.03    4738  378.13  4797.9  377.91  4832.9   377.8  4860.8     376
  4983.9  378.68  4989.2   377.6  4993.5  376.73  4996.3  372.06  4999.1  371.56
  5002.3  372.06  5004.2  375.94  5009.7  375.94  5017.3  378.69  5027.5  377.65
    5104  379.18  5149.6  382.18  5241.2  384.74  5281.9  388.54    5343  389.45
  5383.7  392.94  5556.7  397.77  5577.1  400.25  5587.3  399.42  5695.5   402.6
#Mann= 6 ,-1 , 0
    4176     .05       0  4797.9     .16       0  4989.2     .12       0
  4996.3     .07       0  5002.3     .12       0    5104     .05       0
Bank Sta=4983.9,5017.3
XS Rating Curve= 0 ,0
Exp/Cntr=0.3,0.1

Type RM Length L Ch R = 1 ,25039   ,139,139,139
BEGIN DESCRIPTION:
SANDS BRANCH 43.0
END DESCRIPTION:
XS GIS Cut Line= 4
      3820468.91     10504093.58      3819878.68     10504197.74
       3819375.2     10504262.84      3818850.02     10504393.05
#Sta/Elev= 30
  4008.5  405.84  4109.3  402.83    4259  397.55  4383.5  394.65  4532.2  389.59
  4592.4  384.44  4677.5  380.04  4727.9  379.01  4754.6  377.56  4798.5  375.71
  4902.1  374.41  4959.8  374.74  4981.5  375.79  4997.2  371.99  4999.9  371.49
  5003.2  371.99  5010.2  375.55  5015.3  375.67    5101  375.36  5162.1  376.91
  5172.8  377.98  5193.4  378.22  5255.2   383.7  5286.1   385.4    5317  388.67
  5332.8  388.53  5481.9  394.15  5574.6  396.44  5627.6  398.94  5656.6  398.47
#Mann= 8 ,-1 , 0
  4008.5     .05       0  4109.3     .08       0    4259     .05       0
  4532.2     .08       0  4754.6     .16       0  4997.2     .07       0
  5003.2     .16       0  5015.3     .05       0
Bank Sta=4981.5,5010.2
XS Rating Curve= 0 ,0
Exp/Cntr=0.3,0.1

Type RM Length L Ch R = 1 ,24900   ,257,257,257
BEGIN DESCRIPTION:
Mapping XS 63b909dd
END DESCRIPTION:
XS GIS Cut Line= 4
      3820486.34       10503946.      3819835.27     10504054.51
      3819379.54     10504123.95       3818754.6     10504228.11
#Sta/Elev= 30
  3970.2  404.29  4082.8  402.73  4291.3  396.83    4342   392.7  4516.1  386.28
  4626.9   380.4  4660.2  379.72  4706.8  375.55    4770  374.01  4878.8   373.2
  4959.7  374.61  4970.8  373.99  4979.9  371.27  4997.1  369.25  4999.9  368.75
  5003.1  369.25  5020.4  374.87  5040.6  375.83  5090.2  374.56  5163.4  376.13
    5191  378.04  5253.4  381.55    5280  384.55  5314.2  384.94  5340.8   387.5
  5415.6  389.47    5446  391.96    5584  394.44  5628.5  395.98  5724.8   396.1
#Mann= 9 ,-1 , 0
  3970.2     .08       0  4082.8     .05       0  4626.9     .08       0
  4660.2     .05       0  4997.1     .04       0  5003.1     .05       0
  5090.2     .08       0    5191     .05       0    5584     .08       0
Bank Sta=4959.7,5040.6
XS Rating Curve= 0 ,0
Exp/Cntr=0.3,0.1

Type RM Length L Ch R = 1 ,24643   ,481,481,481
BEGIN DESCRIPTION:
SANDS BRANCH 42.0
END DESCRIPTION:
XS GIS Cut Line= 4
      3820149.62     10503860.19      3819449.61     10503860.19
      3819149.61     10503910.19      3818880.46     10504115.23
#Sta/Elev= 30
  4276.9  396.18  4426.9  390.03  4526.9  383.39  4566.9  382.92  4606.9  379.36
  4686.9   375.2  4696.9  375.53  4716.9  374.02  4786.9  371.46  4836.9  371.64
  4846.9  372.52  4856.9  371.83  4956.9  372.25  4974.4  369.15  5001.8  367.67
  5004.5  367.17  5007.8  367.67  5017.5  368.01  5027.6  371.44  5037.7   373.4
  5065.6  375.14  5126.4  376.14  5179.7   380.4  5240.5  382.02  5288.3  384.72
  5352.7  385.53  5408.9  388.69  5467.1   389.2  5537.8   392.4  5619.4  392.92
#Mann= 3 ,-1 , 0
  4276.9     .05       0  5001.8     .03       0  5007.8     .05       0
Bank Sta=4956.9,5065.6
XS Rating Curve= 0 ,0
Exp/Cntr=0.3,0.1

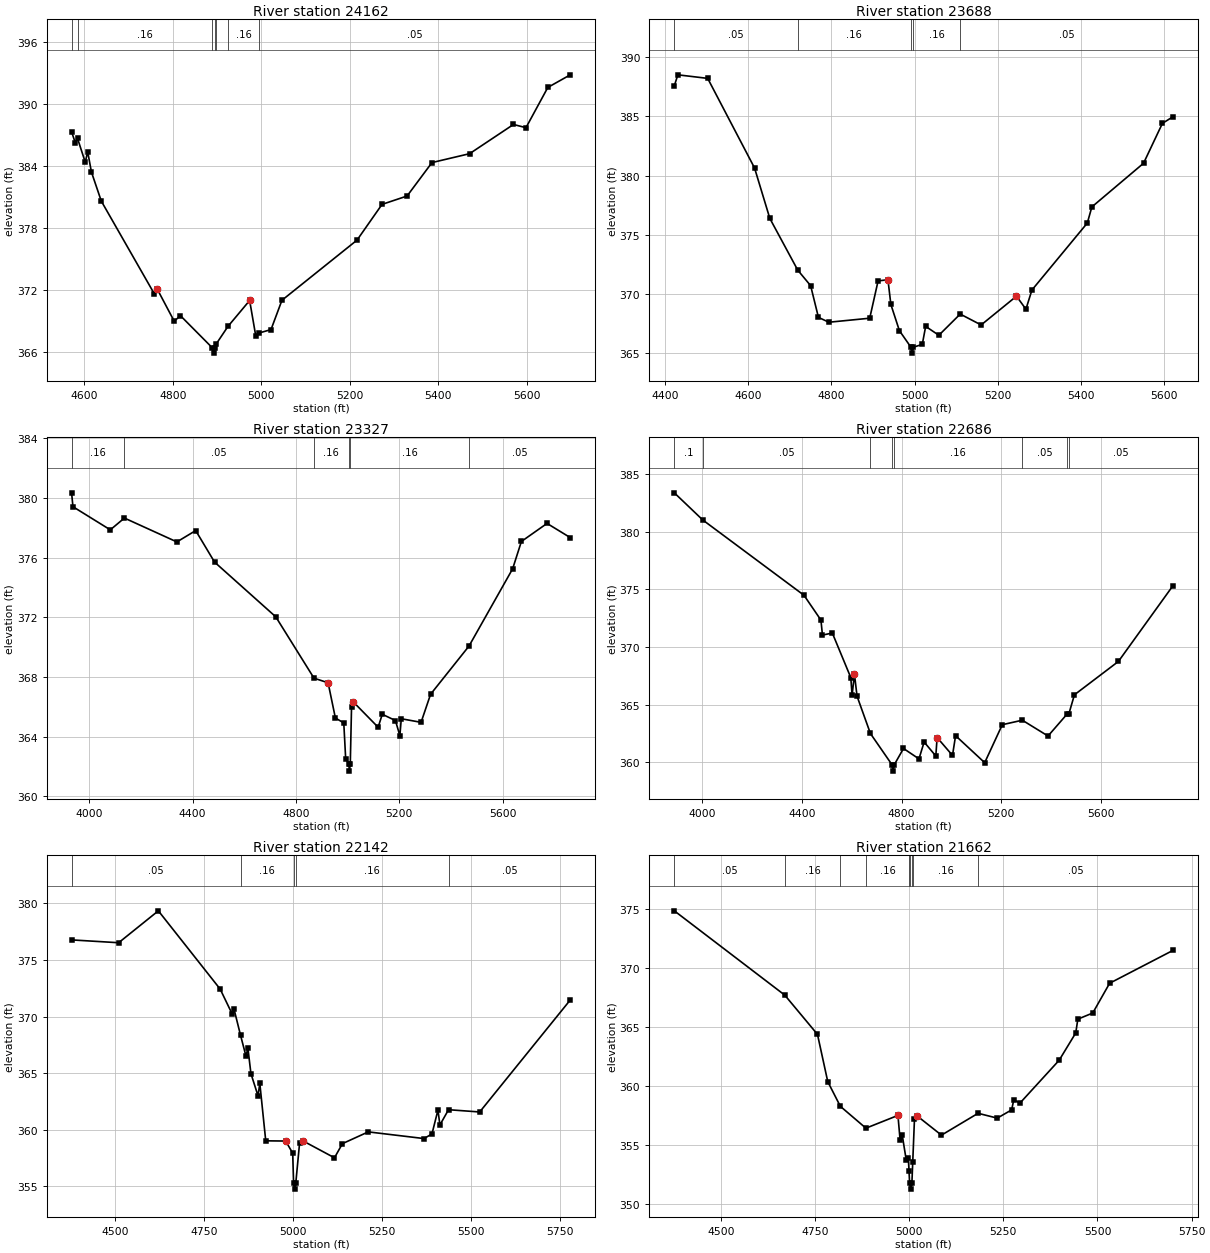
Type RM Length L Ch R = 1 ,24162   ,474,474,474
BEGIN DESCRIPTION:
SANDS BRANCH 41.0
END DESCRIPTION:
XS GIS Cut Line= 4
      3819699.65     10503260.17      3819299.61     10503460.19
      3819049.61     10503710.19      3818810.96     10503932.99
#Sta/Elev= 30
  4571.2  387.29  4579.6  386.22  4584.6  386.65    4602  384.35  4607.6  385.35
    4616   383.4  4638.3  380.58  4758.5  371.57  4764.1  372.11  4803.2  368.94
  4817.2  369.48  4889.7  366.35  4892.4  365.85  4895.7  366.35  4897.4  366.69
  4924.7  368.44  4973.7  370.95  4987.7  367.47  4994.9   367.8    5022  368.13
  5046.7  370.97  5216.5   376.8    5273  380.26  5329.6  381.07  5385.9  384.31
  5470.9  385.17  5570.1     388  5598.4  387.69  5647.8  391.59  5698.5  392.81
#Mann= 7 ,-1 , 0
  4571.2     .05       0  4584.6     .16       0  4889.7     .03       0
  4895.7     .16       0  4897.4     .05       0  4924.7     .16       0
  4994.9     .05       0
Bank Sta=4764.1,4973.7
XS Rating Curve= 0 ,0
Exp/Cntr=0.3,0.1

Type RM Length L Ch R = 1 ,23688   ,361,361,361
BEGIN DESCRIPTION:
SANDS BRANCH 40.0
END DESCRIPTION:
XS GIS Cut Line= 3
      3819817.95     10503134.38      3819249.61     10503010.19
      3818694.19      10503277.4
#Sta/Elev= 30
  4422.8  387.59  4431.3  388.52    4503  388.22  4615.6  380.65  4652.3  376.39
  4719.4  372.02  4750.3  370.71  4769.1  368.03  4794.2  367.62  4892.3  367.96
  4912.4  371.11  4936.1  371.21  4943.1  369.12  4963.6  366.91  4991.3  365.51
  4994.1  365.01  4997.3  365.51  5018.6  365.75  5026.7  367.27  5058.4  366.52
  5109.7  368.31    5160  367.39  5244.9  369.82  5267.6  368.72    5282  370.34
  5415.1     376    5426  377.36  5550.2  381.05  5595.5  384.42  5620.9  384.98
#Mann= 5 ,-1 , 0
  4422.8     .05       0  4719.4     .16       0  4991.3     .07       0
  4997.3     .16       0  5109.7     .05       0
Bank Sta=4936.1,5244.9
XS Rating Curve= 0 ,0
Exp/Cntr=0.3,0.1

Type RM Length L Ch R = 1 ,23327   ,641,641,641
BEGIN DESCRIPTION:
SANDS BRANCH 39.0
END DESCRIPTION:
XS GIS Cut Line= 3
        3820291.     10502826.21      3819453.33     10502583.15
      3818498.43      10503038.9
#Sta/Elev= 30
  3931.9  380.35  3937.1  379.42  4081.7  377.87  4136.3  378.66  4339.4  377.06
  4412.3  377.82  4485.2  375.71  4722.3  372.04  4870.2  367.93  4924.8  367.62
    4953  365.26  4985.5  364.93  4992.8  362.54  5004.7   362.2  5007.4   361.7
  5010.7   362.2  5015.5  365.98  5021.1  366.36  5118.5  364.64  5134.5  365.51
  5185.4  365.09  5202.6  364.08  5208.1  365.21  5284.7  364.97  5321.5  366.85
  5470.2  370.08  5639.2  375.26    5673  377.09  5772.3   378.3  5862.2  377.35
#Mann= 6 ,-1 , 0
  3931.9     .16       0  4136.3     .05       0  4870.2     .16       0
  5004.7     .07       0  5010.7     .16       0  5470.2     .05       0
Bank Sta=4924.8,5021.1
XS Rating Curve= 0 ,0
Exp/Cntr=0.3,0.1

Type RM Length L Ch R = 1 ,22686   ,544,544,544
BEGIN DESCRIPTION:
SANDS BRANCH 38.0
END DESCRIPTION:
XS GIS Cut Line= 3
      3820277.95     10501827.95      3819119.13     10502144.79
      3818549.59     10502710.21
#Sta/Elev= 30
  3886.9  383.35  4001.2     381    4408  374.48  4476.1  372.33  4482.2  371.03
  4521.9  371.21  4596.1  367.35  4601.3  365.83  4610.9  367.63  4621.2  365.74
  4674.9  362.51  4763.4  359.75  4766.1  359.25  4769.4  359.75  4807.9  361.21
  4870.1  360.31  4890.8  361.77  4937.8  360.56    4943  362.16  5004.8  360.61
  5017.2  362.32  5134.2  359.98  5204.9  363.27  5285.4  363.66  5388.7  362.29
    5466  364.21  5471.8  364.16  5494.8  365.86  5671.6  368.75  5890.8  375.31
#Mann= 8 ,-1 , 0
  3886.9      .1       0  4001.2     .05       0  4674.9     .16       0
  4763.4     .07       0  4769.4     .16       0  5285.4     .05       0
    5466      .1       0  5471.8     .05       0
Bank Sta=4610.9,4943
XS Rating Curve= 0 ,0
Exp/Cntr=0.3,0.1

Type RM Length L Ch R = 1 ,22142   ,480,480,480
BEGIN DESCRIPTION:
SANDS BRANCH 37.0
END DESCRIPTION:
XS GIS Cut Line= 3
      3819943.78     10501589.23      3819349.61     10501760.19
      3818649.61     10502110.19
#Sta/Elev= 30
  4377.5  376.78  4509.7  376.53  4621.2  379.35  4794.9  372.43  4828.6  370.23
  4833.8  370.66  4852.2  368.34  4867.5  366.49  4872.7  367.24  4881.3  364.96
  4901.1  363.01  4906.3  364.09  4922.9  359.02  4978.9     359  4998.6  357.93
  5001.2  355.25  5003.9  354.75  5007.2  355.25  5018.1  358.86  5026.5  359.03
    5116  357.52  5138.3  358.77    5211  359.81  5367.5  359.22  5389.9  359.63
  5406.7  361.74  5412.2  360.42  5436.4  361.77    5524  361.57  5778.4  371.47
#Mann= 5 ,-1 , 0
  4377.5     .05       0  4852.2     .16       0  5001.2     .07       0
  5007.2     .16       0  5436.4     .05       0
Bank Sta=4978.9,5026.5
XS Rating Curve= 0 ,0
Exp/Cntr=0.3,0.1

Type RM Length L Ch R = 1 ,21662   ,585,585,585
BEGIN DESCRIPTION:
SANDS BRANCH 36.0
END DESCRIPTION:
XS GIS Cut Line= 4
      3819673.15     10501488.13      3819294.64     10501423.89
      3818662.69      10501760.7      3818562.01     10501960.32
#Sta/Elev= 30
  4376.8  374.83  4670.1  367.69  4756.8  364.37  4784.1  360.37  4817.5  358.28
  4885.4  356.43  4970.4  357.51  4976.1  355.43  4981.7  355.86  4992.4  353.73
    4998   353.9  4999.7  352.84  5001.4  351.77  5004.1  351.27  5007.4  351.77
  5009.7  353.59  5014.3  357.24    5020   357.5  5085.9  355.84  5183.1  357.69
    5234  357.28  5272.2  357.98  5277.9  358.84  5294.2  358.55  5398.3  362.18
  5442.3  364.49  5447.9  365.66  5487.5  366.18  5532.3   368.7  5700.4  371.48
#Mann= 9 ,-1 , 0
  4376.8     .05       0  4670.1     .16       0  4817.5     .05       0
  4885.4     .16       0  4999.7     .12       0  5001.4     .07       0
  5007.4     .12       0  5009.7     .16       0  5183.1     .05       0
Bank Sta=4970.4,5020
XS Rating Curve= 0 ,0
Exp/Cntr=0.3,0.1

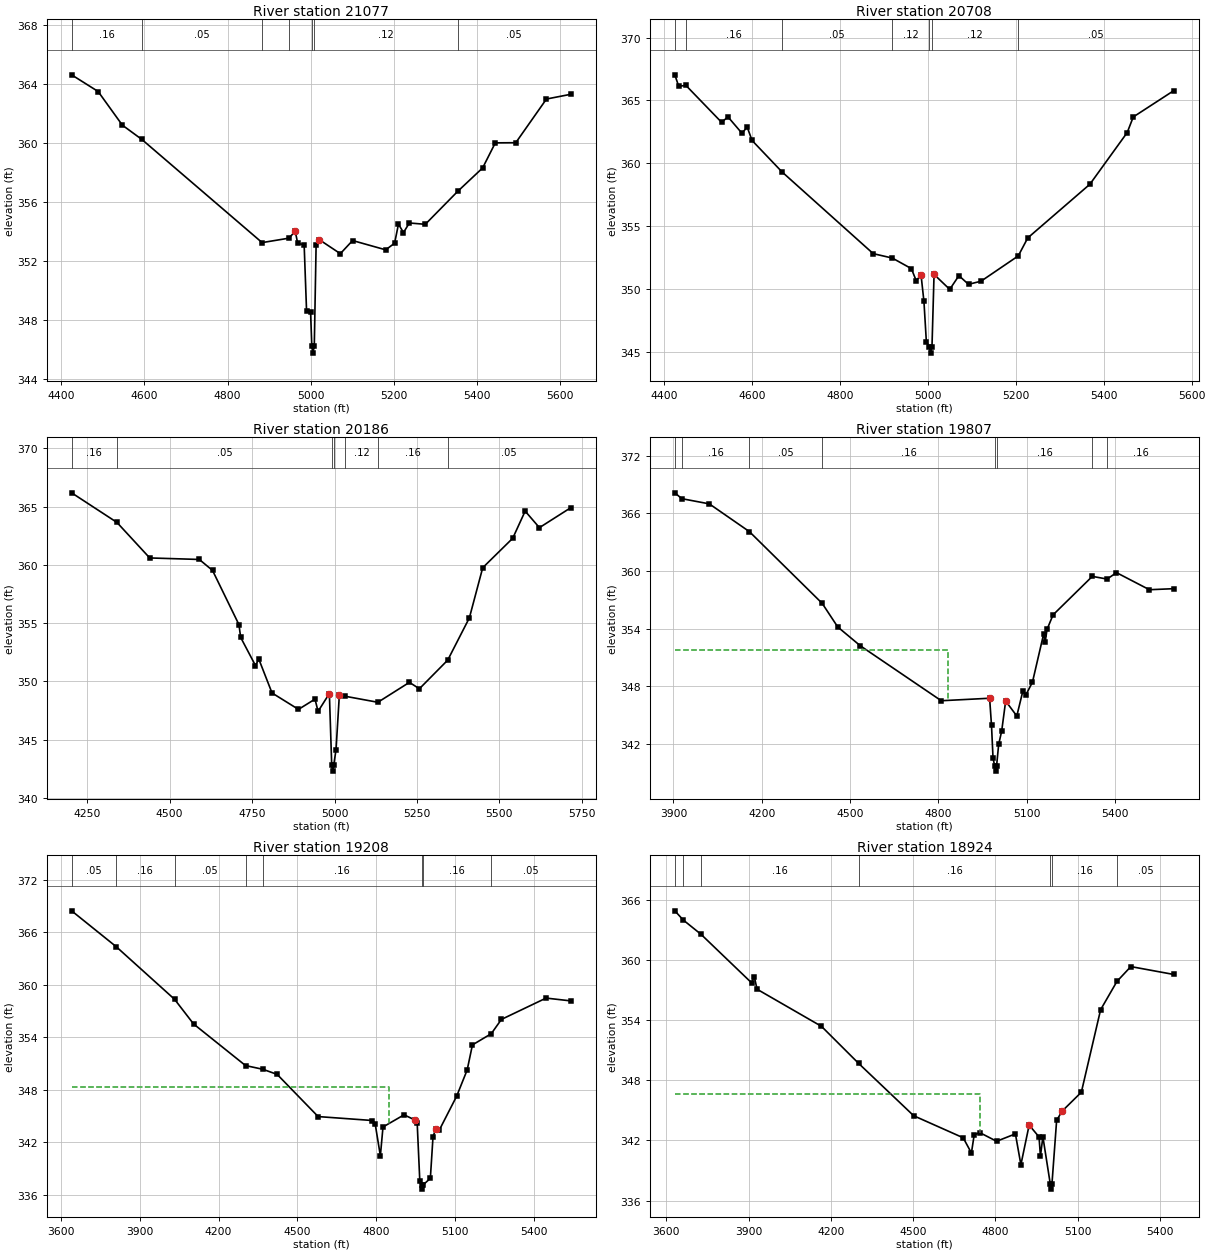
Type RM Length L Ch R = 1 ,21077   ,369,369,369
BEGIN DESCRIPTION:
SANDS BRANCH 35.0
END DESCRIPTION:
XS GIS Cut Line= 2
      3819454.37     10500717.28      3818423.96     10501334.84
#Sta/Elev= 30
  4424.6  364.62  4488.4  363.49  4546.7  361.21  4593.7  360.24  4883.1  353.25
  4947.6  353.55  4962.9  354.02  4968.7   353.2  4984.3   353.1  4990.1  348.62
  4999.8  348.52  5002.7  346.26  5005.4  345.76  5008.7  346.26  5013.1   353.1
  5021.2  353.44  5071.4   352.5  5100.9  353.39  5180.6  352.76    5202  353.21
  5211.3   354.5  5223.4  353.93  5237.5  354.58  5275.9  354.49  5353.8  356.72
  5413.9  358.31  5444.4  360.01  5493.7  360.02  5567.5  362.98  5625.9   363.3
#Mann= 7 ,-1 , 0
  4424.6     .16       0  4593.7     .05       0  4883.1     .16       0
  4947.6     .12       0  5002.7     .07       0  5008.7     .12       0
  5353.8     .05       0
Bank Sta=4962.9,5021.2
XS Rating Curve= 0 ,0
Exp/Cntr=0.3,0.1

Type RM Length L Ch R = 1 ,20708   ,522,522,522
BEGIN DESCRIPTION:
SANDS BRANCH 34.0
END DESCRIPTION:
XS GIS Cut Line= 3
      3819299.58      10500460.2      3818749.61     10500710.19
      3818399.62     10501110.17
#Sta/Elev= 30
  4424.1  367.04  4432.9  366.13  4449.3   366.2  4530.6  363.26  4544.9   363.7
  4576.7   362.4  4588.8  362.88  4599.8  361.82    4668  359.32  4875.5  352.82
  4918.9  352.47  4962.3  351.63  4973.3  350.67  4984.3  351.13  4990.9  349.02
  4996.4  345.82  5003.2  345.41    5006  344.91  5009.2  345.41  5013.9  351.17
  5049.6  349.98  5070.5  351.07  5092.3  350.38  5120.8  350.63  5205.5  352.64
  5227.1  354.07  5368.5  358.34  5453.4  362.45  5467.2  363.69  5559.7  365.79
#Mann= 7 ,-1 , 0
  4424.1     .05       0  4449.3     .16       0    4668     .05       0
  4918.9     .12       0  5003.2     .07       0  5009.2     .12       0
  5205.5     .05       0
Bank Sta=4984.3,5013.9
XS Rating Curve= 0 ,0
Exp/Cntr=0.3,0.1

Type RM Length L Ch R = 1 ,20186   ,379,379,379
BEGIN DESCRIPTION:
SANDS BRANCH 33.0
END DESCRIPTION:
XS GIS Cut Line= 3
      3819225.93     10500222.04       3818475.9     10500270.65
      3818364.79      10501024.1
#Sta/Elev= 30
  4202.9  366.18  4340.3  363.64  4439.7  360.59    4590  360.46  4630.1  359.52
  4710.3  354.86  4715.4  353.77  4760.4  351.35  4770.4  351.91  4810.5     349
  4890.7  347.59  4940.8  348.47  4950.1  347.42  4984.4  348.95  4991.5  342.79
  4994.2  342.29  4997.5  342.79  5004.6  344.14  5014.7  348.85  5031.7  348.72
  5131.4   348.2    5227  349.91  5257.3  349.36  5343.2  351.82  5408.9  355.45
  5449.3  359.75  5540.3  362.28    5578  364.61  5621.2  363.19  5716.1   364.9
#Mann= 7 ,-1 , 0
  4202.9     .16       0  4340.3     .05       0  4991.5     .03       0
  4997.5     .05       0  5031.7     .12       0  5131.4     .16       0
  5343.2     .05       0
Bank Sta=4984.4,5014.7
XS Rating Curve= 0 ,0
Exp/Cntr=0.3,0.1

Type RM Length L Ch R = 1 ,19807   ,599,599,599
BEGIN DESCRIPTION:
SANDS BRANCH 32.0
END DESCRIPTION:
XS GIS Cut Line= 3
      3819343.93     10500250.03       3818687.7       10499974.
      3817729.37     10500192.74
#Sta/Elev= 30
  3904.9  368.13  3928.7  367.52    4022  366.98  4158.1  364.09  4405.3  356.62
  4458.2  354.16  4534.9   352.2  4809.8  346.48  4973.9  346.74  4980.3  343.91
  4985.5  340.51  4991.4  339.65  4994.1  339.15  4997.4  339.65  5004.6  341.93
  5014.9  343.33  5028.4  346.45  5066.2  344.89  5086.7  347.48    5097  347.08
  5119.5  348.43  5157.4  353.44  5162.5  352.57  5168.8   353.9  5189.3  355.42
  5322.6  359.43  5372.9  359.15  5404.7  359.82  5516.6  358.04  5599.8  358.15
#Mann= 8 ,-1 , 0
  3904.9     .05       0  3928.7     .16       0  4158.1     .05       0
  4405.3     .16       0  4991.4     .07       0  4997.4     .16       0
  5322.6     .05       0  5372.9     .16       0
#XS Ineff= 2 , 0
         4830.91  351.78
Permanent Ineff=
       F       F
Bank Sta=4973.9,5028.4
XS Rating Curve= 0 ,0
Exp/Cntr=0.3,0.1

Type RM Length L Ch R = 1 ,19208   ,284,284,284
BEGIN DESCRIPTION:
SANDS BRANCH 31.0
END DESCRIPTION:
XS GIS Cut Line= 3
      3819448.15     10500062.55      3818536.66     10499630.25
      3817646.02     10499572.95
#Sta/Elev= 30
  3640.2  368.47  3809.8  364.38  4032.4  358.36  4104.9  355.54  4302.7  350.79
  4369.1  350.36  4423.2  349.78  4579.3  344.96  4786.4  344.51  4796.4  344.16
  4816.4  340.48  4826.4  343.77  4906.6  345.16  4946.7  344.59  4956.7  344.19
  4966.7  337.55  4973.7  337.17  4976.5  336.67  4979.7  337.17  5006.8   337.9
  5016.8  342.59  5026.8  343.57  5040.6   343.4    5107  347.29  5147.1  350.29
  5167.1  353.15  5238.9  354.43  5277.4  356.06  5447.7   358.5  5541.5  358.18
#Mann= 8 ,-1 , 0
  3640.2     .05       0  3809.8     .16       0  4032.4     .05       0
  4302.7     .16       0  4369.1     .16       0  4973.7     .07       0
  4979.7     .16       0  5238.9     .05       0
#XS Ineff= 2 , 0
         4848.01  348.32
Permanent Ineff=
       F       F
Bank Sta=4946.7,5026.8
XS Rating Curve= 0 ,0
Exp/Cntr=0.3,0.1

Type RM Length L Ch R = 1 ,18924   ,656,656,656
BEGIN DESCRIPTION:
SANDS BRANCH 30.0
END DESCRIPTION:
XS GIS Cut Line= 2
      3819588.71     10499468.78      3817772.81     10499354.32
#Sta/Elev= 30
  3631.2  364.94    3662  364.02  3726.4   362.6  3910.9  357.75  3920.9  358.36
  3930.9  357.11  4165.8   353.4  4301.6  349.69    4502  344.47  4682.4  342.27
  4712.4  340.75  4722.5  342.55  4742.5  342.79  4804.3  341.92  4872.8  342.66
  4892.8  339.58  4922.9  343.54    4959  342.35    4964  340.43    4973  342.37
    5000  337.64  5002.8  337.14    5006  337.64  5023.1  344.01  5043.1  344.93
  5113.2  346.82  5183.4  355.06    5243  357.89  5293.6  359.37  5450.7  358.58
#Mann= 7 ,-1 , 0
  3631.2      .1       0    3662     .05       0  3726.4     .16       0
  4301.6     .16       0    5000     .07       0    5006     .16       0
    5243     .05       0
#XS Ineff= 2 , 0
         4745.45  346.68
Permanent Ineff=
       F       F
Bank Sta=4922.9,5043.1
XS Rating Curve= 0 ,0
Exp/Cntr=0.3,0.1

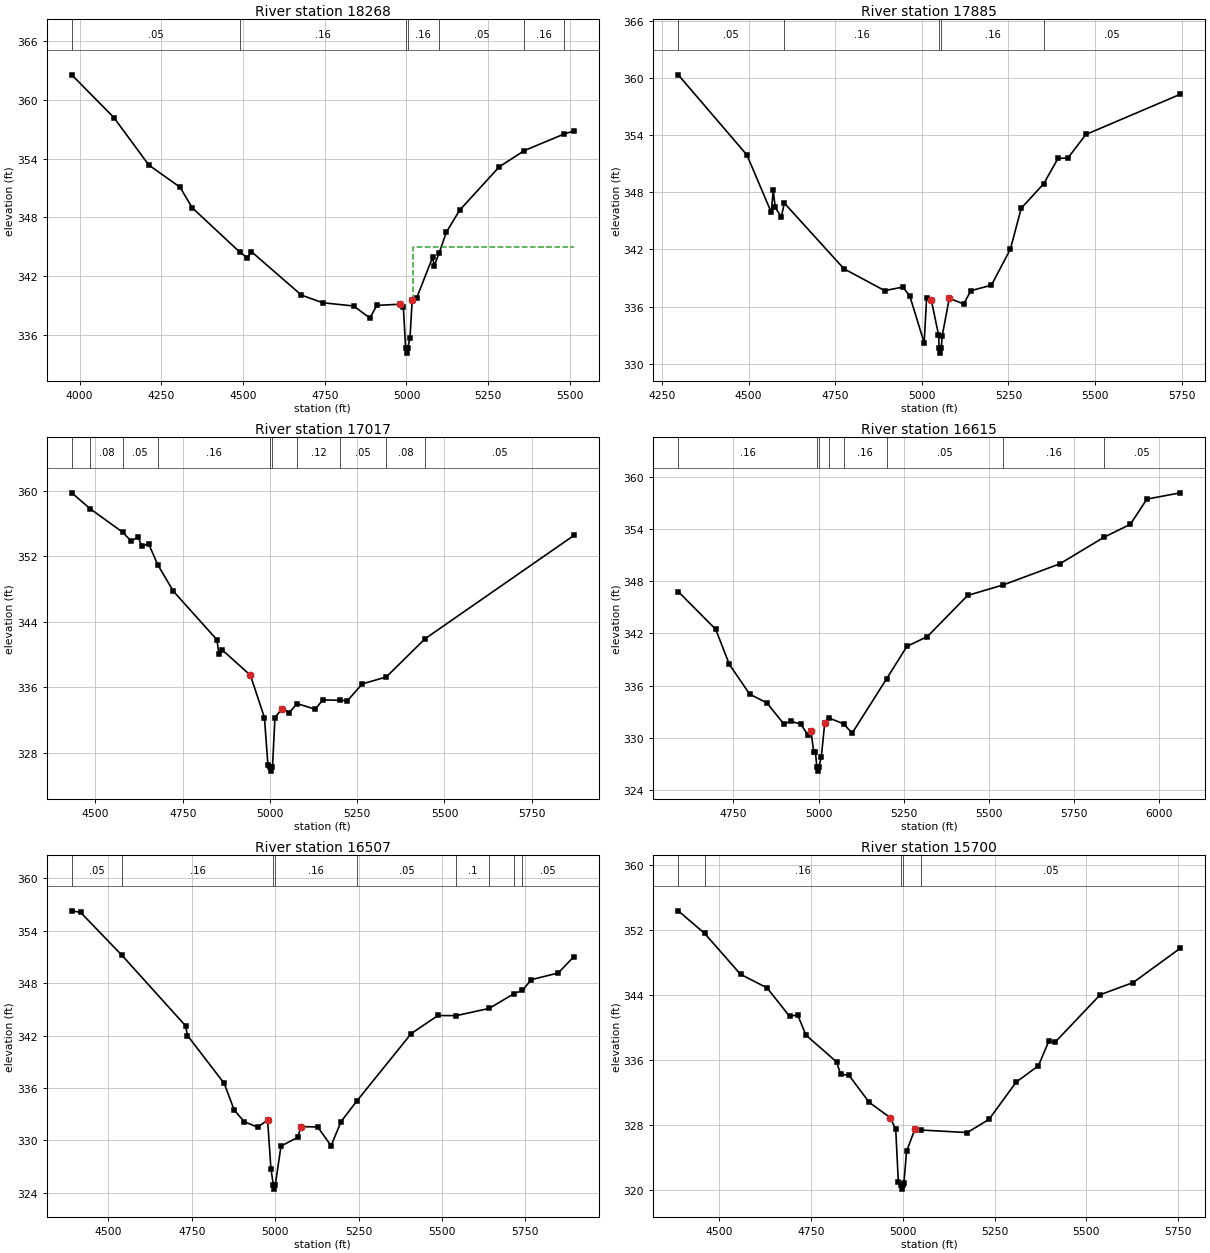
Type RM Length L Ch R = 1 ,18268   ,383,383,383
BEGIN DESCRIPTION:
SANDS BRANCH 29.0
END DESCRIPTION:
XS GIS Cut Line= 3
      3819151.22     10498416.72      3818489.79     10498812.54
      3817734.55     10498932.33
#Sta/Elev= 30
  3976.3  362.57  4105.1   358.2    4212  353.34  4307.4  351.08  4344.3  348.99
  4489.4  344.46  4513.5  343.85  4525.9  344.48  4678.8  340.04  4744.3  339.26
  4838.4  338.93  4887.9   337.7  4909.3  338.99  4980.2  339.11  4990.3  338.83
  4997.4  334.61  5000.2  334.11  5003.4  334.61  5010.6  335.63  5017.5  339.55
  5030.8  339.72  5079.8  343.91  5084.9  343.05  5099.8  344.34  5121.9  346.48
  5162.4  348.72  5283.9  353.17  5360.4  354.82  5481.5  356.51  5511.8  356.83
#Mann= 7 ,-1 , 0
  3976.3     .05       0  4489.4     .16       0  4997.4     .07       0
  5003.4     .16       0  5099.8     .05       0  5360.4     .16       0
  5481.5     .05       0
#XS Ineff= 2 , 0
                         5019.09          344.98
Permanent Ineff=
       F       F
Bank Sta=4980.2,5017.5
XS Rating Curve= 0 ,0
Exp/Cntr=0.3,0.1

Type RM Length L Ch R = 1 ,17885   ,868,868,868
BEGIN DESCRIPTION:
SANDS BRANCH 28.0
END DESCRIPTION:
XS GIS Cut Line= 3
      3819036.65      10498286.5      3818494.99     10498520.87
      3817666.91     10498750.03
#Sta/Elev= 30
  4296.8  360.32  4495.1  351.91  4565.5  345.88    4571  348.23  4576.9   346.4
  4594.4  345.39  4602.9  346.87  4775.2  339.97  4892.6  337.68  4945.2  338.05
  4965.2  337.12  5006.7  332.21  5013.8  336.88  5027.5  336.66  5048.1  333.07
  5050.3  331.62    5053  331.12  5056.3  331.62  5058.6   332.9  5079.3  336.87
  5120.8  336.28  5141.6  337.67  5200.9  338.25  5255.7  342.03  5286.9  346.32
  5351.8  348.89  5393.2  351.55  5421.7  351.59  5473.6  354.06  5746.2  358.28
#Mann= 5 ,-1 , 0
  4296.8     .05       0  4602.9     .16       0  5050.3     .07       0
  5056.3     .16       0  5351.8     .05       0
Bank Sta=5027.5,5079.3
XS Rating Curve= 0 ,0
Exp/Cntr=0.3,0.1

Type RM Length L Ch R = 1 ,17017   ,402,402,402
BEGIN DESCRIPTION:
SANDS BRANCH 27.0
END DESCRIPTION:
XS GIS Cut Line= 3
      3818968.95     10497984.41      3818281.45     10498052.12
      3817750.17     10498578.19
#Sta/Elev= 30
  4432.2  359.73  4484.8  357.79  4577.6  354.93  4602.4  353.84  4622.5  354.33
  4632.5  353.23  4652.6  353.49  4678.5  350.95  4722.9  347.73  4848.4  341.77
  4853.6  340.03  4863.6  340.53    4944  337.45  4984.2  332.28  4994.3  326.47
  5001.3  326.24  5004.1  325.74  5007.3  326.24  5014.3  332.27  5034.4  333.38
  5055.9   332.9  5077.4  333.99    5130   333.3  5151.3  334.44  5201.4  334.39
    5222  334.34  5264.4  336.39  5333.3  337.24  5444.5  341.91  5870.7  354.52
#Mann= 10 ,-1 , 0
  4432.2     .05       0  4484.8     .08       0  4577.6     .05       0
  4678.5     .16       0  5001.3     .07       0  5007.3     .16       0
  5077.4     .12       0  5201.4     .05       0  5333.3     .08       0
  5444.5     .05       0
Bank Sta=4944,5034.4
XS Rating Curve= 0 ,0
Exp/Cntr=0.3,0.1

Type RM Length L Ch R = 1 ,16615   ,108,108,108
BEGIN DESCRIPTION:
SANDS BRANCH 26.0
END DESCRIPTION:
XS GIS Cut Line= 4
      3818649.61     10497810.19      3818249.61     10497810.19
      3817749.61     10497860.19      3817198.11     10498010.46
#Sta/Elev= 30
  4587.9   346.8  4697.9  342.47  4737.9  338.45  4797.9  335.02  4847.9  334.04
  4897.9  331.61  4917.9  331.93  4947.9  331.58  4967.9  330.39  4977.9  330.77
  4985.4  328.45  4990.4  328.45  4994.9   326.7  4997.7   326.2  5000.9   326.7
    5008  327.82    5018  331.73  5030.6  332.29  5073.8  331.62  5098.4  330.55
    5200  336.81  5259.2  340.51  5319.5  341.64  5437.6  346.36  5542.7  347.57
    5708  349.98  5837.3  353.02  5915.3  354.52  5963.9  357.41    6062  358.13
#Mann= 8 ,-1 , 0
  4587.9     .16       0  4994.9     .07       0  5000.9     .16       0
  5030.6     .12       0  5073.8     .16       0    5200     .05       0
  5542.7     .16       0  5837.3     .05       0
Bank Sta=4977.9,5018
XS Rating Curve= 0 ,0
Exp/Cntr=0.3,0.1

Type RM Length L Ch R = 1 ,16507   ,807,807,807
BEGIN DESCRIPTION:
SANDS BRANCH 25.0
END DESCRIPTION:
XS GIS Cut Line= 2
      3818896.06     10497687.54      3817392.68     10497765.57
#Sta/Elev= 30
  4389.9  356.26  4416.4  356.08  4540.4  351.17  4731.1  343.11  4736.8     342
    4847  336.52    4877  333.47    4907  332.14  4947.1  331.52  4977.1  332.32
  4987.1  326.75  4994.2  324.93  4996.9  324.43  5000.2  324.93  5017.2  329.35
  5067.3  330.35  5077.3  331.58  5127.3  331.54  5167.4  329.39  5197.4  332.16
  5244.7  334.51  5407.7  342.22  5487.8  344.29  5542.3  344.27  5641.5   345.1
  5716.1  346.79  5740.7  347.17  5768.2  348.39  5848.3  349.15  5895.3  351.01
#Mann= 9 ,-1 , 0
  4389.9     .05       0  4540.4     .16       0  4994.2     .07       0
  5000.2     .16       0  5244.7     .05       0  5542.3      .1       0
  5641.5     .07       0  5716.1     .08       0  5740.7     .05       0
Bank Sta=4977.1,5077.3
XS Rating Curve= 0 ,0
Exp/Cntr=0.3,0.1

Type RM Length L Ch R = 1 ,15700   ,355,355,355
BEGIN DESCRIPTION:
SANDS BRANCH 24.0
END DESCRIPTION:
XS GIS Cut Line= 2
      3818843.98     10497572.97      3817625.23     10496953.18
#Sta/Elev= 30
  4388.4  354.32  4460.3  351.54    4558  346.51  4630.3  344.84  4691.5  341.35
  4713.7  341.52    4736  339.04  4819.4  335.74  4830.8  334.21  4853.3  334.09
  4908.4  330.76  4965.5  328.88  4980.7  327.45  4987.9   320.9  4994.4  320.58
  4997.1  320.08  5000.4  320.58    5003  320.89  5010.3  324.73  5032.8  327.46
  5049.9  327.35  5175.4  327.04  5234.7  328.66  5308.8  333.25  5369.3  335.26
  5397.8  338.31  5414.2  338.13  5537.6     344  5627.4   345.5  5755.7  349.72
#Mann= 5 ,-1 , 0
  4388.4     .05       0  4460.3     .16       0  4994.4     .07       0
  5000.4     .16       0  5049.9     .05       0
Bank Sta=4965.5,5032.8
XS Rating Curve= 0 ,0
Exp/Cntr=0.3,0.1