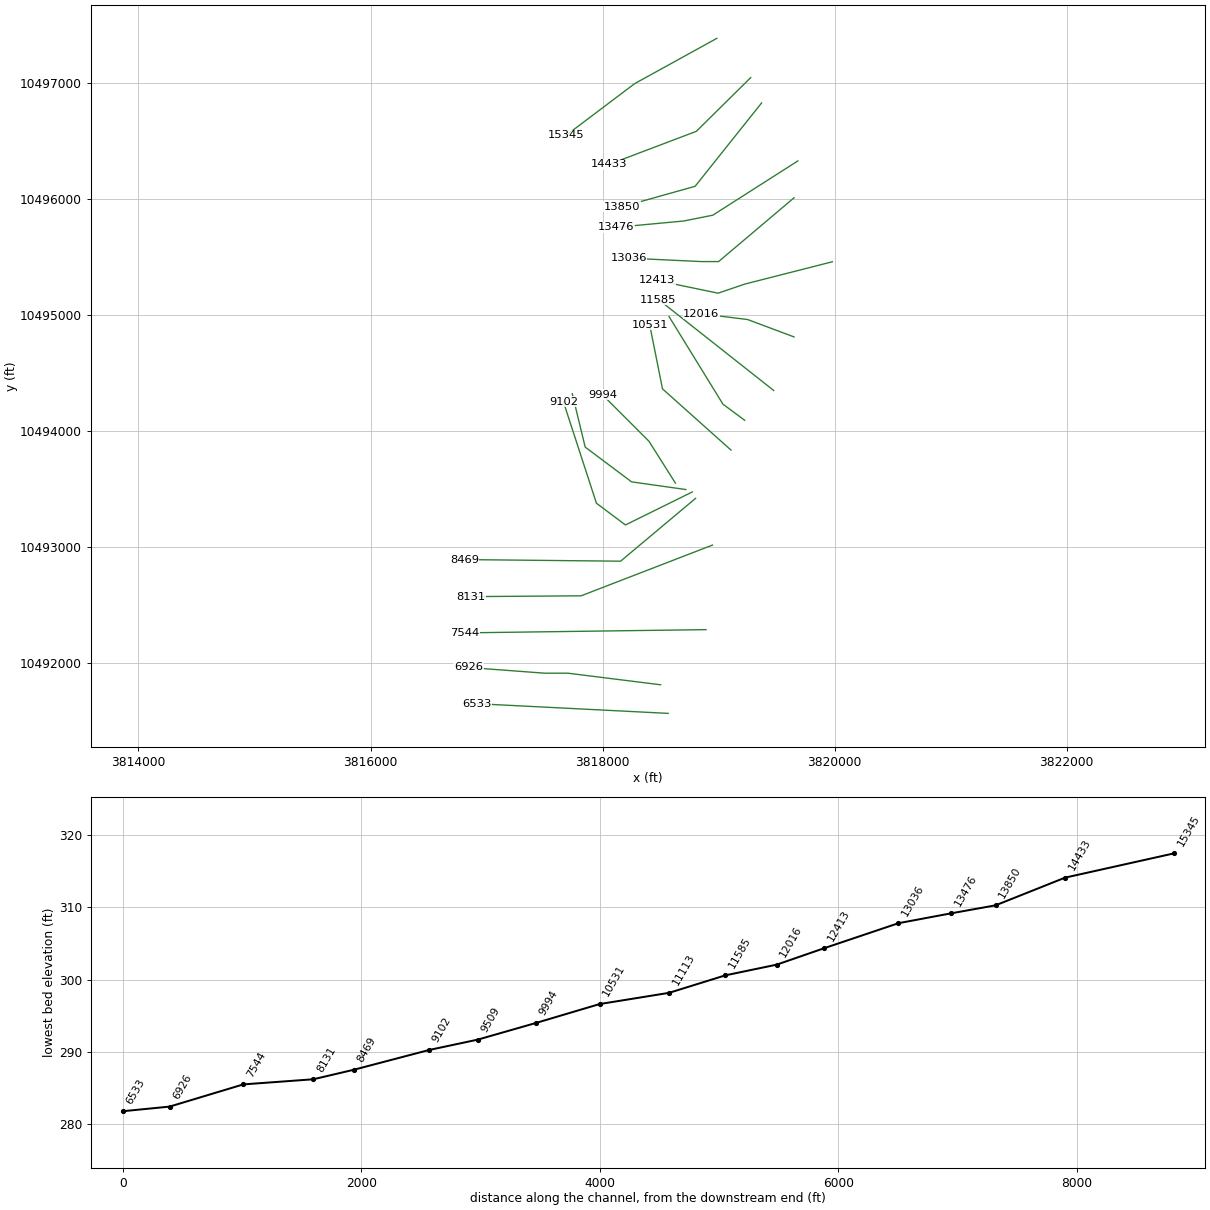
HEC-RAS study SANDS BRANCH.prj: SANDS BRANCH Base Level Engineering

--- SANDS BRANCH.g01 (geometry) --- (continued)

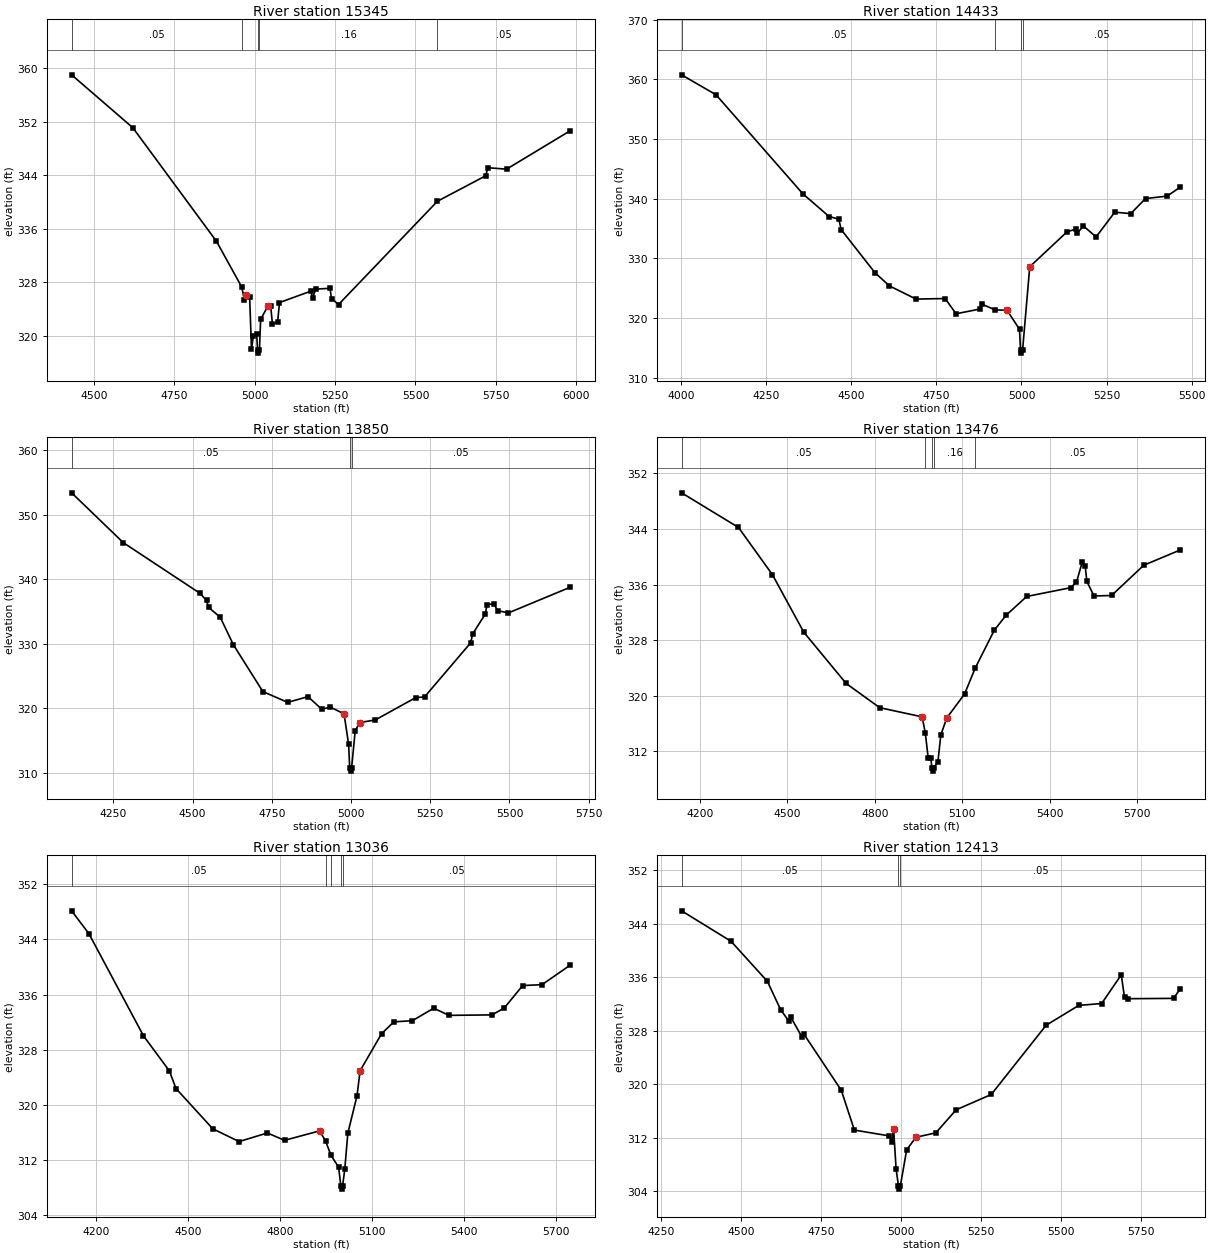
Type RM Length L Ch R = 1 ,15345   ,912,912,912
BEGIN DESCRIPTION:
SANDS BRANCH 23.0
END DESCRIPTION:
XS GIS Cut Line= 3
      3818984.56     10497385.44      3818276.24     10496994.83
      3817683.56     10496547.71
#Sta/Elev= 30
  4430.3  358.96  4620.8  351.07    4881  334.13  4959.5  327.32  4968.1   325.4
  4973.8  326.13  4984.1  325.85  4989.9  318.04  4995.6  319.99  5005.9  320.38
  5008.6  317.96  5011.4  317.46  5014.6  317.96  5018.4  322.51  5041.2  324.49
  5049.5  324.47  5055.2  321.74  5071.3  322.15    5077     325  5174.4   326.7
  5180.1   325.7  5189.7  327.01    5234  327.12  5238.8  325.59  5260.7  324.71
  5568.3  340.11  5718.7  343.91  5724.9  345.11  5783.2  344.89  5981.6  350.63
#Mann= 5 ,-1 , 0
  4430.3     .05       0  4959.5     .16       0  5008.6     .07       0
  5014.6     .16       0  5568.3     .05       0
Bank Sta=4973.8,5041.2
XS Rating Curve= 0 ,0
Exp/Cntr=0.3,0.1

Type RM Length L Ch R = 1 ,14433   ,583,583,583
BEGIN DESCRIPTION:
SANDS BRANCH 22.0
END DESCRIPTION:
XS GIS Cut Line= 3
      3819276.26     10497046.92      3818807.49     10496583.37
      3818053.47     10496297.36
#Sta/Elev= 30
    4001  360.76  4102.4  357.41    4357  340.84  4434.7     337    4463  336.58
  4470.1  334.81  4569.1  327.61  4611.5  325.39  4690.1  323.17  4775.6  323.26
  4807.7  320.71    4879  321.51  4884.3   322.3  4922.9  321.35  4957.5   321.3
  4994.2   318.1  4997.2  314.61    5000  314.11  5003.2  314.61  5024.3  328.59
  5134.2  334.46    5159  334.88  5164.3  334.25  5182.1  335.42  5219.3  333.59
  5274.2  337.74  5321.1  337.49  5364.6  340.02    5428  340.43  5466.7  341.94
#Mann= 4 ,-1 , 0
    4001     .05       0  4922.9     .16       0  4997.2     .07       0
  5003.2     .05       0
Bank Sta=4957.5,5024.3
XS Rating Curve= 0 ,0
Exp/Cntr=0.3,0.1

Type RM Length L Ch R = 1 ,13850   ,374,374,374
BEGIN DESCRIPTION:
SANDS BRANCH 21.0
END DESCRIPTION:
XS GIS Cut Line= 3
        3819370.     10496828.16      3818797.08     10496109.41
      3818166.84     10495932.32
#Sta/Elev= 30
  4118.2  353.39  4281.4  345.67  4523.2  337.83    4544  336.72  4550.4  335.65
  4587.2  334.12  4628.9  329.84  4721.7  322.61  4800.2  320.93  4864.3  321.82
  4907.5  319.87  4934.7   320.2    4978  319.15  4992.4  314.42  4995.8  310.78
  4998.5  310.28  5001.8  310.78  5013.2  316.53  5027.6  317.81  5076.3   318.2
  5203.5  321.65  5232.1  321.78  5377.5  330.15  5384.2  331.56  5423.4  334.59
  5429.4  336.04  5450.2  336.23  5462.7  335.14  5496.8  334.79    5692  338.77
#Mann= 3 ,-1 , 0
  4118.2     .05       0  4995.8     .03       0  5001.8     .05       0
Bank Sta=4978,5027.6
XS Rating Curve= 0 ,0
Exp/Cntr=0.3,0.1

Type RM Length L Ch R = 1 ,13476   ,440,440,440
BEGIN DESCRIPTION:
SANDS BRANCH 20.0
END DESCRIPTION:
XS GIS Cut Line= 4
      3819682.51     10496328.17      3818949.61     10495860.19
      3818699.61     10495810.19       3818114.8     10495755.25
#Sta/Elev= 30
  4136.9  349.21  4332.2  344.23  4448.8  337.43  4556.4  329.16  4701.9  321.78
    4817   318.3  4962.5  316.98  4973.5  314.68  4983.6  311.02  4992.9     311
  4995.9  309.67  4998.6  309.17  5001.9  309.67  5016.7  310.46  5026.9   314.4
  5047.3  316.82  5108.4  320.27  5144.8  323.99  5210.4  329.45  5251.2  331.61
  5321.7   334.3  5472.3  335.56  5492.4  336.35  5512.5  339.29  5522.6  338.63
  5528.1  336.46  5552.7  334.37    5613  334.44  5723.4  338.79  5848.8  340.99
#Mann= 5 ,-1 , 0
  4136.9     .05       0  4973.5     .16       0  4995.9     .07       0
  5001.9     .16       0  5144.8     .05       0
Bank Sta=4962.5,5047.3
XS Rating Curve= 0 ,0
Exp/Cntr=0.3,0.1

Type RM Length L Ch R = 1 ,13036   ,623,623,623
BEGIN DESCRIPTION:
SANDS BRANCH 19.0
END DESCRIPTION:
XS GIS Cut Line= 4
      3819649.59     10496010.17      3818999.61     10495460.19
      3818849.61     10495460.19      3818224.34     10495489.61
#Sta/Elev= 30
  4120.2  348.14  4176.7  344.83  4354.8  330.02  4439.3  324.94  4460.8  322.39
    4581  316.55  4666.8   314.7  4759.1  315.95    4815  314.88  4929.4  316.25
  4948.9   314.8  4966.5  312.72  4991.6  310.98  4998.6  308.31  5001.4  307.81
  5004.6  308.31  5011.6  310.68  5021.6  315.91  5051.6  321.34  5061.6  324.96
  5131.7  330.33  5171.7  332.05  5232.4  332.22  5301.8  334.03  5351.9  332.99
  5492.1  333.06  5532.1  334.06  5592.2  337.31  5655.4  337.44  5747.6  340.28
#Mann= 5 ,-1 , 0
  4120.2     .05       0  4948.9     .16       0  4966.5     .05       0
  4998.6     .03       0  5004.6     .05       0
Bank Sta=4929.4,5061.6
XS Rating Curve= 0 ,0
Exp/Cntr=0.3,0.1

Type RM Length L Ch R = 1 ,12413   ,397,397,397
BEGIN DESCRIPTION:
SANDS BRANCH 18.0
END DESCRIPTION:
XS GIS Cut Line= 4
      3819979.36     10495458.37      3819224.16     10495265.66
      3818994.99     10495187.54      3818468.96     10495296.91
#Sta/Elev= 30
  4314.6  345.93  4469.2  341.38  4582.7   335.4    4624  331.18  4650.4  329.41
  4655.5  330.08  4691.3  327.04  4696.4  327.55  4813.8  319.12  4854.7  313.17
  4964.5   312.3  4972.1   311.4  4977.3  313.39  4985.2  307.32  4992.5  304.85
  4995.2  304.35  4998.5  304.85  5018.2  310.22  5047.1   312.1  5109.4  312.76
  5172.8   316.2  5282.6  318.49    5454  328.83  5556.1   331.8  5627.6  332.08
  5688.9  336.36  5699.1  333.01  5709.3   332.8  5852.3  332.85  5873.4  334.28
#Mann= 3 ,-1 , 0
  4314.6     .05       0  4992.5     .03       0  4998.5     .05       0
Bank Sta=4977.3,5047.1
XS Rating Curve= 0 ,0
Exp/Cntr=0.3,0.1

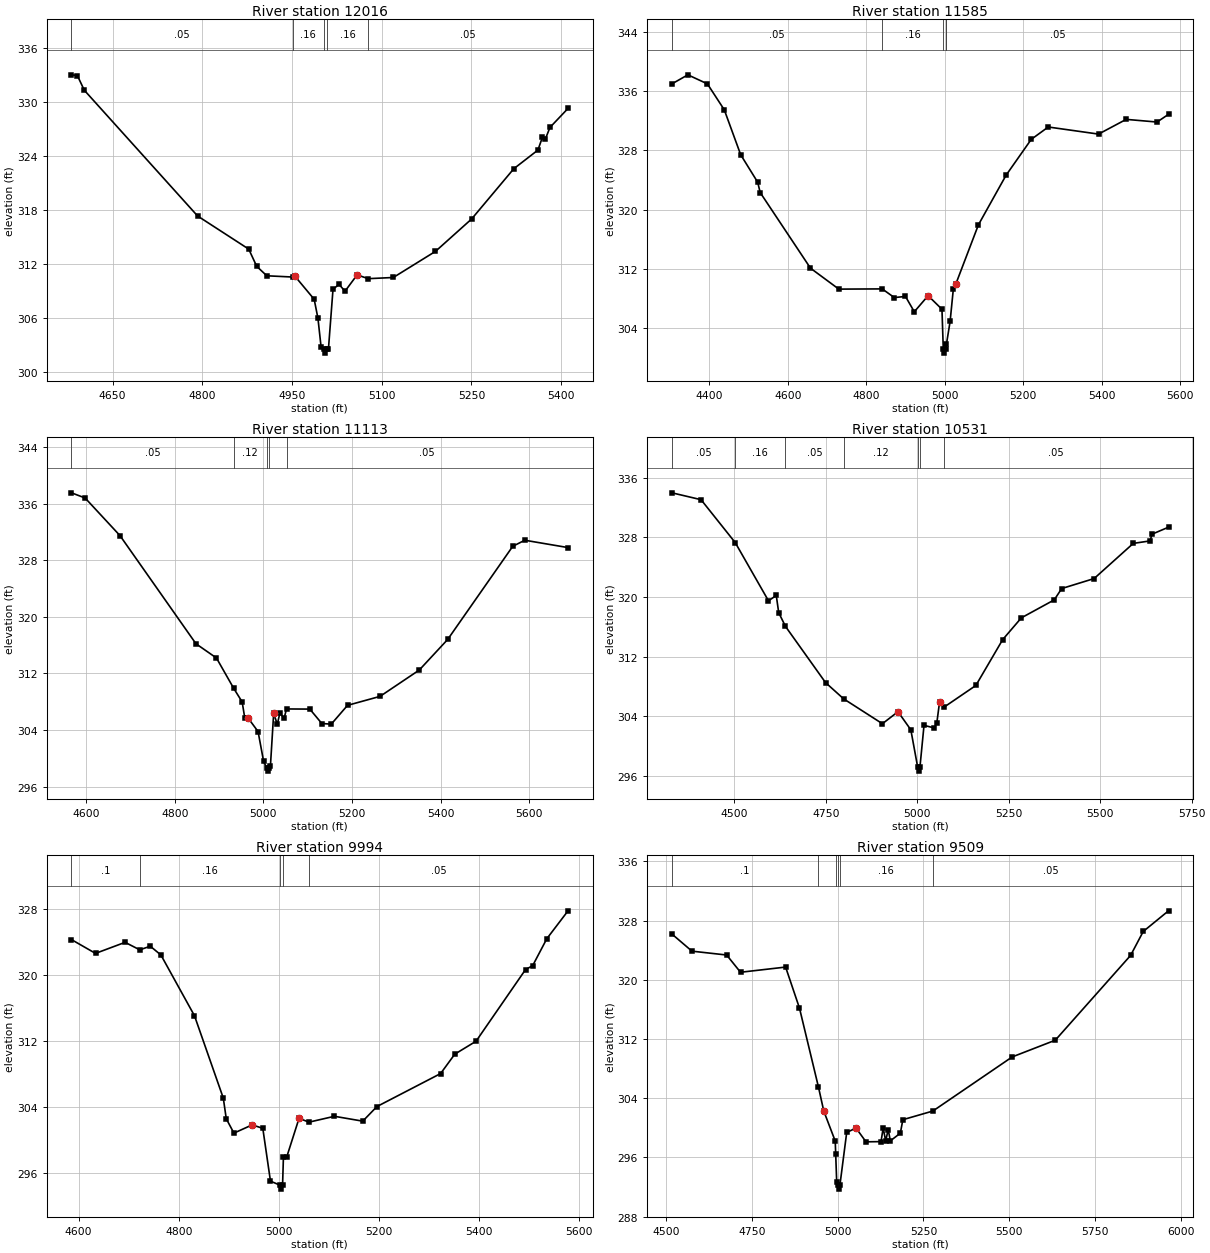
Type RM Length L Ch R = 1 ,12016   ,431,431,431
BEGIN DESCRIPTION:
SANDS BRANCH 17.0
END DESCRIPTION:
XS GIS Cut Line= 3
      3819649.61     10494810.19      3819249.61     10494960.19
      3818849.62     10495010.19
#Sta/Elev= 30
  4581.2  332.99    4591  332.91  4602.6  331.28  4792.1  317.31  4877.6  313.63
  4890.9  311.72  4907.8  310.67  4951.5  310.53    4955  310.61    4987  308.06
  4993.3  305.95  4998.6  302.74  5002.7  302.58  5005.5  302.08  5008.7  302.58
  5010.9  302.58  5018.5  309.18  5028.6  309.71  5038.6  308.96  5058.8  310.77
  5077.4  310.35  5119.3  310.48  5189.8  313.38  5250.3  316.98  5320.8  322.56
  5361.1  324.63  5368.7  326.06  5373.7  325.88  5381.3  327.15  5411.5  329.26
#Mann= 5 ,-1 , 0
  4581.2     .05       0  4951.5     .16       0  5002.7     .07       0
  5008.7     .16       0  5077.4     .05       0
Bank Sta=4955,5058.8
XS Rating Curve= 0 ,0
Exp/Cntr=0.3,0.1

Type RM Length L Ch R = 1 ,11585   ,472,472,472
BEGIN DESCRIPTION:
SANDS BRANCH 16.0
END DESCRIPTION:
XS GIS Cut Line= 2
      3819474.28      10494348.3      3818481.28     10495132.97
#Sta/Elev= 30
  4304.6  336.99  4345.2  338.21  4394.9  336.99    4438  333.48  4479.8  327.41
  4523.1   323.7  4529.5   322.3  4657.7  312.08  4729.9  309.25  4840.5  309.28
  4871.3  308.11  4899.8  308.26  4922.3  306.19  4957.5  308.36  4992.8  306.53
  4996.2   301.1  4998.9   300.6  5002.2   301.1  5004.1  301.77  5013.6   304.9
  5021.7  309.22    5028  309.92  5085.8  317.95  5156.3  324.65  5220.4  329.49
  5263.7  331.16  5391.9   330.2  5462.4  332.19    5541  331.83  5570.2  332.87
#Mann= 5 ,-1 , 0
  4304.6     .05       0  4840.5     .16       0  4996.2     .07       0
  5002.2     .16       0  5004.1     .05       0
Bank Sta=4957.5,5028
XS Rating Curve= 0 ,0
Exp/Cntr=0.3,0.1

Type RM Length L Ch R = 1 ,11113   ,582,582,582
BEGIN DESCRIPTION:
SANDS BRANCH 15.0
END DESCRIPTION:
XS GIS Cut Line= 3
      3819224.32     10494091.32      3819036.81     10494230.22
      3818572.13     10494986.17
#Sta/Elev= 30
    4567  337.57  4597.7  336.84  4676.5  331.51  4847.9  316.21  4894.2  314.19
    4933  309.91  4952.2  307.97    4958  305.73  4964.7  305.77  4988.1  303.78
  5000.6  299.56  5007.2  298.68  5009.9  298.18  5013.2  298.68    5016  298.92
  5023.3  306.34  5031.5  304.82  5037.3  306.38  5046.8  305.67  5052.4  306.98
  5104.9  306.96    5132  304.92  5153.3  304.83    5190  307.49  5263.4  308.76
    5352  312.49  5416.1  316.82  5562.9     330  5590.1  330.86  5687.7  329.82
#Mann= 5 ,-1 , 0
    4567     .05       0    4933     .12       0  5007.2     .07       0
  5013.2     .12       0  5052.4     .05       0
Bank Sta=4964.7,5023.3
XS Rating Curve= 0 ,0
Exp/Cntr=0.3,0.1

Type RM Length L Ch R = 1 ,10531   ,537,537,537
BEGIN DESCRIPTION:
SANDS BRANCH 14.0
END DESCRIPTION:
XS GIS Cut Line= 3
      3819106.27     10493834.37      3818515.97     10494362.16
      3818405.12     10494916.44
#Sta/Elev= 30
  4329.6  333.96  4409.1  333.04  4502.6  327.28  4593.4  319.48  4614.7  320.19
  4621.4  317.88  4639.9  316.04  4749.3  308.51  4798.7  306.33  4904.8  302.99
  4947.4   304.6  4982.5  302.17  5001.3  297.13    5004  296.63  5007.3  297.13
  5018.5  302.77  5046.9  302.42  5053.6  303.14  5061.1  305.94  5072.6  305.19
  5160.2  308.12  5233.5  314.27  5284.5  317.19  5374.4   319.6  5394.8  321.12
  5483.4  322.46  5590.5  327.18  5636.4  327.51  5641.5  328.41  5686.7  329.35
#Mann= 7 ,-1 , 0
  4329.6     .05       0  4502.6     .16       0  4639.9     .05       0
  4798.7     .12       0  5001.3     .07       0  5007.3     .12       0
  5072.6     .05       0
Bank Sta=4947.4,5061.1
XS Rating Curve= 0 ,0
Exp/Cntr=0.3,0.1

Type RM Length L Ch R = 1 ,9994    ,485,485,485
BEGIN DESCRIPTION:
SANDS BRANCH 13.0
END DESCRIPTION:
XS GIS Cut Line= 3
       3818627.1     10493549.64      3818399.61     10493910.19
      3817999.61     10494310.19
#Sta/Elev= 30
  4585.8  324.25  4633.8  322.58  4692.9  323.92  4722.2  323.01  4743.2  323.45
  4764.4  322.39  4831.5  315.02  4889.1  305.03    4895  302.53  4910.3  300.79
  4946.8  301.79    4968  301.37  4983.3  294.97  5001.5   294.5  5004.2     294
  5007.5   294.5  5009.2  297.88  5015.7  297.88  5040.4  302.58  5060.3  302.12
  5111.1  302.83  5167.7  302.24    5196  304.01  5323.2  308.01  5351.5  310.36
    5394  311.93  5492.9  320.62  5507.1  321.09  5535.4  324.36  5577.8  327.74
#Mann= 5 ,-1 , 0
  4585.8      .1       0  4722.2     .16       0  5001.5     .07       0
  5007.5     .16       0  5060.3     .05       0
Bank Sta=4946.8,5040.4
XS Rating Curve= 0 ,0
Exp/Cntr=0.3,0.1

Type RM Length L Ch R = 1 ,9509    ,407,407,407
BEGIN DESCRIPTION:
SANDS BRANCH 12.0
END DESCRIPTION:
XS GIS Cut Line= 4
      3818717.38      10493494.1      3818249.61     10493560.19
      3817849.61     10493860.19       3817738.2     10494320.48
#Sta/Elev= 30
  4517.7  326.17    4576  323.86    4677  323.34  4717.4  321.01  4848.7  321.71
  4889.1  316.16  4944.4  305.49  4959.8  302.26  4993.2   298.2  4994.5  296.51
  4997.4  292.73  5000.7  292.21  5003.4  291.71  5006.7  292.21  5026.6  299.37
  5053.7  299.96  5082.8   298.1  5126.6  298.13  5132.8  299.99  5140.1  298.21
  5147.4  299.76  5153.7  298.23  5182.8  299.27  5190.1  301.09  5277.5  302.26
  5508.5  309.57    5634  311.83  5853.4  323.29  5890.1  326.52  5963.7  329.31
#Mann= 6 ,-1 , 0
  4517.7      .1       0  4944.4     .12       0  4994.5     .16       0
  5000.7     .07       0  5006.7     .16       0  5277.5     .05       0
Bank Sta=4959.8,5053.7
XS Rating Curve= 0 ,0
Exp/Cntr=0.3,0.1

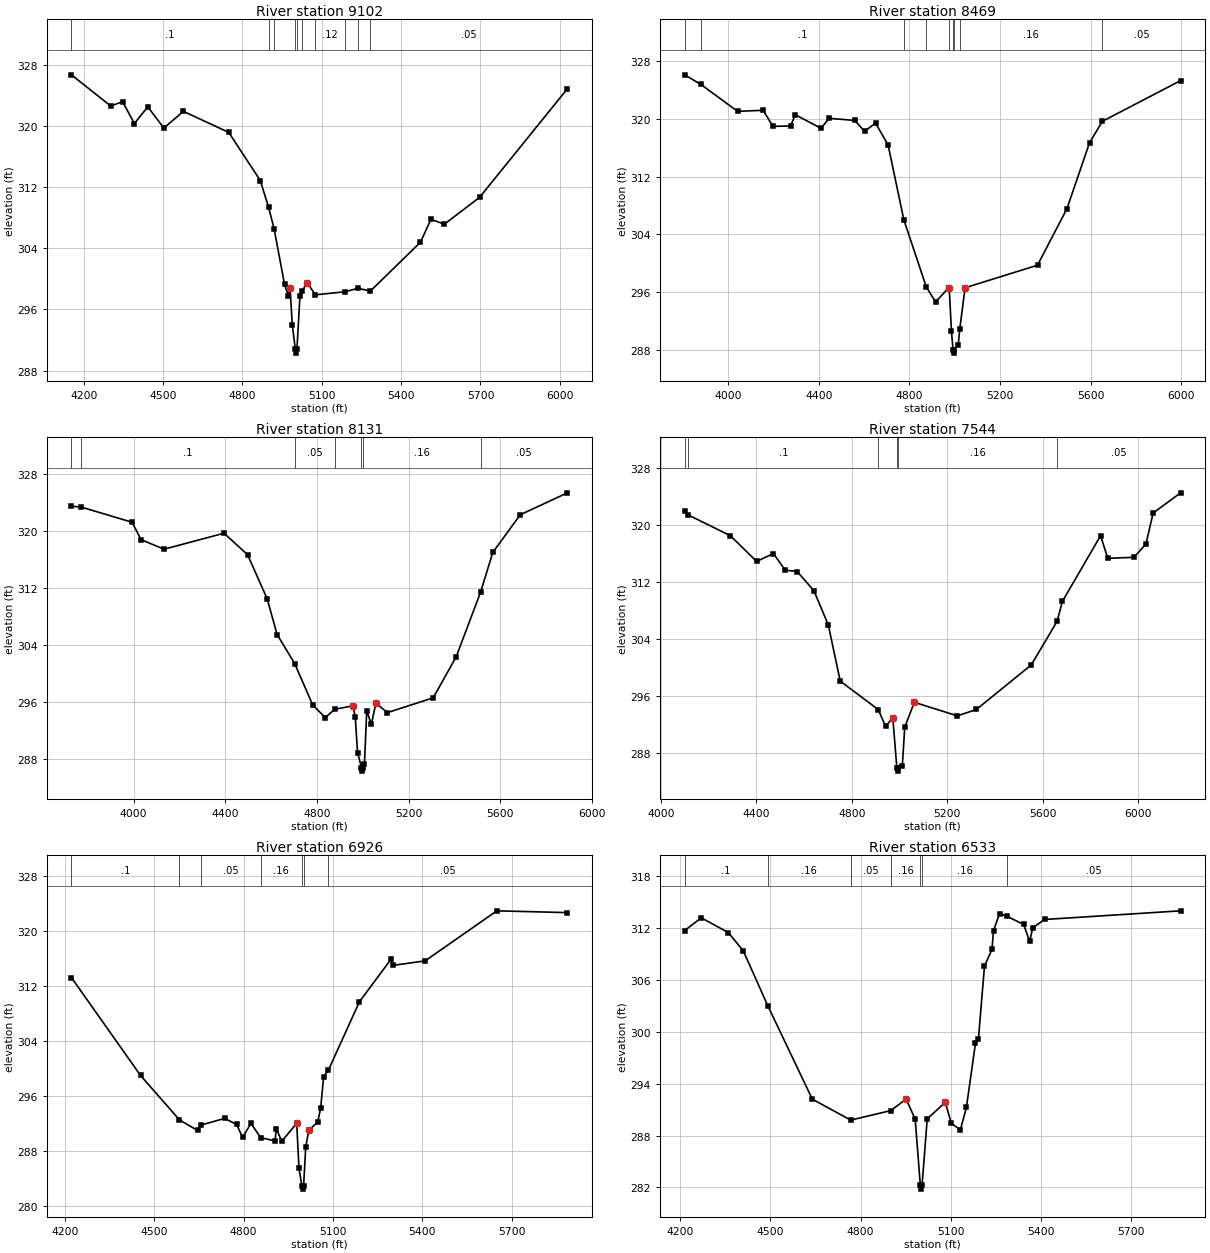
Type RM Length L Ch R = 1 ,9102    ,633,633,633
BEGIN DESCRIPTION:
SANDS BRANCH 11.0
END DESCRIPTION:
XS GIS Cut Line= 4
      3818772.88     10493473.26      3818196.53     10493188.55
      3817946.53     10493376.05      3817661.81     10494251.05
#Sta/Elev= 30
  4153.3  326.69  4301.7  322.61  4346.6  323.18  4391.2  320.32  4441.9   322.5
  4502.7  319.73  4576.6  321.91  4748.1  319.16  4867.3  312.86    4899  309.34
  4919.8  306.51  4959.1  299.27  4973.7  297.77    4980  298.75  4988.3  294.01
  4999.9  290.78  5002.6  290.28  5005.9  290.78  5017.3  297.74  5026.2  298.42
  5044.5  299.52  5075.4  297.91  5188.8  298.31  5235.9  298.76    5284  298.41
  5473.1  304.79  5512.6  307.79  5563.6  307.15  5696.6  310.66  6028.8  324.87
#Mann= 10 ,-1 , 0
  4153.3      .1       0    4899     .16       0  4919.8     .12       0
  4999.9     .07       0  5005.9     .12       0  5026.2     .16       0
  5075.4     .12       0  5188.8     .16       0  5235.9     .12       0
    5284     .05       0
Bank Sta=4980,5044.5
XS Rating Curve= 0 ,0
Exp/Cntr=0.3,0.1

Type RM Length L Ch R = 1 ,8469    ,338,338,338
BEGIN DESCRIPTION:
SANDS BRANCH 10.0
END DESCRIPTION:
XS GIS Cut Line= 3
      3818800.67      10493417.7      3818154.86     10492876.05
      3816807.62     10492889.94
#Sta/Elev= 30
  3807.1  326.13  3878.6   324.8  4040.7  321.07  4153.9  321.21  4196.8  318.98
  4274.8  319.04  4295.7   320.6  4408.9  318.72  4445.3   320.1  4558.5   319.8
  4601.4   318.3    4650  319.43  4705.2  316.43  4775.2  306.01  4874.1  296.72
  4915.3  294.63    4973  296.61  4975.3  296.62  4985.3  290.56  4992.3  288.04
    4995  287.54  4998.3  288.04  5015.3  288.67  5021.9  290.85  5045.3   296.6
  5365.3  299.73  5495.3  307.57  5595.3  316.73  5652.2  319.69  5997.3  325.33
#Mann= 9 ,-1 , 0
  3807.1     .05       0  3878.6      .1       0  4775.2     .05       0
  4874.1     .16       0    4973     .12       0  4992.3     .07       0
  4998.3     .12       0  5021.9     .16       0  5652.2     .05       0
Bank Sta=4975.3,5045.3
XS Rating Curve= 0 ,0
Exp/Cntr=0.3,0.1

Type RM Length L Ch R = 1 ,8131    ,587,587,587
BEGIN DESCRIPTION:
SANDS BRANCH 9.0
END DESCRIPTION:
XS GIS Cut Line= 3
      3818946.54     10493014.94      3817814.58     10492577.44
      3816863.87      10492570.5
#Sta/Elev= 30
  3728.8  323.48  3768.9   323.4  3993.5  321.24  4032.1   318.8  4132.9  317.45
  4394.7   319.7  4497.4  316.67  4582.9  310.46  4626.1  305.45  4703.1  301.35
  4781.8  295.52  4836.4  293.77    4877  294.92  4957.3  295.42  4967.3  293.78
  4977.3  288.84  4994.3  286.73  4997.1  286.23  5000.3  286.73  5007.3  287.25
  5017.3  294.73  5037.3  292.81  5057.3   295.8  5107.3  294.46  5307.3  296.54
  5407.4  302.29    5514   311.4  5567.4  316.99  5687.4   322.3  5893.1  325.38
#Mann= 7 ,-1 , 0
  3728.8     .05       0  3768.9      .1       0  4703.1     .05       0
    4877     .16       0  4994.3     .07       0  5000.3     .16       0
    5514     .05       0
Bank Sta=4957.3,5057.3
XS Rating Curve= 0 ,0
Exp/Cntr=0.3,0.1

Type RM Length L Ch R = 1 ,7544    ,618,618,618
BEGIN DESCRIPTION:
SANDS BRANCH 8.0
END DESCRIPTION:
XS GIS Cut Line= 2
      3818890.97     10492285.77      3816814.56     10492257.99
#Sta/Elev= 30
  4100.1   321.9  4115.8  321.38  4291.5  318.49  4401.5  314.88  4471.5  315.99
  4521.5  313.66  4571.5  313.47  4641.5  310.77  4701.5  305.99  4751.5  298.13
  4910.5  294.14  4941.5  291.78  4971.5     293  4988.5  286.02  4991.3  285.52
  4994.5  286.02  5011.5  286.19  5021.5  291.65  5061.6  295.16  5241.6  293.26
  5321.6  294.15  5551.6   300.4  5659.4  306.49  5681.6  309.28  5841.6  318.49
  5871.6  315.32  5981.6  315.46  6031.6  317.33  6061.6  321.66  6176.7  324.49
#Mann= 6 ,-1 , 0
  4100.1     .05       0  4115.8      .1       0  4910.5     .16       0
  4988.5     .07       0  4994.5     .16       0  5659.4     .05       0
Bank Sta=4971.5,5061.6
XS Rating Curve= 0 ,0
Exp/Cntr=0.3,0.1

Type RM Length L Ch R = 1 ,6926    ,393,393,393
BEGIN DESCRIPTION:
SANDS BRANCH 7.0
END DESCRIPTION:
XS GIS Cut Line= 4
      3818499.57     10491810.19      3817699.61     10491910.19
      3817499.61     10491910.19      3816843.44      10491959.3
#Sta/Elev= 30
  4222.5  313.21  4454.3  298.98    4585  292.51  4645.7  290.98  4657.2  291.76
  4736.4  292.74  4776.7  291.85  4796.9  289.97  4824.6  292.02  4857.4  289.94
  4905.2  289.46  4910.3  291.24  4927.9  289.39  4978.3  292.03  4985.9  285.49
  4995.5  282.95  4998.2  282.45  5001.5  282.95  5008.5  288.51  5018.6     291
  5048.7  292.19  5058.7  294.22  5068.7  298.82  5084.3  299.71  5188.7  309.69
  5294.8  315.89  5299.8  314.98  5409.2  315.64  5649.9  322.92  5886.7  322.66
#Mann= 7 ,-1 , 0
  4222.5      .1       0    4585     .16       0  4657.2     .05       0
  4857.4     .16       0  4995.5     .07       0  5001.5     .16       0
  5084.3     .05       0
Bank Sta=4978.3,5018.6
XS Rating Curve= 0 ,0
Exp/Cntr=0.3,0.1

Type RM Length L Ch R = 1 ,6533    ,1061,1061,1061
BEGIN DESCRIPTION:
SANDS BRANCH 6.0
END DESCRIPTION:
XS GIS Cut Line= 2
       3818564.6     10491563.55      3816918.71     10491646.88
#Sta/Elev= 30
  4215.5  311.71  4270.6  313.18  4360.7  311.48  4410.7  309.34  4491.4  303.04
  4639.7  292.21  4767.3  289.79  4900.3  290.89  4951.4  292.22  4981.5   289.9
  4998.5  282.31  5001.3  281.81  5004.5  282.31  5021.5  289.93  5081.6  291.85
  5101.6  289.42  5131.7  288.66  5151.7  291.25  5181.7  298.65  5191.7  299.19
  5211.8   307.6  5236.7  309.53  5241.8  311.71  5261.8  313.67  5286.5  313.36
  5341.9  312.41    5362  310.45    5372  312.03    5412  312.99  5863.5  313.99
#Mann= 7 ,-1 , 0
  4215.5      .1       0  4491.4     .16       0  4767.3     .05       0
  4900.3     .16       0  4998.5     .07       0  5004.5     .16       0
  5286.5     .05       0
Bank Sta=4951.4,5081.6
XS Rating Curve= 0 ,0
Exp/Cntr=0.3,0.1