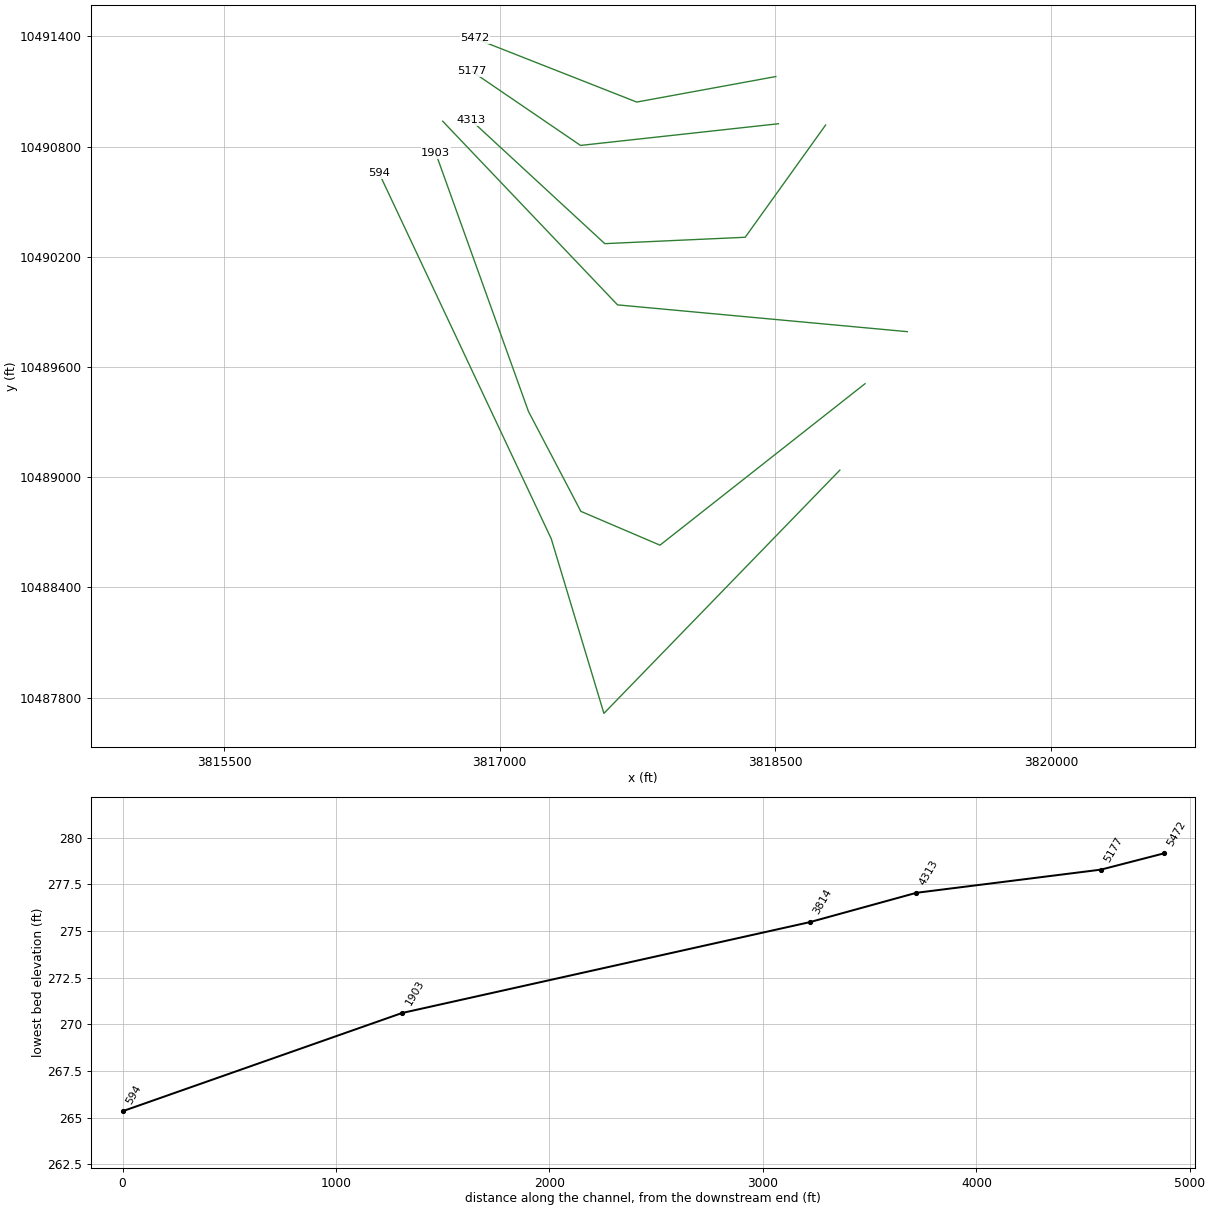
HEC-RAS study SANDS BRANCH.prj: SANDS BRANCH Base Level Engineering

--- SANDS BRANCH.g01 (geometry) --- (continued)

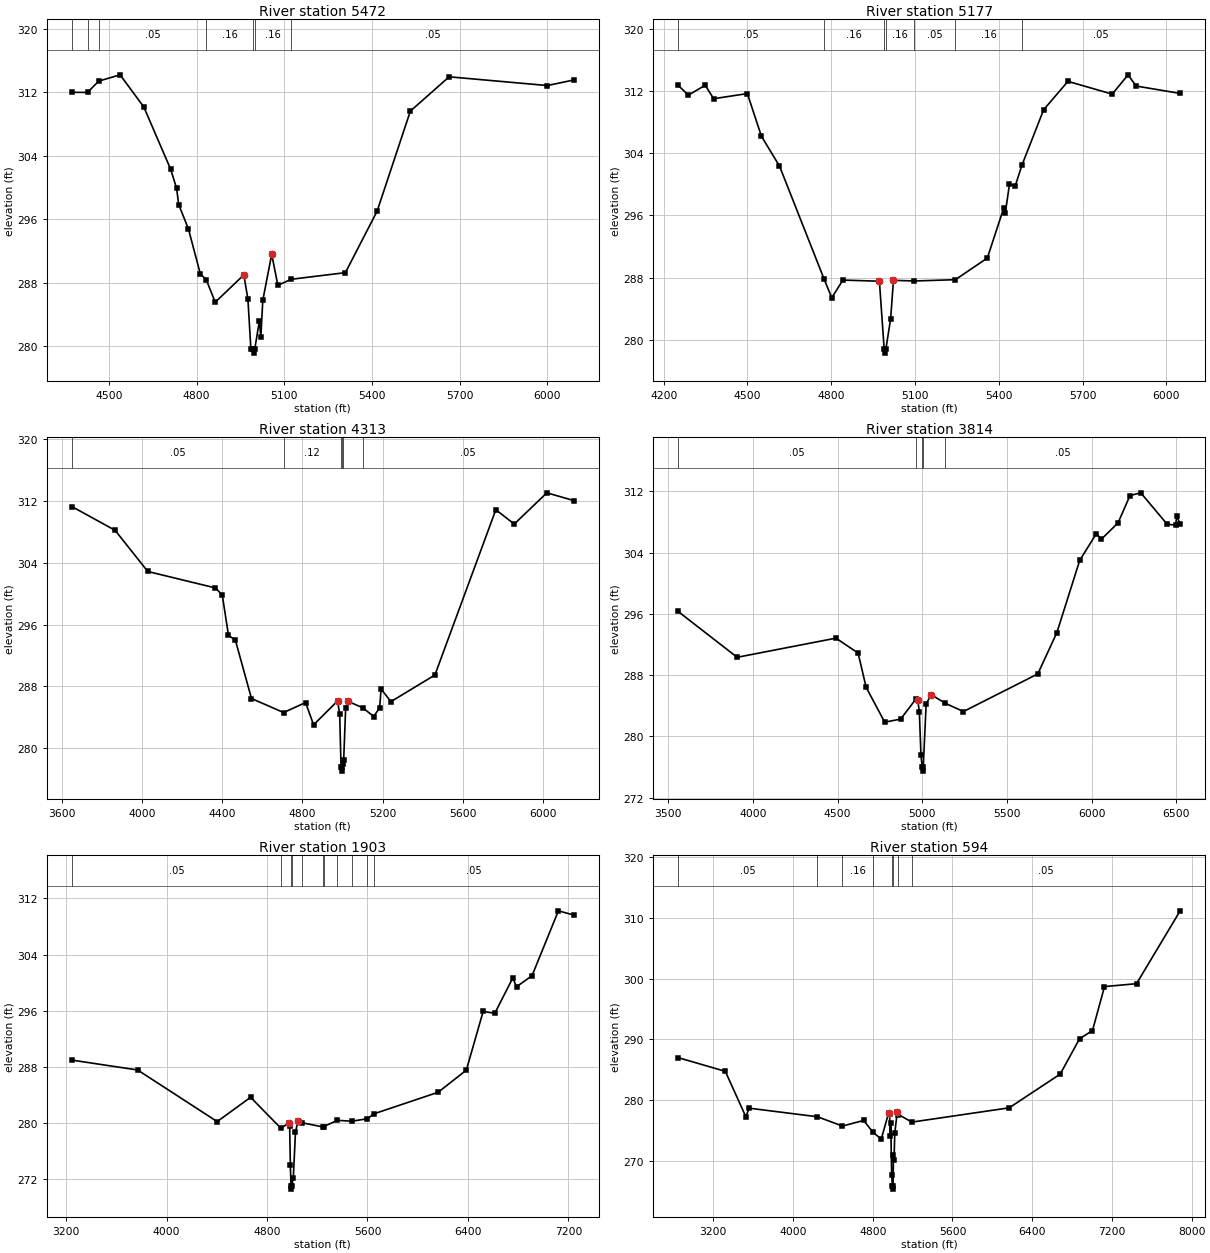
Type RM Length L Ch R = 1 ,5472    ,295,295,295
BEGIN DESCRIPTION:
SANDS BRANCH 4.0
END DESCRIPTION:
XS GIS Cut Line= 3
      3818502.08      10491181.6      3817745.14     10491042.72
      3816863.95     10491389.64
#Sta/Elev= 30
  4373.4  312.01  4427.2  311.99  4465.6  313.42  4538.6  314.21  4619.9  310.15
  4711.4  302.33  4731.8  299.93  4739.1  297.86  4772.4  294.79  4813.1  289.12
  4833.3   288.4  4863.9  285.56  4961.8  289.01  4975.8  285.92  4985.9  279.66
  4993.1  279.65  4995.8  279.15  4999.1  279.65  5014.9  283.19    5020   281.2
  5026.6  285.79  5057.1   291.6  5078.2  287.69  5123.3  288.45  5309.1  289.29
  5417.5  297.03  5531.2  309.64  5663.9  313.96  5999.6  312.86    6090  313.56
#Mann= 7 ,-1 , 0
  4373.4     .05       0  4427.2      .1       0  4465.6     .05       0
  4833.3     .16       0  4993.1     .07       0  4999.1     .16       0
  5123.3     .05       0
Bank Sta=4961.8,5057.1
XS Rating Curve= 0 ,0
Exp/Cntr=0.3,0.1

Type RM Length L Ch R = 1 ,5177    ,864,864,864
BEGIN DESCRIPTION:
SANDS BRANCH 3.0
END DESCRIPTION:
XS GIS Cut Line= 3
      3818515.93     10490924.66      3817439.58     10490806.61
      3816849.31     10491209.38
#Sta/Elev= 30
  4251.9   312.7  4288.4  311.44  4348.8  312.71    4379  310.98  4499.7  311.64
    4550  306.16  4614.7  302.33  4773.9  287.85  4801.9  285.39  4841.7  287.67
  4972.5  287.52  4989.6  278.78  4992.4  278.28  4995.6  278.78  5012.8  282.72
  5022.8  287.64  5096.7  287.55  5244.5  287.72  5358.9   290.5  5417.1  296.87
  5423.2  296.29  5438.1  299.96  5459.1   299.8  5482.5  302.41  5560.7  309.57
  5647.5  313.21    5806  311.57  5862.9  314.05  5891.6  312.61  6049.3  311.66
#Mann= 7 ,-1 , 0
  4251.9     .05       0  4773.9     .16       0  4989.6     .07       0
  4995.6     .16       0  5096.7     .05       0  5244.5     .16       0
  5482.5     .05       0
Bank Sta=4972.5,5022.8
XS Rating Curve= 0 ,0
Exp/Cntr=0.3,0.1

Type RM Length L Ch R = 1 ,4313    ,499,499,499
BEGIN DESCRIPTION:
SANDS BRANCH 2.0
END DESCRIPTION:
XS GIS Cut Line= 4
      3818772.91      10490917.7      3818335.42     10490306.61
      3817571.53     10490271.88      3816843.63     10490944.32
#Sta/Elev= 30
  3647.9  311.29  3864.2  308.21  4027.6  302.88  4365.4  300.75  4399.5  299.84
  4430.5  294.63  4465.3  293.97  4545.4  286.44    4706  284.62  4815.7  285.92
  4855.7  283.03  4975.9  286.14  4985.9  284.37  4992.9  277.54  4995.6  277.04
  4998.9  277.54  5002.3  277.99  5005.9  278.47  5015.9  285.18  5025.9  286.09
  5101.1  285.24    5156  284.11  5185.5  285.24  5192.8  287.65  5242.2  286.04
  5461.6  289.48  5765.8  310.87  5857.9  309.02  6020.7  313.06  6155.1  312.06
#Mann= 6 ,-1 , 0
  3647.9     .05       0    4706     .12       0  4992.9     .07       0
  4998.9     .12       0  5002.3     .16       0  5101.1     .05       0
Bank Sta=4975.9,5025.9
XS Rating Curve= 0 ,0
Exp/Cntr=0.3,0.1

Type RM Length L Ch R = 1 ,3814    ,1911,1911,1911
BEGIN DESCRIPTION:
Mapping XS 86f0da3e
END DESCRIPTION:
XS GIS Cut Line= 3
      3819217.35     10489792.72      3817640.97     10489938.55
      3816689.57     10490938.56
#Sta/Elev= 30
  3559.2  296.31  3907.6  290.33  4490.9  292.83  4621.5  290.88  4669.1   286.4
  4778.6  281.86  4872.5  282.26    4961  284.83    4973  284.82    4983  283.22
  4992.6  277.54  5000.1  275.97  5002.8  275.47  5006.1  275.97  5023.2  284.25
  5053.3  285.45  5135.9  284.33  5243.3  283.25  5682.2  288.16    5795  293.56
  5929.7  302.98  6028.4  306.49  6056.7  305.73  6155.8  307.87  6226.6  311.45
  6290.2   311.8  6445.8   307.7  6495.6  307.59  6502.5  308.77  6522.6  307.69
#Mann= 5 ,-1 , 0
  3559.2     .05       0    4961     .16       0  5000.1     .07       0
  5006.1     .16       0  5135.9     .05       0
Bank Sta=4973,5053.3
XS Rating Curve= 0 ,0
Exp/Cntr=0.3,0.1

Type RM Length L Ch R = 1 ,1903    ,1309,1309,1309
BEGIN DESCRIPTION:
Mapping XS 783be1b3
END DESCRIPTION:
XS GIS Cut Line= 5
      3818987.22     10489509.29      3817871.76     10488630.38
      3817441.32     10488814.42      3817156.16     10489358.69
      3816651.42     10490765.28
#Sta/Elev= 30
  3245.5  288.98    3770  287.57  4403.3  280.22  4669.5  283.68  4910.8  279.27
  4972.5     280  4980.5  279.56  4985.9  274.07  4991.2   271.1    4994   270.6
  4997.2   271.1  5009.5  272.19  5026.9  278.77  5048.6  280.34  5077.2  280.06
  5244.6  279.46  5250.9  279.49  5359.5   280.4  5474.4  280.27  5599.9  280.63
  5652.4  281.33  6163.1   284.4  6387.2  287.55  6521.3  295.92  6613.5  295.63
  6756.6  300.66  6787.4  299.43  6910.3     301  7120.3  310.24  7242.6  309.64
#Mann= 11 ,-1 , 0
  3245.5     .05       0  4910.8     .12       0  4991.2     .07       0
  4997.2     .12       0  5077.2     .16       0  5244.6     .05       0
  5250.9     .16       0  5359.5     .12       0  5474.4     .05       0
  5599.9     .16       0  5652.4     .05       0
Bank Sta=4972.5,5048.6
XS Rating Curve= 0 ,0
Exp/Cntr=0.3,0.1

Type RM Length L Ch R = 1 ,594     ,0,0,0
BEGIN DESCRIPTION:
SANDS BRANCH 1.0
END DESCRIPTION:
XS GIS Cut Line= 4
      3818850.49     10489039.01      3817566.75     10487714.59
       3817280.3     10488665.11      3816343.29     10490656.24
#Sta/Elev= 30
    2847     287  3320.5  284.74  3525.8  277.28    3561  278.67    4245  277.26
  4496.3  275.73  4707.8  276.65  4803.9  274.69  4885.3  273.58  4958.4  277.85
  4968.9  277.69  4975.1  274.12  4980.3  276.24  4989.8  267.62  4997.2  265.84
  4999.9  265.34  5003.2  265.84  5008.1  270.93  5013.3  270.08  5021.1  274.58
  5046.3  278.11  5057.9  277.63  5192.2  276.38  6168.9  278.73  6681.5  284.29
  6874.9   290.1    7005  291.46  7125.6   298.7  7447.1  299.18  7884.8  311.18
#Mann= 8 ,-1 , 0
    2847     .05       0    4245     .12       0  4496.3     .16       0
  4803.9     .12       0  4997.2     .07       0  5003.2     .12       0
  5057.9     .16       0  5192.2     .05       0
Bank Sta=4958.4,5046.3
XS Rating Curve= 0 ,0
Exp/Cntr=0.3,0.1

Chan Stop Cuts=-1
Use User Specified Reach Order=0
Composite Channel Slope=5