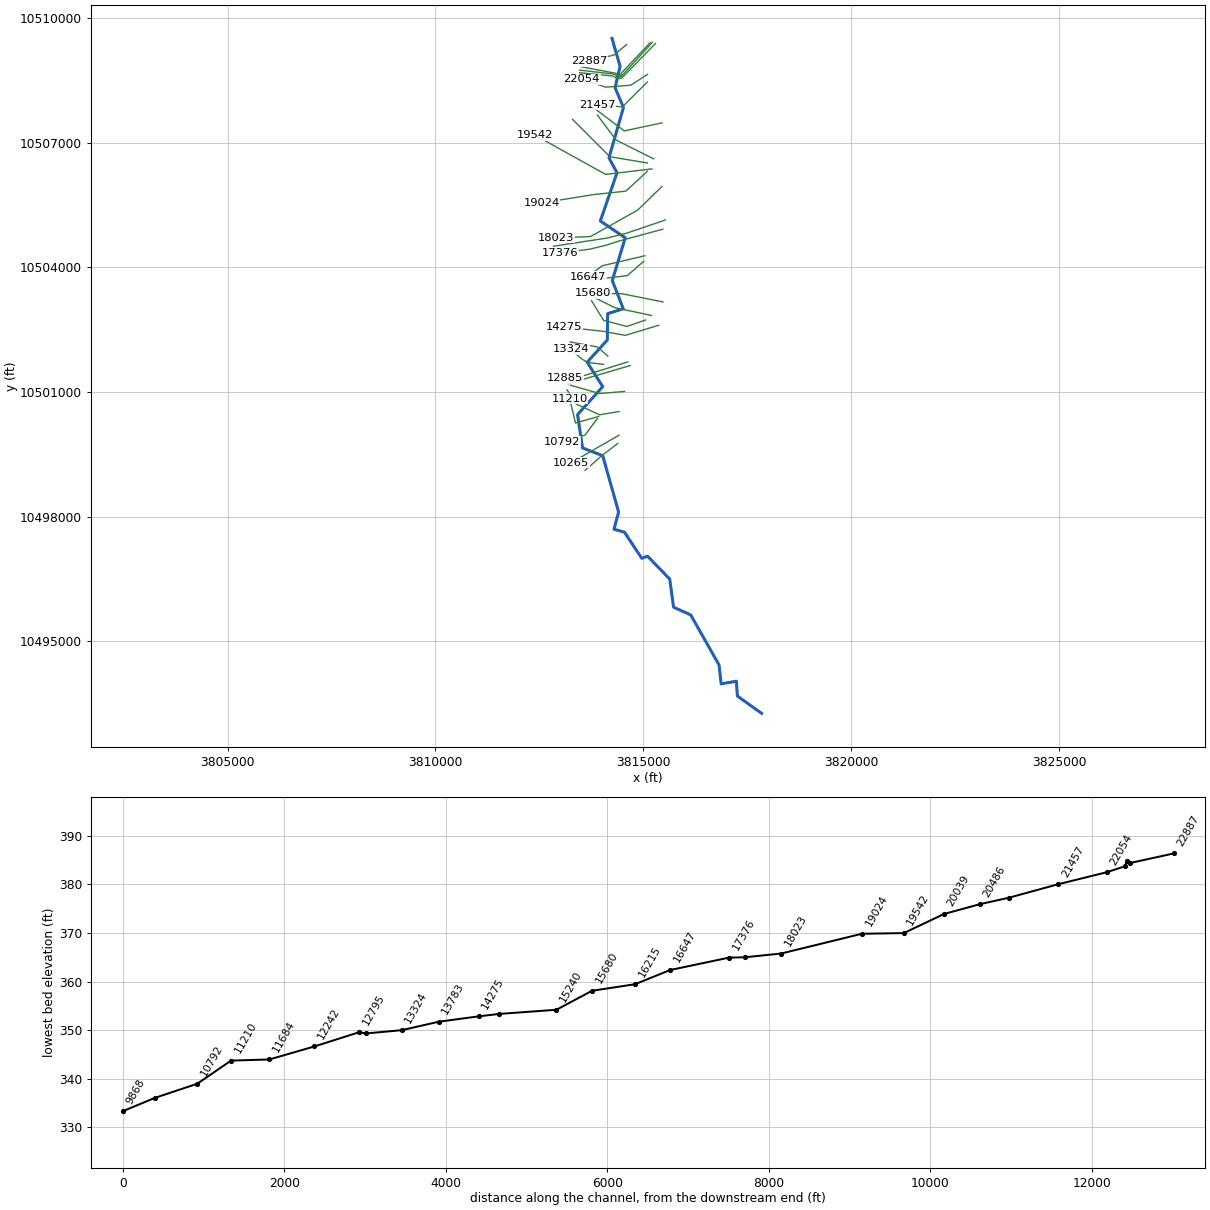
--- SIMS BRANCH.prj (project) ---

Proj Title=SIMS BRANCH Base Level Engineering
Current Plan=p01
Default Exp/Contr=0.3,0.1
English Units
Geom File=g01
Flow File=f01
Plan File=p01
BEGIN DESCRIPTION:
SIMS BRANCH
END DESCRIPTION:

--- SIMS BRANCH.p01 (plan) ---

Plan Title=Multiple Run
Short Identifier=Multiple
Geom File=g01
Flow File=f01
Subcritical Flow
K Sum by GR= 0
Std Step Tol= 0.01
Critical Tol= 0.01
Num of Std Step Trials= 20
Max Error Tol= 0.3
Flow Tol Ratio= 0.001
Split Flow NTrial= 30
Split Flow Tol= 0.02
Split Flow Ratio= 0.02
Log Output Level= 0
Friction Slope Method= 1
Unsteady Friction Slope Method= 2
Unsteady Bridges Friction Slope Method= 1
Parabolic Critical Depth
Global Vel Dist=  1 , 1 , 1
Global Log Level= 0
CheckData=True
Encroach Param= -1, 0, 0, 0
BEGIN DESCRIPTION:
Multiple Run
END DESCRIPTION:

--- SIMS BRANCH.f01 (steady flow) ---

Flow Title=Multiple
Number of Profiles=7
Profile Names=10-year,25-year,50-year,1pct_min,100-year,1pct_plu,500-year
River Rch & RM= SIMS BRANCH,Reach-1,22887
     620     838    1019     911    1232    1666    1806
River Rch & RM= SIMS BRANCH,Reach-1,18023
     782    1067    1305    1171    1583    2141    2340
River Rch & RM= SIMS BRANCH,Reach-1,12795
     944    1297    1591    1431    1936    2618    2878
River Rch & RM= SIMS BRANCH,Reach-1,3924
    1021    1407    1731    1561    2112    2856    3155
Boundary for River Rch & Prof#=SIMS BRANCH,Reach-1,1
Up Type=0
Dn Type=3
Dn Slope=0.005
Boundary for River Rch & Prof#=SIMS BRANCH,Reach-1,2
Up Type=0
Dn Type=3
Dn Slope=0.005
Boundary for River Rch & Prof#=SIMS BRANCH,Reach-1,3
Up Type=0
Dn Type=3
Dn Slope=0.005
Boundary for River Rch & Prof#=SIMS BRANCH,Reach-1,4
Up Type=0
Dn Type=3
Dn Slope=0.005
Boundary for River Rch & Prof#=SIMS BRANCH,Reach-1,5
Up Type=0
Dn Type=3
Dn Slope=0.005
Boundary for River Rch & Prof#=SIMS BRANCH,Reach-1,6
Up Type=0
Dn Type=3
Dn Slope=0.005
Boundary for River Rch & Prof#=SIMS BRANCH,Reach-1,7
Up Type=0
Dn Type=3
Dn Slope=0.005

--- SIMS BRANCH.g01 (geometry) ---

Geom Title=Existing Conditions

River Reach=SIMS BRANCH,Reach-1
Reach XY= 30
      3814249.61     10509510.19      3814444.00     10508837.00
      3814323.50     10508321.00      3814524.50     10507845.00
      3814175.75     10506634.00      3814370.00     10506276.00
      3813968.50     10505114.00      3814567.75     10504708.00
      3814256.25     10503680.00      3814519.75     10503001.00
      3814144.75     10502883.00      3814135.25     10502247.00
      3813651.75     10501715.00      3814025.75     10501126.00
      3813421.25     10500454.00      3813539.75     10499651.00
      3814025.75     10499464.00      3814408.50     10498108.00
      3814297.50     10497694.00      3814550.25     10497621.00
      3814966.25     10496993.00      3815102.25     10497046.00
      3815637.75     10496495.00      3815730.00     10495817.00
      3816142.25     10495632.00      3816823.50     10494428.00
      3816875.25     10493973.00      3817242.25     10494035.00
      3817265.25     10493679.00      3817849.00     10493261.00

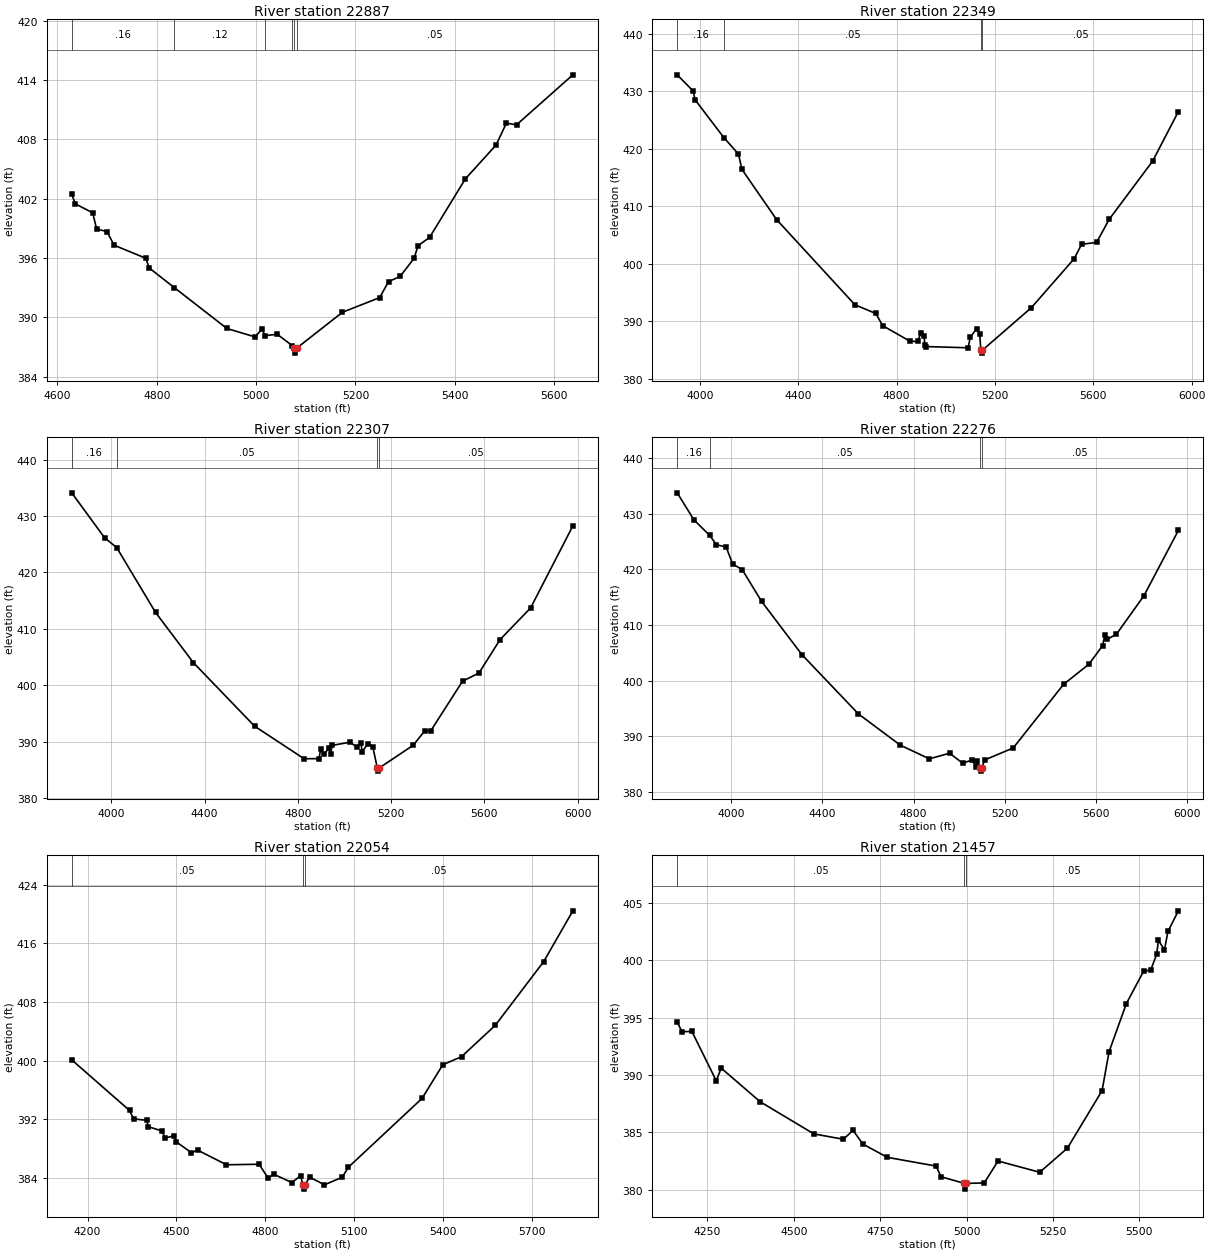
Type RM Length L Ch R = 1,22887,538,538,538
BEGIN DESCRIPTION:
SIMS BRANCH 46.0
END DESCRIPTION:
XS GIS Cut Line= 3
      3814599.62     10509360.20      3814299.61     10509110.19
      3813699.60     10508960.19
#Sta/Elev= 30
  4628.7  402.45  4635.9  401.48  4671.0  400.57  4678.8  398.93  4699.7  398.68
  4714.0  397.30  4777.8  395.98  4784.9  394.99  4835.3  393.01  4941.1  388.88
  4997.7  388.03  5012.1  388.84  5017.7  388.15  5042.4  388.30  5072.3  387.16
  5075.5  386.89  5078.2  386.39  5081.5  386.89  5173.8  390.52  5248.6  392.00
  5266.6  393.62  5289.8  394.14  5318.1  395.98  5325.9  397.25  5349.1  398.08
  5421.2  404.00  5483.1  407.43  5503.7  409.63  5524.3  409.47  5637.7  414.52
#Mann=6,-1,0
  4628.7    0.16       0  4835.3    0.12       0  5017.7    0.07       0
  5072.3    0.05       0  5075.5    0.07       0  5081.5    0.05       0
Bank Sta=5075.5,5081.5
Exp/Cntr=0.3,0.1

Type RM Length L Ch R = 1,22349,42,42,42
BEGIN DESCRIPTION:
Mapping XS 5a46fbbe
END DESCRIPTION:
XS GIS Cut Line= 6
      3815167.29     10509404.75      3814476.33     10508675.60
      3814455.50     10508623.52      3814396.47     10508623.52
      3814344.39     10508668.66      3813512.81     10508824.58
#Sta/Elev= 30
  3907.0  432.88  3972.2  430.05  3979.5  428.55  4096.8  421.96  4156.3  419.08
  4170.4  416.42  4311.6  407.67  4630.1  392.85  4715.0  391.33  4743.4  389.20
  4854.2  386.50  4884.8  386.47  4899.0  387.94  4911.7  387.45  4914.2  385.91
  4919.6  385.57  5090.6  385.36  5099.8  387.26  5125.0  388.64  5137.8  387.74
  5142.4  384.93  5145.1  384.43  5148.4  384.93  5348.1  392.35  5521.8  400.85
  5552.4  403.38  5613.4  403.70  5664.3  407.71  5841.5  417.87  5945.9  426.47
#Mann=4,-1,0
  3907.0    0.16       0  4096.8    0.05       0  5142.4    0.03       0
  5148.4    0.05       0
Bank Sta=5142.4,5148.4
Exp/Cntr=0.3,0.1

Type RM Length L Ch R = 1,22307,31,31,31
BEGIN DESCRIPTION:
SIMS BRANCH 45.0
END DESCRIPTION:
XS GIS Cut Line= 6
      3815222.89     10509415.22      3814462.44     10508585.32
      3814406.89     10508581.85      3814365.22     10508595.74
      3814313.14     10508647.82      3813469.41     10508745.04
#Sta/Elev= 30
  3830.1  434.10  3970.7  426.16  4023.2  424.39  4189.6  412.91  4352.4  403.99
  4614.6  392.75  4826.7  386.99  4890.9  387.00  4897.7  388.68  4911.9  387.80
  4933.1  388.82  4940.2  387.83  4947.3  389.35  5023.2  389.91  5054.5  389.04
  5070.1  389.84  5076.2  388.23  5100.8  389.67  5121.5  389.12  5141.1  385.29
  5143.9  384.79  5147.1  385.29  5295.1  389.38  5345.4  391.98  5370.1  391.92
  5506.5  400.73  5577.0  402.17  5667.5  408.10  5798.4  413.70  5979.8  428.25
#Mann=4,-1,0
  3830.1    0.16       0  4023.2    0.05       0  5141.1    0.03       0
  5147.1    0.05       0
Bank Sta=5141.1,5147.1
Exp/Cntr=0.3,0.1

Type RM Length L Ch R = 1,22276,222,222,222
BEGIN DESCRIPTION:
Mapping XS 6addd53a
END DESCRIPTION:
XS GIS Cut Line= 6
      3815295.81     10509387.44      3814504.11     10508574.91
      3814469.39     10508543.66      3814347.86     10508561.02
      3814271.47     10508602.68      3813469.39     10508682.55
#Sta/Elev= 30
  3763.4  433.75  3836.6  428.90  3906.0  426.09  3935.6  424.42  3978.0  424.01
  4006.3  420.97  4048.7  419.93  4133.6  414.22  4310.4  404.65  4557.8  394.01
  4741.7  388.38  4869.0  385.93  4957.5  386.94  5015.1  385.14  5055.5  385.72
  5073.5  384.48  5079.2  385.57  5092.4  384.22  5095.1  383.72  5098.4  384.22
  5110.9  385.72  5236.6  387.89  5457.7  399.34  5568.2  402.93  5628.5  406.29
  5638.6  408.22  5648.6  407.41  5689.1  408.34  5809.4  415.24  5960.4  426.98
#Mann=4,-1,0
  3763.4    0.16       0  3906.0    0.05       0  5092.4    0.03       0
  5098.4    0.05       0
Bank Sta=5092.4,5098.4
Exp/Cntr=0.3,0.1

Type RM Length L Ch R = 1,22054,597,597,597
BEGIN DESCRIPTION:
SIMS BRANCH 44.0
END DESCRIPTION:
XS GIS Cut Line= 4
      3815105.62     10508642.74      3814699.84     10508382.35
      3814098.72     10508334.61      3813523.04     10508527.22
#Sta/Elev= 30
  4146.7  400.13  4341.9  393.23  4355.8  392.08  4399.4  391.89  4405.3  391.02
  4450.9  390.44  4462.8  389.48  4493.2  389.79  4499.2  388.97  4550.7  387.48
  4571.8  387.83  4669.2  385.83  4779.5  385.90  4809.6  384.02  4829.7  384.52
  4889.9  383.41  4920.0  384.35  4927.0  383.01  4929.8  382.51  4933.0  383.01
  4950.1  384.14  5000.2  383.10  5060.4  384.14  5080.5  385.48  5329.7  394.88
  5399.6  399.46  5462.9  400.56  5577.0  404.84  5740.1  413.51  5838.9  420.44
#Mann=3,-1,0
  4146.7    0.05       0  4927.0    0.03       0  4933.0    0.05       0
Bank Sta=4927,4933
Exp/Cntr=0.3,0.1

Type RM Length L Ch R = 1,21457,616,616,616
BEGIN DESCRIPTION:
SIMS BRANCH 43.0
END DESCRIPTION:
XS GIS Cut Line= 3
      3815099.64     10508460.22      3814499.61     10507860.19
      3813899.66     10507910.18
#Sta/Elev= 30
  4162.5  394.61  4176.7  393.78  4205.0  393.81  4275.7  389.50  4289.8  390.61
  4403.0  387.67  4558.5  384.87  4643.4  384.41  4671.7  385.18  4699.9  383.99
  4770.7  382.83  4912.1  382.07  4926.2  381.14  4993.9  380.56  4996.7  380.06
  4999.9  380.56  5051.2  380.60  5091.3  382.51  5211.8  381.53  5292.0  383.63
  5392.4  388.65  5412.5  392.03  5462.6  396.23  5512.8  399.07  5532.9  399.14
  5550.4  400.53  5555.4  401.74  5573.0  400.93  5583.0  402.52  5613.1  404.32
#Mann=3,-1,0
  4162.5    0.05       0  4993.9    0.03       0  4999.9    0.05       0
Bank Sta=4993.9,4999.9
Exp/Cntr=0.3,0.1

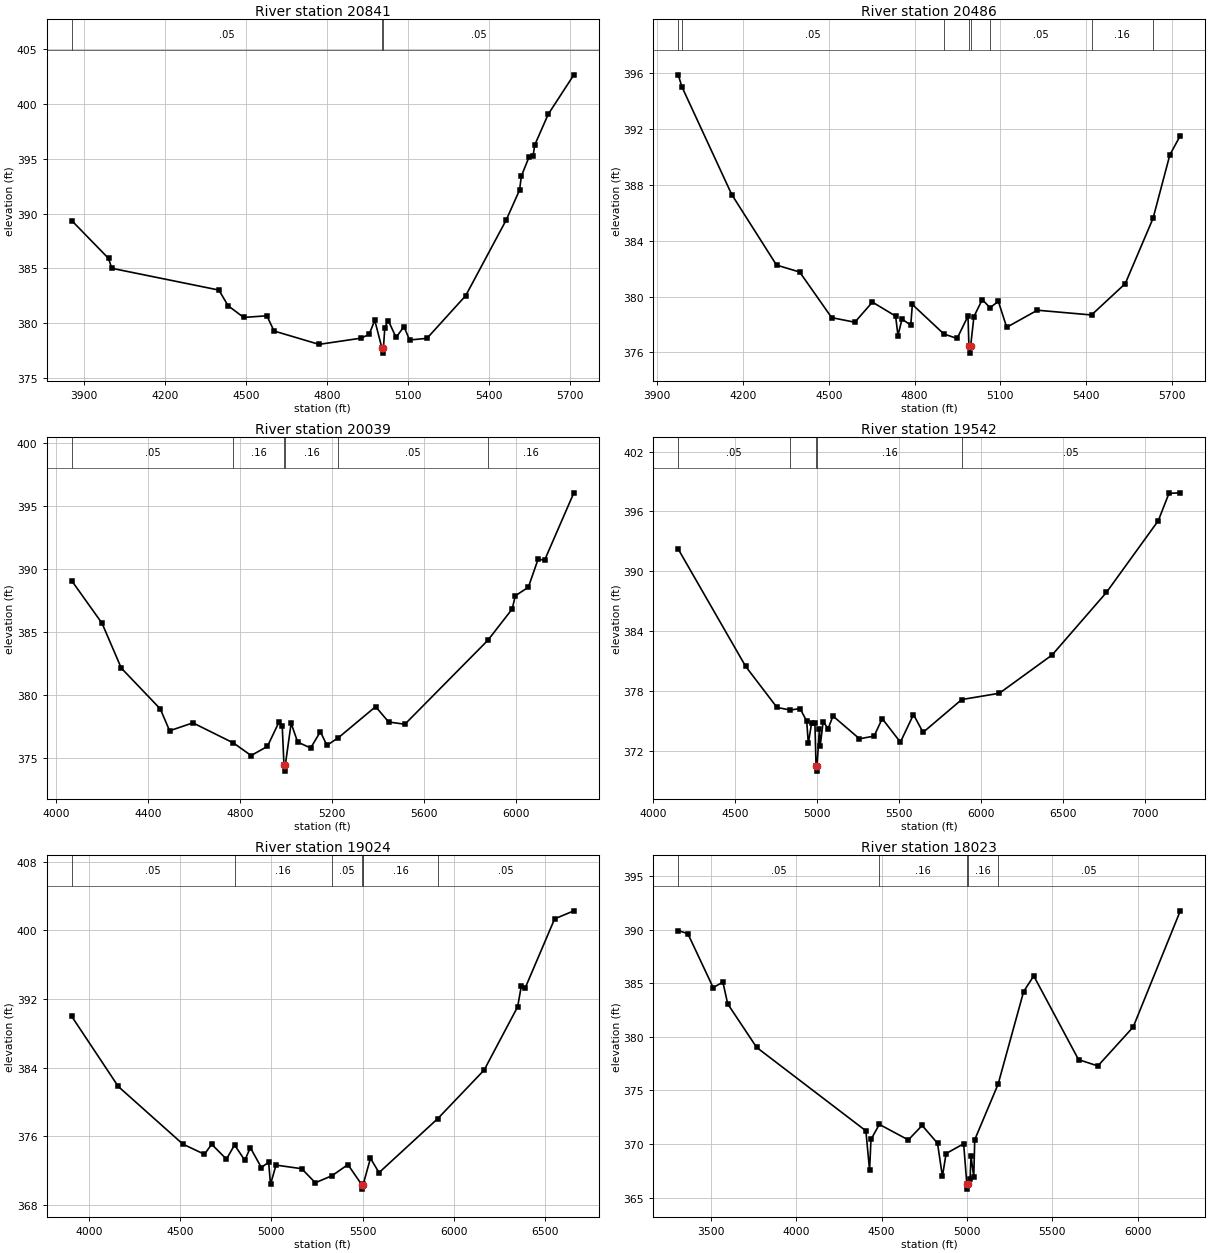
Type RM Length L Ch R = 1,20841,355,355,355
BEGIN DESCRIPTION:
SIMS BRANCH 42.0
END DESCRIPTION:
XS GIS Cut Line= 3
      3815452.91     10507475.24      3814543.59     10507282.09
      3813801.02     10507843.98
#Sta/Elev= 30
  3854.5  389.36  3990.8  385.91  4002.6  385.01  4399.7  383.02  4433.9  381.59
  4491.7  380.52  4577.6  380.67  4604.2  379.28  4771.0  378.06  4927.6  378.63
  4956.7  378.98  4977.5  380.26  5003.6  377.76  5006.4  377.26  5009.6  377.76
  5014.8  379.60  5027.4  380.24  5056.6  378.69  5085.7  379.69  5106.5  378.46
  5171.0  378.61  5314.5  382.51  5464.4  389.41  5514.3  392.17  5520.6  393.42
  5549.7  395.20  5564.2  395.28  5570.5  396.28  5620.4  399.08  5715.3  402.68
#Mann=3,-1,0
  3854.5    0.05       0  5003.6    0.03       0  5009.6    0.05       0
Bank Sta=5003.6,5009.6
Exp/Cntr=0.3,0.1

Type RM Length L Ch R = 1,20486,447,447,447
BEGIN DESCRIPTION:
SIMS BRANCH 41.0
END DESCRIPTION:
XS GIS Cut Line= 3
      3815249.65     10506610.17      3814349.61     10507060.19
      3813899.59     10507660.21
#Sta/Elev= 30
  3973.3  395.86  3986.0  395.01  4160.6  387.29  4317.1  382.25  4398.2  381.75
  4510.0  378.49  4591.1  378.16  4652.5  379.60  4733.6  378.60  4742.0  377.21
  4756.0  378.38  4786.7  377.96  4792.3  379.43  4902.4  377.32  4948.8  377.00
  4986.9  378.60  4990.1  376.45  4992.9  375.95  4996.1  376.45  5007.7  378.57
  5036.9  379.78  5063.8  379.20  5093.1  379.65  5122.3  377.80  5229.6  379.02
  5419.0  378.68  5536.9  380.92  5634.2  385.59  5693.1  390.14  5729.6  391.51
#Mann=8,-1,0
  3973.3    0.16       0  3986.0    0.05       0  4902.4    0.16       0
  4990.1    0.07       0  4996.1    0.16       0  5063.8    0.05       0
  5419.0    0.16       0  5634.2    0.05       0
Bank Sta=4990.1,4996.1
Exp/Cntr=0.3,0.1

Type RM Length L Ch R = 1,20039,497,497,497
BEGIN DESCRIPTION:
SIMS BRANCH 40.0
END DESCRIPTION:
XS GIS Cut Line= 3
      3815099.59     10506510.19      3814199.61     10506660.19
      3813299.60     10507560.20
#Sta/Elev= 30
  4068.6  389.06  4200.4  385.68  4284.0  382.12  4453.8  378.87  4494.4  377.13
  4595.8  377.76  4772.2  376.16  4849.2  375.16  4920.2  375.89  4970.9  377.84
  4984.5  377.54  4992.1  374.42  4994.9  373.92  4998.1  374.42  5023.4  377.73
  5051.7  376.23  5108.3  375.76  5150.7  377.06  5179.0  375.97  5229.1  376.58
  5391.1  379.05  5447.7  377.83  5518.4  377.65  5879.6  384.33  5985.1  386.81
  5999.2  387.87  6055.8  388.55  6098.2  390.78  6126.5  390.70  6253.8  396.06
#Mann=6,-1,0
  4068.6    0.05       0  4772.2    0.16       0  4992.1    0.07       0
  4998.1    0.16       0  5229.1    0.05       0  5879.6    0.16       0
Bank Sta=4992.1,4998.1
Exp/Cntr=0.3,0.1

Type RM Length L Ch R = 1,19542,518,518,518
BEGIN DESCRIPTION:
SIMS BRANCH 39.0
END DESCRIPTION:
XS GIS Cut Line= 3
      3815208.06     10506367.11      3814096.99     10506235.17
      3812395.62     10507179.61
#Sta/Elev= 30
  4151.9  392.23  4563.2  380.49  4754.6  376.37  4836.3  376.11  4895.5  376.26
  4936.1  375.00  4945.9  372.76  4966.0  374.80  4986.2  374.79  4993.2  370.49
  4996.0  369.99  4999.2  370.49  5013.8  374.25  5018.8  372.54  5036.5  374.95
  5066.7  374.25  5096.5  375.51  5258.1  373.23  5347.7  373.50  5396.9  375.25
  5508.0  372.89  5588.0  375.66  5646.3  373.87  5882.3  377.16  6112.0  377.79
  6434.4  381.63  6766.1  387.90  7082.3  395.08  7147.5  397.82  7216.7  397.87
#Mann=5,-1,0
  4151.9    0.05       0  4836.3    0.16       0  4993.2    0.07       0
  4999.2    0.16       0  5882.3    0.05       0
Bank Sta=4993.2,4999.2
Exp/Cntr=0.3,0.1

Type RM Length L Ch R = 1,19024,1001,1001,1001
BEGIN DESCRIPTION:
SIMS BRANCH 38.0
END DESCRIPTION:
XS GIS Cut Line= 4
      3815099.61     10506310.19      3814583.10     10505832.39
      3813805.32     10505749.06      3812555.29     10505547.67
#Sta/Elev= 30
  3906.3  389.98  4161.2  381.82  4515.0  375.11  4633.5  373.92  4673.1  375.09
  4754.2  373.35  4798.5  375.01  4854.8  373.22  4885.0  374.70  4945.3  372.38
  4985.5  372.99  4995.6  370.41  5025.8  372.66  5166.6  372.24  5241.4  370.60
  5333.3  371.43  5419.9  372.72  5496.2  370.36  5499.0  369.86  5502.2  370.36
  5505.0  370.51  5543.5  373.46  5590.4  371.78  5912.6  378.08  6166.8  383.74
  6350.1  391.10  6370.3  393.52  6390.6  393.25  6552.9  401.35  6658.3  402.29
#Mann=7,-1,0
  3906.3    0.05       0  4798.5    0.16       0  5333.3    0.05       0
  5496.2    0.07       0  5502.2    0.05       0  5505.0    0.16       0
  5912.6    0.05       0
Bank Sta=5496.2,5502.2
Exp/Cntr=0.3,0.1

Type RM Length L Ch R = 1,18023,442,442,442
BEGIN DESCRIPTION:
SIMS BRANCH 37.0
END DESCRIPTION:
XS GIS Cut Line= 4
      3815448.53     10505940.94      3814869.12     10505376.71
      3813731.96     10504738.69      3812903.76     10504706.17
#Sta/Elev= 30
  3308.8  389.91  3365.1  389.62  3513.7  384.58  3570.3  385.11  3598.6  383.07
  3768.1  379.01  4408.1  371.23  4429.8  367.54  4438.0  370.42  4487.0  371.83
  4656.8  370.38  4737.8  371.73  4827.9  370.07  4856.5  366.98  4878.2  369.11
  4980.9  370.02  4999.5  366.29  5002.3  365.79  5005.5  366.29  5018.5  366.72
  5024.2  368.86  5040.2  366.93  5045.9  370.40  5182.8  375.58  5332.4  384.22
  5391.6  385.68  5654.0  377.87  5767.3  377.28  5974.2  380.91  6250.3  391.75
#Mann=5,-1,0
  3308.8    0.05       0  4487.0    0.16       0  4999.5    0.07       0
  5005.5    0.16       0  5182.8    0.05       0
Bank Sta=4999.5,5005.5
Exp/Cntr=0.3,0.1

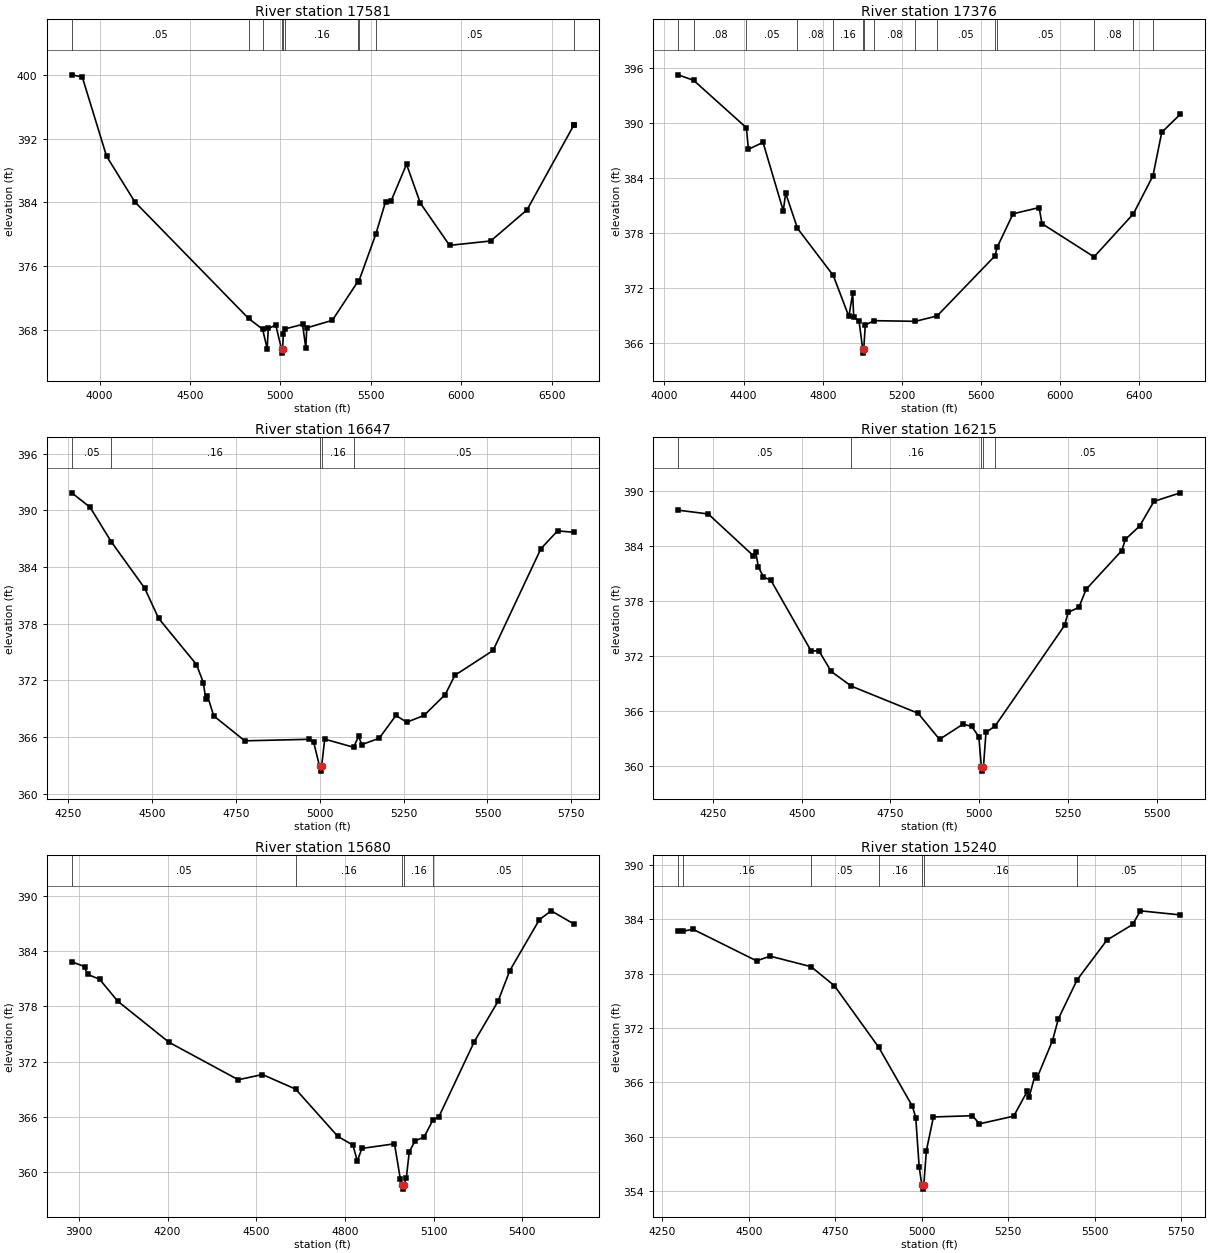
Type RM Length L Ch R = 1,17581,205,205,205
BEGIN DESCRIPTION:
SIMS BRANCH 36.0
END DESCRIPTION:
XS GIS Cut Line= 4
      3815534.52     10505137.96      3814596.99     10504818.50
      3814117.82     10504700.45      3812840.09     10504506.01
#Sta/Elev= 30
  3846.6  400.07  3904.6  399.80  4038.9  389.83  4195.7  384.06  4824.6  369.39
  4902.0  368.04  4927.1  365.59  4933.4  368.14  4974.9  368.55  5006.4  365.53
  5009.2  365.03  5012.4  365.53  5016.4  367.45  5026.6  368.08  5122.7  368.65
  5140.9  365.67  5146.0  368.21  5287.5  369.16  5428.9  374.05  5432.6  373.99
  5528.1  380.02  5581.6  384.08  5612.0  384.17  5697.9  388.81  5773.8  383.93
  5935.7  378.60  6163.2  379.15  6364.1  383.07  6621.7  393.69  6623.0  393.69
#Mann=10,-1,0
  3846.6    0.05       0  4824.6    0.16       0  4902.0    0.05       0
  5006.4    0.04       0  5012.4    0.05       0  5026.6    0.16       0
  5428.9    0.05       0  5432.6    0.08       0  5528.1    0.05       0
  6621.7    0.08       0
Bank Sta=5006.4,5012.4
Exp/Cntr=0.3,0.1

Type RM Length L Ch R = 1,17376,729,729,729
BEGIN DESCRIPTION:
SIMS BRANCH 35.0
END DESCRIPTION:
XS GIS Cut Line= 5
      3815472.00     10504915.73      3814416.44     10504631.00
      3814117.82     10504533.78      3813721.99     10504436.56
      3813006.69     10504339.34
#Sta/Elev= 30
  4070.1  395.30  4147.9  394.70  4414.3  389.53  4424.7  387.18  4498.5  387.93
  4600.8  380.47  4613.0  382.39  4672.6  378.55  4853.2  373.42  4932.2  368.94
  4951.6  371.45  4956.7  368.87  4984.0  368.40  5001.7  365.44  5004.5  364.94
  5007.7  365.44  5015.1  368.01  5060.1  368.48  5268.7  368.41  5378.3  369.00
  5671.3  375.57  5681.3  376.48  5761.9  380.14  5893.8  380.82  5907.6  379.07
  6171.0  375.44  6369.5  380.13  6468.7  384.28  6513.1  389.03  6606.9  391.00
#Mann=15,-1,0
  4070.1    0.05       0  4147.9    0.08       0  4414.3    0.05       0
  4672.6    0.08       0  4853.2    0.16       0  5001.7    0.07       0
  5007.7    0.16       0  5060.1    0.08       0  5268.7    0.16       0
  5378.3    0.05       0  5671.3    0.08       0  5681.3    0.05       0
  6171.0    0.08       0  6369.5    0.05       0  6468.7    0.08       0
Bank Sta=5001.7,5007.7
Exp/Cntr=0.3,0.1

Type RM Length L Ch R = 1,16647,432,432,432
BEGIN DESCRIPTION:
SIMS BRANCH 34.0
END DESCRIPTION:
XS GIS Cut Line= 3
      3815041.40     10504276.83      3814006.71     10504033.78
      3813667.81     10503764.04
#Sta/Elev= 30
  4261.3  391.87  4315.9  390.34  4378.6  386.71  4478.9  381.75  4519.9  378.58
  4632.9  373.68  4653.5  371.76  4660.3  370.03  4665.5  370.38  4684.3  368.24
  4776.7  365.60  4967.5  365.76  4982.2  365.44  4999.7  362.89  5002.5  362.39
  5005.7  362.89  5015.0  365.78  5101.0  364.92  5115.7  366.06  5126.0  365.21
  5177.4  365.87  5227.1  368.29  5259.5  367.57  5310.9  368.29  5374.0  370.50
  5402.9  372.54  5516.6  375.17  5659.1  385.95  5708.8  387.84  5757.3  387.69
#Mann=5,-1,0
  4261.3    0.05       0  4378.6    0.16       0  4999.7    0.07       0
  5005.7    0.16       0  5101.0    0.05       0
Bank Sta=4999.7,5005.7
Exp/Cntr=0.3,0.1

Type RM Length L Ch R = 1,16215,535,535,535
BEGIN DESCRIPTION:
SIMS BRANCH 33.0
END DESCRIPTION:
XS GIS Cut Line= 3
      3815013.64     10504144.88      3814617.82     10503797.67
      3813735.87     10503693.50
#Sta/Elev= 30
  4152.1  387.89  4236.6  387.48  4363.8  382.93  4370.4  383.32  4378.0  381.70
  4392.3  380.62  4413.1  380.26  4527.0  372.53  4547.9  372.61  4583.1  370.33
  4640.0  368.73  4827.9  365.78  4888.3  362.94  4954.6  364.60  4978.9  364.34
  4999.0  363.24  5006.1  359.98  5008.9  359.48  5012.1  359.98  5019.2  363.70
  5044.9  364.39  5240.7  375.35  5250.8  376.76  5281.0  377.32  5301.4  379.28
  5401.8  383.49  5411.9  384.71  5452.2  386.17  5492.5  388.85  5566.7  389.78
#Mann=5,-1,0
  4152.1    0.05       0  4640.0    0.16       0  5006.1    0.07       0
  5012.1    0.16       0  5044.9    0.05       0
Bank Sta=5006.1,5012.1
Exp/Cntr=0.3,0.1

Type RM Length L Ch R = 1,15680,440,440,440
BEGIN DESCRIPTION:
SIMS BRANCH 32.0
END DESCRIPTION:
XS GIS Cut Line= 3
      3815472.00     10503165.73      3814499.77     10503360.17
      3813792.99     10503374.03
#Sta/Elev= 30
  3876.1  382.86  3919.3  382.33  3929.5  381.49  3970.3  380.95  4031.5  378.57
  4204.9  374.10  4439.4  370.02  4521.0  370.59  4633.4  369.00  4776.0  363.86
  4827.0  362.91  4842.2  361.18  4857.5  362.55  4967.8  363.05  4987.8  359.17
  4994.8  358.62  4997.5  358.12  5000.8  358.62  5007.8  359.35  5017.8  362.19
  5037.8  363.38  5067.8  363.78  5098.5  365.68  5117.8  365.98  5237.8  374.17
  5317.8  378.54  5357.8  381.89  5457.9  387.44  5497.9  388.40  5574.5  386.97
#Mann=5,-1,0
  3876.1    0.05       0  4633.4    0.16       0  4994.8    0.07       0
  5000.8    0.16       0  5098.5    0.05       0
Bank Sta=4994.8,5000.8
Exp/Cntr=0.3,0.1

Type RM Length L Ch R = 1,15240,711,711,711
BEGIN DESCRIPTION:
SIMS BRANCH 31.0
END DESCRIPTION:
XS GIS Cut Line= 3
      3815201.18     10502839.33      3814319.21     10503026.84
      3813826.15     10503269.90
#Sta/Elev= 30
  4295.8  382.73  4310.6  382.67  4338.3  382.89  4522.3  379.40  4561.3  379.92
  4679.7  378.76  4747.2  376.66  4875.6  369.85  4972.2  363.40  4982.4  362.12
  4992.3  356.66  4999.8  354.72  5002.6  354.22  5005.8  354.72  5013.1  358.46
  5033.5  362.18  5146.3  362.32  5166.4  361.42  5265.6  362.27  5304.9  365.02
  5310.5  364.42  5327.3  366.79  5332.9  366.48  5377.8  370.61  5394.7  373.01
  5448.8  377.30  5535.0  381.69  5609.6  383.42  5631.8  384.92  5747.2  384.47
#Mann=7,-1,0
  4295.8    0.05       0  4310.6    0.16       0  4679.7    0.05       0
  4875.6    0.16       0  4999.8    0.07       0  5005.8    0.16       0
  5448.8    0.05       0
Bank Sta=4999.8,5005.8
Exp/Cntr=0.3,0.1

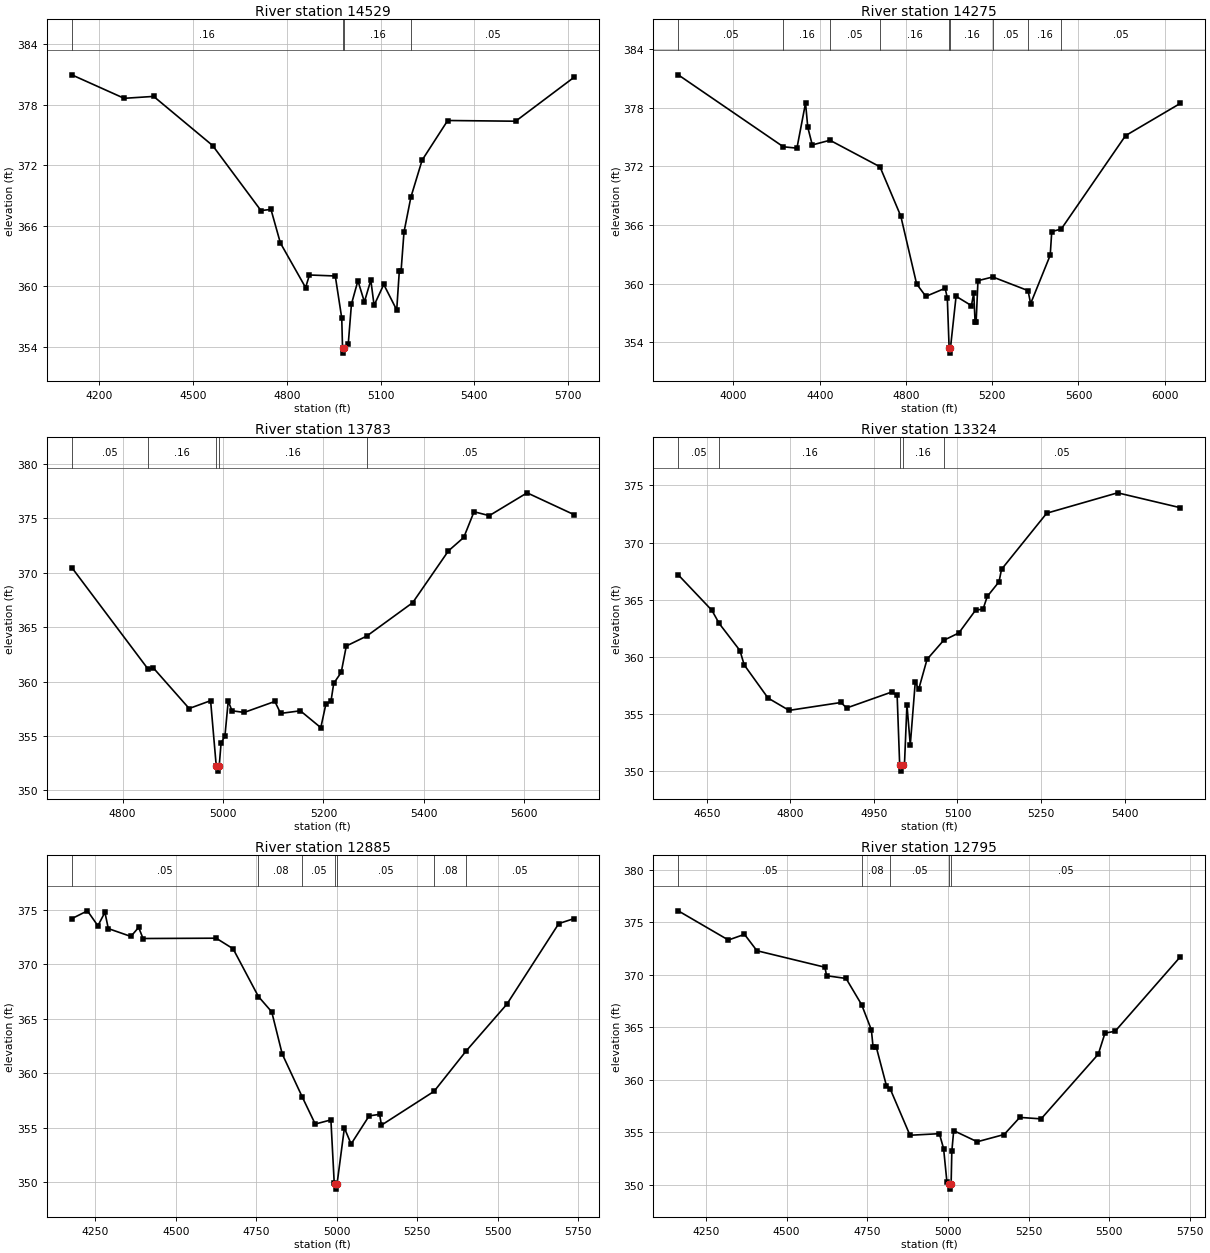
Type RM Length L Ch R = 1,14529,254,254,254
BEGIN DESCRIPTION:
SIMS BRANCH 30.0
END DESCRIPTION:
XS GIS Cut Line= 4
      3815055.36     10502728.24      3814603.94     10502575.45
      3814048.38     10502721.28      3813756.71     10503193.51
#Sta/Elev= 30
  4112.1  380.96  4279.7  378.63  4374.0  378.82  4562.6  373.95  4717.2  367.50
  4749.3  367.61  4779.3  364.29  4860.1  359.86  4872.3  361.11  4955.0  361.01
  4975.7  356.83  4978.2  353.86  4980.9  353.36  4984.2  353.86  4996.4  354.22
  5006.7  358.22  5027.4  360.54  5048.1  358.44  5068.7  360.60  5079.1  358.10
  5110.1  360.17  5151.5  357.64  5159.8  361.48  5165.4  361.48  5174.8  365.37
  5196.8  368.82  5232.8  372.50  5314.6  376.43  5531.9  376.36  5718.1  380.70
#Mann=4,-1,0
  4112.1    0.16       0  4978.2    0.07       0  4984.2    0.16       0
  5196.8    0.05       0
Bank Sta=4978.2,4984.2
Exp/Cntr=0.3,0.1

Type RM Length L Ch R = 1,14275,492,492,492
BEGIN DESCRIPTION:
SIMS BRANCH 29.0
END DESCRIPTION:
XS GIS Cut Line= 4
      3815374.74     10502603.22      3814569.21     10502360.17
      3814041.44     10502457.39      3813097.01     10502561.56
#Sta/Elev= 30
  3744.0  381.40  4231.4  374.02  4294.4  373.88  4334.3  378.51  4344.7  376.02
  4365.6  374.21  4447.6  374.69  4679.4  371.97  4775.9  366.92  4849.4  359.96
  4892.1  358.68  4981.6  359.51  4991.7  358.53  5000.2  353.36  5003.0  352.86
  5006.2  353.36  5032.4  358.69  5103.6  357.73  5114.3  359.03  5120.4  356.10
  5125.5  356.10  5133.9  360.29  5202.5  360.67  5366.2  359.27  5378.0  357.93
  5468.9  362.90  5476.0  365.32  5520.2  365.59  5818.1  375.16  6072.2  378.47
#Mann=9,-1,0
  3744.0    0.05       0  4231.4    0.16       0  4447.6    0.05       0
  4679.4    0.16       0  5000.2    0.07       0  5006.2    0.16       0
  5202.5    0.05       0  5366.2    0.16       0  5520.2    0.05       0
Bank Sta=5000.2,5006.2
Exp/Cntr=0.3,0.1

Type RM Length L Ch R = 1,13783,459,459,459
BEGIN DESCRIPTION:
SIMS BRANCH 28.0
END DESCRIPTION:
XS GIS Cut Line= 3
      3814149.58     10501860.21      3813898.79     10502080.95
      3813244.04     10502202.36
#Sta/Elev= 30
  4698.8  370.49  4850.7  361.15  4861.5  361.24  4932.6  357.52  4975.3  358.24
  4986.5  352.26  4989.3  351.76  4992.5  352.26  4996.2  354.36  5003.8  354.97
  5010.4  358.19  5018.0  357.31  5042.2  357.16  5103.3  358.17  5114.8  357.07
  5154.1  357.31  5194.8  355.76  5205.0  357.94  5215.1  358.19  5220.5  359.83
  5235.5  360.85  5245.6  363.27  5286.2  364.18  5377.9  367.26  5449.0  372.02
  5479.6  373.26  5500.0  375.62  5530.4  375.26  5605.7  377.36  5698.8  375.36
#Mann=5,-1,0
  4698.8    0.05       0  4850.7    0.16       0  4986.5    0.07       0
  4992.5    0.16       0  5286.2    0.05       0
Bank Sta=4986.5,4992.5
Exp/Cntr=0.3,0.1

Type RM Length L Ch R = 1,13324,439,439,439
BEGIN DESCRIPTION:
SIMS BRANCH 27.0
END DESCRIPTION:
XS GIS Cut Line= 4
      3814049.59     10501660.19      3813649.61     10501710.19
      3813499.61     10501810.19      3813260.77     10502020.18
#Sta/Elev= 30
  4598.7  367.18  4659.1  364.08  4672.2  362.93  4709.5  360.56  4717.1  359.31
  4759.9  356.41  4797.7  355.33  4890.9  356.02  4901.0  355.54  4981.6  356.93
  4991.7  356.66  4996.3  350.52  4999.0  350.02  5002.3  350.52  5004.8  350.52
  5009.3  355.82  5015.3  352.31  5024.3  357.85  5030.3  357.16  5045.4  359.79
  5075.1  361.45  5102.5  362.10  5132.5  364.09  5146.0  364.19  5153.5  365.29
  5174.6  366.57  5179.1  367.66  5260.3  372.57  5387.5  374.35  5500.1  373.05
#Mann=5,-1,0
  4598.7    0.05       0  4672.2    0.16       0  4996.3    0.07       0
  5002.3    0.16       0  5075.1    0.05       0
Bank Sta=4996.3,5002.3
Exp/Cntr=0.3,0.1

Type RM Length L Ch R = 1,12885,90,90,90
BEGIN DESCRIPTION:
Mapping XS 0e866212
END DESCRIPTION:
XS GIS Cut Line= 3
      3814627.91     10501720.69      3813560.24     10501386.50
      3813123.27     10501325.93
#Sta/Elev= 30
  4177.0  374.16  4225.6  374.88  4258.1  373.51  4280.0  374.74  4290.5  373.25
  4360.7  372.53  4384.8  373.36  4398.4  372.34  4625.6  372.37  4678.2  371.40
  4756.8  367.02  4798.3  365.61  4830.8  361.75  4893.3  357.79  4933.4  355.32
  4982.1  355.70  4992.5  349.87  4995.3  349.85  4998.1  349.35  5001.3  349.85
  5024.0  354.96  5044.9  353.49  5100.9  356.07  5133.4  356.21  5139.2  355.22
  5302.6  358.32  5401.9  362.01  5528.7  366.31  5690.1  373.71  5736.9  374.16
#Mann=7,-1,0
  4177.0    0.05       0  4756.8    0.08       0  4893.3    0.05       0
  4995.3    0.04       0  5001.3    0.05       0  5302.6    0.08       0
  5401.9    0.05       0
Bank Sta=4995.3,5001.3
Exp/Cntr=0.3,0.1

Type RM Length L Ch R = 1,12795,553,553,553
BEGIN DESCRIPTION:
SIMS BRANCH 26.0
END DESCRIPTION:
XS GIS Cut Line= 2
      3814688.69     10501633.89      3813195.71     10501195.54
#Sta/Elev= 30
  4164.2  376.09  4319.6  373.31  4369.5  373.85  4408.1  372.29  4618.8  370.72
  4624.0  369.91  4684.3  369.65  4732.6  367.15  4762.8  364.75  4768.0  363.12
  4778.1  363.10  4809.4  359.44  4821.4  359.11  4882.4  354.72  4973.5  354.87
  4986.6  353.45  4997.0  350.24  5003.9  350.09  5006.6  349.59  5009.9  350.09
  5012.1  353.19  5017.9  355.16  5090.8  354.10  5174.2  354.79  5222.8  356.42
  5288.8  356.28  5466.0  362.44  5486.8  364.45  5518.1  364.62  5720.2  371.71
#Mann=5,-1,0
  4164.2    0.05       0  4732.6    0.08       0  4821.4    0.05       0
  5003.9    0.04       0  5009.9    0.05       0
Bank Sta=5003.9,5009.9
Exp/Cntr=0.3,0.1

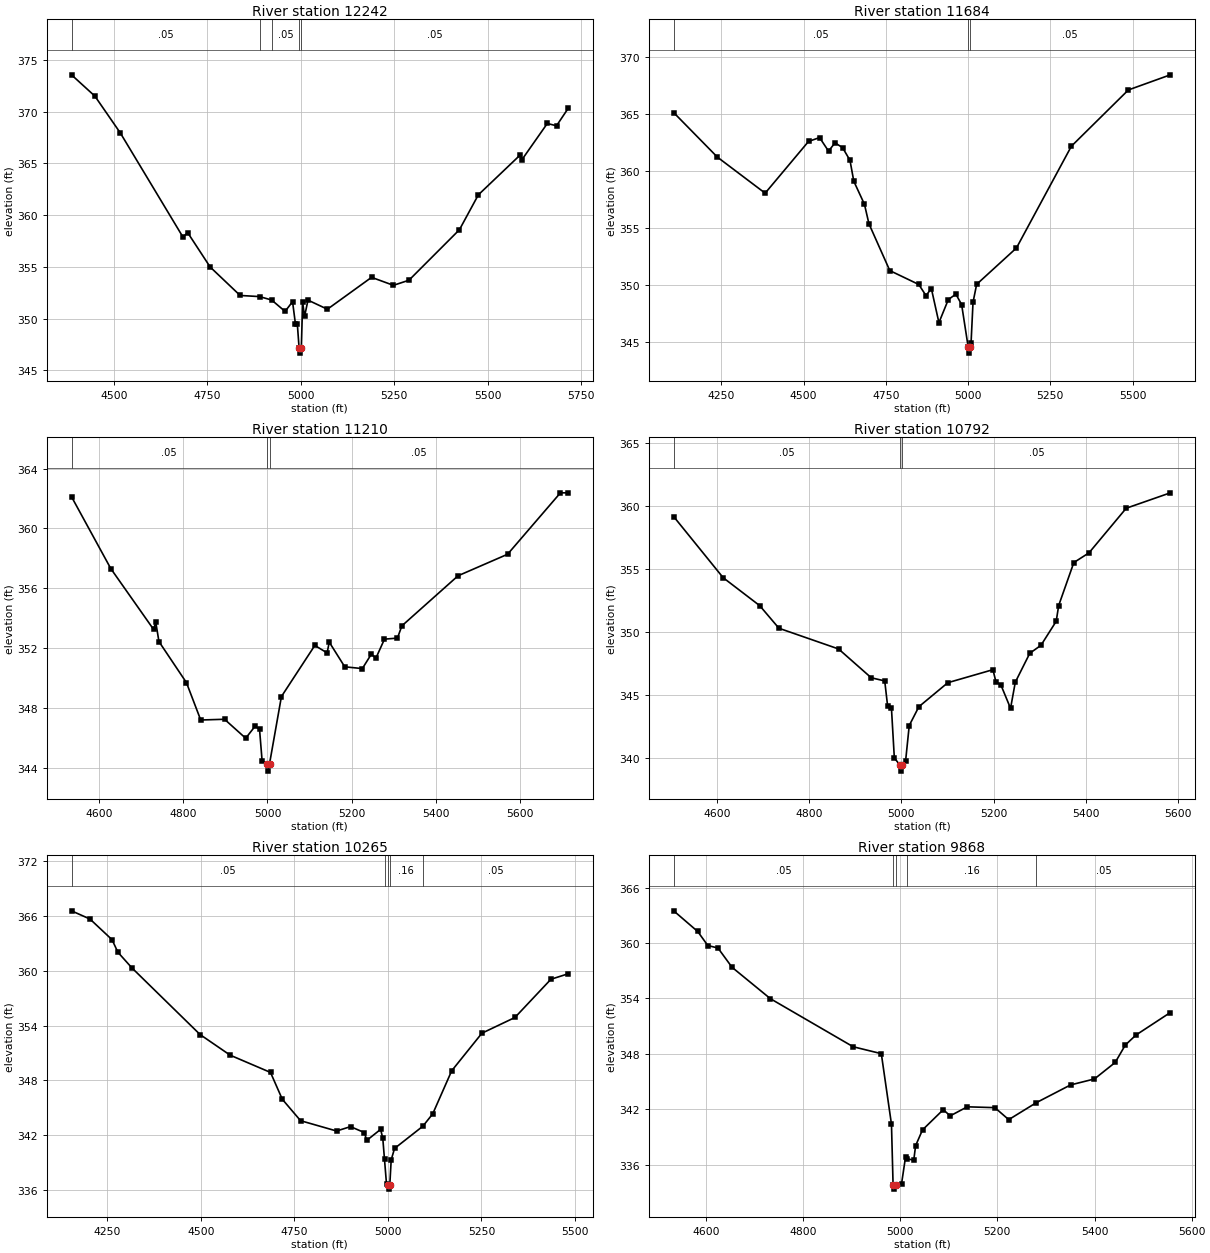
Type RM Length L Ch R = 1,12242,558,558,558
BEGIN DESCRIPTION:
SIMS BRANCH 25.0
END DESCRIPTION:
XS GIS Cut Line= 3
      3814549.61     10501010.19      3813949.61     10500960.19
      3813249.60     10501160.19
#Sta/Elev= 30
  4385.9  373.55  4448.6  371.49  4516.4  367.95  4684.4  357.88  4697.0  358.31
  4757.2  354.99  4837.5  352.24  4889.5  352.13  4921.9  351.80  4957.9  350.70
  4977.9  351.64  4985.5  349.52  4990.6  349.52  4995.4  347.17  4998.1  346.67
  5001.4  347.17  5004.9  351.58  5010.1  350.22  5019.2  351.79  5071.2  350.91
  5189.5  353.99  5248.0  353.22  5289.6  353.71  5424.8  358.59  5475.5  361.96
  5587.3  365.80  5592.5  365.37  5660.1  368.85  5684.8  368.63  5716.0  370.31
#Mann=5,-1,0
  4385.9    0.05       0  4889.5    0.16       0  4921.9    0.05       0
  4995.4    0.03       0  5001.4    0.05       0
Bank Sta=4995.4,5001.4
Exp/Cntr=0.3,0.1

Type RM Length L Ch R = 1,11684,474,474,474
BEGIN DESCRIPTION:
SIMS BRANCH 24.0
END DESCRIPTION:
XS GIS Cut Line= 4
      3814423.94     10500527.12      3813950.87     10500449.00
      3813390.97     10500705.08      3813165.27     10501052.31
#Sta/Elev= 30
  4105.3  365.15  4238.2  361.23  4383.3  358.06  4515.1  362.61  4548.7  362.95
  4575.9  361.76  4595.7  362.49  4618.7  362.06  4641.1  360.95  4652.7  359.11
  4685.1  357.08  4698.7  355.37  4762.1  351.25  4850.1  350.03  4872.1  349.05
  4888.4  349.67  4911.4  346.67  4939.9  348.70  4962.9  349.18  4980.4  348.26
  5000.5  344.49  5003.2  343.99  5006.5  344.49  5009.0  344.87  5015.0  348.46
  5026.0  350.04  5147.0  353.24  5313.9  362.19  5487.1  367.14  5614.6  368.47
#Mann=3,-1,0
  4105.3    0.05       0  5000.5    0.03       0  5006.5    0.05       0
Bank Sta=5000.5,5006.5
Exp/Cntr=0.3,0.1

Type RM Length L Ch R = 1,11210,418,418,418
BEGIN DESCRIPTION:
SIMS BRANCH 23.0
END DESCRIPTION:
XS GIS Cut Line= 3
      3813929.49     10500409.27      3813371.72     10500250.84
      3813230.66     10500834.61
#Sta/Elev= 30
  4534.2  362.12  4627.6  357.31  4729.3  353.24  4734.5  353.72  4742.0  352.43
  4807.4  349.68  4841.3  347.18  4897.9  347.23  4948.2  345.96  4970.7  346.77
  4981.1  346.56  4987.3  344.41  4998.9  344.26  5001.6  343.76  5004.9  344.26
  5033.1  348.75  5112.5  352.17  5141.7  351.67  5146.8  352.39  5183.6  350.74
  5225.4  350.62  5247.1  351.60  5257.4  351.30  5278.0  352.59  5308.8  352.66
  5319.4  353.48  5452.9  356.83  5570.6  358.27  5696.2  362.38  5714.6  362.38
#Mann=3,-1,0
  4534.2    0.05       0  4998.9    0.03       0  5004.9    0.05       0
Bank Sta=4998.9,5004.9
Exp/Cntr=0.3,0.1

Type RM Length L Ch R = 1,10792,527,527,527
BEGIN DESCRIPTION:
SIMS BRANCH 22.0
END DESCRIPTION:
XS GIS Cut Line= 3
      3813899.58     10500360.16      3813599.61     10499960.19
      3813048.07     10499793.62
#Sta/Elev= 30
  4506.7  359.15  4614.0  354.31  4693.1  352.10  4734.8  350.31  4864.0  348.67
  4934.8  346.39  4964.0  346.14  4970.2  344.17  4978.5  344.02  4984.8  340.05
  4996.4  339.50  4999.1  339.00  5002.4  339.50  5009.3  339.83  5017.1  342.61
  5038.0  344.10  5100.7  346.00  5198.4  347.03  5205.1  346.05  5215.6  345.83
  5236.6  343.97  5246.9  346.04  5278.3  348.33  5302.5  348.96  5335.5  350.86
  5340.9  352.11  5373.7  355.51  5406.6  356.28  5487.2  359.81  5582.8  361.03
#Mann=3,-1,0
  4506.7    0.05       0  4996.4    0.03       0  5002.4    0.05       0
Bank Sta=4996.4,5002.4
Exp/Cntr=0.3,0.1

Type RM Length L Ch R = 1,10265,397,397,397
BEGIN DESCRIPTION:
SIMS BRANCH 21.0
END DESCRIPTION:
XS GIS Cut Line= 2
      3814419.66     10499958.57      3813270.01     10499294.82
#Sta/Elev= 30
  4154.4  366.58  4203.8  365.68  4262.7  363.42  4278.4  362.04  4315.8  360.33
  4498.1  353.02  4578.5  350.76  4686.3  348.87  4717.8  345.93  4766.7  343.58
  4862.9  342.45  4900.2  342.93  4937.5  342.27  4943.3  341.41  4980.6  342.63
  4986.4  341.66  4991.0  339.34  4996.4  336.61  4999.2  336.58  5001.9  336.08
  5005.2  336.58  5008.9  339.29  5017.9  340.54  5093.4  342.97  5119.9  344.33
  5170.6  349.05  5251.4  353.17  5339.6  354.89  5435.8  359.08  5481.9  359.68
#Mann=5,-1,0
  4154.4    0.05       0  4991.0    0.16       0  4999.2    0.07       0
  5005.2    0.16       0  5093.4    0.05       0
Bank Sta=4999.2,5005.2
Exp/Cntr=0.3,0.1

Type RM Length L Ch R = 1,9868,472,472,472
BEGIN DESCRIPTION:
SIMS BRANCH 20.0
END DESCRIPTION:
XS GIS Cut Line= 3
      3814389.24     10499758.90      3813999.61     10499460.19
      3813599.58     10499110.16
#Sta/Elev= 30
  4533.6  363.50  4583.1  361.26  4603.9  359.74  4624.8  359.47  4653.8  357.38
  4732.7  353.98  4903.1  348.77  4961.1  348.02  4982.0  340.37  4985.3  333.84
  4988.0  333.34  4991.3  333.84  5002.8  333.94  5011.0  336.83  5014.0  336.63
  5027.9  336.48  5031.7  338.05  5045.9  339.76  5088.6  341.95  5102.9  341.28
  5138.0  342.26  5194.9  342.17  5223.4  340.87  5280.2  342.71  5350.6  344.63
  5399.9  345.28  5442.6  347.07  5463.5  348.96  5485.4  350.04  5556.1  352.48
#Mann=5,-1,0
  4533.6    0.05       0  4985.3    0.03       0  4991.3    0.05       0
  5014.0    0.16       0  5280.2    0.05       0
Bank Sta=4985.3,4991.3
Exp/Cntr=0.3,0.1