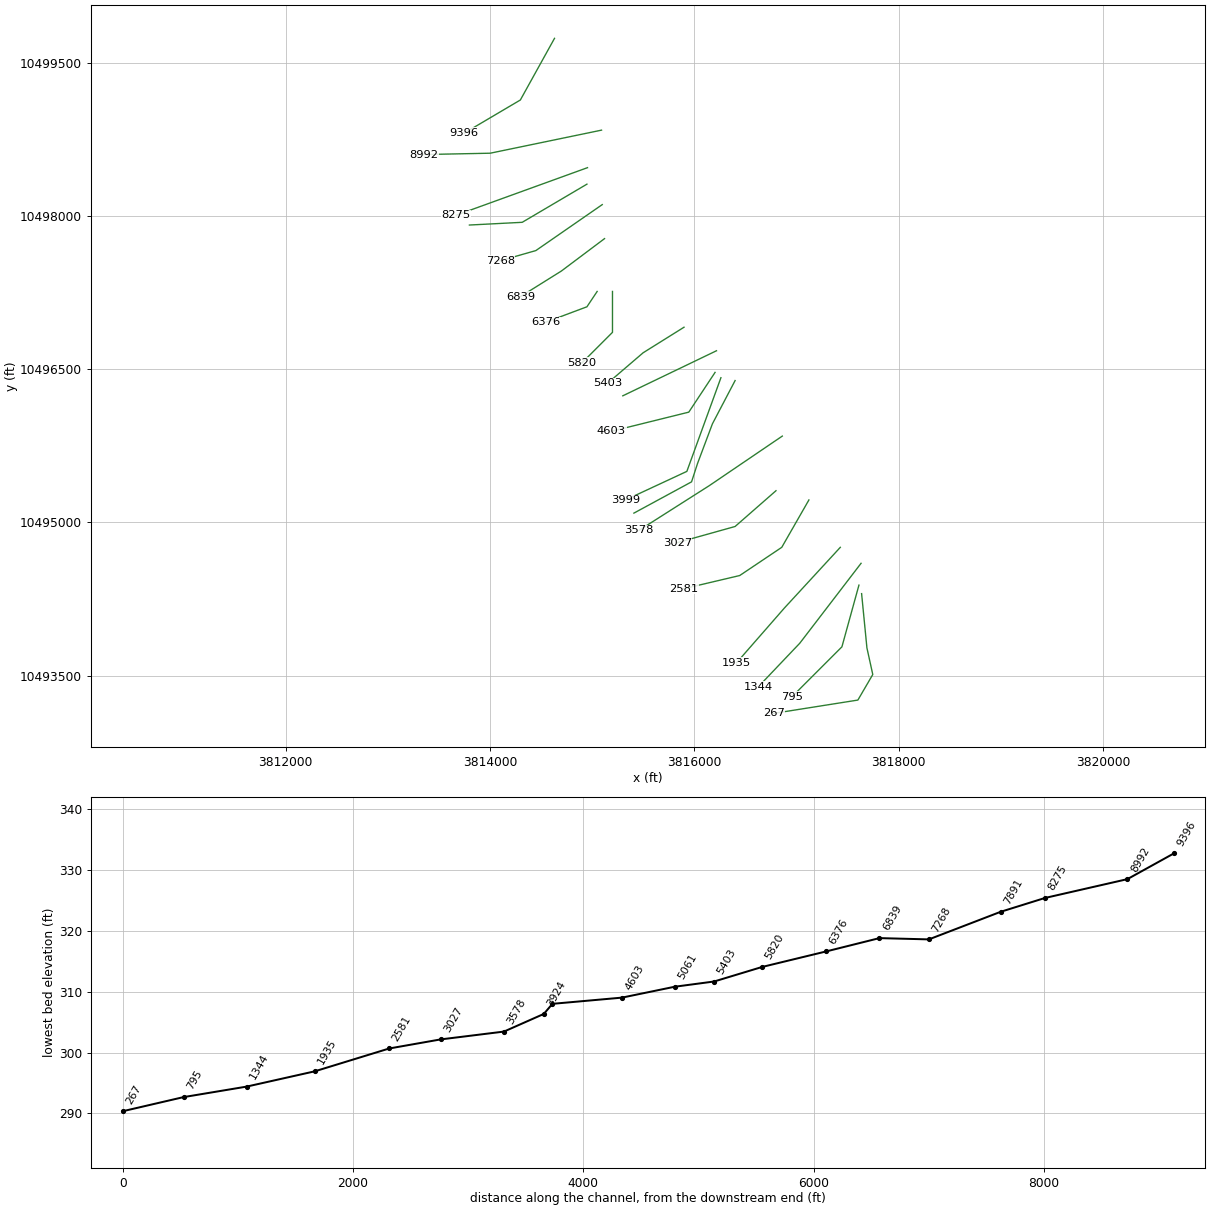
HEC-RAS study SIMS BRANCH.prj: SIMS BRANCH Base Level Engineering

--- SIMS BRANCH.g01 (geometry) --- (continued)

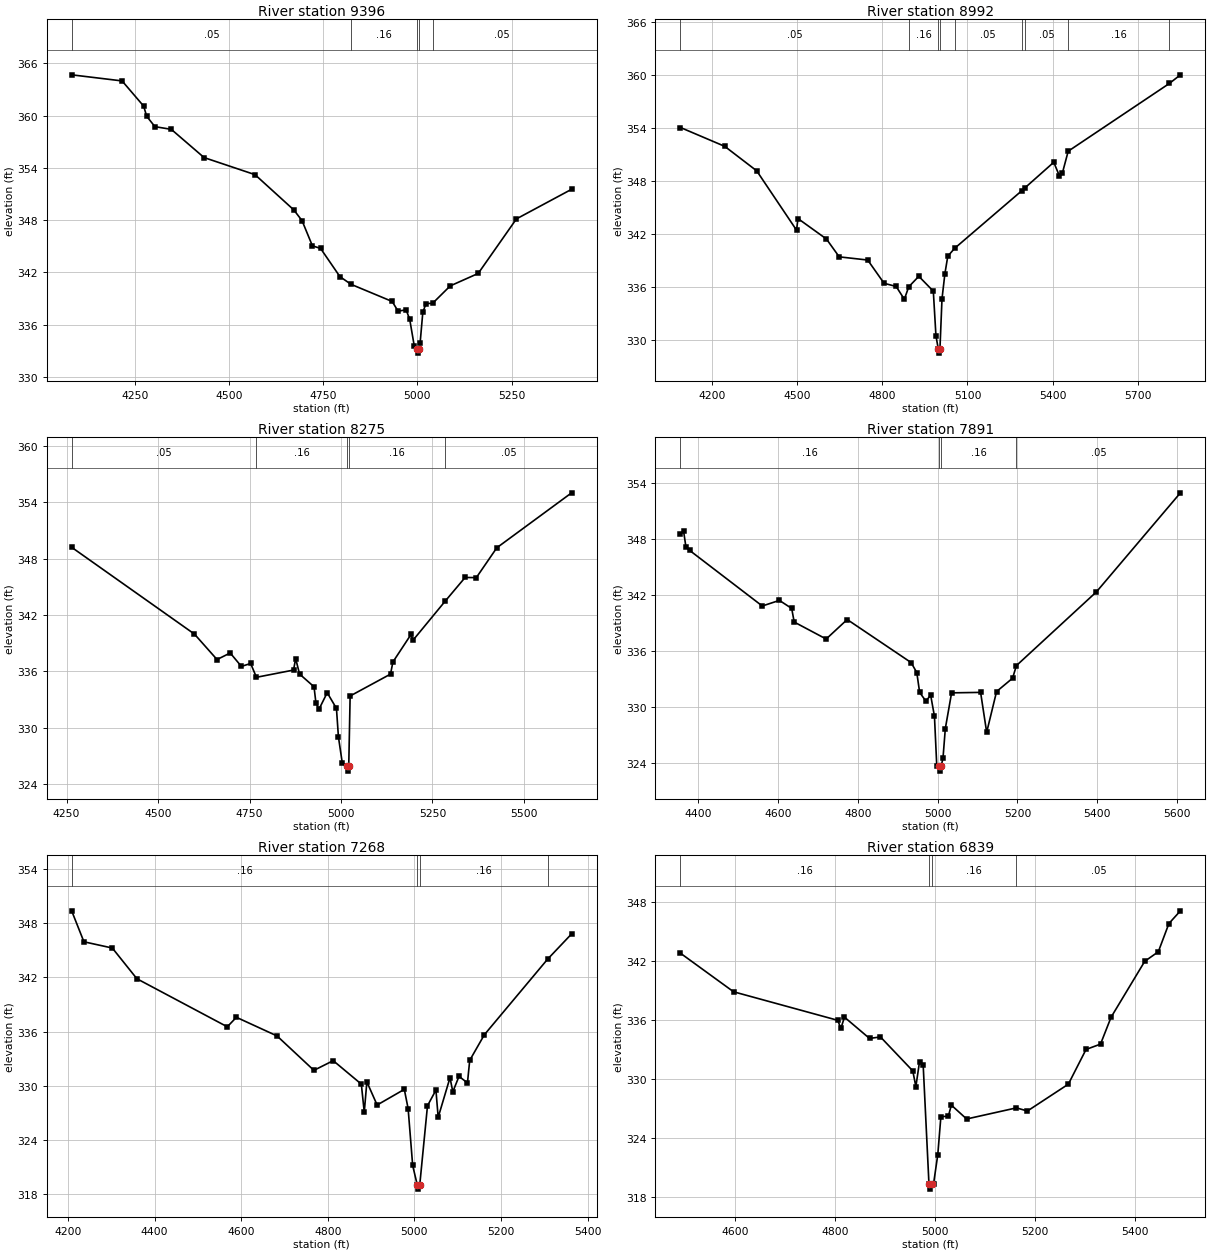
Type RM Length L Ch R = 1,9396,404,404,404
BEGIN DESCRIPTION:
SIMS BRANCH 19.0
END DESCRIPTION:
XS GIS Cut Line= 3
      3814632.31     10499737.23      3814298.09     10499133.90
      3813749.61     10498810.19
#Sta/Elev= 30
  4082.6  364.67  4216.4  363.97  4273.6  361.08  4281.7  359.91  4303.5  358.72
  4347.0  358.41  4434.0  355.17  4569.1  353.21  4672.1  349.16  4693.9  347.93
  4721.4  345.04  4743.1  344.74  4794.5  341.50  4823.9  340.62  4933.1  338.65
  4948.7  337.54  4970.1  337.69  4979.6  336.60  4991.6  333.57  4998.4  333.22
  5001.2  332.72  5004.4  333.22  5007.2  333.86  5014.4  337.41  5022.9  338.41
  5040.4  338.44  5087.2  340.44  5161.4  341.87  5262.8  348.13  5409.2  351.53
#Mann=5,-1,0
  4082.6    0.05       0  4823.9    0.16       0  4998.4    0.07       0
  5004.4    0.16       0  5040.4    0.05       0
Bank Sta=4998.4,5004.4
Exp/Cntr=0.3,0.1

Type RM Length L Ch R = 1,8992,717,717,717
BEGIN DESCRIPTION:
SIMS BRANCH 18.0
END DESCRIPTION:
XS GIS Cut Line= 3
      3815092.35     10498838.76      3814002.95     10498613.06
      3813353.21     10498600.07
#Sta/Elev= 30
  4088.3  354.01  4244.3  351.88  4357.0  349.11  4497.4  342.40  4502.5  343.71
  4602.8  341.40  4647.9  339.38  4748.3  339.02  4806.0  336.39  4848.6  336.03
  4877.5  334.58  4892.9  335.99  4928.5  337.18  4979.6  335.50  4988.9  330.44
  4997.0  328.99  4999.8  328.49  5003.0  328.99  5010.2  334.63  5020.4  337.47
  5030.6  339.45  5054.6  340.34  5291.9  346.87  5302.8  347.19  5404.2  350.08
  5424.2  348.53  5434.2  348.81  5455.1  351.33  5811.6  358.99  5850.7  359.97
#Mann=9,-1,0
  4088.3    0.05       0  4892.9    0.16       0  4997.0    0.07       0
  5003.0    0.16       0  5054.6    0.05       0  5291.9    0.16       0
  5302.8    0.05       0  5455.1    0.16       0  5811.6    0.05       0
Bank Sta=4997,5003
Exp/Cntr=0.3,0.1

Type RM Length L Ch R = 1,8275,384,384,384
BEGIN DESCRIPTION:
SIMS BRANCH 17.0
END DESCRIPTION:
XS GIS Cut Line= 2
      3814955.18     10498471.56      3813670.44     10498006.28
#Sta/Elev= 30
  4263.8  349.22  4599.4  339.98  4661.1  337.27  4697.1  337.97  4727.7  336.54
  4753.0  336.85  4768.8  335.38  4870.2  336.15  4876.0  337.37  4886.6  335.73
  4926.2  334.37  4931.5  332.62  4939.8  331.98  4962.2  333.74  4987.5  332.07
  4992.9  329.04  5003.6  326.21  5015.1  325.89  5017.9  325.39  5021.1  325.89
  5024.9  333.39  5135.3  335.72  5141.8  337.01  5191.3  339.94  5196.6  339.32
  5285.4  343.52  5339.2  346.01  5369.8  345.99  5425.8  349.17  5630.2  355.02
#Mann=5,-1,0
  4263.8    0.05       0  4768.8    0.16       0  5015.1    0.07       0
  5021.1    0.16       0  5285.4    0.05       0
Bank Sta=5015.1,5021.1
Exp/Cntr=0.3,0.1

Type RM Length L Ch R = 1,7891,623,623,623
BEGIN DESCRIPTION:
SIMS BRANCH 16.0
END DESCRIPTION:
XS GIS Cut Line= 3
      3814949.59     10498310.18      3814316.32     10497936.85
      3813799.63     10497910.19
#Sta/Elev= 30
  4355.9  348.57  4363.7  348.84  4369.5  347.16  4379.1  346.77  4560.8  340.82
  4603.7  341.42  4634.5  340.56  4640.8  339.10  4720.9  337.28  4773.6  339.37
  4933.6  334.76  4947.9  333.69  4955.1  331.55  4970.7  330.63  4982.7  331.26
  4992.2  328.99  4998.0  323.66  5002.9  323.62  5005.7  323.12  5008.9  323.62
  5013.6  324.53  5019.4  327.68  5035.1  331.51  5107.8  331.56  5123.0  327.28
  5147.8  331.65  5187.9  333.08  5197.5  334.43  5398.1  342.34  5608.4  352.95
#Mann=4,-1,0
  4355.9    0.16       0  5002.9    0.07       0  5008.9    0.16       0
  5197.5    0.05       0
Bank Sta=5002.9,5008.9
Exp/Cntr=0.3,0.1

Type RM Length L Ch R = 1,7268,429,429,429
BEGIN DESCRIPTION:
SIMS BRANCH 15.0
END DESCRIPTION:
XS GIS Cut Line= 3
      3815099.57     10498110.16      3814449.61     10497660.19
      3814099.63     10497560.20
#Sta/Elev= 30
  4208.7  349.33  4237.0  345.91  4302.6  345.22  4359.3  341.83  4568.1  336.52
  4589.1  337.57  4683.0  335.51  4768.1  331.71  4812.7  332.78  4877.6  330.19
  4884.4  327.09  4890.4  330.44  4914.1  327.88  4976.9  329.61  4985.7  327.48
  4996.2  321.20  5006.6  319.09  5009.4  318.59  5012.6  319.09  5030.4  327.80
  5049.9  329.53  5055.1  326.52  5082.4  330.90  5088.9  329.34  5103.2  331.05
  5122.7  330.32  5127.9  332.81  5161.7  335.64  5307.6  343.98  5363.2  346.78
#Mann=4,-1,0
  4208.7    0.16       0  5006.6    0.07       0  5012.6    0.16       0
  5307.6    0.05       0
Bank Sta=5006.6,5012.6
Exp/Cntr=0.3,0.1

Type RM Length L Ch R = 1,6839,463,463,463
BEGIN DESCRIPTION:
SIMS BRANCH 14.0
END DESCRIPTION:
XS GIS Cut Line= 3
      3815121.89     10497777.14      3814699.61     10497460.19
      3814299.61     10497210.19
#Sta/Elev= 30
  4491.1  342.78  4597.3  338.86  4805.6  335.96  4811.8  335.13  4819.0  336.28
  4869.1  334.12  4891.0  334.27  4955.6  330.82  4961.8  329.22  4969.1  331.75
  4976.4  331.42  4988.0  319.30  4990.7  318.80  4994.0  319.30  4997.2  319.35
  5005.6  322.30  5011.8  326.16  5026.8  326.22  5032.7  327.34  5063.3  325.93
  5162.9  327.06  5184.8  326.74  5266.7  329.47  5302.1  333.00  5331.0  333.54
  5352.2  336.28  5419.5  341.96  5446.6  342.93  5467.8  345.80  5490.8  347.09
#Mann=4,-1,0
  4491.1    0.16       0  4988.0    0.07       0  4994.0    0.16       0
  5162.9    0.05       0
Bank Sta=4988,4994
Exp/Cntr=0.3,0.1

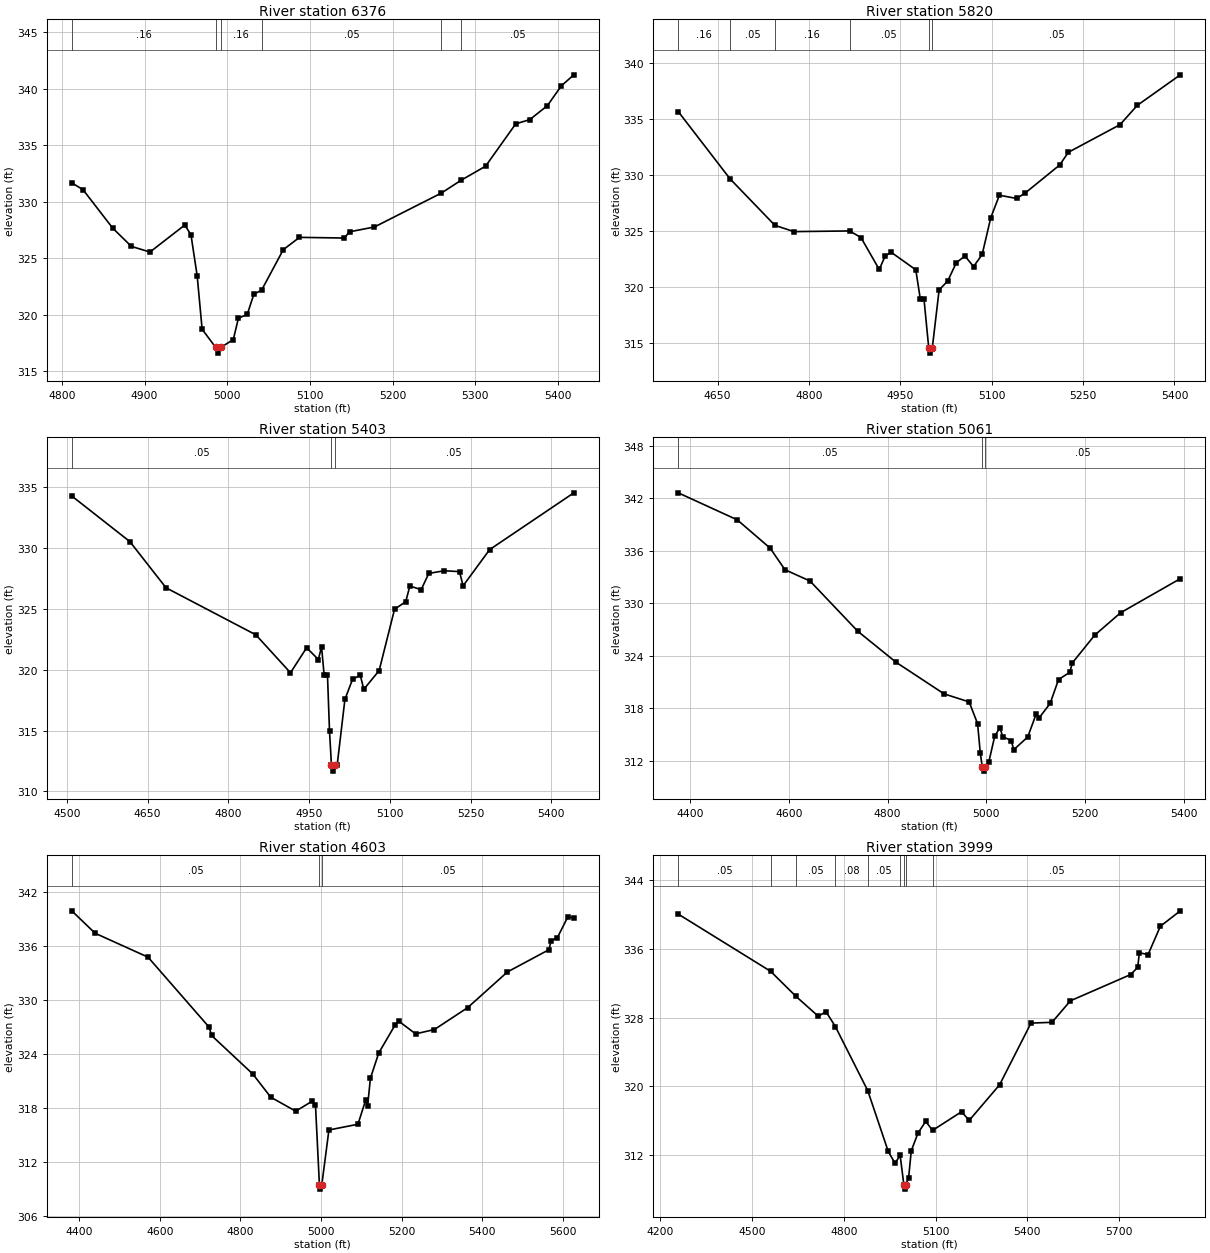
Type RM Length L Ch R = 1,6376,556,556,556
BEGIN DESCRIPTION:
SIMS BRANCH 13.0
END DESCRIPTION:
XS GIS Cut Line= 3
      3815049.58     10497260.15      3814949.61     10497110.19
      3814549.64     10496960.20
#Sta/Elev= 30
  4811.9  331.68  4825.4  331.09  4861.4  327.68  4884.0  326.06  4906.5  325.56
  4948.6  327.95  4956.1  327.09  4963.6  323.46  4969.6  318.72  4986.1  317.11
  4988.9  316.61  4992.1  317.11  5007.3  317.81  5013.5  319.70  5024.2  320.04
  5032.2  321.83  5041.5  322.18  5067.8  325.77  5087.4  326.86  5141.6  326.80
  5147.9  327.35  5178.1  327.78  5259.0  330.78  5283.0  331.92  5312.5  333.16
  5349.0  336.91  5365.9  337.28  5387.3  338.52  5404.2  340.28  5419.3  341.25
#Mann=6,-1,0
  4811.9    0.16       0  4986.1    0.07       0  4992.1    0.16       0
  5041.5    0.05       0  5259.0     0.1       0  5283.0    0.05       0
Bank Sta=4986.1,4992.1
Exp/Cntr=0.3,0.1

Type RM Length L Ch R = 1,5820,417,417,417
BEGIN DESCRIPTION:
SIMS BRANCH 12.0
END DESCRIPTION:
XS GIS Cut Line= 3
      3815199.61     10497260.20      3815199.61     10496860.19
      3814899.59     10496560.17
#Sta/Elev= 30
  4585.3  335.63  4670.4  329.62  4744.0  325.47  4775.3  324.91  4866.7  324.97
  4885.3  324.38  4915.3  321.53  4925.3  322.76  4935.3  323.05  4975.3  321.50
  4982.8  318.87  4988.8  318.87  4996.5  314.56  4999.2  314.06  5002.5  314.56
  5013.6  319.70  5027.7  320.50  5041.9  322.14  5056.0  322.73  5070.2  321.79
  5084.3  322.87  5098.4  326.15  5112.6  328.16  5140.9  327.87  5155.0  328.36
  5211.6  330.86  5225.7  331.99  5310.6  334.46  5338.9  336.18  5409.6  338.91
#Mann=6,-1,0
  4585.3    0.16       0  4670.4    0.05       0  4744.0    0.16       0
  4866.7    0.05       0  4996.5    0.03       0  5002.5    0.05       0
Bank Sta=4996.5,5002.5
Exp/Cntr=0.3,0.1

Type RM Length L Ch R = 1,5403,342,342,342
BEGIN DESCRIPTION:
SIMS BRANCH 11.0
END DESCRIPTION:
XS GIS Cut Line= 3
      3815899.61     10496910.19      3815499.61     10496660.19
      3815149.59     10496360.17
#Sta/Elev= 30
  4509.0  334.30  4616.9  330.55  4684.1  326.75  4851.0  322.88  4915.3  319.76
  4945.3  321.82  4967.1  320.85  4973.0  321.90  4977.8  319.59  4984.0  319.59
  4987.8  314.96  4991.4  312.17  4994.2  311.67  4997.4  312.17  5002.1  312.19
  5016.4  317.57  5030.6  319.22  5044.9  319.57  5051.5  318.40  5080.0  319.94
  5108.6  324.98  5129.4  325.61  5137.1  326.90  5158.0  326.59  5172.2  327.93
  5200.8  328.15  5229.3  328.08  5235.9  326.91  5285.3  329.89  5441.7  334.56
#Mann=3,-1,0
  4509.0    0.05       0  4991.4    0.03       0  4997.4    0.05       0
Bank Sta=4991.4,4997.4
Exp/Cntr=0.3,0.1

Type RM Length L Ch R = 1,5061,458,458,458
BEGIN DESCRIPTION:
SIMS BRANCH 10.0
END DESCRIPTION:
XS GIS Cut Line= 2
      3816217.38     10496679.92      3815300.73     10496238.95
#Sta/Elev= 30
  4375.7  342.62  4495.3  339.53  4561.9  336.30  4591.9  333.83  4642.7  332.54
  4739.4  326.80  4817.1  323.25  4914.3  319.64  4965.1  318.72  4982.2  316.23
  4987.7  312.85  4991.7  311.31  4994.4  310.81  4997.7  311.31  5004.8  311.82
  5016.9  314.80  5027.5  315.79  5033.0  314.75  5050.1  314.31  5055.6  313.26
  5083.8  314.72  5100.9  317.34  5106.4  316.86  5129.1  318.54  5146.2  321.28
  5168.8  322.10  5174.3  323.19  5219.6  326.36  5272.1  328.92  5392.9  332.81
#Mann=3,-1,0
  4375.7    0.05       0  4991.7    0.03       0  4997.7    0.05       0
Bank Sta=4991.7,4997.7
Exp/Cntr=0.3,0.1

Type RM Length L Ch R = 1,4603,604,604,604
BEGIN DESCRIPTION:
SIMS BRANCH 9.0
END DESCRIPTION:
XS GIS Cut Line= 3
      3816203.48     10496468.11      3815946.53     10496079.21
      3815189.62     10495891.72
#Sta/Elev= 30
  4381.3  339.94  4439.2  337.45  4570.6  334.79  4722.2  327.01  4728.2  326.09
  4830.5  321.81  4875.2  319.23  4937.0  317.68  4978.2  318.80  4986.1  318.35
  4995.8  309.52  4998.5  309.02  5001.8  309.52  5019.4  315.59  5091.5  316.23
  5110.3  318.87  5115.5  318.30  5122.4  321.34  5143.0  324.14  5184.2  327.30
  5193.1  327.67  5234.5  326.27  5281.1  326.75  5363.9  329.19  5462.4  333.15
  5565.4  335.62  5570.9  336.64  5586.0  336.93  5612.3  339.27  5627.2  339.16
#Mann=3,-1,0
  4381.3    0.05       0  4995.8    0.03       0  5001.8    0.05       0
Bank Sta=4995.8,5001.8
Exp/Cntr=0.3,0.1

Type RM Length L Ch R = 1,3999,75,75,75
BEGIN DESCRIPTION:
SIMS BRANCH 8.0
END DESCRIPTION:
XS GIS Cut Line= 3
      3816260.78     10496416.06      3815927.43     10495499.35
      3815323.96     10495218.42
#Sta/Elev= 30
  4259.0  340.07  4560.9  333.40  4644.0  330.47  4716.7  328.16  4742.0  328.69
  4772.7  326.95  4878.5  319.48  4945.5  312.39  4967.5  311.02  4984.4  311.93
  4996.5  308.50  4999.2  308.00  5002.5  308.50  5012.0  309.32  5020.7  312.47
  5042.6  314.53  5067.9  315.90  5090.3  314.85  5184.9  317.02  5210.2  316.02
  5309.3  320.16  5412.1  327.36  5480.7  327.45  5540.9  329.96  5737.9  333.02
  5760.8  333.86  5766.3  335.56  5794.7  335.35  5834.9  338.65  5900.1  340.45
#Mann=9,-1,0
  4259.0    0.05       0  4560.9    0.08       0  4644.0    0.05       0
  4772.7    0.08       0  4878.5    0.05       0  4984.4    0.08       0
  4996.5    0.07       0  5002.5    0.08       0  5090.3    0.05       0
Bank Sta=4996.5,5002.5
Exp/Cntr=0.3,0.1

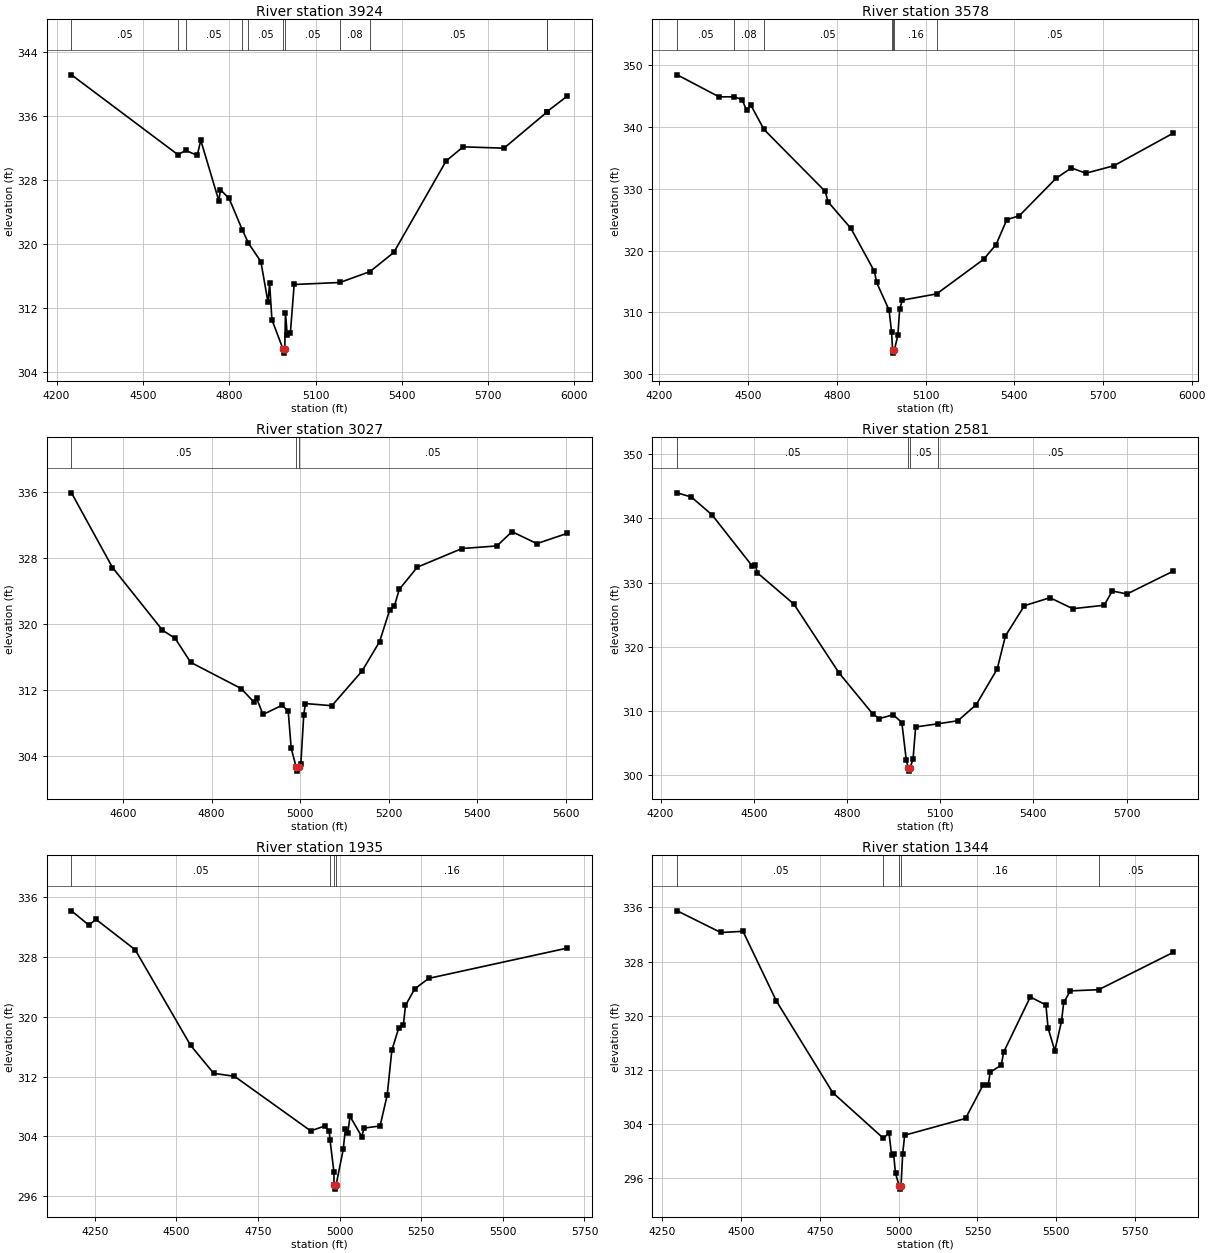
Type RM Length L Ch R = 1,3924,346,346,346
BEGIN DESCRIPTION:
SIMS BRANCH 7.0
END DESCRIPTION:
XS GIS Cut Line= 5
      3816399.65     10496388.24      3816177.43     10495964.63
      3816031.60     10495575.74      3815973.44     10495396.92
      3815409.20     10495090.93
#Sta/Elev= 30
  4251.7  341.09  4621.6  331.12  4649.0  331.65  4688.7  331.03  4701.2  332.91
  4764.0  325.35  4769.4  326.75  4799.6  325.65  4845.9  321.70  4866.5  320.09
  4910.0  317.77  4934.9  312.67  4940.3  315.08  4948.4  310.50  4987.1  306.84
  4989.8  306.34  4993.1  306.84  4995.4  311.37  5001.8  308.55  5012.5  308.85
  5025.7  314.91  5184.7  315.16  5289.2  316.52  5371.9  318.91  5553.9  330.34
  5613.1  332.10  5754.8  331.93  5903.1  336.40  5904.0  336.48  5975.3  338.45
#Mann=11,-1,0
  4251.7    0.05       0  4621.6    0.08       0  4649.0    0.05       0
  4845.9    0.08       0  4866.5    0.05       0  4987.1    0.04       0
  4993.1    0.05       0  5184.7    0.08       0  5289.2    0.05       0
  5903.1    0.08       0  5904.0    0.05       0
Bank Sta=4987.1,4993.1
Exp/Cntr=0.3,0.1

Type RM Length L Ch R = 1,3578,551,551,551
BEGIN DESCRIPTION:
Mapping XS cb5fd9b5
END DESCRIPTION:
XS GIS Cut Line= 3
      3816861.45     10495844.83      3816147.92     10495360.46
      3815460.42     10494922.96
#Sta/Elev= 30
  4260.1  348.36  4401.6  344.81  4452.4  344.81  4479.9  344.36  4494.5  342.62
  4509.4  343.44  4553.6  339.54  4761.0  329.53  4769.9  327.88  4847.8  323.56
  4927.1  316.63  4934.6  314.84  4976.6  310.39  4985.1  306.86  4988.5  303.94
  4991.3  303.44  4994.5  303.94  5006.4  306.32  5012.5  310.53  5021.4  311.99
  5137.5  313.00  5296.2  318.57  5338.5  320.96  5374.9  324.98  5417.2  325.62
  5541.7  331.67  5593.3  333.33  5642.0  332.48  5736.9  333.68  5937.4  338.94
#Mann=7,-1,0
  4260.1    0.05       0  4452.4    0.08       0  4553.6    0.05       0
  4985.1    0.16       0  4988.5    0.07       0  4994.5    0.16       0
  5137.5    0.05       0
Bank Sta=4988.5,4994.5
Exp/Cntr=0.3,0.1

Type RM Length L Ch R = 1,3027,446,446,446
BEGIN DESCRIPTION:
SIMS BRANCH 6.0
END DESCRIPTION:
XS GIS Cut Line= 3
      3816799.64     10495310.21      3816399.61     10494960.19
      3815833.28     10494801.81
#Sta/Elev= 30
  4483.7  335.84  4576.3  326.80  4689.2  319.21  4717.7  318.23  4752.8  315.32
  4866.7  312.15  4895.2  310.53  4901.8  310.95  4916.1  309.01  4958.8  310.11
  4973.0  309.43  4979.7  304.94  4990.9  302.65  4993.6  302.15  4996.9  302.65
  5001.5  303.00  5008.1  308.96  5011.9  310.33  5071.6  310.07  5139.8  314.27
  5179.3  317.82  5202.1  321.65  5212.5  322.09  5223.8  324.16  5264.5  326.84
  5365.5  329.10  5444.2  329.41  5478.3  331.14  5534.4  329.69  5603.3  330.94
#Mann=3,-1,0
  4483.7    0.05       0  4990.9    0.03       0  4996.9    0.05       0
Bank Sta=4990.9,4996.9
Exp/Cntr=0.3,0.1

Type RM Length L Ch R = 1,2581,646,646,646
BEGIN DESCRIPTION:
SIMS BRANCH 5.0
END DESCRIPTION:
XS GIS Cut Line= 4
      3817121.88     10495219.84      3816856.25     10494756.29
      3816444.79     10494480.25      3815893.65     10494350.27
#Sta/Elev= 30
  4253.7  343.96  4299.4  343.30  4365.8  340.53  4495.3  332.56  4505.4  332.74
  4511.2  331.53  4629.1  326.65  4774.4  315.94  4883.0  309.56  4904.3  308.84
  4949.0  309.43  4976.6  308.22  4991.0  302.34  4997.0  301.16  4999.7  300.66
  5003.0  301.16  5012.7  302.56  5021.0  307.53  5091.9  308.02  5157.2  308.50
  5216.1  311.01  5283.4  316.54  5310.0  321.70  5371.0  326.40  5453.2  327.64
  5526.8  325.93  5627.8  326.47  5653.8  328.69  5701.2  328.22  5849.7  331.77
#Mann=4,-1,0
  4253.7    0.05       0  4997.0    0.03       0  5003.0    0.05       0
  5091.9    0.05       0
Bank Sta=4997,5003
Exp/Cntr=0.3,0.1

Type RM Length L Ch R = 1,1935,591,591,591
BEGIN DESCRIPTION:
SIMS BRANCH 4.0
END DESCRIPTION:
XS GIS Cut Line= 3
      3817429.17     10494756.29      3816882.29     10494162.54
      3816414.08     10493626.71
#Sta/Elev= 30
  4178.9  334.20  4232.3  332.28  4253.9  333.06  4374.1  328.98  4543.7  316.18
  4614.6  312.42  4678.1  312.03  4911.7  304.71  4954.3  305.37  4968.4  304.67
  4970.6  303.55  4982.6  299.25  4983.1  297.41  4985.9  296.91  4989.1  297.41
  5011.1  302.22  5017.7  304.91  5025.3  304.46  5032.0  306.66  5068.0  303.94
  5074.7  305.09  5124.0  305.37  5145.9  309.52  5160.1  315.51  5181.0  318.48
  5195.2  318.84  5201.9  321.52  5230.3  323.75  5273.1  325.15  5697.7  329.21
#Mann=4,-1,0
  4178.9    0.05       0  4970.6    0.16       0  4983.1    0.07       0
  4989.1    0.16       0
Bank Sta=4983.1,4989.1
Exp/Cntr=0.3,0.1

Type RM Length L Ch R = 1,1344,549,549,549
BEGIN DESCRIPTION:
SIMS BRANCH 3.0
END DESCRIPTION:
XS GIS Cut Line= 3
      3817632.28     10494600.02      3817033.33     10493818.79
      3816627.11     10493391.74
#Sta/Elev= 30
  4297.1  335.50  4435.2  332.30  4505.9  332.47  4611.9  322.17  4790.5  308.66
  4951.6  301.90  4969.1  302.73  4977.3  299.48  4983.6  299.65  4989.9  296.71
  5001.4  294.90  5004.2  294.40  5007.4  294.90  5012.6  299.63  5018.9  302.36
  5212.1  304.84  5268.2  309.81  5284.0  309.75  5290.3  311.68  5325.5  312.70
  5332.8  314.61  5417.6  322.78  5467.1  321.60  5474.0  318.19  5495.4  314.84
  5516.5  319.16  5523.7  321.97  5544.8  323.68  5634.5  323.85  5870.9  329.36
#Mann=5,-1,0
  4297.1    0.05       0  4951.6    0.16       0  5001.4    0.07       0
  5007.4    0.16       0  5634.5    0.05       0
Bank Sta=5001.4,5007.4
Exp/Cntr=0.3,0.1

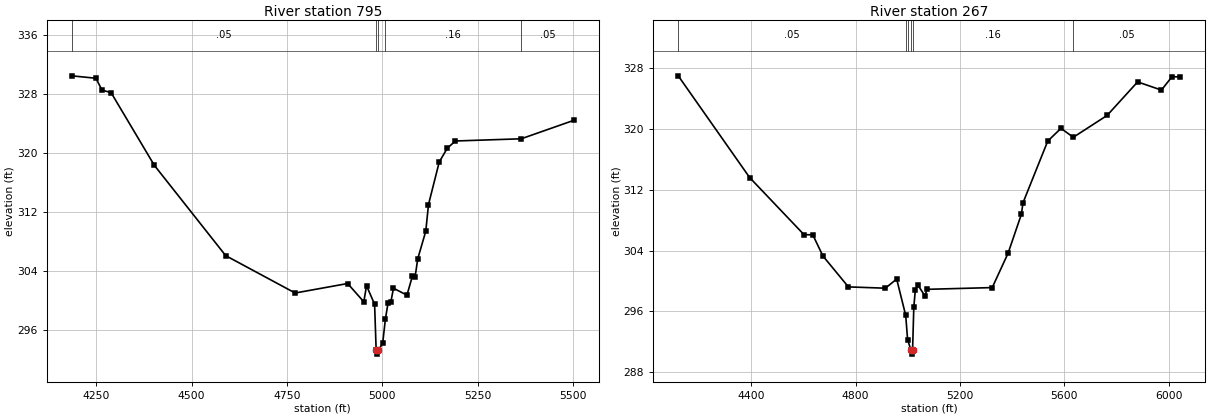
Type RM Length L Ch R = 1,795,528,528,528
BEGIN DESCRIPTION:
SIMS BRANCH 2.0
END DESCRIPTION:
XS GIS Cut Line= 3
      3817611.47     10494386.55      3817444.79     10493782.34
      3816956.45     10493293.99
#Sta/Elev= 30
  4185.4  330.51  4248.9  330.18  4264.6  328.57  4288.5  328.23  4401.9  318.35
  4589.3  306.06  4771.5  300.98  4909.3  302.27  4951.7  299.78  4958.8  301.97
  4980.0  299.45  4984.1  293.17  4986.8  292.67  4990.1  293.17  5001.2  294.16
  5008.3  297.42  5015.4  299.68  5022.4  299.70  5029.5  301.63  5064.9  300.69
  5079.0  303.25  5086.1  303.09  5093.1  305.61  5114.3  309.39  5121.4  313.01
  5149.7  318.81  5170.9  320.68  5192.1  321.65  5364.8  321.95  5502.8  324.46
#Mann=5,-1,0
  4185.4    0.05       0  4984.1    0.03       0  4990.1    0.05       0
  5008.3    0.16       0  5364.8    0.05       0
Bank Sta=4984.1,4990.1
Exp/Cntr=0.3,0.1

Type RM Length L Ch R = 1,267,0,0,0
BEGIN DESCRIPTION:
SIMS BRANCH 1.0
END DESCRIPTION:
XS GIS Cut Line= 5
      3817637.50     10494303.21      3817689.58     10493771.92
      3817746.88     10493511.50      3817601.04     10493261.50
      3816778.09     10493131.29
#Sta/Elev= 30
  4120.8  327.03  4394.4  313.62  4602.4  306.10  4636.3  306.07  4674.9  303.29
  4772.6  299.21  4914.1  299.04  4957.5  300.24  4992.1  295.45  4999.3  292.27
  5012.4  290.85  5015.2  290.35  5018.4  290.85  5023.1  296.54  5028.9  298.81
  5038.6  299.46  5066.1  298.00  5073.3  298.89  5323.5  299.12  5384.3  303.66
  5434.9  308.76  5441.5  310.31  5536.1  318.43  5586.8  320.11  5634.0  318.93
  5763.5  321.81  5880.4  326.23  5971.5  325.15  6012.0  326.91  6043.9  326.89
#Mann=6,-1,0
  4120.8    0.05       0  4992.1    0.12       0  4999.3    0.16       0
  5012.4    0.07       0  5018.4    0.16       0  5634.0    0.05       0
Bank Sta=5012.4,5018.4
Exp/Cntr=0.3,0.1

Chan Stop Cuts=-1