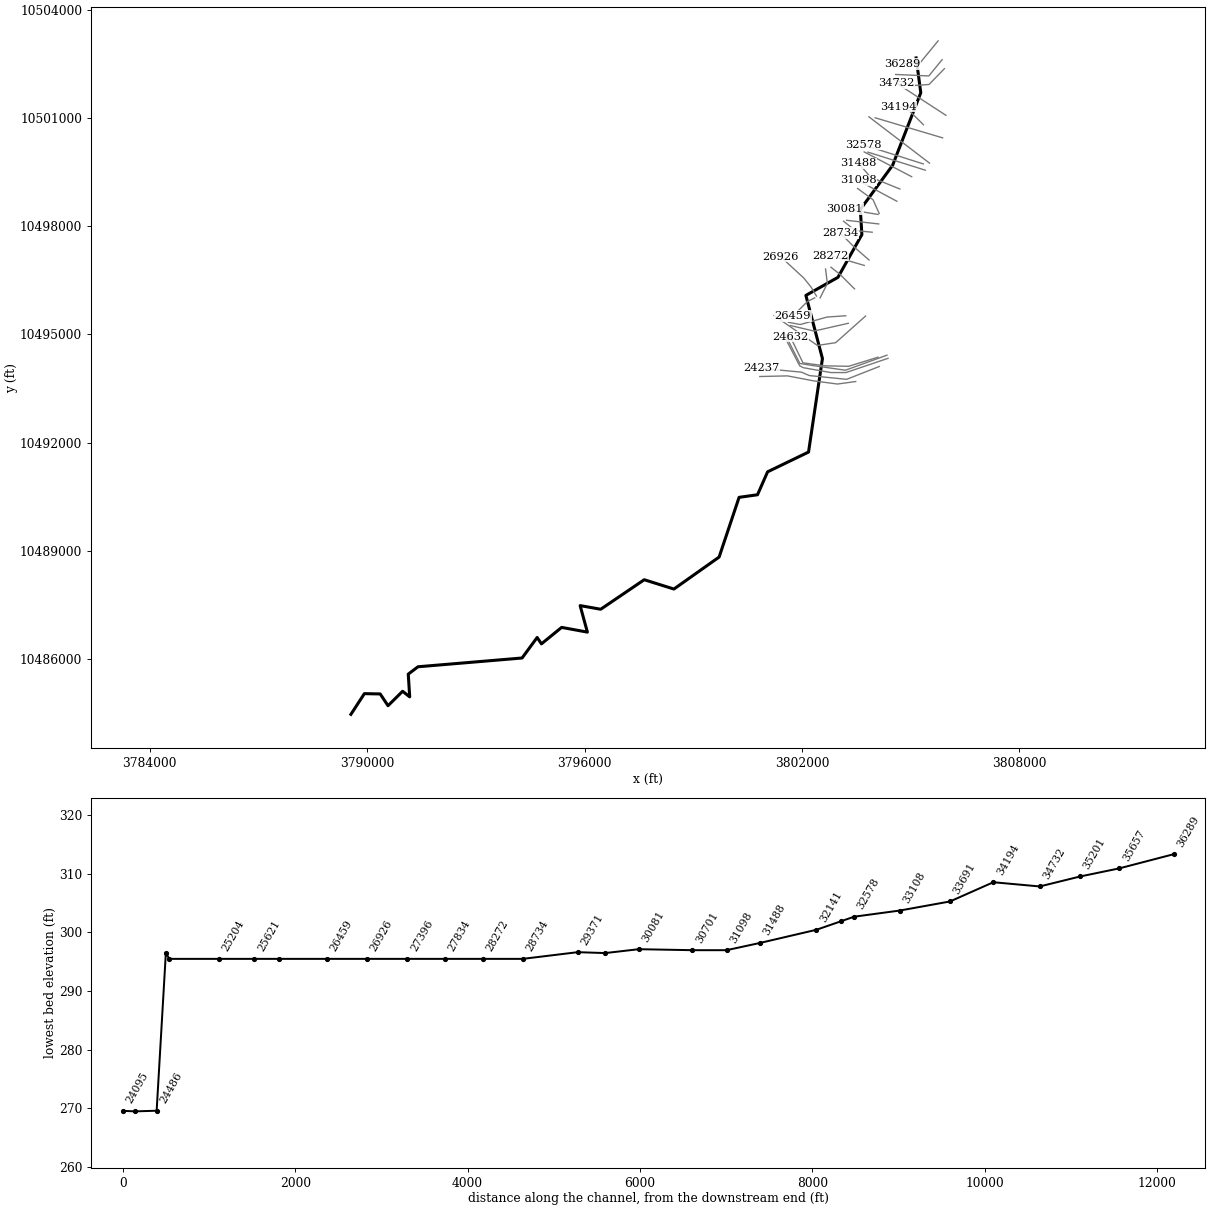
--- SPRING CREEK 1.prj (project) ---

Proj Title=SPRING CREEK 1 Base Level Engineering
Current Plan=p01
Default Exp/Contr=0.3,0.1
English Units
Geom File=g01
Flow File=f01
Plan File=p01
Y Axis Title=Elevation
X Axis Title(PF)=Main Channel Distance
X Axis Title(XS)=Station
BEGIN DESCRIPTION:
SPRING CREEK 1
END DESCRIPTION:
DSS Export Rating Curves= 0
DSS Export Rating Curve Sorted= 0
DSS Export Volume Flow Curves= 0
DXF OffsetX= 0
DXF OffsetY= 0
DXF ScaleX= 1
DXF ScaleY= 10

--- SPRING CREEK 1.p01 (plan) ---

Plan Title=Multiple Run
Short Identifier=Multiple
Geom File=g01
Flow File=f01
Subcritical Flow
K Sum by GR= 0
Std Step Tol= 0.01
Critical Tol= 0.01
Num of Std Step Trials= 20
Max Error Tol= 0.3
Flow Tol Ratio= 0.001
Split Flow NTrial= 30
Split Flow Tol= 0.02
Split Flow Ratio= 0.02
Log Output Level= 0
Friction Slope Method= 1
Unsteady Friction Slope Method= 2
Unsteady Bridges Friction Slope Method= 1
Parabolic Critical Depth
Global Vel Dist=  1 , 1 , 1
Global Log Level= 0
CheckData=True
Encroach Param= -1, 0, 0, 0
BEGIN DESCRIPTION:
Multiple Run
END DESCRIPTION:

--- SPRING CREEK 1.f01 (steady flow) ---

Flow Title=Multiple
Program Version=4.10
Number of Profiles= 7
Profile Names=10-year,25-year,50-year,1pct_min,100-year,1pct_plu,500-year
River Rch & RM=SPRING CREEK 1,Reach-1         ,36289
     734    1002    1226    1101    1489    2014    2206
River Rch & RM=SPRING CREEK 1,Reach-1         ,32422
     908    1247    1530    1379    1864    2521    2777
River Rch & RM=SPRING CREEK 1,Reach-1         ,24095
    1117    1548    1912    1731    2342    3167    3526
Boundary for River Rch & Prof#=SPRING CREEK 1,Reach-1         , 1
Up Type= 0
Dn Type= 3
Dn Slope=0.0047
Boundary for River Rch & Prof#=SPRING CREEK 1,Reach-1         , 2
Up Type= 0
Dn Type= 3
Dn Slope=0.0047
Boundary for River Rch & Prof#=SPRING CREEK 1,Reach-1         , 3
Up Type= 0
Dn Type= 3
Dn Slope=0.0047
Boundary for River Rch & Prof#=SPRING CREEK 1,Reach-1         , 4
Up Type= 0
Dn Type= 3
Dn Slope=0.0047
Boundary for River Rch & Prof#=SPRING CREEK 1,Reach-1         , 5
Up Type= 0
Dn Type= 3
Dn Slope=0.0047
Boundary for River Rch & Prof#=SPRING CREEK 1,Reach-1         , 6
Up Type= 0
Dn Type= 3
Dn Slope=0.0047
Boundary for River Rch & Prof#=SPRING CREEK 1,Reach-1         , 7
Up Type= 0
Dn Type= 3
Dn Slope=0.0047
DSS Import GetInterval= 0
DSS Import GetPeak= 0
DSS Import FillOption= 0

--- SPRING CREEK 1.g01 (geometry) ---

Geom Title=Existing Conditions
Program Version=4.10

River Reach=SPRING CREEK 1  ,Reach-1
Reach XY= 30
      3805149.61     10502660.19      3805277.75       10501696.
      3804500.25       10499685.      3803609.25       10498460.
      3803652.25       10497764.      3802991.75       10496580.
      3802106.75       10496079.       3802563.5       10494329.
      3802179.75       10491738.       3801049.5       10491190.
      3800771.75       10490555.      3800263.25       10490483.
       3799711.5       10488828.      3798464.25       10487942.
      3797644.75       10488200.        3796444.       10487382.
      3795875.75       10487483.        3796076.       10486748.
      3795365.75       10486879.      3794808.25       10486423.
      3794689.25       10486600.      3794273.75       10486031.
        3791401.       10485788.        3791132.       10485584.
        3791172.       10484954.      3790976.25       10485109.
      3790573.25       10484709.       3790357.5       10485035.
       3789920.5       10485043.       3789549.5       10484470.

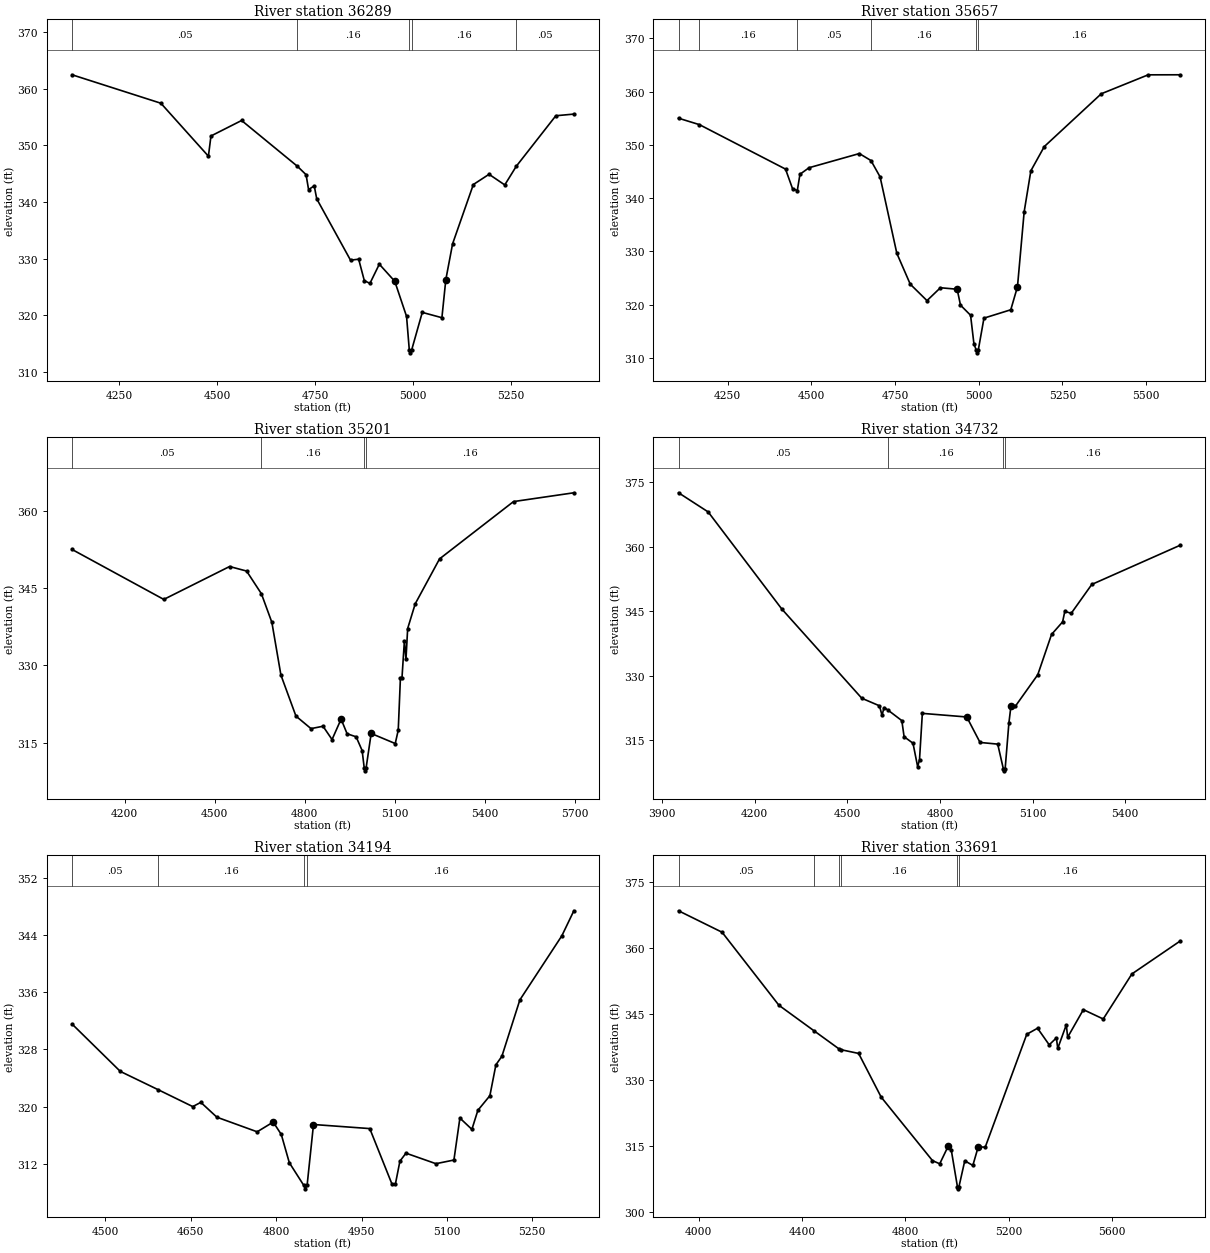
Type RM Length L Ch R = 1 ,36289   ,632,632,632
BEGIN DESCRIPTION:
SPRING CREEK 1 34.0
END DESCRIPTION:
XS GIS Cut Line= 3
      3805756.14     10503132.85      3805263.11     10502528.72
      3804763.71     10502493.73
#Sta/Elev= 30
  4130.4  362.49    4357  357.46  4478.3   348.1  4484.8  351.67    4563  354.41
  4705.3  346.32  4727.5  344.83  4733.9  342.19  4748.3  342.86  4754.7  340.56
  4840.9  329.72  4861.7  329.89  4876.1  326.11  4890.4  325.61  4914.4  329.01
  4953.8  325.99  4983.9  319.78  4990.9  313.84  4993.6  313.34  4996.9  313.84
    5024  320.49  5074.1  319.55  5084.1  326.29  5101.4  332.62  5154.3  343.09
  5194.4   344.9  5234.5  343.02  5263.9  346.32  5364.8  355.25  5410.8  355.54
#Mann= 5 ,-1 , 0
  4130.4     .05       0  4705.3     .16       0  4990.9     .07       0
  4996.9     .16       0  5263.9     .05       0
Bank Sta=4953.8,5084.1
XS Rating Curve= 0 ,0
Exp/Cntr=0.3,0.1

Type RM Length L Ch R = 1 ,35657   ,456,456,456
BEGIN DESCRIPTION:
SPRING CREEK 1 33.0
END DESCRIPTION:
XS GIS Cut Line= 3
      3805867.29     10502612.07      3805499.22     10502160.66
      3804583.61     10502202.28
#Sta/Elev= 30
  4103.1     355  4165.6  353.79  4422.7  345.44  4443.6  341.77  4457.9   341.4
  4465.8  344.47  4493.1   345.7  4643.2  348.36  4677.9  347.05  4705.2  343.98
  4755.2  329.62  4795.3  323.82  4845.3  320.73  4885.4  323.15  4935.4  322.87
  4945.4  319.88  4975.5  317.98  4985.5  312.63  4992.5  311.42  4995.2  310.92
  4998.5  311.42  5015.5  317.44  5095.6  319.01  5115.6  323.33  5135.6  337.42
  5155.6  345.12  5195.7  349.67  5365.9  359.59    5506  363.15  5602.1  363.16
#Mann= 6 ,-1 , 0
  4103.1     .05       0  4165.6     .16       0  4457.9     .05       0
  4677.9     .16       0  4992.5     .07       0  4998.5     .16       0
Bank Sta=4935.4,5115.6
XS Rating Curve= 0 ,0
Exp/Cntr=0.3,0.1

Type RM Length L Ch R = 1 ,35201   ,469,469,469
BEGIN DESCRIPTION:
SPRING CREEK 1 32.0
END DESCRIPTION:
XS GIS Cut Line= 4
      3805929.78     10502362.05      3805506.16     10501924.55
      3805020.05     10501889.83      3804478.42     10502084.26
#Sta/Elev= 30
  4025.1  352.52  4330.7  342.82  4549.9  349.21  4606.5  348.33  4655.9  343.92
  4690.8  338.36  4720.9  328.13    4771  320.16  4821.1  317.73  4861.2  318.19
  4891.3  315.61  4921.4  319.58  4941.4  316.73  4971.5  316.14  4991.5  313.47
  4998.6  310.03  5001.3  309.53  5004.6  310.03  5021.6  316.79  5101.8  314.83
  5111.8  317.43  5119.1  327.62  5124.3  327.62  5132.3  334.78  5137.6  331.24
  5143.2  337.17  5168.3  341.96  5249.4  350.69  5495.8  361.82  5696.9  363.53
#Mann= 4 ,-1 , 0
  4025.1     .05       0  4655.9     .16       0  4998.6     .07       0
  5004.6     .16       0
Bank Sta=4921.4,5021.6
XS Rating Curve= 0 ,0
Exp/Cntr=0.3,0.1

Type RM Length L Ch R = 1 ,34732   ,538,538,538
BEGIN DESCRIPTION:
SPRING CREEK 1 31.0
END DESCRIPTION:
XS GIS Cut Line= 2
      3805971.45     10501070.38       3804610.3     10501959.29
#Sta/Elev= 30
  3952.9  372.57  4048.9  368.11  4287.2  345.53  4546.6  324.73  4603.9  322.97
    4612  320.79    4619  322.56  4630.8  322.01  4676.3  319.52  4683.7  315.77
  4712.5  314.26  4727.6  308.78  4733.6  310.43  4742.8  321.21  4886.7  320.37
  4929.7  314.44    4987  314.05  5005.1  308.33  5007.9  307.83  5011.1  308.33
  5023.2  318.97    5030     323  5044.3  322.89  5116.7   330.2  5161.4  339.59
  5197.2  342.51  5204.3  344.94  5225.3  344.52  5291.8  351.23  5578.6  360.37
#Mann= 4 ,-1 , 0
  3952.9     .05       0  4630.8     .16       0  5005.1     .07       0
  5011.1     .16       0
Bank Sta=4886.7,5030
XS Rating Curve= 0 ,0
Exp/Cntr=0.3,0.1

Type RM Length L Ch R = 1 ,34194   ,503,503,503
BEGIN DESCRIPTION:
SPRING CREEK 1 30.0
END DESCRIPTION:
XS GIS Cut Line= 3
       3805349.6      10500810.2      3804949.61     10501210.19
      3804649.61     10501310.19
#Sta/Elev= 30
  4441.3  331.55  4526.1  324.94  4592.8  322.38  4653.4  320.03  4667.6  320.62
  4695.8  318.55  4766.6  316.51  4794.8  317.87    4809  316.14  4823.1   312.2
  4848.4  309.05  4851.2  308.55  4854.4  309.05  4865.6  317.53  4964.5  316.96
  5003.4  309.24  5009.6  309.24  5017.5  312.41  5028.1  313.53  5080.8  312.06
  5112.4  312.57  5122.9  318.43    5144  316.85  5154.5  319.51  5175.6  321.55
  5186.2  325.86  5196.7  327.05  5228.3  334.92  5302.1  343.87  5323.2  347.36
#Mann= 4 ,-1 , 0
  4441.3     .05       0  4592.8     .16       0  4848.4     .07       0
  4854.4     .16       0
Bank Sta=4794.8,4865.6
XS Rating Curve= 0 ,0
Exp/Cntr=0.3,0.1

Type RM Length L Ch R = 1 ,33691   ,583,583,583
BEGIN DESCRIPTION:
SPRING CREEK 1 29.0
END DESCRIPTION:
XS GIS Cut Line= 2
      3805881.18     10500445.38      3804020.04     10501000.94
#Sta/Elev= 30
  3922.2  368.46  4090.8  363.58  4310.7  346.99  4446.8  341.18  4542.9  337.09
  4551.1  336.89  4619.3  336.04  4706.5  326.12  4905.2  311.68  4933.2  310.96
  4966.3  315.01  4977.9  314.09  5001.7  305.77  5004.4  305.27  5007.7  305.77
  5030.1  311.64  5061.4  310.59  5082.2  314.81  5109.3  314.74  5270.1  340.39
  5311.8  341.77  5356.9     338  5384.8  339.57    5390  337.17  5423.1  342.54
  5428.4  339.72  5489.2  345.99  5566.1  343.87  5677.1  354.11  5864.5  361.61
#Mann= 6 ,-1 , 0
  3922.2     .05       0  4446.8     .16       0  4542.9     .05       0
  4551.1     .16       0  5001.7     .07       0  5007.7     .16       0
Bank Sta=4966.3,5082.2
XS Rating Curve= 0 ,0
Exp/Cntr=0.3,0.1

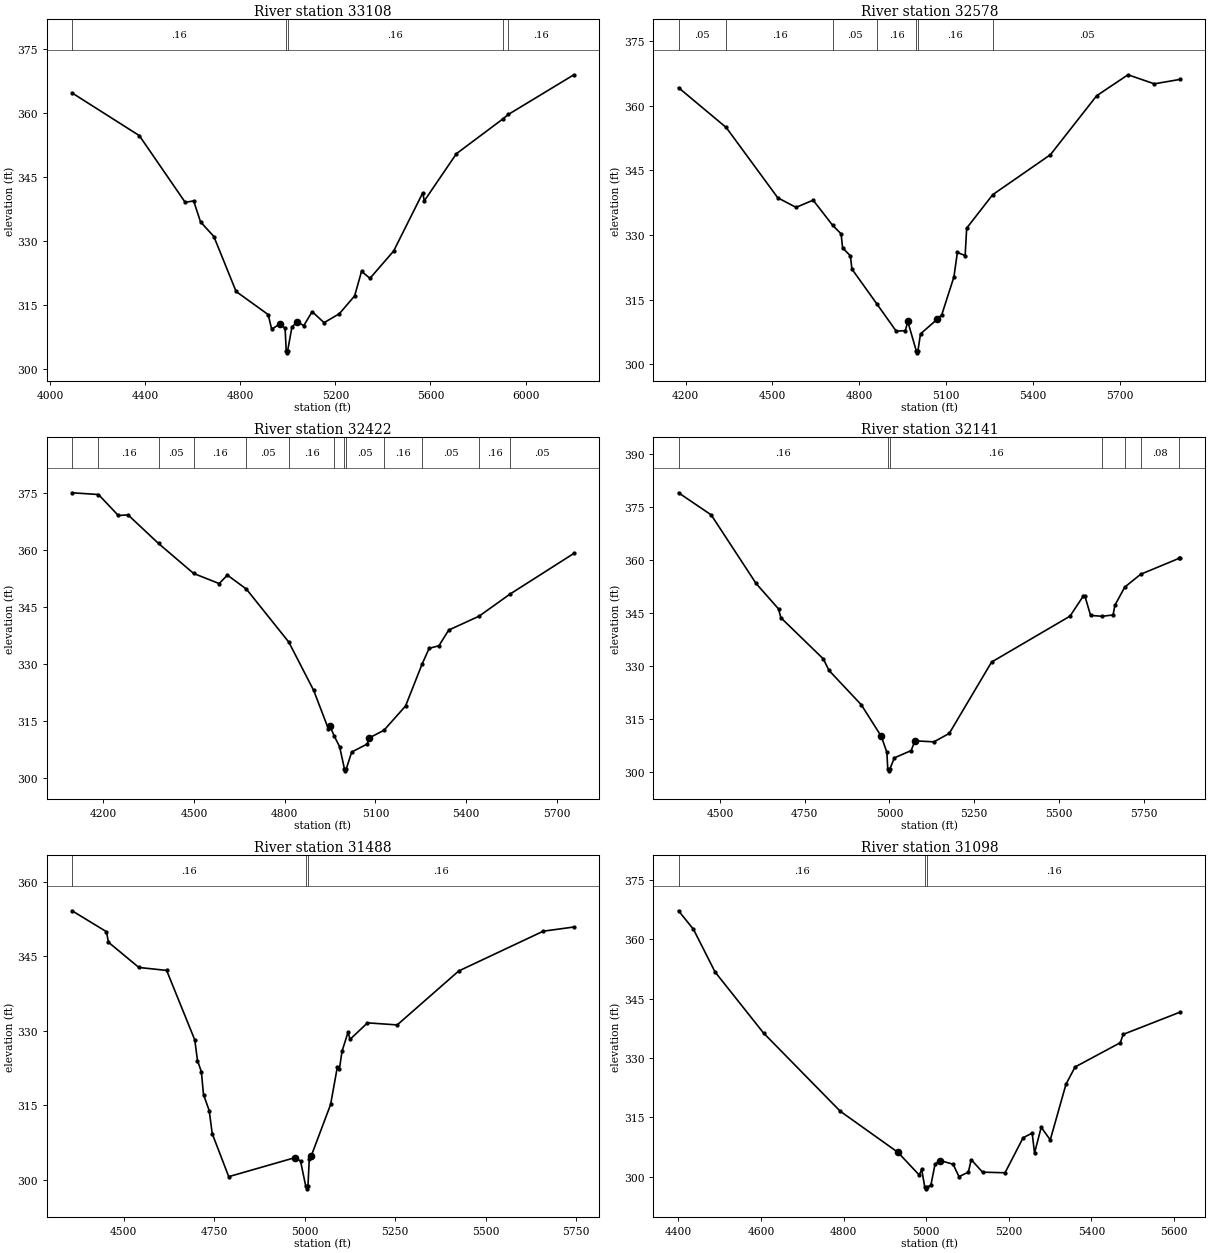
Type RM Length L Ch R = 1 ,33108   ,530,530,530
BEGIN DESCRIPTION:
SPRING CREEK 1 28.0
END DESCRIPTION:
XS GIS Cut Line= 2
      3805520.04     10499744.01      3803846.47      10501028.7
#Sta/Elev= 30
    4093  364.74  4375.7  354.72  4568.7  339.05  4604.1  339.39  4633.1  334.47
  4689.3  331.02  4782.6  318.13  4917.7  312.69  4932.2  309.26  4967.5  310.54
  4988.6   309.5  4993.5  304.22  4996.3  303.72  4999.5  304.22  5017.4  309.77
    5039  310.99  5067.2  310.11  5102.5  313.39  5152.5   310.8  5216.8   312.9
  5281.1  317.09  5310.1  322.85  5345.5  321.21  5445.2  327.63  5567.6  341.29
  5573.9  339.39  5708.9  350.47  5903.6   358.6  5927.8   359.7  6202.8     369
#Mann= 5 ,-1 , 0
    4093     .16       0  4993.5     .07       0  4999.5     .16       0
  5903.6     .05       0  5927.8     .16       0
Bank Sta=4967.5,5039
XS Rating Curve= 0 ,0
Exp/Cntr=0.3,0.1

Type RM Length L Ch R = 1 ,32578   ,156,156,156
BEGIN DESCRIPTION:
SPRING CREEK 1 27.0
END DESCRIPTION:
XS GIS Cut Line= 2
      3805346.41     10499723.17       3803694.1      10500250.8
#Sta/Elev= 30
  4175.4  364.14  4340.2  354.91  4518.5  338.61  4581.6  336.39  4640.7  338.06
  4708.4  332.21  4737.3  330.26  4742.5  327.01  4769.5  325.15  4774.7   322.1
  4861.1  313.99  4927.9  307.69  4959.3  307.81  4967.8  309.94    4997  303.17
  4999.7  302.67    5003  303.17  5011.8  307.06  5069.6  310.46  5085.3  311.49
  5127.3  320.27  5139.2  325.94  5166.1  325.22  5171.4  331.58  5261.5  339.34
    5461  348.61  5620.7  362.27    5729  367.13  5820.1  365.03  5909.9  366.07
#Mann= 7 ,-1 , 0
  4175.4     .05       0  4340.2     .16       0  4708.4     .05       0
  4861.1     .16       0    4997     .07       0    5003     .16       0
  5261.5     .05       0
Bank Sta=4967.8,5069.6
XS Rating Curve= 0 ,0
Exp/Cntr=0.3,0.1

Type RM Length L Ch R = 1 ,32422   ,281,281,281
BEGIN DESCRIPTION:
Mapping XS e4183463
END DESCRIPTION:
XS GIS Cut Line= 2
      3805401.95     10499549.56      3803818.62     10500049.56
#Sta/Elev= 30
  4096.3  375.01  4183.7  374.55  4249.3  369.04  4281.6  369.19  4382.3  361.68
  4498.5  353.79  4583.1  351.13  4610.2  353.35    4673  349.69  4813.3  335.75
  4895.8  323.02  4944.1  312.98  4949.3  313.75  4963.6  311.04  4981.6  308.22
  4997.6  302.37  5000.4  301.87  5003.6  302.37  5021.6  306.82  5073.4  308.94
  5078.6   310.5  5128.1  312.52  5199.9  318.94  5254.3  329.91  5277.9   334.1
  5310.2  334.77  5342.6   338.9  5442.9  342.54  5544.9  348.33  5756.7  359.06
#Mann= 13 ,-1 , 0
  4096.3     .05       0  4183.7     .16       0  4382.3     .05       0
  4498.5     .16       0    4673     .05       0  4813.3     .16       0
  4963.6     .05       0  4997.6     .04       0  5003.6     .05       0
  5128.1     .16       0  5254.3     .05       0  5442.9     .16       0
  5544.9     .05       0
Bank Sta=4949.3,5078.6
XS Rating Curve= 0 ,0
Exp/Cntr=0.3,0.1

Type RM Length L Ch R = 1 ,32141   ,653,653,653
BEGIN DESCRIPTION:
SPRING CREEK 1 26.0
END DESCRIPTION:
XS GIS Cut Line= 2
      3805027.04     10499368.97      3803715.83     10500055.79
#Sta/Elev= 30
  4377.8  379.09  4474.1  372.84  4606.5  353.44  4672.7  346.25  4679.7  343.75
  4805.1  332.08  4821.5  328.85  4916.8  319.14    4976  310.18  4992.4  305.64
    4995  300.94  4997.8  300.44    5001  300.94  5014.5  304.11  5064.2  306.18
  5074.8  308.93  5131.2  308.64  5176.4  311.03  5301.3  331.21  5532.7   344.2
  5571.2   349.8  5576.8  349.77  5593.3   344.4  5627.1  344.16  5659.5  344.52
  5665.1  347.29    5694   352.4    5741  356.04  5854.9  360.57    5858  360.75
#Mann= 7 ,-1 , 0
  4377.8     .16       0    4995     .07       0    5001     .16       0
  5627.1     .08       0    5694     .05       0    5741     .08       0
  5854.9     .05       0
Bank Sta=4976,5074.8
XS Rating Curve= 0 ,0
Exp/Cntr=0.3,0.1

Type RM Length L Ch R = 1 ,31488   ,390,390,390
BEGIN DESCRIPTION:
SPRING CREEK 1 25.0
END DESCRIPTION:
XS GIS Cut Line= 3
      3804700.61     10499028.71      3803895.05      10499355.1
      3803554.79     10499743.98
#Sta/Elev= 30
  4357.8  354.18  4452.8  349.97  4458.2  347.85  4542.3  342.77    4619  342.17
  4696.7  328.18  4704.2  324.02  4714.9  321.79  4720.8  317.18  4736.5  313.97
  4744.9  309.31  4790.5  300.65  4973.9  304.49  4988.8  303.78  5003.3   298.7
    5006   298.2  5009.3   298.7  5012.9  304.19  5018.3  304.81  5071.9  315.19
  5090.6  322.79    5096  322.26  5103.4  325.89  5120.1  329.76  5125.5  328.28
  5173.7  331.62  5255.8   331.2  5425.7  342.06  5659.2  350.07  5743.7  350.91
#Mann= 3 ,-1 , 0
  4357.8     .16       0  5003.3     .07       0  5009.3     .16       0
Bank Sta=4973.9,5018.3
XS Rating Curve= 0 ,0
Exp/Cntr=0.3,0.1

Type RM Length L Ch R = 1 ,31098   ,397,397,397
BEGIN DESCRIPTION:
SPRING CREEK 1 24.0
END DESCRIPTION:
XS GIS Cut Line= 2
       3804617.3     10498688.42      3803547.84     10499264.82
#Sta/Elev= 30
  4400.2  367.18  4436.4  362.49  4488.5  351.75    4606  336.31  4791.7  316.56
  4931.5  306.17  4983.1  300.43  4988.8   301.9  4996.3  297.46  4999.1  296.96
  5002.3  297.46    5011  297.81  5021.2  303.15  5033.7   304.1    5065  303.18
  5079.2  300.04  5101.9  301.17  5108.8  304.32  5136.4  301.17  5190.7  301.02
  5234.5  309.87  5256.4  311.03  5262.1     306  5278.3  312.51  5300.2  309.32
  5338.3  323.39  5360.2  327.73  5469.7  333.86  5476.8  335.97  5615.1  341.61
#Mann= 3 ,-1 , 0
  4400.2     .16       0  4996.3     .07       0  5002.3     .16       0
Bank Sta=4931.5,5033.7
XS Rating Curve= 0 ,0
Exp/Cntr=0.3,0.1

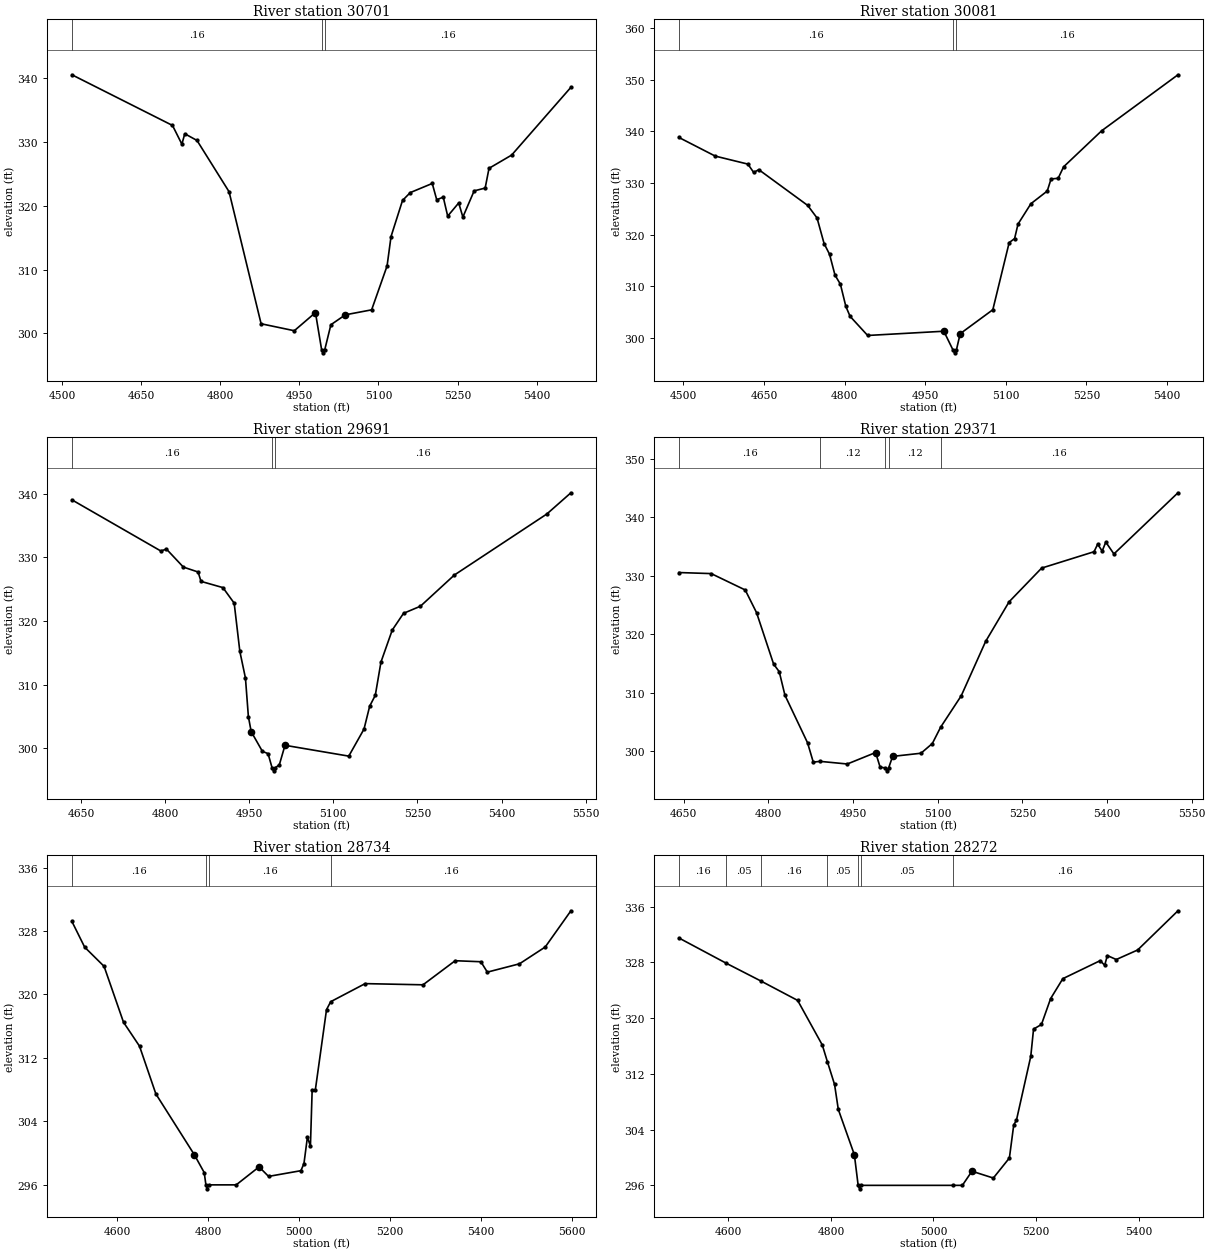
Type RM Length L Ch R = 1 ,30701   ,620,620,620
BEGIN DESCRIPTION:
SPRING CREEK 1 23.0
END DESCRIPTION:
XS GIS Cut Line= 3
      3804130.91     10498347.86      3803960.78     10498729.78
      3803534.18     10499041.93
#Sta/Elev= 30
  4518.4  340.48  4709.2  332.55    4727  329.62  4732.5  331.25  4755.7   330.2
  4816.5  322.18  4877.3  301.51  4940.3  300.42  4980.4  303.26  4992.1  297.46
  4994.8  296.96  4998.1  297.46  5009.7  301.36  5037.1  302.91    5087  303.69
  5116.3  310.56  5123.8  315.16  5145.6  320.81  5160.3  322.04    5202  323.47
  5210.5  320.92  5222.9  321.33  5231.3  318.36  5252.2  320.42  5260.1  318.21
  5281.5  322.31  5302.4  322.75  5309.7  325.84  5352.6  327.91  5465.1  338.52
#Mann= 3 ,-1 , 0
  4518.4     .16       0  4992.1     .07       0  4998.1     .16       0
Bank Sta=4980.4,5037.1
XS Rating Curve= 0 ,0
Exp/Cntr=0.3,0.1

Type RM Length L Ch R = 1 ,30081   ,390,390,390
BEGIN DESCRIPTION:
SPRING CREEK 1 22.0
END DESCRIPTION:
XS GIS Cut Line= 2
      3804096.21     10498323.52       3803179.5     10498472.84
#Sta/Elev= 30
  4491.7  338.79  4559.2  335.19    4620  333.64  4630.8  332.02  4640.2  332.57
  4731.4  325.64  4748.7  323.22  4761.8  318.28    4772  316.19  4782.1  312.17
  4792.2   310.4  4802.3  306.12  4810.2  304.19  4842.9  300.49  4984.7  301.31
    5002  297.63  5004.7  297.13    5008  297.63  5015.1  300.83  5075.9  305.47
  5106.3  318.45  5116.4  319.23  5122.8  322.04  5146.8  325.98  5177.2  328.43
  5184.3  330.77  5197.5  330.89  5207.6  333.11  5278.5  340.09  5420.5  350.92
#Mann= 3 ,-1 , 0
  4491.7     .16       0    5002     .07       0    5008     .16       0
Bank Sta=4984.7,5015.1
XS Rating Curve= 0 ,0
Exp/Cntr=0.3,0.1

Type RM Length L Ch R = 1 ,29691   ,320,320,320
BEGIN DESCRIPTION:
SPRING CREEK 1 21.0
END DESCRIPTION:
XS GIS Cut Line= 2
      3804117.07     10498059.63      3803233.07     10498160.17
#Sta/Elev= 30
  4633.9  339.02  4792.4  330.99  4802.4  331.29  4832.6  328.46  4858.9  327.69
    4864  326.22  4903.1  325.24  4923.2   322.8  4933.3  315.22  4943.3  311.03
  4948.5     305  4953.5  302.63  4973.5  299.53  4983.6  299.17  4990.7  296.97
  4993.4  296.47  4996.7  296.97  5003.7  297.42  5013.8  300.48  5127.5  298.78
  5154.7  303.03  5164.8  306.63  5174.8  308.33  5184.9  313.55    5205  318.57
  5225.1   321.2  5255.3  322.32  5315.7  327.21  5480.7   336.8  5523.6  340.13
#Mann= 3 ,-1 , 0
  4633.9     .16       0  4990.7     .07       0  4996.7     .16       0
Bank Sta=4953.5,5013.8
XS Rating Curve= 0 ,0
Exp/Cntr=0.3,0.1

Type RM Length L Ch R = 1 ,29371   ,637,637,637
BEGIN DESCRIPTION:
SPRING CREEK 1 20.0
END DESCRIPTION:
XS GIS Cut Line= 3
      3803936.48     10497830.47       3803471.2     10497875.61
      3803145.37     10498135.58
#Sta/Elev= 30
  4641.5  330.53  4698.6  330.35  4758.9  327.55    4779  323.67  4809.2  314.88
  4819.2  313.57  4829.3  309.55  4869.4  301.41  4879.5  298.11  4891.5  298.24
  4939.8  297.79    4990  299.75    4998  297.24  5007.1  297.12  5009.8  296.62
  5013.1  297.12  5020.1  299.09  5070.4  299.63  5090.5  301.29  5105.2  304.08
  5141.7  309.45  5184.9  318.74  5226.5  325.52  5284.2  331.29  5377.1  334.09
  5383.5  335.38  5391.5   334.2  5397.9  335.74  5412.3  333.71  5525.8  344.17
#Mann= 5 ,-1 , 0
  4641.5     .16       0  4891.5     .12       0  5007.1     .07       0
  5013.1     .12       0  5105.2     .16       0
Bank Sta=4990,5020.1
XS Rating Curve= 0 ,0
Exp/Cntr=0.3,0.1

Type RM Length L Ch R = 1 ,28734   ,462,462,462
BEGIN DESCRIPTION:
SPRING CREEK 1 19.0
END DESCRIPTION:
XS GIS Cut Line= 3
      3803849.63     10497060.17      3803449.61     10497410.19
      3803049.63     10497810.17
#Sta/Elev= 30
  4500.6  329.21  4528.6  325.97  4571.3  323.55    4614   316.5  4649.2  313.48
  4685.2  307.45  4769.7  299.79  4791.5  297.53  4795.2  295.98  4797.9  295.48
  4801.2  295.98  4861.8  295.98  4912.1  298.25    4933  297.05  5004.1  297.77
  5010.8  298.67  5018.4  302.01    5025  300.86  5028.8  307.91  5035.7  307.91
  5060.4  318.09  5069.6  319.09  5145.3  321.37  5272.6  321.22  5343.3  324.26
  5399.8  324.13    5414  322.82  5484.7  323.87  5541.3  325.99  5597.8  330.56
#Mann= 4 ,-1 , 0
  4500.6     .16       0  4795.2     .07       0  4801.2     .16       0
  5069.6     .16       0
Bank Sta=4769.7,4912.1
XS Rating Curve= 0 ,0
Exp/Cntr=0.3,0.1

Type RM Length L Ch R = 1 ,28272   ,438,438,438
BEGIN DESCRIPTION:
SPRING CREEK 1 18.0
END DESCRIPTION:
XS GIS Cut Line= 2
      3803717.77     10496910.32      3802784.19     10497184.49
#Sta/Elev= 30
  4503.7   331.5  4596.3  327.86  4662.8  325.35  4735.1  322.54  4783.2  316.13
  4793.1  313.74  4807.1  310.47  4814.4  306.88  4845.7  300.38  4853.1  295.98
  4855.9  295.48  4859.1  295.98  5037.1  295.98  5056.3  295.98    5075  298.01
  5116.7  297.03    5148  299.91  5156.5  304.67  5161.7  305.32  5189.7  314.51
  5195.1  318.42  5210.5  319.08  5228.4   322.8  5252.2  325.66  5325.1  328.25
  5333.8  327.58    5339  328.98  5356.4  328.41  5398.1  329.78  5476.7  335.41
#Mann= 7 ,-1 , 0
  4503.7     .16       0  4596.3     .05       0  4662.8     .16       0
  4793.1     .05       0  4853.1    .033       0  4859.1     .05       0
  5037.1     .16       0
Bank Sta=4845.7,5075
XS Rating Curve= 0 ,0
Exp/Cntr=0.3,0.1

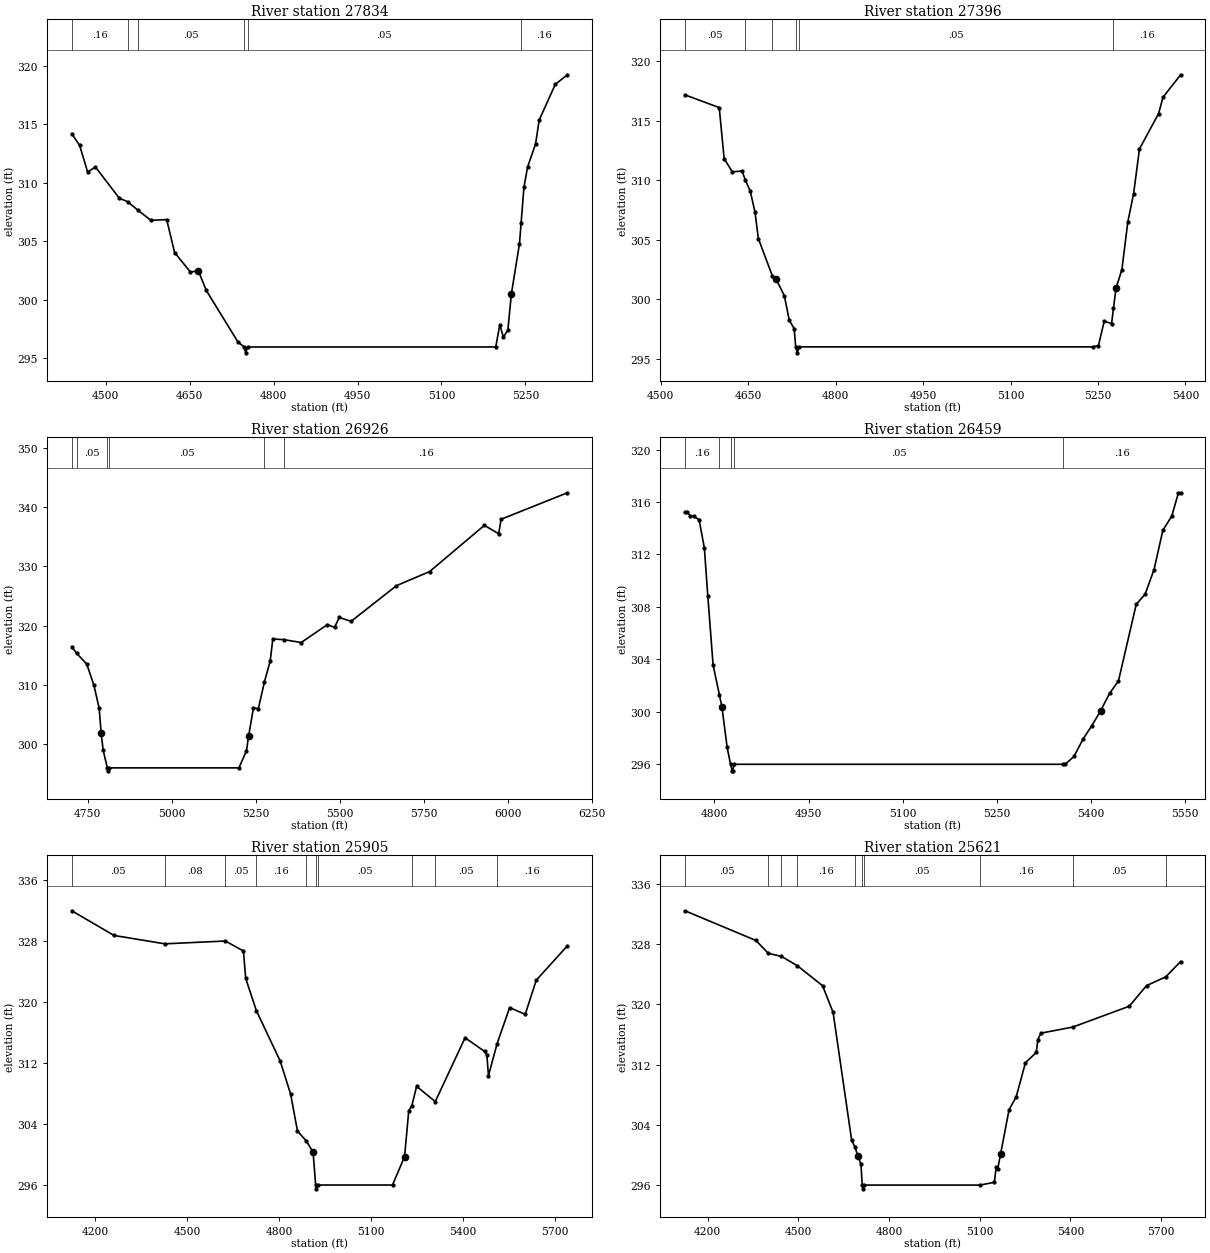
Type RM Length L Ch R = 1 ,27834   ,438,438,438
BEGIN DESCRIPTION:
SPRING CREEK 1 17.0
END DESCRIPTION:
XS GIS Cut Line= 3
      3803449.61     10496260.19      3803049.61     10496660.19
      3802799.64     10496860.16
#Sta/Elev= 30
  4439.2  314.19  4453.3   313.2  4467.5  310.93  4481.6  311.35  4524.1  308.69
    4539  308.39  4557.5  307.66  4580.6   306.8  4608.9  306.86    4623  304.05
  4651.3  302.38  4665.5  302.49  4679.6  300.81  4736.2  296.41  4747.3  295.98
  4750.1  295.48  4753.3  295.98    5197  295.98  5204.2  297.89  5210.6  296.82
  5218.6  297.42    5225  300.54  5239.4  304.81  5242.3  306.56  5247.4  309.63
  5253.8  311.34  5268.2  313.33  5274.6  315.36  5303.4  318.41    5325  319.23
#Mann= 6 ,-1 , 0
  4439.2     .16       0    4539      .1       0  4557.5     .05       0
  4747.3    .033       0  4753.3     .05       0  5242.3     .16       0
Bank Sta=4665.5,5225
XS Rating Curve= 0 ,0
Exp/Cntr=0.3,0.1

Type RM Length L Ch R = 1 ,27396   ,470,470,470
BEGIN DESCRIPTION:
SPRING CREEK 1 16.0
END DESCRIPTION:
XS GIS Cut Line= 3
      3802499.59     10496010.16      3802699.61     10496410.19
       3802649.6     10496810.23
#Sta/Elev= 30
  4541.5  317.17  4600.2   316.1  4608.6  311.82  4622.6   310.7  4639.4  310.77
  4644.9  310.02  4653.3   309.1  4661.7  307.29  4667.3  305.09  4691.5  301.93
  4698.1  301.65    4712  300.27  4720.4  298.21  4728.8  297.52  4731.4  295.98
  4734.1  295.48  4737.4  295.98  5240.7  295.98  5250.8  296.08  5260.8  298.14
  5273.4  297.94  5276.7  299.23    5281  300.92  5291.1  302.48  5301.2  306.46
  5311.2  308.87  5321.3  312.63  5354.1   315.6  5361.6  316.97  5391.9  318.86
#Mann= 6 ,-1 , 0
  4541.5     .05       0  4644.9     .16       0  4691.5     .05       0
  4731.4    .033       0  4737.4     .05       0  5276.7     .16       0
Bank Sta=4698.1,5281
XS Rating Curve= 0 ,0
Exp/Cntr=0.3,0.1

Type RM Length L Ch R = 1 ,26926   ,467,467,467
BEGIN DESCRIPTION:
SPRING CREEK 1 15.0
END DESCRIPTION:
XS GIS Cut Line= 4
      3802399.61     10496060.19      3802249.61     10496310.19
      3802049.61     10496560.19      3801416.72       10497146.
#Sta/Elev= 30
  4702.5  316.44  4717.1  315.32  4747.2  313.49  4768.6  309.89  4784.1  306.02
    4790  301.81  4795.8  298.99  4808.3  295.98  4811.1  295.48  4814.3  295.98
  5199.7  295.98  5222.2  298.86  5228.6   301.4    5243  306.12  5257.4  305.97
  5275.6  310.51  5292.6  313.98  5300.6  317.74  5334.1  317.62  5384.8  317.14
    5463  320.17    5484   319.7  5498.2  321.37  5533.3  320.72  5668.3  326.74
  5766.9  329.12  5929.7  336.92  5972.2  335.51  5979.5  337.95  6176.6  342.42
#Mann= 6 ,-1 , 0
  4702.5     .16       0  4717.1     .05       0  4808.3    .033       0
  4814.3     .05       0  5275.6     .08       0  5334.1     .16       0
Bank Sta=4790,5228.6
XS Rating Curve= 0 ,0
Exp/Cntr=0.3,0.1

Type RM Length L Ch R = 1 ,26459   ,554,554,554
BEGIN DESCRIPTION:
SPRING CREEK 1 14.0
END DESCRIPTION:
XS GIS Cut Line= 3
      3802349.62     10496010.19      3802149.61     10495910.19
      3801749.61     10495510.19
#Sta/Elev= 30
  4753.3  315.23  4756.1  315.23  4761.7  314.95  4767.3  314.89  4775.7  314.65
  4784.1  312.49  4789.6  308.81    4798  303.56    4808  301.29    4812  300.38
  4820.4  297.27  4825.8  295.98  4828.5  295.48    4829  295.48  4831.8  295.98
  5355.4  295.98  5358.8  295.98  5372.9  296.59    5387  297.89  5401.2  298.93
  5415.3  300.07  5429.5   301.4  5443.6  302.34  5471.9  308.19    5486  308.95
  5500.2  310.83  5514.3  313.84  5528.5  314.92  5539.1   316.7  5542.6   316.7
#Mann= 5 ,-1 , 0
  4753.3     .16       0    4808     .05       0  4825.8    .033       0
  4831.8     .05       0  5355.4     .16       0
Bank Sta=4812,5415.3
XS Rating Curve= 0 ,0
Exp/Cntr=0.3,0.1

Type RM Length L Ch R = 1 ,25905   ,284,284,284
BEGIN DESCRIPTION:
SPRING CREEK 1 13.0
END DESCRIPTION:
XS GIS Cut Line= 4
      3803207.52     10495514.82      3802693.66      10495480.1
      3801950.61     10495271.77      3801624.38     10495334.24
#Sta/Elev= 30
  4122.9  331.91    4261  328.68    4427  327.58  4624.6  327.95  4683.7  326.64
    4691  323.06  4725.8  318.84  4803.7  312.22  4837.8   307.9  4860.2  303.05
  4889.4  301.74  4911.2  300.28  4919.6  295.98  4922.3  295.48  4925.6  295.98
  5170.7  295.98    5210   299.7  5223.7  305.73  5233.7  306.36  5249.3  308.91
  5310.3  306.91  5407.6  315.27  5471.7  313.48  5478.9     313    5484   310.3
  5512.2  314.49  5553.2  319.23  5604.1  318.34  5640.1  322.81  5741.8  327.32
#Mann= 10 ,-1 , 0
  4122.9     .05       0    4427     .08       0  4624.6     .05       0
  4725.8     .16       0  4889.4     .05       0  4919.6    .033       0
  4925.6     .05       0  5233.7     .16       0  5310.3     .05       0
  5512.2     .16       0
Bank Sta=4911.2,5210
XS Rating Curve= 0 ,0
Exp/Cntr=0.3,0.1

Type RM Length L Ch R = 1 ,25621   ,417,417,417
BEGIN DESCRIPTION:
SPRING CREEK 1 12.0
END DESCRIPTION:
XS GIS Cut Line= 3
      3803277.03      10495306.5      3802332.55     10495091.22
      3801679.79     10495243.99
#Sta/Elev= 30
  4125.5  332.45  4360.1   328.5    4401  326.79  4444.3  326.39  4497.4  325.13
  4580.3  322.49  4615.2  318.94  4676.7  301.91  4687.2  301.07  4697.2  299.86
  4707.5  298.74  4711.5  295.98  4714.2  295.48  4717.5  295.98  5100.6  295.98
  5148.6  296.35  5154.6  298.36  5159.7  298.14  5169.1   300.1  5197.1     306
  5220.5  307.68  5251.3  312.24  5287.2  313.62  5292.4  315.33  5302.6  316.18
  5407.9  316.99  5594.8  319.76  5651.8   322.5  5715.2  323.66  5764.6   325.7
#Mann= 10 ,-1 , 0
  4125.5     .05       0    4401      .1       0  4444.3     .08       0
  4497.4     .16       0  4687.2     .05       0  4711.5    .033       0
  4717.5     .05       0  5100.6     .16       0  5407.9     .05       0
  5715.2     .16       0
Bank Sta=4697.2,5169.1
XS Rating Curve= 0 ,0
Exp/Cntr=0.3,0.1

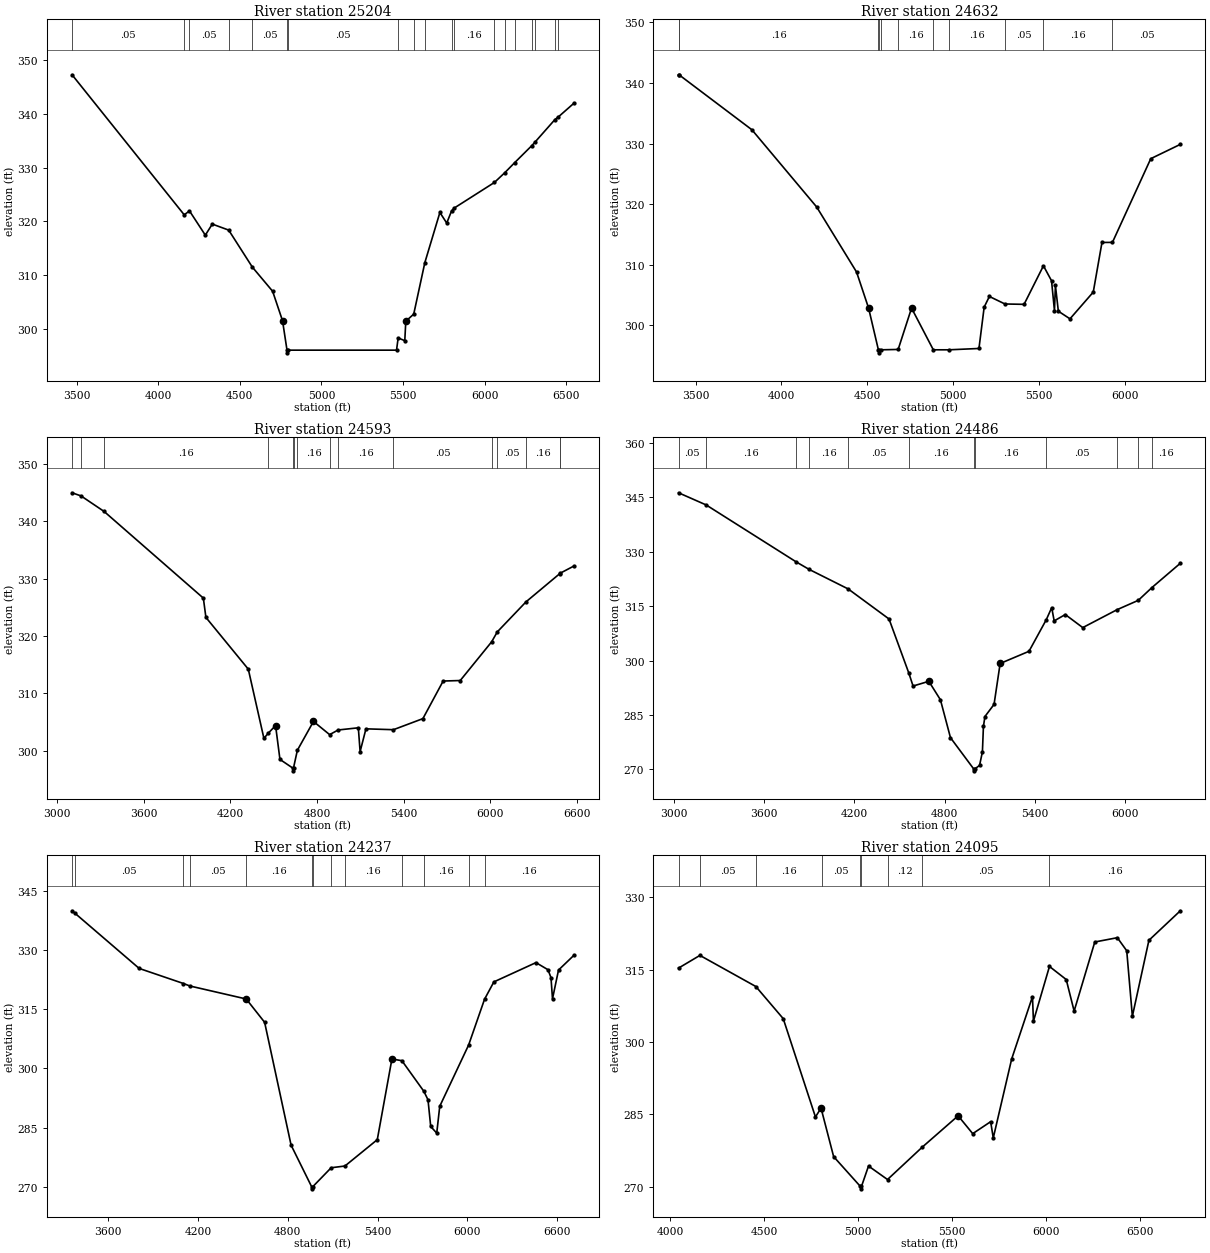
Type RM Length L Ch R = 1 ,25204   ,572,572,572
BEGIN DESCRIPTION:
SPRING CREEK 1 11.0
END DESCRIPTION:
XS GIS Cut Line= 4
      3803754.39     10495507.85      3802929.77     10494770.03
       3802426.3     10494691.91      3801228.38      10495520.9
#Sta/Elev= 30
  3472.7  347.27  4159.4  321.19  4191.8  321.91  4288.7   317.4  4331.4  319.46
  4431.8  318.34  4576.6  311.45  4700.8  306.95  4761.5  301.46  4788.9  295.98
  4791.6  295.48  4794.9  295.98  5459.6  295.98  5469.6  298.26  5510.2  297.74
  5516.3  301.37  5564.9  302.69    5633  312.29  5725.1  321.62    5767  319.65
  5796.4  321.89  5811.9  322.43  6058.8  327.21  6123.2  329.05  6182.3  330.88
  6286.6  334.03  6305.8  334.67  6429.3  338.92    6450  339.41  6545.5  341.96
#Mann= 19 ,-1 , 0
  3472.7     .05       0  4159.4      .1       0  4191.8     .05       0
  4431.8     .16       0  4576.6     .05       0  4788.9    .033       0
  4794.9     .05       0  5469.6     .08       0  5564.9     .05       0
    5633     .16       0  5796.4     .05       0  5811.9     .16       0
  6058.8     .05       0  6123.2     .16       0  6182.3     .08       0
  6286.6     .05       0  6305.8     .16       0  6429.3     .08       0
    6450     .16       0
Bank Sta=4761.5,5516.3
XS Rating Curve= 0 ,0
Exp/Cntr=0.3,0.1

Type RM Length L Ch R = 1 ,24632   ,39,39,39
BEGIN DESCRIPTION:
Mapping XS 043236bf
END DESCRIPTION:
XS GIS Cut Line= 6
       3804097.3     10494366.39      3803285.68     10494114.65
       3802630.3     10494127.67       3802404.6     10494158.06
        3802027.     10494210.14      3801675.42     10494934.99
#Sta/Elev= 30
  3401.2  341.35    3404  341.35  3828.1  332.28    4205  319.54  4437.1  308.81
  4507.1  302.86  4564.1  295.98  4566.8  295.48  4570.1  295.98  4580.2  295.98
  4679.1  296.04  4757.1  302.86  4883.7  295.98  4975.3  295.98  5149.3   296.2
  5179.6  303.02  5209.9  304.78  5300.5  303.54  5411.8  303.48  5524.5  309.84
  5571.6  307.37  5588.6  302.46  5594.2  306.59  5611.2  302.35  5678.9  301.09
  5814.4   305.5  5865.1  313.69  5925.9   313.7    6149  327.51    6321  329.87
#Mann= 11 ,-1 , 0
  3401.2     .05       0    3404     .16       0  4564.1     .07       0
  4570.1     .16       0  4580.2     .05       0  4679.1     .16       0
  4883.7     .05       0  4975.3     .16       0  5300.5     .05       0
  5524.5     .16       0  5925.9     .05       0
Bank Sta=4507.1,4757.1
XS Rating Curve= 0 ,0
Exp/Cntr=0.3,0.1

Type RM Length L Ch R = 1 ,24593   ,107,107,107
BEGIN DESCRIPTION:
SPRING CREEK 1 10.0
END DESCRIPTION:
XS GIS Cut Line= 5
      3804344.71     10494422.81      3803198.87     10494006.15
      3802291.75     10494136.35      3801940.19     10494192.78
      3801497.47     10495073.88
#Sta/Elev= 30
    3102  344.98  3164.3  344.43  3324.3  341.72  4011.9  326.62  4029.6  323.26
  4323.4  314.24  4431.6  302.18  4462.5   303.1  4512.4  304.41  4542.8  298.51
  4630.7  297.02  4633.4  296.52  4636.7  297.02  4663.4   300.1  4775.1  305.13
  4887.1  302.83    4946  303.64    5086  304.02  5098.4  299.87  5138.8  303.84
  5329.3  303.69  5533.5  305.62  5673.9  312.17  5792.3  312.26  6009.8     319
  6049.3  320.74  6248.1  325.97  6480.3  330.85  6486.4  330.98  6579.8  332.21
#Mann= 15 ,-1 , 0
    3102     .16       0  3164.3     .05       0  3324.3     .16       0
  4462.5     .05       0  4630.7     .07       0  4636.7     .05       0
  4663.4     .16       0  4887.1     .05       0    4946     .16       0
  5329.3     .05       0  6009.8     .16       0  6049.3     .05       0
  6248.1     .16       0  6480.3     .05       0  6486.4     .16       0
Bank Sta=4512.4,4775.1
XS Rating Curve= 0 ,0
Exp/Cntr=0.3,0.1

Type RM Length L Ch R = 1 ,24486   ,249,249,249
BEGIN DESCRIPTION:
Mapping XS 0f980528
END DESCRIPTION:
XS GIS Cut Line= 6
      3804375.08       10494336.      3803211.89     10493941.04
      3802795.23     10493941.04      3802035.68     10494075.59
      3801935.85     10494127.67      3801563.37     10494846.66
#Sta/Elev= 30
    3030   346.3    3214  342.94  3814.9  327.18  3899.1  325.16  4158.8  319.77
  4430.7  311.48  4562.6  296.54  4590.7  292.98  4695.6  294.28  4772.8  289.18
  4839.6  278.73  4994.7  270.08  4997.4  269.58  5000.7  270.08  5033.2  271.08
  5052.2  274.83  5058.9  281.82    5069  284.57  5129.7  287.92  5170.1   299.2
  5362.1  302.56  5477.2  311.28  5513.3  314.61  5529.7  310.95  5603.7   312.7
    5720   309.1  5948.6  314.05  6089.4  316.62  6180.5  320.16  6369.2  326.85
#Mann= 12 ,-1 , 0
    3030     .05       0    3214     .16       0  3814.9     .05       0
  3899.1     .16       0  4158.8     .05       0  4562.6     .16       0
  4994.7     .07       0  5000.7     .16       0  5477.2     .05       0
  5948.6     .16       0  6089.4     .05       0  6180.5     .16       0
Bank Sta=4695.6,5170.1
XS Rating Curve= 0 ,0
Exp/Cntr=0.3,0.1

Type RM Length L Ch R = 1 ,24237   ,142,142,142
BEGIN DESCRIPTION:
SPRING CREEK 1 9.0
END DESCRIPTION:
XS GIS Cut Line= 5
      3804132.75     10494109.23      3803229.98     10493753.32
      3802205.67     10493857.49      3801979.98     10493952.98
      3800877.54     10494057.15
#Sta/Elev= 30
  3358.4  339.89  3377.8  339.26  3806.8  325.29  4102.6  321.47  4145.8  320.84
  4521.9  317.55  4644.8  311.65  4821.7  280.53  4959.4  269.97  4962.2  269.47
  4965.4  269.97  5089.3  274.81  5181.4  275.25  5397.5  281.92  5495.3  302.36
    5562  301.92  5708.7  294.17  5736.3  292.02  5754.5  285.26  5794.7  283.58
  5814.8  290.38  6007.6  305.88  6114.1  317.49  6176.4  321.88  6457.6  326.76
    6538  324.96    6558  322.96  6568.1   317.6  6608.3  324.88  6710.8   328.6
#Mann= 13 ,-1 , 0
  3358.4     .16       0  3377.8     .05       0  4102.6     .16       0
  4145.8     .05       0  4521.9     .16       0  4959.4     .07       0
  4965.4     .16       0  5089.3     .08       0  5181.4     .16       0
    5562     .05       0  5708.7     .16       0  6007.6     .05       0
  6114.1     .16       0
Bank Sta=4521.9,5495.3
XS Rating Curve= 0 ,0
Exp/Cntr=0.3,0.1

Type RM Length L Ch R = 1 ,24095   ,214,214,214
BEGIN DESCRIPTION:
SPRING CREEK 1 8.0
END DESCRIPTION:
XS GIS Cut Line= 5
      3803481.69     10493692.56      3802978.24     10493623.12
       3802327.2     10493709.92      3801598.03     10493848.81
      3800834.42     10493831.46
#Sta/Elev= 30
  4043.9  315.32  4157.7  317.95  4455.5   311.5  4601.2  304.84  4772.7  284.46
  4802.9  286.32  4805.2  285.88  4869.5  276.24  5011.8  270.06  5014.6  269.56
  5017.8  270.06  5055.2  274.29  5156.3  271.49    5340  278.16  5532.2   284.7
  5609.9     281  5705.3  283.48  5719.3  280.12  5817.3  296.49    5928   309.4
  5933.1  304.32  6018.4  315.66  6107.6  312.95  6149.7  306.41  6259.7  320.73
  6379.7  321.62  6429.7  318.91  6459.7  305.33  6547.8  321.08    6715   327.2
#Mann= 9 ,-1 , 0
  4043.9     .16       0  4157.7     .05       0  4455.5     .16       0
  4805.2     .05       0  5011.8     .04       0  5017.8     .05       0
  5156.3     .12       0    5340     .05       0  6018.4     .16       0
Bank Sta=4802.9,5532.2
XS Rating Curve= 0 ,0
Exp/Cntr=0.3,0.1