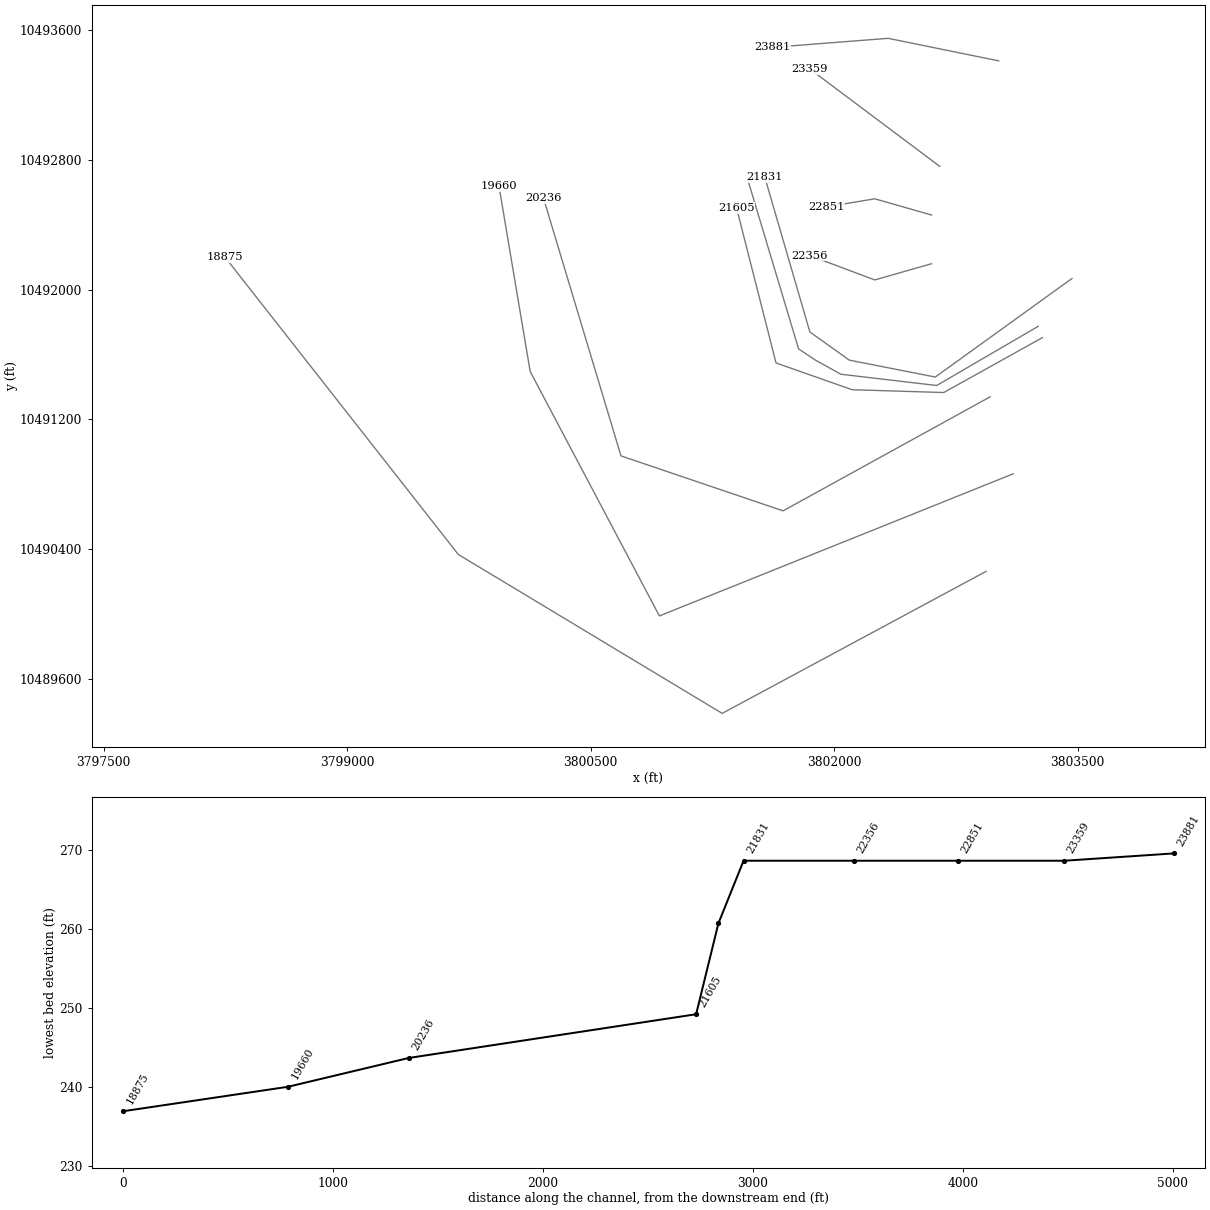
HEC-RAS study SPRING CREEK 1.prj: SPRING CREEK 1 Base Level Engineering

--- SPRING CREEK 1.g01 (geometry) --- (continued)

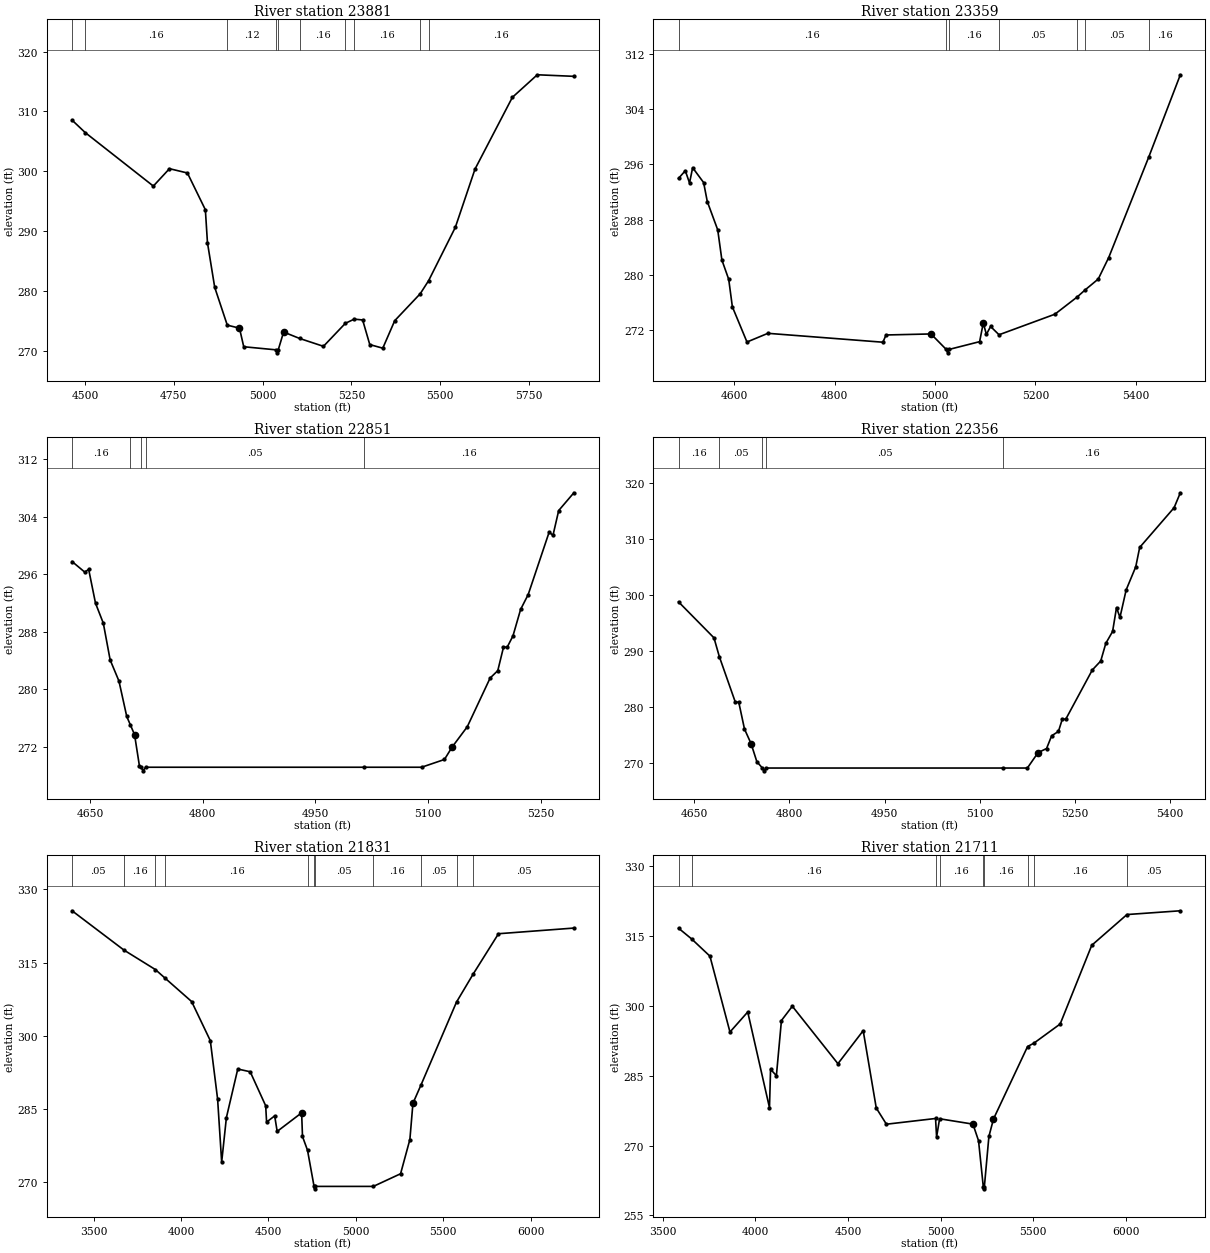
Type RM Length L Ch R = 1 ,23881   ,522,522,522
BEGIN DESCRIPTION:
Mapping XS 10360635
END DESCRIPTION:
XS GIS Cut Line= 3
      3803012.91     10493410.32      3802332.31     10493549.22
        3801617.     10493493.66
#Sta/Elev= 30
  4463.7  308.54  4500.7  306.46  4692.4  297.51  4737.8  300.42  4788.3   299.7
  4838.8  293.55  4844.7  288.04  4865.1  280.57  4900.5  274.24  4934.8  273.74
  4946.8  270.63  5037.9  270.11  5040.7  269.61  5043.9  270.11    5059  273.09
  5103.9  272.02  5171.1   270.7  5232.8  274.55  5257.7  275.25  5281.4  275.11
  5301.5  270.99  5338.1  270.39  5371.7  274.99  5443.5   279.5  5467.1  281.69
  5542.2   290.6  5597.6  300.35  5702.7  312.35  5772.9  316.13  5875.8  315.87
#Mann= 10 ,-1 , 0
  4463.7     .05       0  4500.7     .16       0  4900.5     .12       0
  5037.9     .07       0  5043.9     .12       0  5103.9     .16       0
  5232.8     .12       0  5257.7     .16       0  5443.5     .05       0
  5467.1     .16       0
Bank Sta=4934.8,5059
XS Rating Curve= 0 ,0
Exp/Cntr=0.3,0.1

Type RM Length L Ch R = 1 ,23359   ,508,508,508
BEGIN DESCRIPTION:
SPRING CREEK 1 7.0
END DESCRIPTION:
XS GIS Cut Line= 3
      3802649.59      10492760.2      3802249.61     10493060.19
      3801849.59      10493360.2
#Sta/Elev= 30
  4488.7  293.98  4502.2  295.09  4510.6  293.31  4516.8  295.53  4538.7  293.37
    4546  290.62  4566.8  286.51  4575.1  282.14  4588.7  279.34    4596  275.35
  4625.1  270.25  4666.8  271.51    4896  270.22  4902.2  271.27  4991.8  271.42
  5022.1  269.18  5024.9  268.68  5028.1  269.18  5088.7   270.3    5096     273
  5102.2  271.36  5110.6   272.5  5127.4   271.3  5238.7  274.28    5283  276.77
  5298.9   277.8  5325.1  279.38    5346   282.5  5426.1  297.13  5488.7     309
#Mann= 7 ,-1 , 0
  4488.7     .16       0  5022.1     .07       0  5028.1     .16       0
  5127.4     .05       0    5283     .16       0  5298.9     .05       0
  5426.1     .16       0
Bank Sta=4991.8,5096
XS Rating Curve= 0 ,0
Exp/Cntr=0.3,0.1

Type RM Length L Ch R = 1 ,22851   ,495,495,495
BEGIN DESCRIPTION:
SPRING CREEK 1 6.0
END DESCRIPTION:
XS GIS Cut Line= 3
      3802599.61     10492460.19      3802249.61     10492560.19
      3801949.65      10492510.2
#Sta/Elev= 30
    4626  297.78  4642.9  296.31  4648.1  296.69  4657.2  291.99  4667.6  289.21
  4676.7   284.1  4688.4  281.17  4698.8  276.24  4703.7  275.05  4709.2  273.71
  4715.7  269.35  4717.9  269.18  4720.6  268.68  4723.9  269.18  5014.5  269.18
  5091.4  269.18  5121.8  270.26  5131.9  271.97  5152.2  274.81  5182.6  281.58
  5192.8  282.61  5200.4  285.86  5205.4  285.89    5213  287.43  5223.2  291.12
  5233.3  293.19  5261.2  301.87  5266.3  301.42  5273.9  304.87  5294.1  307.34
#Mann= 5 ,-1 , 0
    4626     .16       0  4703.7     .05       0  4717.9    .033       0
  4723.9     .05       0  5014.5     .16       0
Bank Sta=4709.2,5131.9
XS Rating Curve= 0 ,0
Exp/Cntr=0.3,0.1

Type RM Length L Ch R = 1 ,22356   ,525,525,525
BEGIN DESCRIPTION:
SPRING CREEK 1 5.0
END DESCRIPTION:
XS GIS Cut Line= 3
      3802599.61     10492160.19      3802249.61     10492060.19
      3801849.61     10492210.19
#Sta/Elev= 30
  4625.2  298.82  4681.1   292.4  4689.5  289.06  4714.9  280.88  4720.1  280.96
  4729.2  276.13  4739.6  273.53  4748.7  270.31  4757.4  269.18  4760.2  268.68
  4763.4  269.18  5136.3  269.18  5175.2  269.18  5192.1  271.93  5205.5  272.66
  5213.5  274.93  5224.2  275.71  5230.4  277.93  5235.7  277.88  5277.6  286.67
  5290.9  288.27  5298.9  291.42  5309.6  293.54  5315.8  297.81  5321.2  296.04
    5331  300.96  5346.1  305.07  5352.3  308.53  5406.6  315.62  5416.4  318.28
#Mann= 5 ,-1 , 0
  4625.2     .16       0  4689.5     .05       0  4757.4    .033       0
  4763.4     .05       0  5136.3     .16       0
Bank Sta=4739.6,5192.1
XS Rating Curve= 0 ,0
Exp/Cntr=0.3,0.1

Type RM Length L Ch R = 1 ,21831   ,120,120,120
BEGIN DESCRIPTION:
SPRING CREEK 1 4.0
END DESCRIPTION:
XS GIS Cut Line= 5
      3803464.34     10492069.29      3802622.34     10491461.66
      3802092.82     10491565.82      3801849.77     10491739.44
      3801571.98     10492694.34
#Sta/Elev= 30
  3376.2  325.63  3673.1  317.58  3852.9  313.59  3910.6  311.76  4060.3  307.04
  4167.2  299.03    4209  287.05  4232.2  274.16  4259.3  283.28  4324.3  293.22
  4395.4  292.66  4484.1  285.69  4489.2  282.35  4535.5  283.62  4549.8  280.44
  4689.7  284.25  4694.7   279.4  4723.4  276.58  4760.9  269.18  4763.6  268.68
  4766.9  269.18  5100.1  269.18  5255.9  271.77  5309.1  278.78  5326.6   286.2
  5373.8  290.04  5575.9  306.93  5671.3  312.67  5816.1  320.93  6247.4  322.09
#Mann= 11 ,-1 , 0
  3376.2     .05       0  3673.1     .16       0  3852.9     .05       0
  3910.6     .16       0  4723.4     .05       0  4760.9    .033       0
  4766.9     .05       0  5100.1     .16       0  5373.8     .05       0
  5575.9     .16       0  5671.3     .05       0
Bank Sta=4689.7,5326.6
XS Rating Curve= 0 ,0
Exp/Cntr=0.3,0.1

Type RM Length L Ch R = 1 ,21711   ,106,106,106
BEGIN DESCRIPTION:
Mapping XS a72b4a13
END DESCRIPTION:
XS GIS Cut Line= 6
      3803255.98     10491774.13      3802631.02     10491409.57
      3802040.74     10491479.02      3801884.49     10491565.82
      3801780.32     10491635.27      3801468.09     10492676.03
#Sta/Elev= 30
    3585   316.7  3655.2  314.41  3754.5  310.69  3862.6   294.4  3958.5   298.7
  4075.9  278.15  4081.7  286.39  4113.2  285.03  4140.4  296.87  4199.2  299.94
  4445.3   287.6  4581.7  294.69  4652.2  278.08    4707   274.6  4972.2  275.83
  4977.9  271.86    4994  275.77  5174.1  274.62  5204.2  271.06  5229.8  261.22
  5232.6  260.72  5235.8  261.22  5260.2  271.97    5285  275.73    5469  291.29
  5502.1  291.98  5644.8  296.12  5815.3  313.03  6005.4  319.63  6293.4  320.44
#Mann= 9 ,-1 , 0
    3585     .05       0  3655.2     .16       0  4972.2     .05       0
    4994     .16       0  5229.8     .07       0  5235.8     .16       0
    5469     .05       0  5502.1     .16       0  6005.4     .05       0
Bank Sta=5174.1,5285
XS Rating Curve= 0 ,0
Exp/Cntr=0.3,0.1

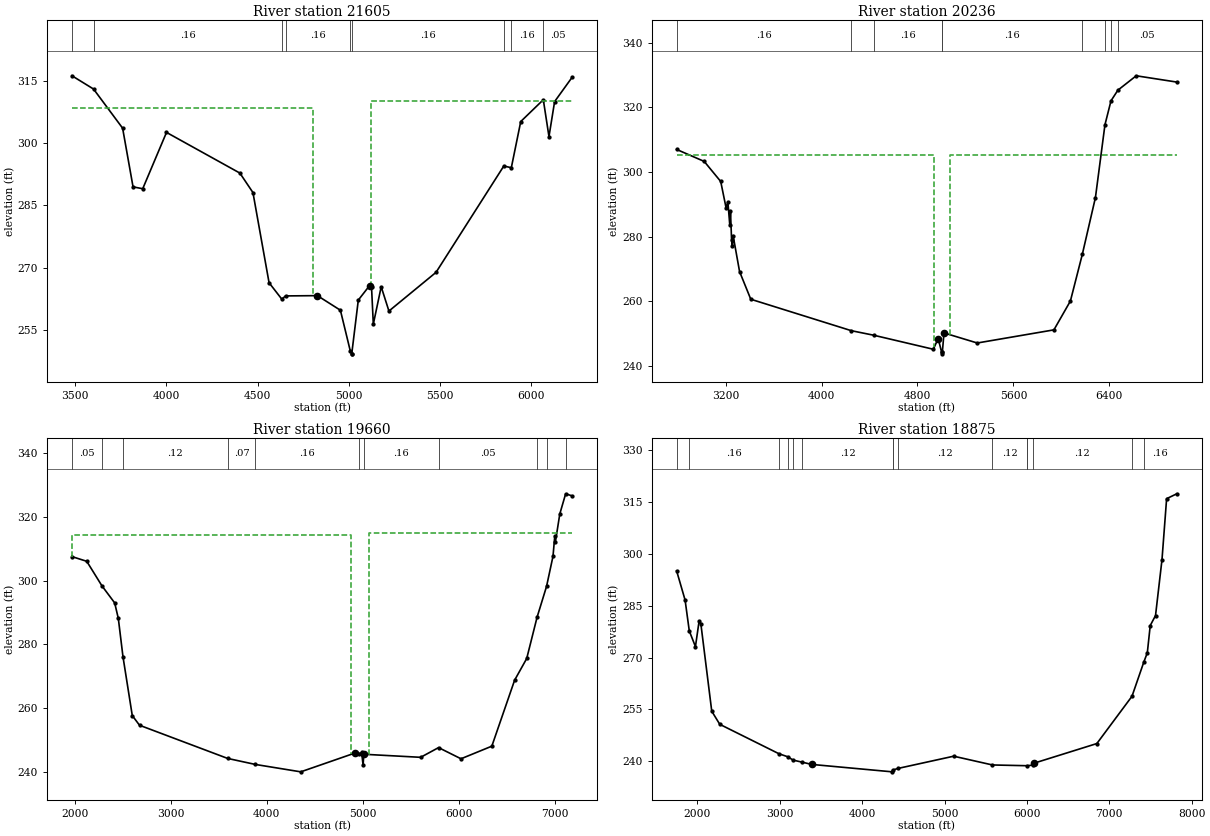
Type RM Length L Ch R = 1 ,21605   ,1369,1369,1369
BEGIN DESCRIPTION:
SPRING CREEK 1 3.0
END DESCRIPTION:
XS GIS Cut Line= 5
      3803282.09     10491704.73      3802674.42     10491366.17
      3802110.19     10491383.53      3801641.44     10491548.46
      3801398.39     10492503.28
#Sta/Elev= 30
  3482.5  316.27  3600.7  313.07  3760.1  303.63  3817.3  289.47  3870.4  289.03
  4000.7  302.61    4403   292.8  4474.7   288.1  4563.1  266.35  4633.1  262.38
  4653.2  263.17    4828  263.24  4954.2  259.72  5008.3  249.92  5015.9   249.2
  5016.4   249.2  5052.4  262.17  5114.4  265.67  5124.9   265.3  5134.7  256.36
  5177.9  265.38  5220.3  259.52  5478.6  268.86  5850.1   294.5  5891.4   294.1
    5943  305.23  6066.8  310.49  6097.8   301.6  6128.7  310.04  6224.8  315.91
#Mann= 9 ,-1 , 0
  3482.5     .05       0  3600.7     .16       0  4633.1     .05       0
  4653.2     .16       0  5008.3     .07       0  5016.4     .16       0
  5850.1     .05       0  5891.4     .16       0  6066.8     .05       0
#XS Ineff= 2 , 0
         4805.12  308.51 5122.05          310.14
Permanent Ineff=
       F       F
Bank Sta=4828,5114.4
XS Rating Curve= 0 ,0
Exp/Cntr=0.3,0.1

Type RM Length L Ch R = 1 ,20236   ,576,576,576
BEGIN DESCRIPTION:
SPRING CREEK 1 2.0
END DESCRIPTION:
XS GIS Cut Line= 4
      3802960.89     10491340.13      3801684.84     10490637.01
      3800686.57     10490975.55      3800209.14      10492564.1
#Sta/Elev= 30
  2792.1  306.99  3021.9  303.28  3159.6  297.06  3204.6  288.82  3219.2  290.79
  3235.3  283.49    3241  287.77  3250.3  278.78  3257.1  277.14  3262.8  280.31
  3316.7  269.14  3410.1  260.57    4249  250.82  4434.8  249.42    4932  245.07
  4972.6  248.39  5001.3  244.15    5004  243.65  5007.3  244.15    5021  250.13
  5298.4  247.01  5937.5  251.08  6074.9  260.02    6174  274.44  6283.6  292.08
    6363  314.65  6413.3  322.06  6470.8  325.36  6623.7  329.82  6961.9  327.87
#Mann= 9 ,-1 , 0
  2792.1     .16       0    4249     .07       0  4434.8     .16       0
  5001.3     .07       0  5007.3     .16       0    6174     .16       0
    6363     .05       0  6413.3     .16       0  6470.8     .05       0
#XS Ineff= 2 , 0
         4939.63   305.2 5070.87           305.2
Permanent Ineff=
       F       F
Bank Sta=4972.6,5021
XS Rating Curve= 0 ,0
Exp/Cntr=0.3,0.1

Type RM Length L Ch R = 1 ,19660   ,785,785,785
BEGIN DESCRIPTION:
Mapping XS 36821975
END DESCRIPTION:
XS GIS Cut Line= 4
      3803102.17     10490865.26      3800923.11     10489989.37
      3800127.31     10491495.51      3799935.32     10492636.81
#Sta/Elev= 30
  1971.3  307.57  2124.9   306.1  2283.5  298.38  2415.9  293.04  2453.9  288.16
  2502.2  276.18  2599.2  257.66  2674.6  254.62  3592.6   244.2  3881.7  242.31
    4354  239.99  4920.9  245.92  4965.4  245.69    4988  246.07  5003.3  242.13
  5010.7  245.51  5602.7  244.55  5789.5   247.6  6023.1  244.09  6344.2  248.05
  6581.4  268.76  6707.6  275.58  6815.2  288.51  6914.1  298.22  6981.2  307.66
  7000.2  314.13  7005.3  312.02  7052.2  320.98  7113.1   327.3  7180.6  326.64
#Mann= 11 ,-1 , 0
  1971.3     .05       0  2283.5     .16       0  2502.2     .12       0
  3592.6     .07       0  3881.7     .16       0  4965.4     .07       0
  5010.7     .16       0  5789.5     .05       0  6815.2     .16       0
  6914.1      .1       0  7113.1     .05       0
#XS Ineff= 2 , 0
         4881.23  314.46 5064.96          315.07
Permanent Ineff=
       F       F
Bank Sta=4920.9,5010.7
XS Rating Curve= 0 ,0
Exp/Cntr=0.3,0.1

Type RM Length L Ch R = 1 ,18875   ,0,0,0
BEGIN DESCRIPTION:
SPRING CREEK 1 1.0
END DESCRIPTION:
XS GIS Cut Line= 4
      3802934.86     10490263.75      3801309.84     10489388.74
      3799684.84     10490367.91      3798247.36     10492201.21
#Sta/Elev= 30
  1747.2  295.07  1849.7  286.64  1900.8  277.68  1975.4  273.15  2019.2  280.43
  2041.1  279.77  2173.4  254.45  2270.7  250.65  2989.3  242.13  3099.3  241.23
  3160.2  240.29  3275.1  239.67  3386.2  239.04    4365  236.89  4368.2  237.39
  4435.5  237.88  5110.8  241.42  5581.6  238.88  6004.4  238.66  6071.6  238.85
  6086.9   239.4    6849  245.08  7275.7  258.77  7418.9  268.65  7461.9  271.38
  7497.2  279.26  7561.4  282.14    7640  298.34  7696.1  315.99  7819.7  317.41
#Mann= 15 ,-1 , 0
  1747.2     .05       0  1900.8     .16       0  2989.3     .07       0
  3099.3     .05       0  3160.2     .07       0  3275.1     .12       0
  4368.2     .03       0  4368.2     .05       0  4435.5     .12       0
  5581.6     .12       0  6004.4     .07       0  6004.4     .05       0
  6071.6     .12       0  7275.7     .05       0  7418.9     .16       0
Bank Sta=3386.2,6086.9
XS Rating Curve= 0 ,0
Exp/Cntr=0.3,0.1

Chan Stop Cuts=-1
Use User Specified Reach Order=0
Composite Channel Slope=5