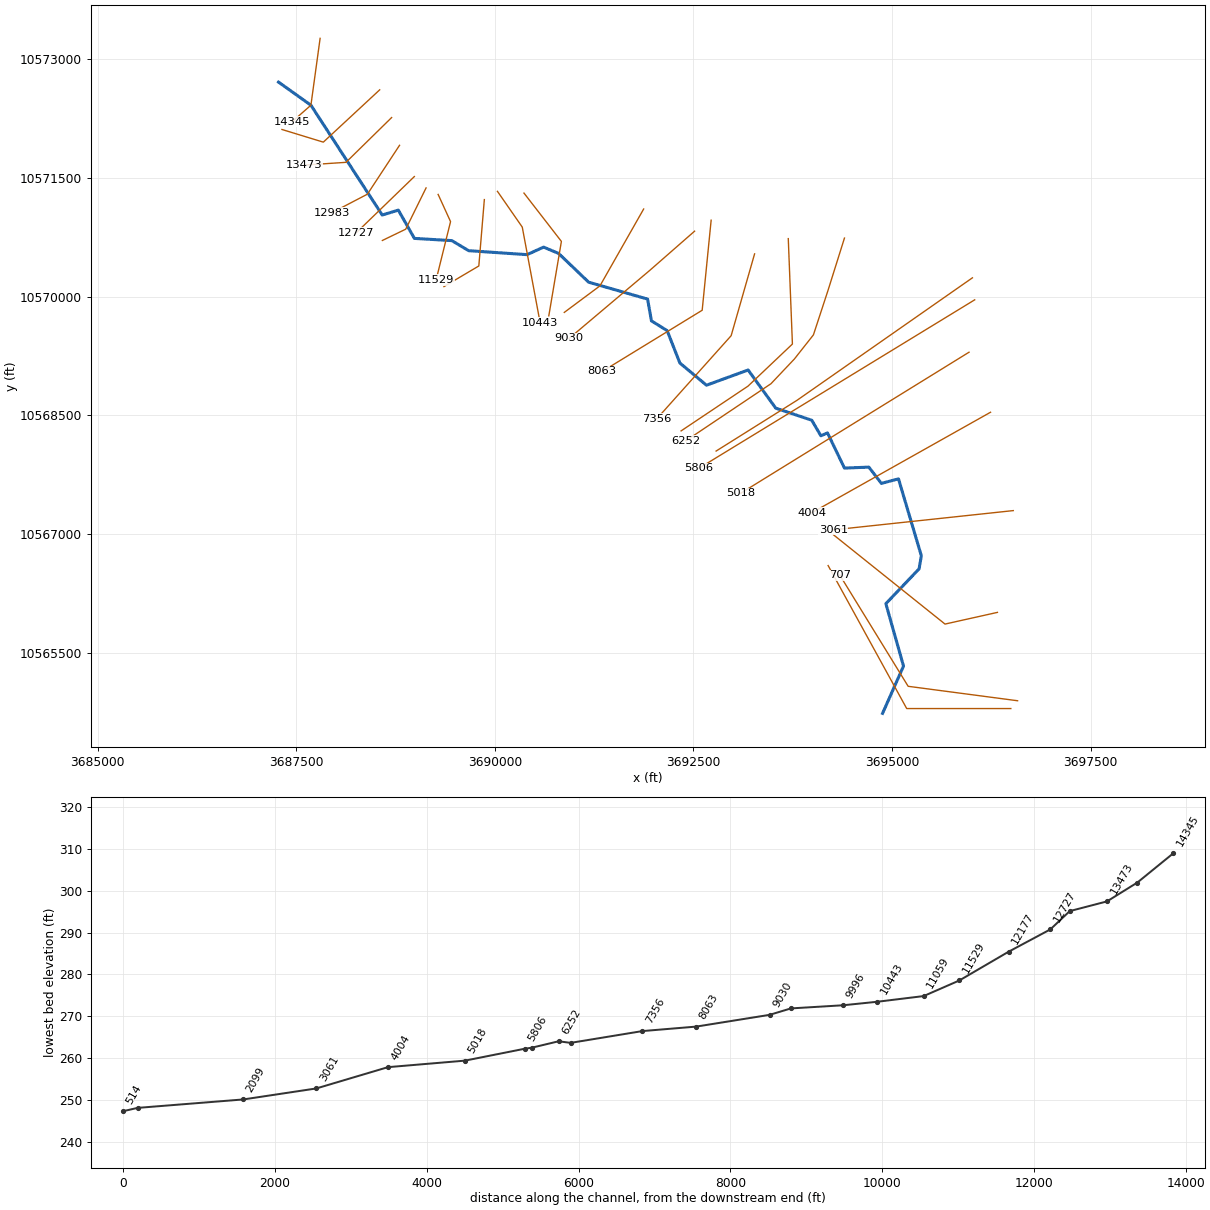
--- TOMS CREEK.prj (project) ---

Proj Title=TOMS CREEK Base Level Engineering
Current Plan=p01
Default Exp/Contr=0.3,0.1
English Units
Geom File=g01
Flow File=f01
Plan File=p01
Y Axis Title=Elevation
X Axis Title(PF)=Main Channel Distance
X Axis Title(XS)=Station
BEGIN DESCRIPTION:
TOMS CREEK
END DESCRIPTION:
DSS Export Rating Curves= 0
DSS Export Rating Curve Sorted= 0
DSS Export Volume Flow Curves= 0
DXF OffsetX= 0
DXF OffsetY= 0
DXF ScaleX= 1
DXF ScaleY= 10

--- TOMS CREEK.p01 (plan) ---

Plan Title=Multiple Run
Short Identifier=Multiple
Geom File=g01
Flow File=f01
Subcritical Flow
K Sum by GR= 0
Std Step Tol= 0.01
Critical Tol= 0.01
Num of Std Step Trials= 20
Max Error Tol= 0.3
Flow Tol Ratio= 0.001
Split Flow NTrial= 30
Split Flow Tol= 0.02
Split Flow Ratio= 0.02
Log Output Level= 0
Friction Slope Method= 1
Unsteady Friction Slope Method= 2
Unsteady Bridges Friction Slope Method= 1
Parabolic Critical Depth
Global Vel Dist=  1 , 1 , 1
Global Log Level= 0
CheckData=True
Encroach Param= -1, 0, 0, 0
BEGIN DESCRIPTION:
Multiple Run
END DESCRIPTION:

--- TOMS CREEK.f01 (steady flow) ---

Flow Title=Multiple
Program Version=4.10
Number of Profiles= 7
Profile Names=10-year,25-year,50-year,1pct_min,100-year,1pct_plu,500-year
River Rch & RM=TOMS CREEK,Reach-1         ,14345
     588     806     989     893    1207    1633    1806
River Rch & RM=TOMS CREEK,Reach-1         ,9311
     990    1383    1716    1562    2112    2857    3217
River Rch & RM=TOMS CREEK,Reach-1         ,5895
    1173    1647    2051    1873    2533    3425    3880
River Rch & RM=TOMS CREEK,Reach-1         ,3061
    1173    1647    2051    1873    2533    3425    3880
Boundary for River Rch & Prof#=TOMS CREEK,Reach-1         , 1
Up Type= 0
Dn Type= 3
Dn Slope=0.003
Boundary for River Rch & Prof#=TOMS CREEK,Reach-1         , 2
Up Type= 0
Dn Type= 3
Dn Slope=0.003
Boundary for River Rch & Prof#=TOMS CREEK,Reach-1         , 3
Up Type= 0
Dn Type= 3
Dn Slope=0.003
Boundary for River Rch & Prof#=TOMS CREEK,Reach-1         , 4
Up Type= 0
Dn Type= 3
Dn Slope=0.003
Boundary for River Rch & Prof#=TOMS CREEK,Reach-1         , 5
Up Type= 0
Dn Type= 3
Dn Slope=0.003
Boundary for River Rch & Prof#=TOMS CREEK,Reach-1         , 6
Up Type= 0
Dn Type= 3
Dn Slope=0.003
Boundary for River Rch & Prof#=TOMS CREEK,Reach-1         , 7
Up Type= 0
Dn Type= 3
Dn Slope=0.003
DSS Import GetInterval= 0
DSS Import GetPeak= 0
DSS Import FillOption= 0

--- TOMS CREEK.g01 (geometry) ---

Geom Title=Existing Conditions
Program Version=4.10

River Reach=TOMS CREEK      ,Reach-1
Reach XY= 30
      3687275.75       10572708.      3687683.75       10572416.
       3688581.5       10571030.      3688784.25       10571092.
      3688986.75       10570735.      3689458.25       10570707.
      3689669.25       10570580.      3690404.25       10570530.
       3690613.5       10570625.      3690802.25       10570545.
       3691180.5       10570182.        3691922.       10569969.
      3691970.75       10569694.      3692168.25       10569571.
      3692328.75       10569162.       3692663.5       10568882.
      3693187.75       10569074.        3693536.       10568592.
        3693989.       10568440.       3694103.5       10568244.
        3694187.       10568280.       3694400.5       10567836.
      3694707.75       10567848.      3694865.25       10567643.
      3695080.75       10567700.       3695368.5       10566729.
        3695340.       10566564.      3694921.86     10566124.57
        3695144.       10565337.      3694880.25       10564740.

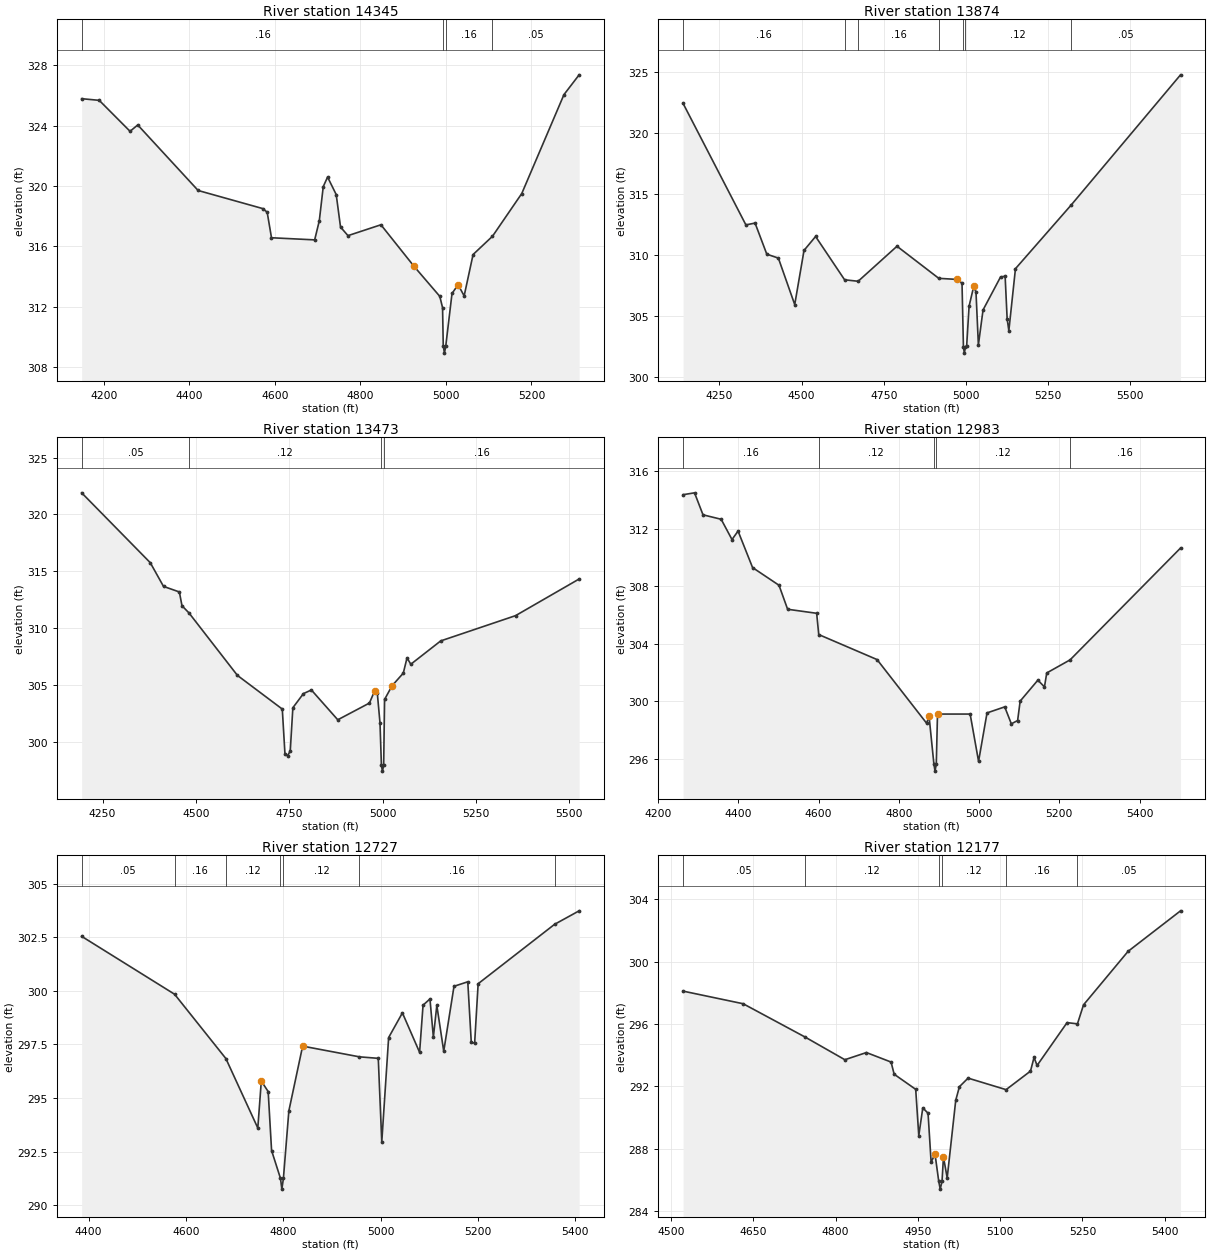
Type RM Length L Ch R = 1 ,14345   ,471,471,471
BEGIN DESCRIPTION:
TOMS CREEK 19.0
END DESCRIPTION:
XS GIS Cut Line= 3
      3687799.61     10573260.19      3687683.75       10572416.
      3687449.64     10572210.21
#Sta/Elev= 30
  4147.9  325.78    4189  325.67  4261.1  323.62  4279.1  324.04  4420.4   319.7
  4571.8   318.5  4581.9  318.26    4592  316.57    4693  316.43  4703.8  317.69
  4713.1  319.96  4723.2  320.59  4743.4  319.43  4753.5  317.28  4770.9  316.71
    4848  317.43  4925.1  314.69  4985.7  312.69  4992.2  311.94  4993.8  309.43
  4996.6  308.93  4999.8  309.43  5014.3  312.88  5028.5  313.46  5042.7  312.72
  5063.6  315.46    5109  316.67  5177.5   319.5  5276.2  326.05  5311.7  327.36
#Mann= 4 ,-1 , 0
  4147.9     .16       0  4993.8     .07       0  4999.8     .16       0
    5109     .05       0
Bank Sta=4925.1,5028.5
XS Rating Curve= 0 ,0
Exp/Cntr=0.3,0.1

Type RM Length L Ch R = 1 ,13874   ,401,401,401
BEGIN DESCRIPTION:
TOMS CREEK 18.0
END DESCRIPTION:
XS GIS Cut Line= 3
       3688549.6     10572610.18      3687840.11     10571949.97
       3687319.3     10572109.69
#Sta/Elev= 30
  4139.4  322.44  4330.6  312.48  4358.5  312.63  4394.2  310.08  4429.4  309.76
  4479.2  305.95  4507.5  310.39  4542.7  311.53    4631  307.98  4672.2  307.86
  4790.4  310.73  4917.6   308.1  4974.1  308.01  4988.3   307.7  4992.6  302.47
  4995.4  301.97  4998.6  302.47  5002.5  302.59  5009.8  305.82    5024  307.45
  5030.8  306.99  5038.1  302.64  5052.3  305.51  5105.5  308.21  5119.5  308.27
  5125.6  304.79  5130.8  303.81  5150.9  308.89  5320.2   314.1  5653.3  324.78
#Mann= 7 ,-1 , 0
  4139.4     .16       0    4631     .12       0  4672.2     .16       0
  4917.6     .12       0  4992.6     .07       0  4998.6     .12       0
  5320.2     .05       0
Bank Sta=4974.1,5024
XS Rating Curve= 0 ,0
Exp/Cntr=0.3,0.1

Type RM Length L Ch R = 1 ,13473   ,490,490,490
BEGIN DESCRIPTION:
TOMS CREEK 17.0
END DESCRIPTION:
XS GIS Cut Line= 3
      3688699.62      10572260.2        3688125.       10571695.
      3687599.65     10571660.19
#Sta/Elev= 30
    4194   321.9  4377.8  315.76  4413.2  313.68  4455.7  313.19  4462.7  311.98
  4481.4  311.35  4611.2  305.86  4731.4   302.9  4738.5  298.98  4745.6   298.8
  4752.7  299.22  4759.7  303.02    4788  304.26  4809.3  304.58    4880  301.96
  4964.8  303.43    4979  304.52    4986  304.27  4993.1  301.68  4996.9  297.95
  4999.6  297.45  5002.9  297.95  5005.4  303.75  5025.4  304.95  5055.5  306.06
  5065.5   307.4  5075.6  306.84  5155.7  308.89  5356.2  311.11  5526.5  314.33
#Mann= 4 ,-1 , 0
    4194     .05       0  4481.4     .12       0  4996.9     .07       0
  5002.9     .16       0
Bank Sta=4979,5025.4
XS Rating Curve= 0 ,0
Exp/Cntr=0.3,0.1

Type RM Length L Ch R = 1 ,12983   ,256,256,256
BEGIN DESCRIPTION:
TOMS CREEK 16.0
END DESCRIPTION:
XS GIS Cut Line= 3
      3688799.59     10571910.17      3688394.75       10571293.
      3687949.65     10571060.21
#Sta/Elev= 30
  4261.9  314.36  4290.5  314.49  4311.6  312.96  4356.9  312.65  4383.9  311.24
    4399  311.83  4435.2  309.29  4501.1  308.06  4522.6  306.39    4595  306.11
  4600.2  304.63  4745.6  302.89  4869.2  298.46  4875.2  298.96  4887.3  295.63
  4890.1  295.13  4893.3  295.63  4896.3   299.1  4977.7   299.1  4998.7  295.81
  5019.8  299.18  5063.9   299.6  5080.4  298.42  5096.1  298.65  5102.4     300
  5146.6  301.46    5163  300.99  5168.7  301.96  5226.9  302.87  5502.3  310.65
#Mann= 5 ,-1 , 0
  4261.9     .16       0  4600.2     .12       0  4887.3     .07       0
  4893.3     .12       0  5226.9     .16       0
Bank Sta=4875.2,4896.3
XS Rating Curve= 0 ,0
Exp/Cntr=0.3,0.1

Type RM Length L Ch R = 1 ,12727   ,550,550,550
BEGIN DESCRIPTION:
TOMS CREEK 15.0
END DESCRIPTION:
XS GIS Cut Line= 2
      3688985.95     10571515.66      3688252.45     10570803.86
#Sta/Elev= 30
  4385.7  302.54  4576.6  299.84    4682  296.84  4747.6   293.6  4754.8  295.79
  4768.9   295.3  4775.9  292.55  4794.2  291.25    4797  290.75  4800.2  291.25
  4811.4   294.4  4839.7  297.42  4956.4  296.92  4995.1  296.85  5002.3  292.95
  5016.4  297.82  5044.7  298.97    5080  297.13  5087.1  299.33  5101.3  299.62
  5108.3  297.84  5115.4  299.32  5129.6  297.18  5150.7  300.21    5179  300.42
  5186.2  297.59  5193.1  297.56  5200.3  300.33  5357.3   303.1  5407.8  303.73
#Mann= 7 ,-1 , 0
  4385.7     .05       0  4576.6     .16       0    4682     .12       0
  4794.2     .07       0  4800.2     .12       0  4956.4     .16       0
  5357.3     .05       0
Bank Sta=4754.8,4839.7
XS Rating Curve= 0 ,0
Exp/Cntr=0.3,0.1

Type RM Length L Ch R = 1 ,12177   ,648,648,648
BEGIN DESCRIPTION:
TOMS CREEK 14.0
END DESCRIPTION:
XS GIS Cut Line= 3
      3689133.51     10571372.41      3688877.44     10570851.59
      3688583.49     10570708.94
#Sta/Elev= 30
  4521.9  298.11  4631.5   297.3  4744.1  295.17  4816.9  293.71  4856.2  294.17
  4901.2  293.56  4906.8  292.78  4946.1  291.81  4951.7  288.84    4959  290.62
  4968.6  290.28  4974.2  287.14  4981.3  287.66  4988.1  285.91  4990.8  285.41
  4994.1  285.91  4996.7  287.47  5003.5  286.13  5019.1  291.11  5025.8  291.98
  5041.6  292.53  5110.9  291.79  5155.4  292.98  5161.9  293.86  5167.4  293.34
  5222.1  296.09    5241  296.01  5252.1  297.23  5333.3  300.66    5429  303.26
#Mann= 6 ,-1 , 0
  4521.9     .05       0  4744.1     .12       0  4988.1     .07       0
  4994.1     .12       0  5110.9     .16       0    5241     .05       0
Bank Sta=4981.3,4996.7
XS Rating Curve= 0 ,0
Exp/Cntr=0.3,0.1

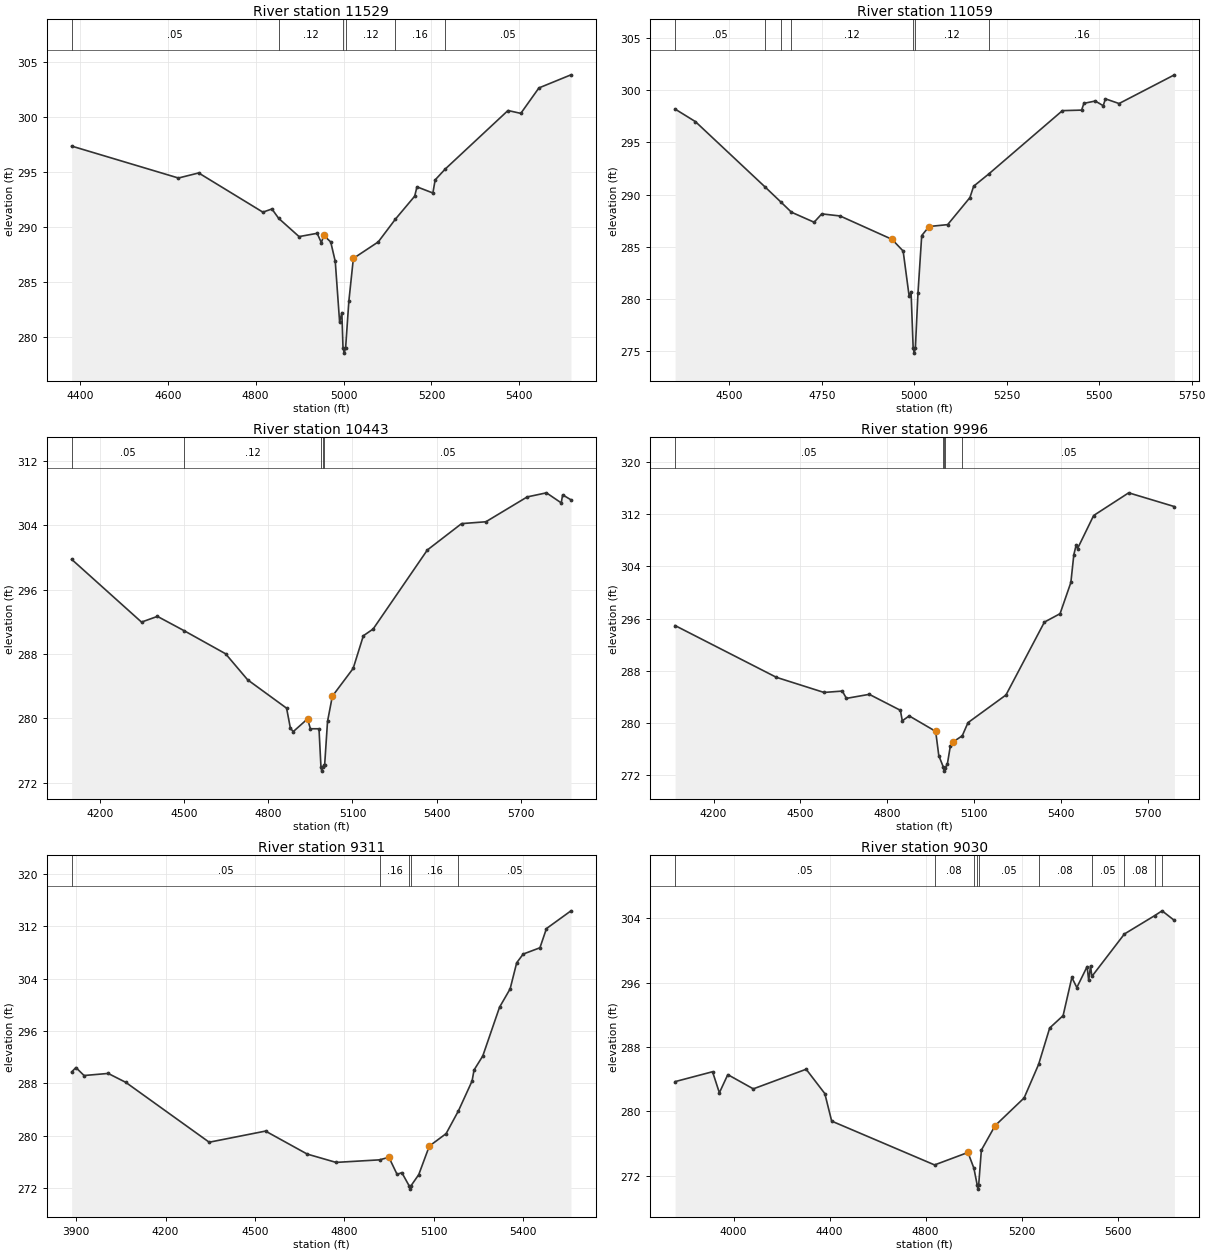
Type RM Length L Ch R = 1 ,11529   ,470,470,470
BEGIN DESCRIPTION:
TOMS CREEK 13.0
END DESCRIPTION:
XS GIS Cut Line= 3
      3689285.42     10571289.97      3689441.68     10570947.08
      3689259.39     10570209.28
#Sta/Elev= 30
    4381  297.34  4624.1  294.44  4670.2   294.9  4816.4  291.34    4837  291.63
  4852.3  290.78  4898.8  289.12    4940  289.42  4949.6  288.56  4954.8  289.24
  4970.9  288.63  4981.2  286.86  4991.1  281.35  4996.2  282.22  4998.8  279.04
  5001.6  278.54  5004.8  279.04  5012.1  283.24  5022.4  287.14  5079.1  288.64
  5118.2  290.71    5162  292.79  5167.2  293.64  5203.4  293.08  5208.6  294.27
  5231.4  295.25  5374.4  300.57  5403.6  300.31  5444.8  302.62  5517.8  303.81
#Mann= 6 ,-1 , 0
    4381     .05       0  4852.3     .12       0  4998.8     .07       0
  5004.8     .12       0  5118.2     .16       0  5231.4     .05       0
Bank Sta=4954.8,5022.4
XS Rating Curve= 0 ,0
Exp/Cntr=0.3,0.1

Type RM Length L Ch R = 1 ,11059   ,616,616,616
BEGIN DESCRIPTION:
TOMS CREEK 12.0
END DESCRIPTION:
XS GIS Cut Line= 3
      3689867.03     10571224.89      3689797.58     10570387.18
      3689359.18     10570126.75
#Sta/Elev= 30
  4352.9  298.19  4407.8  296.99  4595.9  290.74  4639.5  289.27  4667.6  288.31
  4728.9  287.35  4749.6  288.15  4799.1  287.95  4939.6  285.71  4969.7  284.59
    4986  280.24  4991.1   280.7  4996.8  275.31  4999.6  274.81  5002.8  275.31
  5009.8  280.55  5019.9  286.07  5039.9  286.94  5090.1  287.12  5150.3  289.71
  5160.4   290.8  5200.8  291.96  5400.5  298.04  5452.4  298.09  5458.6  298.74
  5489.4  298.96  5510.8  298.51  5516.8  299.17  5553.7  298.72  5703.4  301.47
#Mann= 7 ,-1 , 0
  4352.9     .05       0  4595.9     .12       0  4639.5     .05       0
  4667.6     .12       0  4996.8     .07       0  5002.8     .12       0
  5200.8     .16       0
Bank Sta=4939.6,5039.9
XS Rating Curve= 0 ,0
Exp/Cntr=0.3,0.1

Type RM Length L Ch R = 1 ,10443   ,447,447,447
BEGIN DESCRIPTION:
TOMS CREEK 11.0
END DESCRIPTION:
XS GIS Cut Line= 3
      3690031.98     10571328.99      3690344.45     10570877.64
      3690570.16     10569666.65
#Sta/Elev= 30
  4098.5  299.79  4347.7  291.98  4404.5  292.69  4498.6  290.93  4647.5  288.04
  4726.2   284.8  4865.1  281.27  4878.8  278.76    4889  278.36  4939.9  279.94
    4950  278.71  4980.7  278.71  4987.7  273.94  4990.5  273.44  4993.7  273.94
  4999.2  274.16  5000.9  274.23  5011.1  279.62  5028.3  282.76  5102.6  286.22
  5138.9  290.28  5173.8  291.12  5367.1  300.95  5489.2  304.23  5575.9  304.46
  5723.1  307.55  5791.8  308.06  5844.6  306.81  5849.6  307.81  5879.3  307.19
#Mann= 5 ,-1 , 0
  4098.5     .05       0  4498.6     .12       0  4987.7     .03       0
  4993.7     .12       0  4999.2     .05       0
Bank Sta=4939.9,5028.3
XS Rating Curve= 0 ,0
Exp/Cntr=0.3,0.1

Type RM Length L Ch R = 1 ,9996    ,685,685,685
BEGIN DESCRIPTION:
TOMS CREEK 9.0
END DESCRIPTION:
XS GIS Cut Line= 3
      3690366.13     10571306.81      3690837.07     10570697.08
      3690678.66     10569757.88
#Sta/Elev= 30
  4067.3  294.94  4416.8     287  4581.1  284.68  4644.3  284.89  4658.5  283.77
  4737.3  284.39  4844.7  281.94  4851.2  280.33  4875.1  281.08  4966.4  278.71
  4977.2  274.99  4993.3  273.18  4993.8  273.11  4996.6  272.61  4999.8  273.11
    5007  273.76  5017.1  276.48  5027.3  277.11  5058.1  278.03    5078  280.05
    5209  284.29  5341.6  295.47  5395.6  296.76  5432.9  301.55  5443.1  305.81
    5451  307.26    5456  306.75  5511.5  311.82  5632.4   315.3  5790.2  313.19
#Mann= 5 ,-1 , 0
  4067.3     .05       0  4993.3     .12       0  4993.8     .07       0
  4999.8     .12       0  5058.1     .05       0
Bank Sta=4966.4,5027.3
XS Rating Curve= 0 ,0
Exp/Cntr=0.3,0.1

Type RM Length L Ch R = 1 ,9311    ,281,281,281
BEGIN DESCRIPTION:
TOMS CREEK 8.0
END DESCRIPTION:
XS GIS Cut Line= 3
      3691872.66     10571105.93       3691322.5       10570136.
      3690873.66     10569801.12
#Sta/Elev= 30
  3884.9  289.74  3899.2  290.42  3926.6   289.2  4007.4  289.52  4066.5  288.16
  4346.4  279.02  4535.3  280.72  4675.2  277.21  4771.9  275.94    4918  276.33
  4949.2  276.72  4976.7  274.11  4992.6  274.38  5017.2  272.36    5020  271.86
  5023.2  272.36  5049.4  274.08  5084.8  278.43  5141.1  280.33  5182.6  283.82
  5228.2  288.36  5234.9  290.05  5264.1  292.18  5320.4  299.63  5355.9  302.43
  5377.9  306.41  5399.7  307.74  5455.9   308.7  5477.7  311.63    5560  314.34
#Mann= 5 ,-1 , 0
  3884.9     .05       0    4918     .16       0  5017.2     .07       0
  5023.2     .16       0  5182.6     .05       0
Bank Sta=4949.2,5084.8
XS Rating Curve= 0 ,0
Exp/Cntr=0.3,0.1

Type RM Length L Ch R = 1 ,9030    ,967,967,967
BEGIN DESCRIPTION:
TOMS CREEK 7.0
END DESCRIPTION:
XS GIS Cut Line= 3
      3692513.95     10570826.33      3691949.73     10570331.55
      3690934.38      10569472.4
#Sta/Elev= 30
  3756.3  283.69  3912.4  284.92  3940.8   282.3  3975.9  284.56  4082.2  282.79
  4302.4  285.23  4380.2   282.2  4408.7  278.78  4837.5  273.33  4976.5  274.88
  5001.2  272.93  5015.2  270.82  5017.9  270.32  5021.2  270.82  5032.4  275.17
  5089.6  278.21  5210.5  281.66    5271  285.84  5317.1  290.36    5373   291.9
  5409.4  296.64  5430.2  295.39  5473.1     298  5479.6  296.27  5487.4  298.08
  5492.8  296.77  5628.4  302.05  5753.8  304.32  5785.4  304.93  5836.8  303.73
#Mann= 10 ,-1 , 0
  3756.3     .05       0  4837.5     .08       0  5001.2     .05       0
  5015.2     .07       0  5021.2     .05       0    5271     .08       0
  5492.8     .05       0  5628.4     .08       0  5753.8     .05       0
  5785.4     .08       0
Bank Sta=4976.5,5089.6
XS Rating Curve= 0 ,0
Exp/Cntr=0.3,0.1

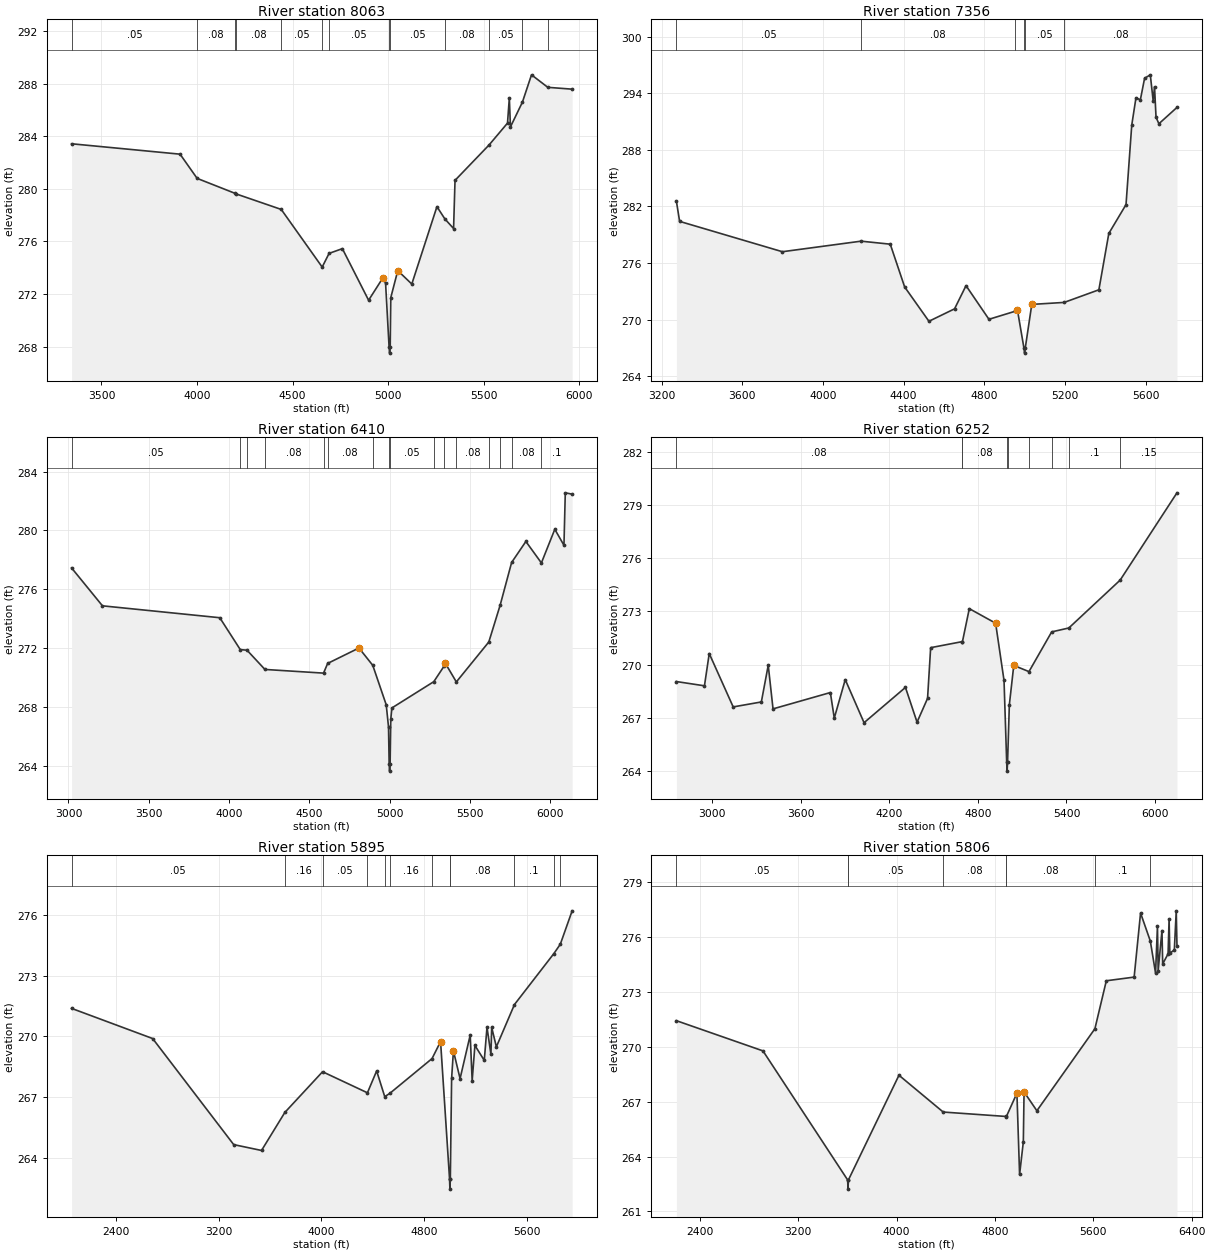
Type RM Length L Ch R = 1 ,8063    ,707,707,707
BEGIN DESCRIPTION:
TOMS CREEK 6.0
END DESCRIPTION:
XS GIS Cut Line= 3
       3692722.3     10570965.19      3692609.46     10569828.08
      3691350.75     10569055.49
#Sta/Elev= 30
  3343.6  283.42  3911.4  282.63  4000.7  280.79  4199.7  279.65  4206.6   279.6
  4440.9  278.43  4655.1  274.05  4691.2  275.09  4760.7  275.45    4898  271.53
  4971.4   273.2  4986.8  272.84  5005.1  268.01  5007.9  267.51  5011.1  268.01
  5014.1  271.73  5050.7  273.78  5124.1  272.76  5255.6  278.64  5297.1  277.71
  5342.7  276.98  5350.3  280.64  5529.1  283.34  5624.9  284.99  5634.5   286.9
  5640.3   284.7  5703.1  286.59  5750.5  288.66  5835.8  287.71  5963.2  287.57
#Mann= 13 ,-1 , 0
  3343.6     .05       0  4000.7     .08       0  4199.7      .1       0
  4206.6     .08       0  4440.9     .05       0  4655.1     .08       0
  4691.2     .05       0  5005.1     .04       0  5011.1     .05       0
  5297.1     .08       0  5529.1     .05       0  5703.1     .08       0
  5835.8     .05       0
Bank Sta=4971.4,5050.7
XS Rating Curve= 0 ,0
Exp/Cntr=0.3,0.1

Type RM Length L Ch R = 1 ,7356    ,946,946,946
BEGIN DESCRIPTION:
TOMS CREEK 5.0
END DESCRIPTION:
XS GIS Cut Line= 3
      3693269.18      10570539.9      3692974.04      10569506.9
      3692036.56     10568456.57
#Sta/Elev= 30
  3273.4  282.57  3289.4  280.42    3799   277.2  4189.2  278.32  4333.9     278
  4405.3  273.46  4525.7  269.82  4652.8  271.14  4709.6   273.6  4823.3  270.03
  4954.2  270.89  4964.6  271.01  4997.1  266.94  4999.9  266.44  5003.1  266.94
  5035.7  271.61  5196.2  271.82  5368.4  273.16  5417.7  279.14    5503   282.2
  5531.4  290.64  5552.3  293.53  5574.1  293.32    5595   295.6  5623.4  295.97
  5637.6  293.22  5644.3  294.71  5651.8  291.47    5666  290.78  5755.6  292.51
#Mann= 6 ,-1 , 0
  3273.4     .05       0  4189.2     .08       0  4954.2     .05       0
  4997.1     .04       0  5003.1     .05       0  5196.2     .08       0
Bank Sta=4964.6,5035.7
XS Rating Curve= 0 ,0
Exp/Cntr=0.3,0.1

Type RM Length L Ch R = 1 ,6410    ,158,158,158
BEGIN DESCRIPTION:
TOMS CREEK 4.0
END DESCRIPTION:
XS GIS Cut Line= 4
      3693693.27     10570732.37      3693745.35     10569401.65
      3693186.32      10568870.4      3692344.17      10568305.5
#Sta/Elev= 30
  3019.4  277.45  3211.7  274.87  3942.3  274.06  4069.9  271.89  4111.8  271.85
  4223.4  270.54  4588.4  270.29    4614  270.95    4809     272  4894.9  270.82
  4978.8  268.13    4993  266.62  4996.9  264.12  4999.6  263.62  5002.9  264.12
  5007.1  267.16    5014  267.92  5275.1  269.71  5339.8  270.78  5344.1  271.01
  5415.3  269.69  5617.5  272.41    5688  274.91  5759.5  277.82  5848.3  279.25
  5944.9  277.79  6028.4  280.08  6085.4  278.99  6093.7  282.56  6136.4  282.47
#Mann= 16 ,-1 , 0
  3019.4     .05       0  4069.9     .08       0  4111.8     .05       0
  4223.4     .08       0  4588.4     .05       0    4614     .08       0
  4894.9     .05       0  4996.9     .07       0  5002.9     .05       0
  5275.1      .1       0  5339.8     .05       0  5415.3     .08       0
  5617.5      .1       0    5688     .05       0  5759.5     .08       0
  5944.9      .1       0
Bank Sta=4809,5344.1
XS Rating Curve= 0 ,0
Exp/Cntr=0.3,0.1

Type RM Length L Ch R = 1 ,6252    ,357,357,357
BEGIN DESCRIPTION:
TOMS CREEK 3.0
END DESCRIPTION:
XS GIS Cut Line= 6
      3694400.64     10570739.34      3694191.53     10570072.66
       3694009.8     10569517.14      3693770.52     10569213.28
      3693475.39     10568900.78      3692403.96     10568180.72
#Sta/Elev= 30
  2757.8  269.05  2947.9  268.81  2980.3  270.63  3142.5  267.62  3333.3   267.9
  3379.9  269.97  3412.4  267.51  3800.7  268.43  3827.3  266.99  3901.6  269.16
    4029  266.73  4309.4  268.72    4388  266.76  4459.1   268.1  4480.1  270.96
  4693.4   271.3  4695.2  271.29  4741.9  273.16  4920.1  272.34  4977.1  269.11
  4995.1   264.5  4997.9     264  5001.1   264.5  5013.1  267.74  5043.1  269.96
    5146  269.61  5299.9  271.85    5416  272.07  5763.8  274.77  6148.5  279.69
#Mann= 9 ,-1 , 0
  2757.8     .08       0  4693.4      .1       0  4695.2     .08       0
  4995.1     .07       0  5001.1     .08       0    5146      .1       0
  5299.9     .15       0    5416      .1       0  5763.8     .15       0
Bank Sta=4920.1,5043.1
XS Rating Curve= 0 ,0
Exp/Cntr=0.3,0.1

Type RM Length L Ch R = 1 ,5895    ,89,89,89
BEGIN DESCRIPTION:
TOMS CREEK 2.0
END DESCRIPTION:
XS GIS Cut Line= 3
      3696011.59     10570237.62      3693802.77     10568691.18
      3692784.94     10568050.97
#Sta/Elev= 30
  2054.9  271.38  2686.4  269.89  3317.6  264.65  3534.4  264.36  3716.1  266.24
  4009.8  268.25  4359.2  267.21    4431  268.29    4494  267.02  4533.4  267.18
  4862.5   268.9  4928.9  269.74  4998.9  262.95  5001.7  262.45  5004.9  262.95
  5014.9  267.92    5029  269.28  5080.8  267.91  5159.7  270.06    5175  267.81
  5196.3  269.55  5269.3  268.81  5290.5  270.45  5321.1  269.11    5327  270.44
  5363.5  269.48  5504.4  271.57  5811.6  274.09  5861.5  274.55  5953.7   276.2
#Mann= 12 ,-1 , 0
  2054.9     .05       0  3716.1     .16       0  4009.8     .05       0
  4359.2     .12       0    4494     .08       0  4533.4     .16       0
  4862.5     .08       0  4998.9     .07       0  5004.9     .08       0
  5504.4      .1       0  5811.6     .08       0  5861.5      .1       0
Bank Sta=4928.9,5029
XS Rating Curve= 0 ,0
Exp/Cntr=0.3,0.1

Type RM Length L Ch R = 1 ,5806    ,788,788,788
BEGIN DESCRIPTION:
Mapping XS 1563ff7d
END DESCRIPTION:
XS GIS Cut Line= 2
       3696040.2     10569959.81      3692567.96     10567833.06
#Sta/Elev= 30
  2208.8  271.42  2913.1  269.77    3602  262.72  3604.7  262.22    3608  262.72
  4019.3  268.44  4379.1  266.43  4888.1  266.19    4890  266.14  4978.7  267.46
  5000.5  263.02  5030.9   264.8  5036.8  267.53  5141.1   266.5  5613.1  270.98
    5706   273.6  5932.3   273.8  5984.5   277.3  6063.9  275.77  6106.4  274.02
  6121.9  276.58  6127.7  274.16  6158.6  276.34  6164.5  274.52  6208.3  275.07
  6216.6  276.97  6222.5  275.11  6259.2  275.28  6274.7  277.42  6280.6  275.52
#Mann= 8 ,-1 , 0
  2208.8     .05       0    3602     .07       0    3608     .05       0
  4379.1     .08       0  4888.1     .05       0    4890     .08       0
  5613.1      .1       0  6063.9     .08       0
Bank Sta=4978.7,5036.8
XS Rating Curve= 0 ,0
Exp/Cntr=0.3,0.1

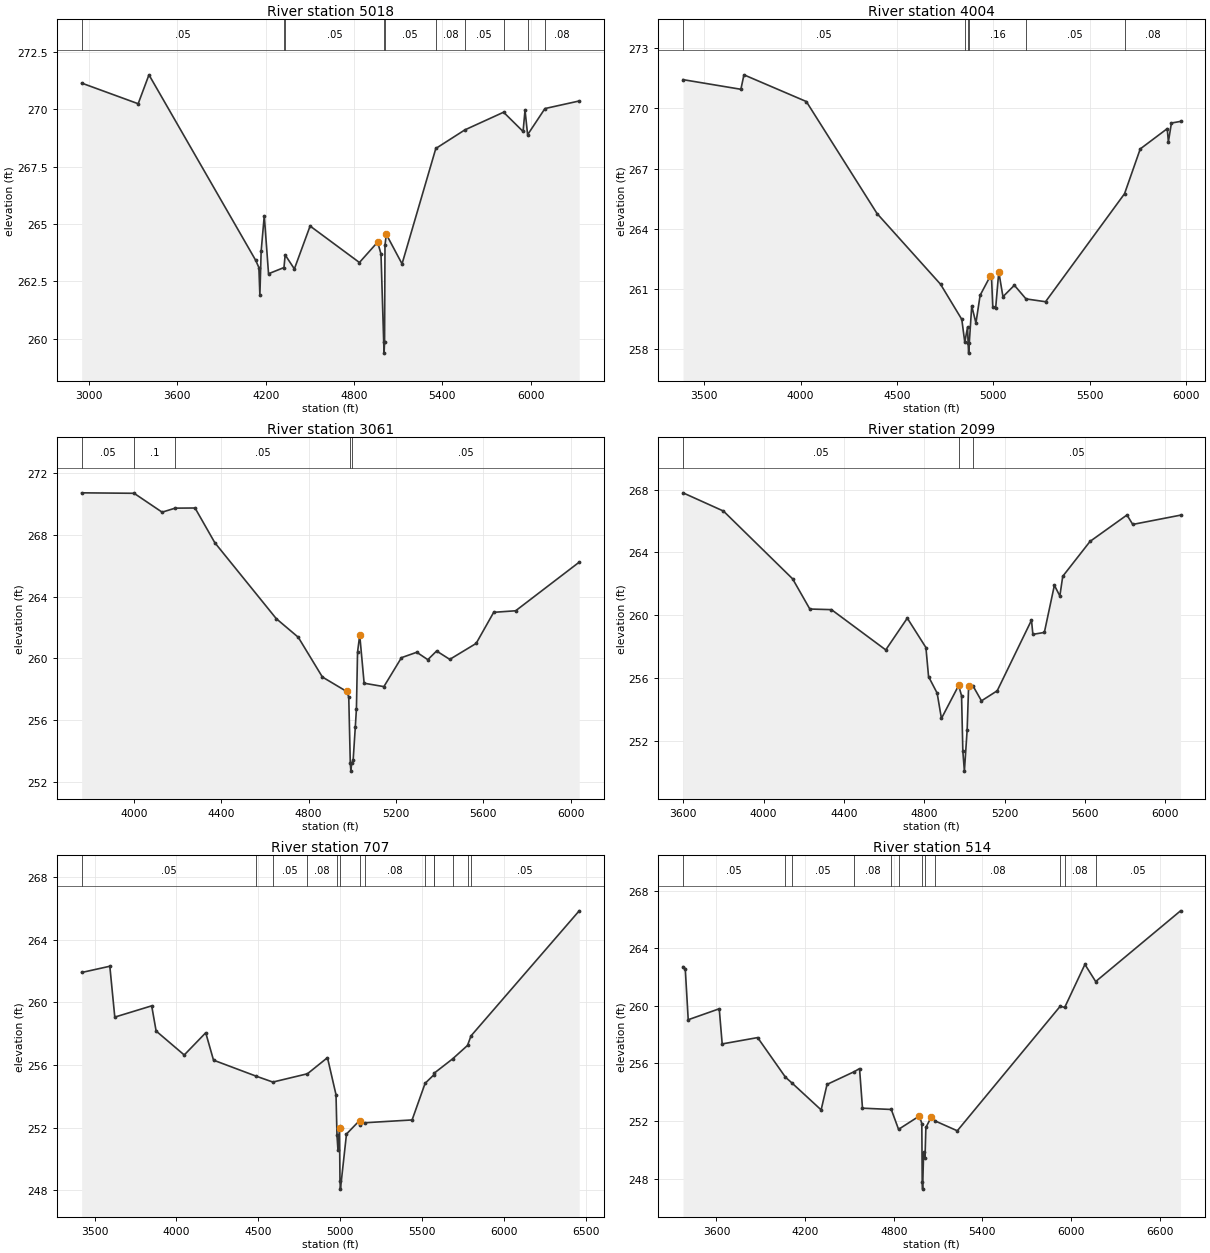
Type RM Length L Ch R = 1 ,5018    ,1014,1014,1014
BEGIN DESCRIPTION:
Mapping XS 6994431b
END DESCRIPTION:
XS GIS Cut Line= 2
      3695968.82     10569298.55      3693095.54     10567519.03
#Sta/Elev= 30
  2949.6  271.14  3333.4  270.24  3406.7   271.5  4132.2  263.41  4153.4   263.1
  4160.2  261.89  4168.8  263.81    4190  265.36    4219  262.83  4323.9   263.1
    4332  263.65  4394.5  263.04  4501.3  264.91  4836.4  263.32  4960.1  264.21
  4982.9  263.69  5001.2  259.87  5003.9  259.37  5007.2  259.87  5010.1  264.07
  5018.9  264.55  5125.9  263.26  5355.3  268.29  5552.6   269.1  5815.7  269.87
  5948.1  269.03  5961.3  269.96  5978.9  268.89  6096.6  270.03  6329.3  270.36
#Mann= 10 ,-1 , 0
  2949.6     .05       0  4323.9     .07       0    4332     .05       0
  5001.2     .03       0  5007.2     .05       0  5355.3     .08       0
  5552.6     .05       0  5815.7     .08       0  5978.9     .05       0
  6096.6     .08       0
Bank Sta=4960.1,5018.9
XS Rating Curve= 0 ,0
Exp/Cntr=0.3,0.1

Type RM Length L Ch R = 1 ,4004    ,943,943,943
BEGIN DESCRIPTION:
Mapping XS a8f09146
END DESCRIPTION:
XS GIS Cut Line= 2
      3696239.41     10568540.72      3693991.12     10567273.35
#Sta/Elev= 30
  3389.8  271.43    3690  270.95  3705.9  271.67  4029.5  270.34  4396.5  264.76
  4725.8  261.24    4836  259.49  4851.5  258.35    4866  259.11  4868.7  258.31
  4871.5  257.81  4874.7  258.31  4887.6  260.16  4909.3  259.31    4931  260.69
  4984.5  261.66  4990.2  261.59  4996.7  260.12  5011.9  260.08  5027.8  261.86
  5049.5  260.62  5108.7  261.19  5169.1  260.51  5270.5  260.37  5680.3  265.75
  5761.7  267.98  5901.8  268.99  5907.6  268.33  5923.5  269.27  5970.7  269.35
#Mann= 6 ,-1 , 0
  3389.8     .05       0  4851.5     .16       0  4868.7     .07       0
  4874.7     .16       0  5169.1     .05       0  5680.3     .08       0
Bank Sta=4984.5,5027.8
XS Rating Curve= 0 ,0
Exp/Cntr=0.3,0.1

Type RM Length L Ch R = 1 ,3061    ,962,962,962
BEGIN DESCRIPTION:
Mapping XS 72f012d0
END DESCRIPTION:
XS GIS Cut Line= 2
      3696525.86      10567299.4      3694260.26     10567056.35
#Sta/Elev= 30
  3760.6   270.7  4000.7  270.67    4129  269.45  4188.8  269.71  4279.8  269.72
  4370.3  267.48  4651.9  262.57  4752.5  261.37  4863.1   258.8  4973.8  257.87
  4983.8  257.51  4990.9  253.22  4993.6  252.72  4996.9  253.22  5003.9  253.42
  5013.9  255.59  5018.9  256.73  5024.1  260.41  5034.1  261.51  5054.2   258.4
  5144.7  258.18  5225.2  260.05  5295.3   260.4  5345.9  259.92  5386.1  260.48
  5446.5  259.94  5567.2  260.97  5647.6  262.98  5748.2  263.08  6039.2  266.22
#Mann= 5 ,-1 , 0
  3760.6     .05       0  4000.7      .1       0  4188.8     .05       0
  4990.9     .03       0  4996.9     .05       0
Bank Sta=4973.8,5034.1
XS Rating Curve= 0 ,0
Exp/Cntr=0.3,0.1

Type RM Length L Ch R = 1 ,2099    ,1392,1392,1392
BEGIN DESCRIPTION:
Mapping XS 984d24a8
END DESCRIPTION:
XS GIS Cut Line= 3
      3696326.22     10566014.68      3695666.49     10565867.11
      3694260.46     10566995.41
#Sta/Elev= 30
  3598.1  267.79  3799.6  266.63  4144.2  262.32  4229.9   260.4  4337.8  260.36
  4608.2   257.8  4715.5  259.82  4808.3  257.95  4821.5   256.1  4864.3  255.05
  4885.6  253.44  4971.5  255.54  4985.9  254.88  4992.3  251.36    5000  250.09
  5013.8  252.72  5021.1  255.52  5041.9  255.53  5085.1  254.56  5163.5   255.2
  5334.3  259.69  5341.2  258.79  5398.4  258.91  5448.4  261.91  5475.6  261.23
    5490  262.48    5626   264.7    5810  266.38  5838.8  265.78  6076.9  266.37
#Mann= 3 ,-1 , 0
  3598.1     .05       0  4971.5     .03       0  5041.9     .05       0
Bank Sta=4971.5,5021.1
XS Rating Curve= 0 ,0
Exp/Cntr=0.3,0.1

Type RM Length L Ch R = 1 ,707     ,193,193,193
BEGIN DESCRIPTION:
Mapping XS 3316a50a
END DESCRIPTION:
XS GIS Cut Line= 3
      3696579.95      10564899.4      3695202.34     10565081.69
      3694342.11     10566484.88
#Sta/Elev= 30
  3421.6  261.91  3593.4  262.31  3623.7  259.06  3848.8  259.78  3875.9  258.17
  4047.4  256.64  4178.5  258.06    4226  256.31  4487.9  255.28  4588.2  254.91
  4799.1  255.44  4921.3  256.47  4973.4   254.1  4979.3  251.51  4985.4  250.55
  4994.7  251.96  4997.6  248.57  5000.4  248.07  5037.3  251.59  5116.7  252.45
  5122.7  252.19  5147.5  252.31  5437.6  252.49    5517  254.83  5572.2  255.39
  5573.8  255.49  5684.6  256.39  5775.7  257.25    5797  257.86  6457.1  265.85
#Mann= 14 ,-1 , 0
  3421.6     .05       0  4487.9     .08       0  4588.2     .05       0
  4799.1     .08       0  4979.3     .07       0  5000.4     .05       0
  5122.7     .12       0  5147.5     .08       0    5517     .12       0
  5572.2     .05       0  5573.8     .08       0  5684.6     .05       0
  5775.7     .08       0    5797     .05       0
Bank Sta=4994.7,5116.7
XS Rating Curve= 0 ,0
Exp/Cntr=0.3,0.1

Type RM Length L Ch R = 1 ,514     ,0,0,0
BEGIN DESCRIPTION:
TOMS CREEK 1.0
END DESCRIPTION:
XS GIS Cut Line= 3
      3696494.87     10564800.88      3695184.11     10564800.88
      3694194.92     10566605.71
#Sta/Elev= 30
  3373.3  262.71  3388.6  262.56  3408.6  259.03  3618.6  259.79  3638.6  257.35
  3878.6  257.79  4067.1  255.04  4110.9  254.64  4308.6  252.77  4348.6  254.54
  4533.9  255.43  4568.6  255.64  4588.6  252.89  4783.6   252.8  4832.9  251.42
  4974.2  252.35  4990.3  251.82    4993  247.77  4995.7  247.27  5002.6  249.83
    5012  249.45  5017.8  251.55  5055.7   252.3  5081.3     252  5230.6  251.32
  5927.8  259.97  5957.6  259.88  6094.7  262.87  6167.6  261.68  6742.2  266.59
#Mann= 12 ,-1 , 0
  3373.3     .05       0  4067.1      .1       0  4110.9     .05       0
  4533.9     .08       0  4783.6     .12       0  4832.9     .05       0
    4993     .07       0    5012     .05       0  5081.3     .08       0
  5927.8      .1       0  5957.6     .08       0  6167.6     .05       0
Bank Sta=4974.2,5055.7
XS Rating Curve= 0 ,0
Exp/Cntr=0.3,0.1

Chan Stop Cuts=-1
Use User Specified Reach Order=0
Composite Channel Slope=5