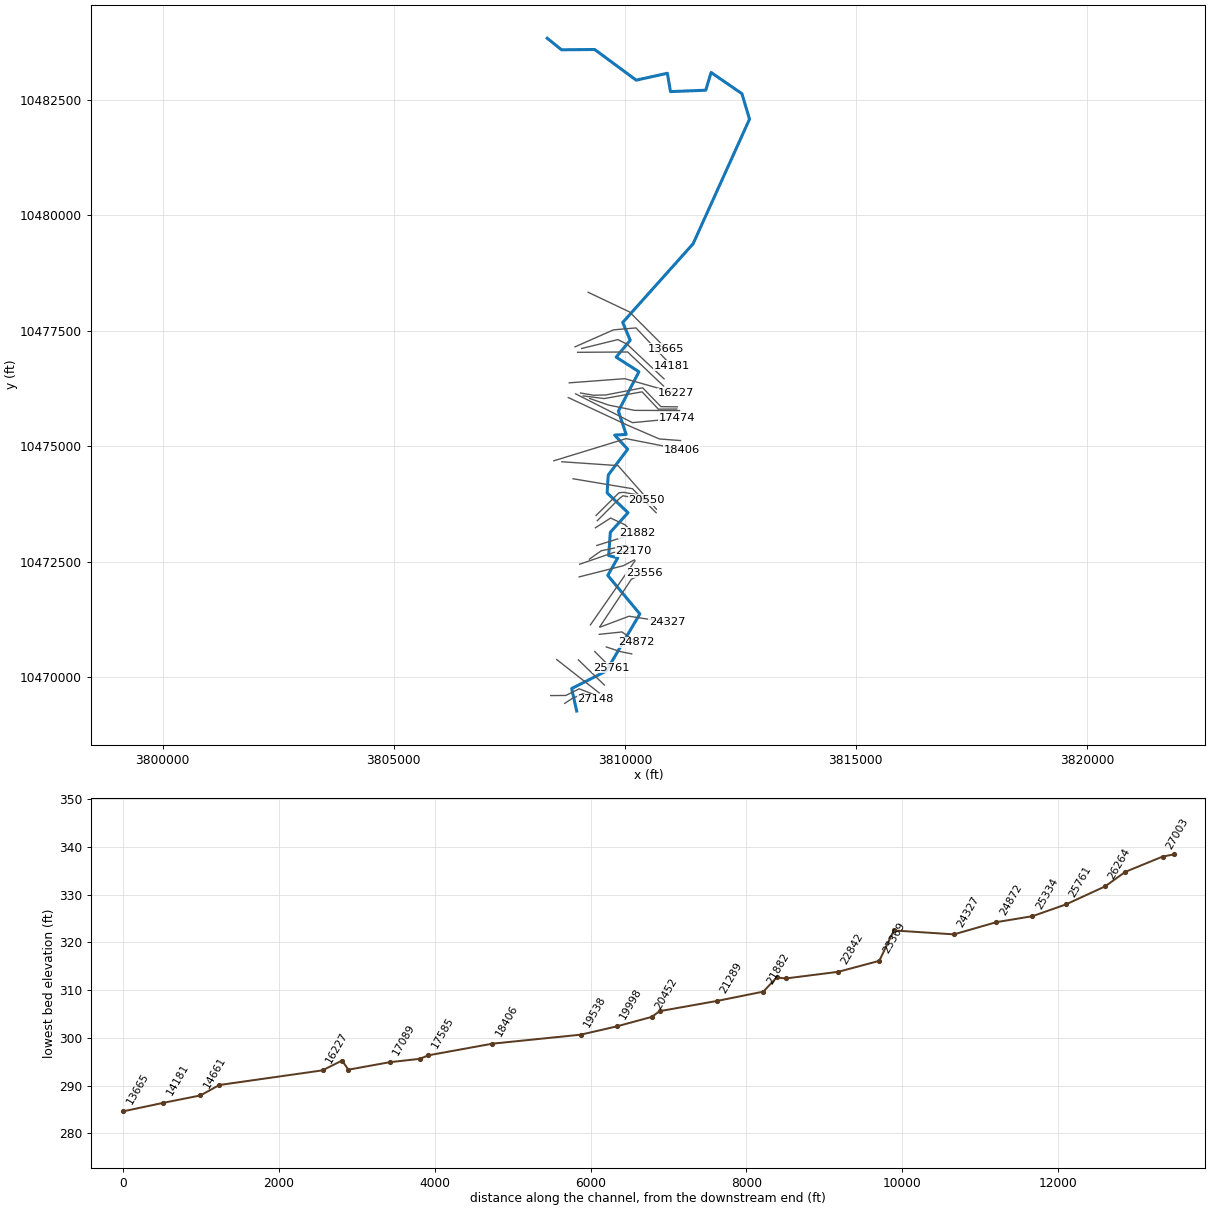
--- TOWN BRANCH CR TRIB.prj (project) ---

Proj Title=TOWN BRANCH CR TRIB Base Level Engineering
Current Plan=p01
Default Exp/Contr=0.3,0.1
English Units
Geom File=g01
Flow File=f01
Plan File=p01
Y Axis Title=Elevation
X Axis Title(PF)=Main Channel Distance
X Axis Title(XS)=Station
BEGIN DESCRIPTION:
TOWN BRANCH CR TRIB
END DESCRIPTION:
DSS Export Rating Curves= 0
DSS Export Rating Curve Sorted= 0
DSS Export Volume Flow Curves= 0
DXF OffsetX= 0
DXF OffsetY= 0
DXF ScaleX= 1
DXF ScaleY= 10

--- TOWN BRANCH CR TRIB.p01 (plan) ---

Plan Title=Multiple Run
Short Identifier=Multiple
Geom File=g01
Flow File=f01
Subcritical Flow
K Sum by GR= 0
Std Step Tol= 0.01
Critical Tol= 0.01
Num of Std Step Trials= 20
Max Error Tol= 0.3
Flow Tol Ratio= 0.001
Split Flow NTrial= 30
Split Flow Tol= 0.02
Split Flow Ratio= 0.02
Log Output Level= 0
Friction Slope Method= 1
Unsteady Friction Slope Method= 2
Unsteady Bridges Friction Slope Method= 1
Parabolic Critical Depth
Global Vel Dist=  1 , 1 , 1
Global Log Level= 0
CheckData=True
Encroach Param= -1, 0, 0, 0
BEGIN DESCRIPTION:
Multiple Run
END DESCRIPTION:

--- TOWN BRANCH CR TRIB.f01 (steady flow) ---

Flow Title=Multiple
Program Version=4.10
Number of Profiles= 7
Profile Names=10-year,25-year,50-year,1pct_min,100-year,1pct_plu,500-year
River Rch & RM=TOWN BRANCH CR T,Reach-1         ,27148
     762    1040    1271    1141    1543    2087    2283
River Rch & RM=TOWN BRANCH CR T,Reach-1         ,19998
     920    1267    1557    1405    1900    2570    2839
River Rch & RM=TOWN BRANCH CR T,Reach-1         ,18406
    1149    1597    1976    1792    2423    3277    3661
River Rch & RM=TOWN BRANCH CR T,Reach-1         ,14902
    1326    1847    2289    2078    2810    3801    4254
Boundary for River Rch & Prof#=TOWN BRANCH CR T,Reach-1         , 1
Up Type= 0
Dn Type= 3
Dn Slope=0.0033
Boundary for River Rch & Prof#=TOWN BRANCH CR T,Reach-1         , 2
Up Type= 0
Dn Type= 3
Dn Slope=0.0033
Boundary for River Rch & Prof#=TOWN BRANCH CR T,Reach-1         , 3
Up Type= 0
Dn Type= 3
Dn Slope=0.0033
Boundary for River Rch & Prof#=TOWN BRANCH CR T,Reach-1         , 4
Up Type= 0
Dn Type= 3
Dn Slope=0.0033
Boundary for River Rch & Prof#=TOWN BRANCH CR T,Reach-1         , 5
Up Type= 0
Dn Type= 3
Dn Slope=0.0033
Boundary for River Rch & Prof#=TOWN BRANCH CR T,Reach-1         , 6
Up Type= 0
Dn Type= 3
Dn Slope=0.0033
Boundary for River Rch & Prof#=TOWN BRANCH CR T,Reach-1         , 7
Up Type= 0
Dn Type= 3
Dn Slope=0.0033
DSS Import GetInterval= 0
DSS Import GetPeak= 0
DSS Import FillOption= 0

--- TOWN BRANCH CR TRIB.g01 (geometry) ---

Geom Title=Existing Conditions
Program Version=4.10

River Reach=TOWN BRANCH CR T,Reach-1
Reach XY= 30
      3808957.88      10469273.5      3808849.61     10469760.19
      3809599.25       10470140.      3810324.75       10471375.
        3809631.       10472208.       3809847.5       10472589.
      3809650.75       10472637.      3809686.75       10473141.
      3810069.75       10473565.        3809617.       10473994.
        3809641.       10474380.       3810062.5       10474938.
        3809780.       10475244.        3810028.       10475259.
      3809861.25       10475763.        3810306.       10476614.
       3809812.5       10476931.        3810117.       10477296.
      3809954.25       10477681.        3811478.       10479384.
       3812698.5       10482080.      3812534.65     10482630.98
       3811867.5       10483090.      3811751.25       10482706.
       3810988.5       10482676.      3810920.75       10483073.
      3810246.25       10482924.      3809348.25       10483587.
        3808629.       10483581.      3808320.25       10483831.

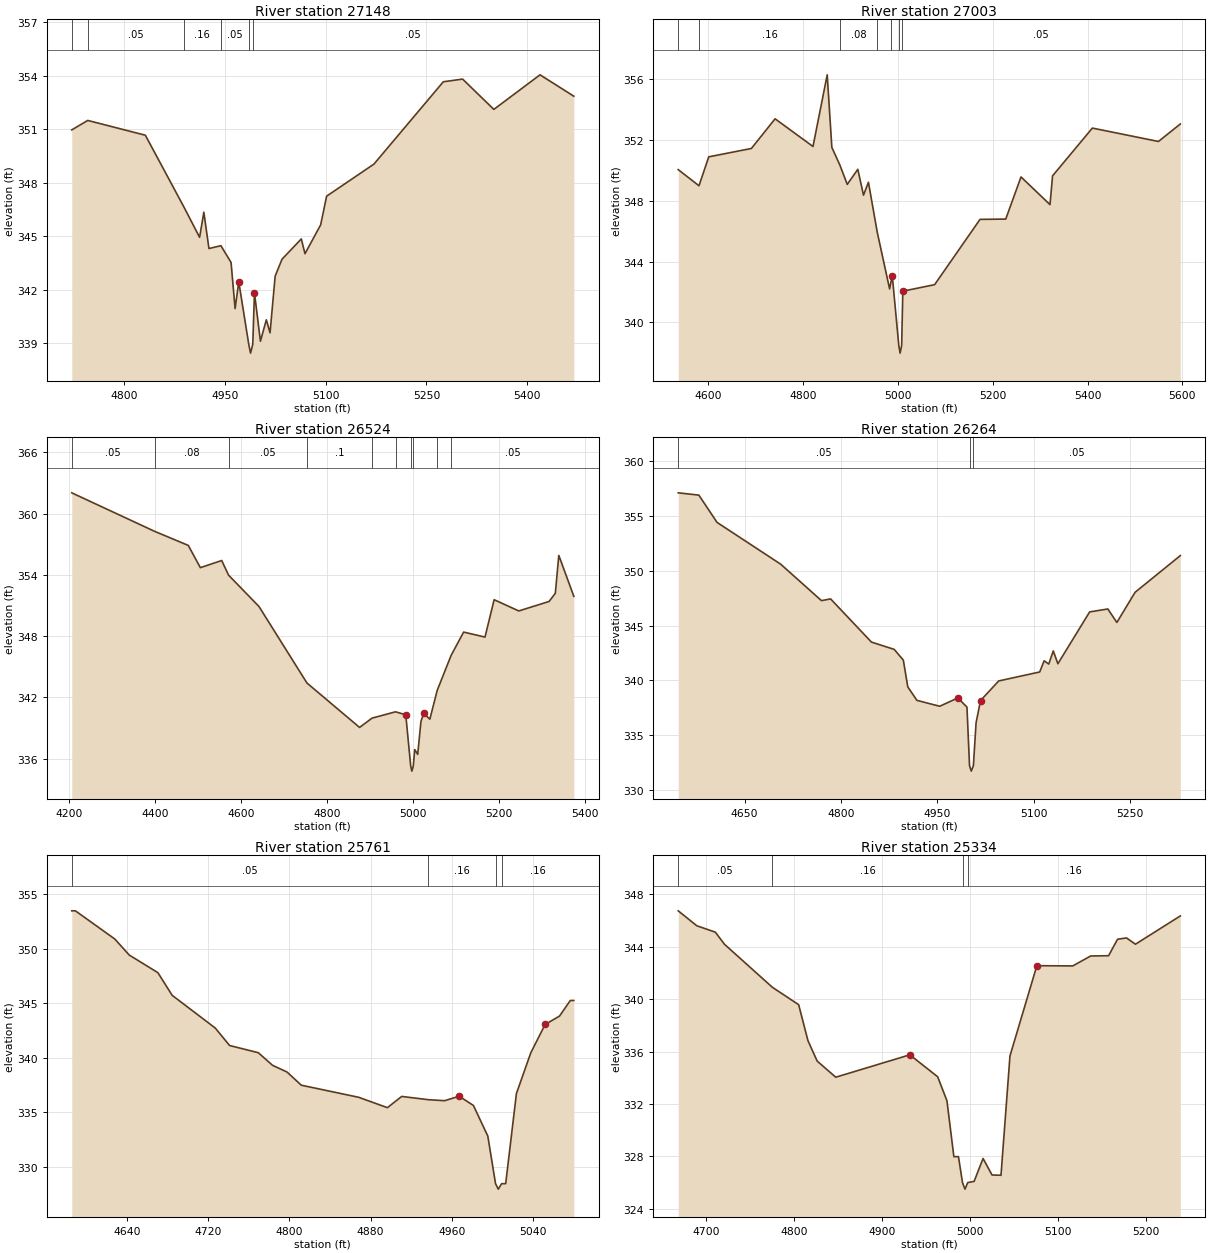
Type RM Length L Ch R = 1 ,27148   ,145,145,145
BEGIN DESCRIPTION:
TOWN BRANCH CR TRIB 32.0
END DESCRIPTION:
XS GIS Cut Line= 4
      3808698.07     10469438.75      3808859.54     10469544.66
      3809093.92     10469648.83      3809365.55     10469527.71
#Sta/Elev= 30
  4722.4  350.96  4746.2  351.49  4831.9  350.66    4889  346.65  4912.6  344.93
  4918.9  346.34  4926.5   344.3  4944.3  344.46  4959.4  343.52  4965.4  340.93
  4970.9  342.43  4985.7  338.93  4988.4  338.43  4991.7  338.93  4994.2  341.82
  5003.1   339.1  5011.9   340.3  5017.4  339.57    5025  342.75  5035.2   343.7
  5063.9  344.84  5069.4  344.01  5092.7  345.63  5101.6  347.24    5172  349.04
  5275.2  353.66  5303.9  353.81  5350.4  352.11  5419.1  354.05  5469.4  352.85
#Mann= 6 ,-1 , 0
  4722.4     .16       0  4746.2     .05       0    4889     .16       0
  4944.3     .05       0  4985.7     .04       0  4991.7     .05       0
Bank Sta=4970.9,4994.2
XS Rating Curve= 0 ,0
Exp/Cntr=0.3,0.1

Type RM Length L Ch R = 1 ,27003   ,479,479,479
BEGIN DESCRIPTION:
TOWN BRANCH CR TRIB 31.0
END DESCRIPTION:
XS GIS Cut Line= 4
      3808395.21      10469608.1      3808724.13     10469610.63
      3809012.32     10469754.73      3809392.52     10469605.43
#Sta/Elev= 30
  4536.2  350.04    4580  348.98  4600.6  350.88  4690.6  351.43  4740.6  353.38
  4820.6  351.56  4850.6  356.27  4860.4   351.5  4877.6  350.32  4892.9  349.07
  4915.2  350.06  4927.2  348.36  4937.6  349.21  4956.3  345.91  4982.3   342.2
    4986  342.78  4987.9  343.08  5001.7  338.48  5004.4  337.98  5007.7  338.48
  5010.2  342.05  5077.3  342.48  5173.1  346.77  5227.4  346.79  5259.6  349.56
  5320.8  347.74  5326.2  349.63  5410.2  352.77  5549.7  351.89  5595.8  353.04
#Mann= 7 ,-1 , 0
  4536.2     .05       0    4580     .16       0  4877.6     .08       0
  4956.3     .16       0    4986     .05       0  5001.7     .03       0
  5007.7     .05       0
Bank Sta=4987.9,5010.2
XS Rating Curve= 0 ,0
Exp/Cntr=0.3,0.1

Type RM Length L Ch R = 1 ,26524   ,260,260,260
BEGIN DESCRIPTION:
Mapping XS 06073c59
END DESCRIPTION:
XS GIS Cut Line= 2
      3808526.24     10470387.69       3809445.5     10469666.16
#Sta/Elev= 30
  4206.1  362.03  4398.8  358.26  4477.3  356.88  4505.4   354.7  4555.1   355.4
    4571  353.97  4641.8   350.9  4753.5   343.4    4876  339.05    4905  339.96
  4959.6  340.58  4983.5  340.29    4995  335.27  4997.7  334.77    5001  335.27
  5004.3  336.88  5011.3  336.41  5018.8  339.63  5025.1  340.42  5039.6  339.86
  5056.6  342.67  5089.1  346.11  5118.2  348.39  5167.9   347.9  5189.2  351.56
  5246.6  350.46  5317.1  351.39  5331.6  352.19  5339.7   355.9  5374.7  351.89
#Mann= 10 ,-1 , 0
  4206.1     .05       0  4398.8     .08       0    4571     .05       0
  4753.5      .1       0    4905     .16       0  4959.6     .05       0
    4995     .03       0    5001     .05       0  5056.6     .08       0
  5089.1     .05       0
Bank Sta=4983.5,5025.1
XS Rating Curve= 0 ,0
Exp/Cntr=0.3,0.1

Type RM Length L Ch R = 1 ,26264   ,503,503,503
BEGIN DESCRIPTION:
TOWN BRANCH CR TRIB 30.0
END DESCRIPTION:
XS GIS Cut Line= 2
      3808994.95     10470380.78        3809556.     10469837.04
#Sta/Elev= 30
  4546.6  357.12  4578.7  356.91    4607  354.42    4706  350.61  4769.5  347.28
  4783.7  347.44  4847.2   343.5  4882.7  342.83  4896.9  341.85  4903.8  339.41
    4918  338.18  4953.5  337.64  4981.8   338.4  4995.9  337.56  4999.9  332.22
  5002.6  331.72  5005.9  332.22  5010.1  336.14    5017  338.16  5045.3  339.95
  5109.1  340.77    5116  341.79  5123.2  341.49  5130.2  342.69  5137.4  341.52
  5186.8  346.25  5215.1  346.52  5229.2  345.29  5257.5  348.04  5327.9  351.39
#Mann= 3 ,-1 , 0
  4546.6     .05       0  4999.9     .03       0  5005.9     .05       0
Bank Sta=4981.8,5017
XS Rating Curve= 0 ,0
Exp/Cntr=0.3,0.1

Type RM Length L Ch R = 1 ,25761   ,427,427,427
BEGIN DESCRIPTION:
TOWN BRANCH CR TRIB 29.0
END DESCRIPTION:
XS GIS Cut Line= 3
      3809349.58     10470560.22      3809649.61     10470260.19
       3809699.6      10470210.2
#Sta/Elev= 30
  4585.4  353.46    4589  353.46  4627.9  350.87    4642  349.41  4670.3  347.79
  4684.4  345.71  4726.9  342.71    4741  341.11  4769.3  340.45  4783.4  339.29
  4797.6  338.68  4811.7  337.47  4868.3  336.36  4896.6  335.41  4910.7  336.44
  4937.1  336.14  4953.1  336.05  4967.3  336.46  4981.4  335.61  4995.6   332.8
  5003.2  328.44  5005.9  327.94  5009.2  328.44  5013.2  328.44  5023.8  336.71
    5038  340.45  5052.1  343.04  5066.3  343.81  5076.9  345.24  5080.4  345.24
#Mann= 4 ,-1 , 0
  4585.4     .05       0  4937.1     .16       0  5003.2     .07       0
  5009.2     .16       0
Bank Sta=4967.3,5052.1
XS Rating Curve= 0 ,0
Exp/Cntr=0.3,0.1

Type RM Length L Ch R = 1 ,25334   ,462,462,462
BEGIN DESCRIPTION:
TOWN BRANCH CR TRIB 28.0
END DESCRIPTION:
XS GIS Cut Line= 3
       3809599.6     10470660.19      3809899.61     10470560.19
      3810149.62     10470510.19
#Sta/Elev= 30
  4668.4  346.75  4689.5  345.61  4710.6  345.12  4721.1  344.19  4775.5  340.91
  4805.4  339.58    4816  336.83  4826.5  335.27  4847.6  334.04  4931.9  335.75
  4963.6  334.07  4974.1  332.24    4982  327.97  4987.2  327.97  4991.8  325.99
  4994.6  325.49  4997.8  325.99    5005  326.08  5015.2  327.83  5025.4  326.57
  5035.6  326.55  5045.8  335.66  5076.4  342.56  5117.2  342.54  5137.6   343.3
    5158  343.32  5168.2  344.58  5178.4  344.68  5188.6   344.2  5239.6  346.36
#Mann= 4 ,-1 , 0
  4668.4     .05       0  4775.5     .16       0  4991.8     .07       0
  4997.8     .16       0
Bank Sta=4931.9,5076.4
XS Rating Curve= 0 ,0
Exp/Cntr=0.3,0.1

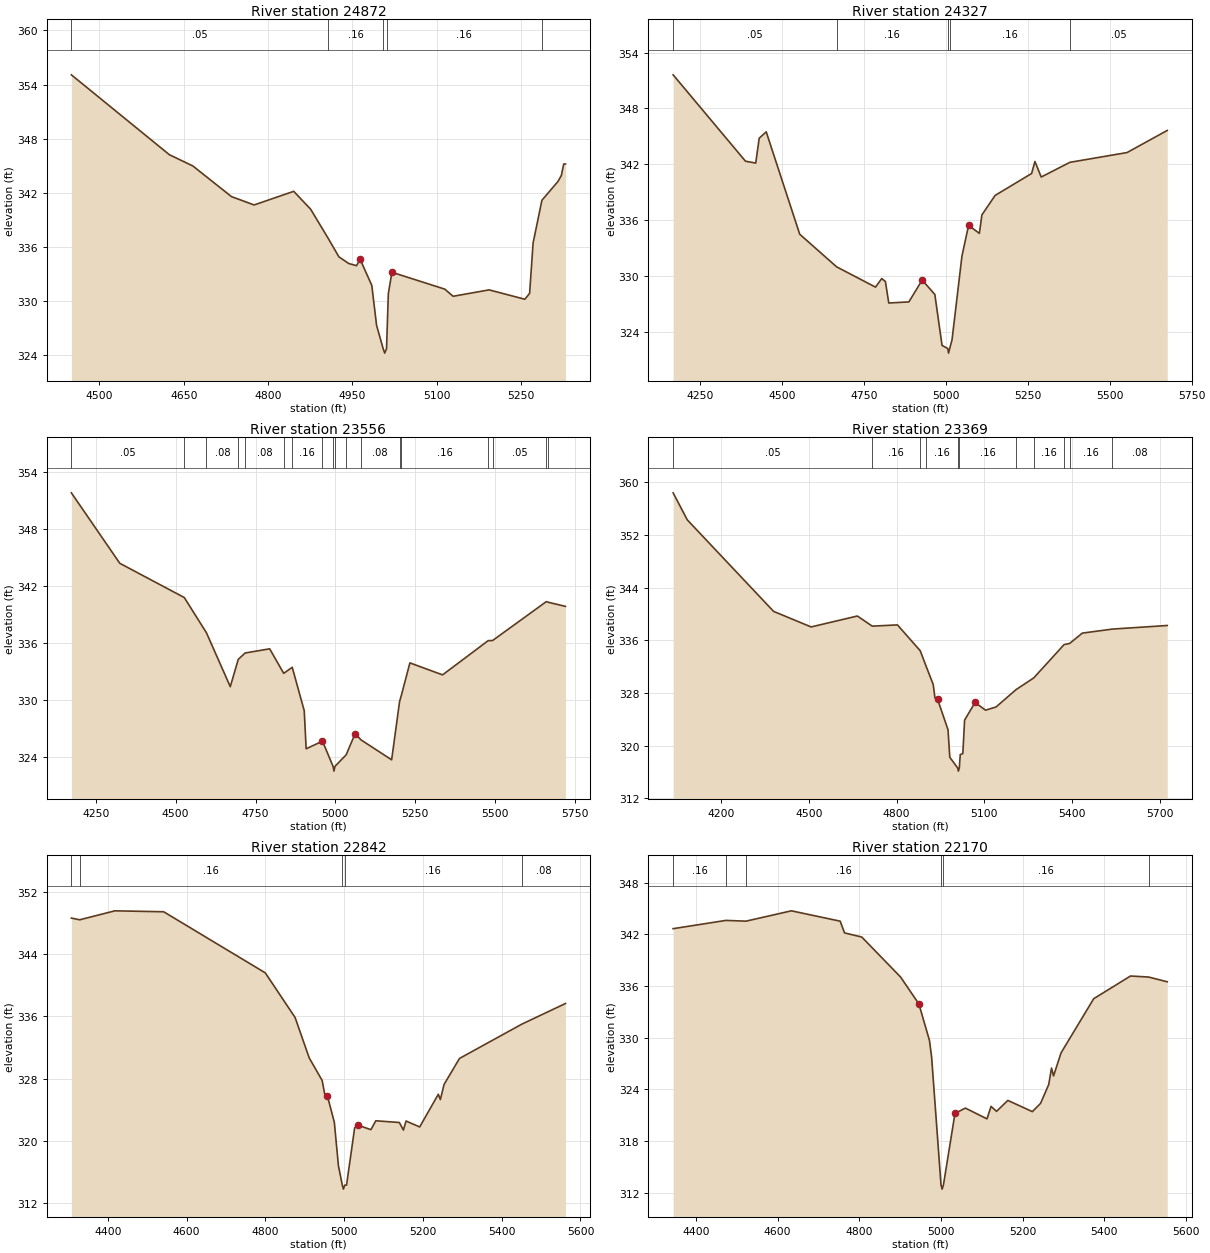
Type RM Length L Ch R = 1 ,24872   ,545,545,545
BEGIN DESCRIPTION:
TOWN BRANCH CR TRIB 41.0
END DESCRIPTION:
XS GIS Cut Line= 3
      3809446.32     10470932.85       3809939.4     10470984.94
      3810249.62     10470760.18
#Sta/Elev= 30
  4450.2  355.08  4624.5  346.23  4666.3  344.98  4735.1  341.58  4775.3  340.66
  4845.7  342.17  4875.8  340.19  4907.5  336.91  4926.1  334.91  4943.6  334.17
  4957.5  333.93  4963.7  334.66  4984.6  331.74  4993.1  327.32  5004.8  324.74
  5007.6  324.24  5010.8  324.74    5014  330.83  5020.4   333.2  5114.5  331.33
  5129.2  330.54  5193.3  331.25  5256.8  330.21  5265.3  330.86  5271.5  336.44
  5287.2  341.18  5315.6  343.25  5321.7  343.92    5326   345.2  5329.1   345.2
#Mann= 5 ,-1 , 0
  4450.2     .05       0  4907.5     .16       0  5004.8     .07       0
  5010.8     .16       0  5287.2      .1       0
Bank Sta=4963.7,5020.4
XS Rating Curve= 0 ,0
Exp/Cntr=0.3,0.1

Type RM Length L Ch R = 1 ,24327   ,771,771,771
BEGIN DESCRIPTION:
TOWN BRANCH CR TRIB 40.0
END DESCRIPTION:
XS GIS Cut Line= 3
      3809463.74     10471089.12      3810092.18     10471325.21
      3810918.53     10471196.75
#Sta/Elev= 30
  4167.9  351.61  4388.7  342.32  4419.9  342.12  4430.5  344.79  4451.9  345.48
  4554.1  334.47  4666.7  330.96  4785.3  328.78  4804.4   329.7  4815.6  329.38
  4825.8  327.07  4887.2  327.19  4927.7  329.54  4966.4  327.99  4988.4  322.51
  5005.7  322.18  5008.4  321.68  5011.7  322.18  5018.8   323.1  5049.1  332.12
  5069.4  335.42  5102.3  334.56  5109.9  336.54  5150.3  338.64  5261.7     341
  5271.8  342.29    5291  340.62  5378.5   342.2  5552.8  343.25  5675.5  345.63
#Mann= 5 ,-1 , 0
  4167.9     .05       0  4666.7     .16       0  5005.7     .07       0
  5011.7     .16       0  5378.5     .05       0
Bank Sta=4927.7,5069.4
XS Rating Curve= 0 ,0
Exp/Cntr=0.3,0.1

Type RM Length L Ch R = 1 ,23556   ,187,187,187
BEGIN DESCRIPTION:
TOWN BRANCH CR TRIB 39.0
END DESCRIPTION:
XS GIS Cut Line= 3
      3809460.25     10471099.54      3810140.79     10472123.83
      3810422.07     10472269.68
#Sta/Elev= 30
  4173.5  351.76  4325.1  344.35    4527  340.75  4596.4  337.04  4670.9  331.38
  4695.9  334.25  4717.3  334.92  4794.2  335.36  4838.2  332.78  4864.8  333.42
  4902.4  328.85  4908.4  324.85    4959  325.64  4959.5  325.66  4992.6     323
  4995.4   322.5  4998.6     323  5033.7  324.22  5061.8  326.45  5079.9  325.79
    5176  323.69  5200.8  329.81  5206.7  330.51  5233.1  333.88  5335.4  332.62
  5478.2  336.22  5491.9  336.23  5660.1  340.32  5666.8  340.25  5720.1  339.82
#Mann= 18 ,-1 , 0
  4173.5     .05       0    4527     .16       0  4596.4     .08       0
  4695.9     .16       0  4717.3     .08       0  4838.2     .05       0
  4864.8     .16       0    4959     .08       0  4992.6     .07       0
  4998.6     .08       0  5033.7     .16       0  5079.9     .08       0
  5200.8     .05       0  5206.7     .16       0  5478.2     .08       0
  5491.9     .05       0  5660.1     .16       0  5666.8     .05       0
Bank Sta=4959.5,5061.8
XS Rating Curve= 0 ,0
Exp/Cntr=0.3,0.1

Type RM Length L Ch R = 1 ,23369   ,527,527,527
BEGIN DESCRIPTION:
TOWN BRANCH CR TRIB 38.0
END DESCRIPTION:
XS GIS Cut Line= 2
      3809255.35     10471137.68      3810220.67     10472523.15
#Sta/Elev= 30
  4036.4   358.4  4084.8  354.29  4379.8  340.39    4508  338.03    4666  339.69
  4716.8  338.15    4803  338.34  4880.7  334.42  4900.2  332.15  4925.2  329.29
  4931.2  327.24    4940  327.06  4975.8  322.41  4981.9  318.23  5008.5  316.63
  5011.3  316.13  5014.5  316.63  5017.6  318.65  5026.4  318.79  5032.5  323.88
  5068.2  326.56    5104  325.39  5139.8  325.87  5208.6  328.52  5268.8  330.29
  5372.5  335.35  5391.7  335.53  5434.7  337.09  5536.5   337.7    5725  338.25
#Mann= 11 ,-1 , 0
  4036.4     .05       0  4716.8     .16       0  4880.7     .05       0
  4900.2     .16       0  5008.5     .07       0  5014.5     .16       0
  5208.6     .05       0  5268.8     .16       0  5372.5     .05       0
  5391.7     .16       0  5536.5     .08       0
Bank Sta=4940,5068.2
XS Rating Curve= 0 ,0
Exp/Cntr=0.3,0.1

Type RM Length L Ch R = 1 ,22842   ,672,672,672
BEGIN DESCRIPTION:
TOWN BRANCH CR TRIB 37.0
END DESCRIPTION:
XS GIS Cut Line= 3
      3809012.36     10472175.92      3809970.65     10472418.96
      3810205.72     10472543.41
#Sta/Elev= 30
  4307.3  348.61  4328.4  348.39  4417.9  349.54  4541.7  349.42  4799.7  341.58
  4875.4  335.85  4911.2  330.67  4944.1  327.77  4952.2  325.58  4957.4  325.78
    4975  322.41  4985.4  316.83  4995.3  314.33  4998.1  313.83  5001.3  314.33
    5006  314.35  5026.6  321.69  5034.1  322.05  5067.9  321.46  5080.3   322.6
  5140.1  322.38  5150.4  321.41  5157.1  322.57  5191.7  321.81    5239     326
  5244.2  325.32  5253.6  327.26  5292.8   330.6  5451.5  335.01  5561.9  337.65
#Mann= 5 ,-1 , 0
  4307.3     .05       0  4328.4     .16       0  4995.3     .07       0
  5001.3     .16       0  5451.5     .08       0
Bank Sta=4957.4,5034.1
XS Rating Curve= 0 ,0
Exp/Cntr=0.3,0.1

Type RM Length L Ch R = 1 ,22170   ,118,118,118
BEGIN DESCRIPTION:
TOWN BRANCH CR TRIB 36.0
END DESCRIPTION:
XS GIS Cut Line= 3
       3809022.7      10472450.2      3809769.26     10472707.16
      3810189.41     10472731.46
#Sta/Elev= 30
  4343.9  342.65  4473.3  343.61  4522.2  343.52  4633.6  344.72  4753.1  343.52
  4763.8  342.16    4806  341.68  4901.1  337.04  4945.9  333.92  4971.8  329.69
  4977.1  327.76  5000.1  312.94  5002.8  312.44  5006.1  312.94  5034.3  321.22
  5059.8  321.84  5112.7  320.59  5122.7  322.04  5136.1  321.46  5163.8  322.73
  5223.9  321.43    5244  322.39    5264  324.58  5270.8  326.48  5275.8  325.57
  5294.1  328.24  5374.2  334.53  5464.3  337.16  5508.6  337.04  5554.3  336.49
#Mann= 6 ,-1 , 0
  4343.9     .16       0  4473.3     .08       0  4522.2     .16       0
  5000.1     .07       0  5006.1     .16       0  5508.6      .1       0
Bank Sta=4945.9,5034.3
XS Rating Curve= 0 ,0
Exp/Cntr=0.3,0.1

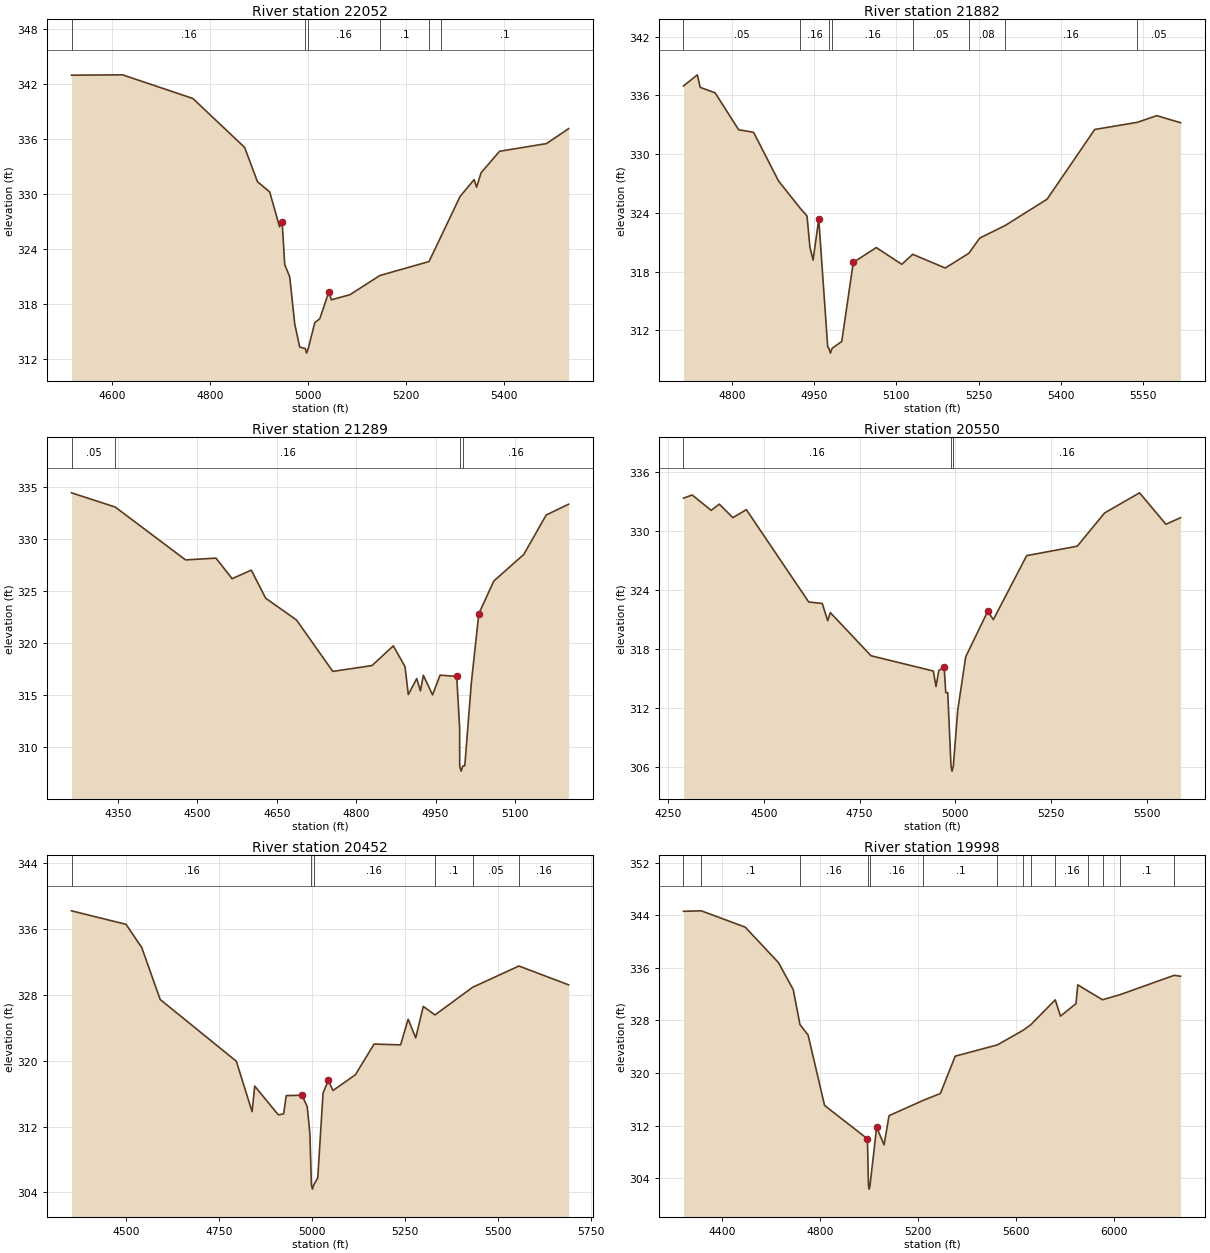
Type RM Length L Ch R = 1 ,22052   ,170,170,170
BEGIN DESCRIPTION:
Mapping XS 17161bd0
END DESCRIPTION:
XS GIS Cut Line= 4
      3809234.51      10472561.3      3809491.49     10472741.88
      3809994.96     10472846.05       3810175.5     10472804.38
#Sta/Elev= 30
  4518.1  342.97  4622.1  343.01  4765.5  340.43  4871.1  335.09  4897.2  331.35
  4922.2  330.23  4942.3  326.42  4947.5     327  4952.8  322.32    4963  320.96
  4973.2  315.83  4983.4  313.31  4994.7  313.15  4997.4  312.65  5000.7  313.15
  5014.1  315.97  5024.3  316.41  5042.8  319.34  5047.9  318.47  5085.6  319.02
  5146.9  321.12    5247  322.64  5270.4  325.26  5310.2  329.73  5338.9  331.58
    5344  330.75  5353.2  332.33  5390.8  334.67  5486.6  335.51  5531.6  337.14
#Mann= 6 ,-1 , 0
  4518.1     .16       0  4994.7     .07       0  5000.7     .16       0
  5146.9      .1       0    5247     .16       0  5270.4      .1       0
Bank Sta=4947.5,5042.8
XS Rating Curve= 0 ,0
Exp/Cntr=0.3,0.1

Type RM Length L Ch R = 1 ,21882   ,593,593,593
BEGIN DESCRIPTION:
TOWN BRANCH CR TRIB 35.0
END DESCRIPTION:
XS GIS Cut Line= 2
      3809394.25     10472856.46      3810258.83     10473127.29
#Sta/Elev= 30
  4711.9  336.96  4737.2   338.1  4742.4  336.82  4769.6  336.26  4812.5  332.49
  4839.7  332.23  4885.2  327.26  4924.6  324.48  4937.1  323.68  4942.3  320.55
  4948.1  319.18  4958.5  323.35  4974.8  310.32    4977  310.18  4979.7  309.68
    4983  310.18  5000.4  310.87  5021.4  318.94  5063.3  320.46  5109.8  318.75
  5129.7  319.77  5189.1  318.37  5232.1  319.88  5251.9  321.43  5298.5  322.72
  5374.6   325.4  5461.5  332.52  5539.2  333.25  5574.5  333.93  5617.9  333.21
#Mann= 8 ,-1 , 0
  4711.9     .05       0  4924.6     .16       0    4977     .07       0
    4983     .16       0  5129.7     .05       0  5232.1     .08       0
  5298.5     .16       0  5539.2     .05       0
Bank Sta=4958.5,5021.4
XS Rating Curve= 0 ,0
Exp/Cntr=0.3,0.1

Type RM Length L Ch R = 1 ,21289   ,739,739,739
BEGIN DESCRIPTION:
TOWN BRANCH CR TRIB 34.0
END DESCRIPTION:
XS GIS Cut Line= 4
      3809363.78     10473238.37      3809692.31     10473449.42
      3810007.19     10473302.61       3810149.6      10473160.2
#Sta/Elev= 30
  4262.1  334.41  4344.6  333.05  4477.6  327.98  4535.1  328.15  4565.5  326.18
  4601.8     327  4628.9  324.31  4687.2  322.22  4755.8  317.29  4829.9  317.85
  4870.2  319.74  4892.3  317.74  4898.5  315.07  4914.4   316.6  4921.4  315.42
  4926.9  316.92  4944.3  315.04  4958.5  316.93    4990  316.81  4995.5  311.86
  4995.6  308.23  4998.3  307.73  5001.6  308.23  5005.2  308.23  5017.6  316.19
  5031.7  322.82    5060  325.95  5116.6   328.5    5159  332.28  5201.4  333.32
#Mann= 4 ,-1 , 0
  4262.1     .05       0  4344.6     .16       0  4995.6     .07       0
  5001.6     .16       0
Bank Sta=4990,5031.7
XS Rating Curve= 0 ,0
Exp/Cntr=0.3,0.1

Type RM Length L Ch R = 1 ,20550   ,98,98,98
BEGIN DESCRIPTION:
TOWN BRANCH CR TRIB 33.0
END DESCRIPTION:
XS GIS Cut Line= 4
      3809404.68     10473392.85      3809890.46     10473878.94
      3809959.66     10473931.22      3810474.91      10473838.9
#Sta/Elev= 30
  4290.4  333.31  4313.2  333.63  4362.7  332.07  4383.9   332.7  4419.3  331.33
  4454.6  332.14  4617.3  322.76  4652.6  322.61  4666.8  320.86  4673.8  321.68
  4779.9   317.3  4942.5  315.75  4949.6  314.17  4956.7  315.79  4970.8  316.16
    4975  313.55  4980.2  313.55  4988.7  306.08  4991.4  305.58  4994.7  306.08
  5006.2  311.76  5027.1   317.2  5084.6  321.82  5099.2  320.97  5186.2  327.47
  5318.3  328.43  5389.4   331.8  5480.8  333.85  5549.5  330.66  5587.8  331.32
#Mann= 3 ,-1 , 0
  4290.4     .16       0  4988.7     .07       0  4994.7     .16       0
Bank Sta=4970.8,5084.6
XS Rating Curve= 0 ,0
Exp/Cntr=0.3,0.1

Type RM Length L Ch R = 1 ,20452   ,454,454,454
BEGIN DESCRIPTION:
Mapping XS b47c5a4f
END DESCRIPTION:
XS GIS Cut Line= 4
      3809377.68     10473504.63       3809872.5     10473995.11
      3809976.66     10474005.96      3810504.05     10473906.13
#Sta/Elev= 30
  4352.4  338.23  4499.1  336.59  4541.5  333.76  4591.1  327.45  4796.1  319.94
  4838.5  313.81  4845.6  316.92  4909.2  313.42  4923.4  313.54  4930.5  315.76
  4972.9  315.81    4987   314.4  4994.1  311.13  4998.2  304.89  5000.9  304.39
  5004.2  304.89  5015.3  305.75  5029.5  316.06  5043.6   317.6  5056.3  316.38
  5116.6   318.3    5167  322.03  5238.3  321.93  5258.6  325.05    5279  322.78
  5299.3  326.61  5330.8  325.57  5432.1  328.93  5556.9  331.52  5690.6  329.23
#Mann= 6 ,-1 , 0
  4352.4     .16       0  4998.2     .07       0  5004.2     .16       0
  5330.8      .1       0  5432.1     .05       0  5556.9     .16       0
Bank Sta=4972.9,5043.6
XS Rating Curve= 0 ,0
Exp/Cntr=0.3,0.1

Type RM Length L Ch R = 1 ,19998   ,460,460,460
BEGIN DESCRIPTION:
TOWN BRANCH CR TRIB 24.0
END DESCRIPTION:
XS GIS Cut Line= 3
      3808880.46     10474299.15      3810165.21     10474083.87
      3810678.02     10473564.13
#Sta/Elev= 30
  4241.2  344.59  4314.2  344.66  4493.8  342.18  4629.5   336.8  4690.1  332.69
  4717.6  327.38  4750.8  325.79  4818.3  315.09  4993.5  310.02  4997.8  302.88
  5000.5  302.38  5003.8  302.88  5031.2  311.76  5061.6  309.11  5081.9  313.54
    5222  315.87  5291.8  316.91  5352.5  322.58  5524.6  324.29  5628.7  326.48
  5662.2  327.38  5761.6  331.14  5782.9  328.66  5846.5  330.56  5853.7  333.42
  5894.4  332.49    5955  331.15  6027.2  331.93  6247.8  334.86    6274  334.72
#Mann= 14 ,-1 , 0
  4241.2     .05       0  4314.2      .1       0  4717.6     .16       0
  4997.8     .07       0  5003.8     .16       0    5222      .1       0
  5524.6     .05       0  5628.7      .1       0  5662.2     .05       0
  5761.6     .16       0  5894.4      .1       0    5955     .16       0
  6027.2      .1       0  6247.8     .05       0
Bank Sta=4993.5,5031.2
XS Rating Curve= 0 ,0
Exp/Cntr=0.3,0.1

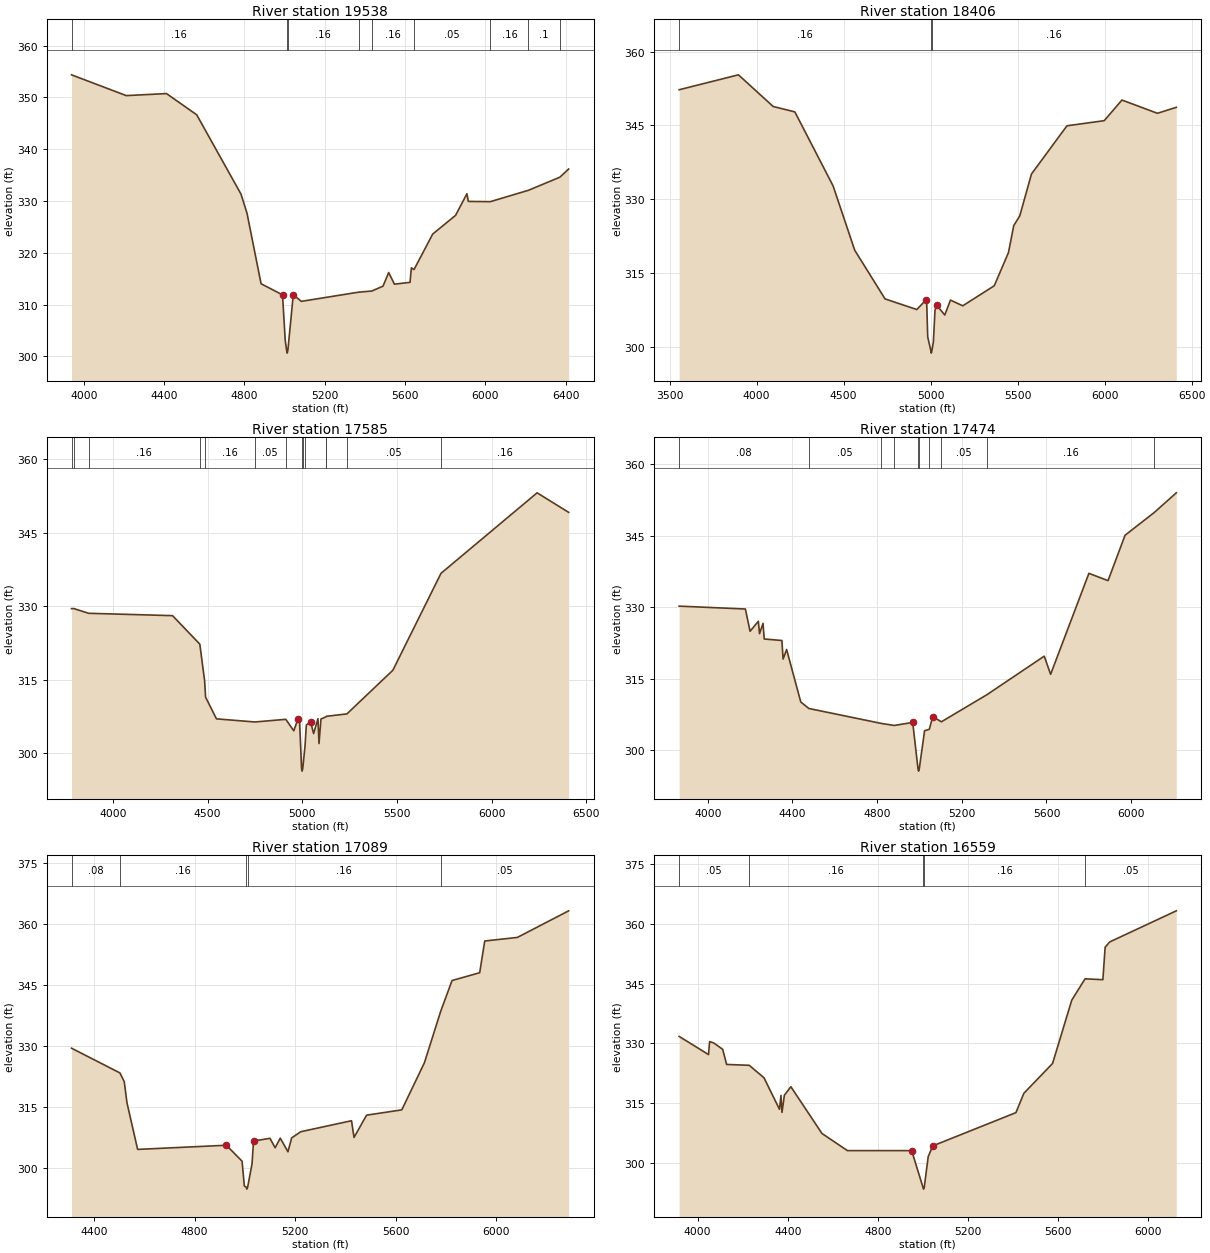
Type RM Length L Ch R = 1 ,19538   ,1132,1132,1132
BEGIN DESCRIPTION:
TOWN BRANCH CR TRIB 23.0
END DESCRIPTION:
XS GIS Cut Line= 3
      3808637.48      10474667.2      3809852.71     10474583.87
      3810685.31     10473640.26
#Sta/Elev= 30
  3939.1  354.36  4211.9  350.35  4412.3  350.74  4562.7  346.65  4783.2  331.35
  4813.3  327.65  4883.4  314.04  4990.2  311.89  5003.7  303.11  5010.7  301.15
  5013.5  300.65  5016.7  301.15  5043.8  311.93  5083.9  310.64  5370.1  312.42
  5434.7  312.63  5490.7  313.57  5519.1   316.2  5547.6  313.96  5625.4  314.31
  5632.1  317.11  5645.3  316.78  5738.3  323.63  5852.1  327.23  5908.9  331.41
  5915.7  329.93  6025.1  329.88  6215.4  332.08  6371.6   334.6  6415.6  336.18
#Mann= 9 ,-1 , 0
  3939.1     .16       0  5010.7     .07       0  5016.7     .16       0
  5370.1      .1       0  5434.7     .16       0  5645.3     .05       0
  6025.1     .16       0  6215.4      .1       0  6371.6     .05       0
Bank Sta=4990.2,5043.8
XS Rating Curve= 0 ,0
Exp/Cntr=0.3,0.1

Type RM Length L Ch R = 1 ,18406   ,821,821,821
BEGIN DESCRIPTION:
TOWN BRANCH CR TRIB 22.0
END DESCRIPTION:
XS GIS Cut Line= 3
      3808463.85     10474688.04      3810026.32      10475167.2
      3811226.18     10474931.39
#Sta/Elev= 30
  3554.8  352.25  3895.5  355.28  4095.1  348.85  4219.8  347.75  4439.4  332.73
    4564  319.65  4738.2  309.78  4920.6  307.62  4972.6  309.55  4977.8  308.67
  4983.3  302.06  5001.3  299.27    5004  298.77  5007.3  299.27  5015.8  301.04
  5025.2  307.51  5035.6  308.46  5081.3  306.51    5114  309.54  5184.8  308.38
  5365.7  312.45  5447.2  319.17  5477.8  324.67  5512.1  326.62  5579.7  335.15
  5783.5  344.93  5997.6  345.97  6099.5  350.16  6303.3  347.47  6411.9  348.68
#Mann= 3 ,-1 , 0
  3554.8     .16       0  5001.3     .07       0  5007.3     .16       0
Bank Sta=4972.6,5035.6
XS Rating Curve= 0 ,0
Exp/Cntr=0.3,0.1

Type RM Length L Ch R = 1 ,17585   ,111,111,111
BEGIN DESCRIPTION:
TOWN BRANCH CR TRIB 21.0
END DESCRIPTION:
XS GIS Cut Line= 4
      3808776.32     10476056.09      3810040.21     10475465.81
      3810748.55     10475160.26      3811205.77     10475125.62
#Sta/Elev= 30
  3781.8  329.52  3792.8  329.55  3872.3  328.57  4315.2  328.09  4459.2  322.27
  4484.4  314.84  4489.6  311.45    4547  307.01  4749.6  306.37  4913.1  306.91
  4955.3  304.57  4977.4     307    4986  306.44  4996.5  296.83  4999.2  296.33
  5002.5  296.83  5014.6  301.41  5021.6  305.74  5043.6  306.45  5060.1     304
    5083  307.05  5088.5  301.97  5098.8  306.97  5125.6  307.42  5127.4  307.53
  5235.8  308.02  5478.4  316.93  5732.7  336.74  6240.1  353.18  6406.7  349.19
#Mann= 14 ,-1 , 0
  3781.8     .16       0  3792.8     .08       0  3872.3     .16       0
  4459.2     .05       0  4484.4     .16       0  4749.6     .05       0
  4913.1     .16       0  4996.5     .07       0  5002.5     .16       0
  5014.6     .08       0  5125.6     .05       0  5127.4     .16       0
  5235.8     .05       0  5732.7     .16       0
Bank Sta=4977.4,5043.6
XS Rating Curve= 0 ,0
Exp/Cntr=0.3,0.1

Type RM Length L Ch R = 1 ,17474   ,385,385,385
BEGIN DESCRIPTION:
TOWN BRANCH CR TRIB 20.0
END DESCRIPTION:
XS GIS Cut Line= 3
      3808935.72     10476136.67      3810164.87     10475513.41
      3811130.53     10475604.71
#Sta/Elev= 30
    3865   330.2  4177.8   329.6    4200  324.93    4239  327.02  4244.6  324.43
  4261.2  326.59  4266.8  323.31  4350.3  322.99  4355.9   319.1  4372.6   321.1
  4439.4   310.1  4477.7  308.73  4820.5  305.59  4881.2  305.17  4968.1  305.81
  4993.1  296.09  4995.8  295.59  4999.1  296.09  5024.2  304.06  5046.5  304.37
  5062.9  307.02  5103.6  305.94  5318.2  311.61  5589.4  319.71  5619.5   315.9
  5800.3  337.08  5890.7  335.55  5971.1  345.07  6108.1  349.81  6213.1  353.97
#Mann= 10 ,-1 , 0
    3865     .08       0  4477.7     .05       0  4820.5     .16       0
  4881.2     .05       0  4993.1     .04       0  4999.1     .05       0
  5046.5     .16       0  5103.6     .05       0  5318.2     .16       0
  6108.1     .05       0
Bank Sta=4968.1,5062.9
XS Rating Curve= 0 ,0
Exp/Cntr=0.3,0.1

Type RM Length L Ch R = 1 ,17089   ,530,530,530
BEGIN DESCRIPTION:
TOWN BRANCH CR TRIB 18.0
END DESCRIPTION:
XS GIS Cut Line= 4
      3809241.29     10476035.98      3809649.25     10475893.62
      3810211.75     10475779.04      3811183.61     10475775.33
#Sta/Elev= 30
  4310.1  329.55  4502.8  323.46  4519.9  321.31  4530.7  316.14  4573.1  304.66
  4926.2  305.68  4988.7  301.76  4997.7  295.64  5004.9  295.39  5007.6  294.89
  5010.9  295.39  5028.3  301.12  5034.2  306.71  5099.7  307.39  5120.2  305.06
  5140.6  307.43  5171.2  304.08  5185.9  307.48  5222.2  309.01  5424.1  311.71
  5434.1   307.6  5484.1  313.08  5624.1  314.38  5714.1  325.96  5779.3  338.68
  5824.1  346.19  5934.1  348.11  5954.1  355.91  6084.1  356.79  6288.1  363.33
#Mann= 5 ,-1 , 0
  4310.1     .08       0  4502.8     .16       0  5004.9     .07       0
  5010.9     .16       0  5779.3     .05       0
Bank Sta=4926.2,5034.2
XS Rating Curve= 0 ,0
Exp/Cntr=0.3,0.1

Type RM Length L Ch R = 1 ,16559   ,82,82,82
BEGIN DESCRIPTION:
Mapping XS d375a394
END DESCRIPTION:
XS GIS Cut Line= 5
      3809097.81     10476091.75      3809553.53     10476034.46
      3810373.84      10476180.3       3810725.4      10475805.3
       3811125.5      10475807.9
#Sta/Elev= 30
  3917.8  331.71  4048.1  327.15  4053.1   330.4  4070.8  330.08  4111.1  328.46
  4128.5  324.66  4228.9  324.45  4294.3  321.31  4363.1  313.39  4369.7  316.88
  4374.2   312.6  4384.8  316.93  4413.7  319.06  4551.7  307.31  4664.7     303
  4949.8     303  4999.8  293.82  5002.6  293.32  5005.8  293.82  5023.2  301.48
  5043.5  304.19  5412.6  312.55  5447.8  317.41  5575.3  324.92  5660.3  340.81
  5719.4  346.19  5798.5  345.97  5808.5  354.12  5828.5  355.45  6124.4  363.28
#Mann= 5 ,-1 , 0
  3917.8     .05       0  4228.9     .16       0  4999.8     .07       0
  5005.8     .16       0  5719.4     .05       0
Bank Sta=4949.8,5043.5
XS Rating Curve= 0 ,0
Exp/Cntr=0.3,0.1

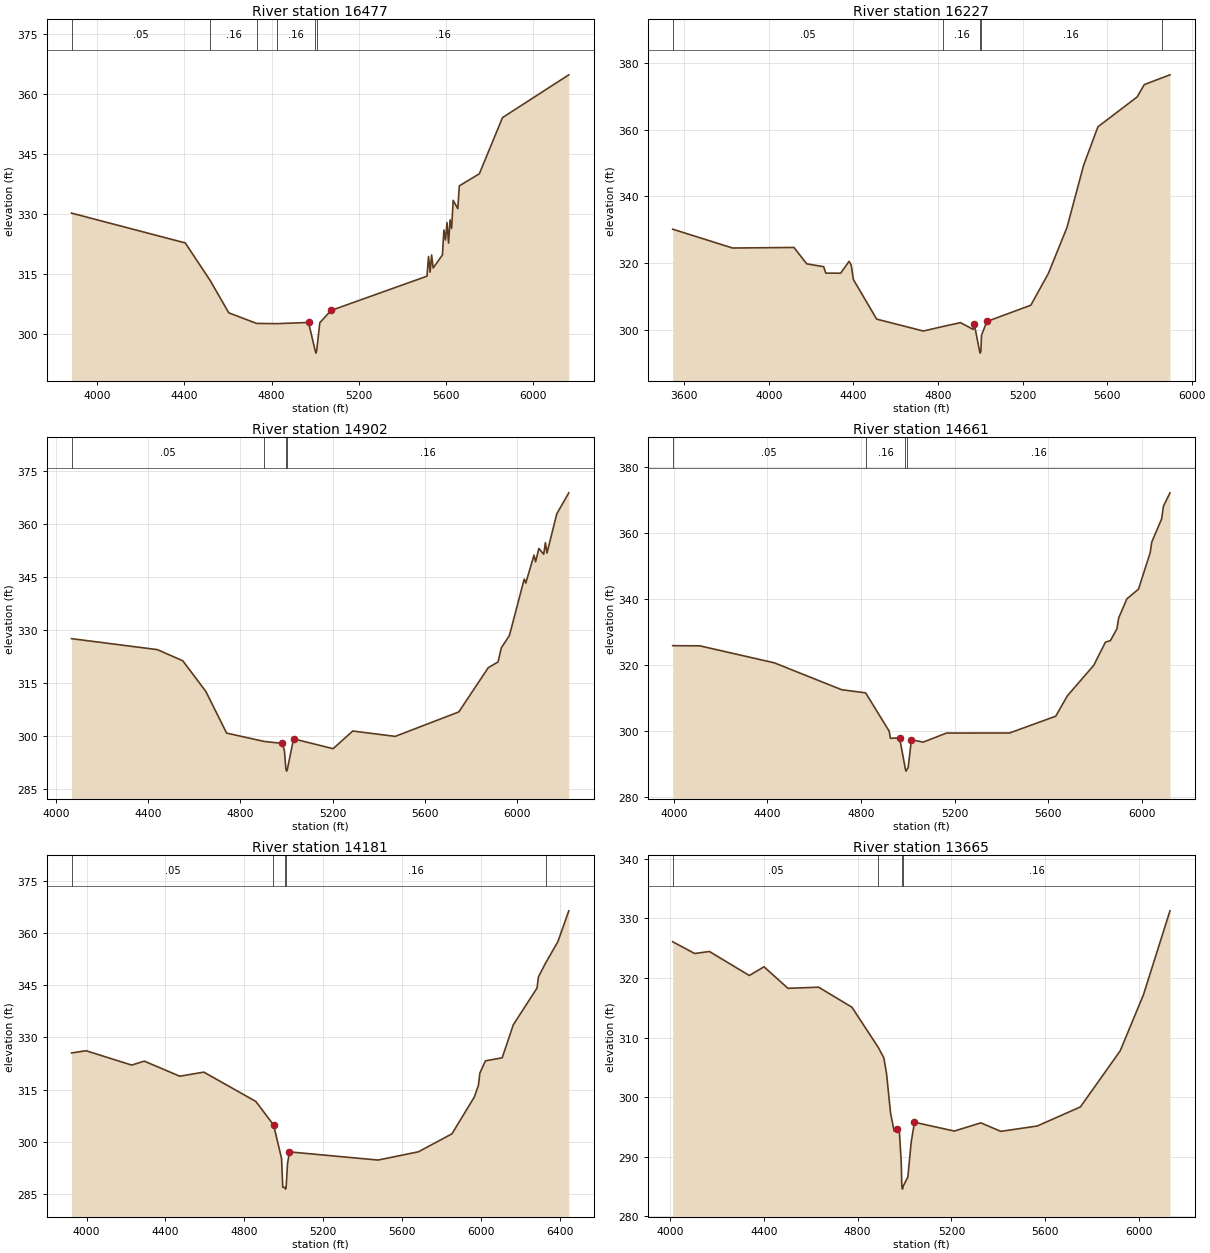
Type RM Length L Ch R = 1 ,16477   ,250,250,250
BEGIN DESCRIPTION:
Mapping XS 0370ca18
END DESCRIPTION:
XS GIS Cut Line= 6
        3809041.     10476154.62      3809323.09     10476106.88
       3809583.5     10476111.22      3810386.45     10476267.47
      3810781.42     10475859.48      3811134.18     10475855.18
#Sta/Elev= 30
  3880.9  330.23  4403.6  322.78  4518.5  313.35  4603.5  305.31  4731.2  302.66
  4824.5   302.6  4970.1  302.89  5001.2  295.73  5003.9  295.23  5007.2  295.73
  5021.8  302.83  5073.4  305.89  5514.5  314.47  5521.5  319.39  5528.7  315.48
  5535.6  319.78  5542.8  316.51  5585.3  319.77  5592.2     326  5599.4  323.52
  5606.4  327.85  5613.6  322.74  5620.5  328.54  5627.7   326.4  5634.7  333.42
    5656  331.34    5663  337.05    5755  340.06  5861.5  354.11  6166.1   364.8
#Mann= 6 ,-1 , 0
  3880.9     .05       0  4518.5     .16       0  4731.2     .05       0
  4824.5     .16       0  5001.2     .07       0  5007.2     .16       0
Bank Sta=4970.1,5073.4
XS Rating Curve= 0 ,0
Exp/Cntr=0.3,0.1

Type RM Length L Ch R = 1 ,16227   ,1325,1325,1325
BEGIN DESCRIPTION:
Mapping XS bd1d3d9e
END DESCRIPTION:
XS GIS Cut Line= 3
      3808797.51      10476374.7      3809998.86     10476464.97
      3811103.06     10476152.46
#Sta/Elev= 30
  3545.1  330.23    3828   324.6  4118.8  324.77    4179  319.87  4259.2  319.02
  4269.2   317.1  4339.4  317.07  4379.5  320.62  4389.6  319.49  4399.6  315.21
  4509.9  303.35  4730.5  299.79  4824.6  301.16  4906.5   302.3  4966.5  300.26
  4971.7  301.93    4997  293.68  4999.8  293.18    5003  293.68  5005.7  298.49
  5031.2  302.64  5239.1   307.5  5322.2     317  5410.3  330.76  5488.6  349.27
  5556.5  360.83  5741.8  369.74  5775.8  373.44  5858.8  375.45  5897.4  376.37
#Mann= 5 ,-1 , 0
  3545.1     .05       0  4824.6     .16       0    4997     .07       0
    5003     .16       0  5858.8     .05       0
Bank Sta=4971.7,5031.2
XS Rating Curve= 0 ,0
Exp/Cntr=0.3,0.1

Type RM Length L Ch R = 1 ,14902   ,241,241,241
BEGIN DESCRIPTION:
TOWN BRANCH CR TRIB 17.0
END DESCRIPTION:
XS GIS Cut Line= 3
      3808977.76     10477035.26      3810061.05      10477042.2
      3810838.83     10476306.09
#Sta/Elev= 30
  4068.4  327.62  4440.3  324.51  4550.3  321.36  4650.3  312.67  4740.3  300.87
  4902.9  298.51  4980.3  297.96  4990.3  296.11  4997.3   290.6    5000   290.1
  5003.3   290.6  5030.3  299.24  5201.7  296.46  5286.7  301.46  5470.4  299.94
  5746.2  306.87  5873.7   319.4  5916.1  321.02  5930.3  325.01  5965.5  328.54
  6029.4  344.48  6036.3  343.36  6071.9  351.27  6078.8   349.4  6092.9  353.16
    6114  351.52  6121.2  354.81  6128.1  351.87  6170.6  362.98  6222.6  368.92
#Mann= 4 ,-1 , 0
  4068.4     .05       0  4902.9     .16       0  4997.3     .07       0
  5003.3     .16       0
Bank Sta=4980.3,5030.3
XS Rating Curve= 0 ,0
Exp/Cntr=0.3,0.1

Type RM Length L Ch R = 1 ,14661   ,480,480,480
BEGIN DESCRIPTION:
TOWN BRANCH CR TRIB 16.0
END DESCRIPTION:
XS GIS Cut Line= 4
        3809068.     10477118.59      3809849.61     10477310.19
      3810049.61     10477210.19      3810849.58     10476460.21
#Sta/Elev= 30
  3995.4  325.89  4111.3  325.84  4429.5   320.7  4717.8  312.55  4819.8  311.61
  4920.3  300.03  4925.9  297.86  4965.1  297.96    4990  288.42  4992.8  287.92
    4996  288.42  5001.4  288.93  5015.4  297.41    5066   296.7  5165.2  299.44
  5434.3  299.45  5632.1  304.54  5681.7   310.7  5794.8  319.97  5844.6  326.97
  5865.6   327.4  5893.9  331.04    5901  334.27  5936.4  340.08  5985.8     343
  6035.6  354.01  6042.4  357.23  6084.9   364.3  6092.2  368.08  6120.3  372.15
#Mann= 4 ,-1 , 0
  3995.4     .05       0  4819.8     .16       0    4990     .07       0
    4996     .16       0
Bank Sta=4965.1,5015.4
XS Rating Curve= 0 ,0
Exp/Cntr=0.3,0.1

Type RM Length L Ch R = 1 ,14181   ,516,516,516
BEGIN DESCRIPTION:
TOWN BRANCH CR TRIB 15.0
END DESCRIPTION:
XS GIS Cut Line= 4
      3808922.19     10477153.33      3809755.49     10477521.37
       3810241.6     10477563.04       3811011.7     10476744.38
#Sta/Elev= 30
  3923.9  325.52  3997.5  326.16  4229.1  322.03  4292.8  323.17  4473.1  318.83
  4595.1  320.01  4859.1  311.57    4948  304.89  4949.4  304.76  4989.5  295.16
  4995.6  286.89  5006.6  286.86  5009.4  286.36  5012.6  286.86  5019.7   293.7
  5029.7  297.07  5478.8  294.72    5684   297.1  5853.9  302.26  5967.2  312.84
  5988.2  316.19  5995.5  319.73  6023.8  323.25  6108.8  324.12    6165  333.61
  6285.6  344.19  6292.5  347.38  6329.1  351.39  6391.6  357.56  6446.7  366.39
#Mann= 5 ,-1 , 0
  3923.9     .05       0    4948     .16       0  5006.6     .07       0
  5012.6     .16       0  6329.1     .05       0
Bank Sta=4949.4,5029.7
XS Rating Curve= 0 ,0
Exp/Cntr=0.3,0.1

Type RM Length L Ch R = 1 ,13665   ,365,365,365
BEGIN DESCRIPTION:
TOWN BRANCH CR TRIB 14.0
END DESCRIPTION:
XS GIS Cut Line= 3
      3809206.84     10478333.89      3810099.61     10477910.19
      3810899.62     10477110.17
#Sta/Elev= 30
    4012  326.07  4105.7   324.1  4168.4  324.44  4338.5  320.41  4401.2  321.87
  4503.2  318.26    4634  318.45    4776  315.09  4888.3  308.34  4911.7  306.62
  4923.4     304  4940.6  297.34  4955.9   294.3  4968.9  294.65  4978.1  294.27
  4986.1  289.18  4988.6  285.07  4991.4  284.57  4994.6  285.07  5014.4  286.62
  5028.5  292.44  5042.6  295.79  5212.3  294.31  5325.5  295.69  5410.3  294.26
  5565.9  295.16  5749.7  298.36  5919.4  307.77  6018.4  317.16  6131.6  331.26
#Mann= 4 ,-1 , 0
    4012     .05       0  4888.3     .16       0  4988.6     .07       0
  4994.6     .16       0
Bank Sta=4968.9,5042.6
XS Rating Curve= 0 ,0
Exp/Cntr=0.3,0.1