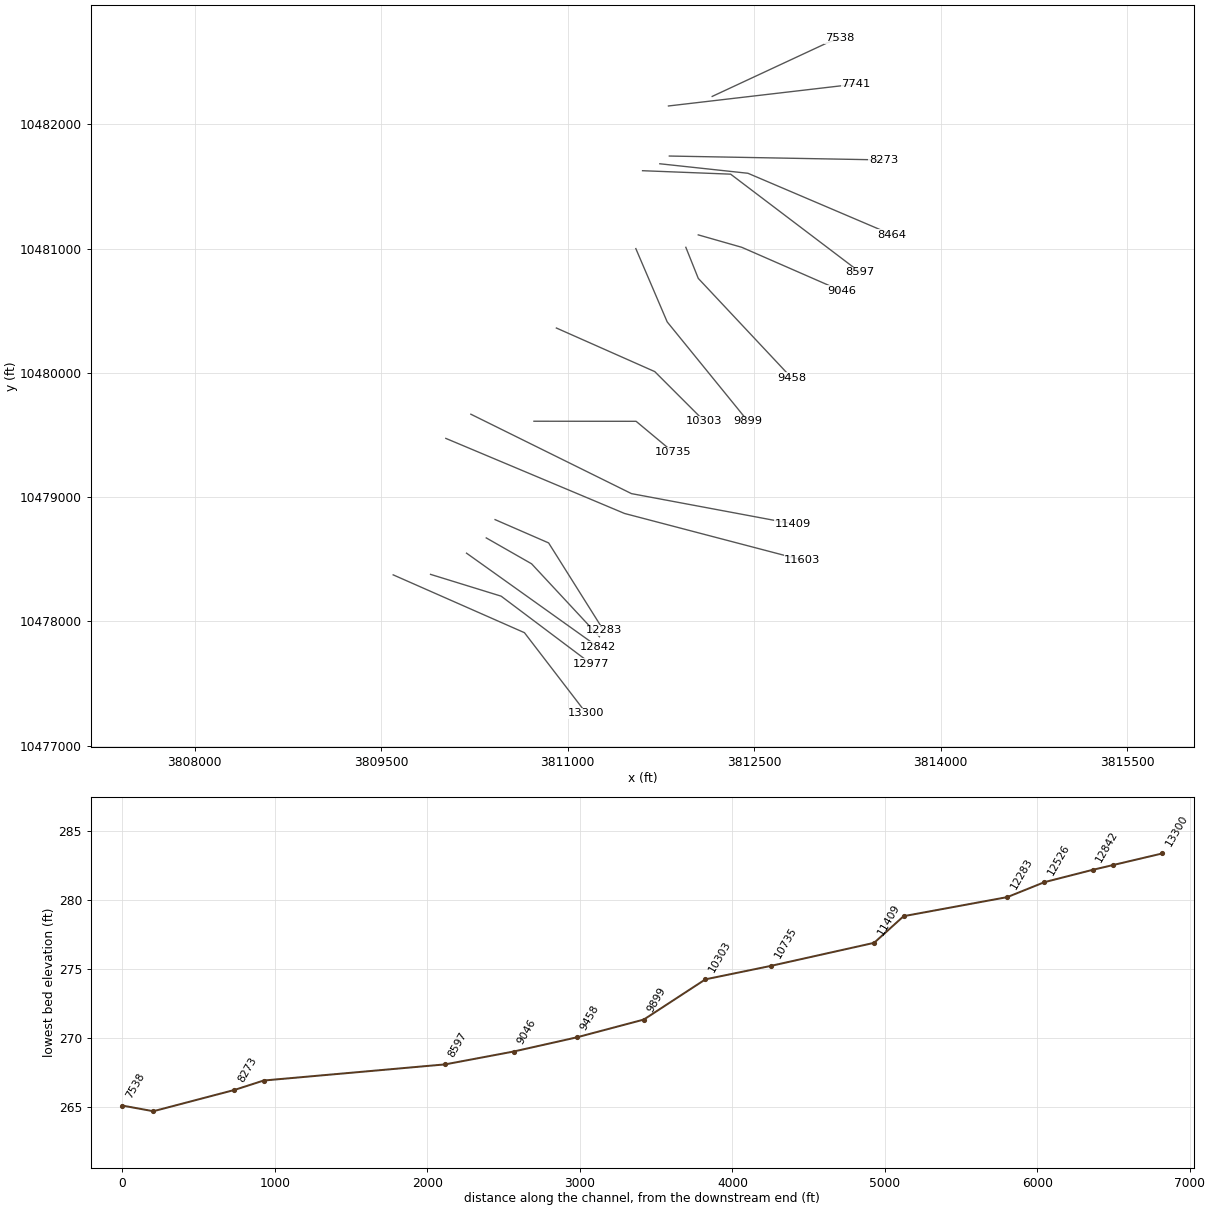
HEC-RAS study TOWN BRANCH CR TRIB.prj: TOWN BRANCH CR TRIB Base Level Engineering

--- TOWN BRANCH CR TRIB.g01 (geometry) --- (continued)

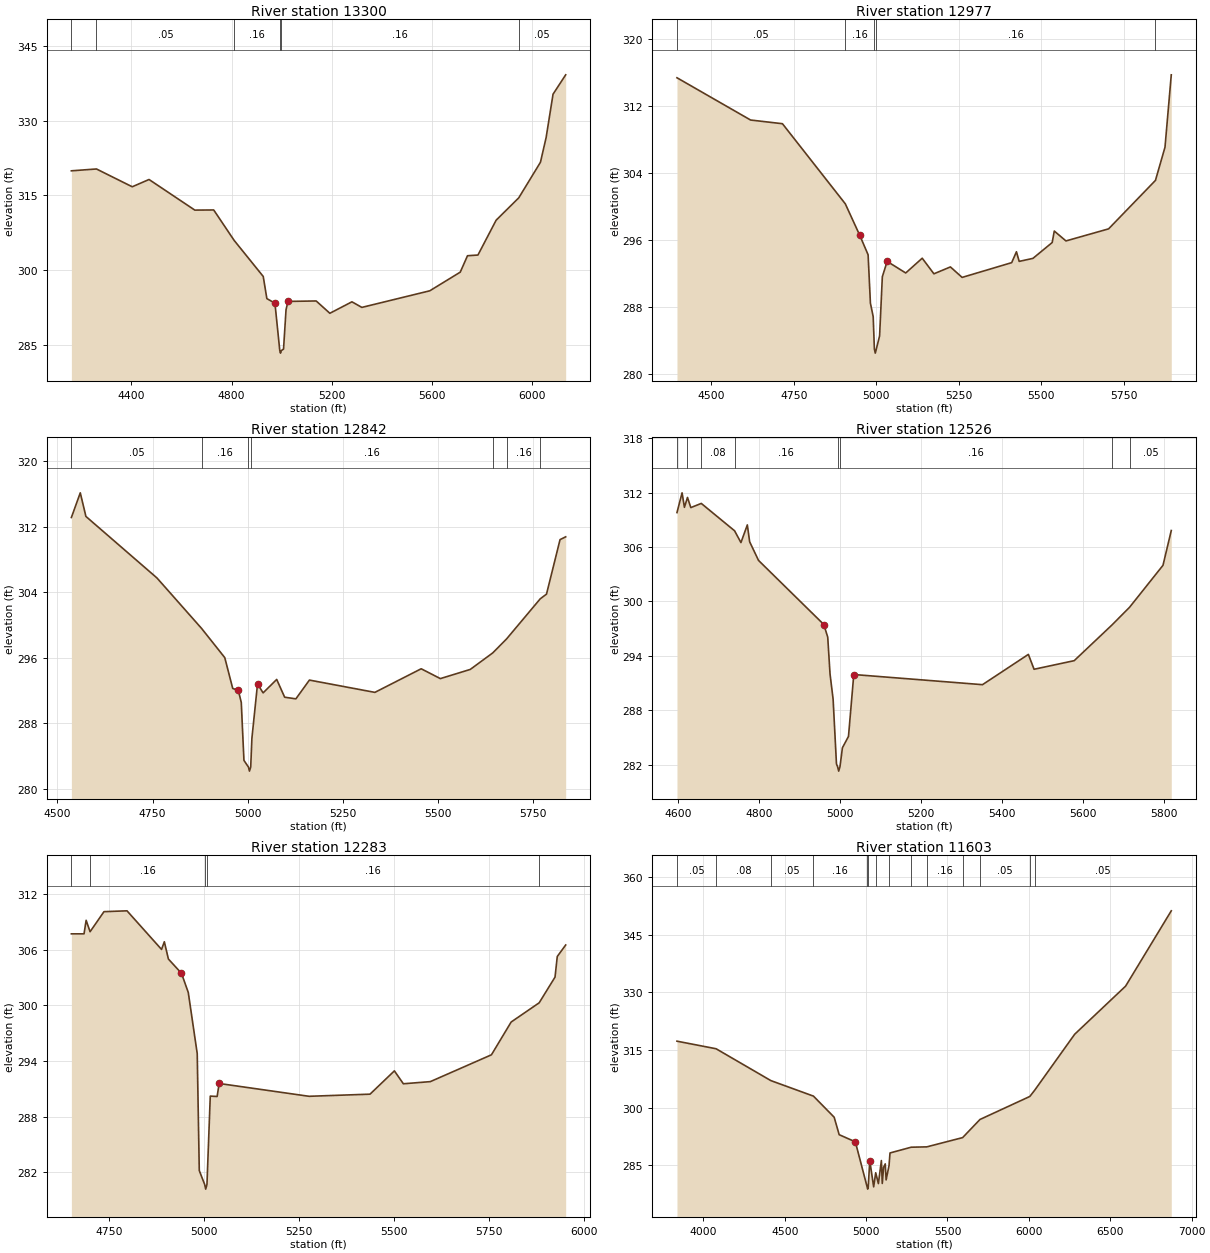
Type RM Length L Ch R = 1 ,13300   ,323,323,323
BEGIN DESCRIPTION:
TOWN BRANCH CR TRIB 13.0
END DESCRIPTION:
XS GIS Cut Line= 3
      3809596.08     10478374.69      3810651.64     10477909.42
      3811149.63     10477260.16
#Sta/Elev= 30
  4161.2  319.91  4261.2  320.28    4404  316.71    4471  318.17  4653.6  312.03
    4729  312.06  4810.6  305.95  4926.6  298.72    4941  294.28  4973.2  293.37
  4992.6  283.85  4995.4  283.35  4998.6  283.85  5007.5  284.16  5017.5  292.07
  5025.3  293.72  5137.7  293.81  5192.3  291.34  5280.4  293.64  5319.9  292.52
    5591  295.85  5712.4  299.59  5741.4  302.88    5783  303.02  5855.6  310.01
  5945.8  314.49  6032.3  321.62    6055  326.58  6082.6  335.28    6133  339.16
#Mann= 6 ,-1 , 0
  4161.2     .08       0  4261.2     .05       0  4810.6     .16       0
  4992.6     .07       0  4998.6     .16       0  5945.8     .05       0
Bank Sta=4973.2,5025.3
XS Rating Curve= 0 ,0
Exp/Cntr=0.3,0.1

Type RM Length L Ch R = 1 ,12977   ,135,135,135
BEGIN DESCRIPTION:
Mapping XS f52e6b57
END DESCRIPTION:
XS GIS Cut Line= 3
      3809896.63      10478378.6      3810464.37     10478203.24
      3811185.91     10477660.81
#Sta/Elev= 30
  4396.3  315.35  4619.2  310.31  4715.7  309.87    4906  300.32  4949.5  296.59
  4975.1  294.24  4982.1  288.47  4990.5  286.86  4994.1  283.01  4996.8  282.51
  5000.1  283.01  5009.9  284.56  5018.2  291.62  5032.8  293.45    5089  292.07
    5139  293.83  5174.4  291.97  5224.4  292.79  5259.8  291.54  5409.9   293.3
  5424.3   294.6  5432.6  293.45  5474.3  293.81  5532.6   295.7  5538.9  297.07
  5574.3  295.89  5703.4  297.33  5845.3  303.11  5874.2  307.07  5893.2   315.7
#Mann= 5 ,-1 , 0
  4396.3     .05       0    4906     .16       0  4994.1     .07       0
  5000.1     .16       0  5845.3     .08       0
Bank Sta=4949.5,5032.8
XS Rating Curve= 0 ,0
Exp/Cntr=0.3,0.1

Type RM Length L Ch R = 1 ,12842   ,316,316,316
BEGIN DESCRIPTION:
TOWN BRANCH CR TRIB 12.0
END DESCRIPTION:
XS GIS Cut Line= 2
      3810186.05     10478549.15      3811243.78     10477794.58
#Sta/Elev= 30
  4536.6  313.11    4560  316.12  4574.8  313.24  4761.6  305.73  4878.9  299.57
  4939.8  296.01  4960.7  292.25  4975.5  292.01  4983.2  290.53  4990.2  283.47
    5002  282.66  5004.7  282.16    5008  282.66  5011.1  286.16  5025.9  292.79
  5040.6  291.71  5076.3  293.35  5097.2  291.18  5126.7  290.98  5162.3  293.27
  5334.4  291.77  5456.1  294.65  5506.5  293.45  5585.1  294.57  5644.3  296.59
  5680.7   298.3  5769.1  303.19  5785.5  303.76  5821.1  310.41  5835.9  310.75
#Mann= 7 ,-1 , 0
  4536.6     .05       0  4878.9     .16       0    5002     .07       0
    5008     .16       0  5644.3     .12       0  5680.7     .16       0
  5769.1     .05       0
Bank Sta=4975.5,5025.9
XS Rating Curve= 0 ,0
Exp/Cntr=0.3,0.1

Type RM Length L Ch R = 1 ,12526   ,243,243,243
BEGIN DESCRIPTION:
Mapping XS d65758e4
END DESCRIPTION:
XS GIS Cut Line= 3
      3810344.57     10478671.99      3810709.16     10478463.66
      3811255.11     10477876.47
#Sta/Elev= 30
  4597.5   309.8  4610.1  311.98  4615.9  310.38  4623.5  311.47  4631.7  310.35
  4657.6  310.81  4739.9  307.79  4755.6  306.49  4771.4  308.44  4777.1  306.58
  4799.1  304.52  4960.4  297.45  4970.1  296.06  4975.8  291.99  4983.4  289.21
  4991.7  282.06  4994.4  281.77  4997.2  281.27  5000.4  281.77  5006.4  283.85
  5021.4   285.1  5034.5  291.93  5352.6  290.81    5466  294.15  5480.1  292.51
  5579.3  293.46    5672  297.37  5716.1  299.35  5798.7  303.98  5819.2  307.82
#Mann= 8 ,-1 , 0
  4597.5     .08       0  4623.5     .05       0  4657.6     .08       0
  4739.9     .16       0  4994.4     .07       0  5000.4     .16       0
    5672     .12       0  5716.1     .05       0
Bank Sta=4960.4,5034.5
XS Rating Curve= 0 ,0
Exp/Cntr=0.3,0.1

Type RM Length L Ch R = 1 ,12283   ,680,680,680
BEGIN DESCRIPTION:
TOWN BRANCH CR TRIB 11.0
END DESCRIPTION:
XS GIS Cut Line= 3
      3810415.52     10478819.14      3810846.09     10478631.64
      3811287.86     10477928.88
#Sta/Elev= 30
  4651.3  307.69  4684.6  307.69  4690.1  309.15  4700.5  307.92    4737  310.08
  4797.6  310.17  4888.4  306.01  4895.7  306.84  4906.4  304.98  4940.8  303.44
  4958.7  301.37  4982.2  294.79  4987.6  282.19  5001.8  280.69  5004.5  280.19
  5007.8  280.69  5016.5  290.21  5034.5  290.17  5039.9  291.57  5276.2  290.19
  5436.6  290.42  5500.6  292.93  5524.2  291.54  5595.1  291.77  5755.8  294.66
  5807.6  298.19  5881.3  300.26    5923  303.03  5928.9  305.25    5951  306.49
#Mann= 5 ,-1 , 0
  4651.3     .05       0  4700.5     .16       0  5001.8     .07       0
  5007.8     .16       0  5881.3     .05       0
Bank Sta=4940.8,5039.9
XS Rating Curve= 0 ,0
Exp/Cntr=0.3,0.1

Type RM Length L Ch R = 1 ,11603   ,194,194,194
BEGIN DESCRIPTION:
TOWN BRANCH CR TRIB 10.0
END DESCRIPTION:
XS GIS Cut Line= 3
      3810019.36     10479472.76      3811456.88     10478868.59
      3812885.98     10478493.97
#Sta/Elev= 30
  3838.1  317.32  4078.3  315.35  4414.8  307.06  4676.5  303.02  4803.8  297.53
  4834.6  292.98  4933.9  291.12  5006.9  279.31  5009.6  278.81  5012.9  279.31
  5022.6   286.2  5046.4   279.4    5059  283.07  5075.5  280.25  5093.9  286.25
  5099.3  280.29  5107.5  284.49  5117.6  285.38    5123  281.21  5140.8  284.92
  5146.8  288.22    5277  289.72  5372.9  289.81    5593  292.22  5699.5  296.94
  6005.8  302.93  6037.3  304.65  6281.3  319.12  6594.1  331.64  6874.8  351.25
#Mann= 14 ,-1 , 0
  3838.1     .05       0  4078.3     .08       0  4414.8     .05       0
  4676.5     .16       0  5006.9     .07       0  5012.9     .16       0
    5059     .05       0  5140.8     .16       0    5277     .05       0
  5372.9     .16       0    5593     .08       0  5699.5     .05       0
  6005.8     .08       0  6037.3     .05       0
Bank Sta=4933.9,5022.6
XS Rating Curve= 0 ,0
Exp/Cntr=0.3,0.1

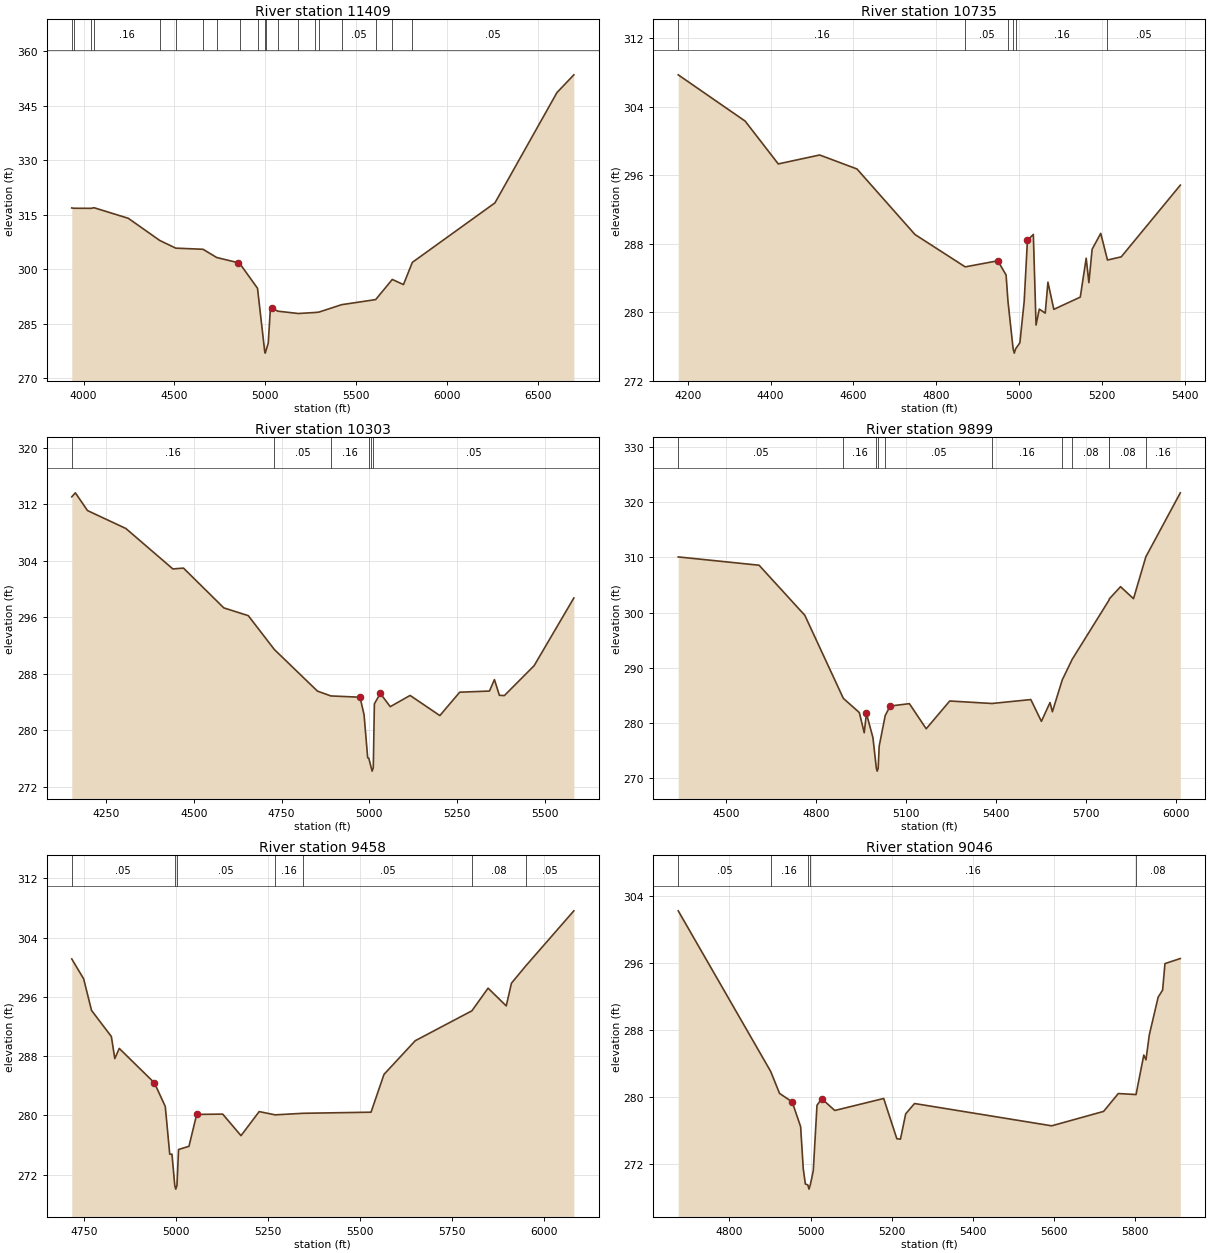
Type RM Length L Ch R = 1 ,11409   ,674,674,674
BEGIN DESCRIPTION:
TOWN BRANCH CR TRIB 9.0
END DESCRIPTION:
XS GIS Cut Line= 3
      3810220.76     10479667.21      3811512.44     10479028.31
      3812811.04     10478785.26
#Sta/Elev= 30
  3935.2  316.86  3945.6  316.78  4040.9  316.75    4058  316.92  4246.3  314.01
  4419.2  307.91  4507.5  305.79  4657.2  305.48  4732.3  303.22  4848.7   301.8
  4862.7  301.33  4957.1  294.74  4996.6  277.38  4999.4  276.88  5002.6  277.38
  5016.1  279.66  5027.6  288.89  5038.4  289.18  5069.5  288.43  5181.9  287.79
  5273.6  288.07  5294.3  288.17  5419.7  290.22  5607.1  291.62  5698.6  297.17
    5760  295.76  5808.8  301.87  6263.3  318.25  6604.4  348.63  6697.4  353.52
#Mann= 20 ,-1 , 0
  3935.2     .05       0  3945.6     .16       0  4040.9     .05       0
    4058     .16       0  4419.2     .08       0  4507.5     .16       0
  4657.2      .1       0  4732.3     .05       0  4862.7     .05       0
  4957.1     .16       0  4996.6     .07       0  5002.6     .16       0
  5069.5     .12       0  5181.9     .08       0  5273.6     .05       0
  5294.3     .16       0  5419.7     .05       0  5607.1     .05       0
  5698.6     .08       0  5808.8     .05       0
Bank Sta=4848.7,5038.4
XS Rating Curve= 0 ,0
Exp/Cntr=0.3,0.1

Type RM Length L Ch R = 1 ,10735   ,432,432,432
BEGIN DESCRIPTION:
TOWN BRANCH CR TRIB 8.0
END DESCRIPTION:
XS GIS Cut Line= 3
      3810728.07      10479610.8      3811549.61     10479610.19
      3811849.65     10479360.16
#Sta/Elev= 30
  4177.2  307.71  4338.7  302.31  4418.7  297.31  4518.7  298.35  4608.7  296.72
  4748.7  289.07    4870  285.29  4948.7     286  4968.7  284.34  4973.3  281.25
  4985.7  275.72  4988.5  275.22  4991.7  275.72    5002  276.43  5012.4  281.27
  5020.2  288.39  5034.5  289.08    5041   278.5  5048.9  280.36  5063.2  279.89
  5069.7  283.51    5084  280.33  5147.8  281.76  5162.1   286.3  5168.6  283.45
  5176.4  287.35  5197.2   289.2  5213.5  286.09  5246.7  286.46  5389.3  294.83
#Mann= 6 ,-1 , 0
  4177.2     .16       0    4870     .05       0  4973.3     .16       0
  4985.7     .07       0  4991.7     .16       0  5213.5     .05       0
Bank Sta=4948.7,5020.2
XS Rating Curve= 0 ,0
Exp/Cntr=0.3,0.1

Type RM Length L Ch R = 1 ,10303   ,404,404,404
BEGIN DESCRIPTION:
TOWN BRANCH CR TRIB 7.0
END DESCRIPTION:
XS GIS Cut Line= 3
      3810908.57     10480360.81      3811699.61     10480010.19
      3812099.64     10479610.15
#Sta/Elev= 30
  4152.1  313.05  4162.3  313.62    4197  311.11  4306.4  308.57  4440.3  302.85
  4470.5  302.97  4585.4  297.34  4655.2  296.24  4729.5  291.45  4852.4  285.56
  4890.7  284.88  4973.6   284.7  4985.2  282.22  4995.5  276.13  4998.7  276.07
  5005.5  274.74  5008.2  274.24  5011.5  274.74  5014.6  283.76  5031.5  285.24
  5059.8  283.36  5116.4  284.95  5201.2   282.1  5257.8  285.41  5342.6  285.57
  5356.8  287.19  5370.9  284.97  5385.1  284.93  5469.9  289.16  5583.1  298.74
#Mann= 6 ,-1 , 0
  4152.1     .16       0  4729.5     .05       0  4890.7     .16       0
  4998.7     .05       0  5005.5     .03       0  5011.5     .05       0
Bank Sta=4973.6,5031.5
XS Rating Curve= 0 ,0
Exp/Cntr=0.3,0.1

Type RM Length L Ch R = 1 ,9899    ,441,441,441
BEGIN DESCRIPTION:
TOWN BRANCH CR TRIB 6.0
END DESCRIPTION:
XS GIS Cut Line= 3
      3811547.46     10480999.73      3811799.61     10480410.19
      3812449.63     10479610.17
#Sta/Elev= 30
  4341.5  310.06  4610.7  308.56  4763.1   299.5  4891.3  284.49  4944.6  281.92
  4960.9  278.26  4968.2  281.75  4989.9  277.39  5001.3  271.83    5004  271.33
  5007.3  271.83  5010.7  275.85  5030.8  281.38  5047.1   283.1  5111.3  283.53
  5167.3  278.99  5245.6  284.01  5386.3  283.56  5515.7  284.27  5550.9  280.33
  5579.6  283.74  5587.5  282.07  5620.4  287.83  5653.6  291.56  5776.2  302.26
  5777.5   302.5  5814.5  304.68  5857.6  302.51  5898.8  310.09  6013.5  321.65
#Mann= 11 ,-1 , 0
  4341.5     .05       0  4891.3     .16       0  5001.3     .07       0
  5007.3     .16       0  5030.8     .05       0  5386.3     .16       0
  5620.4     .05       0  5653.6     .08       0  5776.2     .05       0
  5777.5     .08       0  5898.8     .16       0
Bank Sta=4968.2,5047.1
XS Rating Curve= 0 ,0
Exp/Cntr=0.3,0.1

Type RM Length L Ch R = 1 ,9458    ,412,412,412
BEGIN DESCRIPTION:
TOWN BRANCH CR TRIB 5.0
END DESCRIPTION:
XS GIS Cut Line= 3
      3811949.62     10481010.15      3812049.61     10480760.19
      3812799.61     10479960.19
#Sta/Elev= 30
  4716.1  301.12  4748.4  298.44  4769.9  294.17  4823.8  290.65  4833.2  287.67
  4845.3  289.04  4940.9  284.39  4970.5   281.2  4982.6  274.76  4988.7  274.76
  4996.3  270.54    4999  270.04  5002.3  270.54  5006.6  275.39  5034.9  275.82
  5055.9  280.13  5126.7  280.17  5176.5  277.26  5225.9  280.51  5269.3  280.07
  5345.1  280.28  5530.2  280.43  5565.4  285.53  5650.4  290.08  5804.6  294.12
  5848.6  297.18    5898  294.78  5912.2  297.85  5951.1  300.18  6081.9  307.62
#Mann= 7 ,-1 , 0
  4716.1     .05       0  4996.3     .03       0  5002.3     .05       0
  5269.3     .16       0  5345.1     .05       0  5804.6     .08       0
  5951.1     .05       0
Bank Sta=4940.9,5055.9
XS Rating Curve= 0 ,0
Exp/Cntr=0.3,0.1

Type RM Length L Ch R = 1 ,9046    ,449,449,449
BEGIN DESCRIPTION:
TOWN BRANCH CR TRIB 4.0
END DESCRIPTION:
XS GIS Cut Line= 3
       3812049.6     10481110.19      3812399.61     10481010.19
      3813199.59      10480660.2
#Sta/Elev= 30
  4673.9  302.21  4901.7  283.06  4923.5  280.44  4954.7  279.42  4975.5  276.47
    4982  271.44  4987.2  269.63  4993.3  269.52  4996.1  269.02  4999.3  269.52
  5006.7  271.22  5015.8  279.02  5027.5   279.8  5059.7   278.4  5180.2  279.83
  5212.6  275.03  5221.5  274.98  5234.4     278  5256.2  279.23  5594.2  276.57
  5722.1  278.29  5758.3  280.42    5802   280.3  5821.1  285.01  5826.5  284.44
  5834.7  287.42  5856.5  291.91  5867.5  292.76  5873.3  295.92  5911.1  296.52
#Mann= 5 ,-1 , 0
  4673.9     .05       0  4901.7     .16       0  4993.3     .03       0
  4999.3     .16       0    5802     .08       0
Bank Sta=4954.7,5027.5
XS Rating Curve= 0 ,0
Exp/Cntr=0.3,0.1

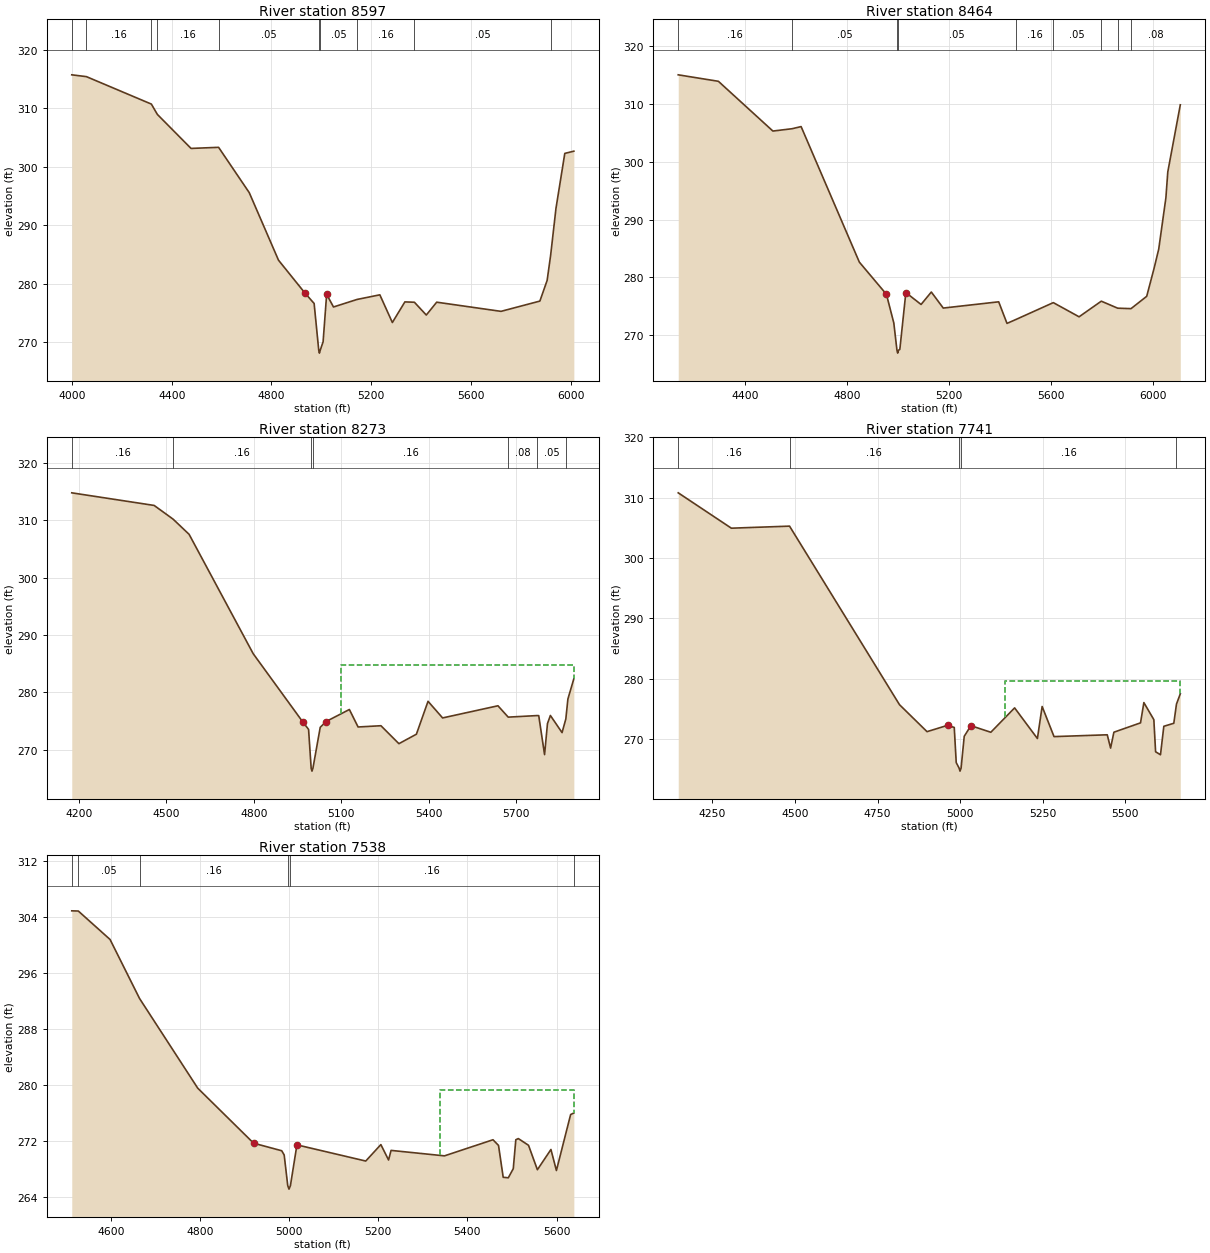
Type RM Length L Ch R = 1 ,8597    ,1191,1191,1191
BEGIN DESCRIPTION:
TOWN BRANCH CR TRIB 3.0
END DESCRIPTION:
XS GIS Cut Line= 3
      3811601.54     10481626.56      3812309.92     10481598.78
      3813349.57     10480810.22
#Sta/Elev= 30
    3999  315.73  4057.7  315.42  4318.3  310.72  4342.4  308.95  4477.4  303.13
  4587.9  303.32  4710.9  295.56  4828.2     284  4934.4  278.37  4971.1  276.59
  4989.6  268.59  4992.3  268.09  4995.6  268.59  5007.1  270.03  5021.3  278.15
  5048.8  275.99  5143.4  277.28  5234.7  278.07  5284.9  273.33  5335.1  276.86
  5373.3   276.8    5421  274.61  5462.7  276.81  5720.6  275.24  5876.6     277
  5905.7  280.54  5919.9   284.9  5941.1  292.86  5976.5  302.28  6012.8  302.66
#Mann= 10 ,-1 , 0
    3999     .05       0  4057.7     .16       0  4318.3     .05       0
  4342.4     .16       0  4587.9     .05       0  4989.6     .03       0
  4995.6     .05       0  5143.4     .16       0  5373.3     .05       0
  5919.9     .08       0
Bank Sta=4934.4,5021.3
XS Rating Curve= 0 ,0
Exp/Cntr=0.3,0.1

Type RM Length L Ch R = 1 ,8464    ,191,191,191
BEGIN DESCRIPTION:
Mapping XS 1f366e37
END DESCRIPTION:
XS GIS Cut Line= 3
      3811740.53     10481682.36      3812448.82     10481605.97
      3813604.81     10481113.03
#Sta/Elev= 30
  4139.2  315.03  4296.7  313.91  4510.4  305.31  4585.4  305.71  4621.1  306.08
  4849.5  282.65  4955.7  277.09  4984.7  272.13    4997  267.42  4999.8  266.92
    5003  267.42  5008.3  267.56  5031.9  277.39  5091.6  275.33  5131.8  277.48
  5178.6  274.71    5396  275.79  5428.6  272.06  5463.8  272.74  5610.2  275.65
  5711.3   273.2  5798.4   275.9  5862.7  274.69    5915  274.61  5976.5  276.74
  6005.5  281.59  6023.7  284.91  6051.8  293.78  6059.2  298.25  6108.3  309.85
#Mann= 9 ,-1 , 0
  4139.2     .16       0  4585.4     .05       0    4997     .03       0
    5003     .05       0  5463.8     .16       0  5610.2     .05       0
  5798.4     .16       0  5862.7     .05       0    5915     .08       0
Bank Sta=4955.7,5031.9
XS Rating Curve= 0 ,0
Exp/Cntr=0.3,0.1

Type RM Length L Ch R = 1 ,8273    ,532,532,532
BEGIN DESCRIPTION:
TOWN BRANCH CR TRIB 2.0
END DESCRIPTION:
XS GIS Cut Line= 2
      3811816.84     10481744.61      3813540.05     10481713.17
#Sta/Elev= 30
  4175.2  314.79    4458  312.59    4523   310.2    4578  307.55  4798.1  286.72
  4968.1  274.83  4988.1  273.52    4997  266.74  4999.8  266.24    5003  266.74
  5028.1  273.88  5048.1  274.89  5128.1  276.99  5158.1  273.94  5236.5  274.16
  5298.2  271.03  5358.2  272.68  5398.2  278.42  5448.2  275.52  5638.2  277.64
  5673.4  275.66  5772.3  275.93  5778.2  275.92  5798.2  269.12  5808.2  274.54
  5818.2  275.95  5858.2  272.96  5871.2  275.34  5878.3  278.82  5898.7  282.36
#Mann= 7 ,-1 , 0
  4175.2     .16       0    4523     .16       0    4997     .07       0
    5003     .16       0  5673.4     .08       0  5772.3     .05       0
  5871.2     .16       0
#XS Ineff= 2 , 0
                            5100          284.79
Permanent Ineff=
       F       F
Bank Sta=4968.1,5048.1
XS Rating Curve= 0 ,0
Exp/Cntr=0.3,0.1

Type RM Length L Ch R = 1 ,7741    ,203,203,203
BEGIN DESCRIPTION:
TOWN BRANCH CR TRIB 1.0
END DESCRIPTION:
XS GIS Cut Line= 2
      3811809.88     10482147.39      3813319.21     10482323.83
#Sta/Elev= 30
  4146.9  310.82  4307.7  304.96  4483.8   305.3  4816.6  275.71  4899.9  271.24
  4962.1  272.29  4982.3  271.94  4988.3  266.11    4997   265.2  4999.8   264.7
    5003   265.2  5012.5  270.47  5032.6  272.23    5093  271.14    5165  275.18
    5234   270.1  5248.3  275.41  5284.3  270.42  5445.4  270.72  5455.5  268.52
  5465.5  271.15  5546.1   272.7  5556.2  276.06  5586.4  273.23  5591.7  267.91
  5606.5  267.41  5616.6  272.13  5646.8  272.63  5654.9  275.81  5666.5  277.52
#Mann= 5 ,-1 , 0
  4146.9     .16       0  4483.8     .16       0    4997     .07       0
    5003     .16       0  5654.9     .16       0
#XS Ineff= 2 , 0
                         5137.27           279.7
Permanent Ineff=
       F       F
Bank Sta=4962.1,5032.6
XS Rating Curve= 0 ,0
Exp/Cntr=0.3,0.1

Type RM Length L Ch R = 1 ,7538    ,602,602,602
BEGIN DESCRIPTION:
TOWN BRANCH CR TRIB 26.0
END DESCRIPTION:
XS GIS Cut Line= 3
       3812161.7     10482224.32      3813084.02     10482654.02
      3813186.32     10482691.64
#Sta/Elev= 30
  4512.4  304.85  4527.1  304.82  4598.3  300.76  4664.5  292.33    4795  279.53
  4920.4  271.67  4983.5  270.59    4989  269.98    4997  265.61  4999.8  265.11
    5003  265.61  5017.6  271.43    5172  269.12  5205.9  271.47  5223.2  269.27
  5228.8  270.64  5348.6  269.86  5457.5  272.16  5469.9  271.35  5480.4   266.8
  5491.9  266.73    5503  268.03  5508.7  272.16  5514.3  272.33  5537.2  271.37
  5557.1  267.88  5587.5  270.77  5599.8  267.77  5631.7  275.76  5638.9  275.98
#Mann= 6 ,-1 , 0
  4512.4     .16       0  4527.1     .05       0  4664.5     .16       0
    4997     .07       0    5003     .16       0  5638.9     .16       0
#XS Ineff= 2 , 0
                         5337.84          279.26
Permanent Ineff=
       F       F
Bank Sta=4920.4,5017.6
XS Rating Curve= 0 ,0
Exp/Cntr=0.3,0.1