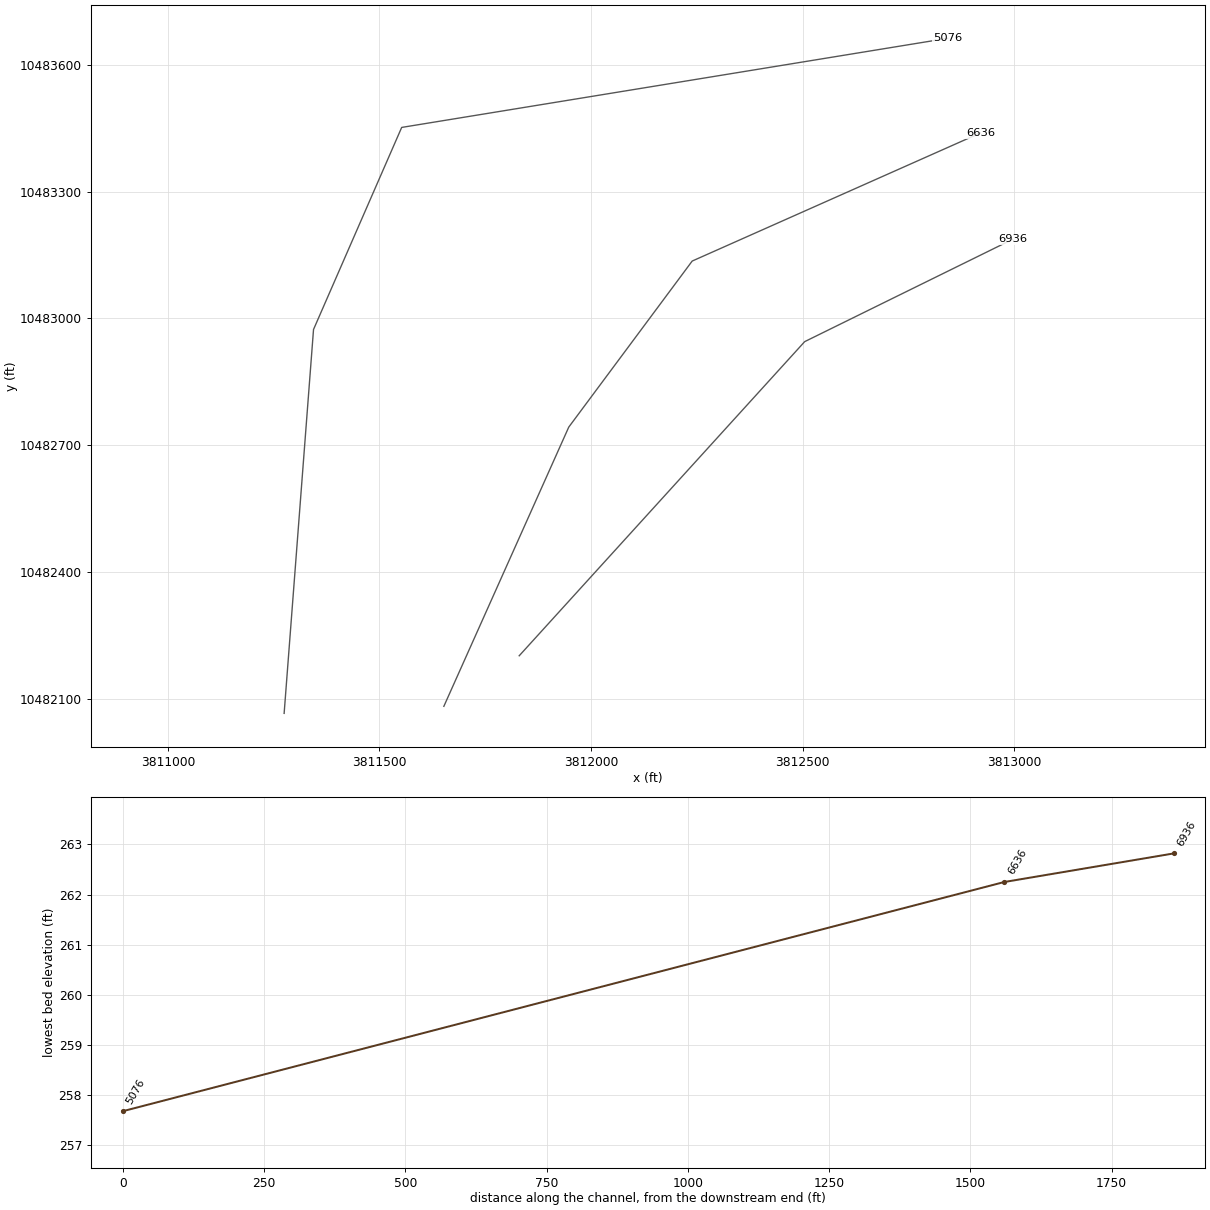
HEC-RAS study TOWN BRANCH CR TRIB.prj: TOWN BRANCH CR TRIB Base Level Engineering

--- TOWN BRANCH CR TRIB.g01 (geometry) --- (continued)

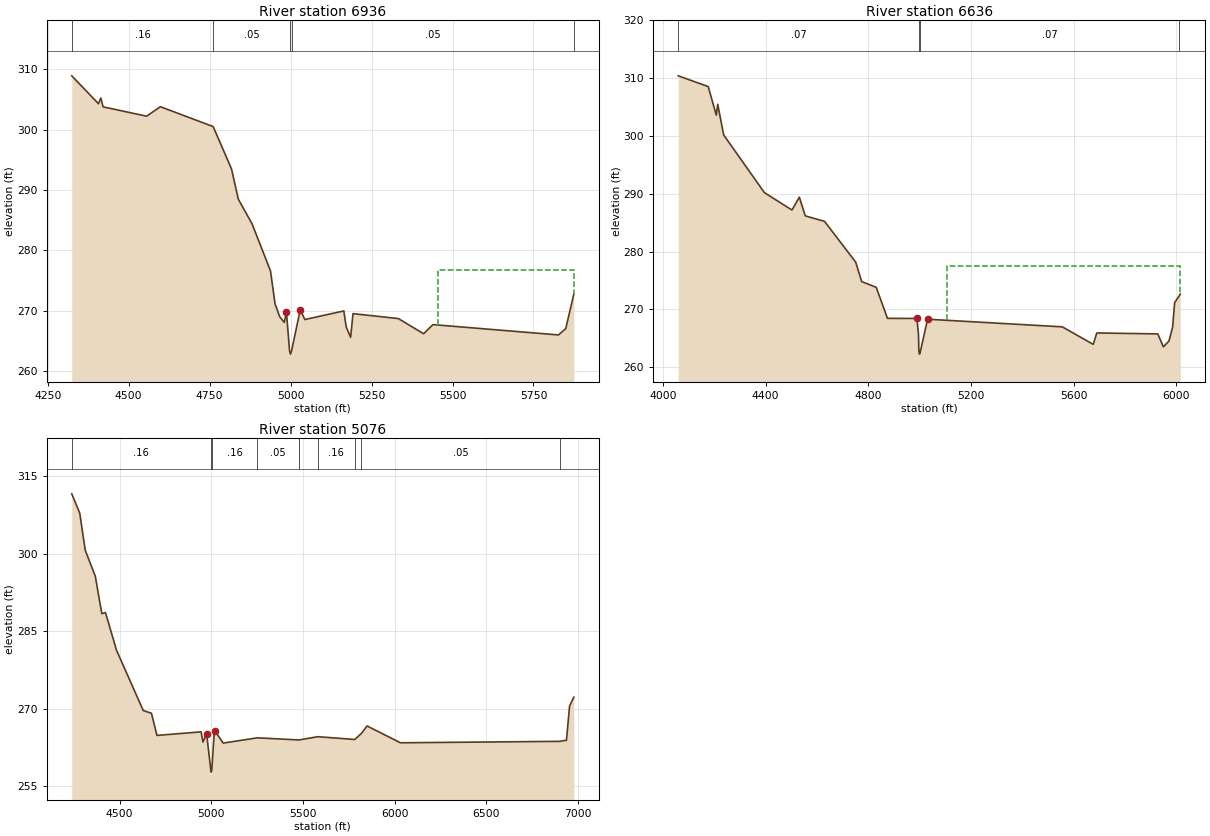
Type RM Length L Ch R = 1 ,6936    ,300,300,300
BEGIN DESCRIPTION:
Mapping XS 118f6cfe
END DESCRIPTION:
XS GIS Cut Line= 3
      3811830.29     10482203.04      3812504.79     10482945.26
      3812995.76     10483186.84
#Sta/Elev= 30
  4324.5  308.94  4406.9  304.32  4414.3  305.26  4421.1   303.8  4555.5  302.25
  4598.1  303.82    4761  300.53  4817.7  293.51  4838.7   288.5  4881.2   284.4
    4938  276.62  4952.2  271.13  4966.4  269.03  4980.6  268.08  4987.3  269.75
    4997  263.32  4999.8  262.82    5003  263.32  5029.9  270.18  5044.1  268.55
  5164.4  269.98  5171.8  267.33  5185.4   265.6  5192.8  269.53  5332.9  268.71
  5410.8   266.2  5439.6  267.71  5827.1     266  5849.6  267.04  5874.6  272.78
#Mann= 5 ,-1 , 0
  4324.5     .16       0    4761     .05       0    4997     .03       0
    5003     .05       0  5874.6     .16       0
#XS Ineff= 2 , 0
                         5454.89          276.73
Permanent Ineff=
       F       F
Bank Sta=4987.3,5029.9
XS Rating Curve= 0 ,0
Exp/Cntr=0.3,0.1

Type RM Length L Ch R = 1 ,6636    ,1560,1560,1560
BEGIN DESCRIPTION:
Mapping XS 3852ace9
END DESCRIPTION:
XS GIS Cut Line= 4
      3811652.24      10482083.6      3811947.38     10482743.35
      3812239.05     10483135.71      3812919.88     10483438.31
#Sta/Elev= 30
  4059.2   310.4    4176  308.54  4207.6   303.6  4213.1  305.48  4236.3  300.17
  4395.1  290.19  4502.5  287.18  4531.1  289.41  4554.3  286.17  4629.4  285.22
  4750.9  278.16  4774.1   274.8  4830.8  273.81  4874.7  268.44  4989.4  268.42
  4995.6  265.61    4997  262.75  4999.8  262.25    5003  262.75  5031.1  268.29
    5556  266.97  5676.4  263.94  5690.5  265.91  5928.1  265.75  5949.9  263.51
  5971.8  264.52  5985.9  266.92  5993.7  271.14  6009.2  272.18  6015.9  272.64
#Mann= 4 ,-1 , 0
  4059.2     .07       0    4997     .05       0    5003     .07       0
  6009.2     .07       0
#XS Ineff= 2 , 0
                         5105.11          277.57
Permanent Ineff=
       F       F
Bank Sta=4989.4,5031.1
XS Rating Curve= 0 ,0
Exp/Cntr=0.3,0.1

Type RM Length L Ch R = 1 ,5076    ,0,0,0
BEGIN DESCRIPTION:
TOWN BRANCH CR TRIB 25.0
END DESCRIPTION:
XS GIS Cut Line= 4
      3811274.84     10482066.93      3811344.29     10482974.03
      3811552.62     10483451.46      3812842.49     10483661.96
#Sta/Elev= 30
  4239.3  311.57  4282.7  307.85  4312.8  300.64  4367.6  295.62    4403  288.37
  4423.1  288.58  4483.3  281.28    4629  269.61  4673.8  269.08  4703.9  264.79
  4944.6  265.48  4954.6   263.5  4974.7  265.12    4997  258.18  4999.8  257.68
    5003  258.18  5014.8  264.72  5021.1  265.62    5065   263.3  5251.3  264.32
  5478.6  263.91    5581  264.54  5782.3     264  5818.9  265.19  5849.3  266.62
  6031.7  263.36  6899.2  263.64  6936.7  263.86  6953.7  270.49  6976.9  272.18
#Mann= 9 ,-1 , 0
  4239.3     .16       0    4997     .07       0    5003     .16       0
  5251.3     .05       0  5478.6     .12       0    5581     .16       0
  5782.3     .12       0  5818.9     .05       0  6899.2     .16       0
Bank Sta=4974.7,5021.1
XS Rating Curve= 0 ,0
Exp/Cntr=0.3,0.1

Chan Stop Cuts=-1
Use User Specified Reach Order=0
Composite Channel Slope=5