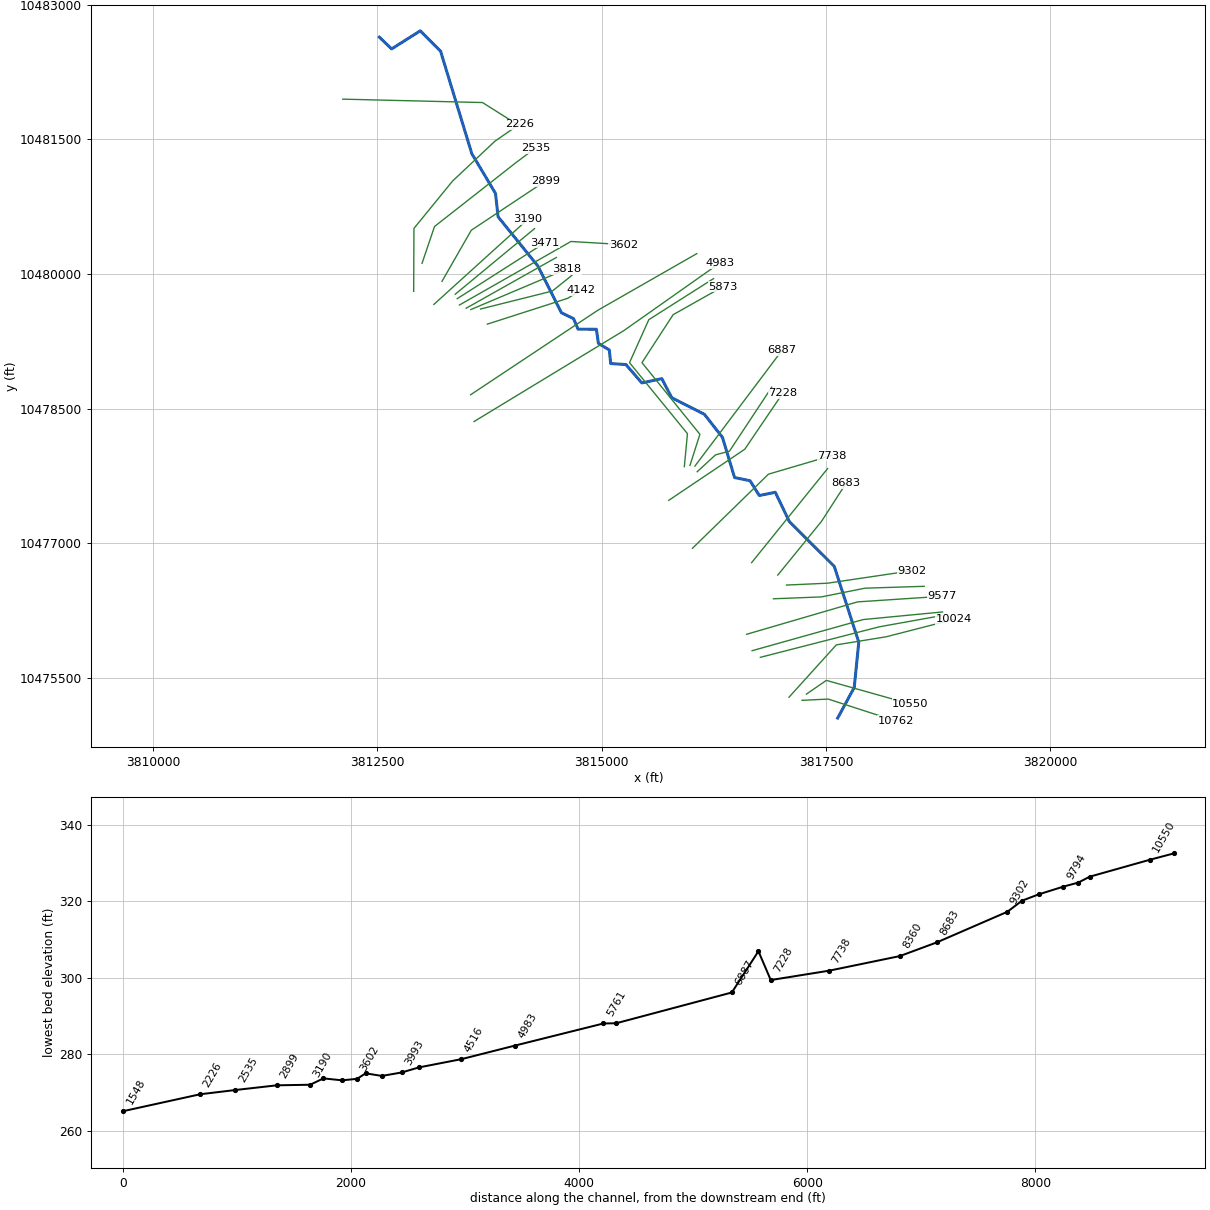
--- TOWN BRANCH.prj (project) ---

Proj Title=TOWN BRANCH Base Level Engineering
Current Plan=p01
Default Exp/Contr=0.3,0.1
English Units
Geom File=g01
Flow File=f01
Plan File=p01
Y Axis Title=Elevation
X Axis Title(PF)=Main Channel Distance
X Axis Title(XS)=Station
BEGIN DESCRIPTION:
TOWN BRANCH
END DESCRIPTION:
DSS Export Rating Curves= 0
DSS Export Rating Curve Sorted= 0
DSS Export Volume Flow Curves= 0
DXF OffsetX= 0
DXF OffsetY= 0
DXF ScaleX= 1
DXF ScaleY= 10

--- TOWN BRANCH.p01 (plan) ---

Plan Title=Multiple Run
Short Identifier=Multiple
Geom File=g01
Flow File=f01
Subcritical Flow
K Sum by GR= 0
Std Step Tol= 0.01
Critical Tol= 0.01
Num of Std Step Trials= 20
Max Error Tol= 0.3
Flow Tol Ratio= 0.001
Split Flow NTrial= 30
Split Flow Tol= 0.02
Split Flow Ratio= 0.02
Log Output Level= 0
Friction Slope Method= 1
Unsteady Friction Slope Method= 2
Unsteady Bridges Friction Slope Method= 1
Parabolic Critical Depth
Global Vel Dist=  1 , 1 , 1
Global Log Level= 0
CheckData=True
Encroach Param= -1, 0, 0, 0
BEGIN DESCRIPTION:
Multiple Run
END DESCRIPTION:

--- TOWN BRANCH.f01 (steady flow) ---

Flow Title=Multiple
Program Version=4.10
Number of Profiles= 7
Profile Names=10-year,25-year,50-year,1pct_min,100-year,1pct_plu,500-year
River Rch & RM=TOWN BRANCH,Reach-1         ,10762
     529     701     840     740    1001    1353    1424
River Rch & RM=TOWN BRANCH,Reach-1         ,4983
     812    1101    1340    1196    1618    2188    2367
River Rch & RM=TOWN BRANCH,Reach-1         ,4142
     812    1101    1340    1196    1618    2188    2367
Boundary for River Rch & Prof#=TOWN BRANCH,Reach-1         , 1
Up Type= 0
Dn Type= 3
Dn Slope=0.005
Boundary for River Rch & Prof#=TOWN BRANCH,Reach-1         , 2
Up Type= 0
Dn Type= 3
Dn Slope=0.005
Boundary for River Rch & Prof#=TOWN BRANCH,Reach-1         , 3
Up Type= 0
Dn Type= 3
Dn Slope=0.005
Boundary for River Rch & Prof#=TOWN BRANCH,Reach-1         , 4
Up Type= 0
Dn Type= 3
Dn Slope=0.005
Boundary for River Rch & Prof#=TOWN BRANCH,Reach-1         , 5
Up Type= 0
Dn Type= 3
Dn Slope=0.005
Boundary for River Rch & Prof#=TOWN BRANCH,Reach-1         , 6
Up Type= 0
Dn Type= 3
Dn Slope=0.005
Boundary for River Rch & Prof#=TOWN BRANCH,Reach-1         , 7
Up Type= 0
Dn Type= 3
Dn Slope=0.005
DSS Import GetInterval= 0
DSS Import GetPeak= 0
DSS Import FillOption= 0

--- TOWN BRANCH.g01 (geometry) ---

Geom Title=Existing Conditions
Program Version=4.10

River Reach=TOWN BRANCH     ,Reach-1
Reach XY= 30
        3817630.       10475050.      3817814.75       10475391.
       3817865.5       10475896.      3817592.25       10476741.
      3817091.25       10477241.        3816935.       10477567.
       3816756.5       10477531.       3816653.5       10477696.
        3816481.       10477731.        3816346.       10478179.
      3816145.32     10478435.56      3815780.39     10478621.33
      3815670.54     10478833.76      3815446.75       10478786.
      3815269.75       10478991.      3815100.25       10479002.
        3815085.       10479153.      3814963.25       10479227.
      3814940.75       10479384.      3814736.75       10479385.
        3814686.       10479503.       3814551.5       10479568.
      3814287.75       10480090.        3813845.       10480638.
        3813816.       10480899.      3813552.25       10481341.
      3813204.25       10482483.      3812977.61     10482710.63
       3812658.6     10482509.32       3812521.5       10482640.

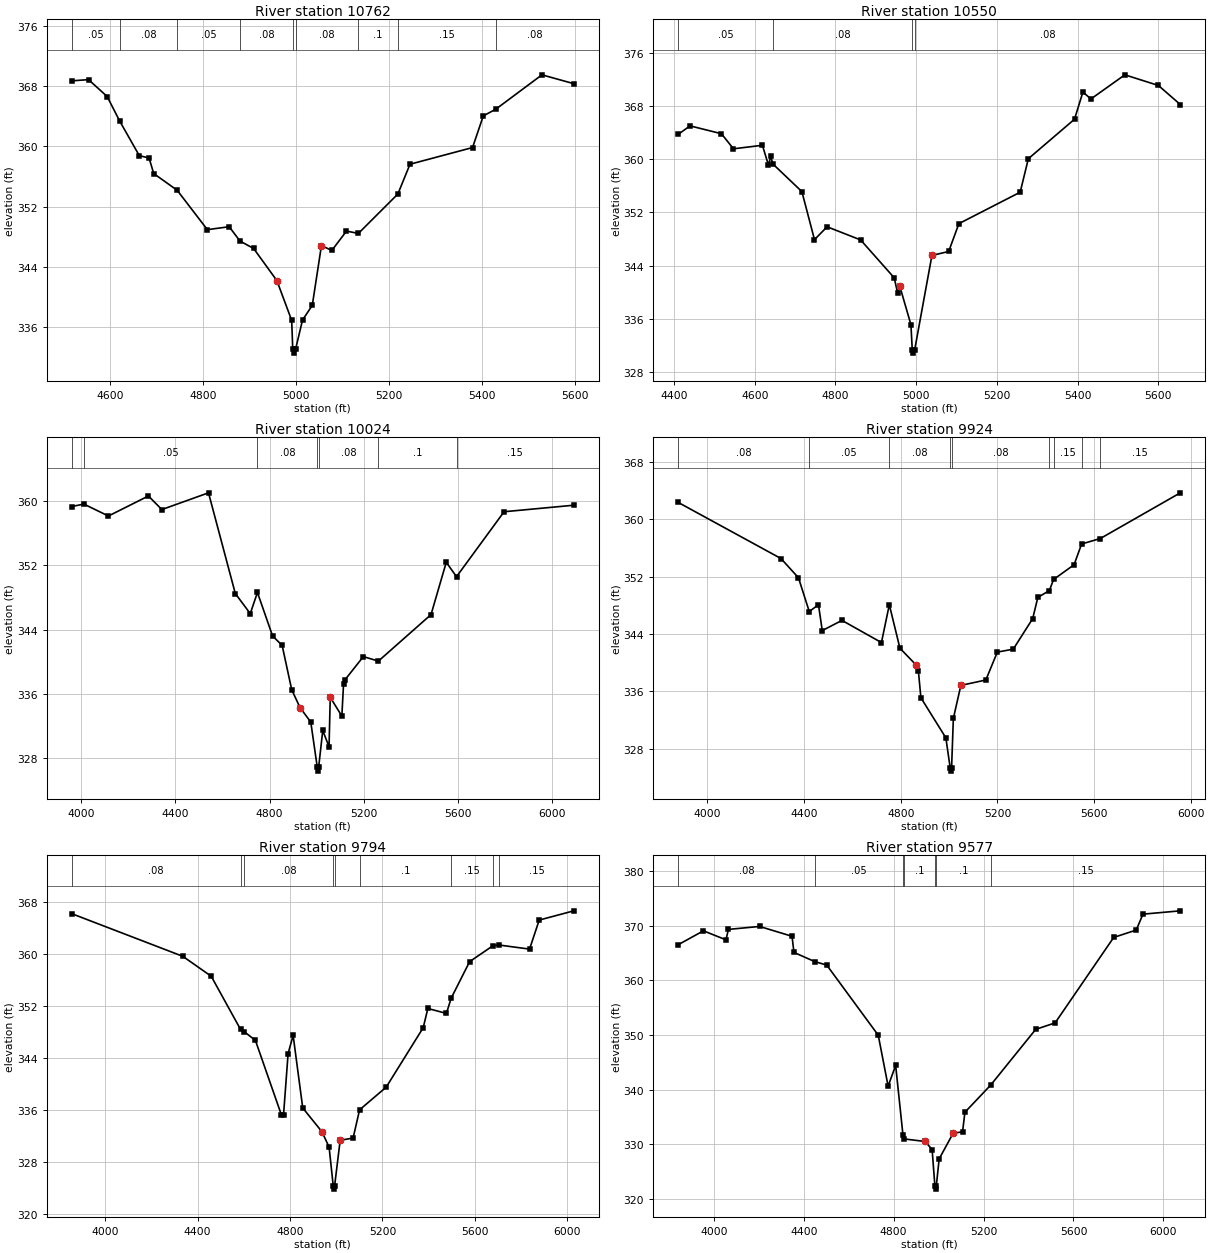
Type RM Length L Ch R = 1 ,10762   ,212,212,212
BEGIN DESCRIPTION:
TOWN BRANCH 20.0
END DESCRIPTION:
XS GIS Cut Line= 3
      3817233.52     10475248.08       3817525.2     10475261.97
      3818274.91     10475019.01
#Sta/Elev= 30
  4518.3  368.72  4554.4  368.88  4594.5  366.63  4621.4  363.37  4663.6  358.77
  4684.6  358.46  4694.6  356.39    4745  354.17    4810  348.93    4857  349.32
  4880.2  347.41  4909.5  346.43  4959.5  342.16  4991.4  336.86  4993.7  333.01
  4996.4  332.51  4999.7  333.01  5014.7  336.91  5035.7  338.86  5055.4  346.81
  5077.7  346.16  5109.3  348.74  5134.9  348.43  5219.8  353.67  5245.9  357.63
  5380.5  359.85  5403.6  364.06  5430.3  364.94  5529.8  369.52  5598.4  368.34
#Mann= 9 ,-1 , 0
  4518.3     .05       0  4621.4     .08       0    4745     .05       0
  4880.2     .08       0  4993.7     .07       0  4999.7     .08       0
  5134.9      .1       0  5219.8     .15       0  5430.3     .08       0
Bank Sta=4959.5,5055.4
XS Rating Curve= 0 ,0
Exp/Cntr=0.3,0.1

Type RM Length L Ch R = 1 ,10550   ,526,526,526
BEGIN DESCRIPTION:
TOWN BRANCH 19.0
END DESCRIPTION:
XS GIS Cut Line= 3
       3817282.1      10475317.5      3817504.36     10475470.31
      3818441.91      10475206.4
#Sta/Elev= 30
  4410.5  363.76  4439.8  365.03  4517.5  363.85  4547.3  361.58    4619  362.11
  4633.9  359.15    4640  360.47  4644.4  359.33  4716.8  355.14    4748  347.91
  4779.2  349.85  4862.3  347.87  4945.4  342.18    4954   339.9  4959.2  340.93
  4986.9  335.12  4990.2  331.34    4993  330.84  4996.2  331.34  5038.9  345.54
  5080.4  346.13  5105.7  350.32  5257.5  355.05  5277.8  360.09  5392.1  366.03
  5412.9  370.12  5432.8  369.08  5516.8  372.71  5599.9  371.11  5654.2  368.24
#Mann= 4 ,-1 , 0
  4410.5     .05       0  4644.4     .08       0  4990.2     .07       0
  4996.2     .08       0
Bank Sta=4959.2,5038.9
XS Rating Curve= 0 ,0
Exp/Cntr=0.3,0.1

Type RM Length L Ch R = 1 ,10024   ,100,100,100
BEGIN DESCRIPTION:
Mapping XS befa0f38
END DESCRIPTION:
XS GIS Cut Line= 4
      3817087.69      10475282.8      3817615.47     10475866.14
      3818171.03     10475956.42       3818926.3     10476150.43
#Sta/Elev= 30
  3961.3   359.3  4012.7   359.6  4116.8  358.12  4286.4  360.61  4343.2  358.92
  4541.2     361  4654.8  348.49  4718.3  345.99  4748.7  348.62  4812.9  343.22
  4853.5  342.04    4894  336.54  4929.3  334.32    4975  332.51  5002.4  326.92
  5005.2  326.42  5008.4  326.92  5025.7  331.47  5052.4  329.45  5057.5  335.59
  5106.7  333.26    5114  337.29    5119  337.73  5197.9  340.65  5261.6  340.09
  5484.9  345.87  5549.5  352.37    5593  350.58  5794.6  358.65  6090.6  359.46
#Mann= 7 ,-1 , 0
  3961.3     .08       0  4012.7     .05       0  4748.7     .08       0
  5002.4     .07       0  5008.4     .08       0  5261.6      .1       0
    5593     .15       0
Bank Sta=4929.3,5057.5
XS Rating Curve= 0 ,0
Exp/Cntr=0.3,0.1

Type RM Length L Ch R = 1 ,9924    ,130,130,130
BEGIN DESCRIPTION:
TOWN BRANCH 18.0
END DESCRIPTION:
XS GIS Cut Line= 3
      3816768.27     10475727.25      3818094.64     10476067.53
      3818789.06     10476192.52
#Sta/Elev= 30
  3880.6  362.33  4305.3  354.51  4377.5  351.83  4422.1  347.12  4460.1  348.08
  4475.8  344.47  4557.3  345.89  4720.4   342.8  4752.9  348.07  4796.7  342.02
  4862.7   339.7  4873.1  338.83  4883.4  335.11  4986.6  329.52  5004.3  325.38
    5007  324.88  5010.3  325.38  5017.6  332.23  5048.6  336.83  5151.8  337.58
  5199.3  341.47  5265.1  341.88  5345.5  346.14  5366.7   349.1  5414.4  350.04
  5431.6  351.59  5516.5  353.65  5547.6  356.54  5624.9   357.3  5955.5  363.67
#Mann= 9 ,-1 , 0
  3880.6     .08       0  4422.1     .05       0  4752.9     .08       0
  5004.3     .07       0  5010.3     .08       0  5414.4      .1       0
  5431.6     .15       0  5547.6      .1       0  5624.9     .15       0
Bank Sta=4862.7,5048.6
XS Rating Curve= 0 ,0
Exp/Cntr=0.3,0.1

Type RM Length L Ch R = 1 ,9794    ,217,217,217
BEGIN DESCRIPTION:
Mapping XS 05a2aea5
END DESCRIPTION:
XS GIS Cut Line= 3
      3816676.53     10475801.29      3817915.69     10476148.51
      3818798.96     10476233.15
#Sta/Elev= 30
  3854.9  366.14  4335.8  359.59  4458.8  356.53  4585.8  348.36    4601  348.03
  4650.1  346.68  4762.8  335.22    4772  335.27  4791.7  344.65  4813.5  347.45
  4855.1   336.3  4938.2  332.65  4969.3  330.28  4987.1  324.33  4989.8  323.83
  4993.1  324.33  5017.2  331.34  5073.2  331.67  5101.2  336.01  5216.4  339.49
  5376.8  348.63  5396.9  351.58  5477.2  350.82    5498  353.17  5577.7  358.77
  5680.1  361.25  5704.6  361.33  5837.3   360.7  5879.1  365.16  6029.1  366.58
#Mann= 9 ,-1 , 0
  3854.9     .08       0  4585.8     .05       0    4601     .08       0
  4987.1     .07       0  4993.1     .08       0  5101.2      .1       0
    5498     .15       0  5680.1      .1       0  5704.6     .15       0
Bank Sta=4938.2,5017.2
XS Rating Curve= 0 ,0
Exp/Cntr=0.3,0.1

Type RM Length L Ch R = 1 ,9577    ,146,146,146
BEGIN DESCRIPTION:
TOWN BRANCH 17.0
END DESCRIPTION:
XS GIS Cut Line= 3
      3816615.46     10475984.19      3817851.58     10476345.31
      3818795.33     10476407.76
#Sta/Elev= 30
  3841.6  366.54  3953.7  369.08  4054.1  367.43  4064.7  369.34  4203.6  369.88
  4347.8  368.08  4356.4  365.13  4448.5  363.45  4502.3  362.81  4731.4  349.97
  4775.3  340.65  4808.8  344.45  4841.5  331.65  4844.7     331  4939.8  330.52
  4971.1  329.05  4983.5   322.3  4986.3   321.8  4989.5   322.3  5002.3  327.33
  5064.8  332.05  5106.5  332.28  5116.9  335.87  5231.5  340.84  5431.8  351.04
  5518.3  352.23  5778.8  367.87    5879  369.22  5909.1  372.13  6075.2  372.74
#Mann= 7 ,-1 , 0
  3841.6     .08       0  4448.5     .05       0  4841.5     .08       0
  4844.7      .1       0  4983.5     .07       0  4989.5      .1       0
  5231.5     .15       0
Bank Sta=4939.8,5064.8
XS Rating Curve= 0 ,0
Exp/Cntr=0.3,0.1

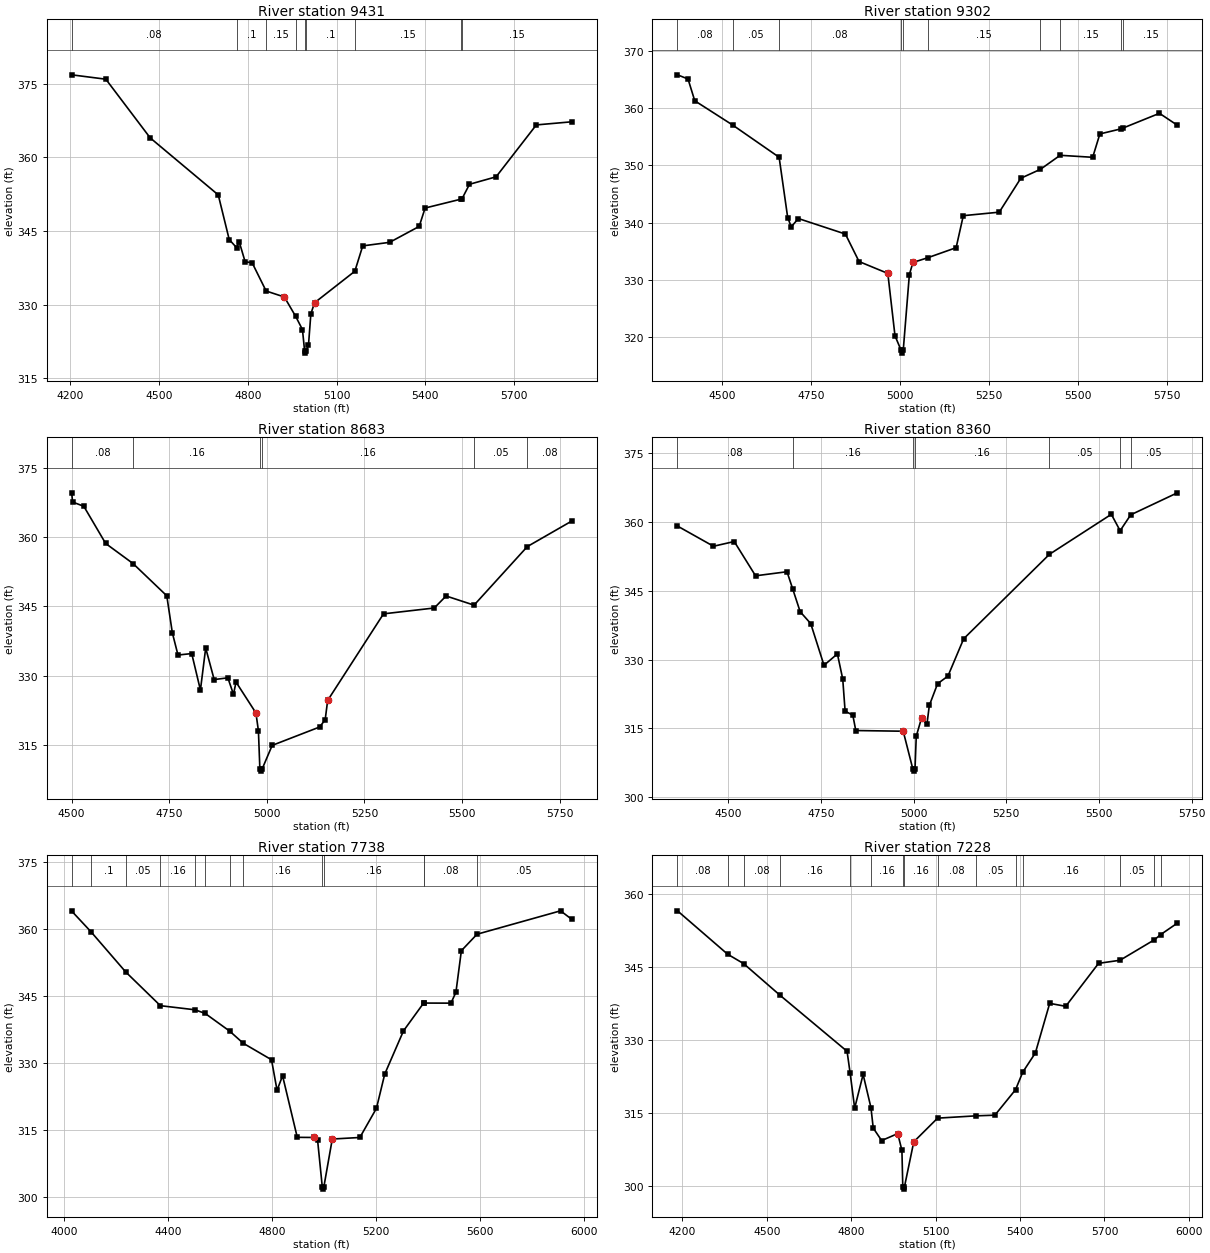
Type RM Length L Ch R = 1 ,9431    ,129,129,129
BEGIN DESCRIPTION:
Mapping XS 285ef461
END DESCRIPTION:
XS GIS Cut Line= 4
      3816914.11     10476380.03      3817448.81     10476400.86
      3817934.92     10476498.08      3818594.65     10476518.92
#Sta/Elev= 30
  4204.1  376.77  4319.7  375.88  4469.8  363.94    4700  352.34  4737.1  343.25
  4761.9  341.62  4770.6  342.85    4791  338.72  4814.4  338.56  4861.9  332.79
  4923.6  331.57    4962  327.61  4984.8  324.94    4992  320.65  4994.7  320.15
    4998  320.65  5005.2  321.76  5013.2  328.13  5025.6  330.39    5162  336.81
  5188.7  341.97  5279.7  342.69  5379.7  345.93  5399.7  349.67    5522  351.49
  5524.9  351.59  5549.8   354.5  5639.8  356.02  5775.9  366.58    5895  367.21
#Mann= 9 ,-1 , 0
  4204.1     .08       0  4761.9      .1       0  4861.9     .15       0
    4962      .1       0    4992     .07       0    4998      .1       0
    5162     .15       0    5522     .05       0  5524.9     .15       0
Bank Sta=4923.6,5025.6
XS Rating Curve= 0 ,0
Exp/Cntr=0.3,0.1

Type RM Length L Ch R = 1 ,9302    ,619,619,619
BEGIN DESCRIPTION:
TOWN BRANCH 16.0
END DESCRIPTION:
XS GIS Cut Line= 3
      3817059.93     10476532.81      3817518.25     10476553.64
      3818455.13     10476692.44
#Sta/Elev= 30
  4374.3  365.83    4404   365.1  4422.9   361.3  4529.8  357.05  4660.2  351.44
  4684.3  340.91  4694.3  339.29  4714.3  340.74  4846.6  338.03    4885  333.23
  4965.9  331.16  4986.1  320.26  5003.3  317.74  5006.1  317.24  5009.3  317.74
  5026.5  330.95  5036.6  333.07    5078  333.89    5158  335.65  5178.2  341.24
  5279.3  341.85  5339.9  347.77  5395.3  349.34  5450.6  351.78  5542.1  351.43
  5562.3  355.51  5620.7  356.38  5628.7  356.57  5729.9  359.11  5780.2  357.03
#Mann= 10 ,-1 , 0
  4374.3     .08       0  4529.8     .05       0  4660.2     .08       0
  5003.3     .07       0  5009.3     .08       0    5078     .15       0
  5395.3      .1       0  5450.6     .15       0  5620.7      .1       0
  5628.7     .15       0
Bank Sta=4965.9,5036.6
XS Rating Curve= 0 ,0
Exp/Cntr=0.3,0.1

Type RM Length L Ch R = 1 ,8683    ,323,323,323
BEGIN DESCRIPTION:
TOWN BRANCH 15.0
END DESCRIPTION:
XS GIS Cut Line= 3
      3816962.67     10476643.89      3817448.81     10477241.14
      3817725.62     10477670.21
#Sta/Elev= 30
    4500  369.69  4502.4  367.69  4531.1  366.77  4587.1  358.69  4657.2  354.33
  4743.7  347.32    4758  339.26  4772.4  334.45  4807.6  334.77  4829.9  326.84
  4843.4  335.98  4865.1  329.12  4900.2   329.5  4914.6   325.9  4921.1  328.58
  4972.1  321.87  4978.5  317.98  4982.2  309.73  4984.9  309.23  4988.2  309.73
  5013.7  314.82  5135.1  318.81  5149.5  320.38  5155.9  324.59    5299   343.4
    5429  344.67  5459.3  347.28    5531  345.29  5667.4  358.01  5780.7  363.53
#Mann= 6 ,-1 , 0
    4500     .08       0  4657.2     .16       0  4982.2     .07       0
  4988.2     .16       0    5531     .05       0  5667.4     .08       0
Bank Sta=4972.1,5155.9
XS Rating Curve= 0 ,0
Exp/Cntr=0.3,0.1

Type RM Length L Ch R = 1 ,8360    ,622,622,622
BEGIN DESCRIPTION:
TOWN BRANCH 14.0
END DESCRIPTION:
XS GIS Cut Line= 2
      3816671.04     10476782.82      3817518.26     10477831.43
#Sta/Elev= 30
  4363.4  359.15  4460.5  354.74  4516.5  355.77    4574  348.29  4658.8  349.18
  4674.6  345.32  4694.3  340.45  4722.8  337.86  4758.6  328.76  4794.7  331.25
  4809.1  325.76  4815.5  318.75  4836.3  317.87  4844.3  314.52  4972.2  314.37
    4998  306.16  5000.7  305.66    5004  306.16  5007.4  313.28  5021.8  317.29
  5036.2  315.88  5042.6  319.99  5064.9  324.74  5092.8   326.4  5135.3  334.55
  5366.7  352.99  5533.5  361.71  5557.2  358.13  5585.8   361.6  5711.5   366.4
#Mann= 7 ,-1 , 0
  4363.4     .08       0  4674.6     .16       0    4998     .07       0
    5004     .16       0  5366.7     .05       0  5557.2     .08       0
  5585.8     .05       0
Bank Sta=4972.2,5021.8
XS Rating Curve= 0 ,0
Exp/Cntr=0.3,0.1

Type RM Length L Ch R = 1 ,7738    ,510,510,510
BEGIN DESCRIPTION:
TOWN BRANCH 13.0
END DESCRIPTION:
XS GIS Cut Line= 3
      3816011.29     10476942.51      3816858.53     10477768.92
      3817565.73     10477976.92
#Sta/Elev= 30
  4029.5  364.12  4103.6  359.49  4237.3  350.47  4370.5  342.92  4503.6     342
  4542.4  341.19  4636.7  337.22  4688.7  334.51  4797.4  330.81  4818.7  323.98
  4839.9  327.22  4896.4  313.43  4960.2   313.4  4974.3  312.89  4992.5  302.33
  4995.2  301.83  4998.5  302.33  5030.9  313.05  5136.9   313.4  5200.6  319.93
  5232.5  327.61  5304.5  337.28  5381.8   343.5  5383.3  343.51  5486.9  343.49
    5506  345.93  5526.9  355.24  5587.1  358.93    5908  364.17  5950.2  362.31
#Mann= 13 ,-1 , 0
  4029.5     .08       0  4103.6      .1       0  4237.3     .05       0
  4370.5     .16       0  4503.6     .05       0  4542.4     .08       0
  4636.7     .05       0  4688.7     .16       0  4992.5     .07       0
  4998.5     .16       0  5381.8     .05       0  5383.3     .08       0
  5587.1     .05       0
Bank Sta=4960.2,5030.9
XS Rating Curve= 0 ,0
Exp/Cntr=0.3,0.1

Type RM Length L Ch R = 1 ,7228    ,108,108,108
BEGIN DESCRIPTION:
TOWN BRANCH 12.0
END DESCRIPTION:
XS GIS Cut Line= 3
       3815747.4     10477477.24      3816594.64     10478046.69
      3817018.27     10478671.73
#Sta/Elev= 30
  4182.9  356.63    4361  347.71    4418  345.77  4547.5  339.25  4785.4  327.74
  4796.5  323.18  4812.4  316.04  4842.4  322.98  4870.3  316.15  4878.4  311.95
  4908.3  309.38  4965.4  310.81  4980.3  307.36  4983.4  299.89  4986.1  299.39
  4989.4  299.89  5022.4  309.12    5107  313.99  5242.7  314.46  5310.6   314.6
    5384  319.84  5409.5  323.44  5454.4   327.4  5505.3   337.6  5562.2  336.99
    5679  345.83    5755  346.46  5877.4  350.68    5899  351.72  5958.8   354.1
#Mann= 15 ,-1 , 0
  4182.9     .08       0    4361     .05       0    4418     .08       0
  4547.5     .16       0  4796.5     .05       0  4870.3     .16       0
  4983.4     .07       0  4989.4     .16       0    5107     .08       0
  5242.7     .05       0    5384     .08       0  5409.5     .16       0
    5755     .05       0  5877.4     .16       0    5899     .05       0
Bank Sta=4965.4,5022.4
XS Rating Curve= 0 ,0
Exp/Cntr=0.3,0.1

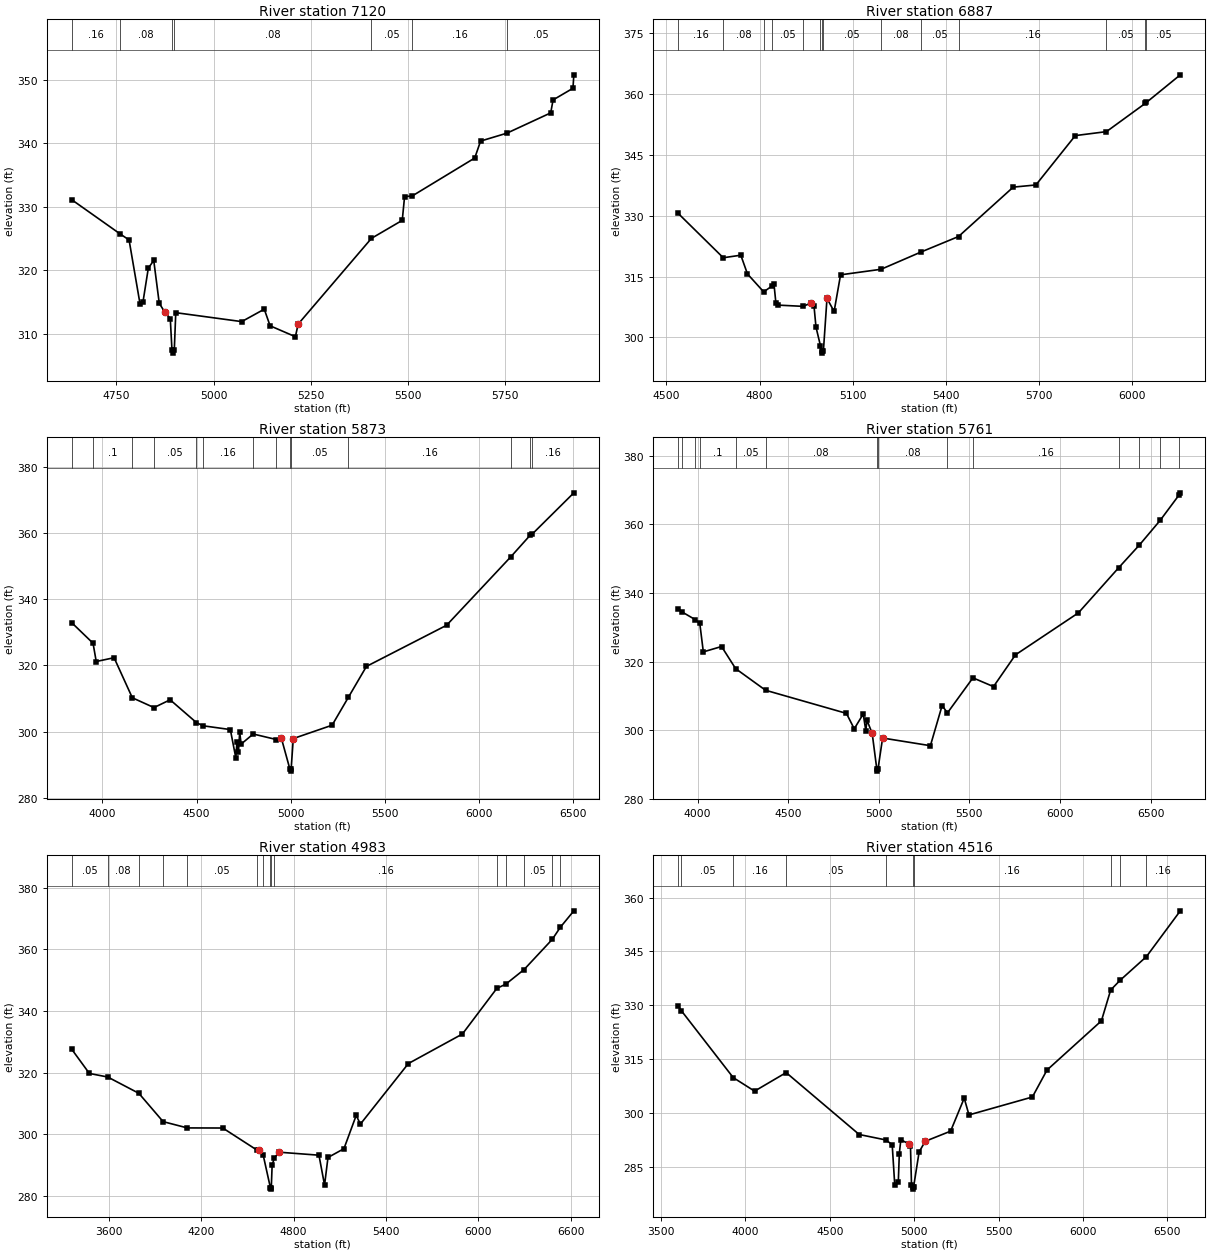
Type RM Length L Ch R = 1 ,7120    ,233,233,233
BEGIN DESCRIPTION:
Mapping XS 694107a3
END DESCRIPTION:
XS GIS Cut Line= 4
      3816064.86     10477796.37      3816268.01     10477983.89
      3816424.26     10478025.56      3816895.09     10478738.31
#Sta/Elev= 30
  4634.9  331.12  4759.6  325.72  4782.4  324.78  4810.8  314.62  4818.2     315
  4831.9  320.32  4845.9  321.55  4860.1  314.79  4874.3   313.4  4888.5  312.37
  4892.8  307.43  4895.6  306.93  4898.8  307.43  4902.6  313.31  5072.4   311.9
  5130.4  313.86  5145.4  311.24  5210.5  309.52  5217.7  311.51  5406.3  325.03
  5485.6  327.87  5491.6  331.62  5511.1  331.71  5672.2   337.7  5687.2  340.37
    5755  341.62  5867.8  344.82  5873.8  346.86    5925   348.7  5927.3  350.82
#Mann= 7 ,-1 , 0
  4634.9     .16       0  4759.6     .08       0  4892.8     .07       0
  4898.8     .08       0  5406.3     .05       0  5511.1     .16       0
    5755     .05       0
Bank Sta=4874.3,5217.7
XS Rating Curve= 0 ,0
Exp/Cntr=0.3,0.1

Type RM Length L Ch R = 1 ,6887    ,1014,1014,1014
BEGIN DESCRIPTION:
TOWN BRANCH 11.0
END DESCRIPTION:
XS GIS Cut Line= 2
      3816039.06     10477859.16       3817011.3     10479150.85
#Sta/Elev= 30
  4538.2  330.57  4683.2  319.65  4739.7  320.28  4761.1  315.66  4813.4  311.24
  4839.6  312.66  4846.4  313.23  4852.7  308.47    4861  307.97  4939.9  307.67
  4967.2  308.52  4975.5  307.64  4981.8  302.54  4996.1  297.98  4999.6  296.64
  5002.4  296.14  5005.6  296.64  5017.2  309.63  5040.1  306.41  5060.9  315.44
  5191.4  316.81  5319.2  321.04  5440.7  324.88  5616.9  337.06  5689.8  337.59
  5816.8  349.76  5917.1  350.74  6042.4  357.72  6045.6  357.92  6154.9  364.74
#Mann= 14 ,-1 , 0
  4538.2     .16       0  4683.2     .08       0  4813.4      .1       0
  4839.6     .05       0  4939.9      .1       0  4996.1     .05       0
  4999.6     .03       0  5005.6     .05       0  5191.4     .08       0
  5319.2     .05       0  5440.7     .16       0  5917.1     .05       0
  6042.4     .16       0  6045.6     .05       0
Bank Sta=4967.2,5017.2
XS Rating Curve= 0 ,0
Exp/Cntr=0.3,0.1

Type RM Length L Ch R = 1 ,5873    ,112,112,112
BEGIN DESCRIPTION:
TOWN BRANCH 9.0
END DESCRIPTION:
XS GIS Cut Line= 5
      3815983.53     10477866.15      3816094.64     10478213.36
      3815448.81     10479011.97      3815796.03     10479546.69
      3816351.57     10479859.19
#Sta/Elev= 30
  3837.3   332.9  3950.3  326.71  3967.2  321.19    4062  322.34  4158.9  310.24
  4273.9  307.28  4359.7  309.63  4499.5  302.74  4533.5  301.79  4679.5  300.64
  4708.3  292.18  4714.7  296.82  4722.7  293.97  4729.1  299.81  4737.1  296.27
    4801   299.3  4923.2  297.64  4949.7   298.2  4996.3  288.59  4999.1  288.09
  5002.3  288.59  5013.7  297.92    5220  301.96  5306.7  310.41  5402.3  319.71
  5828.1  332.14  6170.1  352.87  6271.2  359.28  6281.2  359.58  6503.9  372.13
#Mann= 14 ,-1 , 0
  3837.3     .16       0  3950.3      .1       0  4158.9     .08       0
  4273.9     .05       0  4499.5     .08       0  4533.5     .16       0
    4801     .08       0  4923.2     .05       0  4996.3     .04       0
  5002.3     .05       0  5306.7     .16       0  6170.1     .08       0
  6271.2     .05       0  6281.2     .16       0
Bank Sta=4949.7,5013.7
XS Rating Curve= 0 ,0
Exp/Cntr=0.3,0.1

Type RM Length L Ch R = 1 ,5761    ,778,778,778
BEGIN DESCRIPTION:
TOWN BRANCH 8.0
END DESCRIPTION:
XS GIS Cut Line= 5
      3815921.03     10477852.25      3815955.75     10478220.31
      3815309.92     10479011.97       3815525.2     10479491.14
      3816246.02     10479948.59
#Sta/Elev= 30
  3893.5  335.46  3913.4  334.51  3986.1  332.27  4012.3  331.18    4032  322.82
  4132.5  324.39  4210.1  317.94  4375.2  311.63  4821.6  304.88  4864.6  300.38
  4914.2  304.69  4928.5  299.88    4935  302.87  4963.7  299.04  4989.4  288.53
  4992.2  288.03  4995.4  288.53  5021.2  297.69  5284.9  295.45  5349.6  307.17
  5378.9  305.02  5519.6  315.25  5633.1  312.69  5754.3  321.96  6101.6  334.21
  6324.1  347.39  6438.4  354.02  6552.7  361.19  6656.9  368.59  6663.9  369.23
#Mann= 14 ,-1 , 0
  3893.5     .16       0  3913.4     .08       0  3986.1     .16       0
  4012.3      .1       0  4210.1     .05       0  4375.2     .08       0
  4989.4     .07       0  4995.4     .08       0  5378.9     .05       0
  5519.6     .16       0  6324.1     .08       0  6438.4     .05       0
  6552.7     .16       0  6656.9     .05       0
Bank Sta=4963.7,5021.2
XS Rating Curve= 0 ,0
Exp/Cntr=0.3,0.1

Type RM Length L Ch R = 1 ,4983    ,467,467,467
BEGIN DESCRIPTION:
TOWN BRANCH 7.0
END DESCRIPTION:
XS GIS Cut Line= 3
      3813577.25     10478355.71      3815247.42     10479369.61
      3816315.76     10480122.31
#Sta/Elev= 30
  3358.8   327.6  3473.1  319.77  3592.5  318.61  3794.3  313.33  3952.1  304.13
  4109.4  302.09  4339.5  302.06  4559.3  294.97  4572.1  294.89  4601.4  293.41
  4648.6  282.73  4651.3  282.23  4654.6  282.73  4660.1  290.08  4674.4   292.3
  4703.9  294.22  4964.2  293.24  5000.5  283.53  5022.7   292.5  5126.4  295.35
  5205.9  306.14  5233.3  303.33  5544.8  322.98  5895.8  332.57  6118.9  347.35
  6178.5  348.78  6296.2  353.48  6479.2  363.27  6531.8  367.21  6619.5  372.54
#Mann= 15 ,-1 , 0
  3358.8     .05       0  3592.5     .08       0  3794.3     .05       0
  3952.1     .16       0  4109.4     .05       0  4559.3     .16       0
  4601.4     .12       0  4648.6     .07       0  4654.6     .12       0
  4674.4     .16       0  6118.9     .05       0  6178.5     .08       0
  6296.2     .05       0  6479.2     .16       0  6531.8     .05       0
Bank Sta=4572.1,4703.9
XS Rating Curve= 0 ,0
Exp/Cntr=0.3,0.1

Type RM Length L Ch R = 1 ,4516    ,374,374,374
BEGIN DESCRIPTION:
TOWN BRANCH 6.0
END DESCRIPTION:
XS GIS Cut Line= 3
      3813539.12     10478654.35      3814955.75     10479595.31
      3816059.94     10480227.26
#Sta/Elev= 30
  3603.1  329.71  3621.8  328.43  3928.8  309.79  4055.2  306.02  4242.1  311.19
  4674.5  293.93  4832.3  292.41    4870   291.1    4885  279.94  4906.1  280.61
  4912.2  288.61  4921.1  292.47  4972.2  291.22  4978.2   290.8  4984.3  279.89
  4990.3   279.2    4993   278.7  4996.3   279.2  5029.4  289.06  5065.4  292.03
  5215.8  294.86  5296.4  304.06  5324.6  299.39    5700  304.38  5786.5  311.89
  6108.9  325.62  6163.6  334.21  6219.6  336.93  6375.3  343.52    6576  356.29
#Mann= 10 ,-1 , 0
  3603.1     .08       0  3621.8     .05       0  3928.8     .16       0
  4242.1     .05       0  4832.3     .16       0  4990.3     .07       0
  4996.3     .16       0  6163.6      .1       0  6219.6     .05       0
  6375.3     .16       0
Bank Sta=4972.2,5065.4
XS Rating Curve= 0 ,0
Exp/Cntr=0.3,0.1

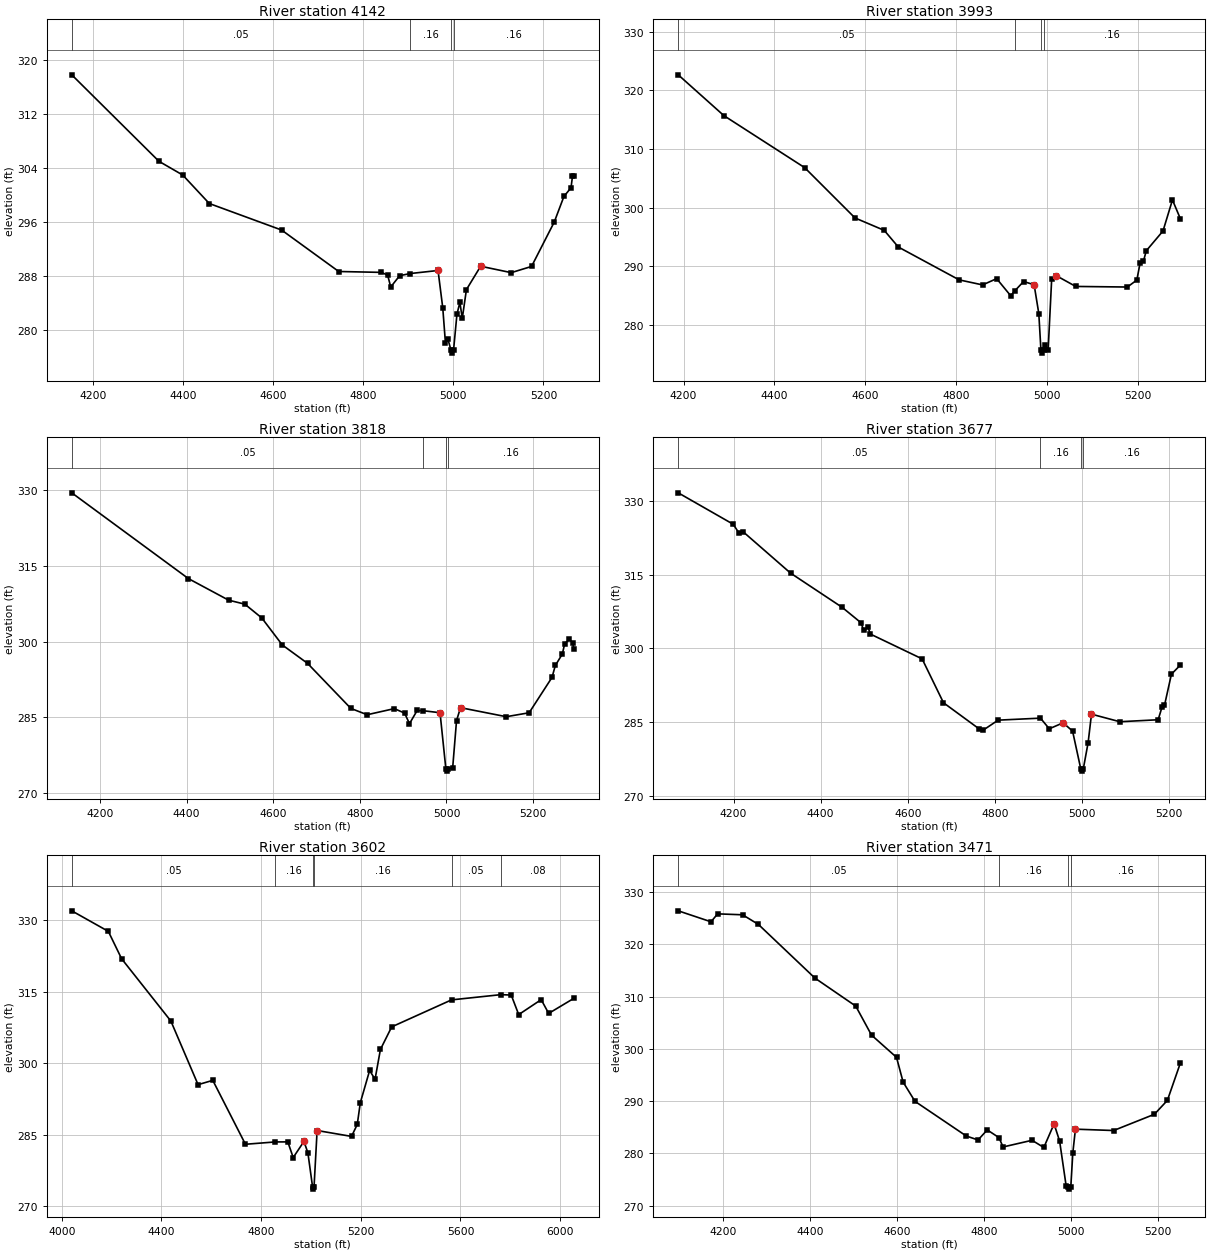
Type RM Length L Ch R = 1 ,4142    ,149,149,149
BEGIN DESCRIPTION:
Mapping XS 27e16fb3
END DESCRIPTION:
XS GIS Cut Line= 3
       3813725.3     10479441.43      3814617.66     10479727.89
      3814770.46     10479818.18
#Sta/Elev= 30
  4152.9  317.75  4346.5  304.94  4399.2  302.91  4458.2  298.69  4618.8  294.76
  4745.6  288.62  4840.1  288.49  4854.1  288.09  4861.1  286.33  4880.9     288
  4904.5  288.32  4966.1  288.77  4976.6  283.22  4982.5  278.04  4987.8  278.64
  4994.6  277.03  4997.4  276.53  5000.6  277.03  5008.1  282.31  5014.6  284.04
  5019.9  281.68  5029.1  285.94  5060.7   289.4  5128.6  288.45  5173.7  289.37
  5224.2  295.96  5245.6  299.74  5261.3  301.02  5264.6  302.74  5267.6  302.74
#Mann= 4 ,-1 , 0
  4152.9     .05       0  4904.5     .16       0  4994.6     .07       0
  5000.6     .16       0
Bank Sta=4966.1,5060.7
XS Rating Curve= 0 ,0
Exp/Cntr=0.3,0.1

Type RM Length L Ch R = 1 ,3993    ,175,175,175
BEGIN DESCRIPTION:
TOWN BRANCH 5.0
END DESCRIPTION:
XS GIS Cut Line= 3
      3813649.64      10479610.2      3814449.61     10479810.19
      3814668.73     10479985.49
#Sta/Elev= 30
  4188.4  322.63  4288.9  315.68  4466.7  306.82  4577.5  298.25  4641.9  296.13
  4672.8   293.3  4806.8   287.7  4858.4  286.84  4889.3  287.91  4920.2     285
  4929.4  285.84  4948.6  287.42  4971.8  286.87  4982.1  281.97  4986.8  275.72
  4989.5  275.22  4992.8  275.72  4994.9  276.57  5002.7  275.82  5010.4  287.78
  5020.2  288.43  5063.4  286.58  5177.1  286.48  5197.9  287.67  5205.1  290.58
  5212.3  290.84  5218.7  292.66  5255.5  296.03  5276.3  301.32  5293.6  298.14
#Mann= 4 ,-1 , 0
  4188.4     .05       0  4929.4     .16       0  4986.8     .07       0
  4992.8     .16       0
Bank Sta=4971.8,5020.2
XS Rating Curve= 0 ,0
Exp/Cntr=0.3,0.1

Type RM Length L Ch R = 1 ,3818    ,141,141,141
BEGIN DESCRIPTION:
Mapping XS 1aa7e8ef
END DESCRIPTION:
XS GIS Cut Line= 2
      3813541.69     10479603.75      3814608.93     10480055.71
#Sta/Elev= 30
  4135.1  329.48  4404.3  312.48  4497.2   308.2  4534.6  307.41  4573.7  304.68
  4621.1  299.32  4679.3  295.68  4779.4  286.74    4817  285.49  4879.6   286.7
  4903.3  285.82  4914.7  283.72  4932.4  286.33  4946.7  286.28  4985.2  285.89
  4998.6  274.81  5001.4  274.31  5004.6  274.81  5014.3  274.88  5023.3  284.33
  5032.5  286.89  5138.1   285.1  5190.9  285.88  5243.7  292.89  5251.4  295.26
  5267.4   297.5  5273.1   299.6    5284  300.43  5291.1   299.8  5294.1  298.55
#Mann= 4 ,-1 , 0
  4135.1     .05       0  4946.7     .16       0  4998.6     .07       0
  5004.6     .16       0
Bank Sta=4985.2,5032.5
XS Rating Curve= 0 ,0
Exp/Cntr=0.3,0.1

Type RM Length L Ch R = 1 ,3677    ,75,75,75
BEGIN DESCRIPTION:
Mapping XS cfaae24c
END DESCRIPTION:
XS GIS Cut Line= 2
      3813489.66     10479618.97      3814494.01     10480184.25
#Sta/Elev= 30
  4073.1  331.67  4199.3  325.27  4212.3  323.51  4222.2  323.73  4330.8  315.33
  4449.4  308.35  4492.7  305.21  4498.5  303.72  4508.6  304.28  4514.4   302.9
  4632.9  297.86    4682  288.92  4762.9  283.66    4773  283.34  4807.4  285.38
  4904.6  285.79  4924.8  283.62  4956.6  284.84  4978.3  283.15    4997   275.5
  4999.8     275    5003   275.5    5014  280.81  5021.7   286.6  5086.7  285.06
  5174.7  285.46  5183.6  288.04  5189.3   288.4  5205.2  294.74  5225.6  296.59
#Mann= 4 ,-1 , 0
  4073.1     .05       0  4904.6     .16       0    4997     .07       0
    5003     .16       0
Bank Sta=4956.6,5021.7
XS Rating Curve= 0 ,0
Exp/Cntr=0.3,0.1

Type RM Length L Ch R = 1 ,3602    ,131,131,131
BEGIN DESCRIPTION:
TOWN BRANCH 4.0
END DESCRIPTION:
XS GIS Cut Line= 3
      3813414.06     10479654.32      3814657.14     10480362.67
      3815240.47     10480327.95
#Sta/Elev= 30
    4040     332  4186.7  327.69    4240  321.94  4437.7  308.86  4546.9   295.5
    4606   296.4    4737  282.98  4856.6  283.47  4907.1  283.48  4928.7  280.19
  4971.9  283.58  4987.7  281.17  5006.4  274.06  5009.1  273.56  5012.4  274.06
  5024.7  285.87  5162.8  284.63  5185.8  287.14  5198.1  291.71  5235.5  298.48
  5257.2  296.62  5278.8  302.89    5324  307.63  5564.2   313.3  5762.7   314.4
  5803.8  314.31  5833.8  310.21    5924  313.35  5954.1  310.46  6055.1  313.62
#Mann= 6 ,-1 , 0
    4040     .05       0  4856.6     .16       0  5006.4     .07       0
  5012.4     .16       0  5564.2     .05       0  5762.7     .08       0
Bank Sta=4971.9,5024.7
XS Rating Curve= 0 ,0
Exp/Cntr=0.3,0.1

Type RM Length L Ch R = 1 ,3471    ,164,164,164
BEGIN DESCRIPTION:
Mapping XS 5f3e35f4
END DESCRIPTION:
XS GIS Cut Line= 2
      3813389.84     10479725.31      3814364.73     10480347.45
#Sta/Elev= 30
  4095.8  326.44  4171.3  324.34  4186.5  325.86  4244.1  325.68  4280.4  323.84
  4410.7  313.56  4504.7   308.2    4541  302.65  4598.6  298.39  4613.8  293.65
  4641.2  289.96  4759.3  283.33  4786.4  282.57  4807.6   284.5  4834.6  283.02
    4844  281.23  4910.8  282.51  4937.9  281.13  4961.5  285.65  4974.3  282.36
  4989.5  273.68  4994.1  273.66  4996.9  273.16  5000.1  273.66  5004.7  280.11
  5010.7  284.64  5098.7  284.38  5192.6  287.49  5222.5  290.15  5252.3  297.27
#Mann= 4 ,-1 , 0
  4095.8     .05       0  4834.6     .16       0  4994.1     .07       0
  5000.1     .16       0
Bank Sta=4961.5,5010.7
XS Rating Curve= 0 ,0
Exp/Cntr=0.3,0.1

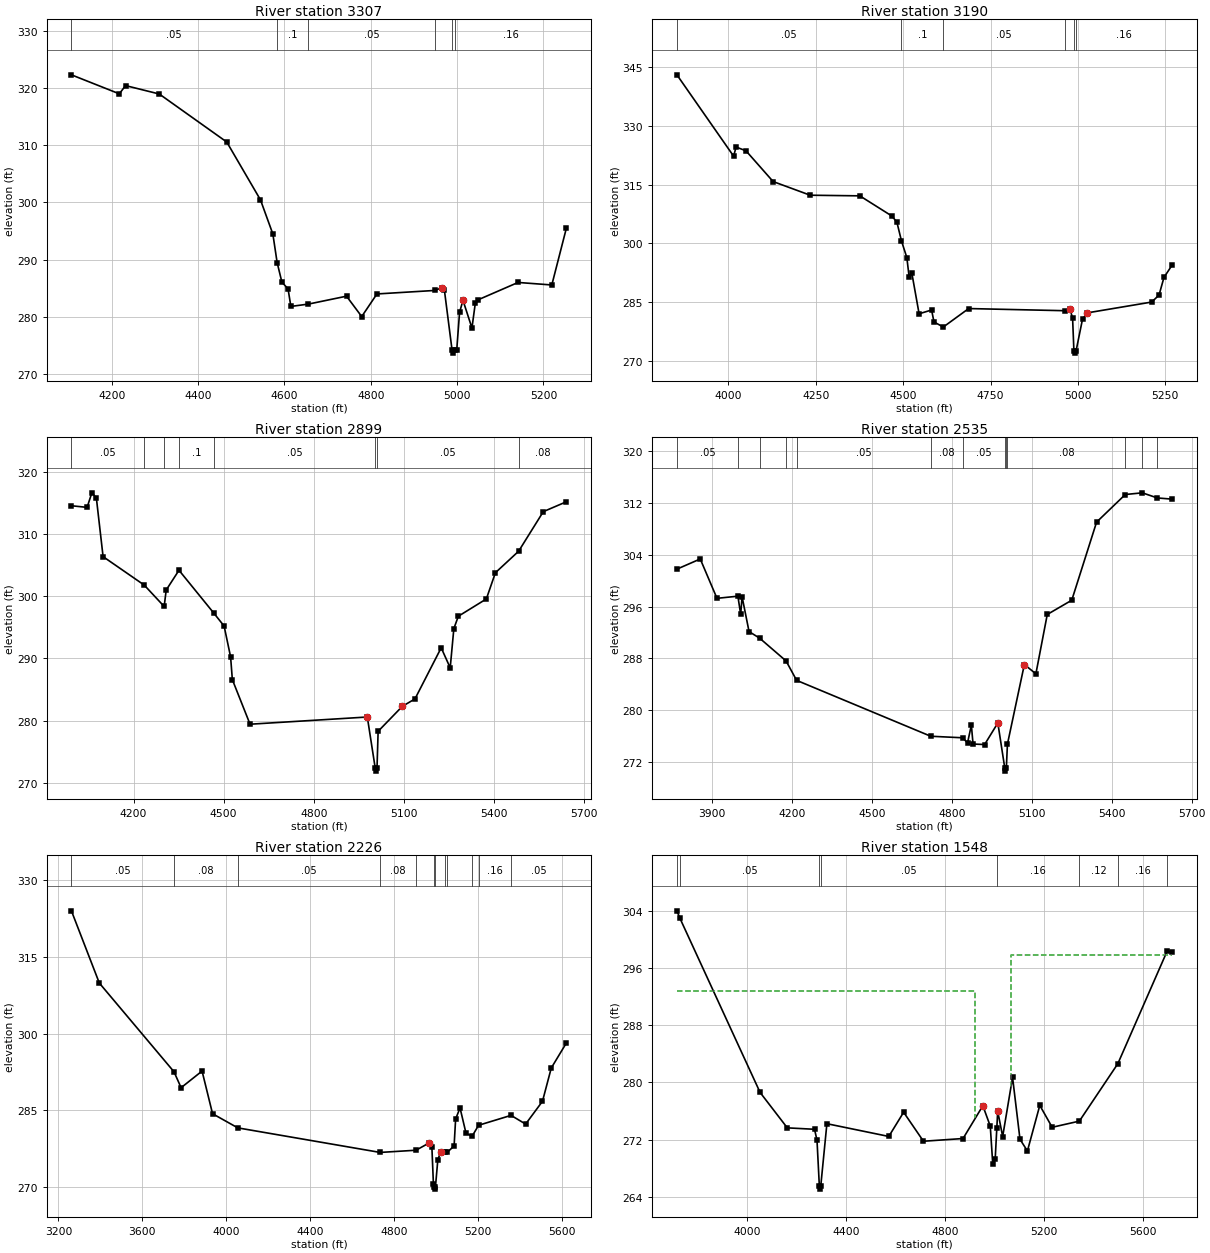
Type RM Length L Ch R = 1 ,3307    ,117,117,117
BEGIN DESCRIPTION:
Mapping XS 89707794
END DESCRIPTION:
XS GIS Cut Line= 2
      3813368.13     10479775.22      3814251.36     10480506.07
#Sta/Elev= 30
  4106.6   322.3  4217.6  318.98  4231.9  320.42  4310.1  318.95  4466.4  310.56
  4544.5  300.45  4573.2  294.48  4583.1  289.49    4594   286.1  4608.4  284.89
  4614.9  281.83  4655.6  282.24  4743.8  283.62    4779  280.06  4814.2  284.01
  4947.9  284.62    4964  285.07  4970.5  284.68  4988.3  274.17    4991  273.67
  4994.3  274.17  4999.1  274.25  5005.6  280.77  5013.5  282.91  5034.3  278.06
  5042.1   282.4  5048.6  282.99  5141.1  286.02  5219.3  285.58    5253   295.5
#Mann= 6 ,-1 , 0
  4106.6     .05       0  4583.1      .1       0  4655.6     .05       0
  4947.9     .16       0  4988.3     .07       0  4994.3     .16       0
Bank Sta=4964,5013.5
XS Rating Curve= 0 ,0
Exp/Cntr=0.3,0.1

Type RM Length L Ch R = 1 ,3190    ,291,291,291
BEGIN DESCRIPTION:
TOWN BRANCH 3.0
END DESCRIPTION:
XS GIS Cut Line= 2
      3813129.35     10479661.27      3814178.96     10480612.48
#Sta/Elev= 30
  3852.4     343  4014.7  322.25  4021.7  324.58  4050.1  323.62  4127.8  315.77
  4233.9  312.29  4375.9  312.13  4467.8  306.97    4482  305.41  4495.1  300.62
  4510.4   296.4  4517.1   291.4  4524.6  292.49  4545.5  282.05  4581.3  283.01
  4588.1  279.96  4614.8  278.67  4687.4  283.38  4962.4  282.83  4977.4  283.17
  4984.8  280.97  4988.6  272.51  4991.3  272.01  4994.6  272.51  5013.2  280.68
  5026.9  282.28  5211.2  285.04  5232.2  286.82  5246.3  291.32  5268.9  294.37
#Mann= 6 ,-1 , 0
  3852.4     .05       0  4495.1      .1       0  4614.8     .05       0
  4962.4     .16       0  4988.6     .07       0  4994.6     .16       0
Bank Sta=4977.4,5026.9
XS Rating Curve= 0 ,0
Exp/Cntr=0.3,0.1

Type RM Length L Ch R = 1 ,2899    ,364,364,364
BEGIN DESCRIPTION:
TOWN BRANCH 2.0
END DESCRIPTION:
XS GIS Cut Line= 3
      3813219.62     10479918.19      3813546.03     10480487.67
      3814371.59     10481035.73
#Sta/Elev= 30
  3993.3  314.57  4045.5  314.31  4061.3  316.65  4076.3  315.84  4098.7  306.38
  4235.7   301.8    4302  298.36  4308.8  301.01  4351.3  304.19  4466.9  297.31
  4501.5  295.21  4523.1  290.25  4528.9  286.59  4587.8  279.41  4978.1  280.57
  5004.4  272.36  5007.2  271.86  5010.4  272.36  5014.1  278.27  5094.7  282.29
  5136.7  283.48    5224  291.71    5254  288.48  5266.1  294.79  5281.1  296.79
  5374.3  299.57  5404.4  303.79  5481.7  307.25  5563.8  313.62  5640.6  315.21
#Mann= 8 ,-1 , 0
  3993.3     .05       0  4235.7     .16       0    4302     .05       0
  4351.3      .1       0  4466.9     .05       0  5004.4     .03       0
  5010.4     .05       0  5481.7     .08       0
Bank Sta=4978.1,5094.7
XS Rating Curve= 0 ,0
Exp/Cntr=0.3,0.1

Type RM Length L Ch R = 1 ,2535    ,309,309,309
BEGIN DESCRIPTION:
Mapping XS daeb4a7c
END DESCRIPTION:
XS GIS Cut Line= 4
       3812997.4     10480119.57      3813136.31     10480529.33
      3814039.08     10481237.67      3814261.27     10481404.31
#Sta/Elev= 30
  3767.8  301.78  3855.4  303.35  3918.2  297.28  3996.7  297.61  4007.2   294.8
  4012.4  297.53  4038.6  292.15  4078.2  291.14  4177.6  287.62  4217.1  284.63
  4720.6  276.01  4841.4  275.77  4858.6  274.96  4873.1  277.73  4879.4  274.81
  4922.8  274.73  4972.5  278.06  4998.4  271.13  5001.2  270.63  5004.4  271.13
  5008.5  274.79    5072  287.07  5115.3  285.64    5158  294.79    5250  296.99
  5343.1  309.03  5450.9  313.29  5514.9  313.55  5571.1  312.76  5625.7  312.58
#Mann= 13 ,-1 , 0
  3767.8     .05       0  3996.7      .1       0  4078.2     .05       0
  4177.6     .08       0  4217.1     .05       0  4720.6     .08       0
  4841.4     .05       0  4998.4     .04       0  5004.4     .05       0
  5008.5     .08       0  5450.9     .15       0  5514.9      .1       0
  5571.1     .15       0
Bank Sta=4972.5,5072
XS Rating Curve= 0 ,0
Exp/Cntr=0.3,0.1

Type RM Length L Ch R = 1 ,2226    ,678,678,678
BEGIN DESCRIPTION:
Mapping XS c3f54729
END DESCRIPTION:
XS GIS Cut Line= 5
      3812904.06     10479807.05      3812907.14      10480508.5
       3813337.7     10481036.28      3813809.92     10481480.72
      3814080.79     10481668.25
#Sta/Elev= 30
  3261.9  324.04    3395  309.89  3751.1  292.51    3785  289.39    3885  292.65
    3935  284.29  4055.4  281.52  4734.3  276.71  4905.3  277.14  4966.8  278.54
    4981  277.81  4988.3  270.57  4992.2  270.02  4994.9  269.52  4998.2  270.02
  5009.3  275.23  5023.5  276.89  5041.6  276.74  5054.5  276.74    5087  277.98
  5094.3  283.26  5115.3  285.43  5143.7  280.48  5172.7  279.87  5203.8  282.03
  5358.6  283.97  5428.1  282.26  5508.5  286.73  5550.4  293.25  5622.4  298.15
#Mann= 12 ,-1 , 0
  3261.9     .05       0  3751.1     .08       0  4055.4     .05       0
  4734.3     .08       0  4905.3     .05       0  4992.2     .03       0
  4998.2     .05       0  5041.6     .08       0  5054.5     .16       0
  5172.7     .08       0  5203.8     .16       0  5358.6     .05       0
Bank Sta=4966.8,5023.5
XS Rating Curve= 0 ,0
Exp/Cntr=0.3,0.1

Type RM Length L Ch R = 1 ,1548    ,0,0,0
BEGIN DESCRIPTION:
TOWN BRANCH 1.0
END DESCRIPTION:
XS GIS Cut Line= 3
      3812113.65     10481949.21      3813671.03     10481911.28
      3814045.28     10481675.64
#Sta/Elev= 30
  3716.6  303.96    3728  302.98  4052.7  278.59  4162.7  273.64  4272.7  273.44
  4282.7  271.92  4292.1  265.58  4294.9  265.08  4298.1  265.58  4322.7  274.22
  4572.8  272.44  4632.8  275.82  4712.9  271.77  4872.9  272.15  4952.9  276.73
  4982.9  273.88  4992.9   268.6  5002.9  269.34  5009.3  273.58  5012.9  275.96
    5033  272.43    5073  280.69    5103  272.04    5133  270.41    5183  276.78
    5233  273.72  5342.9  274.58  5498.5  282.61  5697.1  298.29  5716.7  298.19
#Mann= 8 ,-1 , 0
  3716.6     .16       0    3728     .05       0  4292.1     .03       0
  4298.1     .05       0  5009.3     .16       0  5342.9     .12       0
  5498.5     .16       0  5697.1     .05       0
#XS Ineff= 2 , 0
         4922.02  292.76 5066.19          297.72
Permanent Ineff=
       F       F
Bank Sta=4952.9,5012.9
XS Rating Curve= 0 ,0
Exp/Cntr=0.3,0.1

Chan Stop Cuts=-1
Use User Specified Reach Order=0
Composite Channel Slope=5