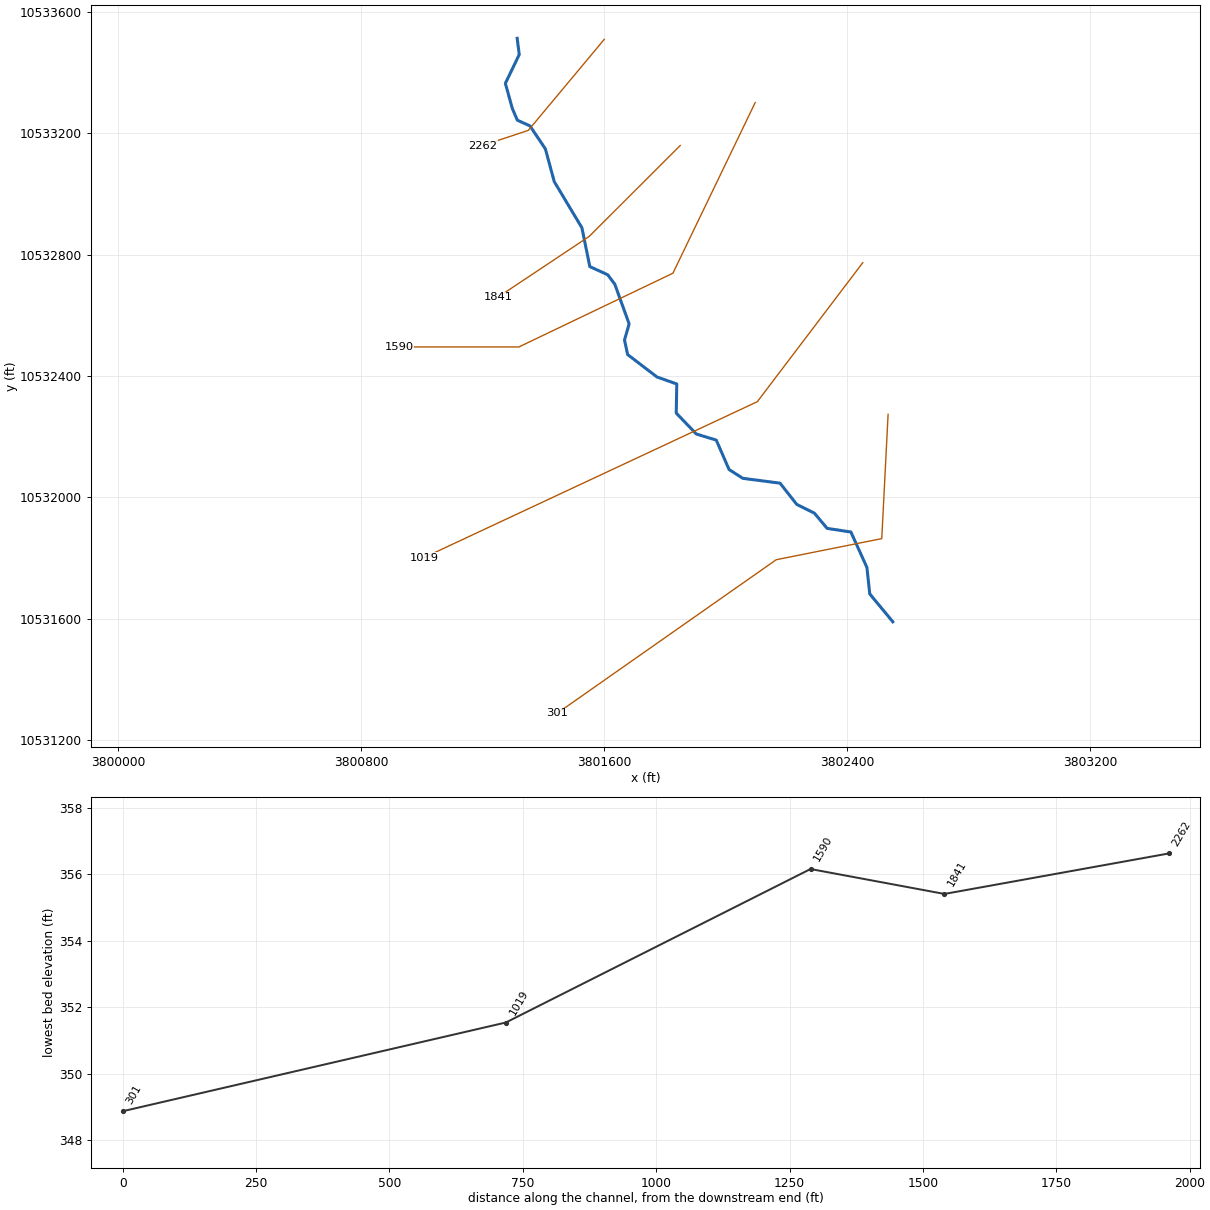
--- TWO MILE BRANCH.prj (project) ---

Proj Title=TWO MILE BRANCH Base Level Engineering
Current Plan=p01
Default Exp/Contr=0.3,0.1
English Units
Geom File=g01
Flow File=f01
Plan File=p01
Y Axis Title=Elevation
X Axis Title(PF)=Main Channel Distance
X Axis Title(XS)=Station
BEGIN DESCRIPTION:
TWO MILE BRANCH
END DESCRIPTION:
DSS Export Rating Curves= 0
DSS Export Rating Curve Sorted= 0
DSS Export Volume Flow Curves= 0
DXF OffsetX= 0
DXF OffsetY= 0
DXF ScaleX= 1
DXF ScaleY= 10

--- TWO MILE BRANCH.p01 (plan) ---

Plan Title=Multiple Run
Short Identifier=Multiple
Geom File=g01
Flow File=f01
Subcritical Flow
K Sum by GR= 0
Std Step Tol= 0.01
Critical Tol= 0.01
Num of Std Step Trials= 20
Max Error Tol= 0.3
Flow Tol Ratio= 0.001
Split Flow NTrial= 30
Split Flow Tol= 0.02
Split Flow Ratio= 0.02
Log Output Level= 0
Friction Slope Method= 1
Unsteady Friction Slope Method= 2
Unsteady Bridges Friction Slope Method= 1
Parabolic Critical Depth
Global Vel Dist=  1 , 1 , 1
Global Log Level= 0
CheckData=True
Encroach Param= -1, 0, 0, 0
BEGIN DESCRIPTION:
Multiple Run
END DESCRIPTION:

--- TWO MILE BRANCH.f01 (steady flow) ---

Flow Title=Multiple
Number of Profiles=7
Profile Names=10-year,25-year,50-year,1pct_min,100-year,1pct_plu,500-year
River Rch & RM= TWO MILE BRANCH,Reach-1,2262
     564     759     920     819    1108    1498    1612
River Rch & RM= TWO MILE BRANCH,Reach-1,1590
     775    1060    1298    1168    1579    2136    2346
Boundary for River Rch & Prof#=TWO MILE BRANCH,Reach-1,1
Up Type=0
Dn Type=3
Dn Slope=0.005
Boundary for River Rch & Prof#=TWO MILE BRANCH,Reach-1,2
Up Type=0
Dn Type=3
Dn Slope=0.005
Boundary for River Rch & Prof#=TWO MILE BRANCH,Reach-1,3
Up Type=0
Dn Type=3
Dn Slope=0.005
Boundary for River Rch & Prof#=TWO MILE BRANCH,Reach-1,4
Up Type=0
Dn Type=3
Dn Slope=0.005
Boundary for River Rch & Prof#=TWO MILE BRANCH,Reach-1,5
Up Type=0
Dn Type=3
Dn Slope=0.005
Boundary for River Rch & Prof#=TWO MILE BRANCH,Reach-1,6
Up Type=0
Dn Type=3
Dn Slope=0.005
Boundary for River Rch & Prof#=TWO MILE BRANCH,Reach-1,7
Up Type=0
Dn Type=3
Dn Slope=0.005

--- TWO MILE BRANCH.g01 (geometry) ---

Geom Title=Existing Conditions
Program Version=4.10

River Reach=TWO MILE BRANCH ,Reach-1
Reach XY= 30
      3801312.87      10533513.5      3801319.75       10533460.
        3801274.       10533365.        3801297.       10533282.
      3801313.53     10533243.61      3801355.06     10533224.83
      3801405.75       10533149.        3801435.       10533041.
        3801526.       10532889.        3801552.       10532761.
        3801611.       10532734.      3801634.25       10532703.
       3801681.5       10532572.      3801666.25       10532519.
       3801676.5       10532471.      3801773.25       10532397.
      3801838.25       10532374.       3801836.5       10532278.
      3801902.75       10532209.      3801968.25       10532189.
       3802010.5       10532092.      3802055.75       10532063.
      3802178.25       10532047.      3802233.25       10531977.
       3802291.5       10531948.      3802333.25       10531898.
       3802411.5       10531886.      3802464.25       10531769.
       3802473.5       10531682.       3802549.5       10531590.

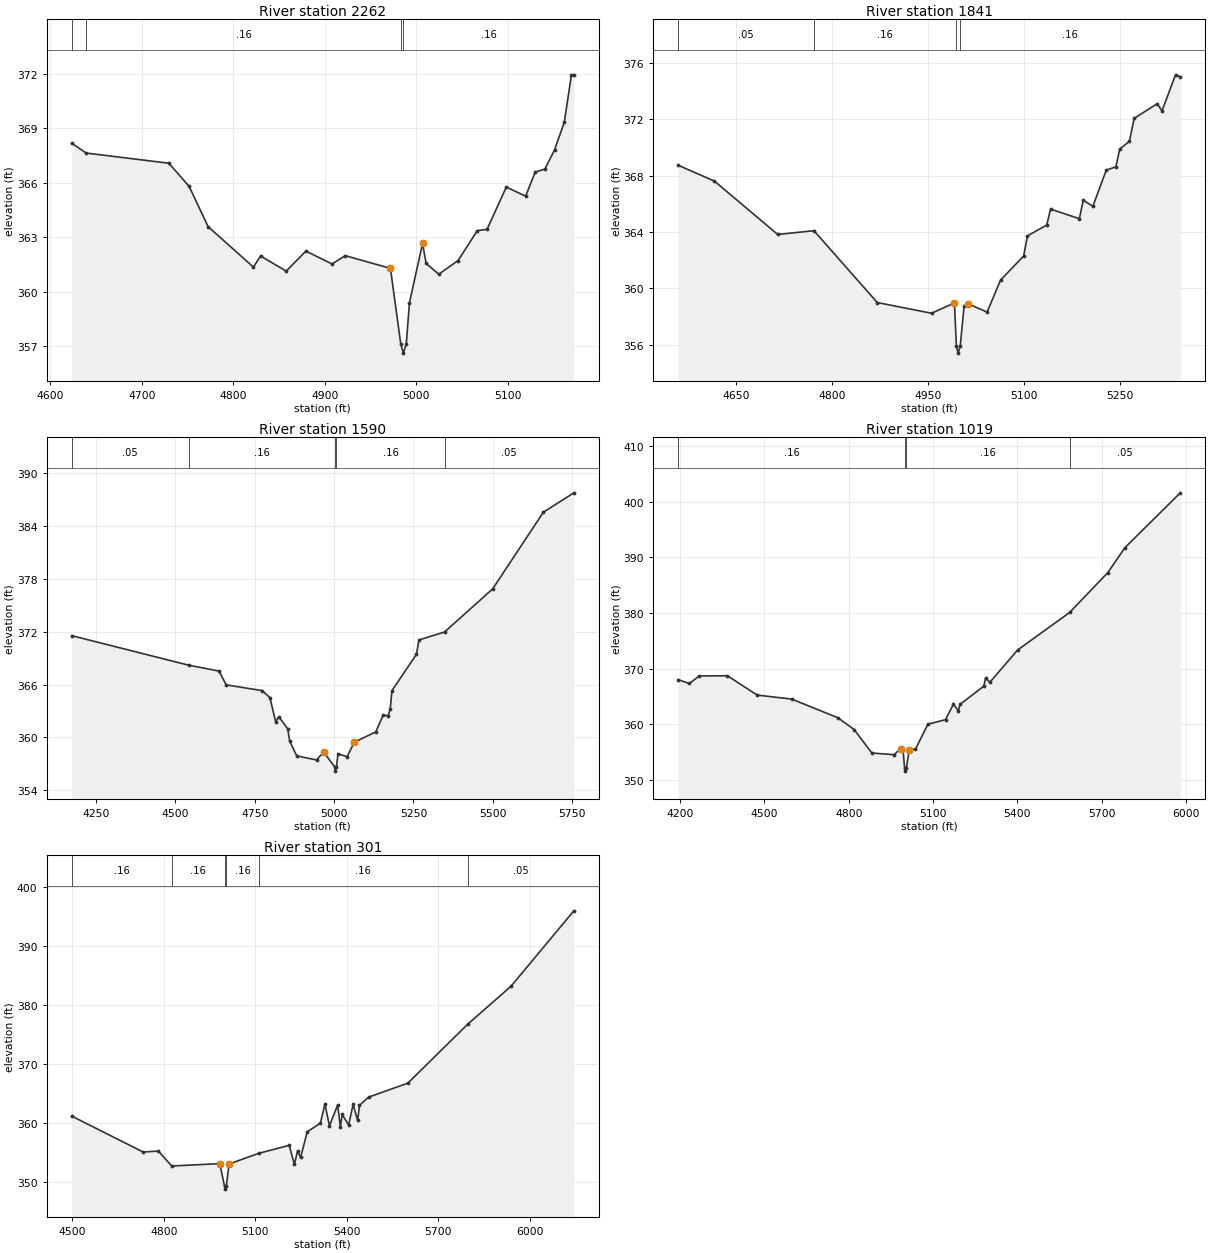
Type RM Length L Ch R = 1 ,2262    ,421,421,421
BEGIN DESCRIPTION:
TWO MILE BRANCH 4.0
END DESCRIPTION:
XS GIS Cut Line= 3
      3801599.59     10533510.17      3801349.61     10533210.19
      3801199.61     10533160.19
#Sta/Elev= 30
  4623.6  368.17  4639.3  367.63  4729.7  367.07  4751.8   365.8  4772.6  363.58
  4822.1  361.36  4829.9  361.97  4857.9  361.14  4879.4  362.24    4908  361.53
  4922.3  361.99  4971.8  361.29  4983.1  357.13  4985.9  356.63  4989.1  357.13
  4992.6  359.41  5006.9  362.66  5010.8  361.56  5024.6  360.97  5045.7  361.72
  5066.8  363.37  5077.3  363.43  5098.4  365.76  5119.5  365.26    5130  366.58
  5140.6  366.75  5151.1   367.8  5161.7  369.31  5169.6  371.93  5172.2  371.93
#Mann= 4 ,-1 , 0
  4623.6     .05       0  4639.3     .16       0  4983.1     .07       0
  4985.9     .16       0
Bank Sta=4971.8,5006.9
XS Rating Curve= 0 ,0
Exp/Cntr=0.3,0.1

Type RM Length L Ch R = 1 ,1841    ,251,251,251
BEGIN DESCRIPTION:
TWO MILE BRANCH 3.0
END DESCRIPTION:
XS GIS Cut Line= 3
      3801849.59     10533160.17      3801549.61     10532860.19
       3801249.6     10532660.18
#Sta/Elev= 30
  4559.3  368.74  4615.8  367.62  4714.8  363.83  4771.4   364.1  4870.4     359
  4955.2  358.24    4991  358.97  4994.1  355.91  4996.8  355.41  5000.1  355.91
  5006.1  358.73  5012.1  358.92  5042.1  358.32  5063.2   360.6  5099.2   362.3
  5105.2  363.73  5135.3   364.5  5141.3  365.63  5186.3  364.95  5192.4  366.26
  5207.4  365.83  5228.4   368.4  5243.4  368.63  5249.4  369.89  5264.5  370.44
    5272  372.07    5308  373.11  5315.5   372.6  5336.6  375.16  5344.1  375.02
#Mann= 4 ,-1 , 0
  4559.3     .05       0  4771.4     .16       0  4994.1     .07       0
  5000.1     .16       0
Bank Sta=4991,5012.1
XS Rating Curve= 0 ,0
Exp/Cntr=0.3,0.1

Type RM Length L Ch R = 1 ,1590    ,571,571,571
BEGIN DESCRIPTION:
TWO MILE BRANCH 2.0
END DESCRIPTION:
XS GIS Cut Line= 4
      3802096.44     10533301.71      3801825.58     10532739.18
      3801318.64     10532496.12      3800923.69     10532496.12
#Sta/Elev= 30
  4173.6  371.55  4541.3   368.2  4637.4  367.53    4660  365.96  4773.1  365.31
  4797.9   364.5  4815.7  361.78  4825.8  362.33    4854  360.96    4860  359.58
  4882.2  357.89  4944.6  357.43  4967.2  358.34  5001.2  356.66  5003.9  356.16
  5007.2  356.66  5012.5  358.13  5040.7   357.8  5063.4  359.44  5131.4  360.62
    5154   362.5  5170.5  362.47  5176.7  363.23  5182.2  365.31  5259.3  369.43
  5267.3  371.06    5348  371.97  5499.2  376.86  5659.2  385.58  5755.1  387.78
#Mann= 5 ,-1 , 0
  4173.6     .05       0  4541.3     .16       0  5001.2     .07       0
  5007.2     .16       0    5348     .05       0
Bank Sta=4967.2,5063.4
XS Rating Curve= 0 ,0
Exp/Cntr=0.3,0.1

Type RM Length L Ch R = 1 ,1019    ,718,718,718
BEGIN DESCRIPTION:
Mapping XS e64d569e
END DESCRIPTION:
XS GIS Cut Line= 3
      3802450.61     10532773.93      3802103.36     10532315.57
      3801006.18      10531801.7
#Sta/Elev= 30
  4193.3     368  4232.9  367.32  4268.2  368.67  4368.1  368.71  4474.2  365.23
  4596.9  364.51  4761.3  361.15  4819.3  359.02  4882.3   354.8  4961.8   354.5
  4984.6   355.6  4993.3  355.36  4998.9  352.04  5001.7  351.54  5004.9  352.04
  5015.4  355.39  5037.5  355.49  5081.7  359.98  5144.4  360.81  5172.8  363.62
  5190.1  362.32  5195.6  363.54  5280.4  366.82  5286.9  368.28  5302.5  367.55
  5401.1  373.35  5586.3  380.11  5722.1  387.29    5783  391.78  5979.9  401.64
#Mann= 4 ,-1 , 0
  4193.3     .16       0  4998.9     .07       0  5004.9     .16       0
  5586.3     .05       0
Bank Sta=4984.6,5015.4
XS Rating Curve= 0 ,0
Exp/Cntr=0.3,0.1

Type RM Length L Ch R = 1 ,301     ,0,0,0
BEGIN DESCRIPTION:
TWO MILE BRANCH 1.0
END DESCRIPTION:
XS GIS Cut Line= 4
      3802533.92     10532273.92      3802513.08     10531864.18
      3802165.86     10531794.73      3801444.09      10531288.1
#Sta/Elev= 30
  4498.6  361.24  4732.6  355.16  4782.7  355.32  4826.3  352.79  4983.8  353.19
  4999.4  349.37  5002.1  348.87  5005.4  349.37  5014.4  353.13  5111.2  354.93
  5211.5  356.29  5228.6  353.05  5238.8  355.34  5248.9  354.23  5270.6  358.58
  5313.9  360.05  5328.7  363.28  5343.5  359.59  5370.5  363.14  5379.2  359.42
  5385.3  361.52  5406.3  359.74  5421.1  363.23  5435.9  360.51    5442  363.07
  5471.6  364.45  5600.5  366.83  5798.1  376.88  5938.7  383.24  6144.8  396.03
#Mann= 6 ,-1 , 0
  4498.6     .16       0  4826.3     .16       0  4999.4     .07       0
  5005.4     .16       0  5111.2     .16       0  5798.1     .05       0
Bank Sta=4983.8,5014.4
XS Rating Curve= 0 ,0
Exp/Cntr=0.3,0.1

Chan Stop Cuts=-1
Use User Specified Reach Order=0
Composite Channel Slope=5