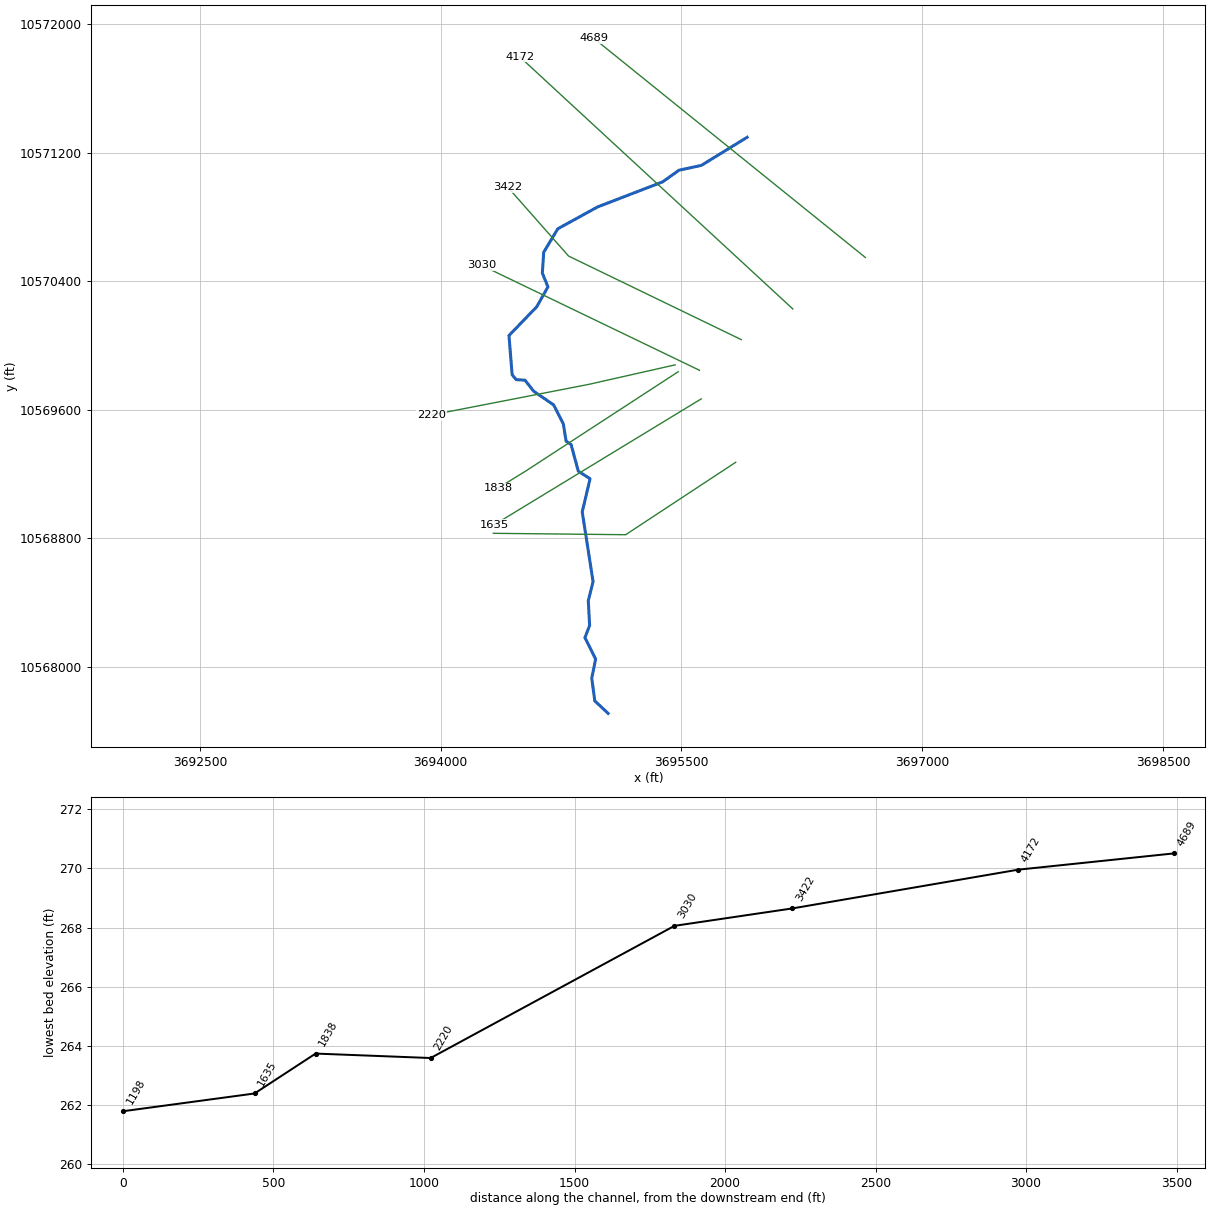
--- UNNAMED TRIBUTARY 1 TO TOMS CR.prj (project) ---

Proj Title=UNNAMED TRIBUTARY 1 TO TOMS CR Base Level Engineering
Current Plan=p01
Default Exp/Contr=0.3,0.1
English Units
Geom File=g01
Flow File=f01
Plan File=p01
Y Axis Title=Elevation
X Axis Title(PF)=Main Channel Distance
X Axis Title(XS)=Station
BEGIN DESCRIPTION:
UNNAMED TRIBUTARY 1 TO TOMS CR
END DESCRIPTION:
DSS Export Rating Curves= 0
DSS Export Rating Curve Sorted= 0
DSS Export Volume Flow Curves= 0
DXF OffsetX= 0
DXF OffsetY= 0
DXF ScaleX= 1
DXF ScaleY= 10

--- UNNAMED TRIBUTARY 1 TO TOMS CR.p01 (plan) ---

Plan Title=Multiple Run
Short Identifier=Multiple
Geom File=g01
Flow File=f01
Subcritical Flow
K Sum by GR= 0
Std Step Tol= 0.01
Critical Tol= 0.01
Num of Std Step Trials= 20
Max Error Tol= 0.3
Flow Tol Ratio= 0.001
Split Flow NTrial= 30
Split Flow Tol= 0.02
Split Flow Ratio= 0.02
Log Output Level= 0
Friction Slope Method= 1
Unsteady Friction Slope Method= 2
Unsteady Bridges Friction Slope Method= 1
Parabolic Critical Depth
Global Vel Dist=  1 , 1 , 1
Global Log Level= 0
CheckData=True
Encroach Param= -1, 0, 0, 0
BEGIN DESCRIPTION:
Multiple Run
END DESCRIPTION:

--- UNNAMED TRIBUTARY 1 TO TOMS CR.f01 (steady flow) ---

Flow Title=Multiple
Program Version=4.10
Number of Profiles= 7
Profile Names=10-year,25-year,50-year,1pct_min,100-year,1pct_plu,500-year
River Rch & RM=UNNAMED TRIBUTAR,Reach-1         ,4689
     342     448     533     466     630     853     886
Boundary for River Rch & Prof#=UNNAMED TRIBUTAR,Reach-1         , 1
Up Type= 0
Dn Type= 3
Dn Slope=0.0027
Boundary for River Rch & Prof#=UNNAMED TRIBUTAR,Reach-1         , 2
Up Type= 0
Dn Type= 3
Dn Slope=0.0027
Boundary for River Rch & Prof#=UNNAMED TRIBUTAR,Reach-1         , 3
Up Type= 0
Dn Type= 3
Dn Slope=0.0027
Boundary for River Rch & Prof#=UNNAMED TRIBUTAR,Reach-1         , 4
Up Type= 0
Dn Type= 3
Dn Slope=0.0027
Boundary for River Rch & Prof#=UNNAMED TRIBUTAR,Reach-1         , 5
Up Type= 0
Dn Type= 3
Dn Slope=0.0027
Boundary for River Rch & Prof#=UNNAMED TRIBUTAR,Reach-1         , 6
Up Type= 0
Dn Type= 3
Dn Slope=0.0027
Boundary for River Rch & Prof#=UNNAMED TRIBUTAR,Reach-1         , 7
Up Type= 0
Dn Type= 3
Dn Slope=0.0027
DSS Import GetInterval= 0
DSS Import GetPeak= 0
DSS Import FillOption= 0

--- UNNAMED TRIBUTARY 1 TO TOMS CR.g01 (geometry) ---

Geom Title=Existing Conditions
Program Version=4.10

River Reach=UNNAMED TRIBUTAR,Reach-1
Reach XY= 30
       3695909.9     10571297.32      3695624.25       10571122.
      3695485.25       10571092.      3695382.25       10571019.
       3694977.5       10570863.        3694730.       10570727.
      3694642.25       10570581.      3694633.75       10570451.
       3694668.5       10570365.       3694598.5       10570241.
      3694425.75       10570062.       3694445.5       10569818.
      3694471.25       10569787.       3694525.5       10569784.
      3694579.75       10569715.        3694704.       10569630.
      3694764.25       10569512.      3694781.75       10569404.
        3694813.       10569383.       3694857.5       10569217.
        3694931.       10569170.      3694882.25       10568963.
      3694949.75       10568529.        3694920.       10568410.
      3694928.25       10568255.        3694899.       10568180.
      3694965.75       10568046.       3694941.5       10567927.
      3694960.25       10567786.       3695043.5       10567708.

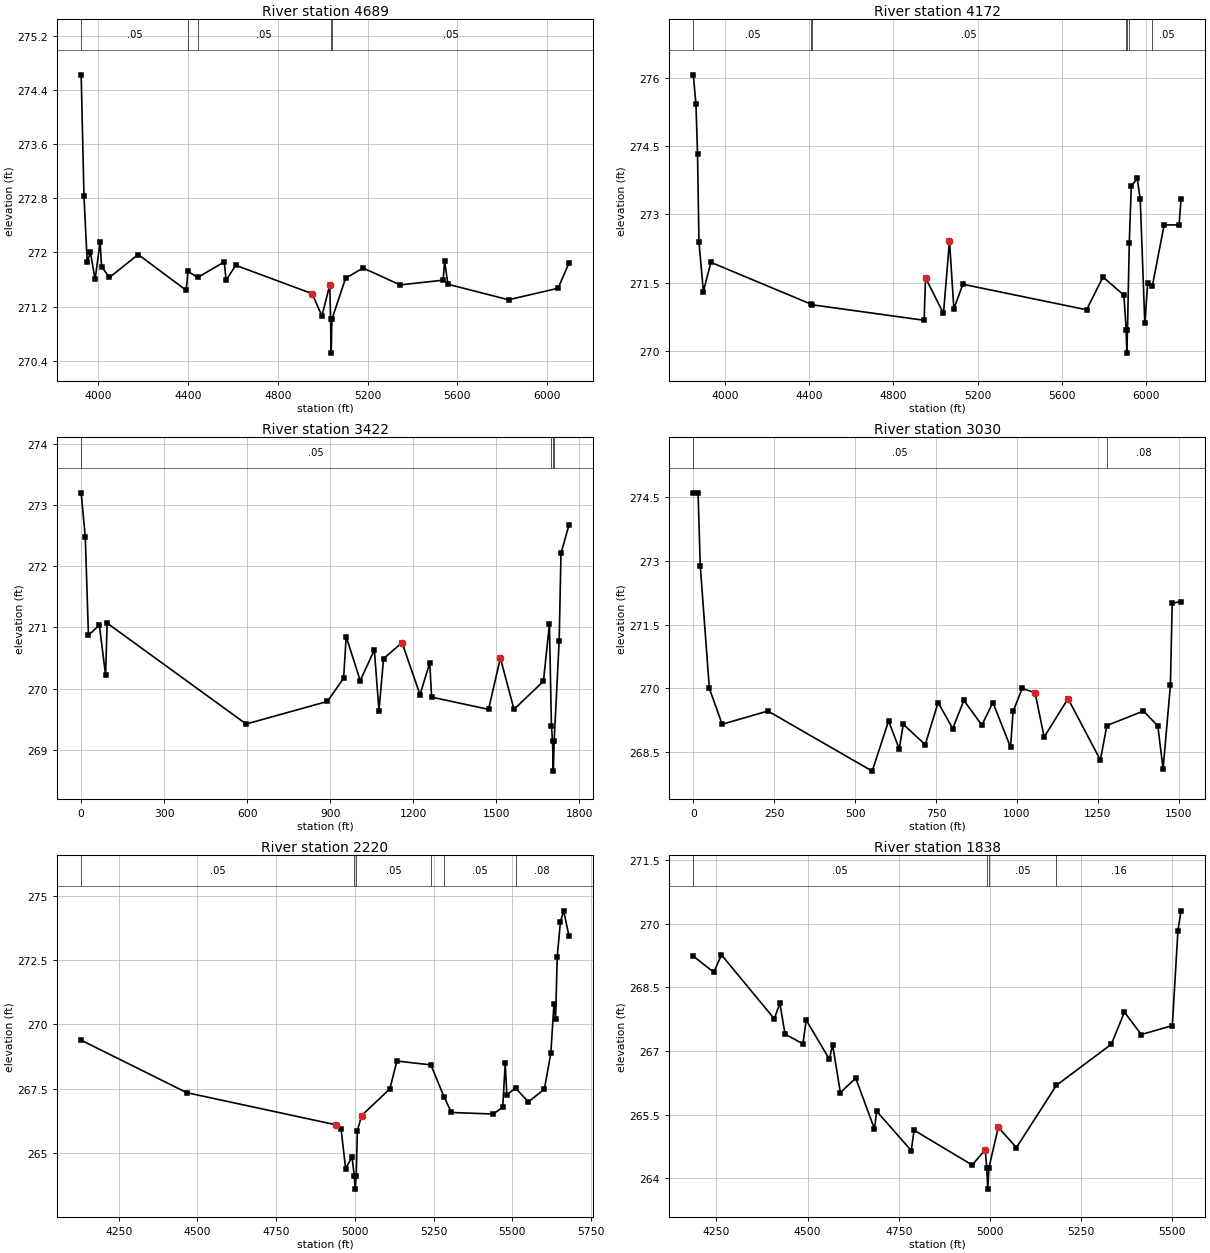
Type RM Length L Ch R = 1 ,4689    ,517,517,517
BEGIN DESCRIPTION:
UNNAMED TRIBUTARY 1 TO TOMS CR 5.0
END DESCRIPTION:
XS GIS Cut Line= 2
      3696645.88     10570548.59      3694954.51     10571913.64
#Sta/Elev= 30
  3923.3  274.63  3935.8  272.83  3950.2  271.86  3964.6     272  3985.4   271.6
  4007.7  272.16  4014.2  271.79  4049.4  271.63  4177.3  271.97  4391.6  271.44
  4399.3  271.72  4442.4  271.63  4561.1  271.86  4569.1  271.59  4612.2  271.81
  4952.9  271.39  4996.1  271.06  5031.3  271.52  5034.7  271.01  5037.4  270.51
  5040.7  271.01  5101.7  271.62    5180  271.77  5344.7  271.52  5536.6  271.59
    5543  271.88  5557.4  271.53  5827.7   271.3  6048.4  271.47  6096.8  271.84
#Mann= 5 ,-1 , 0
  3923.3     .05       0  4399.3     .08       0  4442.4     .05       0
  5034.7     .03       0  5040.7     .05       0
Bank Sta=4952.9,5031.3
XS Rating Curve= 0 ,0
Exp/Cntr=0.3,0.1

Type RM Length L Ch R = 1 ,4172    ,750,750,750
BEGIN DESCRIPTION:
UNNAMED TRIBUTARY 1 TO TOMS CR 4.0
END DESCRIPTION:
XS GIS Cut Line= 2
      3696194.53     10570227.38      3694493.86     10571797.89
#Sta/Elev= 30
  3850.9  276.06  3863.4  275.41  3870.8  274.33  3877.6   272.4  3898.6  271.31
  3934.3  271.95  4411.4  271.03  4413.8  271.02  4946.4  270.68  4953.2  271.61
  5038.3  270.83  5066.7  272.42  5087.6  270.93  5130.2  271.47  5717.6  270.91
  5795.3  271.63  5894.5  271.23  5905.7  270.46  5908.4  269.96  5911.7  270.46
  5920.2  272.38  5929.7  273.62    5958  273.79  5972.2  273.33  5993.8  270.62
  6007.9   271.5  6030.1  271.44  6085.6  272.77  6156.5  272.77  6165.8  273.33
#Mann= 7 ,-1 , 0
  3850.9     .05       0  4411.4     .08       0  4413.8     .05       0
  5905.7     .03       0  5911.7     .05       0  5920.2     .08       0
  6030.1     .05       0
Bank Sta=4953.2,5066.7
XS Rating Curve= 0 ,0
Exp/Cntr=0.3,0.1

Type RM Length L Ch R = 1 ,3422    ,392,392,392
BEGIN DESCRIPTION:
UNNAMED TRIBUTARY 1 TO TOMS CR 3.0
END DESCRIPTION:
XS GIS Cut Line= 3
       3695873.3     10570036.43      3694796.96     10570557.24
     3694418.469    10570986.195
#Sta/Elev= 30
       0   273.2    14.9  272.47    26.3  270.87    65.6  271.04    88.2  270.22
    93.8  271.07   596.3  269.42   889.9  269.79   948.4  270.17   957.7  270.85
  1008.4  270.13  1059.5  270.63  1076.2  269.64  1092.8  270.49  1159.5  270.75
  1224.6   269.9  1259.7  270.42  1266.4  269.86  1472.2  269.66  1514.9   270.5
  1564.2  269.66  1670.5  270.12  1692.2  271.05  1699.4  269.39  1703.4  269.15
  1706.2  268.65  1709.4  269.15  1727.4  270.78    1734  272.21  1762.5  272.67
#Mann= 4 ,-1 , 0
       0     .05       0  1699.4     .08       0  1703.4     .03       0
  1709.4     .08       0
Bank Sta=1159.5,1514.9
XS Rating Curve= 0 ,0
Exp/Cntr=0.3,0.1

Type RM Length L Ch R = 1 ,3030    ,810,810,810
BEGIN DESCRIPTION:
UNNAMED TRIBUTARY 1 TO TOMS CR 2.0
END DESCRIPTION:
XS GIS Cut Line= 2
      3695612.89     10569845.46     3694255.054     10570499.46
#Sta/Elev= 30
       0  274.59    14.7  274.58    21.4  272.88    49.5     270    89.2  269.16
   230.5  269.47   552.8  268.06   603.5  269.24   636.3  268.58   648.8  269.16
   716.7  268.68   756.4  269.67   801.6  269.06   836.1  269.72   891.6  269.14
   925.8  269.67   980.4  268.62   988.1  269.46  1016.3     270    1056   269.9
  1084.2  268.86    1158  269.76  1257.9  268.32    1278  269.13  1391.1  269.47
  1435.5  269.12  1451.7  268.11  1474.3  270.07  1479.9     272 1507.17  272.04
#Mann= 2 ,-1 , 0
       0     .05       0    1278     .08       0
Bank Sta=1056,1158
XS Rating Curve= 0 ,0
Exp/Cntr=0.3,0.1

Type RM Length L Ch R = 1 ,2220    ,382,382,382
BEGIN DESCRIPTION:
Mapping XS ef17a1ee
END DESCRIPTION:
XS GIS Cut Line= 3
      3695461.03     10569879.29      3694922.82     10569757.76
      3693943.27     10569567.06
#Sta/Elev= 30
  4130.4  269.38  4465.9  267.34  4940.1  266.09  4956.3  265.92  4970.7  264.39
  4991.1  264.84  4998.3  264.09    5001  263.59  5004.3  264.09    5008  265.86
  5021.6  266.45  5111.2  267.49  5133.7  268.57  5241.6  268.42  5283.3  267.18
  5306.9  266.57  5439.3  266.51  5469.9  266.77  5477.8  268.49  5482.9  267.26
  5510.6  267.52  5551.4  266.98  5602.3  267.48  5622.7  268.87  5632.7  270.79
  5637.8  270.21  5643.1  272.63  5653.3  273.99  5663.5  274.41  5680.1  273.45
#Mann= 6 ,-1 , 0
  4130.4     .05       0  4998.3     .03       0  5004.3     .05       0
  5241.6     .08       0  5283.3     .05       0  5510.6     .08       0
Bank Sta=4940.1,5021.6
XS Rating Curve= 0 ,0
Exp/Cntr=0.3,0.1

Type RM Length L Ch R = 1 ,1838    ,203,203,203
BEGIN DESCRIPTION:
Mapping XS 1c1c0f8d
END DESCRIPTION:
XS GIS Cut Line= 3
      3695480.34     10569836.62      3694534.14     10569220.29
      3694357.03      10569110.9
#Sta/Elev= 30
  4186.5  269.24  4242.6  268.86  4263.7  269.27  4408.6  267.76  4423.7  268.13
    4438   267.4    4487  267.17  4496.1  267.73  4559.4  266.81  4568.6  267.14
  4589.7  266.02  4631.9  266.36  4683.2  265.16  4689.2  265.58  4784.1  264.65
  4791.9  265.13  4951.2  264.31    4987  264.67  4991.1  264.24  4993.9  263.74
  4997.1  264.24  5022.8   265.2  5072.5  264.72    5182  266.19  5332.8  267.16
  5368.7  267.92  5414.9  267.39    5500   267.6  5515.4  269.84  5523.9  270.31
#Mann= 4 ,-1 , 0
  4186.5     .05       0  4991.1     .03       0  4997.1     .05       0
    5182     .16       0
Bank Sta=4987,5022.8
XS Rating Curve= 0 ,0
Exp/Cntr=0.3,0.1

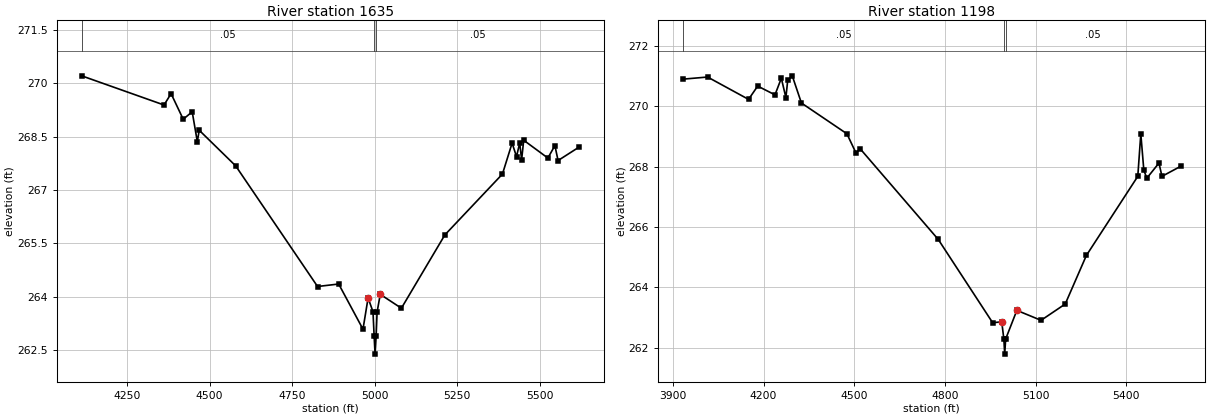
Type RM Length L Ch R = 1 ,1635    ,437,437,437
BEGIN DESCRIPTION:
Mapping XS 4de93f09
END DESCRIPTION:
XS GIS Cut Line= 2
      3695623.58     10569667.36      3694335.96     10568884.37
#Sta/Elev= 30
  4112.8  270.21  4362.3  269.39  4383.6  269.71  4420.4  268.99  4447.6   269.2
  4463.1  268.36  4468.9  268.68  4579.3  267.68  4827.3  264.29  4891.3  264.36
  4964.9  263.09  4980.4  263.97  4995.2  263.58  4998.7  262.89  5001.5  262.39
  5004.7  262.89  5007.6  263.57  5017.2  264.07  5081.2  263.68  5212.9  265.74
  5387.3  267.45  5416.6  268.32  5429.9  267.94  5439.6  268.32  5445.4  267.85
  5451.7   268.4  5524.9   267.9  5546.2  268.25  5555.8  267.83  5619.8  268.21
#Mann= 3 ,-1 , 0
  4112.8     .05       0  4998.7     .03       0  5004.7     .05       0
Bank Sta=4980.4,5017.2
XS Rating Curve= 0 ,0
Exp/Cntr=0.3,0.1

Type RM Length L Ch R = 1 ,1198    ,0,0,0
BEGIN DESCRIPTION:
UNNAMED TRIBUTARY 1 TO TOMS CR 1.0
END DESCRIPTION:
XS GIS Cut Line= 3
      3695838.59      10569272.5      3695152.86     10568821.13
      3694328.25     10568829.81
#Sta/Elev= 30
  3933.4   270.9  4014.7  270.97  4150.2  270.23  4180.4  270.67  4237.6  270.38
  4258.6  270.93  4273.7  270.29  4279.7  270.86  4294.8  271.01    4325  270.11
  4475.5  269.09  4505.7  268.45  4518.8   268.6  4777.6  265.59  4957.6  262.83
  4987.6  262.86  4994.6  262.29  4997.4  261.79  5000.6  262.29  5037.6  263.24
  5117.6  262.91  5197.6  263.45  5267.6  265.06  5437.6  267.68  5447.6  269.09
  5457.6  267.88  5467.6  267.62  5507.6  268.12  5517.6  267.68    5579  268.01
#Mann= 3 ,-1 , 0
  3933.4     .05       0  4994.6     .03       0  5000.6     .05       0
Bank Sta=4987.6,5037.6
XS Rating Curve= 0 ,0
Exp/Cntr=0.3,0.1

Chan Stop Cuts=-1
Use User Specified Reach Order=0
Composite Channel Slope=5