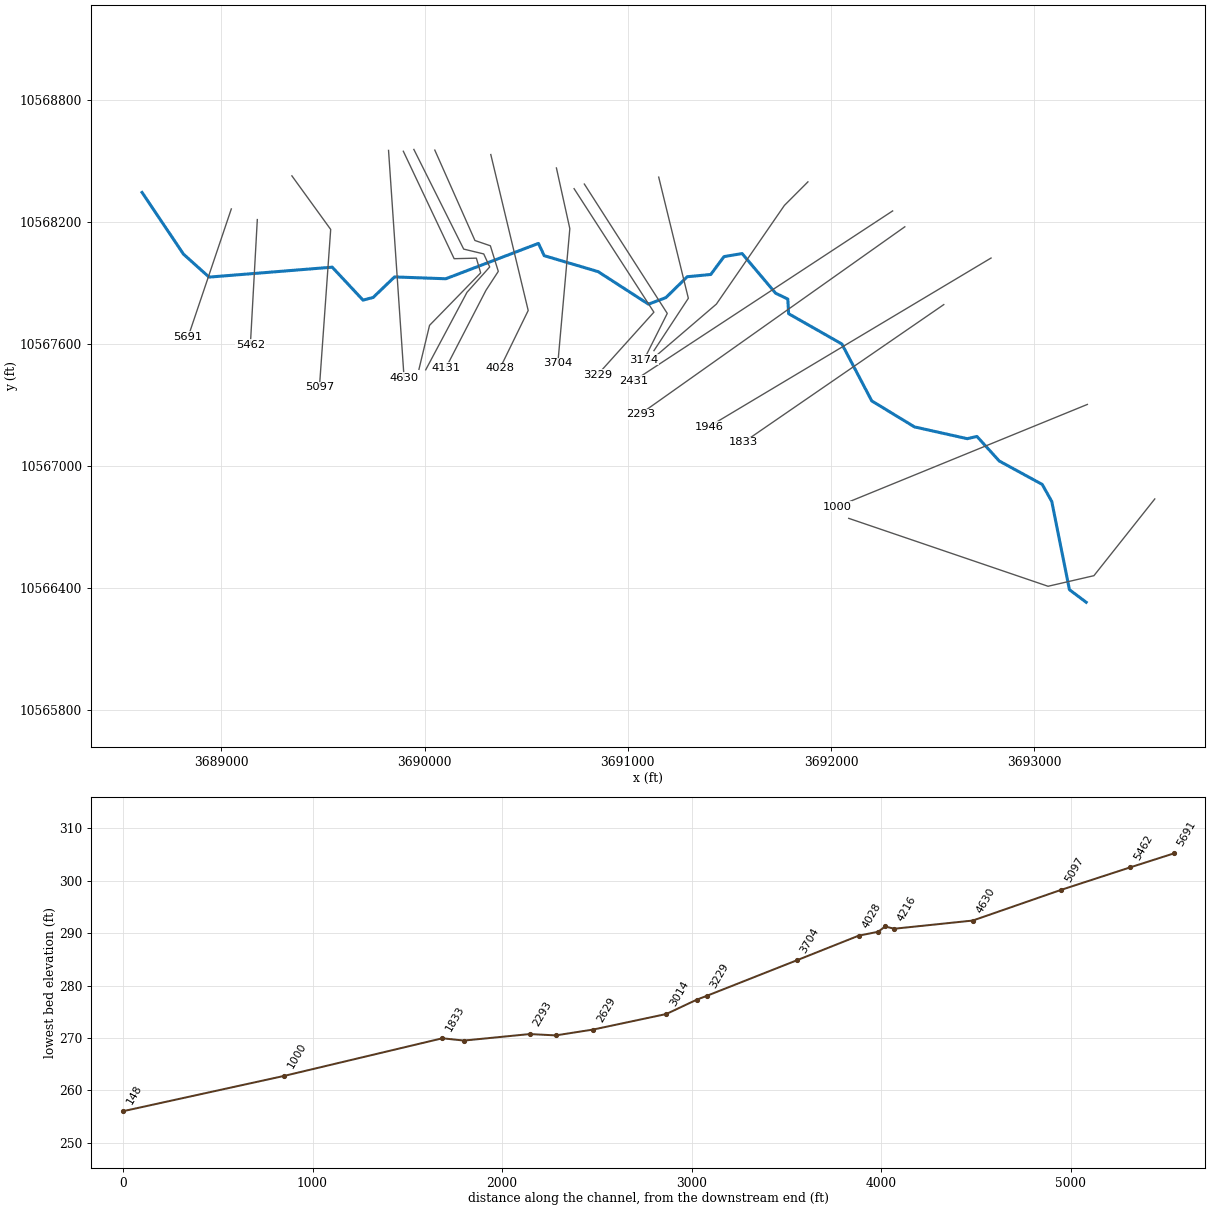
--- UNT004 IN BECR.prj (project) ---

Proj Title=UNT004 IN BECR Base Level Engineering
Current Plan=p01
Default Exp/Contr=0.3,0.1
English Units
Geom File=g01
Flow File=f01
Plan File=p01
BEGIN DESCRIPTION:
UNT004 IN BECR
END DESCRIPTION:

--- UNT004 IN BECR.p01 (plan) ---

Plan Title=Multiple Run
Short Identifier=Multiple
Geom File=g01
Flow File=f01
Subcritical Flow
K Sum by GR= 0
Std Step Tol= 0.01
Critical Tol= 0.01
Num of Std Step Trials= 20
Max Error Tol= 0.3
Flow Tol Ratio= 0.001
Split Flow NTrial= 30
Split Flow Tol= 0.02
Split Flow Ratio= 0.02
Log Output Level= 0
Friction Slope Method= 1
Unsteady Friction Slope Method= 2
Unsteady Bridges Friction Slope Method= 1
Parabolic Critical Depth
Global Vel Dist=  1 , 1 , 1
Global Log Level= 0
CheckData=True
Encroach Param= -1, 0, 0, 0
BEGIN DESCRIPTION:
Multiple Run
END DESCRIPTION:

--- UNT004 IN BECR.f01 (steady flow) ---

Flow Title=Multiple
Number of Profiles=7
Profile Names=10-year,25-year,50-year,1pct_min,100-year,1pct_plu,500-year
River Rch & RM= UNT004 IN BECR,Reach-1,5691
     257     334     395     345     466     630     651
Boundary for River Rch & Prof#=UNT004 IN BECR,Reach-1,1
Up Type=0
Dn Type=3
Dn Slope=0.005
Boundary for River Rch & Prof#=UNT004 IN BECR,Reach-1,2
Up Type=0
Dn Type=3
Dn Slope=0.005
Boundary for River Rch & Prof#=UNT004 IN BECR,Reach-1,3
Up Type=0
Dn Type=3
Dn Slope=0.005
Boundary for River Rch & Prof#=UNT004 IN BECR,Reach-1,4
Up Type=0
Dn Type=3
Dn Slope=0.005
Boundary for River Rch & Prof#=UNT004 IN BECR,Reach-1,5
Up Type=0
Dn Type=3
Dn Slope=0.005
Boundary for River Rch & Prof#=UNT004 IN BECR,Reach-1,6
Up Type=0
Dn Type=3
Dn Slope=0.005
Boundary for River Rch & Prof#=UNT004 IN BECR,Reach-1,7
Up Type=0
Dn Type=3
Dn Slope=0.005

--- UNT004 IN BECR.g01 (geometry) ---

Geom Title=Existing Conditions

River Reach=UNT004 IN BECR,Reach-1
Reach XY= 30
      3688609.37     10568346.75      3688813.36     10568042.93
      3688939.23     10567930.08      3689545.25     10567979.00
      3689696.75     10567817.00      3689746.75     10567830.00
      3689852.00     10567931.00      3690104.25     10567922.00
      3690560.16     10568096.00      3690588.74     10568035.53
      3690854.00     10567957.00      3691101.50     10567797.00
      3691187.25     10567829.00      3691292.50     10567932.00
      3691408.25     10567943.00      3691473.50     10568031.00
      3691562.50     10568046.00      3691727.25     10567851.00
      3691787.50     10567822.00      3691791.50     10567750.00
      3692053.50     10567601.00      3692200.50     10567321.00
      3692410.75     10567193.00      3692670.50     10567135.00
      3692718.25     10567146.00      3692828.09     10567025.19
      3693039.50     10566910.00      3693086.50     10566826.00
      3693173.50     10566392.00      3693256.00     10566330.00

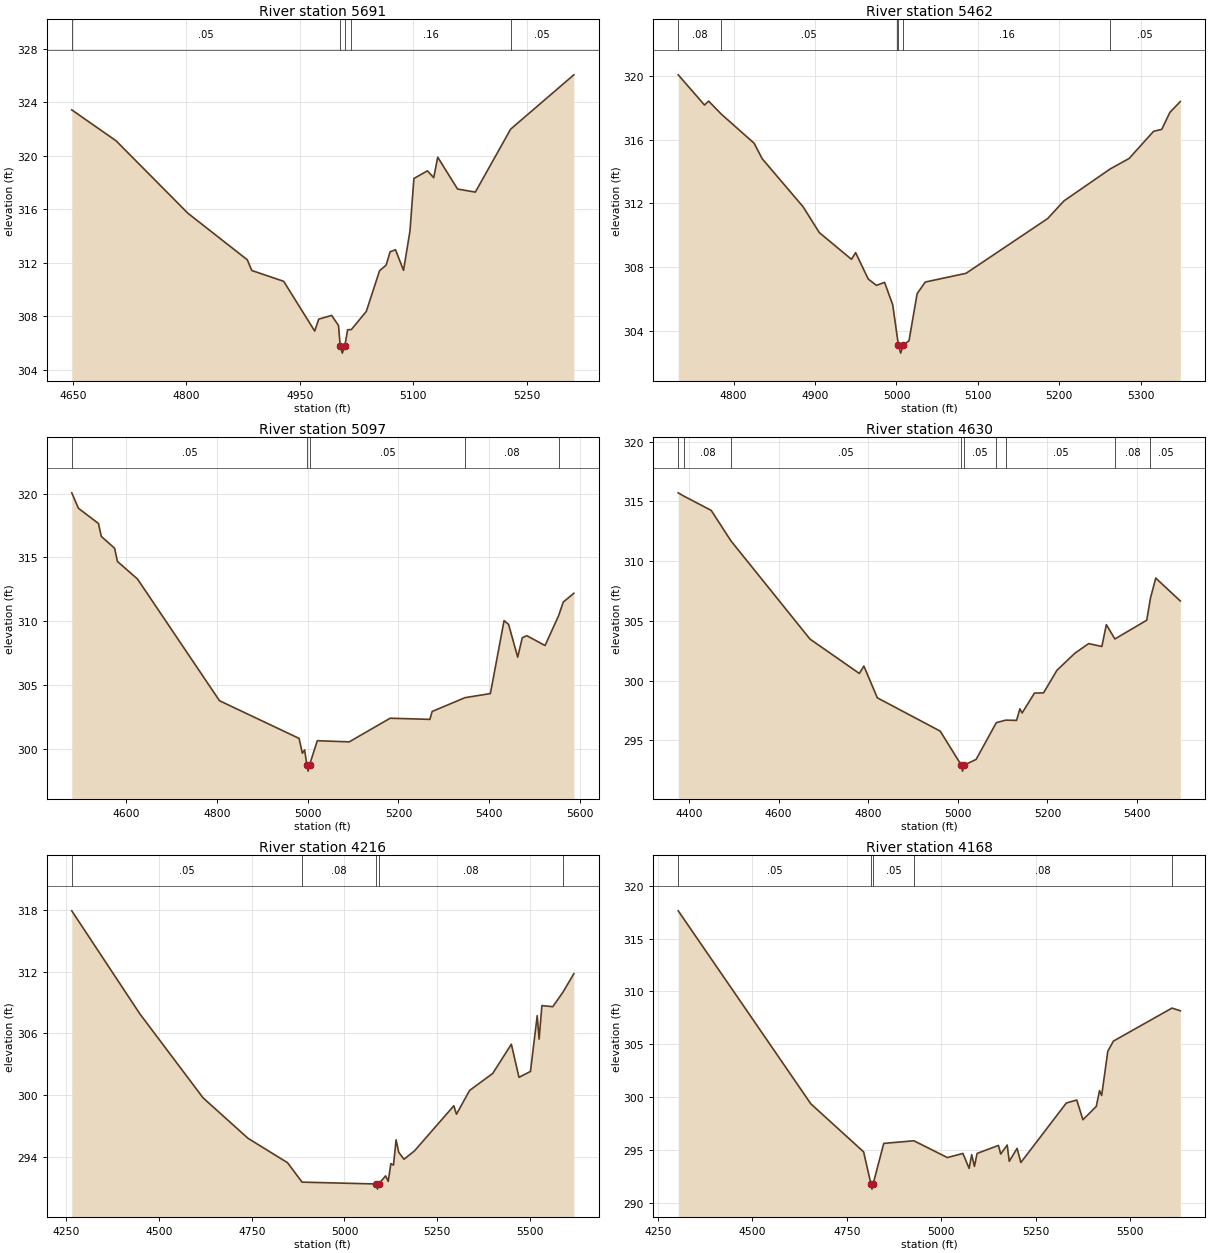
Type RM Length L Ch R = 1,5691,229,229,229
BEGIN DESCRIPTION:
UNT004 IN BECR 10.0
END DESCRIPTION:
XS GIS Cut Line= 2
      3689048.61     10568265.60      3688836.34     10567636.87
#Sta/Elev= 30
  4648.7  323.42  4707.2  321.11  4802.2  315.69  4880.7  312.21  4886.6  311.41
  4928.8  310.60  4969.8  306.88  4975.1  307.77  4992.2  308.05  5001.3  307.29
  5003.5  305.73  5006.3  305.23  5009.5  305.73  5013.3  306.98  5018.2  306.99
  5038.0  308.35  5055.5  311.39  5064.2  311.81  5069.5  312.81  5076.6  312.96
  5087.2  311.42  5095.7  314.36  5100.9  318.29  5118.8  318.86  5127.1  318.35
  5132.4  319.88  5158.6  317.50  5182.1  317.27  5228.8  321.98  5312.3  326.04
#Mann=5,-1,0
  4648.7    0.05       0  5003.5    0.03       0  5009.5    0.05       0
  5018.2    0.16       0  5228.8    0.05       0
Bank Sta=5003.5,5009.5
Exp/Cntr=0.3,0.1

Type RM Length L Ch R = 1,5462,365,365,365
BEGIN DESCRIPTION:
UNT004 IN BECR 9.0
END DESCRIPTION:
XS GIS Cut Line= 2
      3689176.63     10568213.27      3689142.51     10567597.41
#Sta/Elev= 30
  4731.9  320.08  4764.2  318.18  4769.2  318.43  4784.6  317.62  4825.1  315.78
  4835.1  314.80  4885.2  311.79  4905.2  310.16  4944.7  308.48  4949.8  308.90
  4965.3  307.24  4975.4  306.84  4985.4  307.03  4995.4  305.62  5000.6  303.73
  5002.4  303.08  5005.1  302.58  5008.4  303.08  5015.4  303.36  5025.4  306.32
  5035.4  307.05  5085.5  307.60  5185.7  311.04  5205.7  312.15  5262.5  314.16
  5285.8  314.82  5315.9  316.53  5325.9  316.65  5335.9  317.72  5348.7  318.40
#Mann=6,-1,0
  4731.9    0.08       0  4784.6    0.05       0  5000.6    0.16       0
  5002.4    0.03       0  5008.4    0.16       0  5262.5    0.05       0
Bank Sta=5002.4,5008.4
Exp/Cntr=0.3,0.1

Type RM Length L Ch R = 1,5097,467,467,467
BEGIN DESCRIPTION:
UNT004 IN BECR 8.0
END DESCRIPTION:
XS GIS Cut Line= 3
      3689346.87     10568428.32      3689537.74     10568164.67
      3689482.19     10567386.94
#Sta/Elev= 30
  4480.8  320.06  4495.5  318.85  4539.6  317.66  4545.8  316.65  4575.2  315.72
  4581.3  314.69  4625.4  313.32  4806.0  303.79  4981.2  300.84  4988.4  299.68
  4993.4  299.94  4998.3  298.78  5001.0  298.28  5004.3  298.78  5021.3  300.66
  5091.5  300.57  5181.7  302.42  5269.1  302.33  5274.1  302.95  5346.5  304.03
  5402.3  304.35  5432.4  310.06  5442.4  309.76  5462.4  307.20  5472.5  308.72
  5482.5  308.88  5522.6  308.11  5552.4  310.44  5562.7  311.51  5586.0  312.20
#Mann=5,-1,0
  4480.8    0.05       0  4998.3    0.04       0  5004.3    0.05       0
  5346.5    0.08       0  5552.4    0.05       0
Bank Sta=4998.3,5004.3
Exp/Cntr=0.3,0.1

Type RM Length L Ch R = 1,4630,414,414,414
BEGIN DESCRIPTION:
UNT004 IN BECR 7.0
END DESCRIPTION:
XS GIS Cut Line= 2
      3689822.46     10568553.59      3689898.85     10567435.49
#Sta/Elev= 30
  4375.8  315.72  4388.6  315.44  4449.4  314.25  4493.4  311.70  4669.9  303.47
  4780.1  300.59  4790.2  301.21  4820.2  298.55  4960.6  295.76  5007.7  292.91
  5010.4  292.41  5013.7  292.91  5040.7  293.39  5085.8  296.47  5106.9  296.68
  5131.0  296.66  5138.4  297.63  5143.4  297.28  5171.0  298.95  5191.1  298.96
  5221.2  300.86  5261.3  302.29  5291.9  303.09  5321.4  302.85  5331.4  304.68
  5350.5  303.48  5421.6  305.05  5429.8  306.89  5441.7  308.58  5496.5  306.66
#Mann=9,-1,0
  4375.8    0.05       0  4388.6    0.08       0  4493.4    0.05       0
  5007.7    0.04       0  5013.7    0.05       0  5085.8    0.08       0
  5106.9    0.05       0  5350.5    0.08       0  5429.8    0.05       0
Bank Sta=5007.7,5013.7
Exp/Cntr=0.3,0.1

Type RM Length L Ch R = 1,4216,48,48,48
BEGIN DESCRIPTION:
UNT004 IN BECR 6.0
END DESCRIPTION:
XS GIS Cut Line= 6
      3689895.30     10568549.40      3690145.30     10568020.76
      3690254.67     10568023.37      3690275.86     10567950.83
      3690024.21     10567692.64      3689972.13     10567476.51
#Sta/Elev= 30
  4265.1  317.93  4448.7  307.90  4619.0  299.73  4739.9  295.80  4846.6  293.42
  4885.7  291.53  5086.2  291.35  5088.9  290.85  5092.2  291.35  5110.9  292.14
  5117.9  291.60  5125.0  293.33  5132.1  293.19  5139.1  295.65  5146.2  294.43
  5160.4  293.76  5188.6  294.57  5294.7  298.96  5301.8  298.14  5337.1  300.45
  5399.6  302.11  5449.7  304.95  5470.3  301.73  5501.2  302.30  5519.4  307.73
  5524.5  305.45  5532.0  308.71  5561.3  308.60  5588.5  310.00  5618.1  311.81
#Mann=5,-1,0
  4265.1    0.05       0  4885.7    0.08       0  5086.2    0.07       0
  5092.2    0.08       0  5588.5    0.05       0
Bank Sta=5086.2,5092.2
Exp/Cntr=0.3,0.1

Type RM Length L Ch R = 1,4168,37,37,37
BEGIN DESCRIPTION:
Mapping XS 2fed5e23
END DESCRIPTION:
XS GIS Cut Line= 6
      3689947.08     10568558.37      3690192.28     10568067.96
      3690291.02     10568044.09      3690320.32     10567980.07
      3690208.56     10567855.29      3690005.38     10567473.79
#Sta/Elev= 30
  4303.7  317.64  4654.9  299.36  4794.7  294.81  4814.0  291.78  4816.8  291.28
  4820.0  291.78  4848.0  295.61  4927.8  295.86  5016.6  294.27  5057.7  294.66
  5074.1  293.24  5080.9  294.54  5088.2  293.43  5095.1  294.66  5151.8  295.42
  5157.7  294.60  5174.9  295.46  5180.4  293.92  5201.2  295.14  5211.1  293.80
  5331.6  299.44  5359.2  299.72  5375.5  297.85  5410.9  299.12  5419.4  300.61
  5425.1  300.15  5441.4  304.34  5456.2  305.30  5611.4  308.43  5633.4  308.17
#Mann=5,-1,0
  4303.7    0.05       0  4814.0    0.07       0  4820.0    0.05       0
  4927.8    0.08       0  5611.4     0.1       0
Bank Sta=4814,4820
Exp/Cntr=0.3,0.1

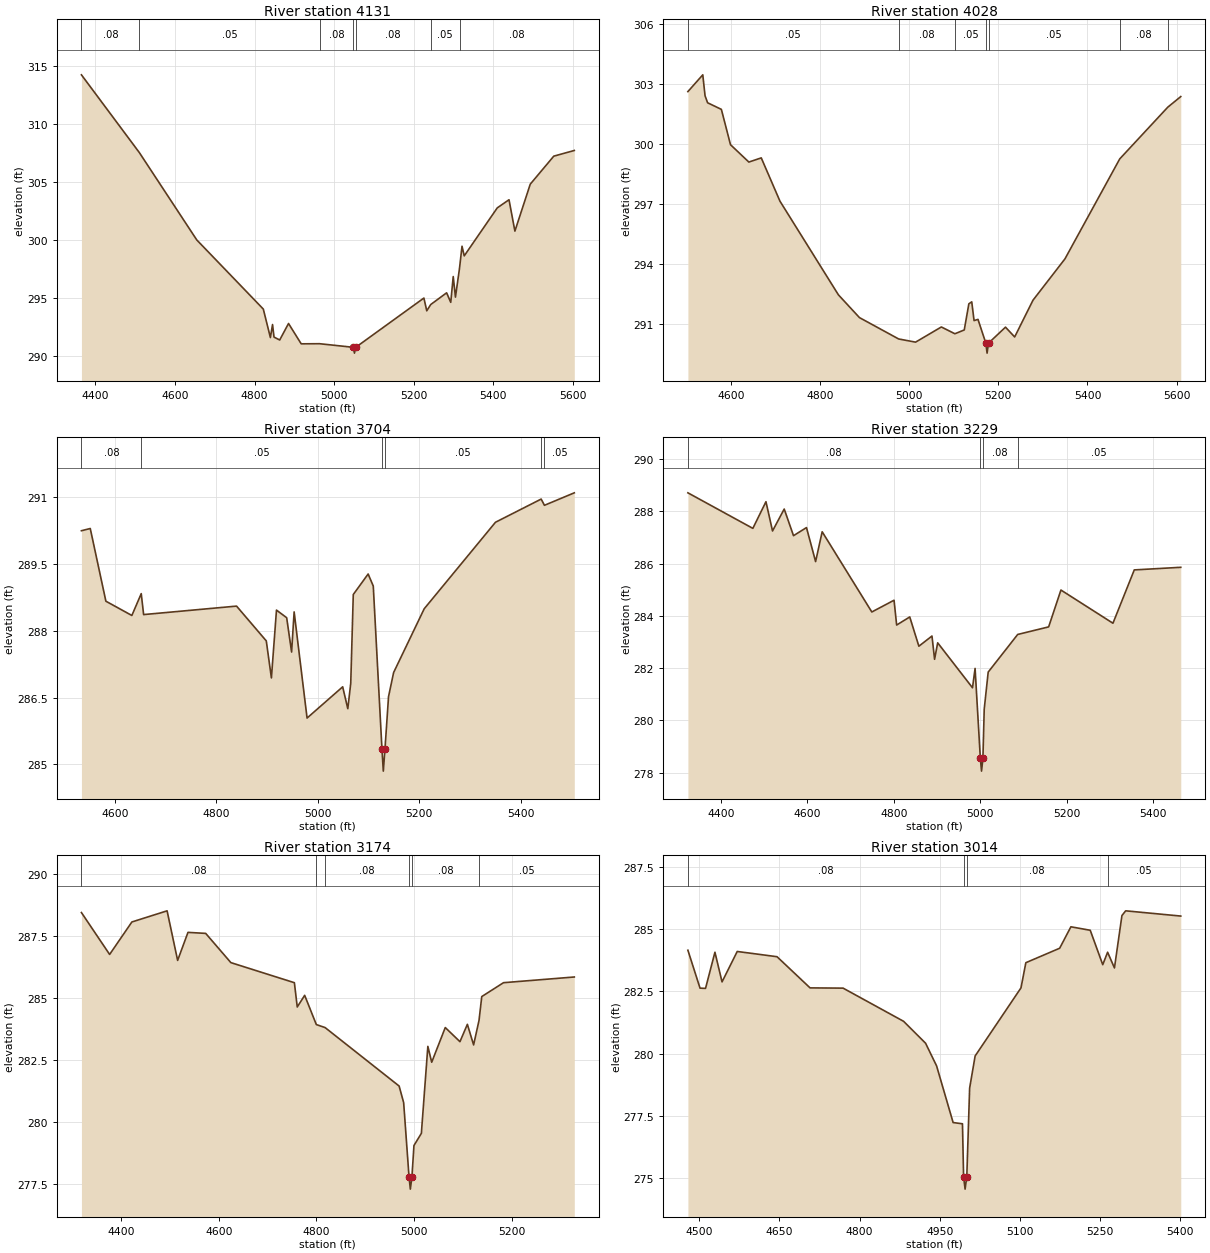
Type RM Length L Ch R = 1,4131,103,103,103
BEGIN DESCRIPTION:
Mapping XS fc687a26
END DESCRIPTION:
XS GIS Cut Line= 6
      3690050.14     10568555.15      3690247.62     10568110.28
      3690323.58     10568084.24      3690362.64     10567958.37
      3690301.88     10567865.06      3690105.06     10567484.40
#Sta/Elev= 30
  4365.0  314.22  4510.5  307.53  4654.9  300.01  4822.1  294.06  4839.9  291.61
  4845.3  292.73  4849.0  291.65  4863.3  291.40  4885.5  292.82  4917.3  291.07
  4963.5  291.08  5048.4  290.77  5051.2  290.27  5054.4  290.77  5225.7  295.01
  5232.9  293.91  5242.8  294.45  5282.8  295.46  5293.2  294.64  5299.4  296.86
  5305.0  295.09  5315.2  297.57  5321.5  299.47  5327.1  298.64  5410.1  302.77
  5439.6  303.47  5454.4  300.77  5493.0  304.81  5552.1  307.22  5603.7  307.71
#Mann=7,-1,0
  4365.0    0.08       0  4510.5    0.05       0  4963.5    0.08       0
  5048.4    0.07       0  5054.4    0.08       0  5242.8    0.05       0
  5315.2    0.08       0
Bank Sta=5048.4,5054.4
Exp/Cntr=0.3,0.1

Type RM Length L Ch R = 1,4028,324,324,324
BEGIN DESCRIPTION:
UNT004 IN BECR 5.0
END DESCRIPTION:
XS GIS Cut Line= 3
      3690325.74     10568533.18      3690509.77     10567765.81
      3690370.90     10567481.11
#Sta/Elev= 30
  4503.5  302.62  4536.9  303.46  4542.0  302.41  4547.7  302.06  4578.6  301.73
  4599.1  299.96  4640.3  299.09  4668.1  299.30  4710.1  297.13  4841.2  292.44
  4888.4  291.30  4976.3  290.23  5014.4  290.07  5072.2  290.83  5102.5  290.49
  5123.6  290.68  5133.9  291.99  5140.4  292.09  5145.6  291.15  5154.4  291.21
  5172.0  290.02  5174.8  289.52  5178.0  290.02  5216.1  290.82  5236.7  290.33
  5277.8  292.17  5349.5  294.24  5472.5  299.25  5580.3  301.84  5609.4  302.37
#Mann=7,-1,0
  4503.5    0.05       0  4976.3    0.08       0  5102.5    0.05       0
  5172.0    0.07       0  5178.0    0.05       0  5472.5    0.08       0
  5580.3    0.05       0
Bank Sta=5172,5178
Exp/Cntr=0.3,0.1

Type RM Length L Ch R = 1,3704,475,475,475
BEGIN DESCRIPTION:
Mapping XS 45c62924
END DESCRIPTION:
XS GIS Cut Line= 3
      3690648.66     10568467.21      3690714.64     10568168.59
      3690655.61     10567505.43
#Sta/Elev= 30
  4534.3  290.24  4551.7  290.29  4582.5  288.66  4633.7  288.34  4652.2  288.83
  4656.9  288.36  4840.1  288.55  4898.7  287.77  4908.8  286.94  4918.8  288.46
  4938.9  288.29  4948.6  287.52  4953.6  288.42  4979.1  286.04  5049.3  286.74
  5059.4  286.25  5065.2  286.82  5070.2  288.81  5099.5  289.27  5109.6  289.00
  5126.7  285.35  5129.4  284.85  5132.7  285.35  5139.7  286.52  5149.7  287.06
  5210.0  288.49  5350.5  290.43  5440.6  290.95  5447.0  290.81  5505.9  291.09
#Mann=6,-1,0
  4534.3    0.08       0  4652.2    0.05       0  5126.7    0.04       0
  5132.7    0.05       0  5440.6    0.08       0  5447.0    0.05       0
Bank Sta=5126.7,5132.7
Exp/Cntr=0.3,0.1

Type RM Length L Ch R = 1,3229,55,55,55
BEGIN DESCRIPTION:
UNT004 IN BECR 4.0
END DESCRIPTION:
XS GIS Cut Line= 3
      3690735.63     10568365.24      3691128.44     10567757.50
      3690850.01     10567448.33
#Sta/Elev= 30
  4323.8  288.71  4474.0  287.35  4504.3  288.37  4519.5  287.25  4546.5  288.09
  4568.0  287.07  4598.0  287.38  4619.1  286.08  4634.3  287.22  4749.1  284.15
  4800.5  284.60  4806.5  283.65  4836.8  283.96  4857.9  282.84  4888.2  283.23
  4894.2  282.34  4901.4  282.97  4981.9  281.25  4987.9  281.99  5000.0  278.56
  5002.8  278.06  5006.0  278.56  5009.0  280.43  5018.2  281.85  5086.4  283.29
  5158.0  283.58  5186.4  284.99  5306.7  283.72  5356.0  285.76  5463.5  285.86
#Mann=4,-1,0
  4323.8    0.08       0  5000.0    0.07       0  5006.0    0.08       0
  5086.4    0.05       0
Bank Sta=5000,5006
Exp/Cntr=0.3,0.1

Type RM Length L Ch R = 1,3174,160,160,160
BEGIN DESCRIPTION:
Mapping XS b7c7630a
END DESCRIPTION:
XS GIS Cut Line= 3
      3690786.10     10568388.02      3691194.21     10567751.41
      3691080.04     10567524.39
#Sta/Elev= 30
  4318.4  288.46  4376.2  286.77  4421.8  288.08  4494.0  288.53  4515.6  286.53
  4536.8  287.66  4573.1  287.62  4624.7  286.44  4754.9  285.63  4760.8  284.65
  4776.0  285.12  4799.9  283.94  4817.8  283.82  4969.6  281.46  4978.9  280.79
  4989.9  277.80  4992.6  277.30  4995.9  277.80  5000.0  279.06  5015.2  279.55
  5028.5  283.06  5036.4  282.42  5064.2  283.82  5094.3  283.25  5109.5  283.95
  5122.3  283.12  5133.4  284.11  5139.0  285.07  5183.6  285.63  5328.7  285.86
#Mann=6,-1,0
  4318.4    0.08       0  4799.9    0.05       0  4817.8    0.08       0
  4989.9    0.07       0  4995.9    0.08       0  5133.4    0.05       0
Bank Sta=4989.9,4995.9
Exp/Cntr=0.3,0.1

Type RM Length L Ch R = 1,3014,385,385,385
BEGIN DESCRIPTION:
Mapping XS 7743ee75
END DESCRIPTION:
XS GIS Cut Line= 3
      3691152.07     10568422.26      3691297.90     10567825.91
      3691128.65     10567568.13
#Sta/Elev= 30
  4478.6  284.15  4501.3  282.63  4511.6  282.62  4529.2  284.07  4542.5  282.88
  4570.9  284.10  4645.4  283.89  4707.2  282.64  4769.0  282.63  4882.2  281.30
  4923.4  280.42  4944.0  279.51  4974.9  277.24  4992.4  277.19  4994.5  275.07
  4997.3  274.57  5000.5  275.07  5005.8  278.62  5016.1  279.91  5101.9  282.64
  5111.0  283.65  5174.3  284.23  5195.3  285.09  5231.5  284.95  5254.9  283.57
  5264.0  284.07  5276.8  283.44  5290.8  285.54  5297.8  285.73  5400.9  285.52
#Mann=4,-1,0
  4478.6    0.08       0  4994.5    0.07       0  5000.5    0.08       0
  5264.0    0.05       0
Bank Sta=4994.5,5000.5
Exp/Cntr=0.3,0.1

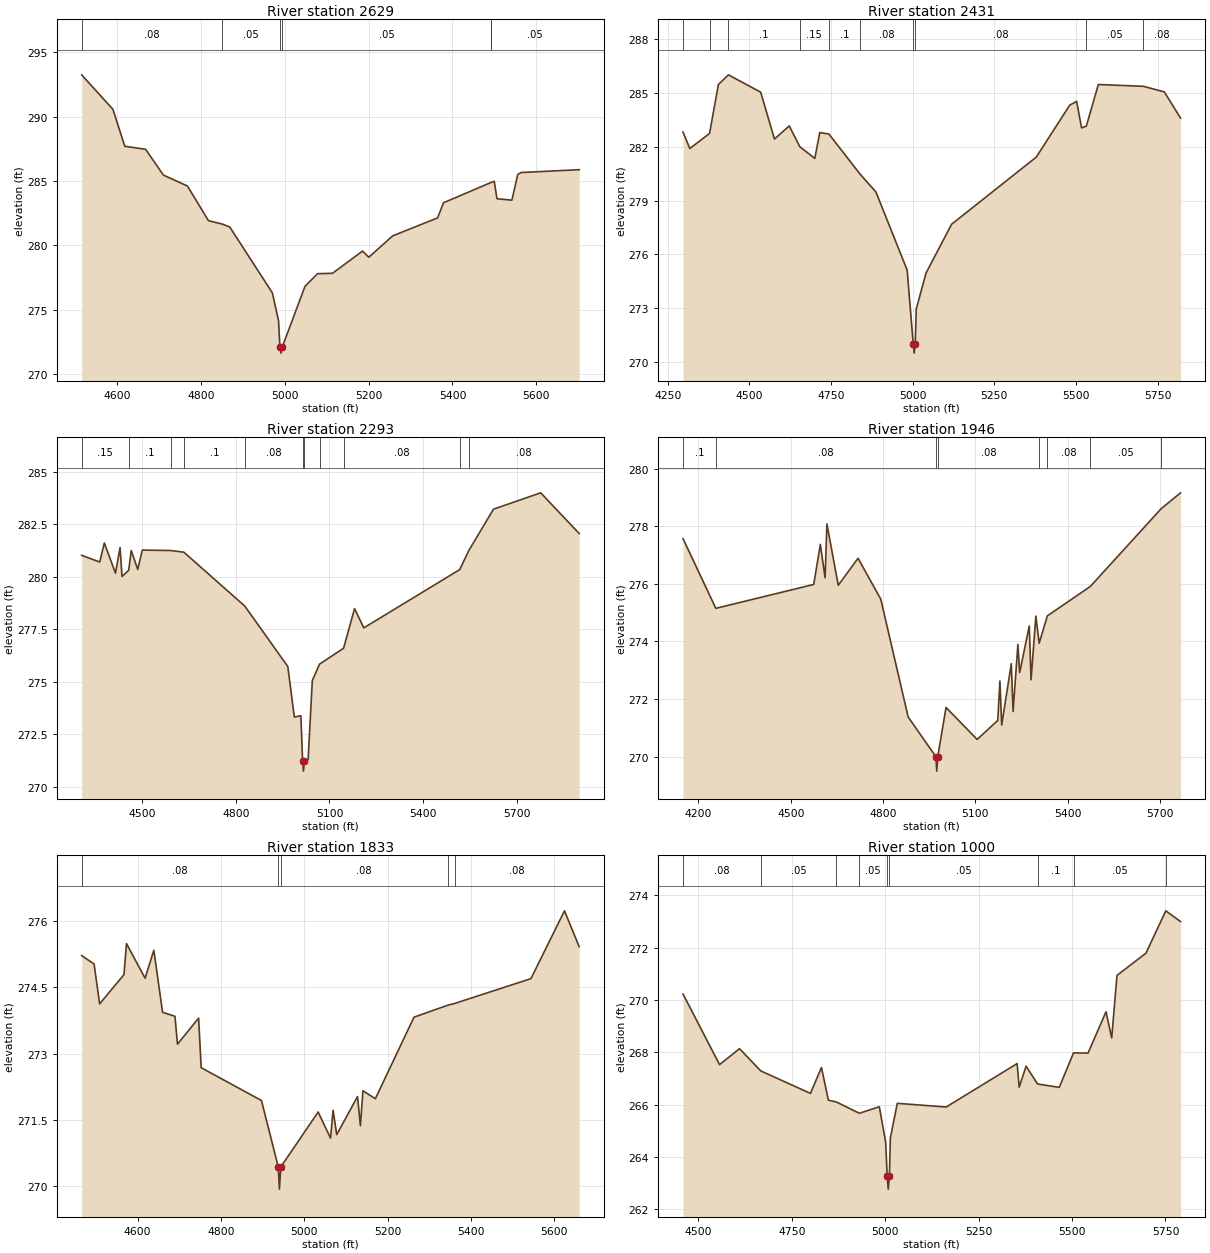
Type RM Length L Ch R = 1,2629,198,198,198
BEGIN DESCRIPTION:
Mapping XS 1adbf745
END DESCRIPTION:
XS GIS Cut Line= 4
      3691886.42     10568398.81      3691770.54     10568282.77
      3691435.92     10567797.27      3691107.80     10567516.02
#Sta/Elev= 30
  4516.2  293.26  4590.8  290.57  4619.0  287.70  4668.5  287.47  4711.0  285.46
  4768.3  284.61  4818.5  281.91  4851.4  281.65  4869.2  281.42  4970.7  276.30
  4985.5  274.12  4988.6  272.11  4991.4  271.61  4994.6  272.11  5048.4  276.80
  5078.2  277.79  5114.0  277.82  5185.7  279.55  5200.6  279.07  5257.4  280.73
  5364.5  282.13  5378.8  283.31  5490.9  284.87  5491.0  284.87  5499.5  284.98
  5506.1  283.62  5541.6  283.51  5555.5  285.50  5563.2  285.66  5702.0  285.88
#Mann=6,-1,0
  4516.2    0.08       0  4851.4    0.05       0  4988.6    0.04       0
  4994.6    0.05       0  5490.9    0.08       0  5491.0    0.05       0
Bank Sta=4988.6,4994.6
Exp/Cntr=0.3,0.1

Type RM Length L Ch R = 1,2431,138,138,138
BEGIN DESCRIPTION:
Mapping XS 7b80da8f
END DESCRIPTION:
XS GIS Cut Line= 2
      3692303.33     10568255.79      3691029.89     10567419.86
#Sta/Elev= 30
  4297.1  282.82  4318.0  281.90  4378.4  282.74  4405.4  285.47  4436.3  286.01
  4535.0  285.04  4577.1  282.43  4622.4  283.16  4654.7  282.00  4700.7  281.35
  4715.8  282.79  4743.7  282.71  4839.8  280.46  4887.7  279.48  4983.4  275.12
  5002.1  270.99  5004.9  270.49  5008.1  270.99  5011.1  272.94  5041.3  274.96
  5119.6  277.68  5378.7  281.42  5481.2  284.32  5502.3  284.53  5517.4  283.05
  5532.0  283.15  5568.7  285.47  5706.5  285.37  5770.6  285.06  5820.4  283.60
#Mann=10,-1,0
  4297.1     0.1       0  4378.4    0.08       0  4436.3     0.1       0
  4654.7    0.15       0  4743.7     0.1       0  4839.8    0.08       0
  5002.1    0.07       0  5008.1    0.08       0  5532.0    0.05       0
  5706.5    0.08       0
Bank Sta=5002.1,5008.1
Exp/Cntr=0.3,0.1

Type RM Length L Ch R = 1,2293,347,347,347
BEGIN DESCRIPTION:
UNT004 IN BECR 3.0
END DESCRIPTION:
XS GIS Cut Line= 2
      3692363.26     10568177.69      3691061.17     10567255.81
#Sta/Elev= 30
  4305.3  281.03  4363.2  280.71  4378.0  281.62  4413.7  280.18  4428.5  281.40
  4434.6  280.02  4456.2  280.32  4464.2  281.26  4485.1  280.36  4499.8  281.28
  4590.5  281.26  4633.0  281.18  4828.4  278.61  4966.3  275.73  4987.2  273.32
  5008.2  273.38  5013.7  271.24  5016.5  270.74  5019.7  271.24  5031.5  271.29
  5044.9  275.06  5068.0  275.84  5145.2  276.60  5180.4  278.49  5209.9  277.57
  5517.7  280.35  5546.8  281.26  5625.9  283.23  5777.3  284.01  5900.7  282.07
#Mann=11,-1,0
  4305.3    0.15       0  4456.2     0.1       0  4590.5    0.15       0
  4633.0     0.1       0  4828.4    0.08       0  5013.7    0.07       0
  5019.7    0.08       0  5068.0     0.1       0  5145.2    0.08       0
  5517.7     0.1       0  5546.8    0.08       0
Bank Sta=5013.7,5019.7
Exp/Cntr=0.3,0.1

Type RM Length L Ch R = 1,1946,113,113,113
BEGIN DESCRIPTION:
Mapping XS b3d471a6
END DESCRIPTION:
XS GIS Cut Line= 2
      3692787.74     10568024.05      3691399.73     10567194.71
#Sta/Elev= 30
  4150.0  277.57  4256.7  275.15  4574.9  275.98  4596.3  277.37  4611.8  276.21
  4617.6  278.08  4654.6  275.95  4718.8  276.89  4792.7  275.47  4881.7  271.38
  4971.9  270.00  4974.7  269.50  4977.9  270.00  5004.8  271.71  5106.0  270.60
  5172.9  271.26  5179.9  272.63  5185.7  271.10  5216.9  273.23  5222.7  271.57
  5238.3  273.90  5244.1  272.92  5275.3  274.54  5281.1  272.67  5296.7  274.88
  5307.5  273.94  5334.2  274.89  5473.7  275.91  5704.0  278.61  5766.9  279.16
#Mann=8,-1,0
  4150.0     0.1       0  4256.7    0.08       0  4971.9    0.07       0
  4977.9    0.08       0  5307.5    0.05       0  5334.2    0.08       0
  5473.7    0.05       0  5704.0    0.08       0
Bank Sta=4971.9,4977.9
Exp/Cntr=0.3,0.1

Type RM Length L Ch R = 1,1833,833,833,833
BEGIN DESCRIPTION:
UNT004 IN BECR 2.0
END DESCRIPTION:
XS GIS Cut Line= 2
      3692555.08     10567794.87      3691571.26     10567118.14
#Sta/Elev= 30
  4465.8  275.21  4495.6  275.02  4508.9  274.12  4567.3  274.78  4573.4  275.48
  4618.0  274.70  4639.0  275.33  4660.0  273.93  4689.7  273.84  4695.8  273.21
  4746.5  273.80  4752.6  272.68  4897.3  271.94  4937.7  270.44  4940.4  269.94
  4943.7  270.44  5033.4  271.68  5063.1  271.09  5069.2  271.72  5078.0  271.17
  5127.9  272.03  5134.8  271.37  5140.9  272.16  5170.7  271.98  5263.4  273.82
  5344.5  274.09  5361.2  274.13  5544.1  274.69  5624.6  276.22  5659.9  275.41
#Mann=5,-1,0
  4465.8    0.08       0  4937.7    0.07       0  4943.7    0.08       0
  5344.5     0.1       0  5361.2    0.08       0
Bank Sta=4937.7,4943.7
Exp/Cntr=0.3,0.1

Type RM Length L Ch R = 1,1000,852,852,852
BEGIN DESCRIPTION:
Mapping XS 494ff79f
END DESCRIPTION:
XS GIS Cut Line= 2
      3693261.71     10567303.58      3692029.07     10566800.11
#Sta/Elev= 30
  4458.8  270.23  4556.6  267.53  4610.1  268.14  4666.9  267.29  4799.8  266.43
  4829.3  267.42  4847.9  266.17  4869.5  266.10  4930.8  265.67  4984.2  265.92
  5001.2  264.56  5005.2  263.27  5008.0  262.77  5011.2  263.27  5013.7  264.72
  5032.3  266.05  5163.2  265.91  5353.0  267.57  5358.4  266.67  5377.0  267.47
  5407.6  266.79  5465.7  266.66  5504.0  267.98  5542.8  267.97  5590.8  269.55
  5606.1  268.55  5620.2  270.94  5697.7  271.79  5750.9  273.41  5790.3  273.00
#Mann=9,-1,0
  4458.8    0.08       0  4666.9    0.05       0  4869.5    0.08       0
  4930.8    0.05       0  5005.2    0.04       0  5011.2    0.05       0
  5407.6     0.1       0  5504.0    0.05       0  5750.9    0.08       0
Bank Sta=5005.2,5011.2
Exp/Cntr=0.3,0.1

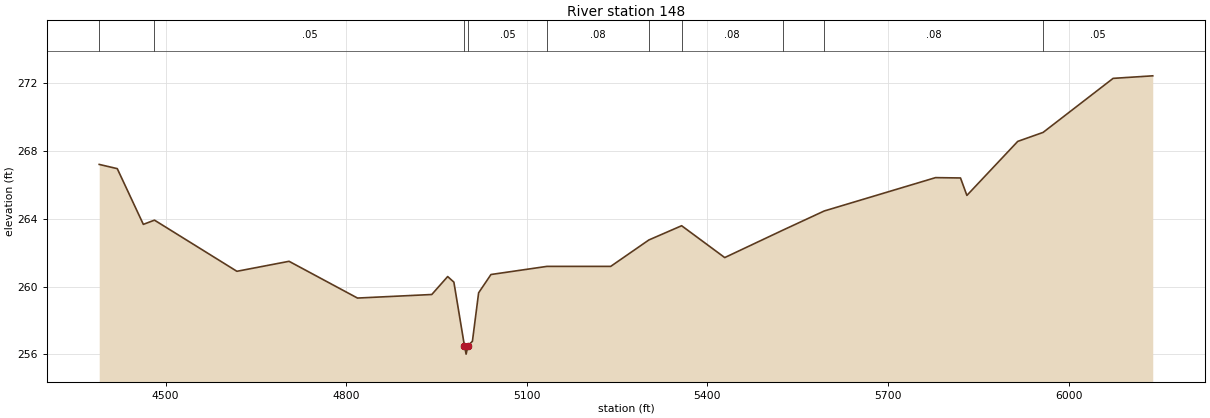
Type RM Length L Ch R = 1,148,0,0,0
BEGIN DESCRIPTION:
UNT004 IN BECR 1.0
END DESCRIPTION:
XS GIS Cut Line= 4
      3693593.48     10566838.47      3693293.98     10566460.83
      3693068.28     10566408.75      3692087.37     10566742.95
#Sta/Elev= 30
  4389.9  267.21  4419.9  266.96  4463.2  263.67  4481.7  263.92  4618.6  260.90
  4705.2  261.49  4818.9  259.32  4942.3  259.53  4968.7  260.59  4979.0  260.26
  4996.5  256.51  4999.3  256.01  5002.5  256.51  5009.8  256.77  5020.1  259.63
  5040.6  260.71  5133.6  261.19  5239.5  261.19  5302.9  262.75  5357.3  263.59
  5428.9  261.71  5525.5  263.33  5594.1  264.46  5779.1  266.43  5820.5  266.41
  5831.1  265.38  5915.6  268.57  5957.7  269.10  6074.0  272.29  6139.8  272.44
#Mann=10,-1,0
  4389.9    0.08       0  4481.7    0.05       0  4996.5    0.04       0
  5002.5    0.05       0  5133.6    0.08       0  5302.9    0.05       0
  5357.3    0.08       0  5525.5    0.05       0  5594.1    0.08       0
  5957.7    0.05       0
Bank Sta=4996.5,5002.5
Exp/Cntr=0.3,0.1

Chan Stop Cuts=-1