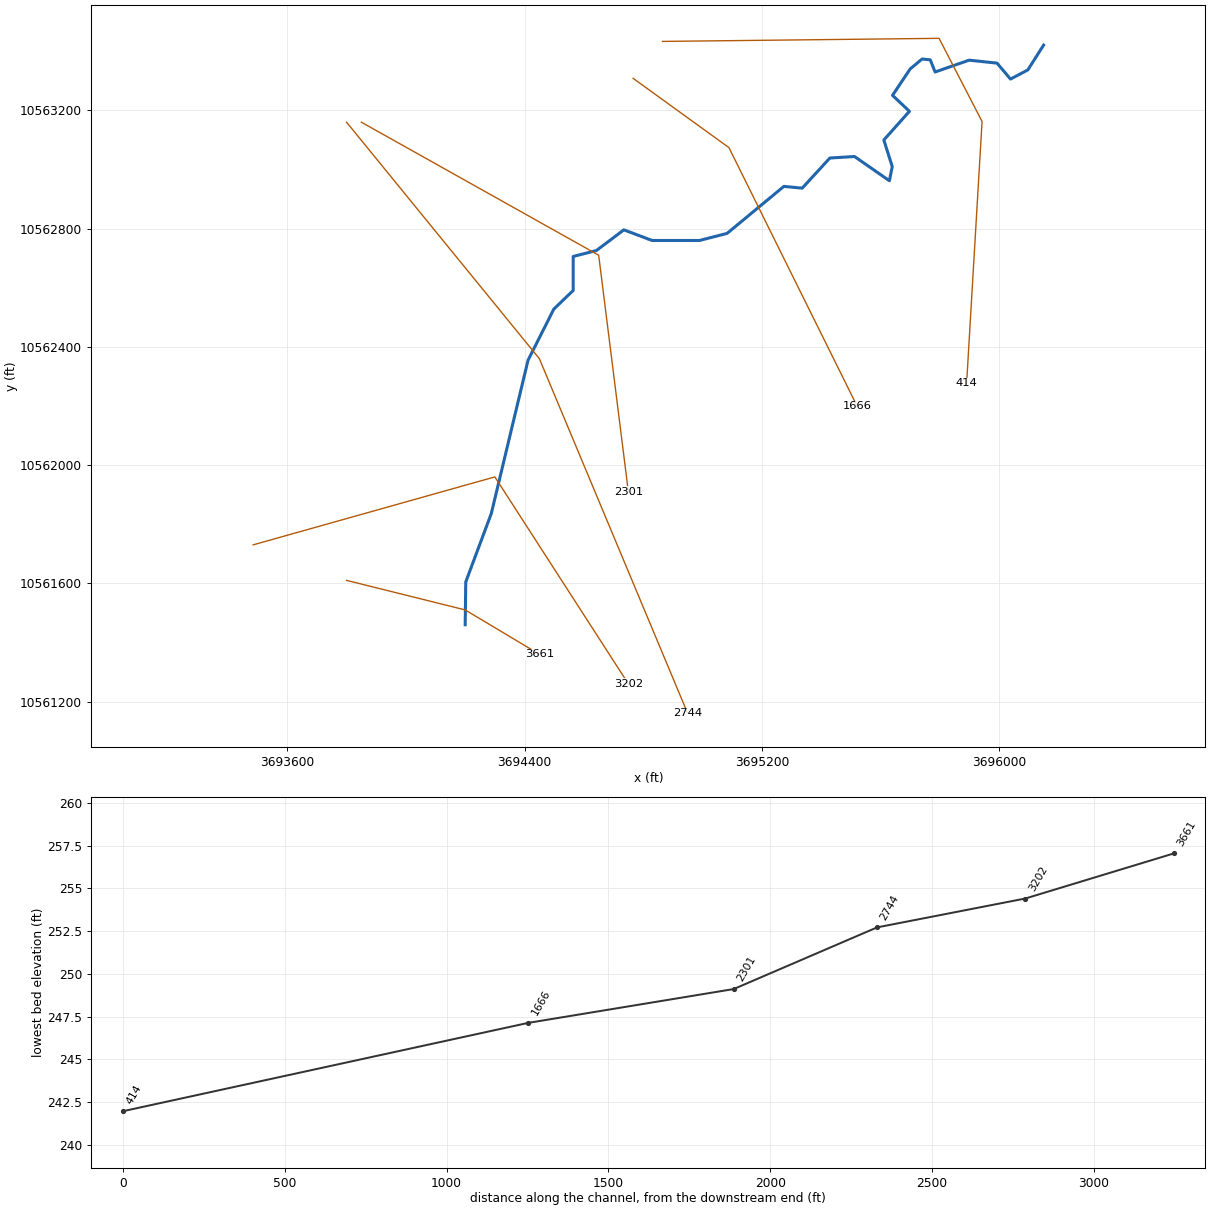
--- UNT005 IN BECR.prj (project) ---

Proj Title=UNT005 IN BECR Base Level Engineering
Current Plan=p01
Default Exp/Contr=0.3,0.1
English Units
Geom File=g01
Flow File=f01
Plan File=p01
BEGIN DESCRIPTION:
UNT005 IN BECR
END DESCRIPTION:

--- UNT005 IN BECR.p01 (plan) ---

Plan Title=Multiple Run
Short Identifier=Multiple
Geom File=g01
Flow File=f01
Subcritical Flow
K Sum by GR= 0
Std Step Tol= 0.01
Critical Tol= 0.01
Num of Std Step Trials= 20
Max Error Tol= 0.3
Flow Tol Ratio= 0.001
Split Flow NTrial= 30
Split Flow Tol= 0.02
Split Flow Ratio= 0.02
Log Output Level= 0
Friction Slope Method= 1
Unsteady Friction Slope Method= 2
Unsteady Bridges Friction Slope Method= 1
Parabolic Critical Depth
Global Vel Dist=  1 , 1 , 1
Global Log Level= 0
CheckData=True
Encroach Param= -1, 0, 0, 0
BEGIN DESCRIPTION:
Multiple Run
END DESCRIPTION:

--- UNT005 IN BECR.f01 (steady flow) ---

Flow Title=Multiple
Number of Profiles=7
Profile Names=10-year,25-year,50-year,1pct_min,100-year,1pct_plu,500-year
River Rch & RM= UNT005 IN BECR,Reach-1,3661
     745    1022    1253    1128    1525    2063    2270
Boundary for River Rch & Prof#=UNT005 IN BECR,Reach-1,1
Up Type=0
Dn Type=3
Dn Slope=0.005
Boundary for River Rch & Prof#=UNT005 IN BECR,Reach-1,2
Up Type=0
Dn Type=3
Dn Slope=0.005
Boundary for River Rch & Prof#=UNT005 IN BECR,Reach-1,3
Up Type=0
Dn Type=3
Dn Slope=0.005
Boundary for River Rch & Prof#=UNT005 IN BECR,Reach-1,4
Up Type=0
Dn Type=3
Dn Slope=0.005
Boundary for River Rch & Prof#=UNT005 IN BECR,Reach-1,5
Up Type=0
Dn Type=3
Dn Slope=0.005
Boundary for River Rch & Prof#=UNT005 IN BECR,Reach-1,6
Up Type=0
Dn Type=3
Dn Slope=0.005
Boundary for River Rch & Prof#=UNT005 IN BECR,Reach-1,7
Up Type=0
Dn Type=3
Dn Slope=0.005

--- UNT005 IN BECR.g01 (geometry) ---

Geom Title=Existing Conditions

River Reach=UNT005 IN BECR,Reach-1
Reach XY= 30
      3694199.61     10561460.19      3694201.50     10561605.00
      3694287.50     10561836.00      3694411.50     10562355.00
      3694498.50     10562528.00      3694563.75     10562591.00
      3694563.75     10562706.00      3694642.00     10562726.00
      3694734.50     10562796.00      3694829.75     10562760.00
      3694989.50     10562760.00      3695082.50     10562784.00
      3695274.00     10562943.00      3695335.75     10562937.00
      3695429.00     10563039.00      3695512.25     10563044.00
      3695629.75     10562962.00      3695639.25     10563010.00
      3695611.00     10563100.00      3695697.25     10563197.00
      3695640.25     10563251.00      3695699.50     10563340.00
      3695740.00     10563374.00      3695767.50     10563371.00
      3695783.75     10563330.00      3695898.50     10563370.00
      3695992.50     10563360.00      3696038.00     10563306.00
      3696096.50     10563337.00      3696149.50     10563421.00

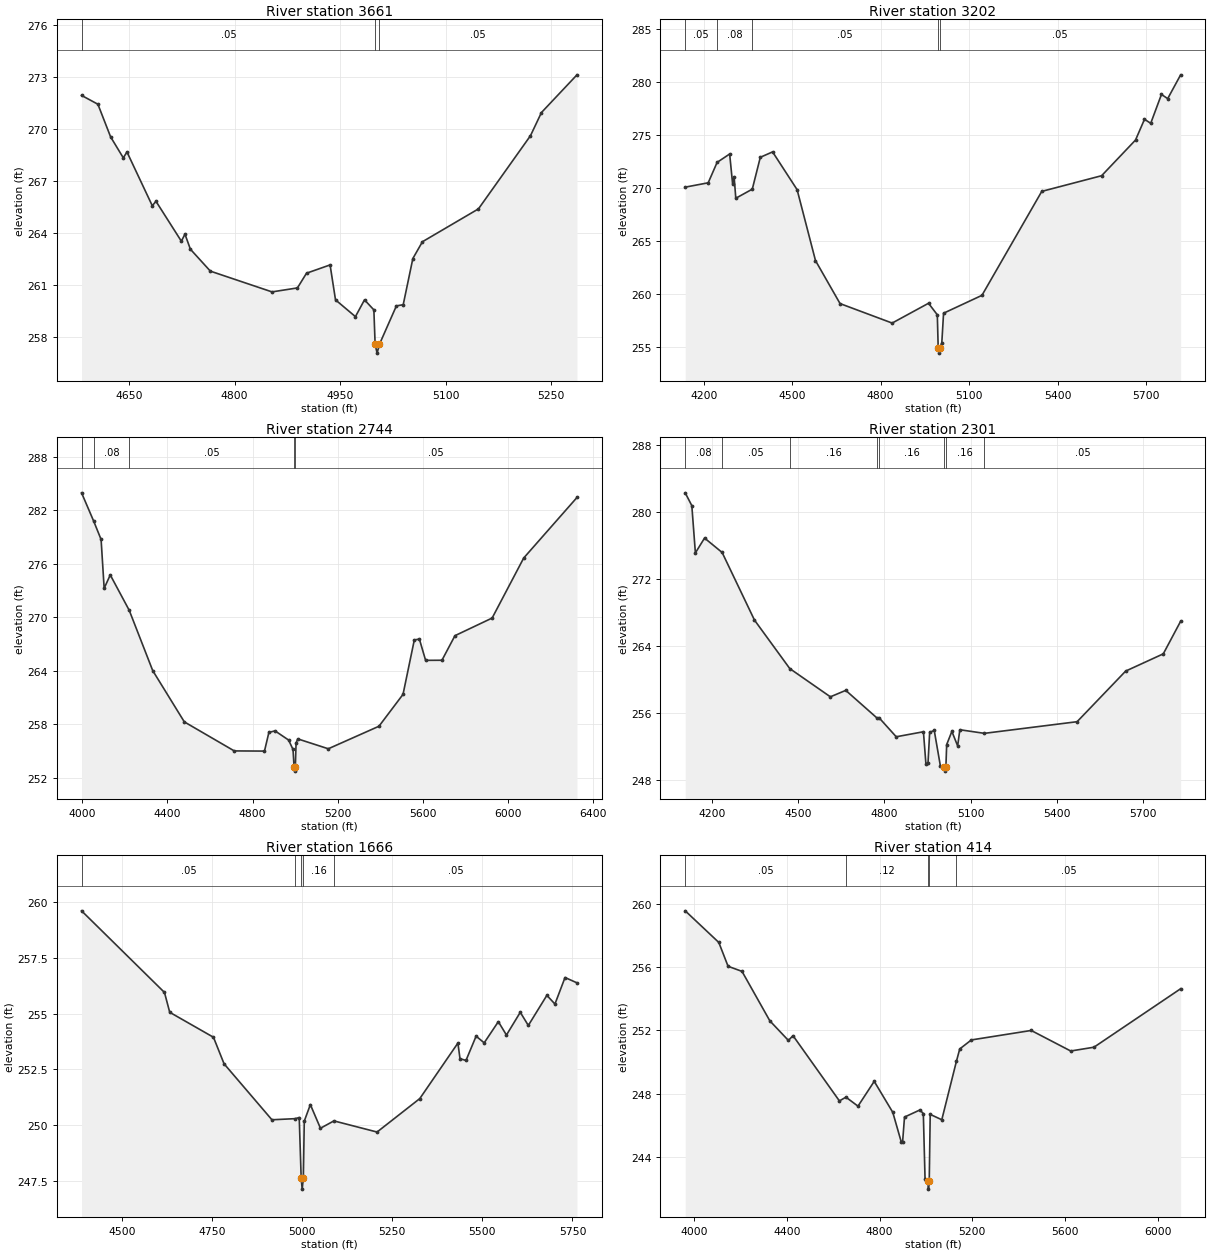
Type RM Length L Ch R = 1,3661,459,459,459
BEGIN DESCRIPTION:
UNT005 IN BECR 4.0
END DESCRIPTION:
XS GIS Cut Line= 3
      3693799.58     10561610.20      3694199.61     10561510.19
      3694449.62     10561360.18
#Sta/Elev= 30
  4582.5  271.95  4605.7  271.44  4623.8  269.55  4641.8  268.34  4647.0  268.68
  4683.0  265.57  4688.2  265.83  4724.3  263.52  4729.4  263.93  4737.1  263.06
  4765.5  261.79  4853.1  260.59  4889.2  260.82  4902.1  261.67  4935.6  262.15
  4943.3  260.13  4971.6  259.16  4984.5  260.13  4997.8  259.55  4999.6  257.55
  5002.4  257.05  5005.6  257.55  5029.8  259.78  5039.5  259.85  5053.2  262.52
  5066.8  263.49  5146.4  265.39  5220.3  269.62  5235.9  270.96  5286.4  273.14
#Mann=3,-1,0
  4582.5    0.05       0  4999.6    0.03       0  5005.6    0.05       0
Bank Sta=4999.6,5005.6
Exp/Cntr=0.3,0.1

Type RM Length L Ch R = 1,3202,458,458,458
BEGIN DESCRIPTION:
UNT005 IN BECR 3.0
END DESCRIPTION:
XS GIS Cut Line= 3
      3693484.66     10561730.33      3694299.61     10561960.19
      3694749.60     10561260.20
#Sta/Elev= 30
  4137.6  270.09  4215.5  270.50  4245.7  272.43  4288.2  273.22  4298.1  270.43
  4303.3  271.08  4309.0  269.04  4364.9  269.90  4392.1  272.91  4433.7  273.42
  4516.8  269.85  4579.1  263.15  4662.3  259.09  4838.9  257.25  4962.1  259.12
  4991.9  258.03  4994.9  254.91  4997.6  254.41  5000.9  254.91  5007.1  255.37
  5013.1  258.18  5143.2  259.87  5345.9  269.69  5548.7  271.17  5663.6  274.54
  5694.0  276.50  5715.1  276.12  5751.5  278.85  5772.6  278.45  5816.5  280.70
#Mann=5,-1,0
  4137.6    0.05       0  4245.7    0.08       0  4364.9    0.05       0
  4994.9    0.03       0  5000.9    0.05       0
Bank Sta=4994.9,5000.9
Exp/Cntr=0.3,0.1

Type RM Length L Ch R = 1,2744,443,443,443
BEGIN DESCRIPTION:
UNT005 IN BECR 2.0
END DESCRIPTION:
XS GIS Cut Line= 3
      3693799.63     10563160.16      3694449.61     10562360.19
      3694949.59     10561160.23
#Sta/Elev= 30
  3995.8  283.97  4053.0  280.78  4087.7  278.73  4102.1  273.25  4130.8  274.75
  4220.0  270.78  4330.5  264.01  4479.2  258.25  4714.1  254.99  4856.3  254.97
  4877.1  257.07  4905.9  257.24  4969.8  256.21  4990.6  255.15  4995.5  253.22
  4998.3  252.72  5001.5  253.22  5005.0  255.88  5012.9  256.34  5156.5  255.23
  5394.9  257.76  5508.1  261.34  5561.2  267.45  5585.0  267.55  5614.3  265.16
  5691.2  265.17  5752.4  267.93  5927.3  269.91  6075.8  276.65  6326.5  283.45
#Mann=5,-1,0
  3995.8    0.05       0  4053.0    0.08       0  4220.0    0.05       0
  4995.5    0.03       0  5001.5    0.05       0
Bank Sta=4995.5,5001.5
Exp/Cntr=0.3,0.1

Type RM Length L Ch R = 1,2301,635,635,635
BEGIN DESCRIPTION:
UNT005 IN BECR 1.0
END DESCRIPTION:
XS GIS Cut Line= 3
      3693849.59     10563160.20      3694649.61     10562710.19
      3694749.61     10561910.22
#Sta/Elev= 30
  4107.0  282.33  4130.0  280.80  4142.4  275.16  4174.3  276.93  4235.5  275.21
  4348.0  267.14  4470.9  261.35  4612.2  257.98  4665.7  258.75  4776.1  255.40
  4781.4  255.49  4841.3  253.21  4936.0  253.81  4944.6  249.99  4951.9  250.07
  4957.7  253.73  4973.6  253.97  4995.3  249.67  5008.2  249.61  5010.9  249.11
  5014.2  249.61  5016.9  252.28  5035.0  253.85  5055.1  252.12  5062.7  254.05
  5148.1  253.62  5470.8  255.01  5639.7  261.05  5770.7  263.11  5831.1  267.00
#Mann=8,-1,0
  4107.0    0.08       0  4235.5    0.05       0  4470.9    0.16       0
  4776.1    0.05       0  4781.4    0.16       0  5008.2    0.07       0
  5014.2    0.16       0  5148.1    0.05       0
Bank Sta=5008.2,5014.2
Exp/Cntr=0.3,0.1

Type RM Length L Ch R = 1,1666,1252,1252,1252
BEGIN DESCRIPTION:
Mapping XS acf77396
END DESCRIPTION:
XS GIS Cut Line= 3
      3694765.86     10563308.46      3695088.80     10563074.07
      3695521.09     10562199.07
#Sta/Elev= 30
  4387.5  259.61  4617.6  255.95  4632.2  255.06  4753.6  253.94  4783.0  252.75
  4915.8  250.24  4980.5  250.29  4991.6  250.34  4997.0  247.63  4999.8  247.13
  5003.0  247.63  5005.6  250.18  5022.5  250.92  5050.5  249.86  5087.9  250.19
  5207.6  249.69  5326.2  251.19  5432.0  253.68  5437.8  252.98  5454.4  252.90
  5482.5  253.99  5504.9  253.69  5544.2  254.64  5566.7  254.04  5605.1  255.06
  5627.4  254.47  5678.9  255.82  5701.3  255.43  5729.3  256.62  5762.5  256.38
#Mann=5,-1,0
  4387.5    0.05       0  4980.5    0.16       0  4997.0    0.07       0
  5003.0    0.16       0  5087.9    0.05       0
Bank Sta=4997,5003
Exp/Cntr=0.3,0.1

Type RM Length L Ch R = 1,414,0,0,0
BEGIN DESCRIPTION:
Mapping XS 6c13b434
END DESCRIPTION:
XS GIS Cut Line= 4
      3694864.85     10563433.44      3695797.13     10563443.86
      3695942.12     10563162.56      3695890.04     10562277.10
#Sta/Elev= 30
  3962.4  259.57  4107.2  257.57  4147.2  256.06  4207.2  255.74  4327.2  252.61
  4407.2  251.37  4427.2  251.67  4627.2  247.54  4655.2  247.78  4707.2  247.21
  4777.2  248.78  4857.2  246.82  4893.5  244.96  4899.6  244.96  4907.8  246.52
  4974.3  246.97  4988.9  246.74  4996.4  242.57  5008.4  242.46  5011.1  241.96
  5014.4  242.46  5018.6  246.69  5068.5  246.35  5131.6  250.05  5145.9  250.83
  5195.9  251.40  5454.0  252.00  5624.3  250.70  5724.5  250.94  6098.2  254.64
#Mann=5,-1,0
  3962.4    0.05       0  4655.2    0.12       0  5008.4    0.07       0
  5014.4    0.12       0  5131.6    0.05       0
Bank Sta=5008.4,5014.4
Exp/Cntr=0.3,0.1

Chan Stop Cuts=-1