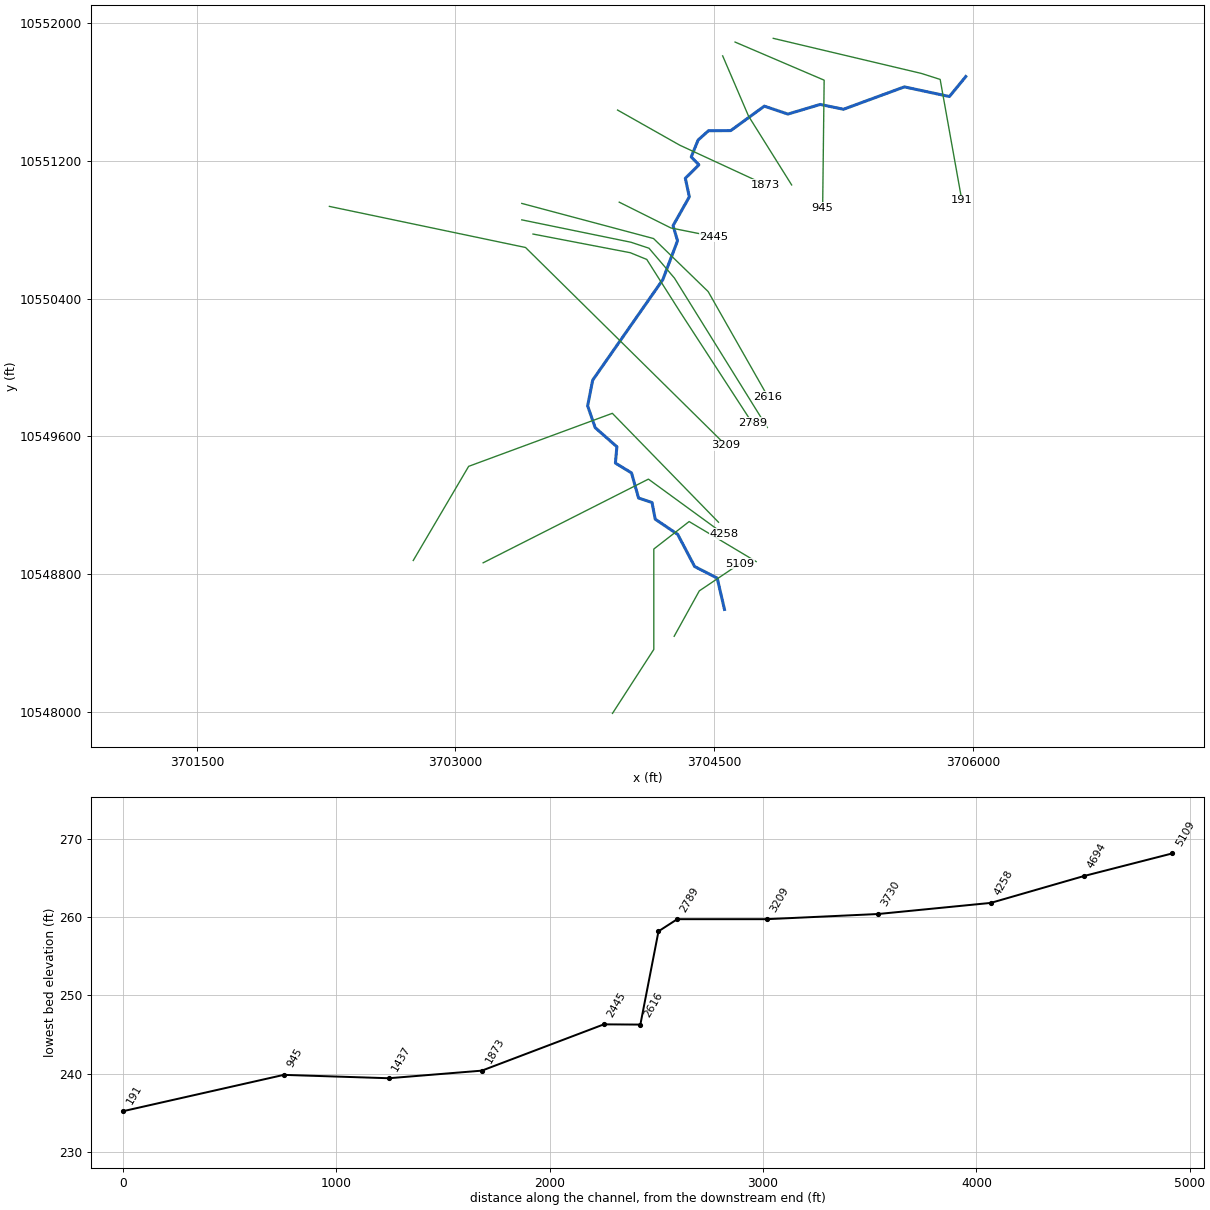
--- UNT007 IN BECR.prj (project) ---

Proj Title=UNT007 IN BECR Base Level Engineering
Current Plan=p01
Default Exp/Contr=0.3,0.1
English Units
Geom File=g01
Flow File=f01
Plan File=p01
Y Axis Title=Elevation
X Axis Title(PF)=Main Channel Distance
X Axis Title(XS)=Station
BEGIN DESCRIPTION:
UNT007 IN BECR
END DESCRIPTION:
DSS Export Rating Curves= 0
DSS Export Rating Curve Sorted= 0
DSS Export Volume Flow Curves= 0
DXF OffsetX= 0
DXF OffsetY= 0
DXF ScaleX= 1
DXF ScaleY= 10

--- UNT007 IN BECR.p01 (plan) ---

Plan Title=Multiple Run
Short Identifier=Multiple
Geom File=g01
Flow File=f01
Subcritical Flow
K Sum by GR= 0
Std Step Tol= 0.01
Critical Tol= 0.01
Num of Std Step Trials= 20
Max Error Tol= 0.3
Flow Tol Ratio= 0.001
Split Flow NTrial= 30
Split Flow Tol= 0.02
Split Flow Ratio= 0.02
Log Output Level= 0
Friction Slope Method= 1
Unsteady Friction Slope Method= 2
Unsteady Bridges Friction Slope Method= 1
Parabolic Critical Depth
Global Vel Dist=  1 , 1 , 1
Global Log Level= 0
CheckData=True
Encroach Param= -1, 0, 0, 0
BEGIN DESCRIPTION:
Multiple Run
END DESCRIPTION:

--- UNT007 IN BECR.f01 (steady flow) ---

Flow Title=Multiple
Number of Profiles=7
Profile Names=10-year,25-year,50-year,1pct_min,100-year,1pct_plu,500-year
River Rch & RM= UNT007 IN BECR,Reach-1,5109
     578     785     955     855    1156    1563    1699
Boundary for River Rch & Prof#=UNT007 IN BECR,Reach-1,1
Up Type=0
Dn Type=3
Dn Slope=0.005
Boundary for River Rch & Prof#=UNT007 IN BECR,Reach-1,2
Up Type=0
Dn Type=3
Dn Slope=0.005
Boundary for River Rch & Prof#=UNT007 IN BECR,Reach-1,3
Up Type=0
Dn Type=3
Dn Slope=0.005
Boundary for River Rch & Prof#=UNT007 IN BECR,Reach-1,4
Up Type=0
Dn Type=3
Dn Slope=0.005
Boundary for River Rch & Prof#=UNT007 IN BECR,Reach-1,5
Up Type=0
Dn Type=3
Dn Slope=0.005
Boundary for River Rch & Prof#=UNT007 IN BECR,Reach-1,6
Up Type=0
Dn Type=3
Dn Slope=0.005
Boundary for River Rch & Prof#=UNT007 IN BECR,Reach-1,7
Up Type=0
Dn Type=3
Dn Slope=0.005

--- UNT007 IN BECR.g01 (geometry) ---

Geom Title=Existing Conditions
Program Version=4.10

River Reach=UNT007 IN BECR  ,Reach-1
Reach XY= 30
        3704560.       10548594.      3704517.75       10548776.
        3704387.       10548843.      3704288.75       10549030.
       3704158.5       10549118.      3704139.75       10549215.
      3704061.75       10549241.        3704021.       10549387.
       3703927.5       10549444.        3703936.       10549539.
      3703810.25       10549650.       3703766.5       10549777.
      3703795.75       10549926.       3704202.5       10550510.
      3704287.75       10550736.        3704262.       10550824.
      3704356.25       10550991.        3704333.       10551099.
      3704411.75       10551177.      3704367.25       10551223.
        3704407.       10551321.      3704467.25       10551375.
       3704596.5       10551376.        3704791.       10551518.
      3704927.75       10551472.      3705115.25       10551528.
      3705250.25       10551500.      3705603.25       10551630.
       3705864.5       10551574.       3705959.5       10551690.

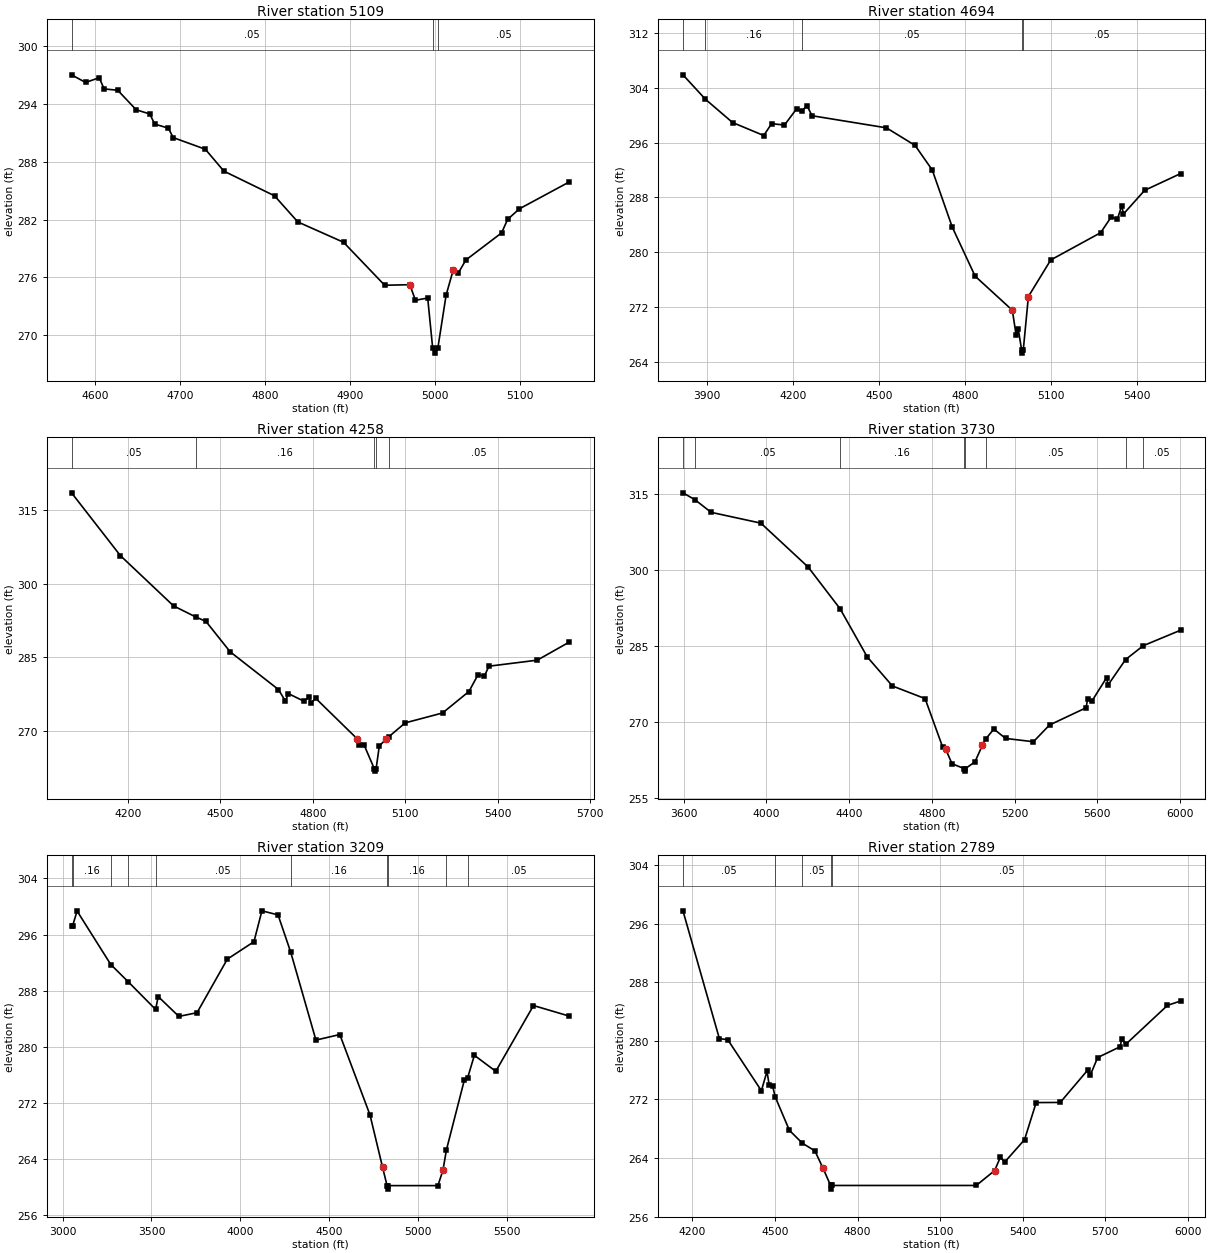
Type RM Length L Ch R = 1 ,5109    ,415,415,415
BEGIN DESCRIPTION:
UNT007 IN BECR 10.0
END DESCRIPTION:
XS GIS Cut Line= 3
      3704268.28     10548437.74      3704414.09     10548701.59
      3704649.61     10548860.19
#Sta/Elev= 30
    4572  297.02  4588.5  296.23  4604.6  296.72  4610.3  295.56  4626.3  295.42
  4648.1  293.39  4664.1  292.96  4669.8  291.91  4685.9  291.49  4691.6  290.51
  4729.4   289.3  4751.2  287.03  4810.8  284.47  4838.2  281.76    4892  279.65
  4940.4  275.19    4970  275.25  4976.6  273.63    4991  273.87  4996.9  268.65
  4999.7  268.15  5002.9  268.65  5012.7  274.18  5020.9  276.73    5027  276.46
  5035.9  277.81  5077.9  280.62  5085.1  282.03  5098.9  283.12  5157.4   285.9
#Mann= 3 ,-1 , 0
    4572     .05       0  4996.9     .03       0  5002.9     .05       0
Bank Sta=4970,5020.9
XS Rating Curve= 0 ,0
Exp/Cntr=0.3,0.1

Type RM Length L Ch R = 1 ,4694    ,436,436,436
BEGIN DESCRIPTION:
UNT007 IN BECR 9.0
END DESCRIPTION:
XS GIS Cut Line= 5
      3703910.64     10547989.81       3704150.2     10548361.31
       3704150.2     10548944.64      3704355.07     10549104.36
      3704743.95     10548871.73
#Sta/Elev= 30
  3815.5  305.93    3894  302.36  3988.7  298.96  4097.6  297.06  4125.3  298.79
  4170.2  298.59  4212.4  300.95  4230.3  300.58  4248.7  301.44  4266.4  299.95
  4526.4  298.18  4626.4  295.61  4686.4  292.02  4756.4  283.66  4836.2   276.5
  4966.2  271.52  4979.6  267.83    4987  268.75  4998.5  265.75  5001.3  265.25
  5004.5  265.75  5022.3  273.52  5100.4  278.87  5274.6  282.85  5311.6  285.15
    5333   284.8  5348.5  286.82  5354.4  285.58  5428.3  289.04  5553.8  291.49
#Mann= 5 ,-1 , 0
  3815.5     .05       0    3894     .16       0  4230.3     .05       0
  4998.5     .03       0  5004.5     .05       0
Bank Sta=4966.2,5022.3
XS Rating Curve= 0 ,0
Exp/Cntr=0.3,0.1

Type RM Length L Ch R = 1 ,4258    ,528,528,528
BEGIN DESCRIPTION:
UNT007 IN BECR 8.0
END DESCRIPTION:
XS GIS Cut Line= 3
      3703160.62     10548864.78      3704118.95     10549350.89
      3704555.49     10549032.15
#Sta/Elev= 30
  4016.7  318.58  4175.3  305.77  4347.8  295.52  4419.4  293.28  4452.9  292.36
  4531.5  286.16  4688.3  278.46  4710.8  276.11  4720.7  277.62  4770.8  276.09
  4787.5  276.88  4793.1  275.65  4809.7  276.64  4943.3  268.44  4948.9  267.18
  4965.6  267.25  4999.3  262.32  5002.1  261.82  5005.3  262.32  5015.7  266.96
    5038  268.37  5046.7  268.84  5099.6  271.66  5220.9  273.68  5306.6  278.06
  5335.9  281.46  5356.8  281.21  5371.5  283.22  5528.3  284.45  5631.8  288.12
#Mann= 5 ,-1 , 0
  4016.7     .05       0  4419.4     .16       0  4999.3     .07       0
  5005.3     .16       0  5046.7     .05       0
Bank Sta=4943.3,5038
XS Rating Curve= 0 ,0
Exp/Cntr=0.3,0.1

Type RM Length L Ch R = 1 ,3730    ,521,521,521
BEGIN DESCRIPTION:
UNT007 IN BECR 7.0
END DESCRIPTION:
XS GIS Cut Line= 4
      3702755.22     10548878.21      3703076.42     10549425.11
      3703909.75     10549733.27      3704525.37     10549100.31
#Sta/Elev= 30
    3597  315.31    3655  313.95  3733.3  311.46  3973.6  309.33  4202.2  300.67
  4356.9  292.42  4488.1  282.93  4609.7   277.2  4767.7  274.71    4853   265.1
  4867.4  264.71  4897.8  261.86  4956.7   260.9  4959.4   260.4  4962.7   260.9
  5008.8  262.23  5044.9  265.53    5060   266.7    5100   268.7  5157.1  266.85
  5291.4   266.2  5369.3   269.5  5546.1   272.9  5553.2  274.59  5574.4  274.23
  5645.1  278.83  5652.3   277.4  5736.9  282.41  5822.2  285.14  6002.7   288.2
#Mann= 8 ,-1 , 0
    3597     .16       0    3655     .05       0  4356.9     .16       0
  4956.7     .07       0  4962.7     .16       0    5060     .05       0
  5736.9     .08       0  5822.2     .05       0
Bank Sta=4867.4,5044.9
XS Rating Curve= 0 ,0
Exp/Cntr=0.3,0.1

Type RM Length L Ch R = 1 ,3209    ,420,420,420
BEGIN DESCRIPTION:
UNT007 IN BECR 6.0
END DESCRIPTION:
XS GIS Cut Line= 3
      3702269.11     10550935.53      3703406.28     10550696.81
      3704569.49     10549546.63
#Sta/Elev= 30
  3050.7  297.28  3056.4  297.23  3081.9  299.35  3271.4  291.73  3370.7  289.24
  3523.5  285.33  3537.8  287.17  3654.1  284.34  3756.3  284.87  3926.7   292.5
  4076.3  294.98  4121.1  299.38  4211.8   298.8  4282.8  293.51  4424.8  280.97
  4559.1  281.76  4728.8  270.31  4799.5  262.85  4824.8  260.24  4827.6  259.74
  4830.8  260.24  5110.7  260.24    5139  262.43  5158.8  265.35  5259.1  275.26
  5278.2  275.63  5315.7   278.8    5436  276.52  5648.1  285.89  5848.5  284.39
#Mann= 10 ,-1 , 0
  3050.7     .05       0  3056.4     .16       0  3271.4     .05       0
  3370.7     .16       0  3523.5     .05       0  4282.8     .16       0
  4824.8    .033       0  4830.8     .16       0  5158.8     .16       0
  5278.2     .05       0
Bank Sta=4799.5,5139
XS Rating Curve= 0 ,0
Exp/Cntr=0.3,0.1

Type RM Length L Ch R = 1 ,2789    ,88,88,88
BEGIN DESCRIPTION:
Mapping XS e501cfd4
END DESCRIPTION:
XS GIS Cut Line= 5
      3703449.72     10550774.93      3704013.92     10550666.43
      3704109.41     10550627.37      3704304.72     10550319.21
      3704721.38     10549676.85
#Sta/Elev= 30
  4165.6  297.75  4297.9   280.3  4328.4  280.15  4450.6  273.18    4471  275.82
    4479  273.95  4491.3  273.84    4501  272.33  4552.4  267.77  4599.6  266.01
    4645  264.97  4674.6  262.59  4702.2  260.24  4704.9  259.74  4708.2  260.24
  5231.5  260.24  5298.1  262.27  5319.2  264.11  5334.4  263.42  5406.9  266.49
  5449.1  271.56  5536.7  271.58  5636.3  275.99  5645.5  275.28  5672.6  277.71
  5754.3  279.19  5760.2  280.22  5775.4  279.54  5926.4  284.84  5973.8  285.43
#Mann= 5 ,-1 , 0
  4165.6     .05       0    4501     .16       0  4599.6     .05       0
  4702.2    .033       0  4708.2     .05       0
Bank Sta=4674.6,5298.1
XS Rating Curve= 0 ,0
Exp/Cntr=0.3,0.1

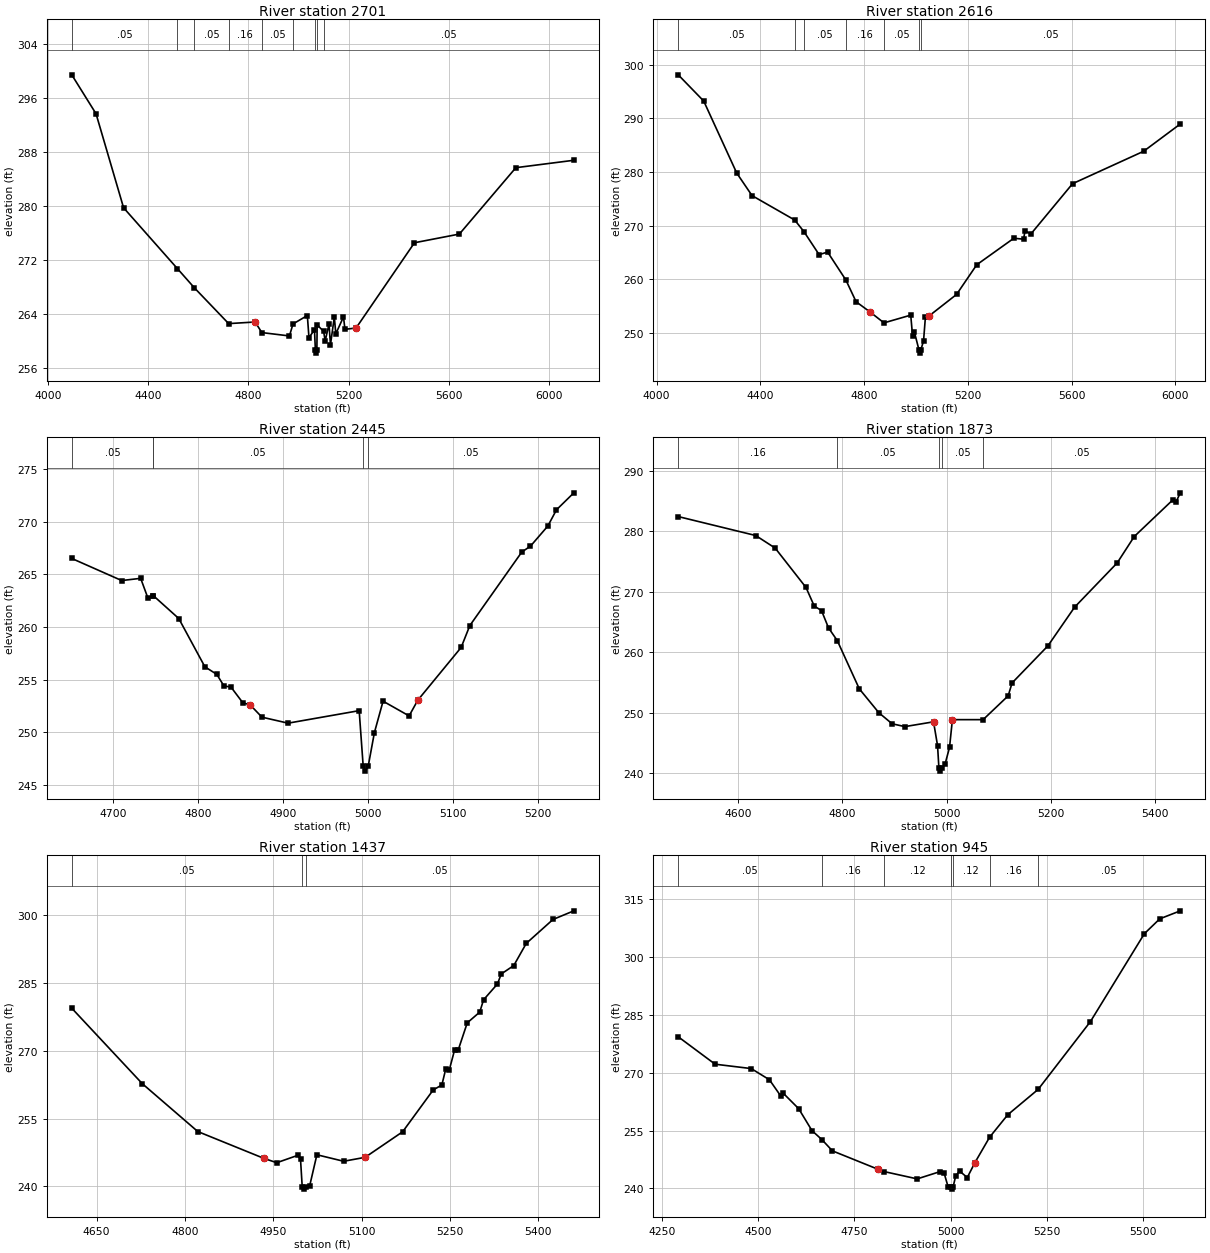
Type RM Length L Ch R = 1 ,2701    ,85,85,85
BEGIN DESCRIPTION:
UNT007 IN BECR 5.0
END DESCRIPTION:
XS GIS Cut Line= 5
      3703384.56     10550857.41      3704018.26     10550727.19
      3704122.43     10550692.47        3704270.     10550518.86
      3704808.21     10549650.77
#Sta/Elev= 30
  4094.1  299.49  4191.1  293.71  4301.1  279.76  4516.4  270.72  4584.2  267.87
  4720.9  262.57  4826.8  262.81  4853.4  261.24  4963.8  260.74    4978  262.52
  5035.3  263.77  5041.8  260.49  5063.8  261.65  5067.4  258.69  5070.1  258.19
  5073.4  258.69  5074.5  262.39  5100.4  261.41  5106.5  259.99  5121.9  262.51
  5127.7  259.43  5143.1  263.56    5149  261.05  5179.7  263.57  5185.6  261.72
  5230.1  261.92  5463.3  274.57  5642.8  275.86  5868.4  285.71  6100.1  286.81
#Mann= 9 ,-1 , 0
  4094.1     .05       0  4516.4     .16       0  4584.2     .05       0
  4720.9     .16       0  4853.4     .05       0    4978     .07       0
  5067.4     .07       0  5073.4     .07       0  5100.4     .05       0
Bank Sta=4826.8,5230.1
XS Rating Curve= 0 ,0
Exp/Cntr=0.3,0.1

Type RM Length L Ch R = 1 ,2616    ,171,171,171
BEGIN DESCRIPTION:
Mapping XS 2f0533f5
END DESCRIPTION:
XS GIS Cut Line= 4
      3703384.62     10550952.88      3704148.47      10550748.9
      3704465.31     10550440.74      3704812.52     10549828.78
#Sta/Elev= 30
  4083.4  298.13  4181.7  293.24    4309  279.82    4368  275.62  4532.5  271.07
  4568.1  268.91  4626.8  264.61  4659.4   265.1    4730  259.88  4769.3  255.84
  4823.4  253.92  4876.8   251.9    4980  253.34  4987.2  249.38  4994.1  250.19
  5012.3  246.76    5015  246.26  5018.3  246.76  5029.4  248.53  5036.6     253
  5050.7  253.19  5156.7   257.2  5234.6  262.73  5377.6  267.67  5415.1   267.5
  5420.9  269.08  5443.1  268.45  5604.1  277.84  5878.1  283.88  6019.6  288.97
#Mann= 7 ,-1 , 0
  4083.4     .05       0  4532.5     .16       0  4568.1     .05       0
    4730     .16       0  4876.8     .05       0  5012.3     .03       0
  5018.3     .05       0
Bank Sta=4823.4,5050.7
XS Rating Curve= 0 ,0
Exp/Cntr=0.3,0.1

Type RM Length L Ch R = 1 ,2445    ,572,572,572
BEGIN DESCRIPTION:
UNT007 IN BECR 4.0
END DESCRIPTION:
XS GIS Cut Line= 3
      3703949.63     10550960.18      3704249.61     10550810.19
      3704499.57      10550760.2
#Sta/Elev= 30
  4651.6  266.51  4710.3  264.41  4732.6  264.62    4741  262.77  4747.3  262.98
  4747.4  262.98  4777.4   260.8  4808.1  256.21  4822.1  255.49  4830.5  254.39
  4838.8  254.28  4852.8  252.78  4861.2   252.6  4875.2  251.42  4905.9  250.85
  4989.5  252.04  4994.2  246.79  4996.9  246.29  5000.2  246.79  5007.4  249.95
  5017.6  252.94  5048.2  251.54  5058.4  253.03  5109.4  258.05  5119.6  260.13
  5180.7  267.12  5190.9  267.68  5211.3  269.59  5221.5  271.14  5241.9  272.75
#Mann= 5 ,-1 , 0
  4651.6     .05       0  4747.3     .16       0  4747.4     .05       0
  4994.2     .03       0  5000.2     .05       0
Bank Sta=4861.2,5058.4
XS Rating Curve= 0 ,0
Exp/Cntr=0.3,0.1

Type RM Length L Ch R = 1 ,1873    ,436,436,436
BEGIN DESCRIPTION:
UNT007 IN BECR 3.0
END DESCRIPTION:
XS GIS Cut Line= 3
       3703940.1     10551495.44      3704300.38     10551291.43
       3704799.6     10551060.19
#Sta/Elev= 30
  4484.8   282.4  4633.6  279.27  4670.9   277.2  4730.1   270.7    4746  267.63
    4760  266.87  4773.4  264.02  4790.2  261.93  4832.5  253.96  4870.1  250.01
  4895.5  248.19    4920  247.72  4975.1  248.51  4982.8  244.58  4985.4  240.87
  4988.1  240.37  4991.4  240.87  4997.2  241.53  5005.8  244.29  5011.3  248.87
  5070.3  248.87  5118.4   252.8  5125.9  254.93  5194.6  261.04    5246  267.44
  5327.8  274.75  5360.5   279.1  5434.8  285.17  5440.3  284.73    5449  286.32
#Mann= 5 ,-1 , 0
  4484.8     .16       0  4790.2     .05       0  4985.4     .07       0
  4991.4     .05       0  5070.3     .05       0
Bank Sta=4975.1,5011.3
XS Rating Curve= 0 ,0
Exp/Cntr=0.3,0.1

Type RM Length L Ch R = 1 ,1437    ,492,492,492
BEGIN DESCRIPTION:
UNT007 IN BECR 2.0
END DESCRIPTION:
XS GIS Cut Line= 3
      3704549.61     10551810.18      3704699.61     10551460.19
      3704949.62     10551060.17
#Sta/Elev= 30
  4607.9   279.4  4727.6  262.72  4821.9  252.13  4934.3  246.19    4956  245.24
  4991.6  246.87  4996.3     246  4999.2   239.9    5002   239.4  5005.2   239.9
  5011.7  240.04  5024.1     247  5069.5  245.56    5106  246.43  5169.7  252.08
  5221.6  261.33  5236.3  262.43  5242.8  265.91  5248.7  265.65  5258.1  270.26
    5264  270.14  5279.4  276.16  5300.6  278.54  5307.1  281.26  5330.7  284.76
  5337.1  286.97  5358.4  288.83  5379.6  293.73    5425  299.02  5460.4  300.93
#Mann= 3 ,-1 , 0
  4607.9     .05       0  4999.2     .03       0  5005.2     .05       0
Bank Sta=4934.3,5106
XS Rating Curve= 0 ,0
Exp/Cntr=0.3,0.1

Type RM Length L Ch R = 1 ,945     ,754,754,754
BEGIN DESCRIPTION:
Mapping XS ffc94a55
END DESCRIPTION:
XS GIS Cut Line= 3
      3704621.53      10551890.4      3705138.05     10551669.03
      3705129.37     10550926.85
#Sta/Elev= 30
  4292.2  279.28    4388  272.18  4481.8  271.05    4529  268.16    4558  264.02
  4563.4  264.82  4605.1  260.66  4639.6  254.98  4665.4  252.65  4692.7  249.74
    4810  245.02  4827.7  244.36    4913  242.48    4973  244.39    4983  243.92
    4993  240.51    5000  240.33  5002.8  239.83    5006  240.33    5013  243.25
    5023   244.5    5043  242.84    5063  246.72  5101.2   253.3  5148.3   259.1
  5227.1  265.66    5363  283.23  5503.1  305.99  5543.1  309.83  5596.4   311.9
#Mann= 7 ,-1 , 0
  4292.2     .05       0  4665.4     .16       0  4827.7     .12       0
    5000     .07       0    5006     .12       0  5101.2     .16       0
  5227.1     .05       0
Bank Sta=4810,5063
XS Rating Curve= 0 ,0
Exp/Cntr=0.3,0.1

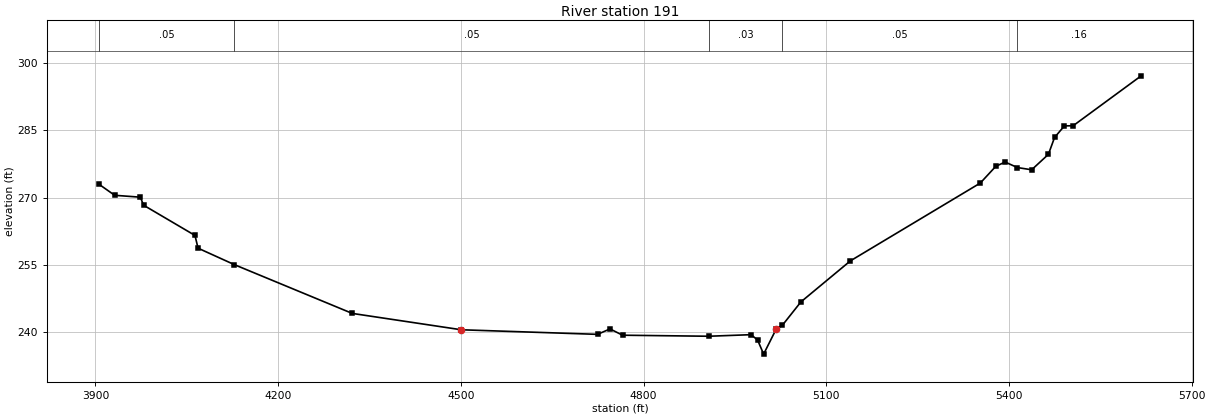
Type RM Length L Ch R = 1 ,191     ,0,0,0
BEGIN DESCRIPTION:
UNT007 IN BECR 1.0
END DESCRIPTION:
XS GIS Cut Line= 4
       3704842.9     10551912.09      3705702.29      10551708.1
      3705810.79     10551673.37      3705936.66     10550970.25
#Sta/Elev= 30
  3905.6  273.02  3931.7  270.53  3973.9  270.11  3979.1  268.33  4063.5   261.6
  4068.6  258.76  4128.3  255.09  4321.8  244.24  4500.9   240.6  4724.5  239.58
    4745  240.79  4765.6  239.39    4907  239.16  4976.6  239.51  4987.3  238.32
  4997.2  235.18  5017.8  240.75  5027.9  241.59  5058.4   246.8  5139.7  255.94
    5353  273.26  5378.4  276.98  5393.7  277.93    5414   276.7  5437.3  276.21
  5464.8  279.65  5474.9  283.41  5491.1  285.98  5505.4  286.01  5617.1  297.12
#Mann= 5 ,-1 , 0
  3905.6     .05       0  4128.3     .05       0    4907     .03       0
  5027.9     .05       0    5414     .16       0
Bank Sta=4500.9,5017.8
XS Rating Curve= 0 ,0
Exp/Cntr=0.3,0.1

Chan Stop Cuts=-1
Use User Specified Reach Order=0
Composite Channel Slope=5