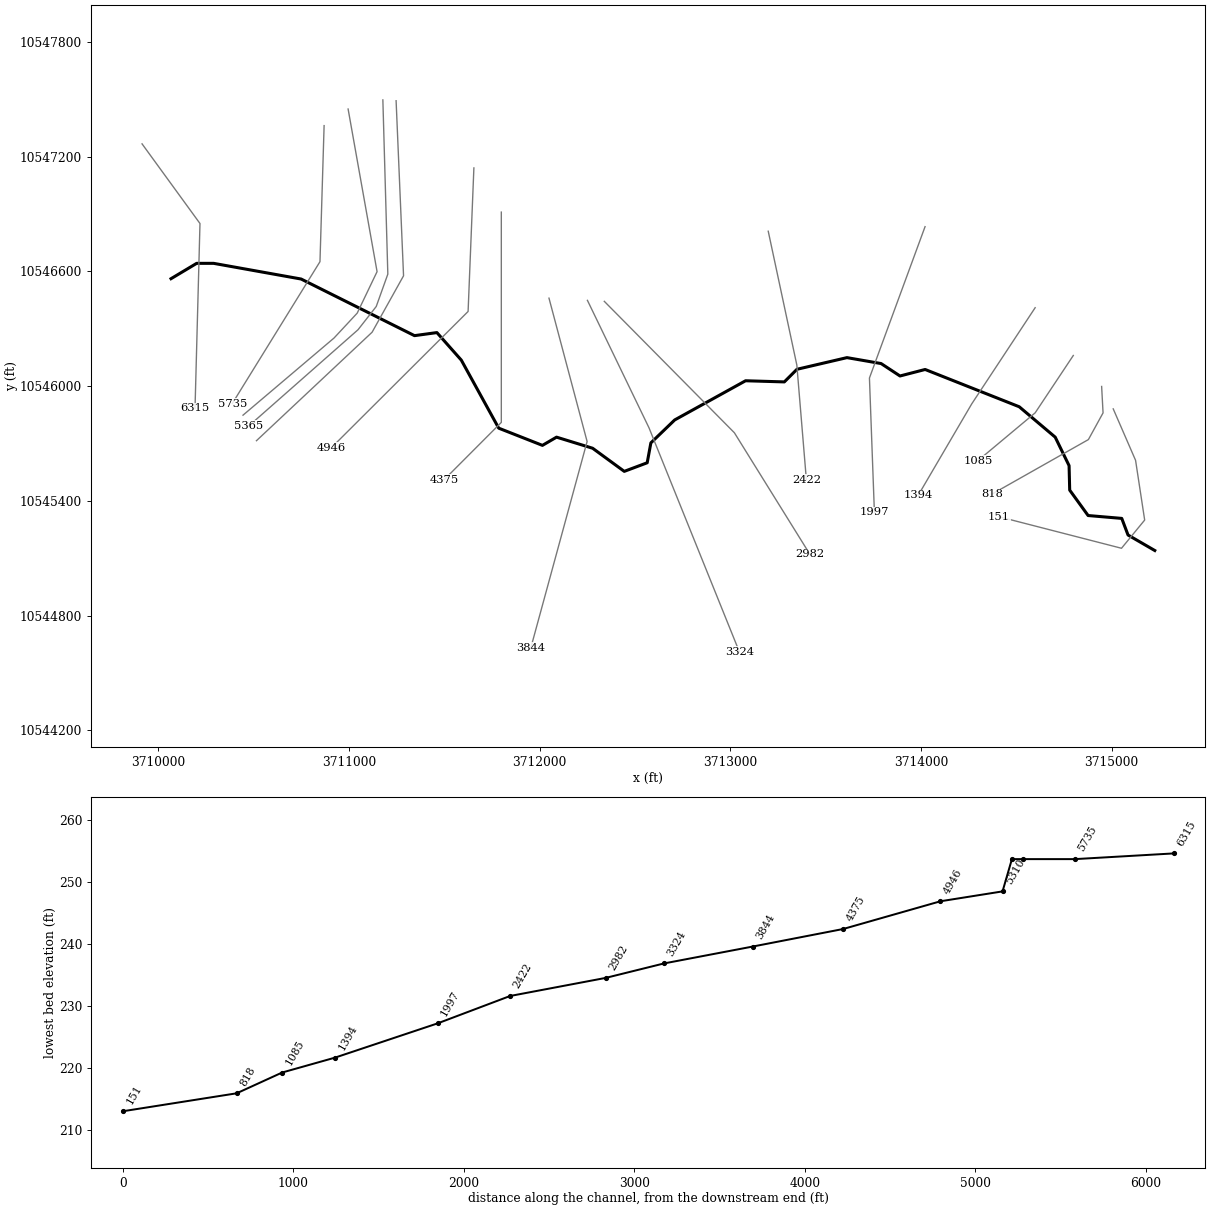
--- UNT009 IN BECR.prj (project) ---

Proj Title=UNT009 IN BECR Base Level Engineering
Current Plan=p01
Default Exp/Contr=0.3,0.1
English Units
Geom File=g01
Flow File=f01
Plan File=p01
Y Axis Title=Elevation
X Axis Title(PF)=Main Channel Distance
X Axis Title(XS)=Station
BEGIN DESCRIPTION:
UNT009 IN BECR
END DESCRIPTION:
DSS Export Rating Curves= 0
DSS Export Rating Curve Sorted= 0
DSS Export Volume Flow Curves= 0
DXF OffsetX= 0
DXF OffsetY= 0
DXF ScaleX= 1
DXF ScaleY= 10

--- UNT009 IN BECR.p01 (plan) ---

Plan Title=Multiple Run
Short Identifier=Multiple
Geom File=g01
Flow File=f01
Subcritical Flow
K Sum by GR= 0
Std Step Tol= 0.01
Critical Tol= 0.01
Num of Std Step Trials= 20
Max Error Tol= 0.3
Flow Tol Ratio= 0.001
Split Flow NTrial= 30
Split Flow Tol= 0.02
Split Flow Ratio= 0.02
Log Output Level= 0
Friction Slope Method= 1
Unsteady Friction Slope Method= 2
Unsteady Bridges Friction Slope Method= 1
Parabolic Critical Depth
Global Vel Dist=  1 , 1 , 1
Global Log Level= 0
CheckData=True
Encroach Param= -1, 0, 0, 0
BEGIN DESCRIPTION:
Multiple Run
END DESCRIPTION:

--- UNT009 IN BECR.f01 (steady flow) ---

Flow Title=Multiple
Program Version=4.10
Number of Profiles= 7
Profile Names=10-year,25-year,50-year,1pct_min,100-year,1pct_plu,500-year
River Rch & RM=UNT009 IN BECR,Reach-1         ,6315
     528     715     870     778    1052    1423    1546
River Rch & RM=UNT009 IN BECR,Reach-1         ,4946
     718     987    1212    1093    1478    1999    2208
River Rch & RM=UNT009 IN BECR,Reach-1         ,151
    1305    1849    2318    2129    2880    3894    4468
Boundary for River Rch & Prof#=UNT009 IN BECR,Reach-1         , 1
Up Type= 0
Dn Type= 3
Dn Slope=0.0083
Boundary for River Rch & Prof#=UNT009 IN BECR,Reach-1         , 2
Up Type= 0
Dn Type= 3
Dn Slope=0.0083
Boundary for River Rch & Prof#=UNT009 IN BECR,Reach-1         , 3
Up Type= 0
Dn Type= 3
Dn Slope=0.0083
Boundary for River Rch & Prof#=UNT009 IN BECR,Reach-1         , 4
Up Type= 0
Dn Type= 3
Dn Slope=0.0083
Boundary for River Rch & Prof#=UNT009 IN BECR,Reach-1         , 5
Up Type= 0
Dn Type= 3
Dn Slope=0.0083
Boundary for River Rch & Prof#=UNT009 IN BECR,Reach-1         , 6
Up Type= 0
Dn Type= 3
Dn Slope=0.0083
Boundary for River Rch & Prof#=UNT009 IN BECR,Reach-1         , 7
Up Type= 0
Dn Type= 3
Dn Slope=0.0083
DSS Import GetInterval= 0
DSS Import GetPeak= 0
DSS Import FillOption= 0

--- UNT009 IN BECR.g01 (geometry) ---

Geom Title=Existing Conditions
Program Version=4.10

River Reach=UNT009 IN BECR  ,Reach-1
Reach XY= 30
      3710067.22     10546561.92      3710201.77     10546642.21
      3710290.74     10546642.21      3710749.61     10546560.19
      3711344.25       10546264.      3711461.75       10546280.
      3711589.75       10546136.        3711786.       10545780.
      3712015.25       10545690.      3712089.25       10545733.
       3712278.5       10545675.       3712444.5       10545554.
      3712564.75       10545599.        3712584.       10545703.
        3712709.       10545823.      3713080.75       10546028.
        3713284.       10546022.      3713350.25       10546088.
       3713612.5       10546149.       3713791.5       10546118.
      3713890.75       10546053.       3714022.5       10546087.
        3714516.       10545892.      3714704.75       10545733.
       3714777.5       10545584.      3714780.75       10545456.
      3714877.25       10545323.      3715053.75       10545308.
      3715086.75       10545221.        3715227.       10545140.

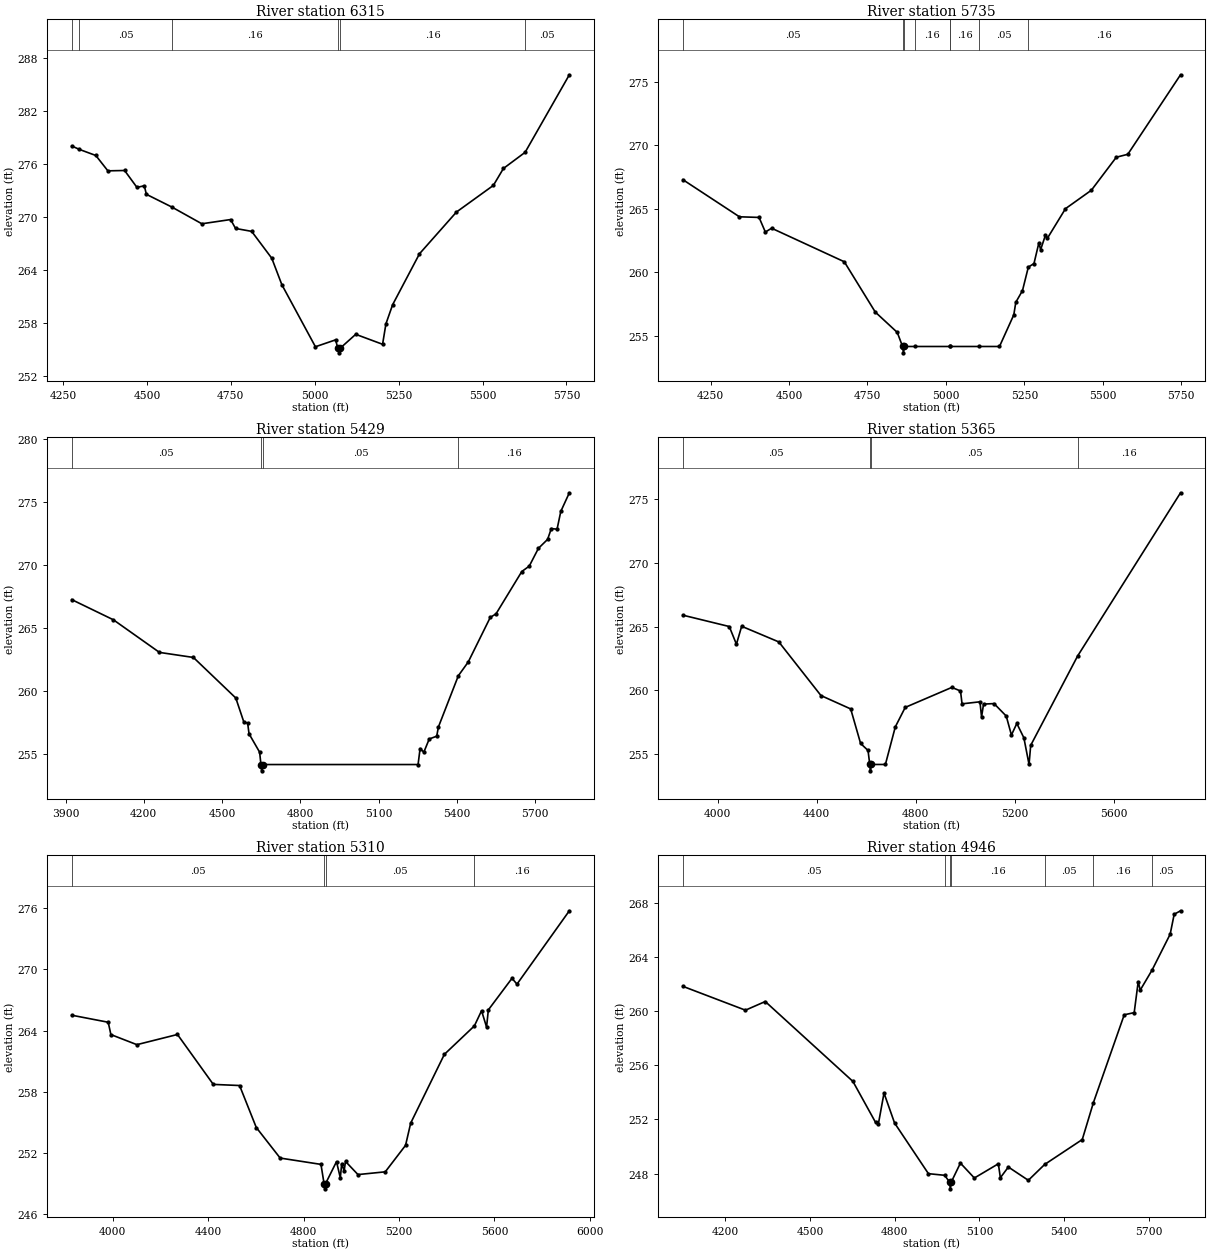
Type RM Length L Ch R = 1 ,6315    ,580,580,580
BEGIN DESCRIPTION:
UNT009 IN BECR 12.0
END DESCRIPTION:
XS GIS Cut Line= 3
       3709915.3     10547267.23      3710219.13     10546850.54
      3710193.12     10545883.89
#Sta/Elev= 30
  4275.9  278.04    4298  277.66  4347.7  276.96  4383.6  275.22  4433.4  275.26
  4470.3  273.34  4492.1  273.53  4498.3  272.56    4574  271.12  4663.6  269.22
  4749.3   269.7    4764  268.69    4812  268.36    4872  265.31    4902  262.31
    5002  255.28    5062  256.06    5069  255.09  5071.8  254.59    5075  255.09
  5122.1  256.69  5202.1  255.56  5212.1  257.88  5232.1  260.05  5312.1  265.82
  5422.2  270.55  5532.2  273.57  5562.2  275.49  5626.8  277.32  5758.6  286.11
#Mann= 6 ,-1 , 0
  4275.9     .16       0    4298     .05       0    4574     .16       0
    5069     .07       0    5075     .16       0  5626.8     .05       0
Bank Sta=5069,5075
XS Rating Curve= 0 ,0
Exp/Cntr=0.3,0.1

Type RM Length L Ch R = 1 ,5735    ,306,306,306
BEGIN DESCRIPTION:
UNT009 IN BECR 11.0
END DESCRIPTION:
XS GIS Cut Line= 3
      3710870.17     10547362.65      3710848.47     10546650.89
       3710388.4     10545908.71
#Sta/Elev= 30
  4162.1   267.3  4342.1  264.38  4404.7  264.33  4424.7  263.18  4444.7  263.48
  4676.2  260.84  4774.9  256.88  4844.9  255.28  4861.9  254.17  4864.6  253.67
  4867.9  254.17  4901.5  254.17  5012.4  254.17    5013  254.17  5105.3  254.17
  5170.6  254.17  5216.2  256.66  5222.6  257.65  5243.9  258.57  5262.5  260.42
  5280.5   260.7  5295.9  262.31  5301.8   261.8  5317.1  262.94    5323  262.68
  5380.9  265.02  5463.3  266.47  5542.8  269.07  5579.4   269.3  5747.4  275.56
#Mann= 8 ,-1 , 0
  4162.1     .05       0  4861.9     .07       0  4867.9     .05       0
  4901.5     .16       0  5012.4     .05       0    5013     .16       0
  5105.3     .05       0  5262.5     .16       0
Bank Sta=4861.9,4867.9
XS Rating Curve= 0 ,0
Exp/Cntr=0.3,0.1

Type RM Length L Ch R = 1 ,5429    ,64,64,64
BEGIN DESCRIPTION:
Mapping XS 27480a9d
END DESCRIPTION:
XS GIS Cut Line= 5
      3710996.04     10547449.46      3711147.95     10546598.81
      3711043.78     10546381.79      3710922.25     10546251.59
      3710444.85     10545847.96
#Sta/Elev= 30
  3923.7  267.26  4083.3  265.66  4260.1  263.07  4390.2  262.67  4552.8  259.45
  4583.2  257.57  4598.3  257.45  4603.6  256.61  4644.2  255.15  4649.2  254.17
  4651.9  253.67  4655.2  254.17  5251.7  254.17  5259.5  255.44  5273.8  255.15
  5294.6   256.2  5323.2  256.42  5329.7  257.15  5406.2  261.22  5444.1  262.31
  5528.6  265.85  5550.6  266.13  5649.5  269.49  5678.1  269.92  5713.2  271.33
  5748.4  272.04  5762.6   272.9  5784.7  272.85    5799  274.26  5831.8  275.74
#Mann= 4 ,-1 , 0
  3923.7     .05       0  4649.2     .03       0  4655.2     .05       0
  5406.2     .16       0
Bank Sta=4649.2,4655.2
XS Rating Curve= 0 ,0
Exp/Cntr=0.3,0.1

Type RM Length L Ch R = 1 ,5365    ,55,55,55
BEGIN DESCRIPTION:
Mapping XS a08e4c9c
END DESCRIPTION:
XS GIS Cut Line= 5
      3711178.33     10547497.21      3711204.37     10546585.79
      3711143.61     10546416.52      3711048.12     10546294.99
       3710475.2     10545791.52
#Sta/Elev= 30
  3860.3  265.89  4047.4     265  4076.3  263.61  4097.4  265.02  4247.5  263.79
  4417.6  259.58  4537.6  258.53  4577.6  255.82  4607.6  255.27  4614.6  254.17
  4617.4  253.67  4620.6  254.17  4677.7  254.17  4717.7  257.12  4757.7  258.65
  4945.9  260.22  4980.9  259.94  4987.2  258.93  5059.5  259.09  5065.9  257.89
  5073.9  258.91  5116.3  258.95  5165.6  257.97  5186.5  256.48  5208.3  257.39
  5236.8  256.26  5257.6  254.17  5264.3  255.67  5453.6  262.68  5869.2   275.5
#Mann= 4 ,-1 , 0
  3860.3     .05       0  4614.6     .03       0  4620.6     .05       0
  5453.6     .16       0
Bank Sta=4614.6,4620.6
XS Rating Curve= 0 ,0
Exp/Cntr=0.3,0.1

Type RM Length L Ch R = 1 ,5310    ,364,364,364
BEGIN DESCRIPTION:
Mapping XS 4cdbfa44
END DESCRIPTION:
XS GIS Cut Line= 4
      3711247.77     10547492.92      3711286.84     10546577.11
      3711121.91     10546281.97      3710515.37     10545714.42
#Sta/Elev= 30
  3828.4  265.51  3981.3  264.82  3992.5  263.61  4101.4  262.62  4271.5  263.62
  4421.7  258.72  4531.8  258.61  4601.8  254.49  4701.9  251.49  4872.9  250.87
  4885.9  248.97  4888.7  248.47  4891.9  248.97    4938  251.14    4954  249.55
  4959.8  250.94    4970  250.23  4975.7  251.16  5027.9  249.87  5142.4  250.14
  5227.4  252.74  5248.9  254.92  5390.1  261.67  5515.8  264.46  5545.9  265.95
  5566.9  264.34  5574.3  266.03  5673.4  269.13  5694.4  268.56  5913.8  275.76
#Mann= 4 ,-1 , 0
  3828.4     .05       0  4885.9     .03       0  4891.9     .05       0
  5515.8     .16       0
Bank Sta=4885.9,4891.9
XS Rating Curve= 0 ,0
Exp/Cntr=0.3,0.1

Type RM Length L Ch R = 1 ,4946    ,571,571,571
BEGIN DESCRIPTION:
UNT009 IN BECR 10.0
END DESCRIPTION:
XS GIS Cut Line= 3
      3711655.76     10547141.35      3711625.38     10546390.48
      3710909.24     10545678.68
#Sta/Elev= 30
  4050.6  261.83  4271.9  260.07    4342  260.71  4652.3  254.81  4732.3  251.79
  4742.3  251.66  4762.3  253.95  4799.7  251.74  4919.5     248  4976.9  247.88
  4994.3  247.38    4997  246.88  5000.3  247.38  5032.7  248.78  5082.1  247.68
    5167  248.73  5174.1   247.7  5202.4  248.49  5273.1  247.51  5330.9  248.68
    5464  250.52  5503.5  253.25  5612.5  259.73  5647.8  259.89    5662  262.18
  5669.1  261.55    5711  263.03  5775.1  265.68  5789.3  267.15  5811.8  267.41
#Mann= 7 ,-1 , 0
  4050.6     .05       0  4976.9     .16       0  4994.3     .07       0
  5000.3     .16       0  5330.9     .05       0  5503.5     .16       0
    5711     .05       0
Bank Sta=4994.3,5000.3
XS Rating Curve= 0 ,0
Exp/Cntr=0.3,0.1

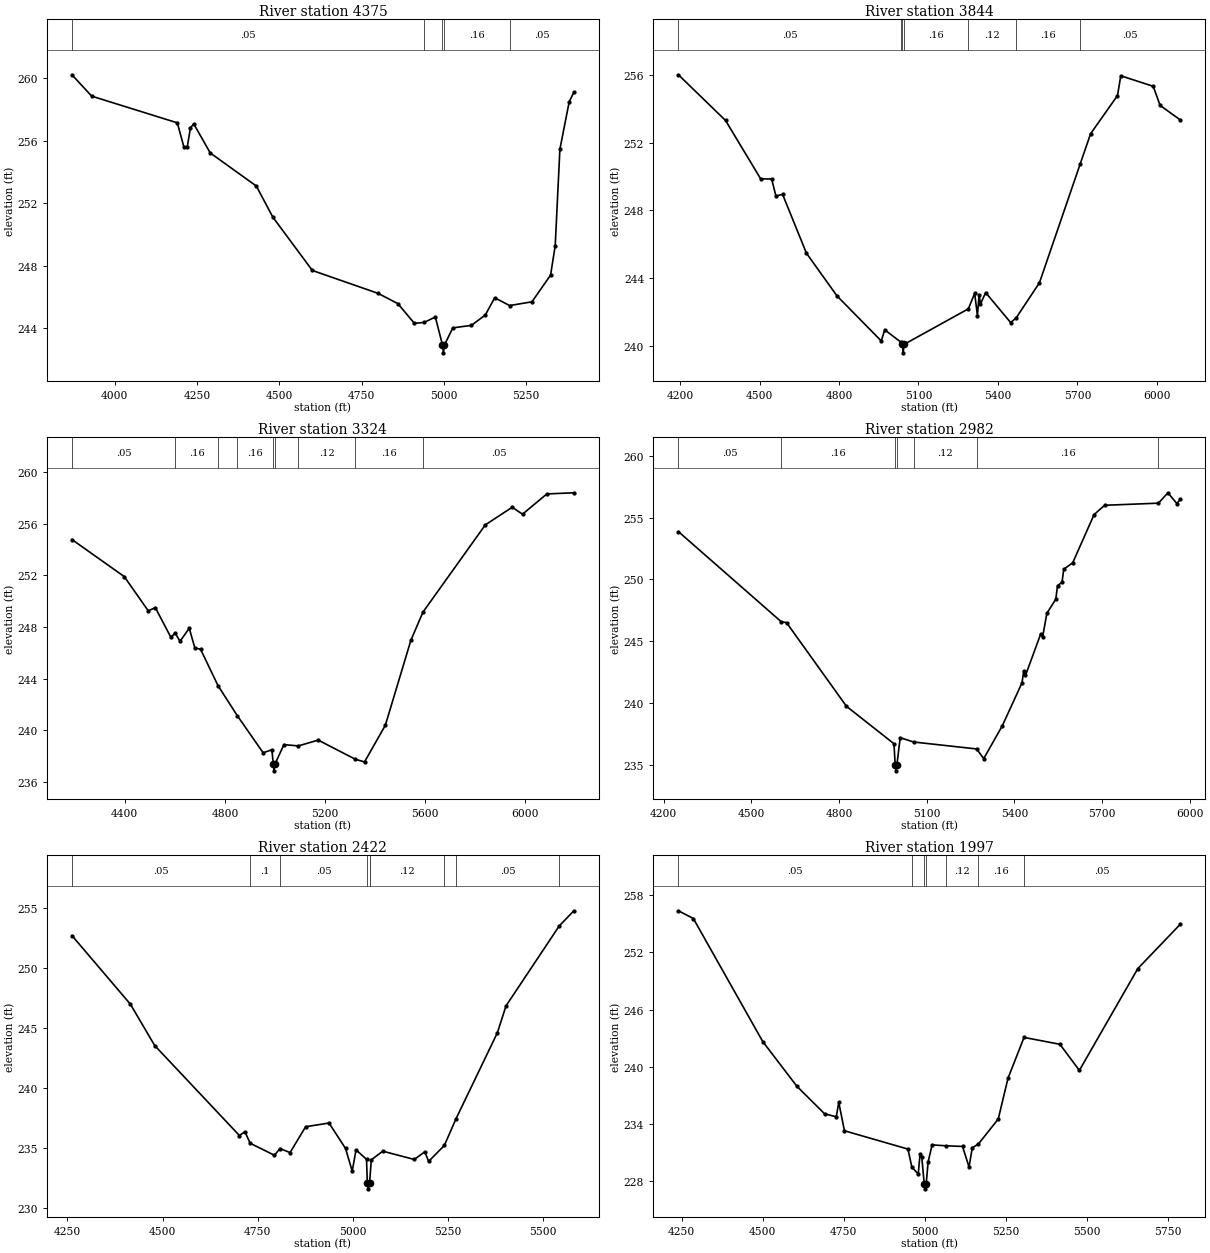
Type RM Length L Ch R = 1 ,4375    ,531,531,531
BEGIN DESCRIPTION:
UNT009 IN BECR 9.0
END DESCRIPTION:
XS GIS Cut Line= 3
      3711799.61     10546910.22      3711799.61     10545810.19
      3711499.61     10545510.19
#Sta/Elev= 30
  3870.3  260.23  3930.3  258.86  4190.3  257.15  4210.3   255.6  4220.3  255.58
  4230.3  256.84  4240.3  257.08  4290.3  255.22  4430.3   253.1  4480.3  251.11
  4600.3  247.69  4800.3  246.22  4860.3  245.56  4910.3   244.3  4940.4  244.36
  4973.9  244.71  4995.6  242.91  4998.4  242.41  5001.6  242.91  5026.9  244.01
  5083.5  244.17  5125.9  244.84  5154.2  245.94  5199.5  245.44  5267.3  245.68
  5323.9  247.39    5338  249.28  5352.2  255.46  5380.5   258.5  5394.6  259.11
#Mann= 5 ,-1 , 0
  3870.3     .05       0  4940.4     .16       0  4995.6     .07       0
  5001.6     .16       0  5199.5     .05       0
Bank Sta=4995.6,5001.6
XS Rating Curve= 0 ,0
Exp/Cntr=0.3,0.1

Type RM Length L Ch R = 1 ,3844    ,520,520,520
BEGIN DESCRIPTION:
UNT009 IN BECR 8.0
END DESCRIPTION:
XS GIS Cut Line= 3
      3712049.62     10546460.16      3712249.61     10545710.19
       3711954.5     10544631.41
#Sta/Elev= 30
  4193.8  256.01  4371.7  253.31  4504.3  249.86  4545.7  249.85  4561.8  248.85
  4587.1  248.94    4677  245.47  4792.1  242.95  4959.6  240.28  4972.6  240.94
  5032.8  240.22  5039.6  240.08  5042.3  239.58  5045.6  240.08  5288.3  242.18
  5312.1   243.1  5322.5  241.78  5328.8  243.02    5334  242.47  5353.6  243.14
  5447.9  241.37  5468.5  241.64  5556.6  243.72    5710  250.72  5749.8  252.53
  5851.2  254.78  5863.7  255.95    5986  255.33  6012.1   254.2  6088.4  253.34
#Mann= 7 ,-1 , 0
  4193.8     .05       0  5032.8     .16       0  5039.6     .03       0
  5045.6     .16       0  5288.3     .12       0  5468.5     .16       0
    5710     .05       0
Bank Sta=5039.6,5045.6
XS Rating Curve= 0 ,0
Exp/Cntr=0.3,0.1

Type RM Length L Ch R = 1 ,3324    ,342,342,342
BEGIN DESCRIPTION:
UNT009 IN BECR 7.0
END DESCRIPTION:
XS GIS Cut Line= 3
      3712251.27     10546448.59      3712574.16     10545781.97
      3713048.12     10544610.09
#Sta/Elev= 30
    4189  254.77    4398   251.9  4493.8  249.25    4522   249.5  4584.2   247.2
  4601.3  247.53  4620.6  246.89  4657.5   247.9    4680  246.37  4702.6  246.28
  4772.4  243.46  4849.5  241.13  4952.7  238.26  4987.6  238.49  4993.4  237.36
  4996.1  236.86  4999.4  237.36  5035.8  238.89  5093.4  238.79  5172.6  239.24
  5320.8  237.76  5357.7  237.55  5440.8  240.39  5542.7  246.96  5591.1  249.15
  5840.4  255.91  5947.7  257.27  5988.7  256.73  6085.8   258.3  6193.8  258.39
#Mann= 9 ,-1 , 0
    4189     .05       0  4601.3     .16       0  4772.4     .05       0
  4849.5     .16       0  4993.4     .07       0  4999.4     .16       0
  5093.4     .12       0  5320.8     .16       0  5591.1     .05       0
Bank Sta=4993.4,4999.4
XS Rating Curve= 0 ,0
Exp/Cntr=0.3,0.1

Type RM Length L Ch R = 1 ,2982    ,560,560,560
BEGIN DESCRIPTION:
UNT009 IN BECR 6.0
END DESCRIPTION:
XS GIS Cut Line= 3
      3712339.79     10546443.42      3713022.08     10545755.93
      3713417.91     10545120.52
#Sta/Elev= 30
  4250.5  253.87  4602.1  246.59  4620.4  246.51  4825.4  239.75    4988  236.72
  4992.1  235.03  4994.9  234.53  4998.1  235.03  5009.3  237.21  5055.6  236.86
  5270.7   236.3  5295.1  235.52  5358.8  238.18  5426.1  241.65    5432  242.61
  5437.9  242.24  5489.8  245.58  5496.8  245.37    5511  247.26  5541.7  248.41
  5547.6   249.5    5563  249.77  5568.9  250.83  5599.5  251.35  5672.7  255.25
  5708.9     256  5892.8  256.17  5925.2  257.01  5955.9  256.14  5967.7  256.49
#Mann= 7 ,-1 , 0
  4250.5     .05       0  4602.1     .16       0  4992.1     .07       0
  4998.1     .16       0  5055.6     .12       0  5270.7     .16       0
  5892.8     .05       0
Bank Sta=4992.1,4998.1
XS Rating Curve= 0 ,0
Exp/Cntr=0.3,0.1

Type RM Length L Ch R = 1 ,2422    ,425,425,425
BEGIN DESCRIPTION:
UNT009 IN BECR 5.0
END DESCRIPTION:
XS GIS Cut Line= 3
      3713199.61      10546810.2      3713349.61     10546110.19
      3713399.61     10545510.17
#Sta/Elev= 30
  4262.2  252.67  4415.6  246.97  4479.5  243.53    4702  236.05  4716.5  236.37
  4730.1  235.41    4794  234.41  4808.4  234.97  4834.9  234.63  4875.8  236.78
  4937.2  237.09  4980.6  234.98  4998.2  233.09  5008.2  234.86  5035.8  234.07
  5037.8  232.12  5040.6  231.62  5043.8  232.12  5043.9  232.16  5048.3  234.03
  5078.4  234.75  5161.2  234.06  5188.8   234.7  5198.9   233.9  5240.2  235.23
  5270.4  237.42  5379.5   244.6  5402.1  246.83  5541.8  253.47  5580.2  254.73
#Mann= 9 ,-1 , 0
  4262.2     .05       0  4730.1      .1       0  4808.4     .05       0
  5037.8     .03       0  5043.8     .05       0  5043.9     .12       0
  5240.2     .16       0  5270.4     .05       0  5541.8     .16       0
Bank Sta=5037.8,5043.8
XS Rating Curve= 0 ,0
Exp/Cntr=0.3,0.1

Type RM Length L Ch R = 1 ,1997    ,603,603,603
BEGIN DESCRIPTION:
UNT009 IN BECR 4.0
END DESCRIPTION:
XS GIS Cut Line= 3
      3714022.08     10546834.05      3713730.41     10546042.38
      3713756.45     10545339.25
#Sta/Elev= 30
  4240.1  256.37  4286.1  255.56    4500  242.66    4605  237.98    4691  235.07
  4726.8  234.77  4734.4  236.28  4751.9   233.3  4947.6  231.38  4959.7   229.5
  4979.5  228.76  4984.9  230.83  4990.2  230.59  4997.9  227.71  5000.6  227.21
  5003.9  227.71    5010  230.05  5022.2  231.82  5065.7  231.72    5116  231.66
    5136   229.5    5146  231.51  5165.1  231.92  5226.1  234.53  5256.1   238.8
  5305.6  243.09  5416.2  242.37  5476.2  239.63  5656.4  250.31  5787.4  254.96
#Mann= 7 ,-1 , 0
  4240.1     .05       0  4959.7     .16       0  4997.9     .07       0
  5003.9     .16       0  5065.7     .12       0  5165.1     .16       0
  5305.6     .05       0
Bank Sta=4997.9,5003.9
XS Rating Curve= 0 ,0
Exp/Cntr=0.3,0.1

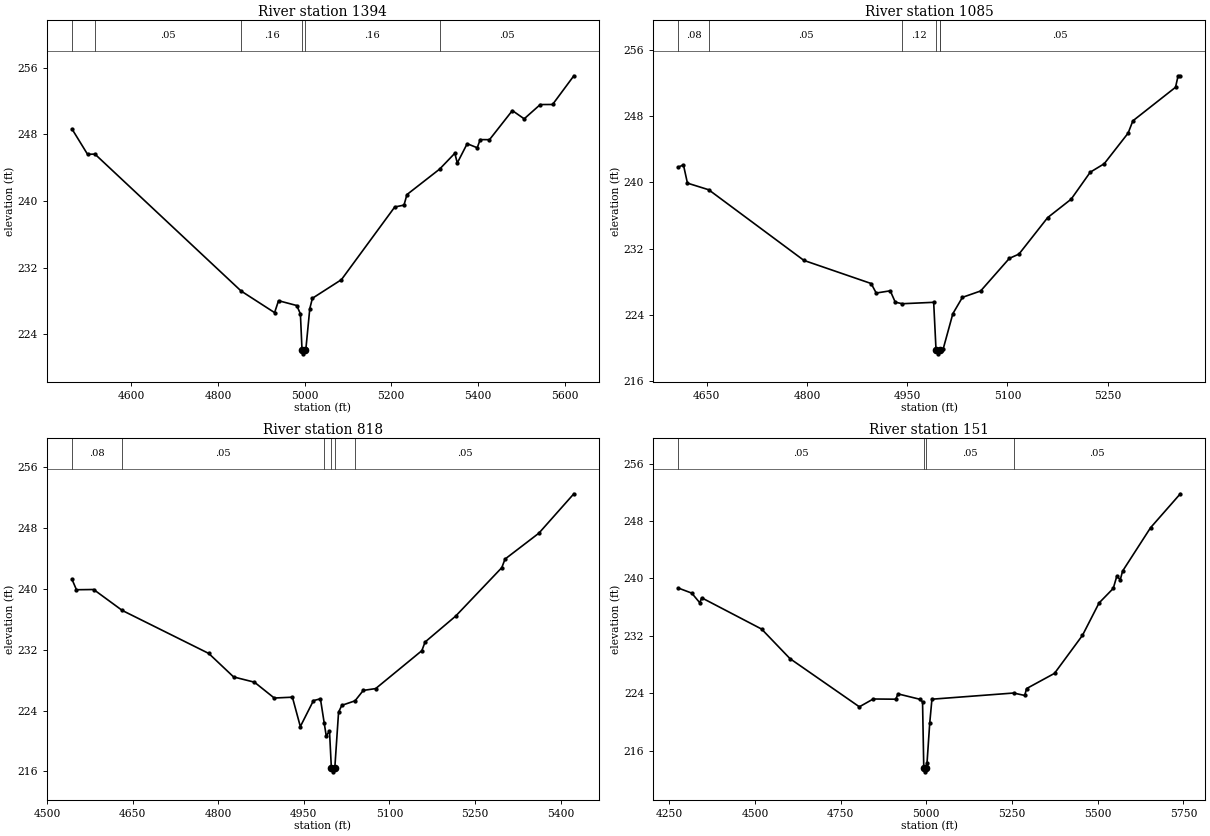
Type RM Length L Ch R = 1 ,1394    ,309,309,309
BEGIN DESCRIPTION:
UNT009 IN BECR 3.0
END DESCRIPTION:
XS GIS Cut Line= 3
      3714599.61      10546410.2      3714266.87     10545906.97
      3713985.62      10545427.8
#Sta/Elev= 30
  4462.7  248.64  4498.7   245.6  4515.8  245.62  4853.3  229.21  4930.6  226.62
  4939.7  228.05  4981.8  227.47  4990.2  226.47  4993.9  222.18  4996.6  221.68
  4999.9  222.18  5002.9  222.29  5011.9  227.11  5017.9  228.34  5084.9  230.57
    5208  239.28  5229.4  239.51  5236.2  240.77  5311.6  243.82  5346.7  245.72
  5352.5  244.56  5375.3  246.87  5398.5  246.38  5405.3  247.36  5426.8  247.35
  5479.6  250.84  5506.9  249.85    5544  251.56  5572.5  251.57  5621.6  255.01
#Mann= 6 ,-1 , 0
  4462.7     .08       0  4515.8     .05       0  4853.3     .16       0
  4993.9     .07       0  4999.9     .16       0  5311.6     .05       0
Bank Sta=4993.9,4999.9
XS Rating Curve= 0 ,0
Exp/Cntr=0.3,0.1

Type RM Length L Ch R = 1 ,1085    ,267,267,267
BEGIN DESCRIPTION:
UNT009 IN BECR 2.0
END DESCRIPTION:
XS GIS Cut Line= 3
      3714799.61     10546160.19      3714599.61     10545860.19
      3714299.58     10545610.17
#Sta/Elev= 30
  4607.6  241.84  4615.1  242.11  4621.1   239.9  4652.9   239.1  4795.4  230.57
    4896  227.78  4903.6  226.63  4924.6   226.9  4932.1  225.53  4942.5  225.34
  4989.6  225.51  4993.1  219.79  4995.9  219.29  4999.1  219.79  4999.7   219.8
  5003.9   219.9  5018.3  224.14  5032.6  226.11  5059.9  226.88  5102.9  230.82
  5117.2  231.33  5160.2  235.74  5195.3  237.96  5223.9  241.22  5244.8  242.24
  5280.6  245.94  5287.7  247.42  5351.5  251.47  5355.4  252.86  5358.7  252.86
#Mann= 6 ,-1 , 0
  4607.6     .08       0  4652.9     .05       0  4942.5     .12       0
  4993.1     .03       0  4999.1     .12       0  4999.7     .05       0
Bank Sta=4993.1,4999.1
XS Rating Curve= 0 ,0
Exp/Cntr=0.3,0.1

Type RM Length L Ch R = 1 ,818     ,667,667,667
BEGIN DESCRIPTION:
Mapping XS f4ec59a9
END DESCRIPTION:
XS GIS Cut Line= 4
      3714948.29     10545998.12      3714955.72     10545859.92
      3714878.85     10545720.34      3714372.16     10545434.51
#Sta/Elev= 30
  4543.6  241.25  4551.5  239.87  4581.6   239.9  4631.7  237.15  4783.3   231.5
  4826.9  228.41  4863.4  227.72  4898.1  225.64  4929.9  225.75  4943.8  221.89
  4966.8   225.3    4979  225.54  4985.7  222.33  4989.2  220.65  4994.9  221.31
  4998.2  216.44    5001  215.94  5004.2  216.44  5010.8  223.78  5016.5  224.68
  5039.6  225.27  5054.1  226.64  5075.8  226.88  5156.7  231.86  5162.4     233
  5215.9   236.4  5296.8  242.77  5302.5   243.9  5361.8   247.3  5423.1  252.48
#Mann= 6 ,-1 , 0
  4543.6     .08       0  4631.7     .05       0  4985.7     .12       0
  4998.2     .07       0  5004.2     .12       0  5039.6     .05       0
Bank Sta=4998.2,5004.2
XS Rating Curve= 0 ,0
Exp/Cntr=0.3,0.1

Type RM Length L Ch R = 1 ,151     ,0,0,0
BEGIN DESCRIPTION:
UNT009 IN BECR 1.0
END DESCRIPTION:
XS GIS Cut Line= 5
      3715009.07      10545880.9      3715126.25     10545611.83
      3715173.99     10545299.33      3715052.46     10545151.76
      3714410.07      10545316.7
#Sta/Elev= 30
  4276.9  238.65  4315.8  237.95  4339.3   236.6  4344.7   237.3  4519.6  232.94
  4602.4  228.82  4804.7  222.11  4845.2   223.2  4910.9  223.17  4917.4  223.91
  4981.2  223.16    4989  222.81  4992.6  213.55  4995.3  213.05  4998.6  213.55
    5002  214.24  5009.9  219.81  5016.4  223.17  5254.5  224.03  5287.1  223.69
  5292.4  224.65  5373.9  226.77  5455.4  232.06  5503.9  236.58  5545.2   238.6
  5555.5  240.28  5565.9  239.84  5572.5  241.02    5654  247.06  5740.9  251.79
#Mann= 4 ,-1 , 0
  4276.9     .05       0  4992.6     .07       0  4998.6     .05       0
  5254.5     .05       0
Bank Sta=4992.6,4998.6
XS Rating Curve= 0 ,0
Exp/Cntr=0.3,0.1

Chan Stop Cuts=-1
Use User Specified Reach Order=0
Composite Channel Slope=5