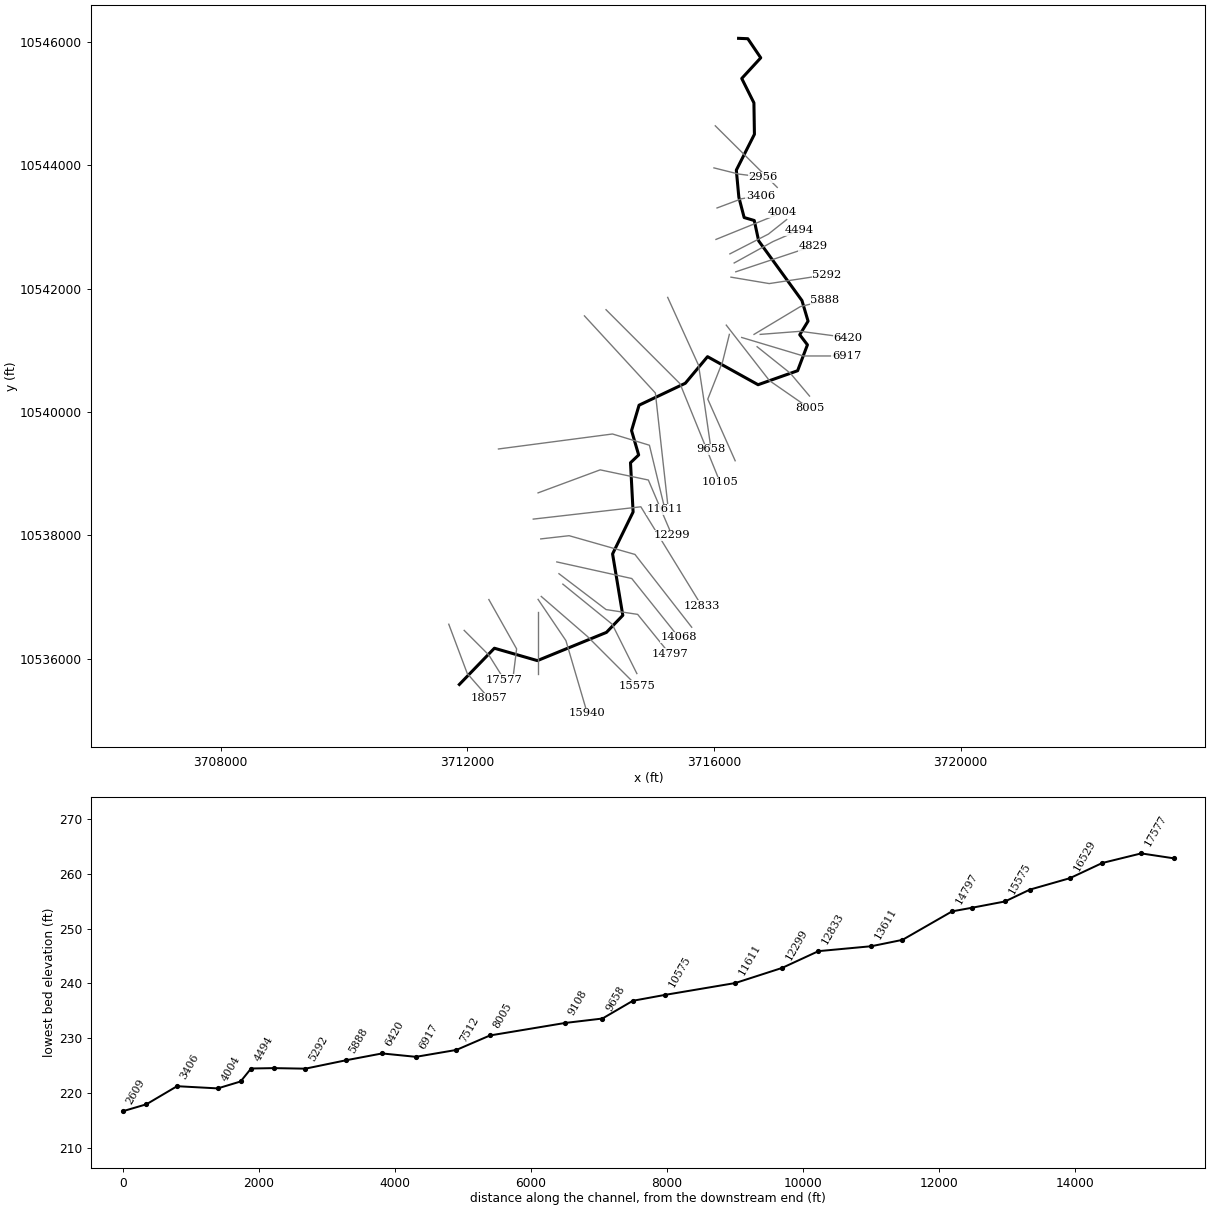
--- UNT010 IN BECR.prj (project) ---

Proj Title=UNT010 IN BECR Base Level Engineering
Current Plan=p01
Default Exp/Contr=0.3,0.1
English Units
Geom File=g01
Flow File=f01
Plan File=p01
Y Axis Title=Elevation
X Axis Title(PF)=Main Channel Distance
X Axis Title(XS)=Station
BEGIN DESCRIPTION:
UNT010 IN BECR
END DESCRIPTION:
DSS Export Rating Curves= 0
DSS Export Rating Curve Sorted= 0
DSS Export Volume Flow Curves= 0
DXF OffsetX= 0
DXF OffsetY= 0
DXF ScaleX= 1
DXF ScaleY= 10

--- UNT010 IN BECR.p01 (plan) ---

Plan Title=Multiple Run
Short Identifier=Multiple
Geom File=g01
Flow File=f01
Subcritical Flow
K Sum by GR= 0
Std Step Tol= 0.01
Critical Tol= 0.01
Num of Std Step Trials= 20
Max Error Tol= 0.3
Flow Tol Ratio= 0.001
Split Flow NTrial= 30
Split Flow Tol= 0.02
Split Flow Ratio= 0.02
Log Output Level= 0
Friction Slope Method= 1
Unsteady Friction Slope Method= 2
Unsteady Bridges Friction Slope Method= 1
Parabolic Critical Depth
Global Vel Dist=  1 , 1 , 1
Global Log Level= 0
CheckData=True
Encroach Param= -1, 0, 0, 0
BEGIN DESCRIPTION:
Multiple Run
END DESCRIPTION:

--- UNT010 IN BECR.f01 (steady flow) ---

Flow Title=Multiple
Program Version=4.10
Number of Profiles= 7
Profile Names=10-year,25-year,50-year,1pct_min,100-year,1pct_plu,500-year
River Rch & RM=UNT010 IN BECR,Reach-1         ,18057
     787    1082    1329    1198    1620    2191    2417
River Rch & RM=UNT010 IN BECR,Reach-1         ,7512
    1017    1412    1745    1580    2137    2890    3221
River Rch & RM=UNT010 IN BECR,Reach-1         ,956
    1017    1412    1745    1580    2137    2890    3221
Boundary for River Rch & Prof#=UNT010 IN BECR,Reach-1         , 1
Up Type= 0
Dn Type= 3
Dn Slope=0.005
Boundary for River Rch & Prof#=UNT010 IN BECR,Reach-1         , 2
Up Type= 0
Dn Type= 3
Dn Slope=0.005
Boundary for River Rch & Prof#=UNT010 IN BECR,Reach-1         , 3
Up Type= 0
Dn Type= 3
Dn Slope=0.005
Boundary for River Rch & Prof#=UNT010 IN BECR,Reach-1         , 4
Up Type= 0
Dn Type= 3
Dn Slope=0.005
Boundary for River Rch & Prof#=UNT010 IN BECR,Reach-1         , 5
Up Type= 0
Dn Type= 3
Dn Slope=0.005
Boundary for River Rch & Prof#=UNT010 IN BECR,Reach-1         , 6
Up Type= 0
Dn Type= 3
Dn Slope=0.005
Boundary for River Rch & Prof#=UNT010 IN BECR,Reach-1         , 7
Up Type= 0
Dn Type= 3
Dn Slope=0.005
DSS Import GetInterval= 0
DSS Import GetPeak= 0
DSS Import FillOption= 0

--- UNT010 IN BECR.g01 (geometry) ---

Geom Title=Existing Conditions
Program Version=4.10

River Reach=UNT010 IN BECR  ,Reach-1
Reach XY= 30
      3711870.84      10535583.3      3712439.25       10536171.
      3713136.75       10535970.      3714256.25       10536428.
       3714521.5       10536704.      3714355.75       10537700.
       3714688.5       10538380.       3714646.5       10539179.
      3714778.75       10539305.       3714663.5       10539700.
      3714785.25       10540112.       3715535.5       10540468.
       3715895.5       10540899.      3716715.25       10540444.
      3717356.25       10540671.       3717515.5       10541091.
      3717390.75       10541254.      3717525.75       10541475.
      3717426.75       10541809.       3716724.5       10542777.
       3716653.5       10543107.       3716489.5       10543155.
      3716403.25       10543485.       3716362.5       10543924.
        3716656.       10544505.      3716647.75       10545015.
      3716450.25       10545410.       3716758.5       10545745.
      3716548.75       10546055.        3716399.       10546061.

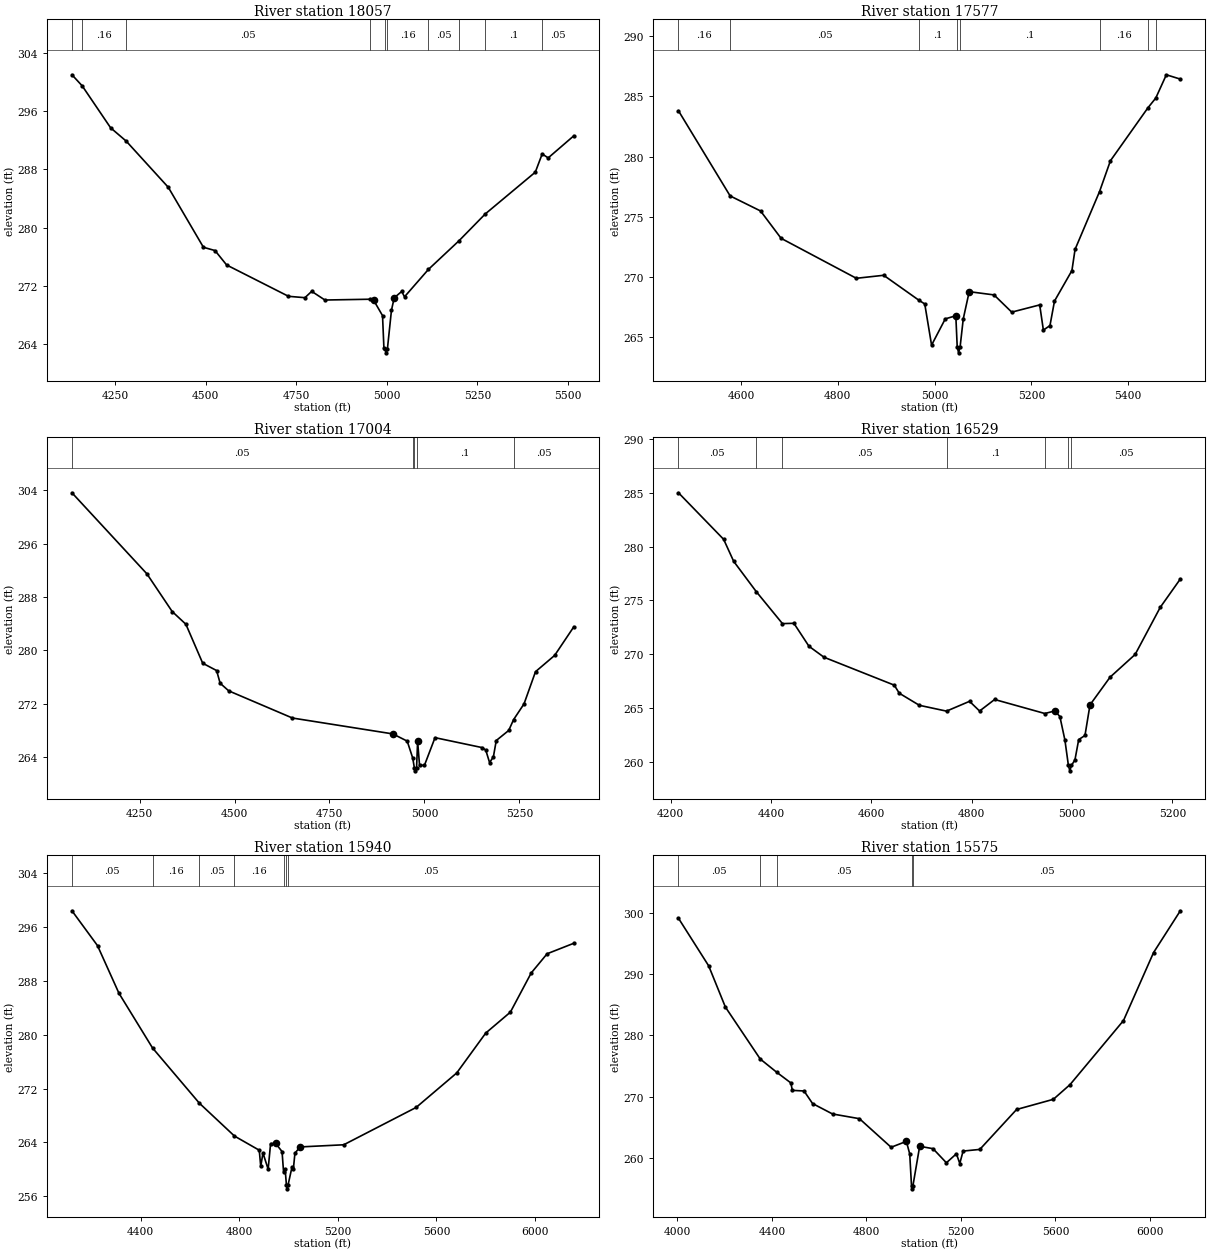
Type RM Length L Ch R = 1 ,18057   ,480,480,480
BEGIN DESCRIPTION:
UNT010 IN BECR 29.0
END DESCRIPTION:
XS GIS Cut Line= 3
      3711699.62     10536560.15      3711999.61     10535760.19
      3712349.63     10535360.17
#Sta/Elev= 30
  4130.2  300.98  4158.5  299.46    4237   293.7  4280.1  291.87  4396.3  285.53
  4493.3   277.3  4525.3  276.85  4557.4  274.87  4728.2  270.57  4773.6  270.38
  4792.3  271.25  4828.8  270.06  4953.6  270.17  4963.2  270.04  4987.9  267.92
  4991.7   263.5  4995.3  263.31  4998.1  262.81  5001.3  263.31  5012.6  268.67
  5020.2  270.37    5041  271.24  5048.6   270.5  5114.6  274.26    5199  278.19
  5271.7  281.88  5409.8  287.61  5428.8  290.11  5445.4  289.57  5516.1   292.6
#Mann= 10 ,-1 , 0
  4130.2     .05       0  4158.5     .16       0  4280.1     .05       0
  4953.6     .16       0  4995.3     .07       0  5001.3     .16       0
  5114.6     .05       0    5199     .16       0  5271.7      .1       0
  5428.8     .05       0
Bank Sta=4963.2,5020.2
XS Rating Curve= 0 ,0
Exp/Cntr=0.3,0.1

Type RM Length L Ch R = 1 ,17577   ,573,573,573
BEGIN DESCRIPTION:
UNT010 IN BECR 28.0
END DESCRIPTION:
XS GIS Cut Line= 3
      3711949.63     10536460.17      3712349.61     10536060.19
      3712599.63     10535660.15
#Sta/Elev= 30
  4470.5  283.81  4577.3  276.74  4640.2  275.49  4682.6  273.22  4838.2   269.9
  4894.7  270.15  4967.8  268.07  4979.6  267.77  4993.7  264.35    5022  266.53
  5043.8  266.79  5046.7  264.21  5049.5  263.71  5052.7  264.21  5059.2  266.53
  5071.5  268.79  5122.8  268.52  5159.4  267.09  5217.2  267.69  5224.8   265.6
  5238.4  265.97  5247.8  268.01  5283.8  270.54  5290.3   272.3  5340.9   277.1
  5363.4  279.66  5440.8  284.05  5457.2  284.87    5479   286.8  5507.9  286.44
#Mann= 8 ,-1 , 0
  4470.5     .16       0  4577.3     .05       0  4967.8      .1       0
  5046.7     .07       0  5052.7      .1       0  5340.9     .16       0
  5440.8      .1       0  5457.2     .05       0
Bank Sta=5043.8,5071.5
XS Rating Curve= 0 ,0
Exp/Cntr=0.3,0.1

Type RM Length L Ch R = 1 ,17004   ,475,475,475
BEGIN DESCRIPTION:
UNT010 IN BECR 27.0
END DESCRIPTION:
XS GIS Cut Line= 3
      3712349.61     10536960.18      3712799.61     10536160.19
      3712749.61     10535760.17
#Sta/Elev= 30
  4072.1  303.61  4269.4  291.47    4336  285.82    4372  283.92  4416.3  278.08
  4452.9  276.98  4462.2  275.08  4484.8  273.94  4652.5  269.87    4917  267.49
  4954.6  266.41  4969.1  263.88  4973.3  262.46    4976  261.96  4979.3  262.46
    4982  266.38  4987.1  262.77    5000  262.79  5027.8  266.93  5151.2  265.45
  5161.3  265.08  5171.4   263.2  5181.4  264.04    5189   266.5  5221.8  268.01
  5234.6  269.63  5262.1  271.99  5292.3  276.81  5342.7  279.25  5393.1  283.53
#Mann= 5 ,-1 , 0
  4072.1     .05       0  4969.1      .1       0  4973.3     .07       0
  4979.3      .1       0  5234.6     .05       0
Bank Sta=4917,4982
XS Rating Curve= 0 ,0
Exp/Cntr=0.3,0.1

Type RM Length L Ch R = 1 ,16529   ,589,589,589
BEGIN DESCRIPTION:
UNT010 IN BECR 26.0
END DESCRIPTION:
XS GIS Cut Line= 3
      3713149.61     10536760.24      3713149.61     10535960.19
      3713149.61     10535760.24
#Sta/Elev= 30
  4215.7  284.99  4305.7  280.67  4325.7  278.63  4370.5  275.83  4422.9  272.85
  4445.7  272.88  4475.7  270.75  4505.7  269.73  4645.7  267.14  4655.7  266.39
  4695.7  265.27  4749.8  264.73  4795.7  265.64  4815.7  264.74  4845.7  265.81
  4945.7  264.51  4965.7  264.75  4975.7  264.23  4985.7  262.05  4992.7  259.69
  4995.5  259.19  4998.7  259.69  5005.7   260.2  5013.2  262.09  5025.7  262.47
  5035.7  265.31  5075.7  267.88  5125.7  269.99  5175.7  274.36  5215.7  276.99
#Mann= 7 ,-1 , 0
  4215.7     .05       0  4370.5     .16       0  4422.9     .05       0
  4749.8      .1       0  4945.7     .05       0  4992.7     .03       0
  4998.7     .05       0
Bank Sta=4965.7,5035.7
XS Rating Curve= 0 ,0
Exp/Cntr=0.3,0.1

Type RM Length L Ch R = 1 ,15940   ,365,365,365
BEGIN DESCRIPTION:
UNT010 IN BECR 25.0
END DESCRIPTION:
XS GIS Cut Line= 3
      3713147.66     10536962.81      3713599.05     10536294.41
      3713946.07     10535114.53
#Sta/Elev= 30
  4121.2  298.44  4224.9  293.26  4311.9  286.18  4448.1  278.05  4638.1  269.84
  4780.6  264.95  4881.3  262.84  4887.3  260.43  4896.3  262.43  4917.3  260.02
  4927.3  263.82  4947.6  263.86  4973.8  262.64  4979.9   259.6  4986.2  260.02
  4991.7   257.6  4994.4   257.1  4997.7   257.6  5014.3  260.37  5019.5  259.98
    5026  262.39  5046.8  263.33    5224  263.65  5517.8   269.2  5682.6  274.33
  5800.3  280.26  5900.3  283.37  5984.9   289.2  6049.4  292.05  6157.6  293.61
#Mann= 7 ,-1 , 0
  4121.2     .05       0  4448.1     .16       0  4638.1     .05       0
  4780.6     .16       0  4979.9     .05       0  4991.7     .03       0
  4997.7     .05       0
Bank Sta=4947.6,5046.8
XS Rating Curve= 0 ,0
Exp/Cntr=0.3,0.1

Type RM Length L Ch R = 1 ,15575   ,478,478,478
BEGIN DESCRIPTION:
UNT010 IN BECR 24.0
END DESCRIPTION:
XS GIS Cut Line= 3
       3713199.6      10537010.2      3713949.61     10536360.19
      3714749.64     10535560.16
#Sta/Elev= 30
  4004.5  299.07  4132.3  291.31    4203  284.59  4350.6  276.11  4420.4  273.95
  4479.9  272.22  4486.5     271  4535.9   270.9    4572  268.85  4656.5  267.15
  4770.5  266.38  4904.4  261.72    4969  262.68  4983.2  260.63  4990.7  255.44
  4993.4  254.94  4996.7  255.44  5025.3  261.88  5081.8  261.49  5138.4  259.19
  5180.8  260.66    5195  259.07  5209.1   261.1  5279.8  261.37  5435.4  267.88
    5591  269.54  5661.7  271.94  5887.9  282.39  6015.2  293.48  6128.4  300.29
#Mann= 5 ,-1 , 0
  4004.5     .05       0  4350.6     .16       0  4420.4     .05       0
  4990.7     .03       0  4996.7     .05       0
Bank Sta=4969,5025.3
XS Rating Curve= 0 ,0
Exp/Cntr=0.3,0.1

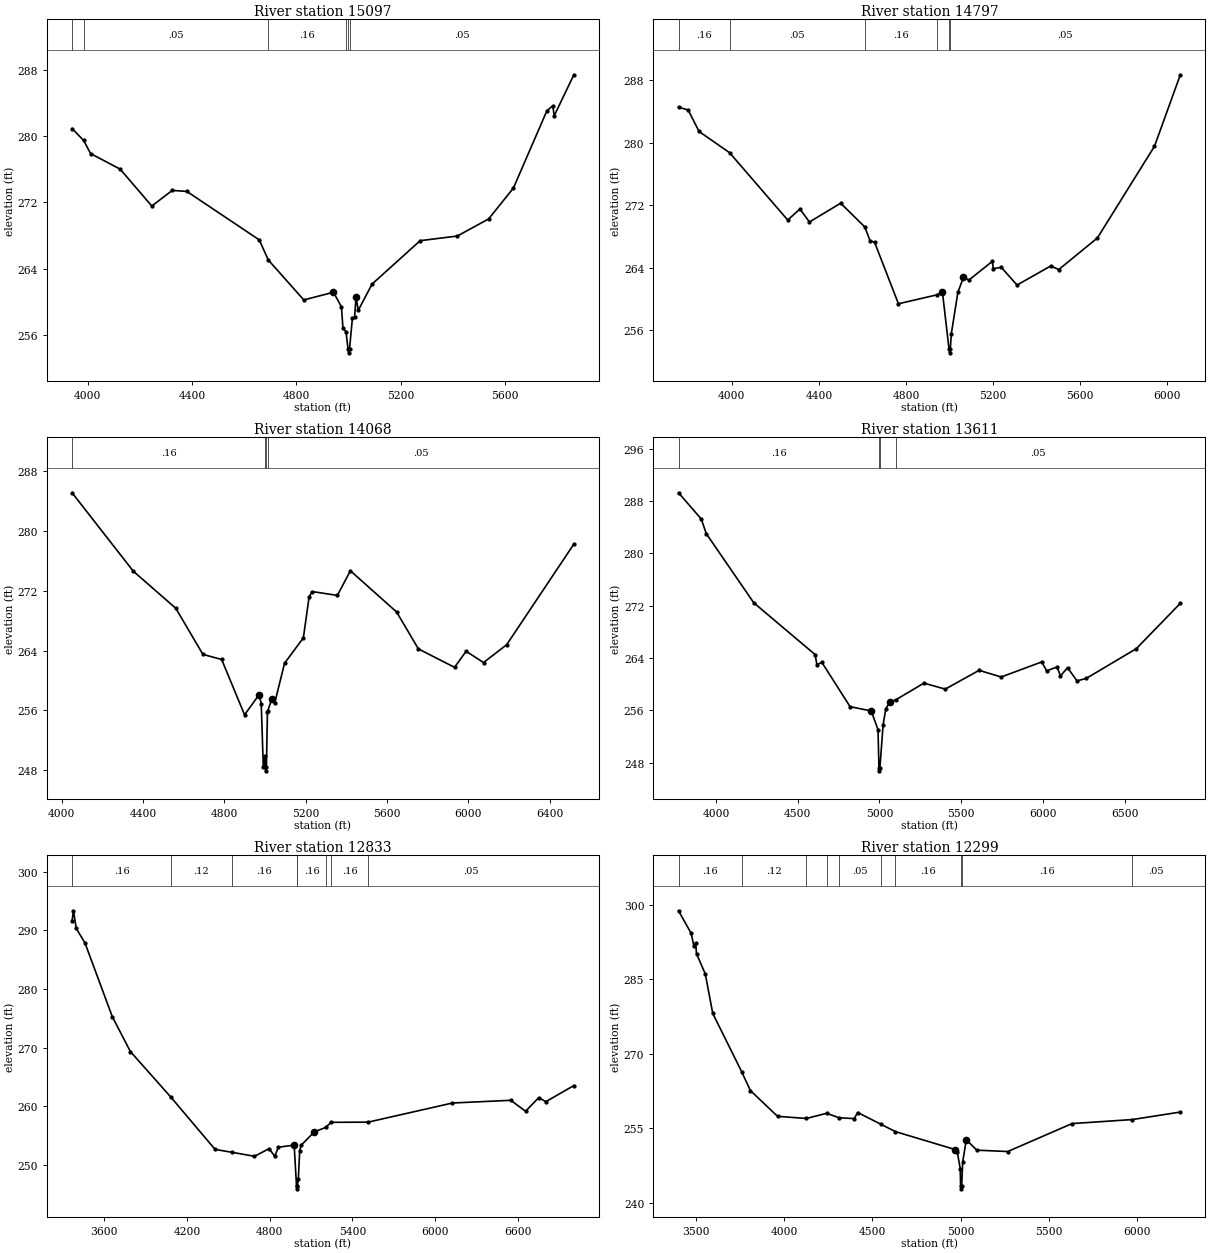
Type RM Length L Ch R = 1 ,15097   ,300,300,300
BEGIN DESCRIPTION:
UNT010 IN BECR 23.0
END DESCRIPTION:
XS GIS Cut Line= 3
      3713549.58     10537210.21      3714349.61     10536560.19
      3714749.59     10535760.22
#Sta/Elev= 30
  3939.6  280.95    3984   279.5  4010.7  277.92  4124.2  276.03  4245.6  271.57
  4323.9  273.46  4379.9  273.34    4658  267.47  4692.3  265.05  4828.7  260.21
  4942.4  261.14  4973.2  259.38  4978.8  256.81  4990.6  256.36  4998.2  254.31
  5000.9  253.81  5004.2  254.31  5015.1  257.99  5023.5  258.09  5029.1  260.58
  5037.5  258.95  5090.6  262.13  5275.1  267.38  5417.6  267.94  5537.8  270.01
  5632.8  273.74  5761.4   283.1  5783.8   283.7  5789.4  282.49  5864.8  287.45
#Mann= 6 ,-1 , 0
  3939.6     .16       0    3984     .05       0  4692.3     .16       0
  4990.6     .05       0  4998.2     .03       0  5004.2     .05       0
Bank Sta=4942.4,5029.1
XS Rating Curve= 0 ,0
Exp/Cntr=0.3,0.1

Type RM Length L Ch R = 1 ,14797   ,729,729,729
BEGIN DESCRIPTION:
UNT010 IN BECR 22.0
END DESCRIPTION:
XS GIS Cut Line= 4
      3713486.18     10537379.49      3714250.09     10536797.88
      3714762.24     10536719.76      3715283.09     10536077.38
#Sta/Elev= 30
  3755.5  284.52  3799.7  284.16  3849.6  281.42  3990.1   278.7  4257.1   270.1
  4313.2  271.51  4356.9  269.85  4500.3  272.25  4611.1  269.22  4635.4  267.45
  4656.2  267.25  4765.7   259.4    4944  260.55    4968  260.85  4998.1  253.63
  5000.8  253.13  5004.1  253.63  5008.5  255.54  5038.8  260.87  5064.6  262.78
  5089.4  262.43  5196.7  264.81  5201.7  263.89  5238.5  264.05  5310.4  261.79
  5465.5  264.23  5502.2  263.77  5679.7  267.81  5941.9  279.52  6060.7  288.66
#Mann= 6 ,-1 , 0
  3755.5     .16       0  3990.1     .05       0  4611.1     .16       0
    4944     .05       0  4998.1     .03       0  5004.1     .05       0
Bank Sta=4968,5064.6
XS Rating Curve= 0 ,0
Exp/Cntr=0.3,0.1

Type RM Length L Ch R = 1 ,14068   ,457,457,457
BEGIN DESCRIPTION:
UNT010 IN BECR 20.0
END DESCRIPTION:
XS GIS Cut Line= 3
       3713451.5     10537570.45      3714666.76     10537301.35
      3715430.64      10536346.5
#Sta/Elev= 30
  4051.6  285.11  4352.6  274.63  4561.8  269.66  4694.9   263.5  4787.1  262.82
  4899.8  255.42  4971.5  258.12  4981.7  256.93    4992  248.48  4999.1  249.94
  5001.2  248.43  5003.9  247.93  5007.2  248.43  5012.4  255.85  5013.7  255.93
  5032.9  257.48  5047.8  256.97  5096.5  262.32  5188.9  265.71  5217.3  271.19
  5232.5   271.9  5356.2  271.39  5420.2  274.68  5647.5  269.17  5754.7  264.23
  5932.4  261.77  5989.3  263.92  6074.9  262.41  6188.6  264.79  6519.1  278.25
#Mann= 4 ,-1 , 0
  4051.6     .16       0  5001.2     .07       0  5007.2     .16       0
  5013.7     .05       0
Bank Sta=4971.5,5032.9
XS Rating Curve= 0 ,0
Exp/Cntr=0.3,0.1

Type RM Length L Ch R = 1 ,13611   ,778,778,778
BEGIN DESCRIPTION:
UNT010 IN BECR 19.0
END DESCRIPTION:
XS GIS Cut Line= 4
       3713191.1     10537943.72      3713651.13      10537995.8
      3714718.84     10537691.98      3715638.95     10536511.46
#Sta/Elev= 30
  3770.7  289.26  3910.1  285.24  3940.3  283.02    4231  272.45  4606.4  264.53
  4616.8  263.01    4648  263.33    4820  256.58  4949.5  255.92  4991.1  253.06
  4996.7  247.27  4999.5  246.77  5002.7  247.27  5022.3  253.81  5038.8  256.28
  5063.8  257.26  5102.2  257.66  5271.8  260.17  5402.5  259.26  5609.7  262.13
  5744.5  261.11  5993.3  263.42  6022.2  262.05  6086.4  262.64  6107.3  261.27
  6150.7  262.54  6208.2  260.52  6264.7  260.89  6571.3  265.44  6840.5  272.37
#Mann= 4 ,-1 , 0
  3770.7     .16       0  4996.7     .07       0  5002.7     .16       0
  5102.2     .05       0
Bank Sta=4949.5,5063.8
XS Rating Curve= 0 ,0
Exp/Cntr=0.3,0.1

Type RM Length L Ch R = 1 ,12833   ,534,534,534
BEGIN DESCRIPTION:
UNT010 IN BECR 18.0
END DESCRIPTION:
XS GIS Cut Line= 3
      3713069.49     10538264.89      3714814.32     10538464.55
      3715799.62     10536860.17
#Sta/Elev= 30
  3367.5  291.67  3377.7  293.36  3397.8  290.34  3460.7  287.89  3659.5  275.26
  3790.4  269.32  4085.2   261.5  4404.3  252.61  4524.5  252.12  4690.4  251.43
  4796.9  252.74  4837.1  251.43  4863.9  252.98  4978.1  253.34  4995.2  246.37
  4997.9  245.87  5001.2  246.37  5008.3   247.5  5018.3  252.41  5028.4   253.3
  5123.7  255.59  5208.2  256.37  5244.6  257.23  5514.3  257.26  6126.3  260.53
  6548.8  260.99  6656.6  259.12  6751.3  261.44  6803.5  260.76  7006.5  263.51
#Mann= 8 ,-1 , 0
  3367.5     .16       0  4085.2     .12       0  4524.5     .16       0
  4995.2     .07       0  5001.2     .16       0  5208.2     .12       0
  5244.6     .16       0  5514.3     .05       0
Bank Sta=4978.1,5123.7
XS Rating Curve= 0 ,0
Exp/Cntr=0.3,0.1

Type RM Length L Ch R = 1 ,12299   ,688,688,688
BEGIN DESCRIPTION:
UNT010 IN BECR 17.0
END DESCRIPTION:
XS GIS Cut Line= 4
      3713147.68     10538690.25       3714154.6     10539063.51
      3714935.85     10538898.58      3715317.64     10538004.85
#Sta/Elev= 30
  3401.2  298.76  3472.8  294.22  3488.6  291.61  3497.8  292.34  3503.1  290.11
  3552.6  286.09  3595.2   278.1  3759.3  266.36  3808.5  262.58  3962.6   257.4
  4126.2  256.97  4240.5  258.01  4310.3  257.12    4397  256.94  4416.4  258.17
  4550.8  255.76    4630  254.33  4970.8   250.7    4981  250.26  4997.9  246.86
    5000  243.31  5002.8  242.81    5006  243.31  5011.7  248.17  5032.1  252.68
  5092.3  250.59  5267.2  250.32  5631.4  255.94  5972.9  256.75  6245.4  258.26
#Mann= 10 ,-1 , 0
  3401.2     .16       0  3759.3     .12       0  4126.2     .05       0
  4240.5     .16       0  4310.3     .05       0  4550.8      .1       0
    4630     .16       0    5000     .07       0    5006     .16       0
  5972.9     .05       0
Bank Sta=4970.8,5032.1
XS Rating Curve= 0 ,0
Exp/Cntr=0.3,0.1

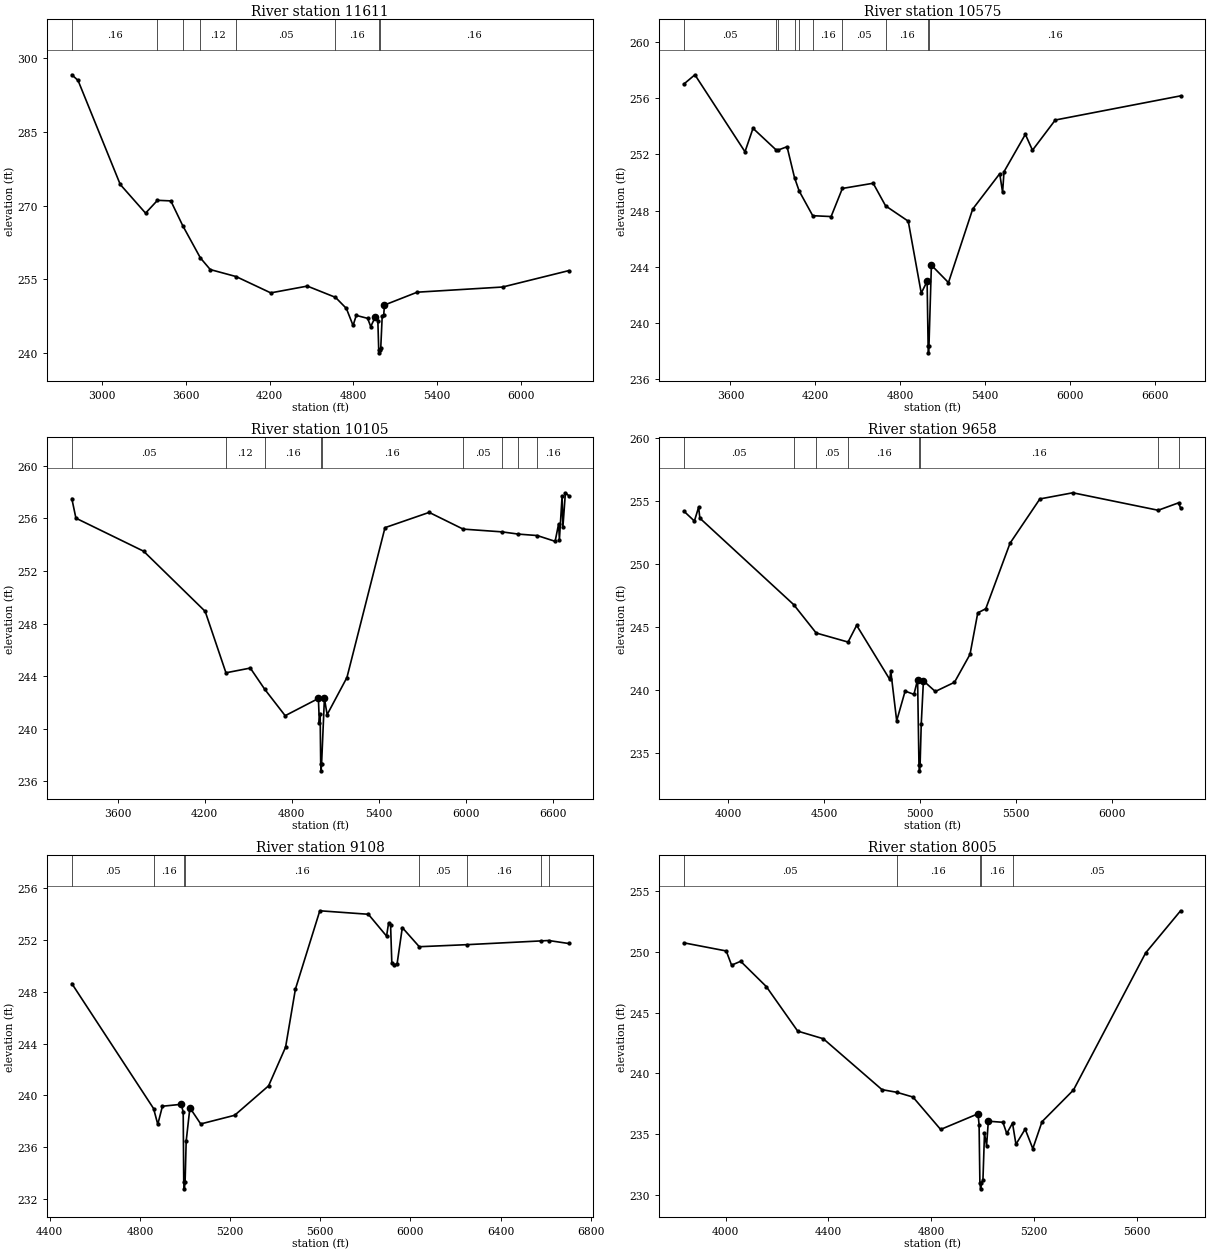
Type RM Length L Ch R = 1 ,11611   ,1036,1036,1036
BEGIN DESCRIPTION:
Mapping XS e7dcb8ae
END DESCRIPTION:
XS GIS Cut Line= 4
      3712505.26     10539402.04      3714354.26      10539645.1
      3714953.21     10539462.81      3715204.78     10538421.87
#Sta/Elev= 30
  2782.4  296.58  2827.1  295.43  3129.7  274.28  3311.3  268.45  3396.8  271.06
  3492.4  270.94  3577.7  265.91  3704.3  259.35  3775.2  256.98  3960.1  255.56
  4208.9  252.24  4471.2  253.62  4673.2  251.33  4751.1  249.08  4799.2  245.61
  4822.1  247.66  4903.8  247.06  4925.8  245.38  4958.7  247.35  4976.9  246.61
  4983.3  240.55  4986.1  240.05  4989.3  240.55  4997.8  241.06  5008.3   247.6
  5018.8  247.68  5024.4  249.77  5259.2  252.38  5871.5  253.43  6344.3  256.75
#Mann= 8 ,-1 , 0
  2782.4     .16       0  3396.8     .05       0  3577.7     .16       0
  3704.3     .12       0  3960.1     .05       0  4673.2     .16       0
  4983.3     .07       0  4989.3     .16       0
Bank Sta=4958.7,5024.4
XS Rating Curve= 0 ,0
Exp/Cntr=0.3,0.1

Type RM Length L Ch R = 1 ,10575   ,470,470,470
BEGIN DESCRIPTION:
UNT010 IN BECR 16.0
END DESCRIPTION:
XS GIS Cut Line= 3
      3713899.58     10541560.22      3715049.61     10540310.19
       3715249.6     10538510.24
#Sta/Elev= 30
  3270.5  257.01  3348.5  257.67  3702.4  252.19  3759.1  253.86  3923.6  252.31
  3933.2   252.3  3999.6  252.55  4052.3  250.35  4085.6  249.39    4181  247.64
  4310.9  247.58  4390.5  249.58  4608.1  249.95  4695.9  248.34  4855.9  247.25
  4947.8  242.13  4989.2  242.97  4996.3  238.38    4999  237.88  5002.3  238.38
  5019.4  244.12  5140.1  242.88  5311.2  248.11  5502.3  250.63  5522.5   249.3
  5532.5  250.77  5683.4  253.43  5733.7   252.3  5894.7  254.45  6780.1  256.17
#Mann= 10 ,-1 , 0
  3270.5     .05       0  3923.6      .1       0  3933.2     .16       0
  4052.3     .12       0  4085.6     .05       0    4181     .16       0
  4390.5     .05       0  4695.9     .16       0  4996.3     .07       0
  5002.3     .16       0
Bank Sta=4989.2,5019.4
XS Rating Curve= 0 ,0
Exp/Cntr=0.3,0.1

Type RM Length L Ch R = 1 ,10105   ,447,447,447
BEGIN DESCRIPTION:
UNT010 IN BECR 15.0
END DESCRIPTION:
XS GIS Cut Line= 3
       3714249.6     10541660.19      3715449.61     10540460.19
      3716099.63     10538860.15
#Sta/Elev= 30
    3285   257.5  3313.3  256.01    3780   253.5  4204.2  248.93  4347.5  244.26
  4515.4  244.62  4614.7  243.01  4755.8     241  4984.8  242.31  4991.4  240.47
  4996.8  241.13  5000.7  237.31  5003.4  236.81  5006.7  237.31  5026.3  242.32
    5045  241.08  5181.5   243.9  5443.9  255.29  5748.4  256.45  5982.3  255.18
  6250.1  254.97  6363.3   254.8  6493.5  254.69  6616.7  254.25  6640.8  255.58
  6646.2  254.38  6664.8  257.71  6670.2  255.32  6687.5  257.94  6709.1  257.73
#Mann= 9 ,-1 , 0
    3285     .05       0  4347.5     .12       0  4614.7     .16       0
  5000.7     .07       0  5006.7     .16       0  5982.3     .05       0
  6250.1     .16       0  6363.3     .05       0  6493.5     .16       0
Bank Sta=4984.8,5026.3
XS Rating Curve= 0 ,0
Exp/Cntr=0.3,0.1

Type RM Length L Ch R = 1 ,9658    ,550,550,550
BEGIN DESCRIPTION:
UNT010 IN BECR 14.0
END DESCRIPTION:
XS GIS Cut Line= 4
      3715249.61     10541860.18      3715749.61     10540760.19
      3715849.61     10540110.19      3715953.08     10539394.27
#Sta/Elev= 30
  3768.6  254.22  3823.5  253.43  3845.5  254.53  3852.1  253.66  4340.9  246.79
  4458.4  244.53  4624.5  243.81  4669.3  245.14  4841.8  240.84  4847.3  241.49
    4878  237.55    4922  239.91  4968.1  239.65    4987  240.83  4994.1  234.07
  4996.9  233.57  5000.1  234.07    5006  237.28  5017.4  240.73  5079.3  239.88
  5179.2  240.61  5260.2  242.83  5300.7  246.13  5342.4  246.46  5468.9  251.67
  5624.4  255.19  5796.2  255.68  6241.1  254.29  6347.3  254.88  6357.9  254.47
#Mann= 8 ,-1 , 0
  3768.6     .05       0  4340.9     .16       0  4458.4     .05       0
  4624.5     .16       0  4994.1     .07       0  5000.1     .16       0
  6241.1     .05       0  6347.3     .16       0
Bank Sta=4987,5017.4
XS Rating Curve= 0 ,0
Exp/Cntr=0.3,0.1

Type RM Length L Ch R = 1 ,9108    ,1103,1103,1103
BEGIN DESCRIPTION:
UNT010 IN BECR 13.0
END DESCRIPTION:
XS GIS Cut Line= 4
      3716249.61     10541260.21      3716140.71     10540820.45
      3715899.61     10540210.19      3716343.83      10539211.1
#Sta/Elev= 30
  4498.2  248.64  4860.8  238.97  4879.4  237.75    4900  239.15  4983.8   239.3
  4992.1  238.68  4994.5  233.26  4997.2  232.76  5000.5  233.26  5005.3  236.44
  5021.8  239.03  5069.8  237.78  5220.3  238.45  5370.8  240.73  5446.1  243.72
  5489.7  248.21  5597.9  254.27  5813.2     254  5893.9  252.31  5902.9  253.32
  5911.7  253.19  5917.2  250.23  5924.8   250.1  5940.4  250.14  5963.7  252.97
  6038.9  251.49  6252.2  251.65  6579.6  251.94  6612.6  251.97  6700.8  251.74
#Mann= 8 ,-1 , 0
  4498.2     .05       0  4860.8     .16       0  4994.5     .07       0
  5000.5     .16       0  6038.9     .05       0  6252.2     .16       0
  6579.6     .05       0  6612.6     .16       0
Bank Sta=4983.8,5021.8
XS Rating Curve= 0 ,0
Exp/Cntr=0.3,0.1

Type RM Length L Ch R = 1 ,8005    ,493,493,493
BEGIN DESCRIPTION:
UNT010 IN BECR 12.0
END DESCRIPTION:
XS GIS Cut Line= 3
      3716199.59     10541410.22      3716899.61     10540510.19
      3717549.63     10540060.18
#Sta/Elev= 30
  3838.1  250.74  4002.8  250.07  4023.6   248.9  4058.9  249.22  4158.5  247.14
  4280.6  243.47  4380.2  242.84  4608.2  238.65  4666.1  238.43  4728.6  238.04
  4836.2  235.37  4981.3  236.66  4985.7  235.77  4988.8  230.98  4991.6  230.48
  4994.8  230.98  5000.6  231.17  5006.7  235.05  5014.8  234.03  5021.6  236.05
  5078.3  235.96  5093.2  235.04  5115.6  235.89    5129  234.15  5164.8   235.4
  5194.5  233.79  5230.3  236.01  5352.6  238.62  5633.1  249.91  5768.9  253.38
#Mann= 5 ,-1 , 0
  3838.1     .05       0  4666.1     .16       0  4988.8     .07       0
  4994.8     .16       0  5115.6     .05       0
Bank Sta=4981.3,5021.6
XS Rating Curve= 0 ,0
Exp/Cntr=0.3,0.1

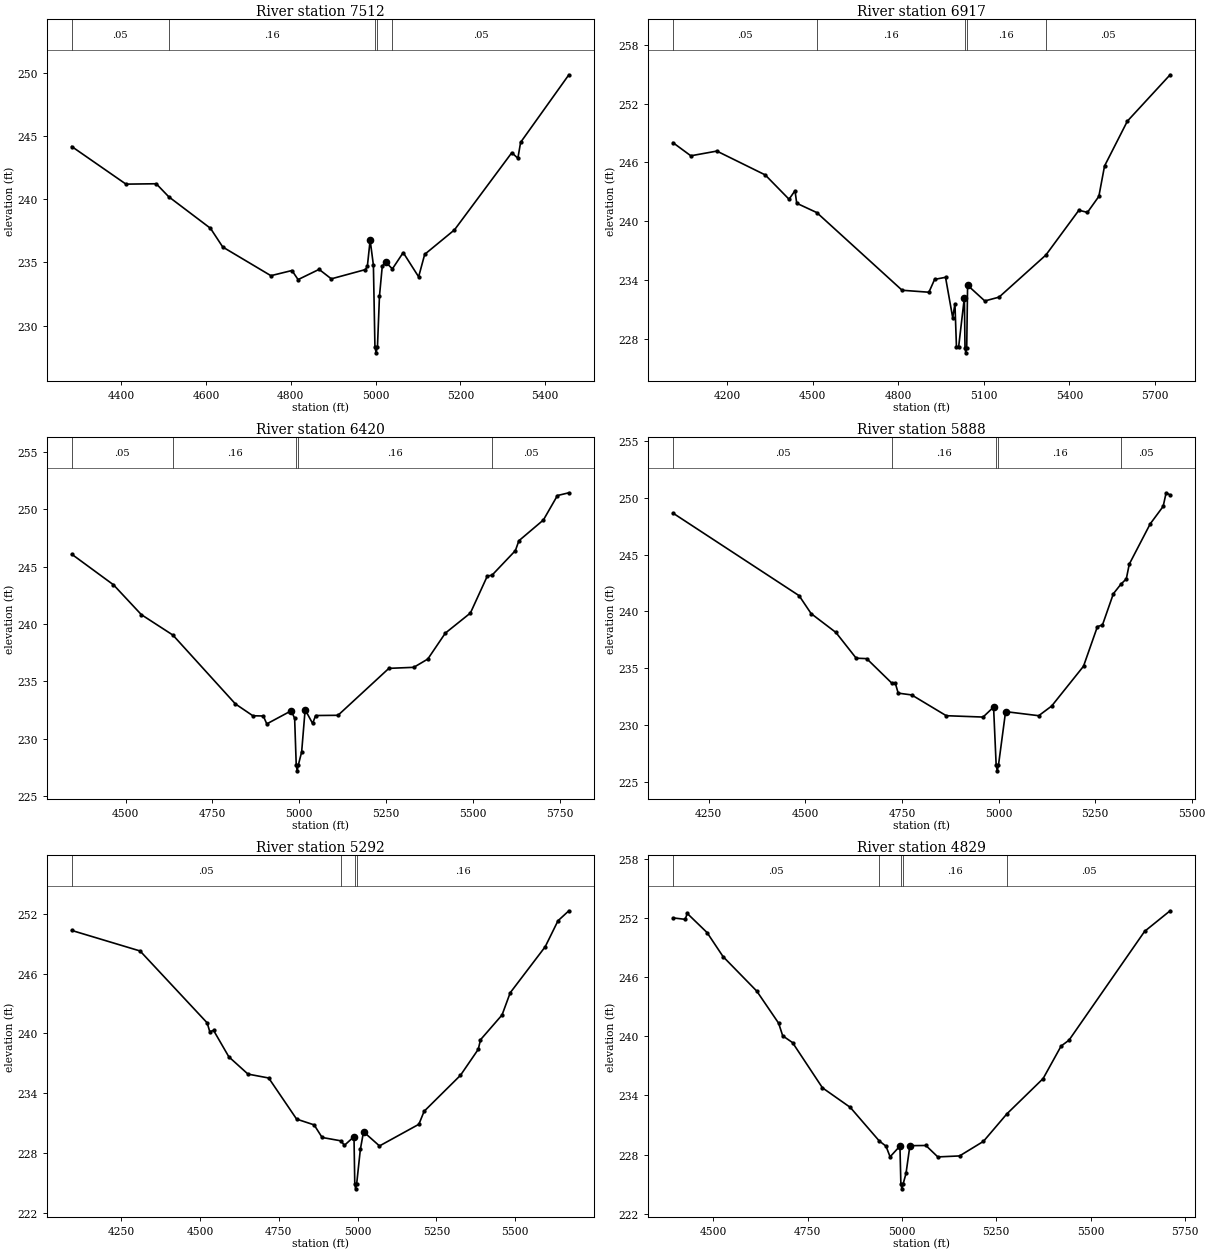
Type RM Length L Ch R = 1 ,7512    ,595,595,595
BEGIN DESCRIPTION:
UNT010 IN BECR 11.0
END DESCRIPTION:
XS GIS Cut Line= 3
      3716699.59      10541060.2      3717238.23     10540630.06
      3717549.61     10540260.19
#Sta/Elev= 30
  4283.2  244.18  4411.2   241.2  4482.6  241.23  4512.1   240.2  4610.6   237.7
  4639.5  236.22  4753.1  233.95  4802.8  234.36  4817.2  233.64  4866.8  234.45
  4895.6   233.7  4975.7  234.43  4980.6  234.68  4987.2  236.77  4994.9  234.78
  4998.5  228.34  5001.2  227.84  5004.5  228.34  5009.2  232.33  5015.8   234.7
  5023.5  235.03  5039.7  234.49  5065.2  235.78  5101.6  233.86  5115.9  235.64
  5186.2  237.58  5321.4  243.69  5335.7  243.25  5342.2  244.51    5456  249.86
#Mann= 5 ,-1 , 0
  4283.2     .05       0  4512.1     .16       0  4998.5     .07       0
  5004.5     .16       0  5039.7     .05       0
Bank Sta=4987.2,5023.5
XS Rating Curve= 0 ,0
Exp/Cntr=0.3,0.1

Type RM Length L Ch R = 1 ,6917    ,497,497,497
BEGIN DESCRIPTION:
UNT010 IN BECR 10.0
END DESCRIPTION:
XS GIS Cut Line= 3
       3716449.6     10541210.19      3717449.61     10540910.19
      3718149.56     10540910.19
#Sta/Elev= 30
  4009.3  248.01    4072  246.67  4163.3  247.15    4333  244.72  4416.5  242.24
  4437.4  243.11  4443.5  241.83  4513.9  240.88  4813.2  232.96  4907.2  232.76
  4927.2  234.07  4965.5  234.28  4990.7  230.16  4998.5  231.59  5003.8  227.21
  5011.6  227.22  5031.6  232.22  5033.8  227.08  5036.6  226.58  5039.8  227.08
  5042.9  233.47  5103.3  231.87  5153.3  232.26  5317.5  236.55  5433.3  241.12
  5463.3   240.9  5503.3  242.53  5523.3  245.63  5603.3   250.2  5753.3  254.93
#Mann= 5 ,-1 , 0
  4009.3     .05       0  4513.9     .16       0  5033.8     .07       0
  5039.8     .16       0  5317.5     .05       0
Bank Sta=5031.6,5042.9
XS Rating Curve= 0 ,0
Exp/Cntr=0.3,0.1

Type RM Length L Ch R = 1 ,6420    ,532,532,532
BEGIN DESCRIPTION:
UNT010 IN BECR 9.0
END DESCRIPTION:
XS GIS Cut Line= 3
      3716749.66     10541260.19      3717399.61     10541310.19
      3718172.22     10541207.32
#Sta/Elev= 30
  4344.9  246.08  4465.2  243.41  4545.4  240.81  4636.2  239.03  4816.2  233.03
  4866.4     232  4896.5  231.98  4906.5  231.29  4976.7  232.43  4986.7  231.78
  4991.3   227.7    4994   227.2  4997.3   227.7  5006.9  228.85  5016.9  232.53
  5038.4  231.33  5047.2  232.02  5111.6  232.04    5258  236.13  5329.7  236.22
    5370  236.94  5420.5   239.2  5492.7  240.95  5541.5  244.18  5554.7  244.24
  5622.2  246.39  5632.3  247.25  5702.9  249.06  5743.3  251.19  5776.2  251.43
#Mann= 5 ,-1 , 0
  4344.9     .05       0  4636.2     .16       0  4991.3     .07       0
  4997.3     .16       0  5554.7     .05       0
Bank Sta=4976.7,5016.9
XS Rating Curve= 0 ,0
Exp/Cntr=0.3,0.1

Type RM Length L Ch R = 1 ,5888    ,596,596,596
BEGIN DESCRIPTION:
UNT010 IN BECR 8.0
END DESCRIPTION:
XS GIS Cut Line= 3
      3716649.57     10541260.16      3717399.61     10541710.19
      3717799.61     10541810.19
#Sta/Elev= 30
  4157.2  248.67  4483.8  241.39  4514.9  239.81    4579  238.15  4631.5  235.88
  4658.7  235.84  4723.8  233.68  4732.6   233.7  4740.3   232.8  4775.3  232.64
  4864.7  230.81    4960  230.69  4987.2  231.57  4993.9  226.45  4996.7  225.95
  4999.9  226.45  5018.3  231.17    5104  230.81  5137.5  231.66    5220  235.17
  5256.1  238.67    5269   238.8  5297.3  241.56  5316.8   242.4  5330.8  242.87
  5338.5  244.17  5392.7  247.72  5426.2  249.26  5433.9  250.46  5444.2  250.27
#Mann= 5 ,-1 , 0
  4157.2     .05       0  4723.8     .16       0  4993.9     .07       0
  4999.9     .16       0  5316.8     .05       0
Bank Sta=4987.2,5018.3
XS Rating Curve= 0 ,0
Exp/Cntr=0.3,0.1

Type RM Length L Ch R = 1 ,5292    ,463,463,463
BEGIN DESCRIPTION:
Mapping XS 0873818f
END DESCRIPTION:
XS GIS Cut Line= 3
      3716275.58     10542188.21      3716896.21     10542084.05
      3717833.72     10542227.28
#Sta/Elev= 30
  4092.7  250.32  4309.7  248.26  4522.7  241.05  4530.8  240.17  4542.9   240.3
  4591.4  237.65  4652.1  235.92  4717.8  235.53  4806.4  231.41    4862  230.83
  4887.3  229.57  4947.2  229.23  4958.1  228.78  4988.5  229.65    4991  224.92
  4993.7  224.42    4997  224.92  5008.7  228.38  5018.8  230.14  5069.4  228.72
  5194.4  230.89    5211  232.19  5326.4   235.8    5383  238.41  5389.9  239.36
  5458.4  241.85  5484.2  244.07  5595.4  248.69  5635.9  251.29  5670.4  252.29
#Mann= 4 ,-1 , 0
  4092.7     .05       0  4947.2     .16       0    4991     .07       0
    4997     .16       0
Bank Sta=4988.5,5018.8
XS Rating Curve= 0 ,0
Exp/Cntr=0.3,0.1

Type RM Length L Ch R = 1 ,4829    ,335,335,335
BEGIN DESCRIPTION:
UNT010 IN BECR 7.0
END DESCRIPTION:
XS GIS Cut Line= 2
      3716353.64     10542275.01      3717603.72     10542691.71
#Sta/Elev= 30
  4393.1  252.02  4425.5  251.87    4431  252.47  4483.5  250.53  4525.9  248.09
  4615.2  244.59  4673.2  241.33    4684  240.05  4710.1  239.36  4789.4  234.77
    4863  232.79  4939.9  229.38  4957.8  228.85  4968.6  227.77  4994.7  228.86
  4997.2  225.02    5000  224.52  5003.2  225.02  5010.8  226.08  5021.1   228.9
  5063.5  228.92  5095.1  227.76  5152.8  227.86  5216.1  229.34  5278.2  232.13
  5374.2  235.71  5421.9  239.01  5442.9  239.61  5643.2  250.65  5710.8  252.74
#Mann= 5 ,-1 , 0
  4393.1     .05       0  4939.9     .16       0  4997.2     .07       0
  5003.2     .16       0  5278.2     .05       0
Bank Sta=4994.7,5021.1
XS Rating Curve= 0 ,0
Exp/Cntr=0.3,0.1

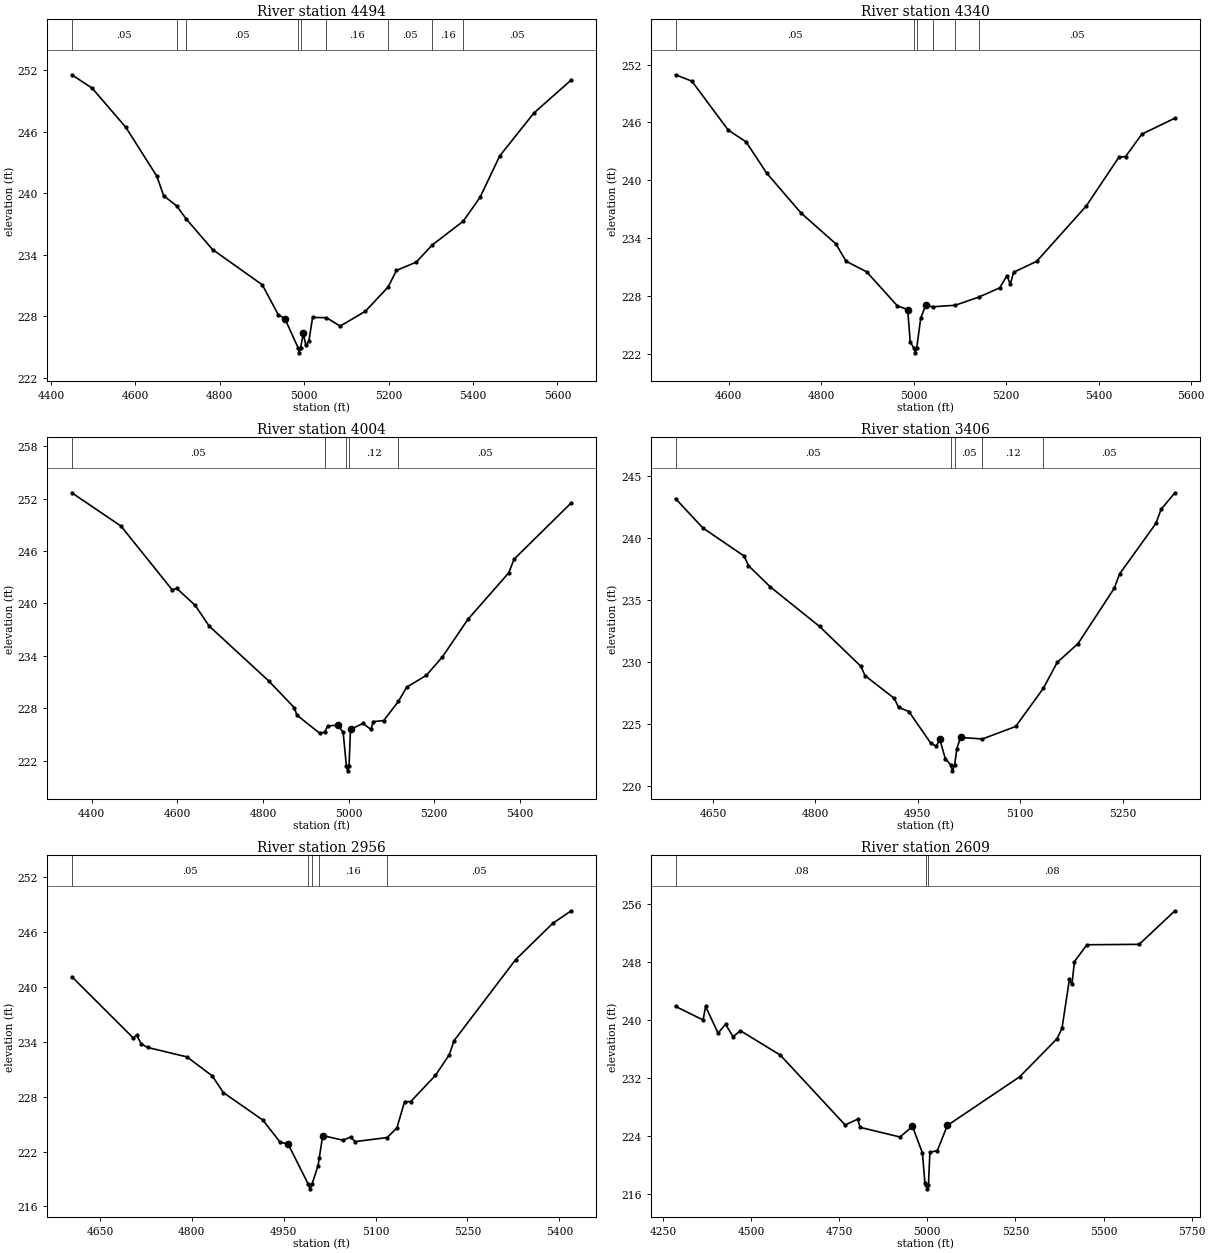
Type RM Length L Ch R = 1 ,4494    ,154,154,154
BEGIN DESCRIPTION:
UNT010 IN BECR 6.0
END DESCRIPTION:
XS GIS Cut Line= 3
      3716327.61     10542418.24      3716956.98     10542765.48
      3717382.33     10542952.11
#Sta/Elev= 30
  4449.2  251.58  4497.2  250.28  4577.1  246.46  4650.6  241.69  4666.7  239.79
  4697.5  238.79  4720.9  237.48  4782.7  234.53  4900.5  231.09  4938.3  228.18
    4954  227.79  4985.3  224.95    4988  224.45  4991.3  224.95  4997.9  226.34
  5003.6  225.18  5011.1  225.65  5019.7   227.9  5052.6  227.88    5085  227.06
  5144.6   228.5  5198.5  230.86  5218.5  232.49  5265.3   233.3  5302.5  234.95
  5376.6  237.29  5416.4  239.62  5463.1  243.66  5544.1  247.85  5632.5  251.07
#Mann= 9 ,-1 , 0
  4449.2     .05       0  4697.5     .08       0  4720.9     .05       0
  4985.3     .04       0  4991.3     .05       0  5052.6     .16       0
  5198.5     .05       0  5302.5     .16       0  5376.6     .05       0
Bank Sta=4954,4997.9
XS Rating Curve= 0 ,0
Exp/Cntr=0.3,0.1

Type RM Length L Ch R = 1 ,4340    ,336,336,336
BEGIN DESCRIPTION:
UNT010 IN BECR 5.0
END DESCRIPTION:
XS GIS Cut Line= 3
      3716258.22     10542565.84      3716883.19       10542887.
      3717178.29     10543121.35
#Sta/Elev= 30
  4485.2  250.94  4520.5  250.28  4599.2   245.2  4637.7  243.98  4682.1  240.74
  4756.6  236.59  4831.8  233.39  4853.9  231.59  4898.3  230.49  4964.9  226.95
    4987  226.57  4992.7  223.16  5000.6  222.58  5003.3  222.08  5006.6  222.58
  5015.2  225.67  5025.8     227  5041.3  226.86  5089.8  227.02  5140.5  227.86
  5185.9  228.82  5201.7   230.1  5208.8  229.19  5216.2  230.45  5265.8  231.57
  5373.2  237.33  5443.7  242.39  5458.1  242.45  5493.3  244.78  5564.7  246.44
#Mann= 6 ,-1 , 0
  4485.2     .05       0  5000.6     .03       0  5006.6     .05       0
  5041.3     .08       0  5089.8     .12       0  5140.5     .05       0
Bank Sta=4987,5025.8
XS Rating Curve= 0 ,0
Exp/Cntr=0.3,0.1

Type RM Length L Ch R = 1 ,4004    ,598,598,598
BEGIN DESCRIPTION:
UNT010 IN BECR 4.0
END DESCRIPTION:
XS GIS Cut Line= 2
      3716032.52     10542800.21       3717113.2     10543238.55
#Sta/Elev= 30
  4353.7  252.69  4468.6  248.87    4588  241.57  4598.8  241.73  4641.9  239.78
  4674.3  237.42  4814.2  231.09  4873.2  228.06  4879.3  227.21  4933.3   225.1
  4944.6  225.28  4950.9  225.95    4975  226.07  4987.3  225.23    4995  221.32
  4997.8  220.82    5001  221.32  5004.5  225.58  5033.9  226.25    5052  225.57
    5058  226.46  5082.1  226.58  5116.5  228.79  5135.7  230.41  5181.5  231.76
  5218.8  233.86  5278.6  238.18  5374.1  243.52  5386.5  245.08  5519.9  251.53
#Mann= 5 ,-1 , 0
  4353.7     .05       0  4944.6     .12       0    4995     .07       0
    5001     .12       0  5116.5     .05       0
Bank Sta=4975,5004.5
XS Rating Curve= 0 ,0
Exp/Cntr=0.3,0.1

Type RM Length L Ch R = 1 ,3406    ,450,450,450
BEGIN DESCRIPTION:
UNT010 IN BECR 3.0
END DESCRIPTION:
XS GIS Cut Line= 3
      3716049.64      10543310.2      3716449.61     10543460.19
      3716749.61     10543510.19
#Sta/Elev= 30
  4595.2   243.2  4635.2  240.83  4695.7  238.56    4702  237.79    4734  236.07
  4806.1  232.88  4866.6  229.66  4872.8   228.9  4915.6  227.07  4921.8  226.35
  4936.9  226.01    4969  223.45    4977  223.21  4982.3  223.76  4990.3  222.19
    4998  221.72  5000.8  221.22    5004  221.72  5007.2  223.02  5012.6  223.92
  5044.4  223.79  5093.3   224.8  5133.8  227.88  5154.2  229.98  5184.6  231.49
  5237.8  235.97  5245.4  237.11  5298.6  241.19  5306.2  242.33  5326.5  243.67
#Mann= 5 ,-1 , 0
  4595.2     .05       0    4998     .03       0    5004     .05       0
  5044.4     .12       0  5133.8     .05       0
Bank Sta=4982.3,5012.6
XS Rating Curve= 0 ,0
Exp/Cntr=0.3,0.1

Type RM Length L Ch R = 1 ,2956    ,347,347,347
BEGIN DESCRIPTION:
UNT010 IN BECR 2.0
END DESCRIPTION:
XS GIS Cut Line= 3
      3715999.59     10543960.19      3716399.61     10543860.19
      3716799.57     10543810.19
#Sta/Elev= 30
    4604  241.13  4704.5  234.41  4709.7  234.74  4717.4  233.77  4727.7  233.39
  4792.1  232.35  4833.4  230.27  4851.4  228.45  4915.8  225.45  4944.2  223.02
  4957.1  222.83  4990.1  218.42  4992.9  217.92  4996.1  218.42    5006  220.44
  5008.1  221.34  5013.7  223.75  5046.6  223.24  5059.2  223.58  5066.7  223.09
  5118.9  223.53  5134.7  224.57  5147.3  227.45  5157.4  227.47  5197.7  230.33
  5220.4   232.6    5228  234.12  5328.7     243  5389.2  246.96  5419.4  248.34
#Mann= 5 ,-1 , 0
    4604     .05       0  4990.1     .03       0  4996.1     .05       0
  5008.1     .16       0  5118.9     .05       0
Bank Sta=4957.1,5013.7
XS Rating Curve= 0 ,0
Exp/Cntr=0.3,0.1

Type RM Length L Ch R = 1 ,2609    ,75,75,75
BEGIN DESCRIPTION:
Mapping XS b93c1870
END DESCRIPTION:
XS GIS Cut Line= 2
      3716021.19     10544642.41      3717026.34     10543643.77
#Sta/Elev= 30
  4285.6  241.88  4363.8     240  4370.9  241.88  4406.3  238.18  4427.5  239.42
  4448.7  237.69  4469.9  238.51    4583  235.14  4766.9  225.48  4802.3  226.28
  4809.3  225.15  4922.4  223.82  4957.8  225.28  4986.1  221.62  4993.2  217.43
  4997.2  217.15    5000  216.65  5003.2  217.15  5007.3   221.7  5028.5  221.94
  5056.8  225.41  5261.9  232.14  5367.9   237.4  5382.1  238.83  5403.3  245.66
  5410.4  244.91  5417.4  248.07  5452.8   250.4  5601.3  250.46  5702.5   255.1
#Mann= 3 ,-1 , 0
  4285.6     .08       0  4997.2     .07       0  5003.2     .08       0
Bank Sta=4957.8,5056.8
XS Rating Curve= 0 ,0
Exp/Cntr=0.3,0.1