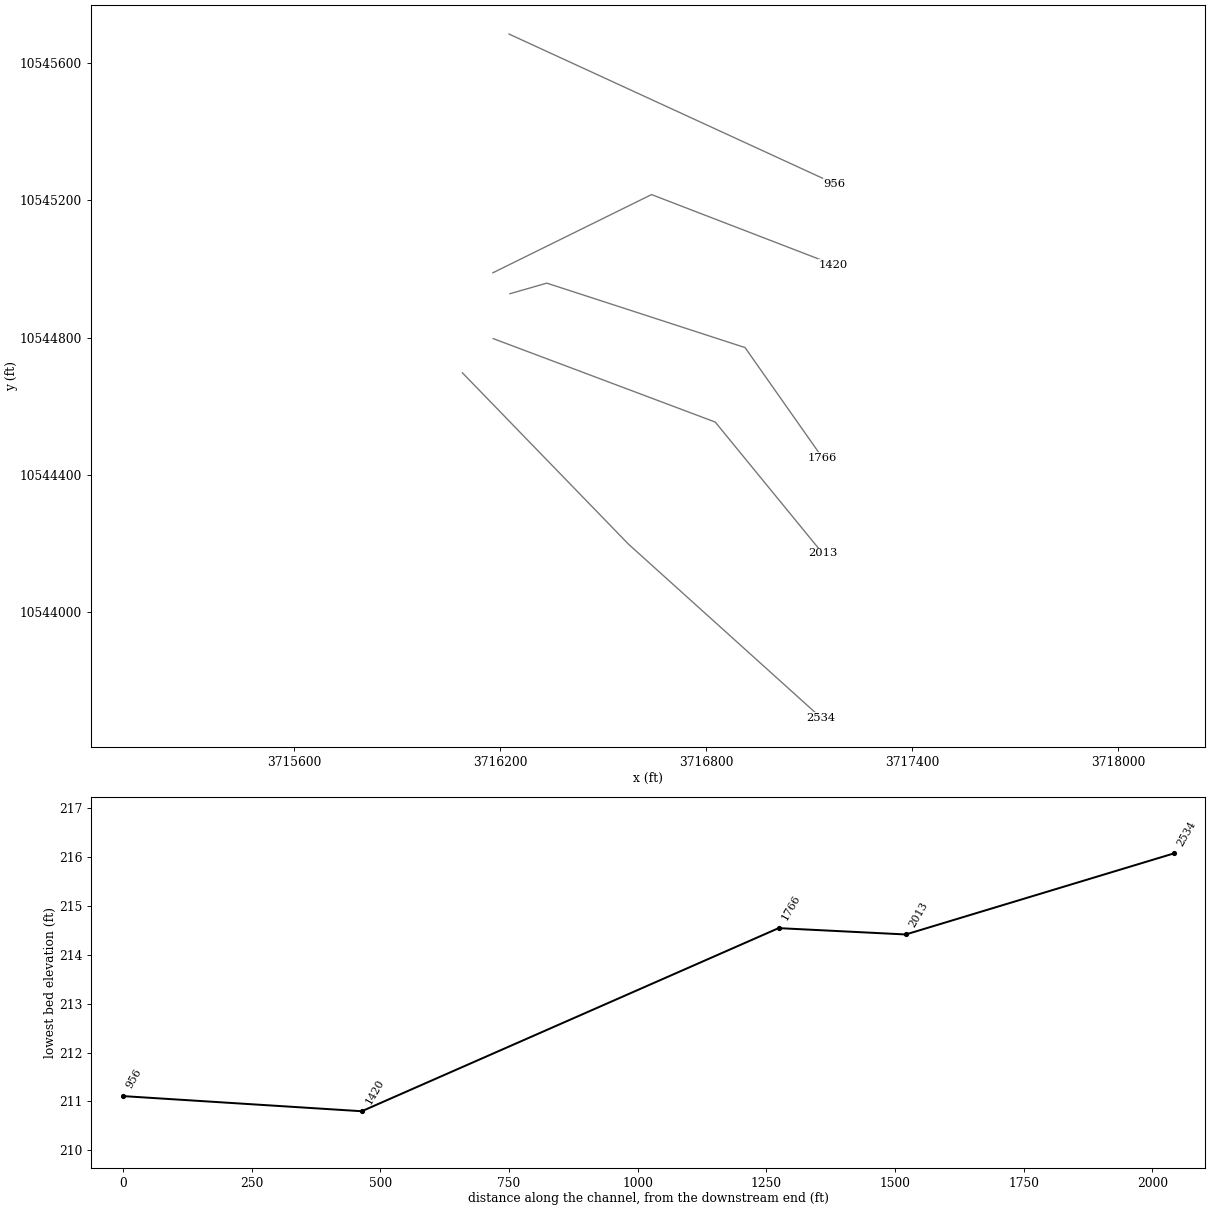
HEC-RAS study UNT010 IN BECR.prj: UNT010 IN BECR Base Level Engineering

--- UNT010 IN BECR.g01 (geometry) --- (continued)

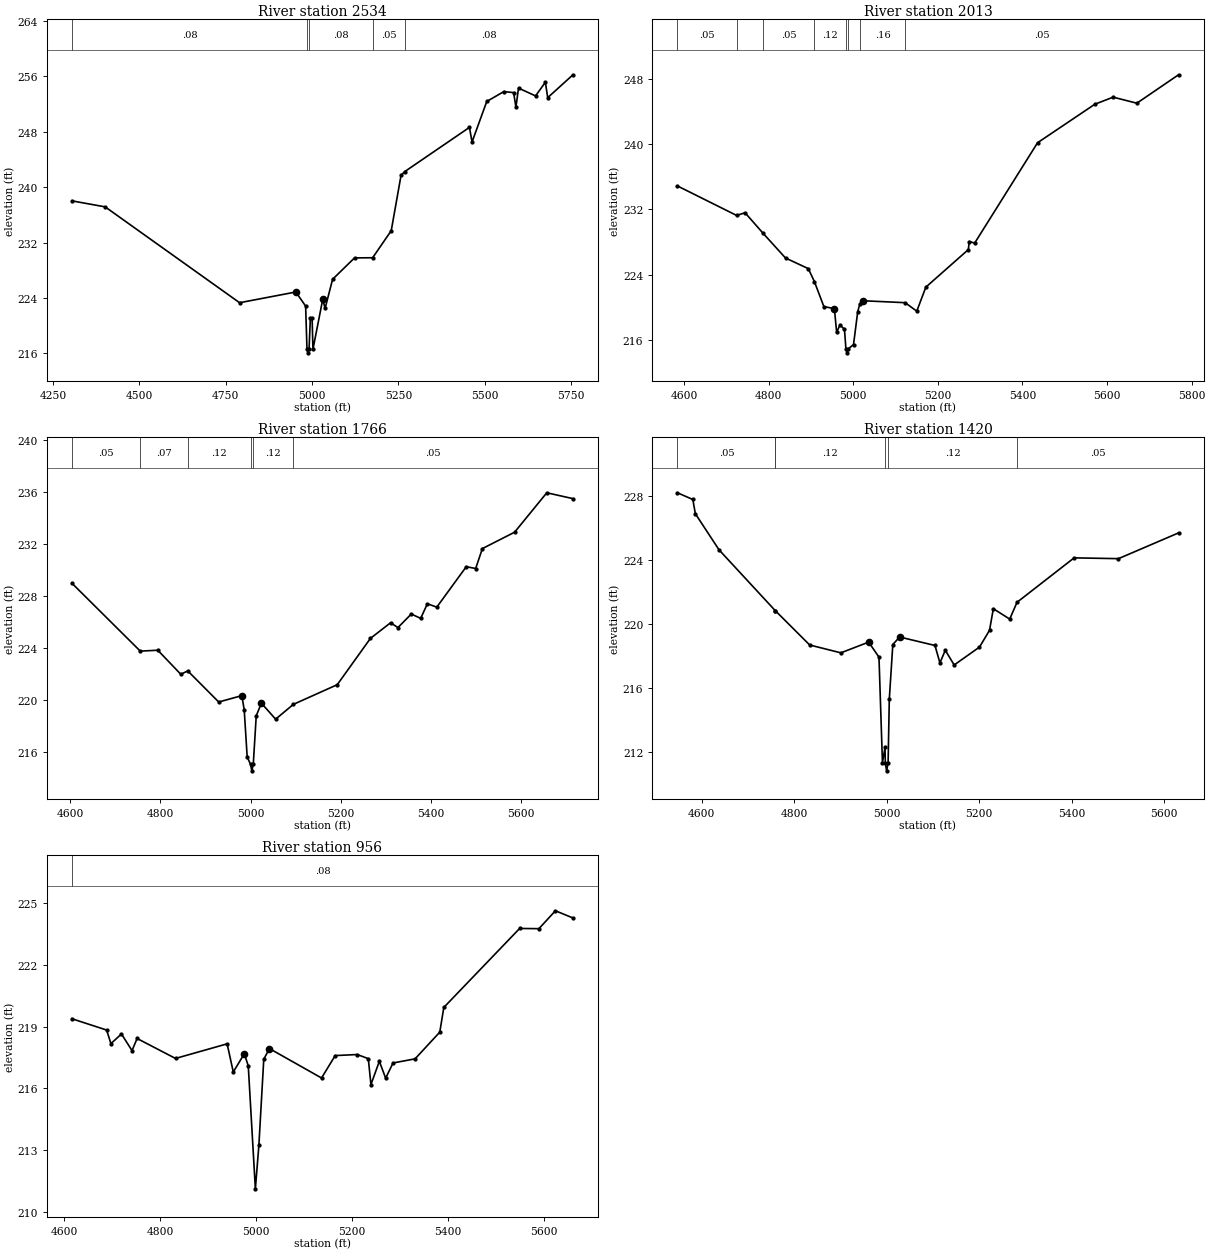
Type RM Length L Ch R = 1 ,2534    ,521,521,521
BEGIN DESCRIPTION:
Mapping XS bf7240c3
END DESCRIPTION:
XS GIS Cut Line= 3
       3716090.2      10544697.1        3716574.       10544198.
      3717134.76     10543692.45
#Sta/Elev= 30
  4304.9  238.01  4401.2  237.14  4790.2  223.31    4953  224.86  4981.3  222.82
  4985.2  216.58    4988  216.08  4991.2  216.58    4995  221.07    5000  221.07
  5002.5   216.6  5030.9  223.83  5037.6  222.48  5059.3  226.69  5122.8  229.78
  5175.2   229.8    5229   233.7  5257.4  241.68  5268.1  242.23  5455.4  248.61
  5462.9   246.5  5505.5  252.35  5554.8  253.77  5583.2  253.63  5589.9  251.53
  5597.4  254.28  5646.7  253.15  5675.1  255.12  5681.9   252.9    5755   256.2
#Mann= 5 ,-1 , 0
  4304.9     .08       0  4985.2     .07       0  4991.2     .08       0
  5175.2     .05       0  5268.1     .08       0
Bank Sta=4953,5030.9
XS Rating Curve= 0 ,0
Exp/Cntr=0.3,0.1

Type RM Length L Ch R = 1 ,2013    ,247,247,247
BEGIN DESCRIPTION:
Mapping XS 8ada226b
END DESCRIPTION:
XS GIS Cut Line= 3
      3716180.04     10544796.74      3716826.77     10544553.67
      3717139.27     10544171.72
#Sta/Elev= 30
  4584.6  234.85  4724.5  231.24  4744.4  231.57  4786.6  229.08    4840  226.03
  4893.9  224.73  4908.4  223.13  4930.7  220.08  4955.6  219.83  4960.9  216.92
  4968.7  217.84  4979.4  217.29  4982.8  214.92  4985.6  214.42  4988.8  214.92
  5000.8  215.44  5010.7  219.46  5015.6  220.38  5022.1   220.8  5122.8  220.56
  5150.3  219.52  5171.7  222.46  5272.2  227.06  5274.3  228.05  5287.2  227.86
  5435.8  240.14  5571.4  244.86  5614.5  245.72  5670.5  244.98    5769  248.46
#Mann= 8 ,-1 , 0
  4584.6     .05       0  4724.5     .08       0  4786.6     .05       0
  4908.4     .12       0  4982.8     .07       0  4988.8     .12       0
  5015.6     .16       0  5122.8     .05       0
Bank Sta=4955.6,5022.1
XS Rating Curve= 0 ,0
Exp/Cntr=0.3,0.1

Type RM Length L Ch R = 1 ,1766    ,810,810,810
BEGIN DESCRIPTION:
Mapping XS 6c771354
END DESCRIPTION:
XS GIS Cut Line= 4
      3716228.71     10544927.58      3716336.08     10544958.37
      3716913.57     10544770.68      3717139.28     10544449.48
#Sta/Elev= 30
  4603.7  228.97  4755.4  223.75  4794.2  223.82  4845.3  221.97  4860.7  222.23
  4929.4  219.84  4980.6  220.33  4985.9  219.25  4992.5  215.62    5000  215.05
  5002.8  214.55    5006  215.05  5012.6  218.78    5024  219.75  5055.6  218.52
    5095  219.66  5192.3  221.17  5265.9  224.73  5310.6  225.93  5326.9  225.56
  5356.5   226.6  5377.4  226.27  5392.2  227.39  5413.1  227.13  5478.5  230.24
  5499.4   230.1  5514.2  231.63  5585.7  232.89  5657.1  235.92  5715.2  235.47
#Mann= 6 ,-1 , 0
  4603.7     .05       0  4755.4     .07       0  4860.7     .12       0
    5000     .07       0    5006     .12       0    5095     .05       0
Bank Sta=4980.6,5024
XS Rating Curve= 0 ,0
Exp/Cntr=0.3,0.1

Type RM Length L Ch R = 1 ,1420    ,464,464,464
BEGIN DESCRIPTION:
Mapping XS 055e0032
END DESCRIPTION:
XS GIS Cut Line= 3
      3716178.97     10544988.51       3716641.2     10545216.37
      3717170.72     10545012.37
#Sta/Elev= 30
  4547.8  228.19    4581  227.77  4586.5  226.88  4637.7  224.62  4759.4  220.81
  4759.5  220.81  4833.6  218.67  4900.9  218.18    4961  218.85  4983.3  217.91
  4990.8   211.3  4996.3  212.27    4997   211.3  4999.8   210.8    5003   211.3
  5005.6  215.27  5013.2   218.7  5027.9  219.17  5104.3  218.64    5115  217.55
  5126.6  218.34  5145.8  217.42  5200.5  218.54  5222.2  219.59  5230.4  220.94
  5265.8  220.29  5281.6  221.34    5405  224.12  5500.8  224.07  5630.6  225.68
#Mann= 6 ,-1 , 0
  4547.8     .05       0  4759.4     .07       0  4759.5     .12       0
    4997     .07       0    5003     .12       0  5281.6     .05       0
Bank Sta=4961,5027.9
XS Rating Curve= 0 ,0
Exp/Cntr=0.3,0.1

Type RM Length L Ch R = 1 ,956     ,0,0,0
BEGIN DESCRIPTION:
UNT010 IN BECR 1.0
END DESCRIPTION:
XS GIS Cut Line= 2
     3716225.849    10545684.085      3717174.03      10545248.1
#Sta/Elev= 30
  4616.3  219.38  4688.7  218.83  4697.5  218.17  4719.5  218.64  4741.5  217.83
  4752.1  218.42  4832.1  217.45  4939.6  218.16  4952.4  216.79  4975.4  217.68
  4983.6  217.09  4998.4  211.11  5005.7  213.22  5015.9  217.41  5027.7  217.93
  5136.2   216.5  5164.7  217.59  5210.7  217.64  5233.6  217.44  5239.1  216.18
  5256.6  217.31  5269.8  216.49  5285.1  217.23    5331  217.43  5382.5  218.73
  5390.9  219.93  5548.8  223.77    5589  223.76  5623.3  224.63  5659.9  224.28
#Mann= 1 ,-1 , 0
  4616.3     .08       0
Bank Sta=4975.4,5027.7
XS Rating Curve= 0 ,0
Exp/Cntr=0.3,0.1

Chan Stop Cuts=-1
Use User Specified Reach Order=0
Composite Channel Slope=5