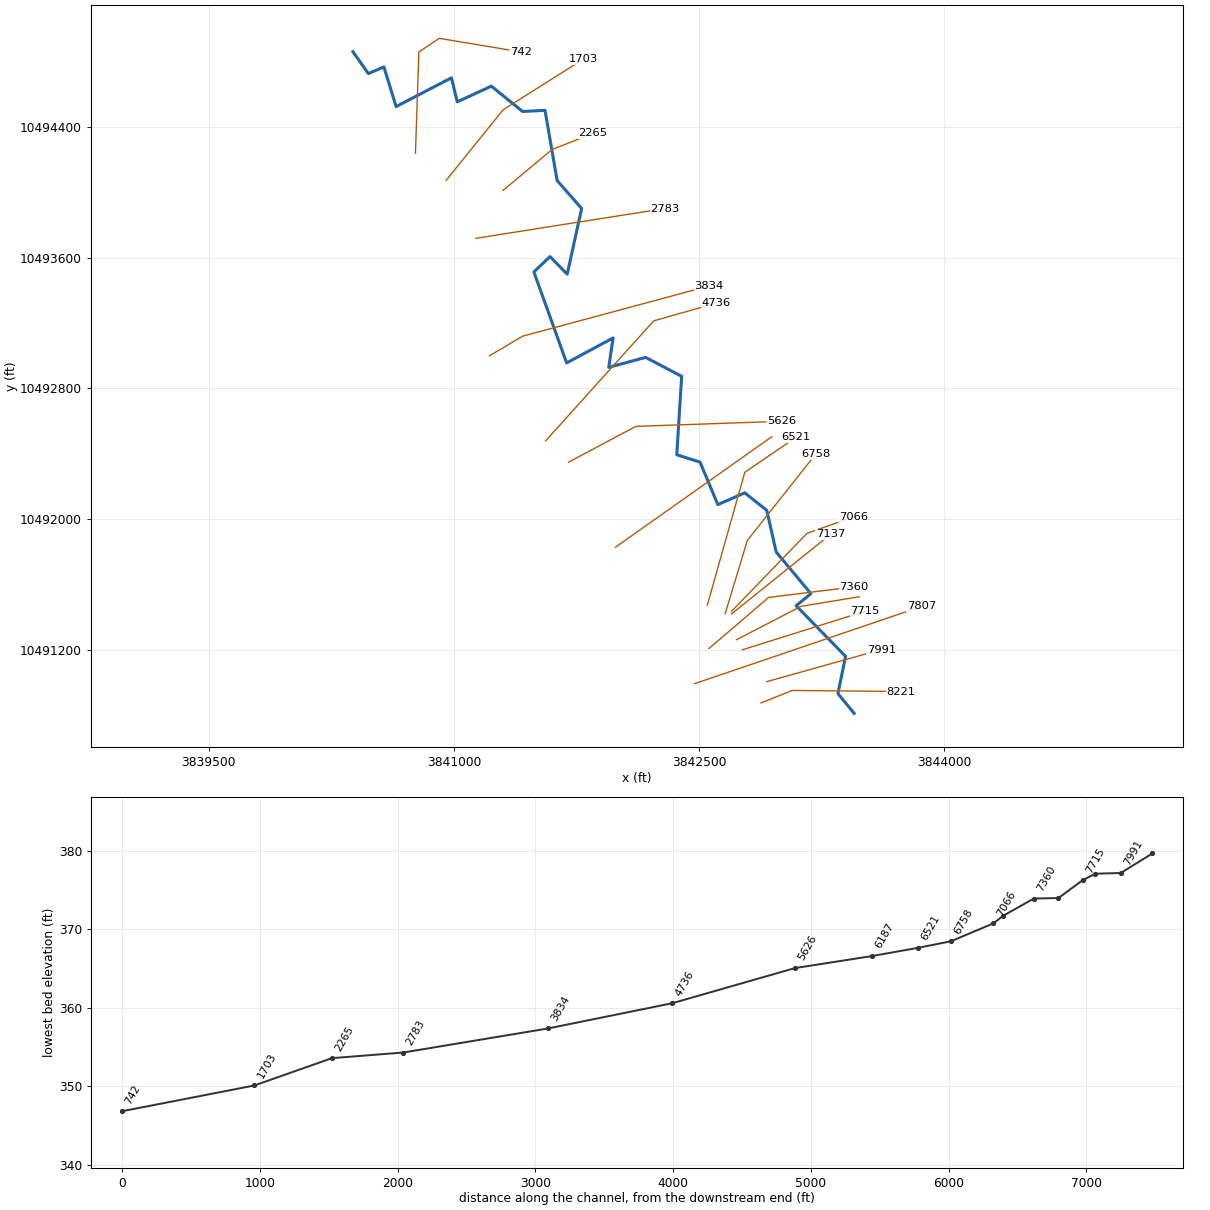
--- UNT012 IN BECR.prj (project) ---

Proj Title=UNT012 IN BECR Base Level Engineering
Current Plan=p01
Default Exp/Contr=0.3,0.1
English Units
Geom File=g01
Flow File=f01
Plan File=p01
BEGIN DESCRIPTION:
UNT012 IN BECR
END DESCRIPTION:

--- UNT012 IN BECR.p01 (plan) ---

Plan Title=Multiple Run
Short Identifier=Multiple
Geom File=g01
Flow File=f01
Subcritical Flow
K Sum by GR= 0
Std Step Tol= 0.01
Critical Tol= 0.01
Num of Std Step Trials= 20
Max Error Tol= 0.3
Flow Tol Ratio= 0.001
Split Flow NTrial= 30
Split Flow Tol= 0.02
Split Flow Ratio= 0.02
Log Output Level= 0
Friction Slope Method= 1
Unsteady Friction Slope Method= 2
Unsteady Bridges Friction Slope Method= 1
Parabolic Critical Depth
Global Vel Dist=  1 , 1 , 1
Global Log Level= 0
CheckData=True
Encroach Param= -1, 0, 0, 0
BEGIN DESCRIPTION:
Multiple Run
END DESCRIPTION:

--- UNT012 IN BECR.f01 (steady flow) ---

Flow Title=Multiple
Number of Profiles=7
Profile Names=10-year,25-year,50-year,1pct_min,100-year,1pct_plu,500-year
River Rch & RM= UNT012 IN BECR,Reach-1,8221
     477     630     754     663     896    1212    1270
Boundary for River Rch & Prof#=UNT012 IN BECR,Reach-1,1
Up Type=0
Dn Type=3
Dn Slope=0.005
Boundary for River Rch & Prof#=UNT012 IN BECR,Reach-1,2
Up Type=0
Dn Type=3
Dn Slope=0.005
Boundary for River Rch & Prof#=UNT012 IN BECR,Reach-1,3
Up Type=0
Dn Type=3
Dn Slope=0.005
Boundary for River Rch & Prof#=UNT012 IN BECR,Reach-1,4
Up Type=0
Dn Type=3
Dn Slope=0.005
Boundary for River Rch & Prof#=UNT012 IN BECR,Reach-1,5
Up Type=0
Dn Type=3
Dn Slope=0.005
Boundary for River Rch & Prof#=UNT012 IN BECR,Reach-1,6
Up Type=0
Dn Type=3
Dn Slope=0.005
Boundary for River Rch & Prof#=UNT012 IN BECR,Reach-1,7
Up Type=0
Dn Type=3
Dn Slope=0.005

--- UNT012 IN BECR.g01 (geometry) ---

Geom Title=Existing Conditions

River Reach=UNT012 IN BECR,Reach-1
Reach XY= 30
      3843449.61     10490810.19      3843350.25     10490931.00
      3843397.25     10491159.00      3843094.75     10491469.00
      3843185.00     10491543.00      3842972.50     10491798.00
      3842914.75     10492053.00      3842780.00     10492160.00
      3842615.25     10492088.00      3842506.50     10492348.00
      3842364.00     10492393.00      3842394.00     10492873.00
      3842173.50     10492989.00      3841947.50     10492928.00
      3841974.50     10493108.00      3841690.00     10492955.00
      3841489.50     10493512.00      3841588.75     10493606.00
      3841693.25     10493498.00      3841782.00     10493900.00
      3841632.00     10494071.00      3841557.50     10494501.00
      3841420.25     10494494.00      3841229.25     10494649.00
      3841020.75     10494553.00      3840985.00     10494700.00
      3840646.50     10494524.00      3840571.50     10494767.00
      3840476.50     10494726.00      3840382.00     10494860.00

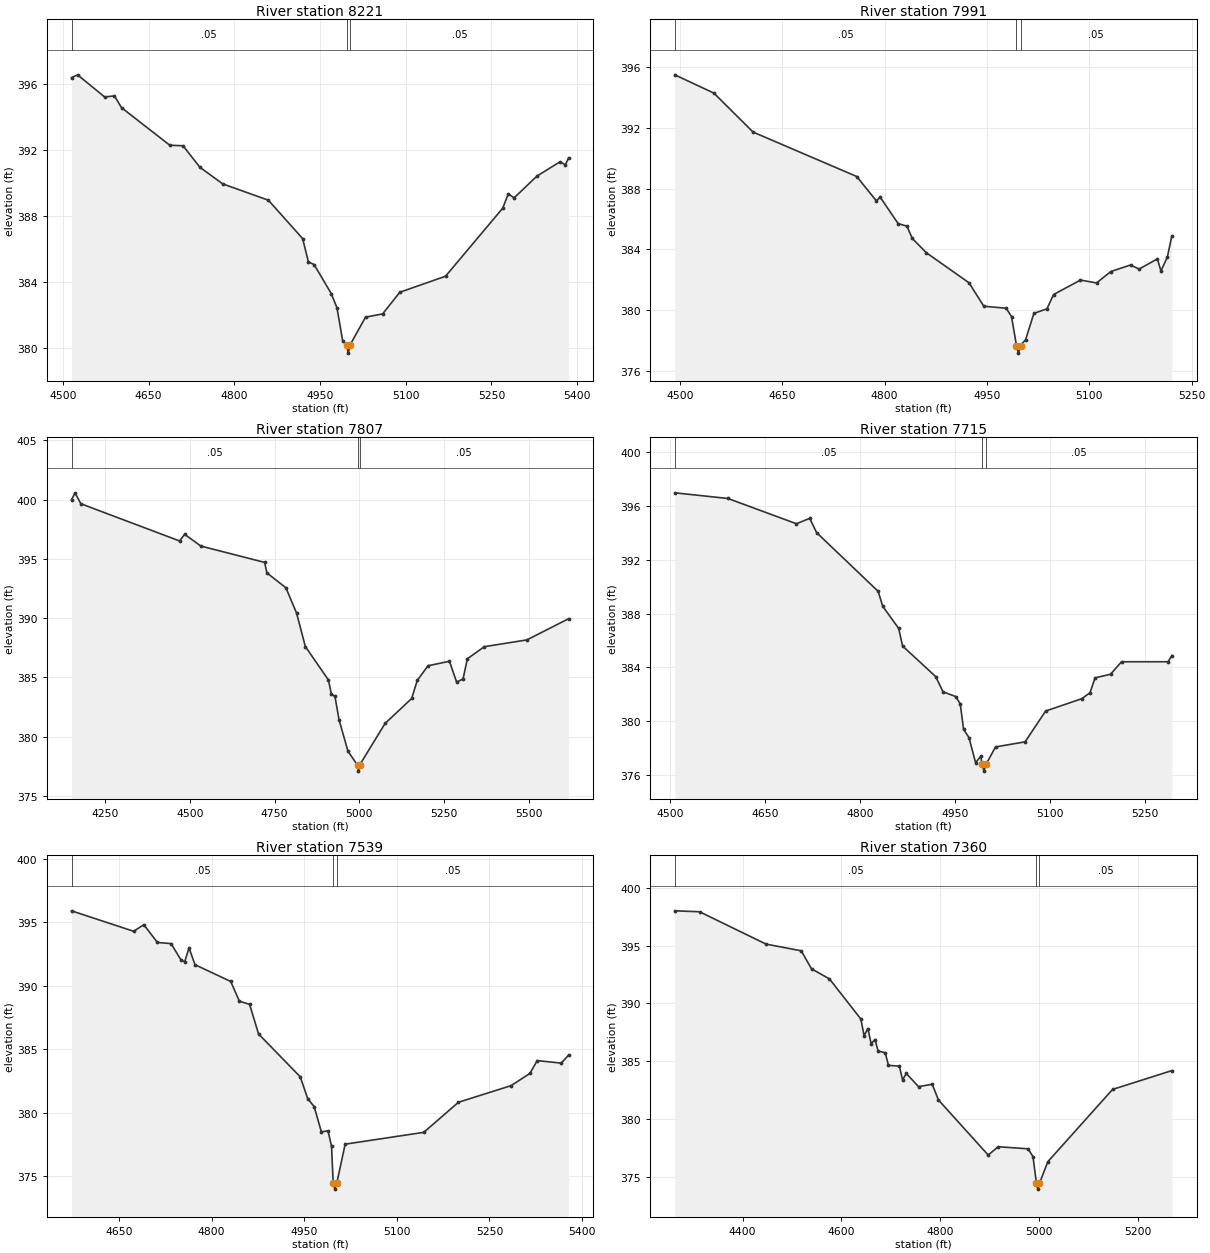
Type RM Length L Ch R = 1,8221,230,230,230
BEGIN DESCRIPTION:
UNT012 IN BECR 12.0
END DESCRIPTION:
XS GIS Cut Line= 3
      3842879.77     10490874.14      3843070.78     10490950.54
      3843735.03     10490943.97
#Sta/Elev= 30
  4515.1  396.39  4525.7  396.56  4573.0  395.22  4590.3  395.28  4602.6  394.57
  4687.2  392.29  4710.3  392.26  4739.7  390.96  4779.7  389.95  4859.7  388.96
  4919.7  386.63  4929.7  385.22  4939.7  385.06  4969.7  383.30  4979.7  382.44
  4989.7  380.44  4996.7  380.19  4999.4  379.69  5002.7  380.19  5029.7  381.87
  5059.7  382.07  5089.7  383.38  5169.7  384.35  5269.7  388.47  5279.7  389.35
  5289.7  389.10  5329.7  390.42  5369.7  391.28  5379.7  391.11  5385.1  391.53
#Mann=3,-1,0
  4515.1    0.05       0  4996.7    0.03       0  5002.7    0.05       0
Bank Sta=4996.7,5002.7
Exp/Cntr=0.3,0.1

Type RM Length L Ch R = 1,7991,184,184,184
BEGIN DESCRIPTION:
Mapping XS bc871361
END DESCRIPTION:
XS GIS Cut Line= 2
      3842914.43     10491004.20      3843615.94     10491200.65
#Sta/Elev= 30
  4492.4  395.47  4549.7  394.27  4607.1  391.71  4759.1  388.79  4788.0  387.18
  4793.2  387.45  4819.7  385.70  4832.6  385.53  4840.5  384.72  4861.2  383.78
  4923.6  381.81  4945.3  380.27  4978.1  380.14  4985.9  379.59  4993.2  377.69
  4996.0  377.19  4999.2  377.69  5006.6  378.08  5018.7  379.80  5037.8  380.10
  5047.6  381.04  5087.0  381.99  5110.5  381.80  5131.5  382.55  5160.4  382.98
  5172.8  382.71  5199.7  383.38  5204.9  382.59  5214.3  383.50  5220.9  384.89
#Mann=3,-1,0
  4492.4    0.05       0  4993.2    0.03       0  4999.2    0.05       0
Bank Sta=4993.2,4999.2
Exp/Cntr=0.3,0.1

Type RM Length L Ch R = 1,7807,92,92,92
BEGIN DESCRIPTION:
UNT012 IN BECR 11.0
END DESCRIPTION:
XS GIS Cut Line= 2
      3842473.58     10490992.22      3843862.40     10491464.42
#Sta/Elev= 30
  4150.8  400.00  4161.2  400.58  4178.3  399.66  4469.7  396.52  4484.6  397.08
  4532.5  396.09  4720.7  394.71  4727.5  393.82  4783.5  392.57  4814.9  390.44
  4840.9  387.61  4909.0  384.79  4917.7  383.59  4928.2  383.41  4940.4  381.43
  4966.5  378.79  4994.8  377.60  4997.6  377.10  5000.8  377.60  5076.1  381.12
  5154.7  383.23  5171.1  384.75  5202.8  385.99  5266.2  386.37  5287.3  384.61
  5306.3  384.88  5319.0  386.58  5369.1  387.60  5494.6  388.17  5617.7  389.96
#Mann=3,-1,0
  4150.8    0.05       0  4994.8    0.03       0  5000.8    0.05       0
Bank Sta=4994.8,5000.8
Exp/Cntr=0.3,0.1

Type RM Length L Ch R = 1,7715,176,176,176
BEGIN DESCRIPTION:
Mapping XS fc035064
END DESCRIPTION:
XS GIS Cut Line= 2
      3842766.32     10491199.52      3843515.35     10491434.75
#Sta/Elev= 30
  4507.0  396.99  4590.9  396.57  4699.1  394.69  4720.1  395.09  4731.0  394.03
  4828.2  389.66  4835.4  388.55  4860.6  386.90  4866.8  385.59  4919.2  383.31
  4930.7  382.18  4950.7  381.83  4957.9  381.28  4963.1  379.39  4971.6  378.78
  4982.1  376.91  4990.3  377.38  4992.5  376.78  4995.3  376.28  4998.5  376.78
  5013.6  378.08  5060.3  378.46  5092.7  380.75  5149.8  381.67  5162.8  382.11
  5170.8  383.22  5195.2  383.49  5212.7  384.42  5286.1  384.42  5292.1  384.88
#Mann=3,-1,0
  4507.0    0.05       0  4992.5    0.03       0  4998.5    0.05       0
Bank Sta=4992.5,4998.5
Exp/Cntr=0.3,0.1

Type RM Length L Ch R = 1,7539,179,179,179
BEGIN DESCRIPTION:
Mapping XS 2c1d883f
END DESCRIPTION:
XS GIS Cut Line= 3
      3842730.56     10491261.40      3843124.40     10491465.37
      3843481.40     10491523.96
#Sta/Elev= 30
  4573.0  395.91  4673.6  394.30  4690.1  394.82  4712.2  393.42  4734.3  393.33
  4750.8  392.01  4756.5  391.92  4763.4  392.99  4773.0  391.67  4830.9  390.35
  4845.0  388.79  4861.5  388.55  4876.0  386.22  4943.6  382.84  4955.7  381.12
  4966.1  380.50  4977.8  378.51  4988.6  378.59  4994.3  377.36  4996.9  374.50
  4999.7  374.00  5002.9  374.50  5016.3  377.54  5143.7  378.47  5199.9  380.84
  5285.3  382.15  5315.7  383.11  5327.5  384.12  5366.4  383.92  5378.3  384.55
#Mann=3,-1,0
  4573.0    0.05       0  4996.9    0.03       0  5002.9    0.05       0
Bank Sta=4996.9,5002.9
Exp/Cntr=0.3,0.1

Type RM Length L Ch R = 1,7360,223,223,223
BEGIN DESCRIPTION:
UNT012 IN BECR 10.0
END DESCRIPTION:
XS GIS Cut Line= 3
      3842561.58     10491207.32      3842926.16     10491519.81
      3843448.79     10491584.48
#Sta/Elev= 30
  4262.7  398.02  4312.8  397.94  4447.5  395.14  4518.8  394.56  4539.6  393.00
  4575.9  392.13  4639.5  388.66  4646.1  387.22  4653.8  387.82  4660.4  386.52
  4668.1  386.88  4674.6  385.88  4688.9  385.74  4695.5  384.64  4717.5  384.58
  4724.0  383.39  4731.7  383.94  4756.4  382.80  4784.1  383.01  4796.7  381.65
  4897.5  376.88  4917.7  377.60  4978.1  377.42  4988.2  376.75  4995.3  374.43
  4998.0  373.93  5001.3  374.43  5018.4  376.31  5149.4  382.56  5269.5  384.19
#Mann=3,-1,0
  4262.7    0.05       0  4995.3    0.03       0  5001.3    0.05       0
Bank Sta=4995.3,5001.3
Exp/Cntr=0.3,0.1

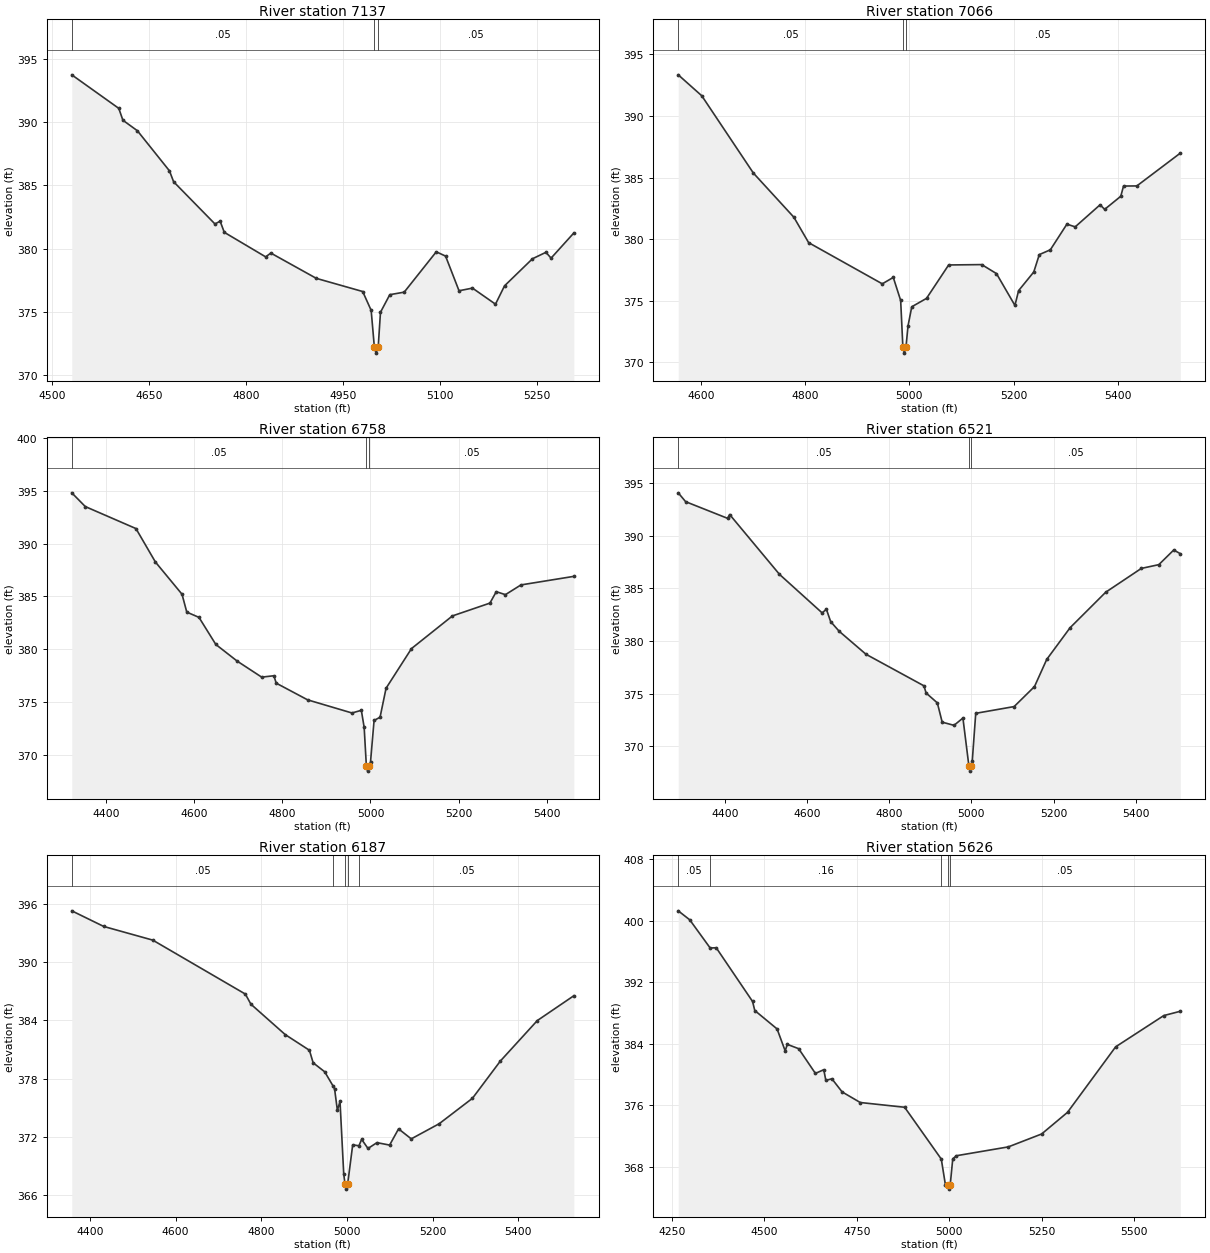
Type RM Length L Ch R = 1,7137,71,71,71
BEGIN DESCRIPTION:
Mapping XS 758c8f6a
END DESCRIPTION:
XS GIS Cut Line= 2
      3842699.04     10491418.74      3843304.07     10491905.62
#Sta/Elev= 30
  4530.9  393.73  4603.6  391.08  4610.0  390.14  4632.4  389.31  4682.0  386.14
  4688.4  385.28  4752.4  381.94  4760.4  382.16  4766.8  381.28  4830.8  379.34
  4838.8  379.64  4909.2  377.64  4980.9  376.60  4994.0  375.11  4998.9  372.23
  5001.7  371.73  5004.9  372.23  5008.4  374.96  5022.8  376.35  5045.1  376.55
  5094.7  379.74  5109.1  379.40  5129.9  376.66  5150.7  376.87  5186.3  375.60
  5200.3  377.05  5243.5  379.19  5264.3  379.70  5272.3  379.24  5307.5  381.23
#Mann=3,-1,0
  4530.9    0.05       0  4998.9    0.03       0  5004.9    0.05       0
Bank Sta=4998.9,5004.9
Exp/Cntr=0.3,0.1

Type RM Length L Ch R = 1,7066,308,308,308
BEGIN DESCRIPTION:
Mapping XS a31be116
END DESCRIPTION:
XS GIS Cut Line= 3
      3842700.30     10491435.63      3843161.25     10491912.21
      3843444.86     10492012.38
#Sta/Elev= 30
  4556.2  393.33  4601.4  391.63  4700.5  385.36  4778.2  381.78  4806.5  379.72
  4947.9  376.38  4969.0  376.90  4983.2  375.03  4987.4  371.26  4990.1  370.76
  4993.4  371.26  4997.3  372.97  5004.5  374.52  5032.8  375.20  5075.3  377.91
  5138.8  377.94  5167.1  377.21  5202.5  374.63  5209.6  375.83  5238.7  377.34
  5249.3  378.75  5270.5  379.14  5302.3  381.22  5318.2  381.00  5366.0  382.79
  5374.8  382.42  5405.7  383.48  5411.0  384.31  5436.6  384.32  5520.0  386.98
#Mann=3,-1,0
  4556.2    0.05       0  4987.4    0.03       0  4993.4    0.05       0
Bank Sta=4987.4,4993.4
Exp/Cntr=0.3,0.1

Type RM Length L Ch R = 1,6758,237,237,237
BEGIN DESCRIPTION:
UNT012 IN BECR 9.0
END DESCRIPTION:
XS GIS Cut Line= 3
      3842660.53     10491420.84      3842795.95     10491868.77
      3843212.60     10492394.79
#Sta/Elev= 30
  4322.4  394.80  4353.1  393.50  4468.0  391.42  4512.1  388.26  4572.5  385.21
  4583.3  383.52  4611.0  383.02  4649.2  380.46  4697.8  378.88  4753.2  377.37
  4780.9  377.50  4786.2  376.80  4857.5  375.22  4958.0  373.98  4979.3  374.23
  4985.7  372.63  4990.7  368.98  4993.5  368.48  4996.7  368.98  5000.1  369.33
  5008.2  373.27  5021.8  373.58  5035.4  376.32  5093.1  380.07  5186.0  383.16
  5271.0  384.37  5285.4  385.45  5306.2  385.17  5341.4  386.09  5461.4  386.90
#Mann=3,-1,0
  4322.4    0.05       0  4990.7    0.03       0  4996.7    0.05       0
Bank Sta=4990.7,4996.7
Exp/Cntr=0.3,0.1

Type RM Length L Ch R = 1,6521,334,334,334
BEGIN DESCRIPTION:
UNT012 IN BECR 8.0
END DESCRIPTION:
XS GIS Cut Line= 3
      3842551.15     10491472.91      3842780.32     10492285.44
      3843092.80     10492498.97
#Sta/Elev= 30
  4286.1  394.08  4304.1  393.24  4406.1  391.66  4411.3  392.02  4532.6  386.34
  4636.5  382.68  4646.9  383.02  4657.3  381.85  4678.1  380.93  4743.3  378.75
  4884.5  375.75  4889.7  375.07  4917.1  374.13  4928.9  372.30  4957.7  372.00
  4979.4  372.69  4993.9  368.15  4996.6  367.65  4999.9  368.15  5002.1  368.59
  5010.6  373.14  5104.1  373.78  5153.7  375.68  5183.5  378.26  5240.4  381.27
  5327.1  384.64  5413.8  386.90  5456.5  387.26  5492.8  388.65  5508.8  388.30
#Mann=3,-1,0
  4286.1    0.05       0  4993.9    0.03       0  4999.9    0.05       0
Bank Sta=4993.9,4999.9
Exp/Cntr=0.3,0.1

Type RM Length L Ch R = 1,6187,561,561,561
BEGIN DESCRIPTION:
UNT012 IN BECR 7.0
END DESCRIPTION:
XS GIS Cut Line= 2
      3841988.67     10491827.11      3842945.78     10492503.33
#Sta/Elev= 30
  4357.7  395.28  4432.3  393.67  4546.8  392.26  4762.9  386.70  4775.8  385.66
  4855.8  382.53  4912.4  380.91  4921.1  379.62  4948.1  378.69  4967.7  377.22
  4971.1  376.94  4977.7  374.71  4983.8  375.65  4992.5  368.15  4995.6  367.10
  4998.4  366.60  5001.6  367.10  5013.4  371.16  5028.0  371.07  5034.3  371.73
  5049.1  370.79  5070.0  371.39  5099.6  371.14  5120.5  372.81  5150.1  371.78
  5215.3  373.34  5292.9  375.96  5358.1  379.80  5444.3  383.97  5529.6  386.53
#Mann=5,-1,0
  4357.7    0.05       0  4967.7    0.16       0  4995.6    0.07       0
  5001.6    0.16       0  5028.0    0.05       0
Bank Sta=4995.6,5001.6
Exp/Cntr=0.3,0.1

Type RM Length L Ch R = 1,5626,890,890,890
BEGIN DESCRIPTION:
UNT012 IN BECR 6.0
END DESCRIPTION:
XS GIS Cut Line= 3
      3841702.19     10492347.93      3842113.66     10492566.69
      3843004.30     10492597.94
#Sta/Elev= 30
  4267.0  401.30  4298.1  400.13  4353.3  396.46  4369.7  396.49  4467.9  389.50
  4473.9  388.32  4534.2  385.92  4556.1  383.06  4561.8  383.91  4592.5  383.35
  4637.8  380.13  4660.4  380.61  4666.0  379.22  4682.3  379.43  4710.0  377.72
  4759.0  376.34  4879.0  375.72  4978.1  368.97  4989.1  365.66  4996.1  365.56
  4998.9  365.06  5002.1  365.56  5009.1  369.01  5019.1  369.41  5159.2  370.56
  5249.3  372.24  5319.3  375.06  5449.4  383.59  5579.5  387.66  5624.2  388.22
#Mann=5,-1,0
  4267.0    0.05       0  4353.3    0.16       0  4978.1    0.05       0
  4996.1    0.03       0  5002.1    0.05       0
Bank Sta=4996.1,5002.1
Exp/Cntr=0.3,0.1

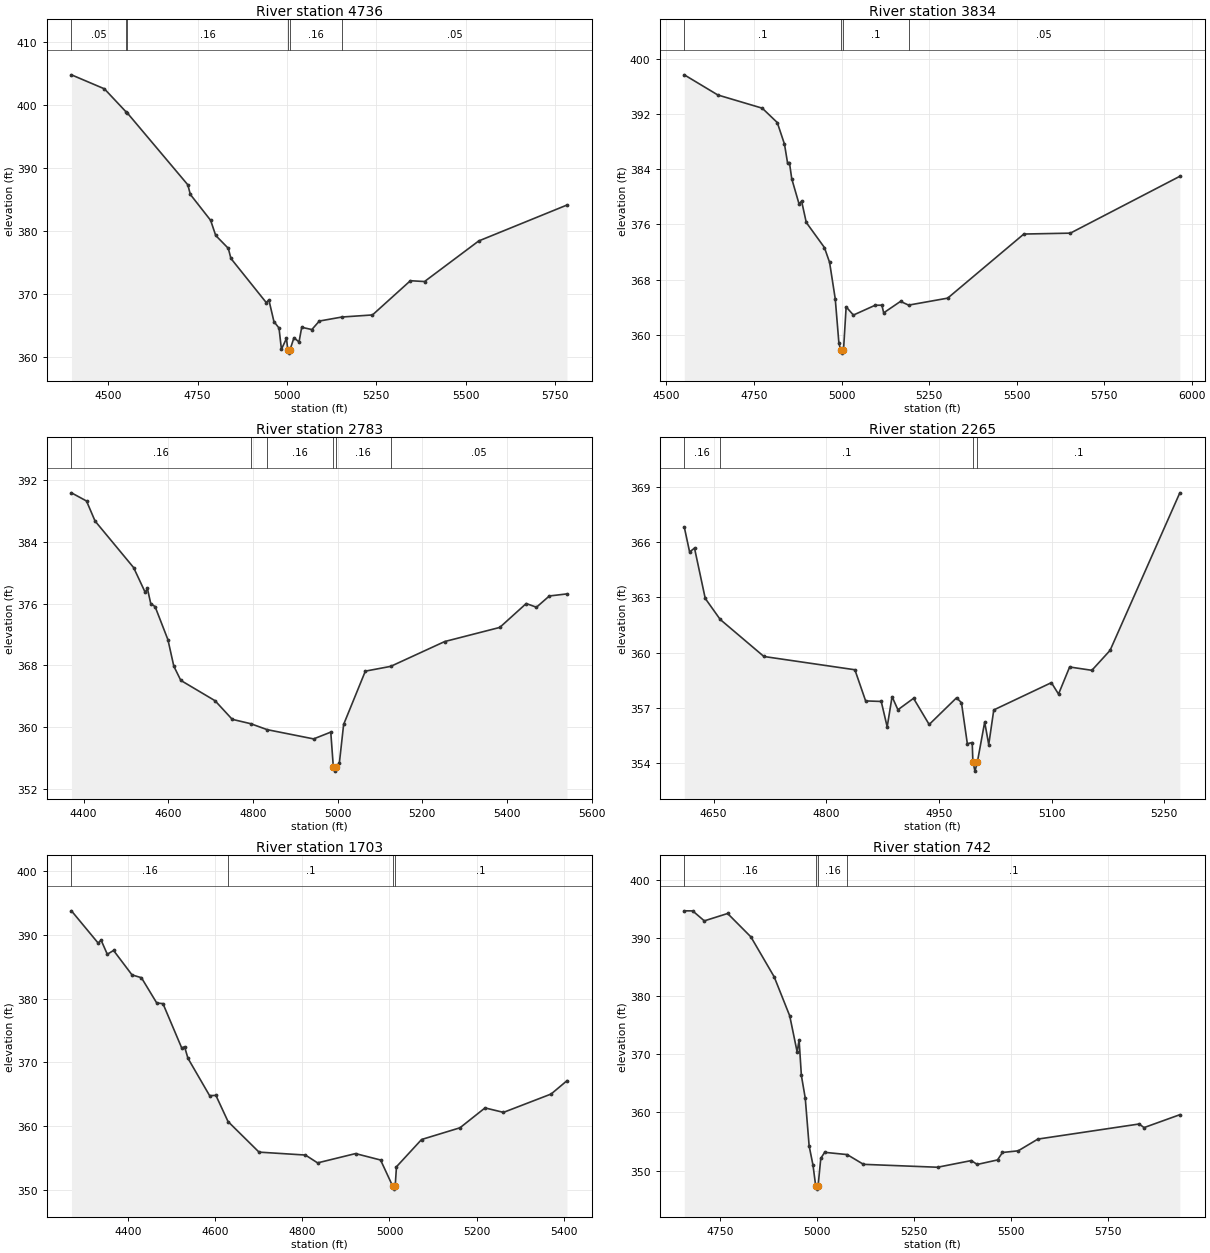
Type RM Length L Ch R = 1,4736,902,902,902
BEGIN DESCRIPTION:
UNT012 IN BECR 5.0
END DESCRIPTION:
XS GIS Cut Line= 3
      3841561.60     10492478.18      3842223.03     10493212.52
      3842606.58     10493321.37
#Sta/Elev= 30
  4396.7  404.74  4488.9  402.52  4549.6  398.86  4552.6  398.72  4722.4  387.29
  4729.5  385.76  4786.3  381.65  4800.5  379.25  4835.7  377.21  4843.1  375.60
  4941.8  368.61  4949.3  369.02  4963.5  365.58  4977.7  364.56  4984.4  361.19
  4998.6  362.91  5002.3  361.08  5005.1  360.58  5008.3  361.08  5019.5  363.02
  5033.7  362.35  5041.2  364.68  5069.6  364.32  5090.5  365.67  5153.9  366.31
  5239.3  366.64  5345.4  372.07  5385.0  371.94  5536.7  378.38  5783.7  384.08
#Mann=6,-1,0
  4396.7    0.05       0  4549.6     0.1       0  4552.6    0.16       0
  5002.3    0.07       0  5008.3    0.16       0  5153.9    0.05       0
Bank Sta=5002.3,5008.3
Exp/Cntr=0.3,0.1

Type RM Length L Ch R = 1,3834,1051,1051,1051
BEGIN DESCRIPTION:
UNT012 IN BECR 4.0
END DESCRIPTION:
XS GIS Cut Line= 3
      3841217.81     10492998.97      3841420.95     10493118.77
      3842559.90     10493425.61
#Sta/Elev= 30
  4550.9  397.65  4646.8  394.73  4773.6  392.82  4816.5  390.74  4837.1  387.61
  4846.1  384.82  4851.3  384.93  4857.8  382.61  4878.6  378.97  4886.0  379.36
  4899.3  376.28  4951.1  372.65  4965.9  370.50  4982.1  365.21  4992.5  358.81
  4997.6  357.86  5000.4  357.36  5003.6  357.86  5005.8  357.92  5013.2  364.06
  5033.9  362.87  5096.0  364.29  5115.3  364.30  5120.4  363.19  5168.5  364.85
  5191.6  364.31  5303.2  365.32  5520.7  374.60  5653.6  374.73  5966.3  382.96
#Mann=4,-1,0
  4550.9     0.1       0  4997.6    0.07       0  5003.6     0.1       0
  5191.6    0.05       0
Bank Sta=4997.6,5003.6
Exp/Cntr=0.3,0.1

Type RM Length L Ch R = 1,2783,518,518,518
BEGIN DESCRIPTION:
UNT012 IN BECR 3.0
END DESCRIPTION:
XS GIS Cut Line= 2
      3841134.47     10493717.73      3842290.79     10493900.03
#Sta/Elev= 30
  4371.3  390.39  4406.9  389.33  4427.1  386.73  4518.2  380.69  4545.6  377.47
  4550.7  377.99  4558.7  376.01  4568.9  375.63  4599.2  371.34  4613.1  367.91
  4629.6  366.06  4710.6  363.42  4751.1  361.01  4794.9  360.44  4833.7  359.67
  4943.4  358.47  4983.9  359.35  4990.0  354.79  4992.8  354.29  4996.0  354.79
  5004.2  355.34  5014.3  360.35  5065.6  367.26  5125.5  367.88  5253.1  371.10
  5383.1  372.93  5445.6  376.03  5469.8  375.55  5500.2  377.01  5541.9  377.28
#Mann=6,-1,0
  4371.3    0.16       0  4794.9     0.1       0  4833.7    0.16       0
  4990.0    0.07       0  4996.0    0.16       0  5125.5    0.05       0
Bank Sta=4990,4996
Exp/Cntr=0.3,0.1

Type RM Length L Ch R = 1,2265,562,562,562
BEGIN DESCRIPTION:
UNT012 IN BECR 2.0
END DESCRIPTION:
XS GIS Cut Line= 3
      3841299.64     10494010.22      3841599.61     10494260.19
      3841849.59     10494360.18
#Sta/Elev= 30
  4611.1  366.81  4618.2  365.46  4624.7  365.67  4639.0  362.94  4658.9  361.80
  4717.1  359.79  4838.2  359.07  4852.5  357.38  4873.3  357.35  4881.2  355.97
  4887.7  357.61  4895.5  356.90  4916.3  357.52  4937.1  356.10  4973.6  357.55
  4980.1  357.28  4987.9  355.06  4994.4  355.12  4995.3  354.07  4998.1  353.57
  5001.3  354.07  5011.0  356.23  5016.4  355.01  5023.1  356.89  5099.8  358.37
  5109.3  357.75  5124.1  359.22  5153.7  359.04  5177.9  360.12  5270.8  368.67
#Mann=4,-1,0
  4611.1    0.16       0  4658.9     0.1       0  4995.3    0.07       0
  5001.3     0.1       0
Bank Sta=4995.3,5001.3
Exp/Cntr=0.3,0.1

Type RM Length L Ch R = 1,1703,961,961,961
BEGIN DESCRIPTION:
Mapping XS 99fe74b4
END DESCRIPTION:
XS GIS Cut Line= 3
      3840952.19     10494071.89      3841301.16     10494504.19
      3841794.10     10494815.52
#Sta/Elev= 30
  4269.3  393.78  4330.9  388.70  4337.3  389.20  4351.7  386.96  4366.1  387.56
  4408.5  383.72  4430.1  383.28  4465.3  379.31  4479.6  379.21  4522.8  372.23
  4529.2  372.45  4537.0  370.63  4586.8  364.76  4601.2  364.81  4629.1  360.70
  4700.3  355.90  4806.9  355.44  4834.9  354.21  4922.0  355.67  4979.6  354.66
  5007.2  350.59  5009.9  350.09  5013.2  350.59  5016.1  353.60  5073.8  357.88
  5162.0  359.72  5219.6  362.84  5262.0  362.14  5371.4  365.02  5407.9  367.11
#Mann=4,-1,0
  4269.3    0.16       0  4629.1     0.1       0  5007.2    0.07       0
  5013.2     0.1       0
Bank Sta=5007.2,5013.2
Exp/Cntr=0.3,0.1

Type RM Length L Ch R = 1,742,0,0,0
BEGIN DESCRIPTION:
UNT012 IN BECR 1.0
END DESCRIPTION:
XS GIS Cut Line= 4
      3840764.70     10494238.58      3840785.53     10494858.36
      3840910.53     10494941.69      3841410.58     10494858.35
#Sta/Elev= 30
  4658.0  394.74  4679.6  394.73  4709.6  393.01  4769.7  394.28  4829.7  390.25
  4889.7  383.37  4929.8  376.64  4948.9  370.43  4953.9  372.50  4959.8  366.38
  4969.8  362.47  4979.8  354.24  4989.8  350.91  4996.8  347.30  4999.6  346.80
  5002.8  347.30  5009.8  352.10  5019.8  353.14  5077.8  352.75  5119.9  351.07
  5310.8  350.57  5397.9  351.72  5412.9  351.05  5465.4  351.83  5478.1  353.11
  5518.7  353.40  5569.4  355.42  5830.4  358.02  5843.1  357.40  5935.3  359.62
#Mann=4,-1,0
  4658.0    0.16       0  4996.8    0.07       0  5002.8    0.16       0
  5077.8     0.1       0
Bank Sta=4996.8,5002.8
Exp/Cntr=0.3,0.1

Chan Stop Cuts=-1