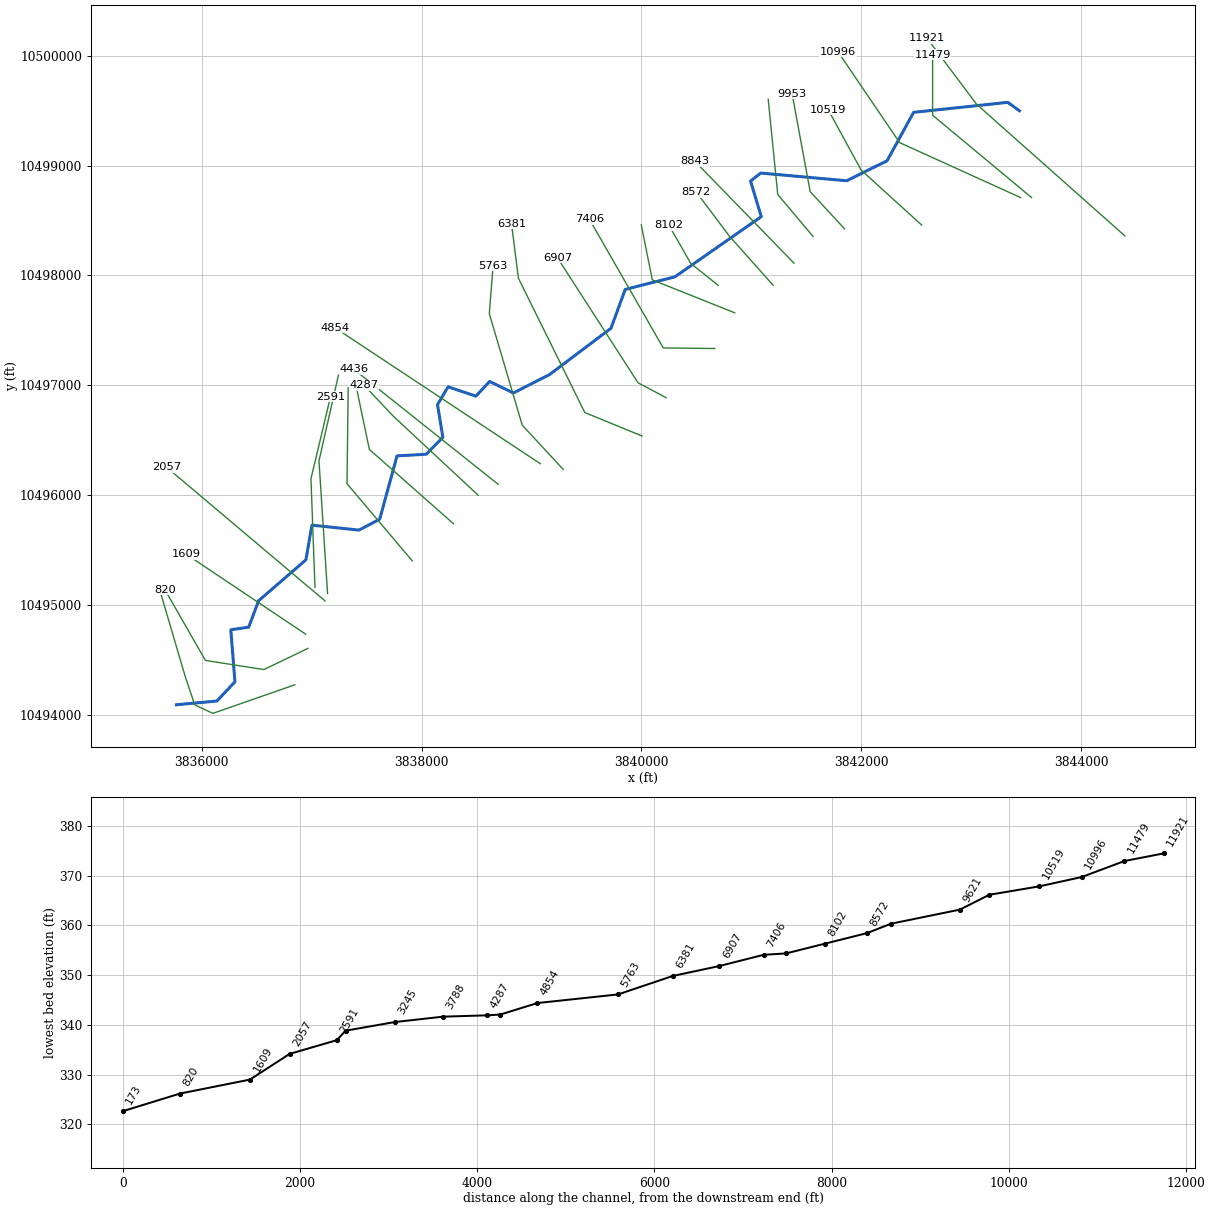
--- UNT014 IN BECR.prj (project) ---

Proj Title=UNT014 IN BECR Base Level Engineering
Current Plan=p01
Default Exp/Contr=0.3,0.1
English Units
Geom File=g01
Flow File=f01
Plan File=p01
Y Axis Title=Elevation
X Axis Title(PF)=Main Channel Distance
X Axis Title(XS)=Station
BEGIN DESCRIPTION:
UNT014 IN BECR
END DESCRIPTION:
DSS Export Rating Curves= 0
DSS Export Rating Curve Sorted= 0
DSS Export Volume Flow Curves= 0
DXF OffsetX= 0
DXF OffsetY= 0
DXF ScaleX= 1
DXF ScaleY= 10

--- UNT014 IN BECR.p01 (plan) ---

Plan Title=Multiple Run
Short Identifier=Multiple
Geom File=g01
Flow File=f01
Subcritical Flow
K Sum by GR= 0
Std Step Tol= 0.01
Critical Tol= 0.01
Num of Std Step Trials= 20
Max Error Tol= 0.3
Flow Tol Ratio= 0.001
Split Flow NTrial= 30
Split Flow Tol= 0.02
Split Flow Ratio= 0.02
Log Output Level= 0
Friction Slope Method= 1
Unsteady Friction Slope Method= 2
Unsteady Bridges Friction Slope Method= 1
Parabolic Critical Depth
Global Vel Dist=  1 , 1 , 1
Global Log Level= 0
CheckData=True
Encroach Param= -1, 0, 0, 0
BEGIN DESCRIPTION:
Multiple Run
END DESCRIPTION:

--- UNT014 IN BECR.f01 (steady flow) ---

Flow Title=Multiple
Program Version=4.10
Number of Profiles= 7
Profile Names=10-year,25-year,50-year,1pct_min,100-year,1pct_plu,500-year
River Rch & RM=UNT014 IN BECR,Reach-1         ,11921
     430     561     666     581     785    1062    1095
River Rch & RM=UNT014 IN BECR,Reach-1         ,8843
     649     868    1045     923    1249    1689    1790
Boundary for River Rch & Prof#=UNT014 IN BECR,Reach-1         , 1
Up Type= 0
Dn Type= 3
Dn Slope=0.0058
Boundary for River Rch & Prof#=UNT014 IN BECR,Reach-1         , 2
Up Type= 0
Dn Type= 3
Dn Slope=0.0058
Boundary for River Rch & Prof#=UNT014 IN BECR,Reach-1         , 3
Up Type= 0
Dn Type= 3
Dn Slope=0.0058
Boundary for River Rch & Prof#=UNT014 IN BECR,Reach-1         , 4
Up Type= 0
Dn Type= 3
Dn Slope=0.0058
Boundary for River Rch & Prof#=UNT014 IN BECR,Reach-1         , 5
Up Type= 0
Dn Type= 3
Dn Slope=0.0058
Boundary for River Rch & Prof#=UNT014 IN BECR,Reach-1         , 6
Up Type= 0
Dn Type= 3
Dn Slope=0.0058
Boundary for River Rch & Prof#=UNT014 IN BECR,Reach-1         , 7
Up Type= 0
Dn Type= 3
Dn Slope=0.0058
DSS Import GetInterval= 0
DSS Import GetPeak= 0
DSS Import FillOption= 0

--- UNT014 IN BECR.g01 (geometry) ---

Geom Title=Existing Conditions
Program Version=4.10

River Reach=UNT014 IN BECR  ,Reach-1
Reach XY= 30
      3843440.07     10499500.17       3843333.5       10499577.
      3842476.75       10499486.       3842235.5       10499045.
       3841868.5       10498863.      3841086.25       10498933.
       3840993.5       10498860.        3841091.       10498536.
      3840305.75       10497988.      3839853.25       10497873.
      3839723.75       10497519.      3839165.25       10497098.
       3838835.5       10496930.       3838619.5       10497035.
      3838494.75       10496901.        3838242.       10496986.
       3838145.5       10496824.      3838194.25       10496527.
      3838043.75       10496372.       3837777.5       10496357.
       3837619.5       10495780.      3837430.75       10495681.
        3837003.       10495726.      3836948.25       10495410.
       3836517.5       10495037.      3836428.25       10494797.
        3836265.       10494773.      3836302.75       10494299.
      3836138.25       10494124.       3835769.5       10494090.

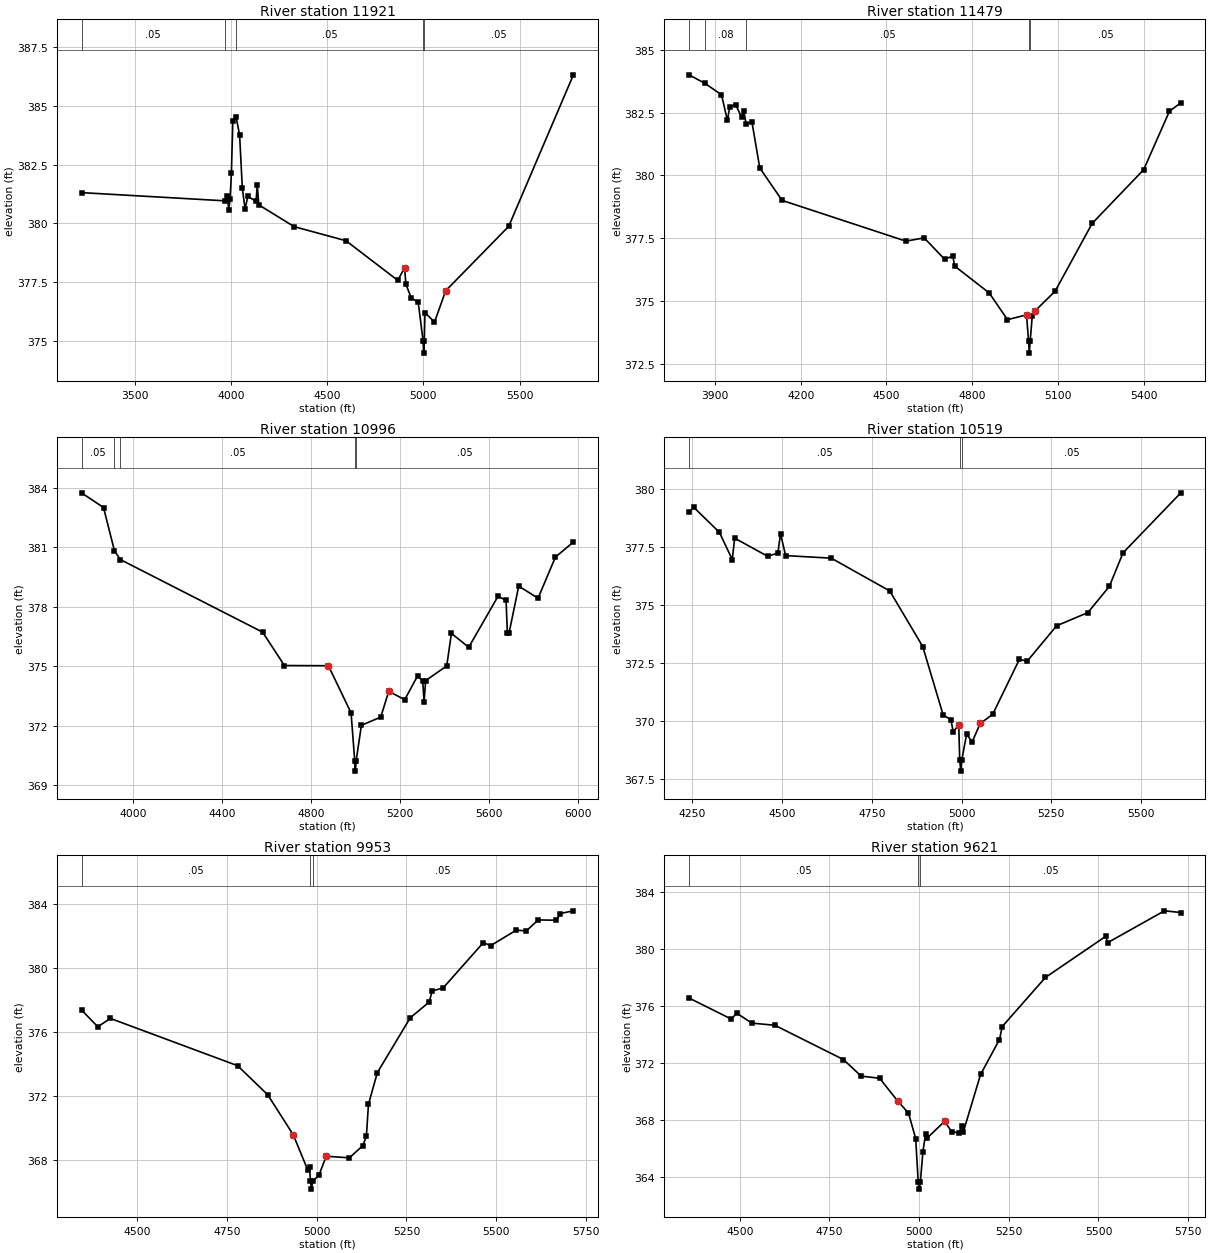
Type RM Length L Ch R = 1 ,11921   ,442,442,442
BEGIN DESCRIPTION:
UNT014 IN BECR 25.0
END DESCRIPTION:
XS GIS Cut Line= 3
      3844399.59      10498360.2      3843049.61     10499560.19
      3842599.62     10500160.18
#Sta/Elev= 30
  3223.2  381.31  3969.3  380.96  3981.2  381.18  3987.9  380.59  3995.4  381.03
  4002.1  382.15  4009.6  384.38  4026.5  384.54  4044.8  383.76    4059  381.49
  4073.2  380.61  4087.4  381.15  4130.1  380.94  4136.7  381.63  4144.3  380.79
  4328.2  379.86  4597.5  379.26  4866.8  377.57  4901.9  378.11    4909   377.4
    4937  376.82    4973  376.64  4998.4  374.97  5001.2  374.47  5004.4  374.97
  5008.1   376.2  5057.5  375.79  5115.9  377.13    5443  379.87  5779.4  386.33
#Mann= 5 ,-1 , 0
  3223.2     .05       0  3969.3     .08       0  4026.5     .05       0
  4998.4     .03       0  5004.4     .05       0
Bank Sta=4901.9,5115.9
XS Rating Curve= 0 ,0
Exp/Cntr=0.3,0.1

Type RM Length L Ch R = 1 ,11479   ,483,483,483
BEGIN DESCRIPTION:
UNT014 IN BECR 24.0
END DESCRIPTION:
XS GIS Cut Line= 3
      3843549.57     10498710.22      3842649.61     10499460.19
      3842649.61      10500010.2
#Sta/Elev= 30
  3808.7     384  3863.3  383.67  3922.6  383.21  3943.4  382.19  3951.2  382.71
    3972  382.82  3992.8  382.32  4000.7  382.57  4008.9  382.04  4029.3  382.12
  4056.6   380.3  4134.7  379.01  4568.2  377.39    4632  377.52  4703.6  376.67
  4732.2   376.8  4738.7   376.4  4859.8  375.33  4923.6  374.27  4990.2  374.46
  4997.2  373.44  4999.9  372.94  5003.2  373.44  5010.2  374.41  5020.2  374.62
  5090.2   375.4  5220.2   378.1  5400.2  380.23  5490.2  382.55  5530.2  382.89
#Mann= 5 ,-1 , 0
  3808.7     .05       0  3863.3     .08       0  4008.9     .05       0
  4997.2     .03       0  5003.2     .05       0
Bank Sta=4990.2,5020.2
XS Rating Curve= 0 ,0
Exp/Cntr=0.3,0.1

Type RM Length L Ch R = 1 ,10996   ,477,477,477
BEGIN DESCRIPTION:
UNT014 IN BECR 23.0
END DESCRIPTION:
XS GIS Cut Line= 3
      3843449.65     10498710.17      3842349.61     10499210.19
       3841787.7     10500039.87
#Sta/Elev= 30
  3768.5  383.74  3867.4     383  3916.3  380.83  3942.7  380.38  4582.5  376.72
  4680.3  375.04    4878  375.03  4979.9  372.65  4996.3  370.22    4999  369.72
  5002.3  370.22  5026.3  372.03  5113.2  372.44  5149.1  373.74    5221  373.32
  5278.8  374.52  5301.8  374.26  5307.9   373.2    5315  374.28  5409.7  375.02
  5430.7  376.66  5508.6  375.96  5640.3  378.53  5676.3  378.32  5682.3  376.68
  5689.4  376.66  5733.2  379.04  5820.1  378.43    5898   380.5  5978.9  381.26
#Mann= 5 ,-1 , 0
  3768.5     .05       0  3916.3     .08       0  3942.7     .05       0
  4996.3     .03       0  5002.3     .05       0
Bank Sta=4878,5149.1
XS Rating Curve= 0 ,0
Exp/Cntr=0.3,0.1

Type RM Length L Ch R = 1 ,10519   ,566,566,566
BEGIN DESCRIPTION:
UNT014 IN BECR 22.0
END DESCRIPTION:
XS GIS Cut Line= 3
      3842549.64     10498460.16      3841999.61     10498960.19
      3841699.59     10499510.23
#Sta/Elev= 30
  4240.9     379  4254.8  379.19  4325.8  378.12  4361.6  376.95  4368.3  377.87
  4460.2  377.09  4488.6  377.23    4496  378.06  4510.2  377.12  4637.3  377.01
  4800.1   375.6    4892  373.21  4948.8  370.27  4970.4  370.06  4977.2  369.53
  4992.3  369.85    4995  368.35  4997.8  367.85    5001  368.35  5014.2  369.43
  5029.8  369.11  5052.1   369.9  5086.8  370.29  5161.3  372.66  5183.1  372.58
  5264.8   374.1  5352.1  374.67  5411.9   375.8  5449.9  377.24  5610.8  379.82
#Mann= 3 ,-1 , 0
  4240.9     .05       0    4995     .03       0    5001     .05       0
Bank Sta=4992.3,5052.1
XS Rating Curve= 0 ,0
Exp/Cntr=0.3,0.1

Type RM Length L Ch R = 1 ,9953    ,332,332,332
BEGIN DESCRIPTION:
UNT014 IN BECR 21.0
END DESCRIPTION:
XS GIS Cut Line= 3
      3841848.45      10498425.3      3841535.97     10498763.82
      3841371.29     10499656.56
#Sta/Elev= 30
  4346.1  377.37  4391.4  376.32  4426.5  376.84  4780.4  373.88  4864.1  372.06
  4935.3  369.55  4975.3  367.36  4980.4  367.56  4983.1  366.65  4985.9  366.15
  4989.1  366.65  5006.5  367.01  5026.8  368.21  5091.4  368.11  5128.5  368.87
  5138.7  369.46  5144.4  371.46  5169.2  373.45  5260.7  376.88  5313.5  377.87
  5321.7  378.56  5352.2  378.75  5464.1  381.59  5484.4   381.4  5555.6  382.37
  5583.5  382.32  5616.6  383.01  5667.4  382.99  5677.6  383.41  5714.6  383.58
#Mann= 3 ,-1 , 0
  4346.1     .05       0  4983.1     .03       0  4989.1     .05       0
Bank Sta=4935.3,5026.8
XS Rating Curve= 0 ,0
Exp/Cntr=0.3,0.1

Type RM Length L Ch R = 1 ,9621    ,778,778,778
BEGIN DESCRIPTION:
UNT014 IN BECR 20.0
END DESCRIPTION:
XS GIS Cut Line= 3
      3841561.99     10498355.86      3841240.83     10498737.78
      3841154.05     10499605.55
#Sta/Elev= 30
  4358.4  376.55  4476.9  375.07  4491.2  375.49  4533.9  374.79  4597.8  374.64
    4789  372.24  4838.5  371.08    4890  370.93  4940.2  369.34  4970.4  368.49
  4990.5  366.71  4997.5  363.67  5000.3  363.17  5003.5  363.67  5010.6  365.79
    5018  367.03    5023  366.76  5070.9  367.91    5091  367.19  5111.1  367.11
  5118.5  367.57  5123.5   367.2  5171.4   371.2    5224  373.64  5231.7  374.55
  5352.3  377.99  5520.5  380.87  5525.5  380.42  5683.9  382.65  5729.5  382.53
#Mann= 3 ,-1 , 0
  4358.4     .05       0  4997.5     .03       0  5003.5     .05       0
Bank Sta=4940.2,5070.9
XS Rating Curve= 0 ,0
Exp/Cntr=0.3,0.1

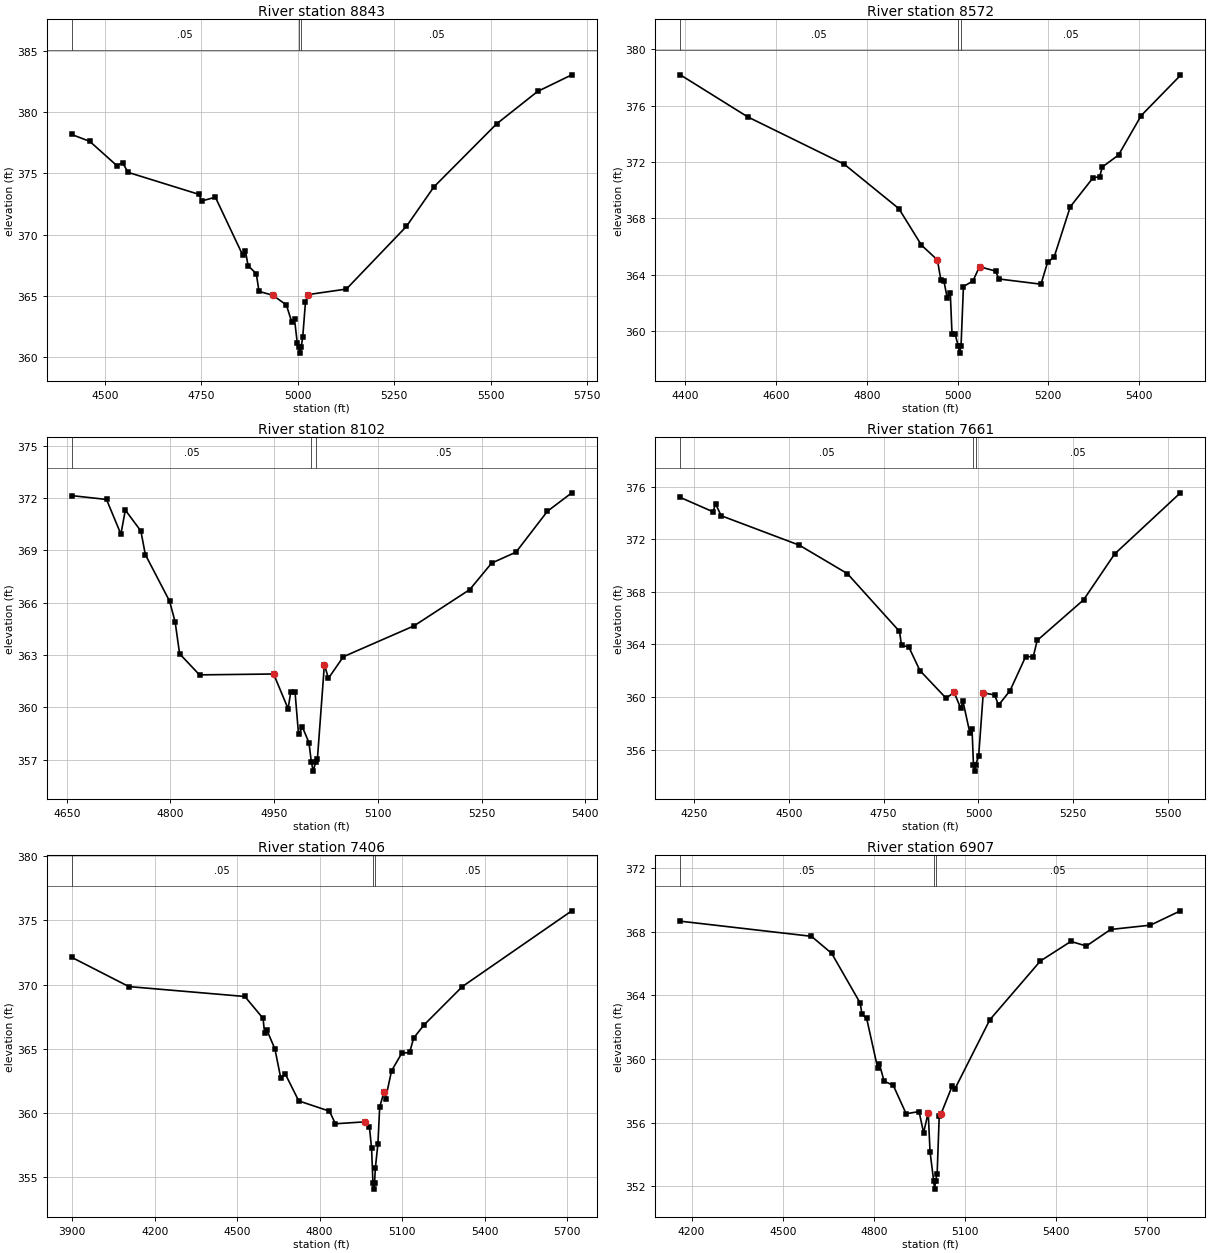
Type RM Length L Ch R = 1 ,8843    ,271,271,271
BEGIN DESCRIPTION:
UNT014 IN BECR 19.0
END DESCRIPTION:
XS GIS Cut Line= 2
       3841388.4     10498112.78       3840485.6     10499041.62
#Sta/Elev= 30
  4414.4  378.18  4461.2  377.62    4532  375.62  4546.1  375.89  4560.3  375.09
  4744.2  373.29  4751.1  372.75  4786.6  373.06  4857.1  368.35  4864.3   368.7
  4871.3  367.47  4892.6  366.81  4899.6  365.37    4935  365.06  4970.3  364.27
  4984.5  362.87  4991.6  363.08  4998.6  361.19  5002.8  360.83  5005.5  360.33
  5008.8  360.83  5012.8  361.62  5019.9  364.49  5026.9  365.11  5125.9  365.56
  5281.5  370.68  5352.3  373.89  5514.8  379.04    5621  381.69  5709.7  383.05
#Mann= 3 ,-1 , 0
  4414.4     .05       0  5002.8     .03       0  5008.8     .05       0
Bank Sta=4935,5026.9
XS Rating Curve= 0 ,0
Exp/Cntr=0.3,0.1

Type RM Length L Ch R = 1 ,8572    ,470,470,470
BEGIN DESCRIPTION:
UNT014 IN BECR 18.0
END DESCRIPTION:
XS GIS Cut Line= 3
      3841199.59     10497910.21      3840799.61     10498360.19
      3840499.64     10498760.15
#Sta/Elev= 30
  4389.1  378.18  4537.5   375.2  4750.3  371.84  4870.7  368.69  4920.5   366.1
  4955.6  365.05  4963.1  363.66  4969.8  363.58  4977.3  362.35    4984  362.72
  4987.8  359.82  4994.3  359.82  5001.7  358.94  5004.4  358.44  5007.7  358.94
    5013  363.16  5033.9  363.56  5048.4  364.57  5083.9  364.26  5091.1   363.7
  5183.9  363.33  5198.4  364.88    5213  365.27  5248.4  368.82  5298.4  370.87
    5313  370.96  5319.3  371.65  5354.7  372.49  5404.7  375.29  5491.1  378.14
#Mann= 3 ,-1 , 0
  4389.1     .05       0  5001.7     .03       0  5007.7     .05       0
Bank Sta=4955.6,5048.4
XS Rating Curve= 0 ,0
Exp/Cntr=0.3,0.1

Type RM Length L Ch R = 1 ,8102    ,441,441,441
BEGIN DESCRIPTION:
UNT014 IN BECR 17.0
END DESCRIPTION:
XS GIS Cut Line= 3
      3840699.61     10497910.19      3840449.61     10498110.19
       3840249.6     10498460.21
#Sta/Elev= 30
  4657.1  372.14  4707.5  371.92  4728.3  369.93  4734.7  371.31  4757.2  370.11
  4763.6  368.76  4798.8  366.08  4806.8  364.88  4813.2  363.07    4842  361.86
  4949.2  361.91  4970.1  359.92  4974.1   360.9  4980.1   360.9  4985.2  358.46
  4990.9  358.86  5000.3  357.97  5003.8  356.84  5006.5  356.34  5009.8  356.84
  5012.5  357.04  5022.6  362.45  5028.4  361.66    5050   362.9  5152.2  364.67
  5232.8  366.75  5264.5  368.27  5299.8   368.9  5345.1  371.24  5380.4   372.3
#Mann= 3 ,-1 , 0
  4657.1     .05       0  5003.8     .03       0  5009.8     .05       0
Bank Sta=4949.2,5022.6
XS Rating Curve= 0 ,0
Exp/Cntr=0.3,0.1

Type RM Length L Ch R = 1 ,7661    ,255,255,255
BEGIN DESCRIPTION:
UNT014 IN BECR 16.0
END DESCRIPTION:
XS GIS Cut Line= 3
      3840849.59     10497660.19      3840099.61     10497960.19
       3839999.6     10498460.23
#Sta/Elev= 30
  4214.4  375.17  4300.5  374.08  4307.3  374.68  4322.1  373.78  4528.1  371.54
  4654.6  369.38  4791.9  364.99  4797.3  363.92  4816.2  363.82  4845.8  362.01
  4914.5  359.92    4936  360.35  4953.5  359.13  4958.9  359.71  4977.7  357.23
  4983.1  357.56  4986.8  354.87  4989.6  354.37  4992.8  354.87  5000.6  355.55
  5012.7  360.32  5042.6  360.16  5052.8  359.38  5083.3  360.49  5124.1  363.06
  5144.5  363.07  5154.7   364.3  5277.1  367.39  5358.7  370.87  5532.1  375.52
#Mann= 3 ,-1 , 0
  4214.4     .05       0  4986.8     .03       0  4992.8     .05       0
Bank Sta=4936,5012.7
XS Rating Curve= 0 ,0
Exp/Cntr=0.3,0.1

Type RM Length L Ch R = 1 ,7406    ,499,499,499
BEGIN DESCRIPTION:
UNT014 IN BECR 15.0
END DESCRIPTION:
XS GIS Cut Line= 3
      3840667.91     10497335.01      3840199.16     10497340.21
      3839527.28      10498512.1
#Sta/Elev= 30
  3897.8  372.13  4106.1  369.85  4527.9  369.08  4594.1  367.38  4599.9   366.2
  4608.6  366.44  4637.3  364.99  4658.8   362.7  4674.7  363.06  4723.9  360.95
  4835.8  360.15  4857.3  359.17  4965.9  359.32  4981.1  358.93    4989  357.25
  4993.9  354.58  4996.6  354.08  4999.9  354.58  5002.6   355.7  5012.1  357.62
  5018.5  360.48  5034.3  361.65    5040  361.13  5061.6  363.29    5099  364.67
  5127.3  364.72  5142.2  365.85  5179.6  366.86  5319.1  369.85  5717.4  375.75
#Mann= 3 ,-1 , 0
  3897.8     .05       0  4993.9     .03       0  4999.9     .05       0
Bank Sta=4965.9,5034.3
XS Rating Curve= 0 ,0
Exp/Cntr=0.3,0.1

Type RM Length L Ch R = 1 ,6907    ,526,526,526
BEGIN DESCRIPTION:
UNT014 IN BECR 14.0
END DESCRIPTION:
XS GIS Cut Line= 3
      3840225.17     10496887.11      3839969.99     10497022.51
       3839235.6     10498163.16
#Sta/Elev= 30
    4163  368.65  4594.5   367.7  4661.1  366.63  4754.9  363.51  4760.8  362.81
    4776  362.56  4812.3  359.44  4818.3  359.67  4833.5  358.61  4863.8  358.34
  4906.1  356.56  4948.6   356.7  4963.5  355.37  4978.7  356.63  4984.7  354.18
  4996.8  352.33  4999.6  351.83  5002.8  352.33  5008.1   352.8    5015  356.44
    5021  356.56  5057.3  358.29  5066.5  358.12  5181.4  362.46  5347.8  366.15
  5448.2  367.38    5499  367.09    5579  368.13  5709.8   368.4  5808.5   369.3
#Mann= 3 ,-1 , 0
    4163     .05       0  4996.8     .03       0  5002.8     .05       0
Bank Sta=4978.7,5021
XS Rating Curve= 0 ,0
Exp/Cntr=0.3,0.1

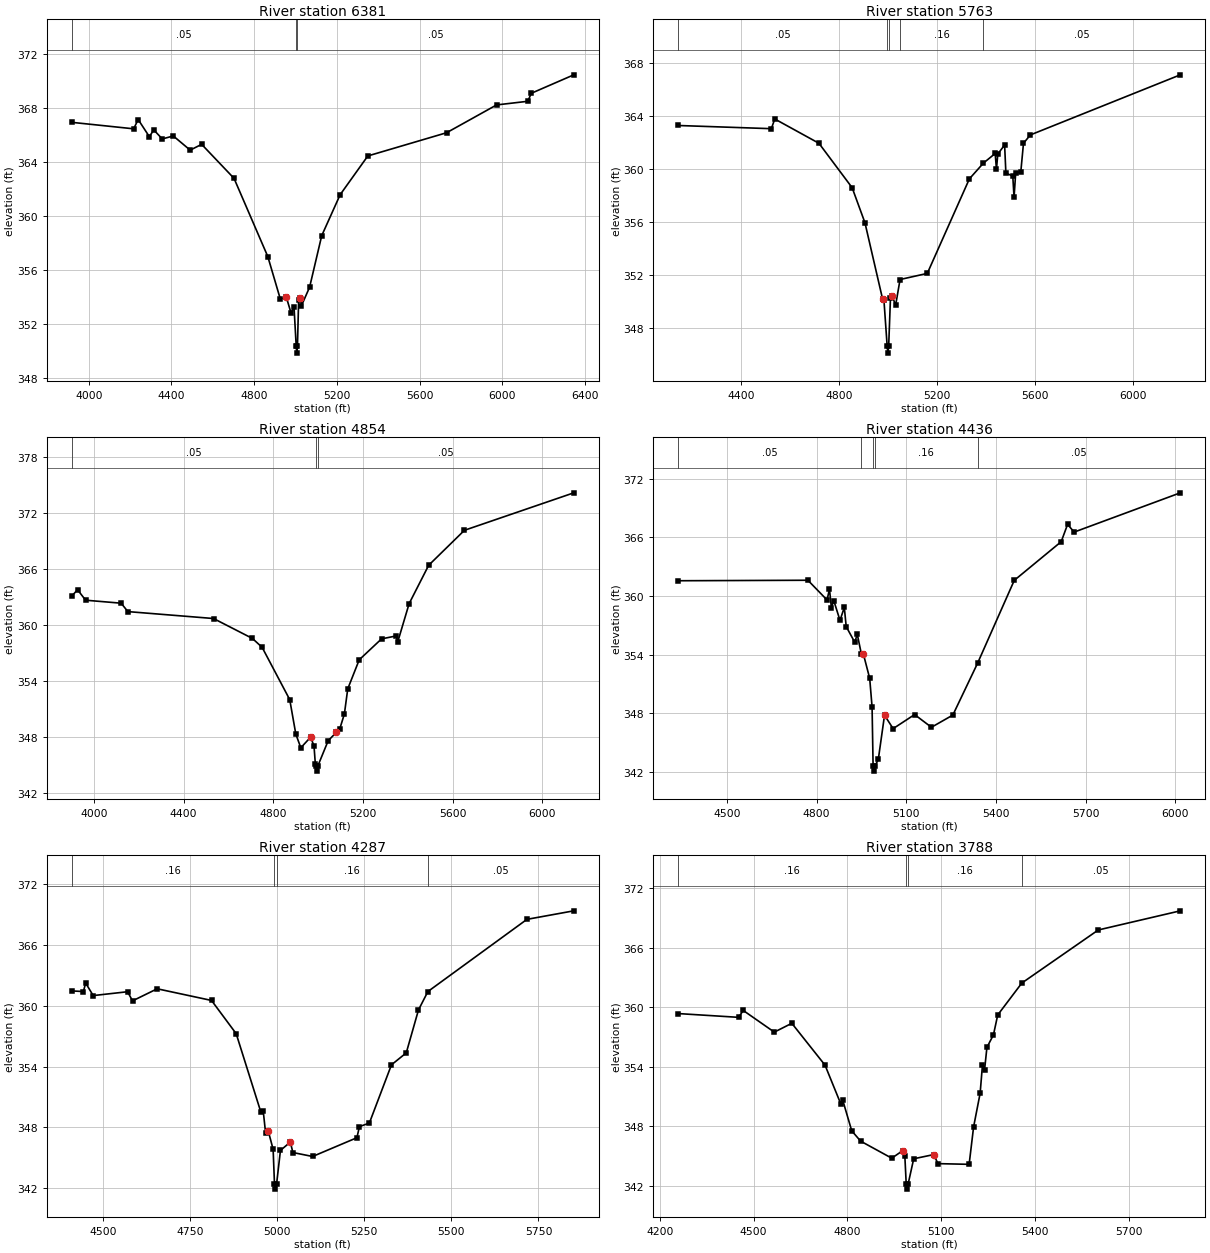
Type RM Length L Ch R = 1 ,6381    ,618,618,618
BEGIN DESCRIPTION:
UNT014 IN BECR 13.0
END DESCRIPTION:
XS GIS Cut Line= 4
      3840006.49     10496538.12      3839485.62     10496751.67
      3838881.45     10497975.63      3838818.96      10498470.4
#Sta/Elev= 30
  3918.2  366.93  4217.4  366.45  4239.1  367.14  4293.1  365.87  4314.7  366.37
  4355.6   365.7    4409  365.92  4490.6  364.87    4546   365.3  4702.5  362.78
  4865.9  356.98  4925.6  353.87  4955.7  353.96  4978.1   352.8  4992.5  353.24
  5003.1  350.33  5005.9  349.83  5009.1  350.33  5014.8  353.77    5023  353.92
  5028.6  353.35  5067.9  354.72  5126.3  358.53  5215.5  361.57  5349.3  364.44
    5730  366.16  5971.6  368.22  6122.8  368.49    6139  369.08  6344.8  370.45
#Mann= 3 ,-1 , 0
  3918.2     .05       0  5003.1     .03       0  5009.1     .05       0
Bank Sta=4955.7,5023
XS Rating Curve= 0 ,0
Exp/Cntr=0.3,0.1

Type RM Length L Ch R = 1 ,5763    ,909,909,909
BEGIN DESCRIPTION:
UNT014 IN BECR 12.0
END DESCRIPTION:
XS GIS Cut Line= 4
      3839289.47     10496233.41      3838916.18     10496637.09
       3838616.7     10497652.71      3838651.42     10498091.06
#Sta/Elev= 30
  4144.5  363.28  4524.1  363.04  4538.3  363.77  4718.4  361.94  4853.9  358.59
  4906.1  355.95  4978.3  350.18  4983.5  350.14  4996.9  346.62  4999.6  346.12
  5002.9  346.62  5010.3   350.3  5016.8  350.46  5031.2  349.72  5049.4  351.67
  5160.5  352.13  5332.3  359.26  5389.8  360.45  5437.5  361.17  5442.7  359.99
  5448.2  361.13    5476  361.81  5481.2  359.69  5509.3  359.47  5514.5  357.86
  5521.2  359.71    5542  359.78    5553  361.94  5581.1  362.57  6192.9   367.1
#Mann= 5 ,-1 , 0
  4144.5     .05       0  4996.9     .03       0  5002.9     .05       0
  5049.4     .16       0  5389.8     .05       0
Bank Sta=4978.3,5016.8
XS Rating Curve= 0 ,0
Exp/Cntr=0.3,0.1

Type RM Length L Ch R = 1 ,4854    ,418,418,418
BEGIN DESCRIPTION:
UNT014 IN BECR 11.0
END DESCRIPTION:
XS GIS Cut Line= 2
      3839081.13     10496285.51      3837214.76     10497522.52
#Sta/Elev= 30
  3901.1  363.12  3926.9   363.8  3962.9  362.68  4121.3  362.36  4151.4  361.46
  4533.4  360.72  4706.7  358.59    4750  357.64  4873.3  352.04  4900.4  348.35
  4922.7  346.89  4966.6  348.03  4981.6  347.06  4987.6   345.1  4991.7  344.89
  4994.4  344.39  4997.7  344.89  5044.8  347.65  5080.9  348.53  5095.9  348.87
    5117  350.51    5132  353.19  5183.1   356.3  5282.6  358.54  5348.6  358.86
  5354.6  358.19  5405.7  362.31    5493  366.42  5652.4  370.16  6140.2  374.17
#Mann= 3 ,-1 , 0
  3901.1     .05       0  4991.7     .03       0  4997.7     .05       0
Bank Sta=4966.6,5080.9
XS Rating Curve= 0 ,0
Exp/Cntr=0.3,0.1

Type RM Length L Ch R = 1 ,4436    ,149,149,149
BEGIN DESCRIPTION:
UNT014 IN BECR 10.0
END DESCRIPTION:
XS GIS Cut Line= 2
      3838697.43     10496098.02      3837384.91     10497144.91
#Sta/Elev= 30
  4337.7  361.57  4771.2  361.62  4835.2   359.6  4843.3  360.71  4849.7  358.82
  4857.7  359.54  4878.5  357.51  4892.9  358.84  4899.3  356.87  4928.1  355.26
  4936.1  356.11  4950.2  354.04  4956.9  354.04  4977.8  351.58  4985.8  348.64
  4989.2  342.58  4991.9  342.08  4995.2  342.58  5006.6  343.28  5027.4   347.8
  5056.2  346.43    5128  347.87  5184.3  346.57  5255.9  347.82  5338.5  353.12
  5461.3  361.61  5618.3  365.57  5639.6  367.34  5661.5  366.55  6016.6  370.57
#Mann= 5 ,-1 , 0
  4337.7     .05       0  4950.2     .16       0  4989.2     .07       0
  4995.2     .16       0  5338.5     .05       0
Bank Sta=4956.9,5027.4
XS Rating Curve= 0 ,0
Exp/Cntr=0.3,0.1

Type RM Length L Ch R = 1 ,4287    ,499,499,499
BEGIN DESCRIPTION:
UNT014 IN BECR 9.0
END DESCRIPTION:
XS GIS Cut Line= 3
      3838515.14     10495999.06       3837744.3     10496717.82
      3837478.68     10496999.06
#Sta/Elev= 30
  4410.6  361.47  4443.8  361.41  4450.6  362.24  4472.1  361.01  4570.8  361.39
    4585  360.49  4655.8  361.68  4811.7  360.53  4882.5  357.25  4952.9  349.56
  4960.2  349.59    4967  347.41  4974.4  347.67  4988.5  345.84  4992.4  342.42
  4995.1  341.92  4998.4  342.42  5009.5  345.74  5037.9  346.56  5045.2  345.53
  5101.8  345.14  5228.9  346.99  5236.2  348.09  5264.6  348.43  5328.1  354.18
  5370.6  355.36  5405.7   359.6  5432.7  361.41    5717  368.53  5851.4  369.37
#Mann= 4 ,-1 , 0
  4410.6     .16       0  4992.4     .07       0  4998.4     .16       0
  5432.7     .05       0
Bank Sta=4974.4,5037.9
XS Rating Curve= 0 ,0
Exp/Cntr=0.3,0.1

Type RM Length L Ch R = 1 ,3788    ,543,543,543
BEGIN DESCRIPTION:
UNT014 IN BECR 8.0
END DESCRIPTION:
XS GIS Cut Line= 3
      3838291.15     10495738.67      3837525.55     10496415.73
      3837406.12     10496986.94
#Sta/Elev= 30
  4259.3  359.35  4452.6  358.97  4466.8  359.67  4566.4  357.48  4622.4  358.37
  4728.6  354.15  4778.8  350.26  4785.5  350.59    4814  347.53  4842.4  346.49
    4942  344.77  4977.1  345.53  4983.8  345.03  4988.3  342.15  4991.1  341.65
  4994.3  342.15  5012.2  344.71  5075.8  345.13    5090  344.22  5189.5  344.15
  5203.8  347.93  5224.7  351.32  5232.2  354.19  5238.9  353.69  5246.4  355.94
  5267.3  357.21  5280.9  359.21  5358.1  362.43  5602.6  367.78  5864.9  369.71
#Mann= 4 ,-1 , 0
  4259.3     .16       0  4988.3     .07       0  4994.3     .16       0
  5358.1     .05       0
Bank Sta=4977.1,5075.8
XS Rating Curve= 0 ,0
Exp/Cntr=0.3,0.1

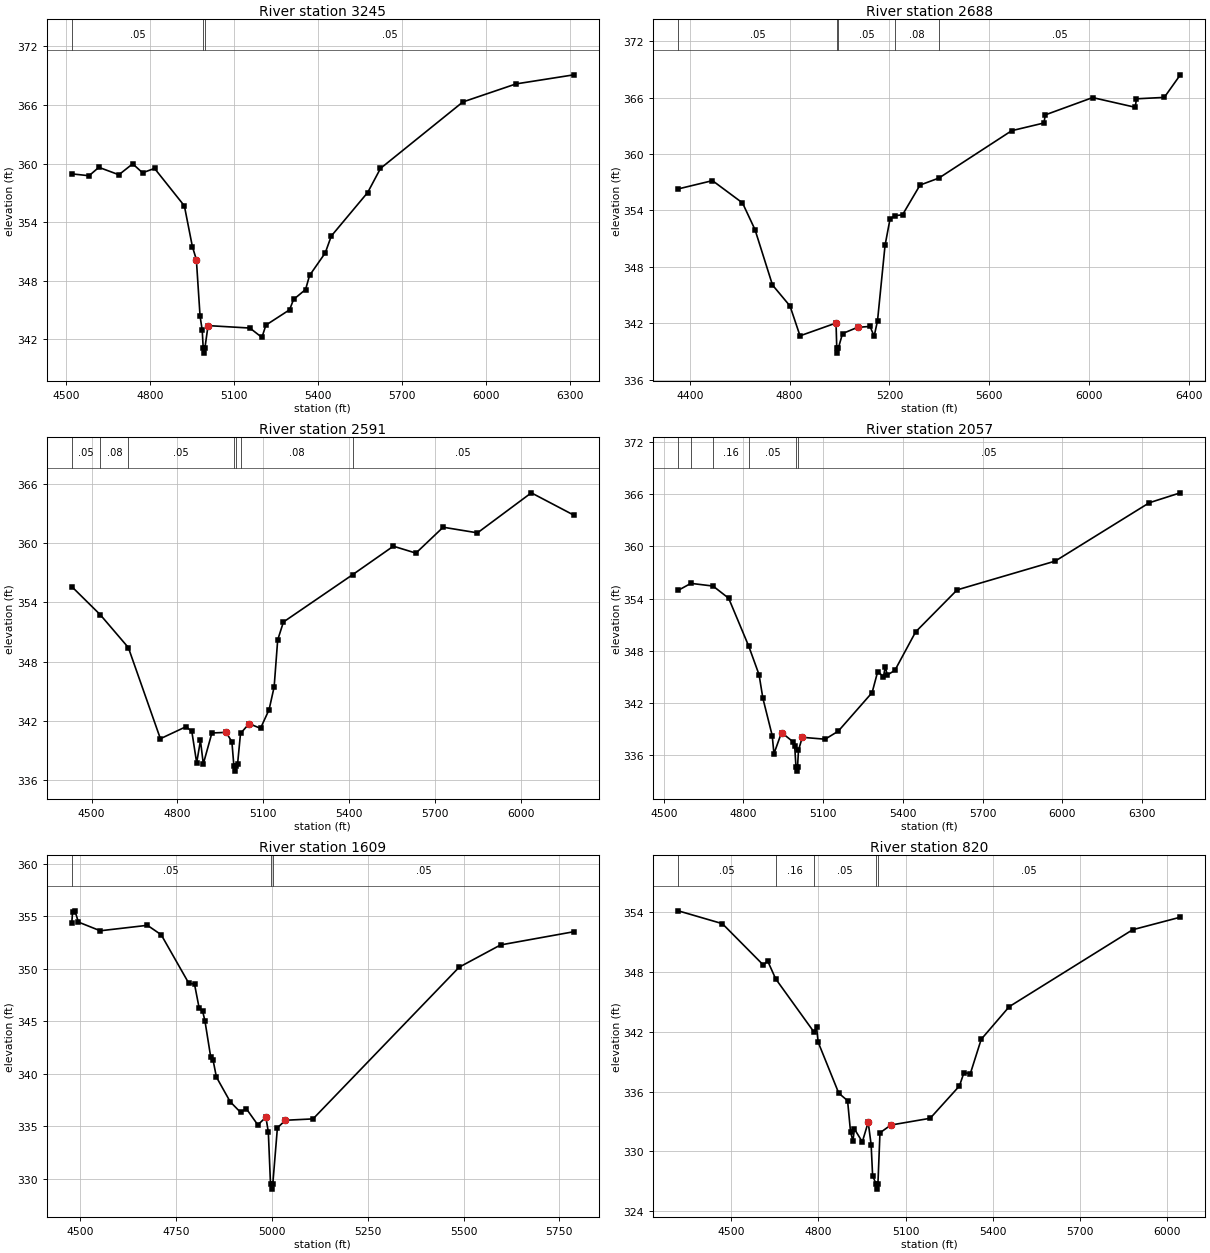
Type RM Length L Ch R = 1 ,3245    ,557,557,557
BEGIN DESCRIPTION:
UNT014 IN BECR 7.0
END DESCRIPTION:
XS GIS Cut Line= 3
      3837916.17     10495400.12      3837322.43     10496103.23
      3837332.82      10496976.7
#Sta/Elev= 30
  4519.4  358.94  4581.1  358.75  4616.2  359.61  4687.7  358.85  4737.1  359.97
  4772.3  359.05  4815.1   359.5  4921.7  355.66  4950.3  351.49  4964.5  350.16
  4977.7  344.38  4985.5   342.9    4989  341.07  4991.8  340.57    4995  341.07
  5006.3  343.39  5155.8  343.14  5198.7  342.18    5213  343.44  5297.5  345.01
  5311.8  346.07  5354.7  347.09    5369  348.53    5425  350.84  5446.6  352.57
  5576.6  357.03  5622.4   359.5  5916.7  366.31  6106.7  368.16  6313.2  369.09
#Mann= 3 ,-1 , 0
  4519.4     .05       0    4989     .03       0    4995     .05       0
Bank Sta=4964.5,5006.3
XS Rating Curve= 0 ,0
Exp/Cntr=0.3,0.1

Type RM Length L Ch R = 1 ,2688    ,97,97,97
BEGIN DESCRIPTION:
UNT014 IN BECR 6.0
END DESCRIPTION:
XS GIS Cut Line= 3
      3837145.34     10495103.23      3837067.22     10496311.57
      3837244.29     10497092.79
#Sta/Elev= 30
  4353.9  356.29  4491.1  357.17  4611.4   354.8  4661.5  351.96  4731.6  346.07
  4801.8  343.84  4841.9  340.67  4986.2  342.03  4989.2  339.33  4991.9  338.83
  4995.2  339.33  5012.2  340.91  5072.4  341.57  5122.5  341.67  5138.9  340.62
  5152.5  342.28  5182.6  350.29  5202.6  353.09  5221.5  353.44  5252.7  353.54
  5322.9   356.7  5398.2  357.44  5690.1  362.48  5819.5   363.3  5824.6  364.16
  6014.5     366    6185  364.97  6190.1  365.87  6301.6  366.02  6365.8  368.42
#Mann= 5 ,-1 , 0
  4353.9     .05       0  4989.2     .03       0  4995.2     .05       0
  5221.5     .08       0  5398.2     .05       0
Bank Sta=4986.2,5072.4
XS Rating Curve= 0 ,0
Exp/Cntr=0.3,0.1

Type RM Length L Ch R = 1 ,2591    ,534,534,534
BEGIN DESCRIPTION:
UNT014 IN BECR 5.0
END DESCRIPTION:
XS GIS Cut Line= 4
      3837030.76     10495160.53       3836994.3     10496150.11
      3837088.05     10496540.73      3837171.38      10496894.9
#Sta/Elev= 30
  4430.5   355.6  4530.3  352.75  4628.4  349.43  4740.4  340.21  4830.4  341.43
  4850.4  340.94  4867.3  337.77  4880.5  340.03  4890.5  337.66  4920.5  340.79
  4970.5  340.85  4990.5  339.89  4997.5  337.43  5000.3  336.93  5003.5  337.43
  5010.5   337.7  5020.6  340.74  5050.6  341.73  5090.6  341.26  5120.6  343.16
  5138.2  345.45  5150.6   350.2  5170.7  352.02  5412.8  356.81  5555.1  359.69
    5634  358.99  5729.3  361.61  5849.3  361.04  6037.6  365.09  6186.3  362.83
#Mann= 7 ,-1 , 0
  4430.5     .05       0  4530.3     .08       0  4628.4     .05       0
  4997.5     .04       0  5003.5     .05       0  5020.6     .08       0
  5412.8     .05       0
Bank Sta=4970.5,5050.6
XS Rating Curve= 0 ,0
Exp/Cntr=0.3,0.1

Type RM Length L Ch R = 1 ,2057    ,448,448,448
BEGIN DESCRIPTION:
UNT014 IN BECR 4.0
END DESCRIPTION:
XS GIS Cut Line= 2
       3837122.8      10495035.5      3835680.08     10496254.26
#Sta/Elev= 30
  4554.6  354.95  4602.3  355.75  4685.5  355.44  4744.3  354.04  4820.1   348.5
  4858.7  345.24  4872.9  342.55  4908.1  338.25  4914.6  336.16  4943.2   338.6
  4986.1  337.54  4992.7  337.01  4997.4  334.66  5000.2  334.16  5003.4  334.66
  5006.9  336.55  5021.2  338.05    5107  337.83  5156.4  338.75  5283.9  343.19
  5304.9  345.61  5326.7  345.02  5333.3  346.19    5341  345.21  5369.6  345.75
  5447.6  350.17  5603.7     355  5972.6  358.31  6326.6  365.02  6443.2  366.16
#Mann= 6 ,-1 , 0
  4554.6     .08       0  4602.3     .05       0  4685.5     .16       0
  4820.1     .05       0  4997.4     .03       0  5003.4     .05       0
Bank Sta=4943.2,5021.2
XS Rating Curve= 0 ,0
Exp/Cntr=0.3,0.1

Type RM Length L Ch R = 1 ,1609    ,789,789,789
BEGIN DESCRIPTION:
UNT014 IN BECR 3.0
END DESCRIPTION:
XS GIS Cut Line= 2
       3836945.7     10494733.43      3835857.16      10495462.6
#Sta/Elev= 30
  4477.7  354.36  4479.9  355.42    4486  355.51  4494.9  354.44    4552  353.61
  4675.1  354.13  4711.1  353.23  4783.1  348.61    4798  348.53  4810.2  346.23
  4819.1  345.97  4825.2  345.03  4840.2   341.6  4846.2  341.33  4855.2  339.67
  4891.2  337.32  4918.3  336.31  4933.2  336.66  4963.2  335.12  4984.3  335.85
  4990.6  334.45  4996.3   329.5    4999     329  5002.3   329.5  5014.3  334.84
  5035.3  335.56  5107.3  335.69  5488.6  350.14  5596.6  352.26  5787.9  353.52
#Mann= 3 ,-1 , 0
  4477.7     .05       0  4996.3     .03       0  5002.3     .05       0
Bank Sta=4984.3,5035.3
XS Rating Curve= 0 ,0
Exp/Cntr=0.3,0.1

Type RM Length L Ch R = 1 ,820     ,647,647,647
BEGIN DESCRIPTION:
UNT014 IN BECR 2.0
END DESCRIPTION:
XS GIS Cut Line= 4
      3836966.49     10494603.22      3836565.48     10494410.53
      3836034.23     10494493.86      3835664.52     10495139.55
#Sta/Elev= 30
  4318.4  354.16  4470.1  352.87  4611.5   348.7  4625.6  349.14  4653.6  347.32
  4785.9  341.95    4794  342.47  4799.6  340.96  4870.5  335.83  4900.8  335.08
    4911  331.94  4919.2  331.02  4924.3  332.23  4951.5  330.94  4971.7  332.91
  4981.8  330.66  4986.9  327.54  4999.1  326.69  5001.8  326.19  5005.1  326.69
  5012.2  331.85  5049.6  332.63  5184.9  333.31  5285.5  336.56  5300.9  337.89
    5323   337.8  5360.4  341.25  5456.8  344.53  5881.3  352.26  6045.1  353.52
#Mann= 5 ,-1 , 0
  4318.4     .05       0  4653.6     .16       0  4785.9     .05       0
  4999.1     .03       0  5005.1     .05       0
Bank Sta=4971.7,5049.6
XS Rating Curve= 0 ,0
Exp/Cntr=0.3,0.1

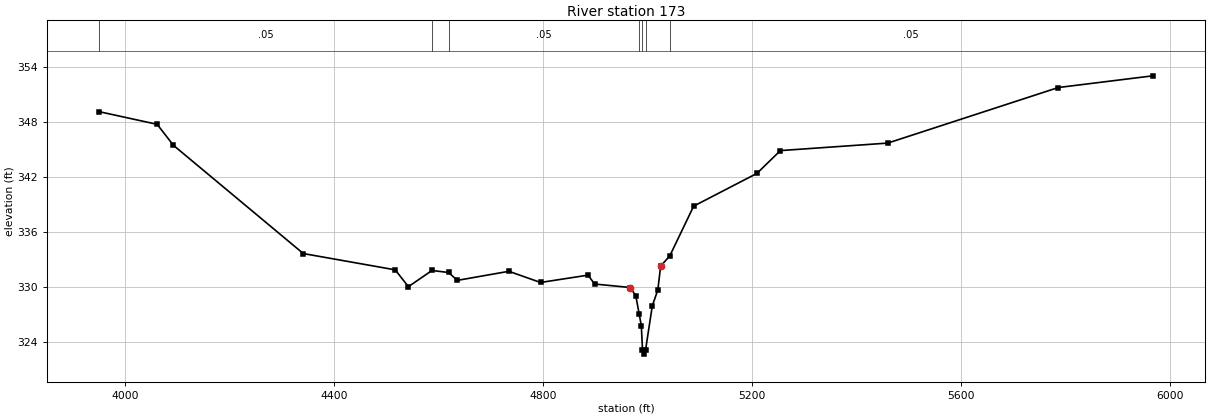
Type RM Length L Ch R = 1 ,173     ,0,0,0
BEGIN DESCRIPTION:
UNT014 IN BECR 1.0
END DESCRIPTION:
XS GIS Cut Line= 5
      3836847.88     10494272.01      3836101.37      10494011.6
      3835936.44     10494089.73      3835849.63     10494350.14
      3835633.02     10495086.62
#Sta/Elev= 30
  3951.5  349.13  4062.1  347.75  4093.2  345.46  4341.7  333.63  4517.5  331.85
  4542.8  330.01  4587.9  331.78  4619.6  331.56  4636.5   330.7    4735  331.69
  4795.5  330.47  4886.5  331.27    4899   330.3  4967.3  329.92  4977.8  329.01
  4984.3  327.02  4988.4  325.76  4990.6  323.14  4993.4  322.64  4996.6  323.14
  5009.4  327.92    5020  329.66  5025.3  332.25  5042.9  333.38  5088.5  338.81
  5209.6  342.39  5254.4  344.88  5459.8   345.7    5786  351.77  5966.8  353.05
#Mann= 7 ,-1 , 0
  3951.5     .05       0  4587.9     .16       0  4619.6     .05       0
  4984.3     .16       0  4990.6     .07       0  4996.6     .16       0
  5042.9     .05       0
Bank Sta=4967.3,5025.3
XS Rating Curve= 0 ,0
Exp/Cntr=0.3,0.1

Chan Stop Cuts=-1
Use User Specified Reach Order=0
Composite Channel Slope=5