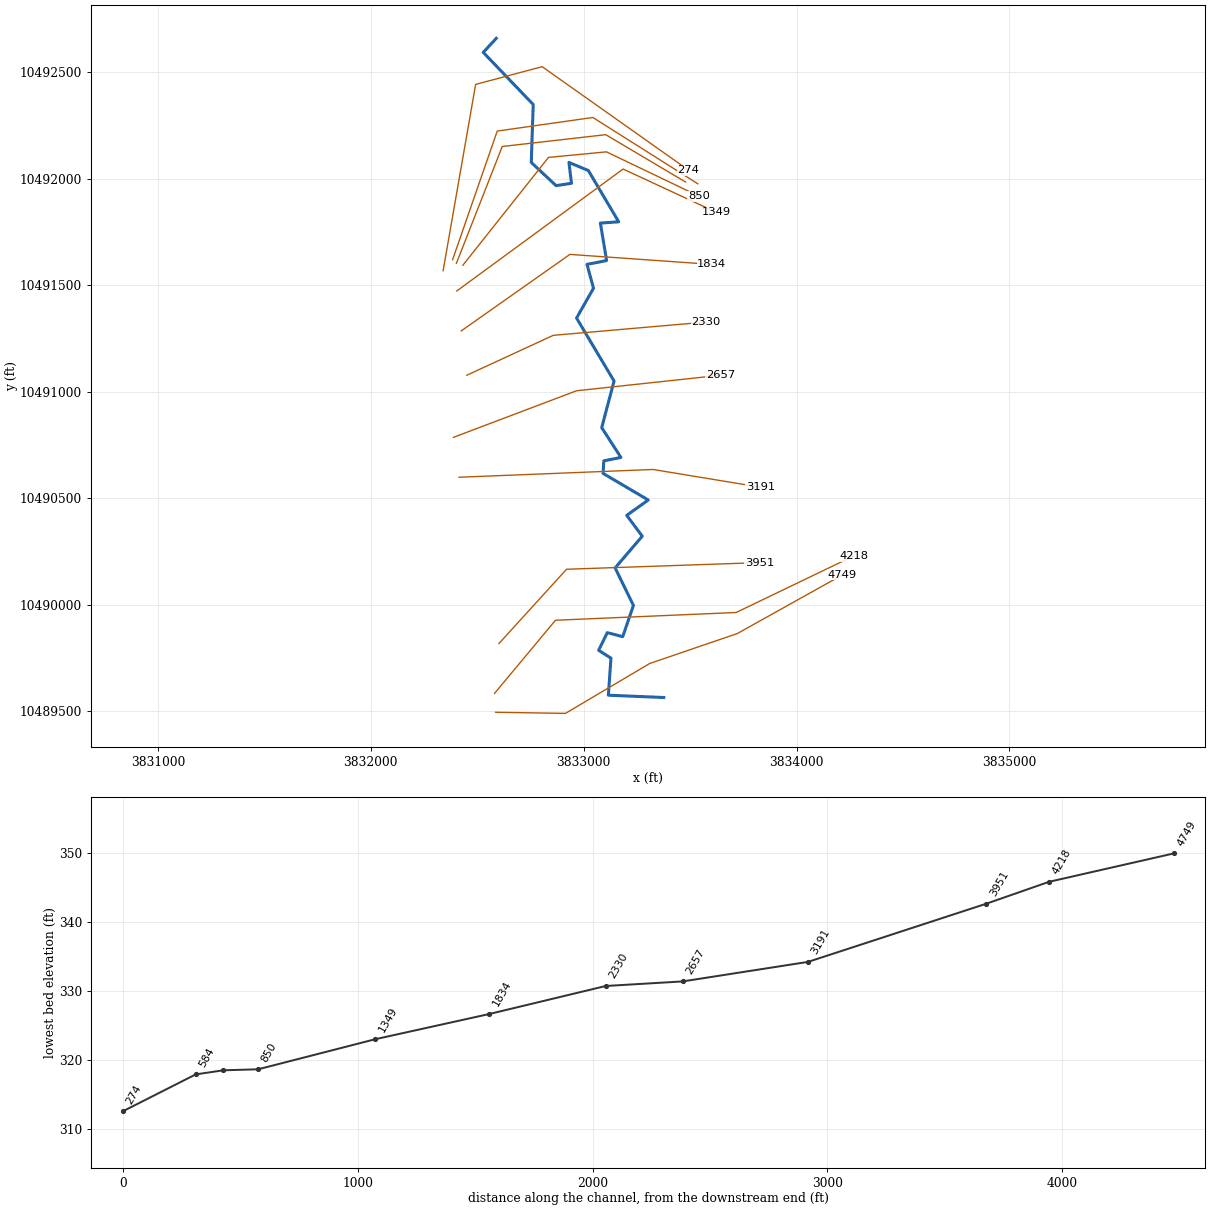
--- UNT015 IN BECR.prj (project) ---

Proj Title=UNT015 IN BECR Base Level Engineering
Current Plan=p01
Default Exp/Contr=0.3,0.1
English Units
Geom File=g01
Flow File=f01
Plan File=p01
Y Axis Title=Elevation
X Axis Title(PF)=Main Channel Distance
X Axis Title(XS)=Station
BEGIN DESCRIPTION:
UNT015 IN BECR
END DESCRIPTION:
DSS Export Rating Curves= 0
DSS Export Rating Curve Sorted= 0
DSS Export Volume Flow Curves= 0
DXF OffsetX= 0
DXF OffsetY= 0
DXF ScaleX= 1
DXF ScaleY= 10

--- UNT015 IN BECR.p01 (plan) ---

Plan Title=Multiple Run
Short Identifier=Multiple
Geom File=g01
Flow File=f01
Subcritical Flow
K Sum by GR= 0
Std Step Tol= 0.01
Critical Tol= 0.01
Num of Std Step Trials= 20
Max Error Tol= 0.3
Flow Tol Ratio= 0.001
Split Flow NTrial= 30
Split Flow Tol= 0.02
Split Flow Ratio= 0.02
Log Output Level= 0
Friction Slope Method= 1
Unsteady Friction Slope Method= 2
Unsteady Bridges Friction Slope Method= 1
Parabolic Critical Depth
Global Vel Dist=  1 , 1 , 1
Global Log Level= 0
CheckData=True
Encroach Param= -1, 0, 0, 0
BEGIN DESCRIPTION:
Multiple Run
END DESCRIPTION:

--- UNT015 IN BECR.f01 (steady flow) ---

Flow Title=Multiple
Program Version=4.10
Number of Profiles= 7
Profile Names=10-year,25-year,50-year,1pct_min,100-year,1pct_plu,500-year
River Rch & RM=UNT015 IN BECR,Reach-1         ,4749
     261     333     390     336     455     615     619
Boundary for River Rch & Prof#=UNT015 IN BECR,Reach-1         , 1
Up Type= 0
Dn Type= 3
Dn Slope=0.01
Boundary for River Rch & Prof#=UNT015 IN BECR,Reach-1         , 2
Up Type= 0
Dn Type= 3
Dn Slope=0.01
Boundary for River Rch & Prof#=UNT015 IN BECR,Reach-1         , 3
Up Type= 0
Dn Type= 3
Dn Slope=0.01
Boundary for River Rch & Prof#=UNT015 IN BECR,Reach-1         , 4
Up Type= 0
Dn Type= 3
Dn Slope=0.01
Boundary for River Rch & Prof#=UNT015 IN BECR,Reach-1         , 5
Up Type= 0
Dn Type= 3
Dn Slope=0.01
Boundary for River Rch & Prof#=UNT015 IN BECR,Reach-1         , 6
Up Type= 0
Dn Type= 3
Dn Slope=0.01
Boundary for River Rch & Prof#=UNT015 IN BECR,Reach-1         , 7
Up Type= 0
Dn Type= 3
Dn Slope=0.01
DSS Import GetInterval= 0
DSS Import GetPeak= 0
DSS Import FillOption= 0

--- UNT015 IN BECR.g01 (geometry) ---

Geom Title=Existing Conditions
Program Version=4.10

River Reach=UNT015 IN BECR  ,Reach-1
Reach XY= 30
        3833376.     10489563.22        3833116.       10489574.
      3833128.25       10489748.      3833070.25       10489785.
        3833111.       10489868.       3833183.5       10489849.
      3833233.75       10489996.      3833147.75       10490172.
      3833275.25       10490321.      3833202.25       10490419.
       3833303.5       10490491.      3833091.25       10490616.
       3833094.5       10490675.        3833175.       10490691.
      3833084.75       10490831.      3833142.75       10491050.
       3832966.5       10491346.      3833046.25       10491486.
       3833015.5       10491598.      3833107.75       10491616.
       3833078.5       10491792.       3833164.5       10491798.
        3833022.       10492039.      3832930.75       10492077.
      3832942.75       10491979.      3832870.25       10491968.
      3832753.75       10492077.        3832763.       10492349.
      3832528.25       10492594.       3832589.5       10492660.

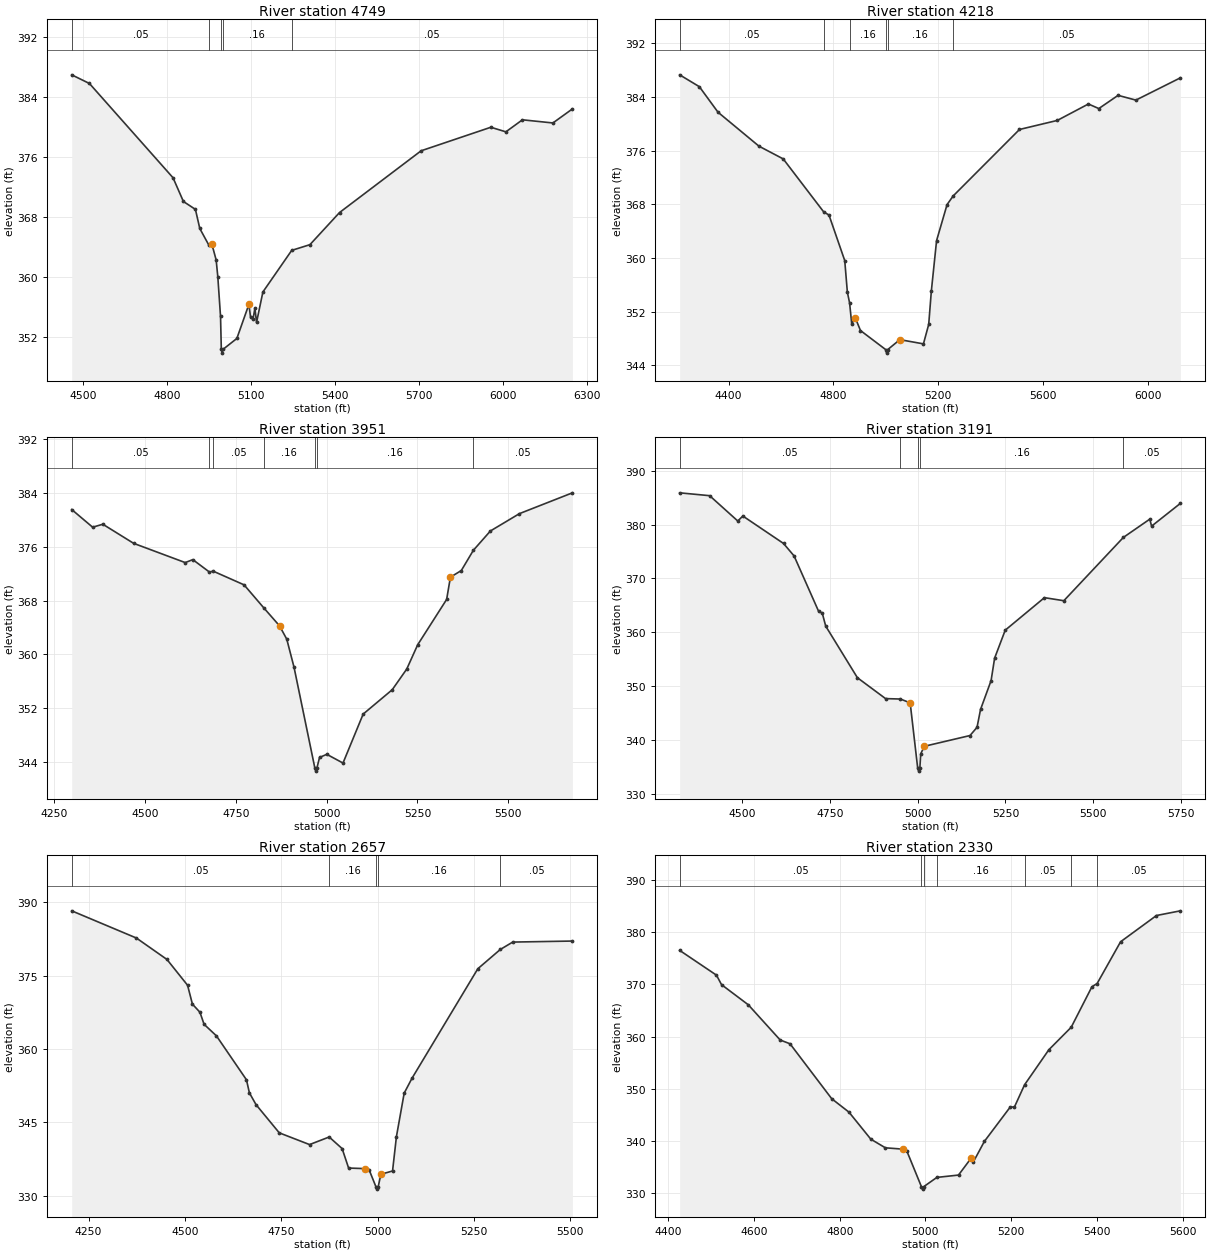
Type RM Length L Ch R = 1 ,4749    ,531,531,531
BEGIN DESCRIPTION:
UNT015 IN BECR 9.0
END DESCRIPTION:
XS GIS Cut Line= 5
      3832586.28     10489493.86      3832914.44     10489488.65
      3833310.27     10489723.03      3833721.73     10489863.65
      3834215.54     10490139.14
#Sta/Elev= 30
  4460.7  386.92    4524  385.77  4822.7  373.23  4859.7  370.08  4902.6  369.03
  4918.2  366.49  4951.1  364.24  4961.1  364.45  4976.7   362.3  4982.5   360.1
  4992.3  354.79  4995.1  350.42  4997.9  349.92  5001.1  350.42  5050.6  351.87
  5093.7  356.41  5099.5   354.7  5108.7  354.51  5115.1  355.92  5120.9     354
  5143.6  358.05  5246.5  363.58  5311.6  364.34  5417.3  368.61  5708.7  376.82
  5957.8  379.95  6011.5  379.34  6070.6  380.94  6179.5  380.52  6249.2  382.39
#Mann= 5 ,-1 , 0
  4460.7     .05       0  4951.1     .16       0  4995.1     .07       0
  5001.1     .16       0  5246.5     .05       0
Bank Sta=4961.1,5093.7
XS Rating Curve= 0 ,0
Exp/Cntr=0.3,0.1

Type RM Length L Ch R = 1 ,4218    ,267,267,267
BEGIN DESCRIPTION:
UNT015 IN BECR 8.0
END DESCRIPTION:
XS GIS Cut Line= 4
      3832581.11      10489582.4      3832867.56     10489926.15
      3833716.52     10489962.61      3834268.64     10490228.25
#Sta/Elev= 30
  4213.2  387.31  4288.4  385.54  4359.6  381.73  4515.8  376.67  4608.3  374.77
  4762.6  366.87  4782.8   366.4  4842.9  359.61  4852.9   354.9  4861.4   353.3
  4869.6  350.14  4882.9   351.1  4902.9  349.18    5000  346.31  5002.8  345.81
    5006  346.31  5053.1  347.82  5143.1  347.19  5163.2   350.1  5173.2  355.06
  5193.2  362.59  5233.2  367.96  5256.5  369.25  5509.4  379.16  5653.6  380.51
  5772.3  382.96    5812  382.28  5885.5  384.25  5953.4  383.54  6123.1  386.86
#Mann= 6 ,-1 , 0
  4213.2     .05       0  4762.6      .1       0  4861.4     .16       0
    5000     .07       0    5006     .16       0  5256.5     .05       0
Bank Sta=4882.9,5053.1
XS Rating Curve= 0 ,0
Exp/Cntr=0.3,0.1

Type RM Length L Ch R = 1 ,3951    ,760,760,760
BEGIN DESCRIPTION:
UNT015 IN BECR 7.0
END DESCRIPTION:
XS GIS Cut Line= 3
      3832601.96      10489816.8      3832919.65     10490165.73
      3833825.21     10490196.96
#Sta/Elev= 30
  4298.7  381.53  4356.3   378.9  4384.4  379.34  4469.2   376.5  4611.1  373.64
    4632  374.08  4677.8  372.23  4687.9  372.37  4773.1  370.33  4827.6  366.89
  4870.6  364.24  4890.6  362.25  4910.6  358.07  4967.7  343.14  4970.4  342.64
  4973.7  343.14  4980.7  344.67  5000.7  345.14  5045.3  343.84  5100.8  351.12
  5180.8  354.74  5220.8  357.82  5250.8  361.42  5330.5  368.16  5340.9  371.47
  5370.9  372.46  5404.1  375.47    5451  378.34    5531  380.92  5676.7  384.01
#Mann= 7 ,-1 , 0
  4298.7     .05       0  4677.8      .1       0  4687.9     .05       0
  4827.6     .16       0  4967.7     .07       0  4973.7     .16       0
  5404.1     .05       0
Bank Sta=4870.6,5340.9
XS Rating Curve= 0 ,0
Exp/Cntr=0.3,0.1

Type RM Length L Ch R = 1 ,3191    ,534,534,534
BEGIN DESCRIPTION:
UNT015 IN BECR 6.0
END DESCRIPTION:
XS GIS Cut Line= 3
      3832414.41     10490598.02       3833325.9     10490634.48
      3833831.15     10490551.14
#Sta/Elev= 30
  4323.2  385.89  4408.5  385.36  4488.5  380.66    4503  381.58  4618.6  376.49
  4648.7  374.17  4718.7  363.85  4728.7  363.59  4738.7  361.13  4828.8  351.55
  4908.9  347.67  4951.2  347.59  4978.9  346.88  5000.4   334.7  5003.1   334.2
  5006.4   334.7  5008.9   337.4    5019  338.81  5149.1  340.81  5169.1  342.34
  5179.1  345.66  5209.1  351.02  5219.1  355.18  5249.3  360.38  5360.8  366.42
    5416  365.85  5585.4  377.61  5660.5     381  5665.6   379.7  5747.5  383.93
#Mann= 5 ,-1 , 0
  4323.2     .05       0  4951.2     .16       0  5000.4     .07       0
  5006.4     .16       0  5585.4     .05       0
Bank Sta=4978.9,5019
XS Rating Curve= 0 ,0
Exp/Cntr=0.3,0.1

Type RM Length L Ch R = 1 ,2657    ,327,327,327
BEGIN DESCRIPTION:
UNT015 IN BECR 5.0
END DESCRIPTION:
XS GIS Cut Line= 3
      3832388.44     10490785.54      3832966.52     10491004.28
      3833643.63     10491077.19
#Sta/Elev= 30
  4206.3  388.28  4374.1  382.72  4453.5  378.33  4506.9  373.06  4519.5   369.2
    4539  367.54  4549.7  365.08  4581.8  362.71  4659.7  353.73  4667.3  351.06
  4684.5  348.65  4744.8  342.88  4823.4  340.48  4874.3  342.03  4907.9  339.66
  4924.7  335.68  4968.3  335.56  4978.4  335.23  4995.5  331.87  4998.2  331.37
  5001.5  331.87  5008.5  334.41  5038.7  335.08  5048.8  342.12  5068.9     351
    5089  354.02    5260  376.44  5318.3  380.38  5350.5  381.89  5505.4   382.1
#Mann= 5 ,-1 , 0
  4206.3     .05       0  4874.3     .16       0  4995.5     .07       0
  5001.5     .16       0  5318.3     .05       0
Bank Sta=4968.3,5008.5
XS Rating Curve= 0 ,0
Exp/Cntr=0.3,0.1

Type RM Length L Ch R = 1 ,2330    ,496,496,496
BEGIN DESCRIPTION:
UNT015 IN BECR 4.0
END DESCRIPTION:
XS GIS Cut Line= 3
      3832450.92      10491077.2      3832857.15     10491264.69
      3833575.24     10491327.13
#Sta/Elev= 30
  4426.6  376.54  4512.5  371.78  4524.3  369.96  4586.8  366.09  4661.2  359.33
  4684.1  358.61  4781.4  348.06  4821.6  345.49  4872.6   340.3  4906.6  338.64
  4946.7  338.39  4956.8  337.99  4990.5  331.21  4993.3  330.71  4996.5  331.21
  5026.7  332.96  5077.2  333.41  5106.5  336.64  5111.5  335.88  5137.5  339.87
  5197.7  346.45  5207.7  346.48  5231.3  350.74    5288  357.47  5340.1  361.78
  5388.4  369.55  5400.6  370.18  5455.3  378.19    5539  383.23  5594.8  384.13
#Mann= 7 ,-1 , 0
  4426.6     .05       0  4990.5     .03       0  4996.5     .05       0
  5026.7     .16       0  5231.3     .05       0  5340.1     .16       0
  5400.6     .05       0
Bank Sta=4946.7,5106.5
XS Rating Curve= 0 ,0
Exp/Cntr=0.3,0.1

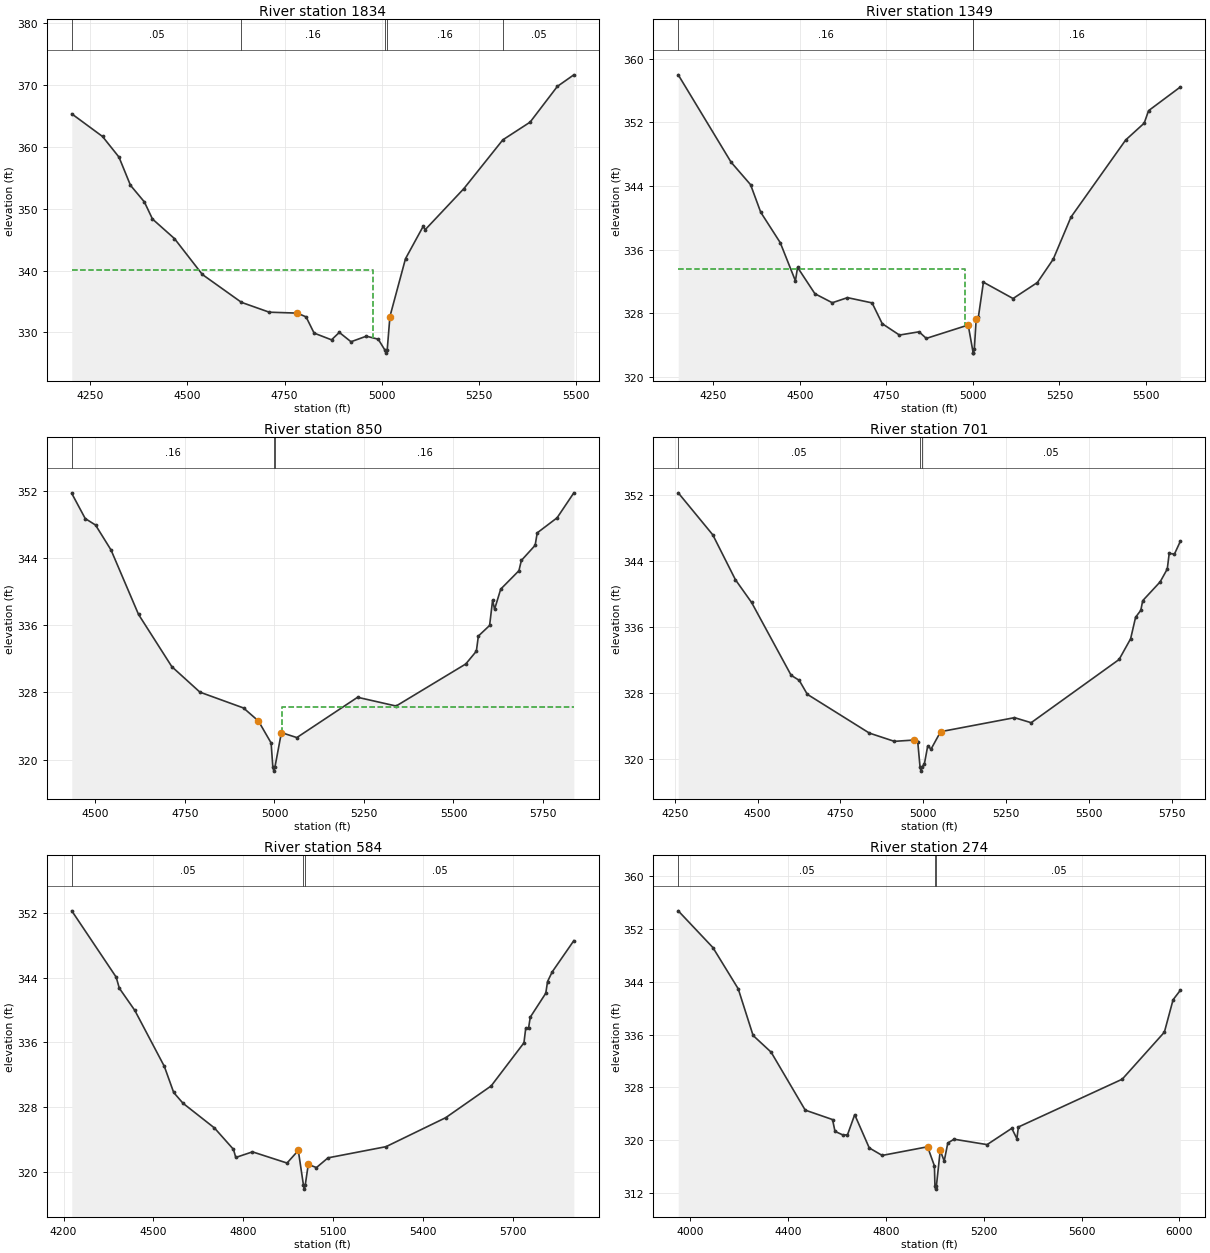
Type RM Length L Ch R = 1 ,1834    ,485,485,485
BEGIN DESCRIPTION:
UNT015 IN BECR 3.0
END DESCRIPTION:
XS GIS Cut Line= 3
      3832424.82      10491285.5      3832935.27      10491644.9
      3833601.94     10491598.03
#Sta/Elev= 30
  4202.3  365.34  4281.5  361.68  4323.8  358.35  4353.4  353.79  4389.2   351.1
  4410.1  348.33  4466.7  345.17  4538.4  339.37  4639.2  334.86  4710.6  333.27
    4783  333.12  4805.5  332.51  4826.2  329.89    4871   328.8  4891.1     330
  4921.2  328.49  4960.7  329.39  4991.3   328.9  5008.4  327.15  5011.1  326.65
  5014.4  327.15  5021.4  332.57  5061.5  341.92  5107.1  347.16  5112.1   346.6
  5211.9  353.26  5312.1  361.14  5382.3     364  5452.5  369.78  5494.9  371.65
#Mann= 5 ,-1 , 0
  4202.3     .05       0  4639.2     .16       0  5008.4     .07       0
  5014.4     .16       0  5312.1     .05       0
#XS Ineff= 2 , 0
         4978.75  340.05
Permanent Ineff=
       F       F
Bank Sta=4783,5021.4
XS Rating Curve= 0 ,0
Exp/Cntr=0.3,0.1

Type RM Length L Ch R = 1 ,1349    ,499,499,499
BEGIN DESCRIPTION:
UNT015 IN BECR 2.0
END DESCRIPTION:
XS GIS Cut Line= 3
      3832403.99     10491473.01      3833185.27     10492045.94
      3833622.78     10491842.82
#Sta/Elev= 30
  4148.1  357.96  4300.8  346.99  4357.2  344.16  4386.5   340.7  4442.9  336.88
  4486.8  332.08    4493  333.77  4543.2  330.46  4593.4  329.33  4637.3  329.97
  4708.4  329.31  4737.7   326.7  4787.5  325.27  4844.2  325.68  4865.1  324.85
  4986.2  326.53  5000.7     323  5001.2     323  5003.9   323.5  5009.4  327.33
  5015.6  327.52  5030.2  331.91  5115.9  329.86  5186.2  331.87    5232   334.8
  5283.3  340.09  5441.5  349.78  5494.9  351.89  5507.6  353.46  5599.3  356.43
#Mann= 3 ,-1 , 0
  4148.1     .16       0  5000.7     .07       0  5001.2     .16       0
#XS Ineff= 2 , 0
         4978.18  333.57
Permanent Ineff=
       F       F
Bank Sta=4986.2,5009.4
XS Rating Curve= 0 ,0
Exp/Cntr=0.3,0.1

Type RM Length L Ch R = 1 ,850     ,149,149,149
BEGIN DESCRIPTION:
Mapping XS 678c3041
END DESCRIPTION:
XS GIS Cut Line= 4
      3832432.52     10491594.18      3832834.84     10492100.66
      3833106.98      10492126.7      3833541.85     10491918.38
#Sta/Elev= 30
  4433.9  351.66  4471.5  348.67  4500.3   347.9  4543.6  344.93  4620.4  337.27
  4713.4  331.06  4791.9  328.03  4913.6  326.15  4955.3   324.6  4990.7  321.99
  4995.5  319.14  4998.3  318.64  5001.5  319.14  5019.4  323.22  5062.6  322.63
  5232.2  327.42  5339.9  326.38  5534.4  331.38    5564   332.9  5569.6   334.7
    5601  335.96  5609.4  338.97  5614.9  337.89    5632  340.28  5682.9  342.47
  5689.7  343.69  5728.2  345.49    5734  346.97  5789.5  348.76  5836.3  351.73
#Mann= 3 ,-1 , 0
  4433.9     .16       0  4998.3     .07       0  5001.5     .16       0
#XS Ineff= 2 , 0
                         5020.91          326.26
Permanent Ineff=
       F       F
Bank Sta=4955.3,5019.4
XS Rating Curve= 0 ,0
Exp/Cntr=0.3,0.1

Type RM Length L Ch R = 1 ,701     ,117,117,117
BEGIN DESCRIPTION:
Mapping XS 0e78265f
END DESCRIPTION:
XS GIS Cut Line= 4
      3832402.18      10491603.2      3832617.48     10492151.85
      3833103.59      10492207.4      3833478.54     10491985.21
#Sta/Elev= 30
  4260.8  352.22    4365  347.13  4433.3  341.69  4482.1  338.93  4601.3  330.11
  4625.8  329.49  4650.2   327.8  4837.3   323.1  4912.7   322.1  4973.1  322.26
  4983.2  322.08  4990.2  318.99    4993  318.49  4996.2  318.99  5003.3  319.36
  5013.4  321.55  5023.4  321.16  5052.2  323.27  5275.1  324.97  5325.4  324.36
  5590.6  332.02  5625.4  334.53  5640.4  337.14  5656.1  337.98  5661.9  339.15
  5714.5  341.43    5736  342.99  5741.8  344.89  5757.4  344.78  5775.3  346.34
#Mann= 3 ,-1 , 0
  4260.8     .05       0  4990.2     .03       0  4996.2     .05       0
Bank Sta=4973.1,5052.2
XS Rating Curve= 0 ,0
Exp/Cntr=0.3,0.1

Type RM Length L Ch R = 1 ,584     ,310,310,310
BEGIN DESCRIPTION:
Mapping XS 95a9c789
END DESCRIPTION:
XS GIS Cut Line= 4
      3832384.31     10491620.15      3832593.96     10492224.36
      3833043.18     10492288.16      3833536.29     10491976.72
#Sta/Elev= 30
  4227.6  352.25  4375.8  344.07  4386.4   342.7  4438.1  339.96  4536.7  333.05
  4567.9  329.83    4599   328.5    4704  325.45  4767.5  322.81  4775.2  321.81
    4831   322.5  4946.4  321.12    4984  322.67  5001.2   318.4  5003.9   317.9
  5007.2   318.4  5017.3  320.95  5044.6  320.56  5083.2  321.76  5276.9  323.14
  5476.3  326.72  5628.1  330.64  5737.5  335.96  5743.4  337.75  5752.8  337.77
  5758.7  339.13  5810.4  342.08  5816.3  343.52  5831.6   344.7  5904.1  348.57
#Mann= 3 ,-1 , 0
  4227.6     .05       0  5001.2     .03       0  5007.2     .05       0
Bank Sta=4984,5017.3
XS Rating Curve= 0 ,0
Exp/Cntr=0.3,0.1

Type RM Length L Ch R = 1 ,274     ,0,0,0
BEGIN DESCRIPTION:
UNT015 IN BECR 1.0
END DESCRIPTION:
XS GIS Cut Line= 4
       3832339.7     10491568.52      3832492.48     10492443.51
      3832804.98     10492526.85      3833492.44     10492040.76
#Sta/Elev= 30
  3949.9  354.76  4091.7  349.19  4195.2  342.94  4256.1  335.86  4329.8  333.33
  4469.3  324.54    4581  323.11  4591.1  321.32  4622.3  320.79  4641.9  320.77
  4671.7  323.85  4731.2  318.81    4784  317.67  4969.7  318.98  4997.7  316.09
  4999.9  313.06  5002.7  312.56  5005.9  313.06  5021.5  318.42  5037.8  316.82
  5052.5  319.55  5077.9  320.13  5213.2  319.31  5314.2  321.78  5335.1  320.21
  5341.2  321.98  5765.9  329.23  5938.3  336.36    5974  341.28  6003.5  342.71
#Mann= 3 ,-1 , 0
  3949.9     .05       0  4999.9     .03       0  5005.9     .05       0
Bank Sta=4969.7,5021.5
XS Rating Curve= 0 ,0
Exp/Cntr=0.3,0.1

Chan Stop Cuts=-1
Use User Specified Reach Order=0
Composite Channel Slope=5