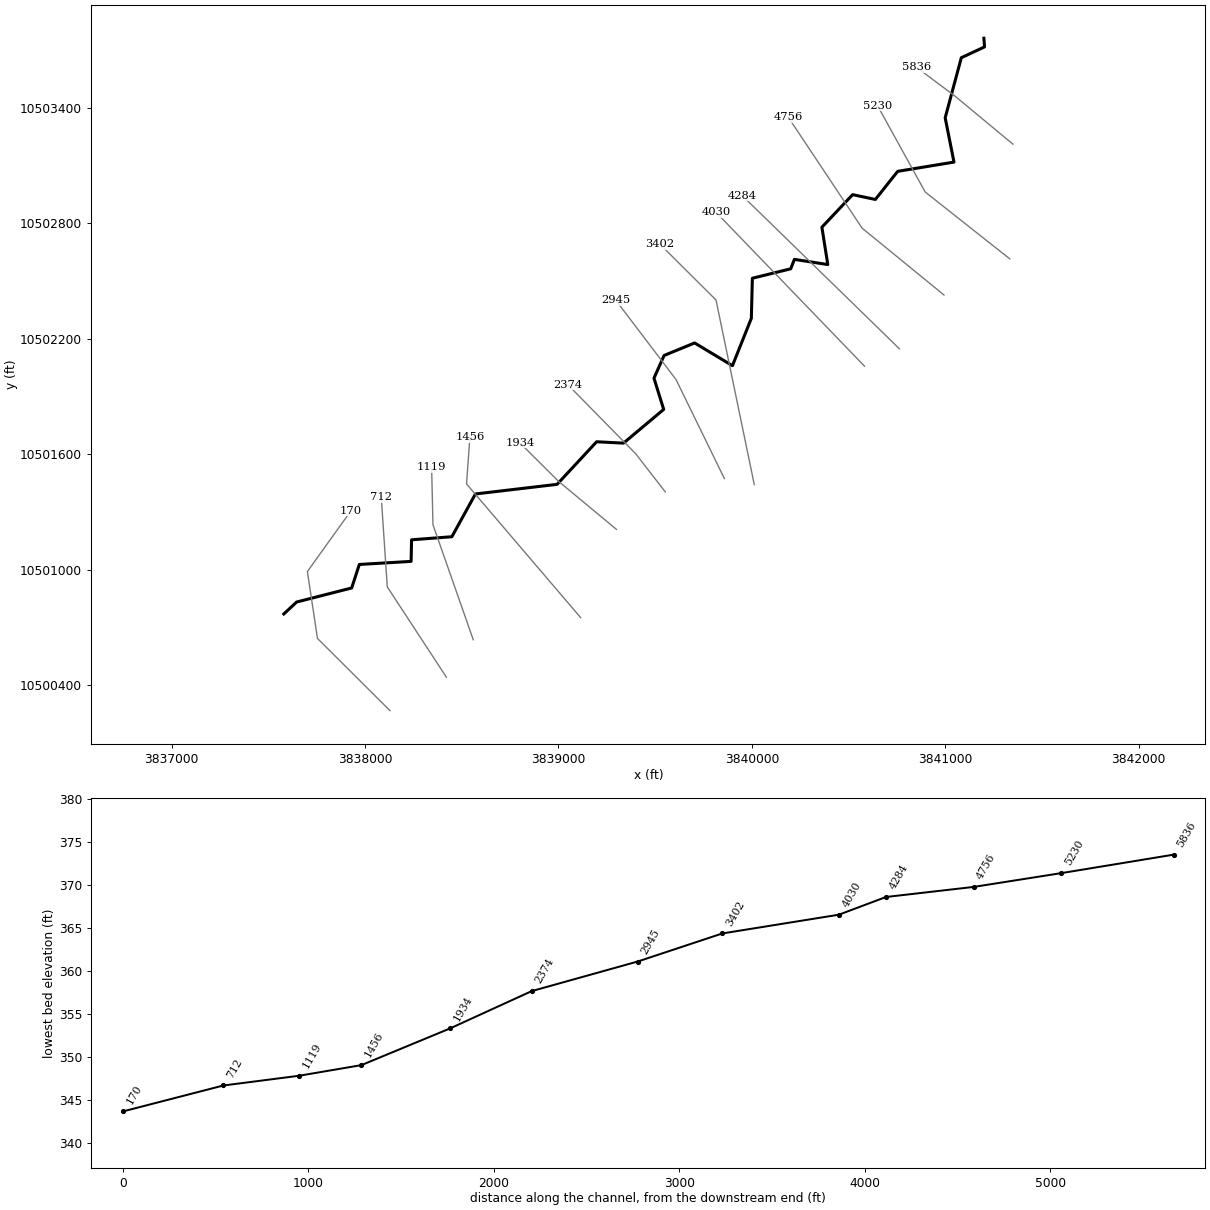
--- UNT017 IN BECR.prj (project) ---

Proj Title=UNT017 IN BECR Base Level Engineering
Current Plan=p01
Default Exp/Contr=0.3,0.1
English Units
Geom File=g01
Flow File=f01
Plan File=p01
Y Axis Title=Elevation
X Axis Title(PF)=Main Channel Distance
X Axis Title(XS)=Station
BEGIN DESCRIPTION:
UNT017 IN BECR
END DESCRIPTION:
DSS Export Rating Curves= 0
DSS Export Rating Curve Sorted= 0
DSS Export Volume Flow Curves= 0
DXF OffsetX= 0
DXF OffsetY= 0
DXF ScaleX= 1
DXF ScaleY= 10

--- UNT017 IN BECR.p01 (plan) ---

Plan Title=Multiple Run
Short Identifier=Multiple
Geom File=g01
Flow File=f01
Subcritical Flow
K Sum by GR= 0
Std Step Tol= 0.01
Critical Tol= 0.01
Num of Std Step Trials= 20
Max Error Tol= 0.3
Flow Tol Ratio= 0.001
Split Flow NTrial= 30
Split Flow Tol= 0.02
Split Flow Ratio= 0.02
Log Output Level= 0
Friction Slope Method= 1
Unsteady Friction Slope Method= 2
Unsteady Bridges Friction Slope Method= 1
Parabolic Critical Depth
Global Vel Dist=  1 , 1 , 1
Global Log Level= 0
CheckData=True
Encroach Param= -1, 0, 0, 0
BEGIN DESCRIPTION:
Multiple Run
END DESCRIPTION:

--- UNT017 IN BECR.f01 (steady flow) ---

Flow Title=Multiple
Program Version=4.10
Number of Profiles= 7
Profile Names=10-year,25-year,50-year,1pct_min,100-year,1pct_plu,500-year
River Rch & RM=UNT017 IN BECR,Reach-1         ,5836
     424     554     657     573     775    1049    1082
Boundary for River Rch & Prof#=UNT017 IN BECR,Reach-1         , 1
Up Type= 0
Dn Type= 3
Dn Slope=0.0063
Boundary for River Rch & Prof#=UNT017 IN BECR,Reach-1         , 2
Up Type= 0
Dn Type= 3
Dn Slope=0.0063
Boundary for River Rch & Prof#=UNT017 IN BECR,Reach-1         , 3
Up Type= 0
Dn Type= 3
Dn Slope=0.0063
Boundary for River Rch & Prof#=UNT017 IN BECR,Reach-1         , 4
Up Type= 0
Dn Type= 3
Dn Slope=0.0063
Boundary for River Rch & Prof#=UNT017 IN BECR,Reach-1         , 5
Up Type= 0
Dn Type= 3
Dn Slope=0.0063
Boundary for River Rch & Prof#=UNT017 IN BECR,Reach-1         , 6
Up Type= 0
Dn Type= 3
Dn Slope=0.0063
Boundary for River Rch & Prof#=UNT017 IN BECR,Reach-1         , 7
Up Type= 0
Dn Type= 3
Dn Slope=0.0063
DSS Import GetInterval= 0
DSS Import GetPeak= 0
DSS Import FillOption= 0

--- UNT017 IN BECR.g01 (geometry) ---

Geom Title=Existing Conditions
Program Version=4.10

River Reach=UNT017 IN BECR  ,Reach-1
Reach XY= 30
      3841199.61     10503760.19        3841203.       10503715.
        3841083.       10503659.       3840999.5       10503347.
        3841045.       10503117.        3840754.       10503069.
       3840638.5       10502923.        3840521.       10502948.
        3840362.       10502779.       3840392.5       10502585.
      3840219.75       10502612.        3840201.       10502563.
       3840002.5       10502514.      3839997.25       10502306.
       3839899.5       10502060.        3839704.       10502178.
        3839546.       10502113.      3839493.75       10501995.
        3839544.       10501833.      3839336.25       10501658.
      3839197.25       10501665.      3838992.75       10501444.
       3838570.5       10501394.      3838448.75       10501172.
      3838240.25       10501156.        3838238.       10501044.
      3837970.25       10501028.      3837930.75       10500906.
        3837646.       10500833.      3837579.75       10500771.

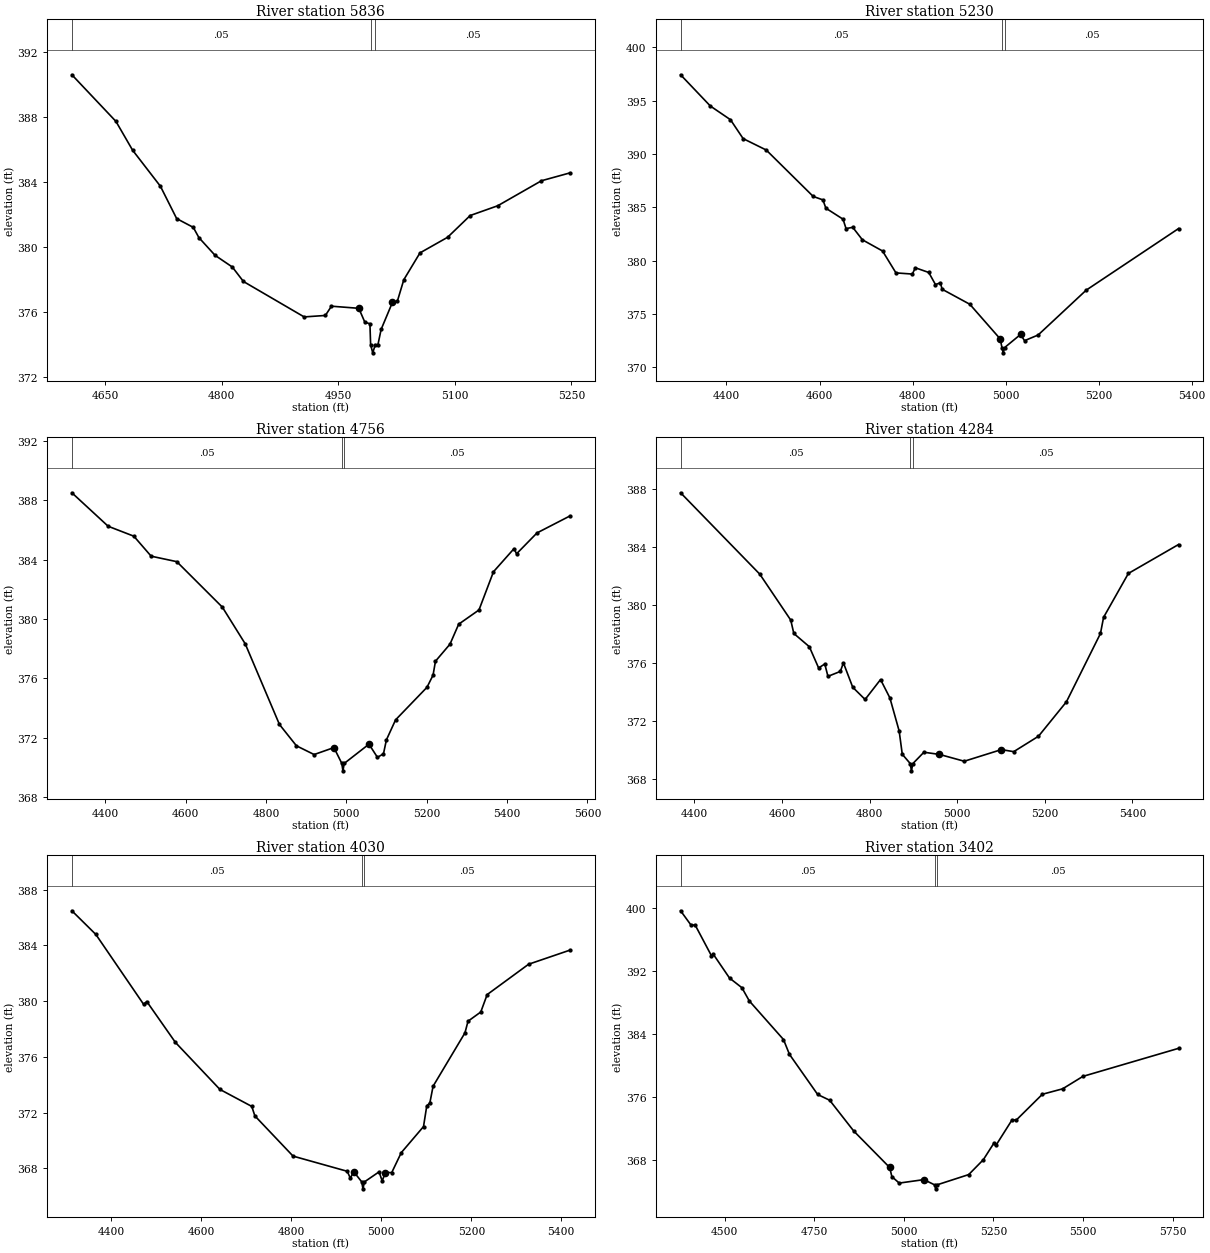
Type RM Length L Ch R = 1 ,5836    ,606,606,606
BEGIN DESCRIPTION:
UNT017 IN BECR 12.0
END DESCRIPTION:
XS GIS Cut Line= 3
      3841349.64     10503210.17      3841049.61     10503460.19
      3840849.65     10503610.16
#Sta/Elev= 30
  4607.4  390.62  4664.1  387.75  4685.5  385.98  4721.3  383.76  4742.2  381.77
  4763.6  381.23  4770.8   380.6  4791.6  379.51  4813.8  378.79  4828.1   377.9
  4906.2  375.72  4933.5  375.81  4941.3  376.38  4976.5  376.25  4984.3  375.39
  4990.8   375.3  4991.7  374.01  4994.4  373.51  4997.7  374.01  5001.1  374.01
  5005.2  374.95  5019.8  376.62  5026.1  376.69  5034.4  378.01  5055.2  379.66
  5090.7  380.62  5119.8  381.96  5155.2  382.56  5211.5   384.1  5247.9  384.58
#Mann= 3 ,-1 , 0
  4607.4     .05       0  4991.7     .03       0  4997.7     .05       0
Bank Sta=4976.5,5019.8
XS Rating Curve= 0 ,0
Exp/Cntr=0.3,0.1

Type RM Length L Ch R = 1 ,5230    ,474,474,474
BEGIN DESCRIPTION:
UNT017 IN BECR 11.0
END DESCRIPTION:
XS GIS Cut Line= 3
       3841333.6     10502614.54      3840896.12     10502961.74
      3840649.58     10503410.23
#Sta/Elev= 30
  4301.4  397.41  4365.4  394.48  4408.6   393.2  4435.8  391.43  4485.5  390.36
  4586.5  386.01  4607.3  385.69  4613.7  384.91  4650.6  383.88    4657     383
  4671.4  383.12  4692.2  381.95  4735.5   380.9  4764.3  378.85  4799.6  378.74
  4805.9  379.33  4834.8  378.89  4849.2  377.76  4859.9  377.92  4863.5  377.32
  4923.1  375.91  4988.5  372.66  4992.1  371.86  4994.8  371.36  4998.1  371.86
  5032.1  373.08  5040.7   372.5  5069.9  373.03  5173.2  377.23  5371.7     383
#Mann= 3 ,-1 , 0
  4301.4     .05       0  4992.1     .03       0  4998.1     .05       0
Bank Sta=4988.5,5032.1
XS Rating Curve= 0 ,0
Exp/Cntr=0.3,0.1

Type RM Length L Ch R = 1 ,4756    ,472,472,472
BEGIN DESCRIPTION:
UNT017 IN BECR 10.0
END DESCRIPTION:
XS GIS Cut Line= 3
      3840993.35     10502427.02      3840569.73     10502774.24
      3840187.78     10503350.64
#Sta/Elev= 30
  4316.9  388.52  4407.2  386.26  4471.1  385.59  4514.2  384.24    4578  383.87
  4691.4   380.8  4748.4  378.32  4833.5  372.88  4875.8  371.44  4919.8  370.85
  4969.1  371.32  4988.7  370.25  4991.5  369.75  4994.7  370.25  5056.3  371.55
  5077.4  370.66  5092.4   370.9  5099.7  371.84  5122.5  373.19  5200.7  375.39
  5215.8  376.21  5221.8  377.15  5257.9   378.3  5279.6  379.65  5330.1  380.61
  5366.2  383.19  5417.3  384.75  5423.6   384.4  5474.5  385.81  5556.1  386.95
#Mann= 3 ,-1 , 0
  4316.9     .05       0  4988.7     .03       0  4994.7     .05       0
Bank Sta=4969.1,5056.3
XS Rating Curve= 0 ,0
Exp/Cntr=0.3,0.1

Type RM Length L Ch R = 1 ,4284    ,254,254,254
BEGIN DESCRIPTION:
UNT017 IN BECR 9.0
END DESCRIPTION:
XS GIS Cut Line= 2
      3840762.81     10502147.76      3839950.34     10502942.87
#Sta/Elev= 30
  4368.5  387.71  4549.3  382.11    4620  378.95    4627  378.03  4662.4  377.12
  4683.6  375.66  4697.7  375.93  4704.9  375.08  4733.2  375.42  4740.2  376.01
  4761.5  374.33  4789.7  373.49    4825  374.86  4846.3   373.6  4867.5  371.32
  4874.6  369.72  4892.8  369.08  4895.5  368.58  4898.8  369.08    4924  369.86
  4959.5  369.71  5016.1  369.24  5100.8  370.04  5129.1   369.9  5185.6  370.96
  5249.4  373.33  5327.1  378.03  5334.2  379.14  5390.8  382.16  5505.3  384.15
#Mann= 3 ,-1 , 0
  4368.5     .05       0  4892.8     .03       0  4898.8     .05       0
Bank Sta=4959.5,5100.8
XS Rating Curve= 0 ,0
Exp/Cntr=0.3,0.1

Type RM Length L Ch R = 1 ,4030    ,628,628,628
BEGIN DESCRIPTION:
UNT017 IN BECR 8.0
END DESCRIPTION:
XS GIS Cut Line= 2
      3840582.28     10502057.46      3839815.35     10502855.61
#Sta/Elev= 30
    4312  386.49  4365.3  384.79  4471.3  379.78  4478.6  379.97  4542.1  377.04
  4641.1  373.66  4711.9  372.44  4718.8  371.76  4803.7  368.87  4924.2  367.78
  4931.1  367.28  4938.3  367.76  4956.4  367.02  4959.1  366.52  4962.4  367.02
  4994.9  367.74  5001.8  367.09  5009.1  367.69  5023.1  367.69  5044.3  369.12
  5093.7  370.99  5100.9  372.47  5107.8  372.69    5115  373.89  5185.8  377.72
  5192.7  378.56    5221  379.22  5235.2  380.47  5327.3  382.65  5418.9  383.66
#Mann= 3 ,-1 , 0
    4312     .05       0  4956.4     .03       0  4962.4     .05       0
Bank Sta=4938.3,5009.1
XS Rating Curve= 0 ,0
Exp/Cntr=0.3,0.1

Type RM Length L Ch R = 1 ,3402    ,457,457,457
BEGIN DESCRIPTION:
UNT017 IN BECR 7.0
END DESCRIPTION:
XS GIS Cut Line= 3
      3840012.44     10501442.64      3839814.53     10502400.98
      3839523.74     10502691.77
#Sta/Elev= 30
  4376.9  399.65    4405  397.89    4418   397.8  4463.1  393.93  4468.2  394.13
  4513.4  391.11    4548  389.88  4568.7   388.2  4664.1   383.3  4680.7  381.42
  4759.5  376.32    4793  375.59    4860  371.69  4960.5  367.05  4966.6  365.89
  4987.1  365.07  5055.9  365.51  5086.2  364.84  5088.9  364.34  5092.2  364.84
  5181.1  366.15  5221.9  368.04  5251.8  370.17  5256.9  369.85  5302.1   373.1
  5313.8  373.07  5386.7  376.35  5443.2  377.04  5499.8  378.62  5766.7  382.18
#Mann= 3 ,-1 , 0
  4376.9     .05       0  5086.2     .03       0  5092.2     .05       0
Bank Sta=4960.5,5055.9
XS Rating Curve= 0 ,0
Exp/Cntr=0.3,0.1

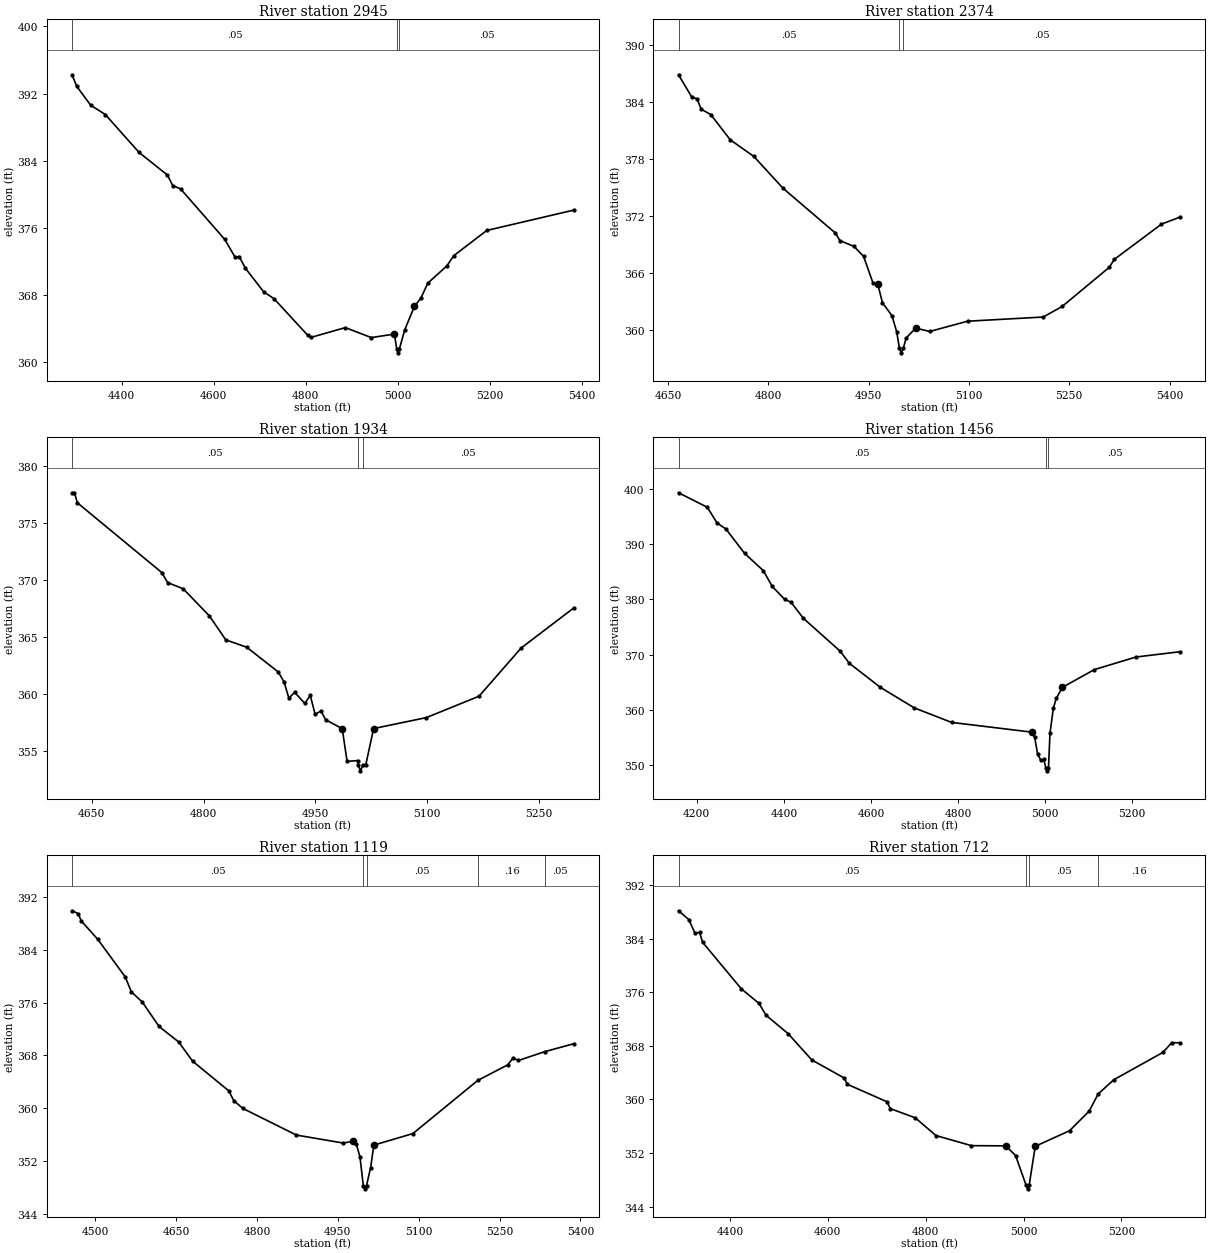
Type RM Length L Ch R = 1 ,2945    ,571,571,571
BEGIN DESCRIPTION:
UNT017 IN BECR 6.0
END DESCRIPTION:
XS GIS Cut Line= 3
      3839857.94     10501473.87      3839607.93     10501987.78
       3839295.4     10502401.01
#Sta/Elev= 30
  4292.4  394.24  4302.5  392.86  4332.8  390.61  4364.6   389.5  4437.8  384.98
  4499.6  382.27    4511  381.02    4528  380.63  4623.8  374.61  4646.3  372.49
  4655.3  372.56  4668.9  371.15  4708.4  368.35  4730.9  367.53  4804.2  363.16
    4811  362.91  4885.8  364.08  4942.1  362.89  4992.3  363.31  4997.3  361.57
    5000  361.07  5003.3  361.57  5014.8  363.82  5035.7   366.6  5050.2  367.63
  5064.8  369.38  5106.4  371.45    5121  372.65  5192.9  375.67    5382   378.1
#Mann= 3 ,-1 , 0
  4292.4     .05       0  4997.3     .03       0  5003.3     .05       0
Bank Sta=4992.3,5035.7
XS Rating Curve= 0 ,0
Exp/Cntr=0.3,0.1

Type RM Length L Ch R = 1 ,2374    ,440,440,440
BEGIN DESCRIPTION:
UNT017 IN BECR 5.0
END DESCRIPTION:
XS GIS Cut Line= 3
      3839552.36     10501404.47       3839399.6     10501602.37
      3839049.63     10501960.17
#Sta/Elev= 30
  4665.6   386.9  4685.5  384.54  4693.2  384.37  4699.5  383.28    4714   382.7
    4743  380.05  4778.3   378.3  4821.8  374.96  4900.2  370.24    4907  369.44
  4928.1  368.83  4942.3  367.79  4956.4  364.99  4963.6  364.85  4970.6   362.9
  4984.7  361.55  4991.9  359.85  4995.9  358.13  4998.6  357.63  5001.9  358.13
    5006  359.19  5020.2  360.23  5041.3  359.88  5097.9  360.96    5211   361.4
  5239.3  362.51    5310  366.64  5317.2  367.46  5387.9  371.18  5416.1  371.93
#Mann= 3 ,-1 , 0
  4665.6     .05       0  4995.9     .03       0  5001.9     .05       0
Bank Sta=4963.6,5020.2
XS Rating Curve= 0 ,0
Exp/Cntr=0.3,0.1

Type RM Length L Ch R = 1 ,1934    ,478,478,478
BEGIN DESCRIPTION:
UNT017 IN BECR 4.0
END DESCRIPTION:
XS GIS Cut Line= 3
       3839299.6      10501210.2      3838999.61     10501460.19
      3838799.64     10501660.16
#Sta/Elev= 30
  4623.6  377.69  4626.8  377.69  4630.7  376.81    4744  370.69  4751.8  369.81
  4772.6  369.27  4807.8  366.89  4829.9  364.78  4857.9  364.14  4900.2  361.97
    4908   361.1  4914.5  359.67  4922.3  360.18    4936   359.2  4943.2  359.92
  4949.7  358.25  4957.5  358.54    4964  357.77  4986.1  356.99  4992.6  354.12
  5006.9  354.19  5007.8  353.79  5010.6  353.29  5013.8  353.79  5017.6  353.79
  5028.2     357  5098.9  357.96  5169.7  359.84  5226.2  364.07  5296.9  367.59
#Mann= 3 ,-1 , 0
  4623.6     .05       0  5007.8     .03       0  5013.8     .05       0
Bank Sta=4986.1,5028.2
XS Rating Curve= 0 ,0
Exp/Cntr=0.3,0.1

Type RM Length L Ch R = 1 ,1456    ,337,337,337
BEGIN DESCRIPTION:
UNT017 IN BECR 3.0
END DESCRIPTION:
XS GIS Cut Line= 3
      3839114.85      10500751.7       3838524.6     10501446.12
      3838541.82     10501687.23
#Sta/Elev= 30
    4158  399.24  4224.2  396.62  4246.2  393.81    4267  392.69  4309.9  388.29
  4352.7  385.19  4373.5  382.32  4402.1  379.97  4416.4  379.49  4444.7  376.58
  4529.5  370.63  4550.3  368.46  4621.8   364.1  4699.7  360.39  4785.4  357.77
  4969.7  356.01  4976.5  355.05  4983.1  352.04  4990.8  350.89  4997.3  351.09
  5002.1  349.52  5004.8  349.02  5008.1  349.52  5011.6  355.82  5019.3  360.31
  5025.9  362.09  5040.2   364.1  5113.6  367.31  5209.4  369.58  5311.1  370.54
#Mann= 3 ,-1 , 0
    4158     .05       0  5002.1     .03       0  5008.1     .05       0
Bank Sta=4969.7,5040.2
XS Rating Curve= 0 ,0
Exp/Cntr=0.3,0.1

Type RM Length L Ch R = 1 ,1119    ,407,407,407
BEGIN DESCRIPTION:
UNT017 IN BECR 2.0
END DESCRIPTION:
XS GIS Cut Line= 3
      3838559.33     10500637.05      3838350.98     10501234.31
      3838344.04     10501532.97
#Sta/Elev= 30
  4456.7  389.93  4468.2   389.5  4473.5  388.42  4504.5  385.59  4555.3  379.92
  4566.7  377.65  4587.1  376.09  4618.2  372.39  4654.6  370.04  4680.4  367.13
  4747.8  362.62  4756.6  361.17  4773.6  359.97  4873.1  355.93    4960  354.72
    4979  355.01  4984.3  354.54    4991  352.64  4997.2  348.28  4999.9  347.78
  5003.2  348.28  5010.8     351  5016.8  354.41  5089.3  356.16  5209.7  364.22
  5265.2  366.57  5275.2  367.62  5285.2  367.24  5334.6  368.59    5388  369.78
#Mann= 5 ,-1 , 0
  4456.7     .05       0  4997.2     .03       0  5003.2     .05       0
  5209.7     .16       0  5334.6     .05       0
Bank Sta=4979,5016.8
XS Rating Curve= 0 ,0
Exp/Cntr=0.3,0.1

Type RM Length L Ch R = 1 ,712     ,542,542,542
BEGIN DESCRIPTION:
Mapping XS 30c62861
END DESCRIPTION:
XS GIS Cut Line= 3
      3838420.41     10500442.67      3838114.87     10500911.39
      3838083.67     10501375.93
#Sta/Elev= 30
  4295.2  388.18  4316.1  386.87  4329.1  384.79  4338.2  384.98  4344.2  383.49
  4423.5  376.52  4459.4  374.36    4474  372.58    4519  369.83  4567.5   365.9
  4633.9  363.19  4639.9  362.27  4721.5  359.64  4727.5  358.64  4778.8  357.26
    4821  354.61  4893.6   353.1  4963.8  353.07  4983.8  351.61  5005.4  347.15
  5008.1  346.65  5011.4  347.15  5023.9     353    5094  355.33  5134.1  358.26
  5152.6  360.83  5184.3  362.94  5284.5  367.02  5302.9  368.48  5320.3  368.46
#Mann= 4 ,-1 , 0
  4295.2     .05       0  5005.4     .03       0  5011.4     .05       0
  5152.6     .16       0
Bank Sta=4963.8,5023.9
XS Rating Curve= 0 ,0
Exp/Cntr=0.3,0.1

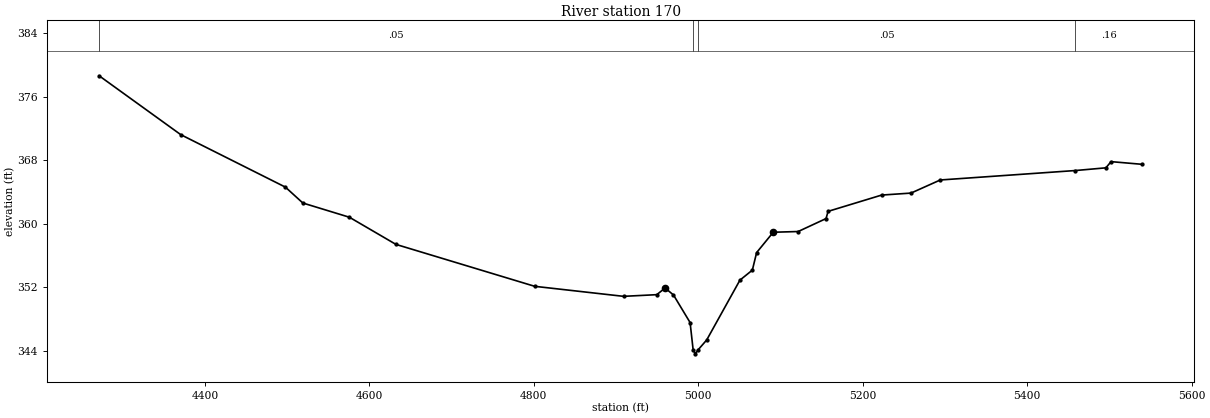
Type RM Length L Ch R = 1 ,170     ,0,0,0
BEGIN DESCRIPTION:
UNT017 IN BECR 1.0
END DESCRIPTION:
XS GIS Cut Line= 4
      3838128.77     10500269.03      3837753.76     10500644.03
      3837701.68     10500991.26      3837926.65     10501306.21
#Sta/Elev= 30
  4271.5  378.64  4370.7  371.23    4498  364.62  4519.2  362.62  4575.8  360.83
  4632.4  357.41  4801.2  352.13  4909.2  350.87  4949.6  351.08  4959.7  351.92
  4969.9  351.04  4990.1  347.57  4993.8  344.13  4996.5  343.63  4999.8  344.13
  5010.3  345.38  5050.7  352.91  5065.8  354.17    5071  356.38  5091.2  358.94
  5121.5  359.03  5155.4  360.66  5157.9  361.57    5223  363.62  5258.7  363.87
  5294.3  365.52  5458.7  366.71  5495.7  367.05    5502  367.83    5540  367.49
#Mann= 4 ,-1 , 0
  4271.5     .05       0  4993.8     .03       0  4999.8     .05       0
  5458.7     .16       0
Bank Sta=4959.7,5091.2
XS Rating Curve= 0 ,0
Exp/Cntr=0.3,0.1

Chan Stop Cuts=-1
Use User Specified Reach Order=0
Composite Channel Slope=5