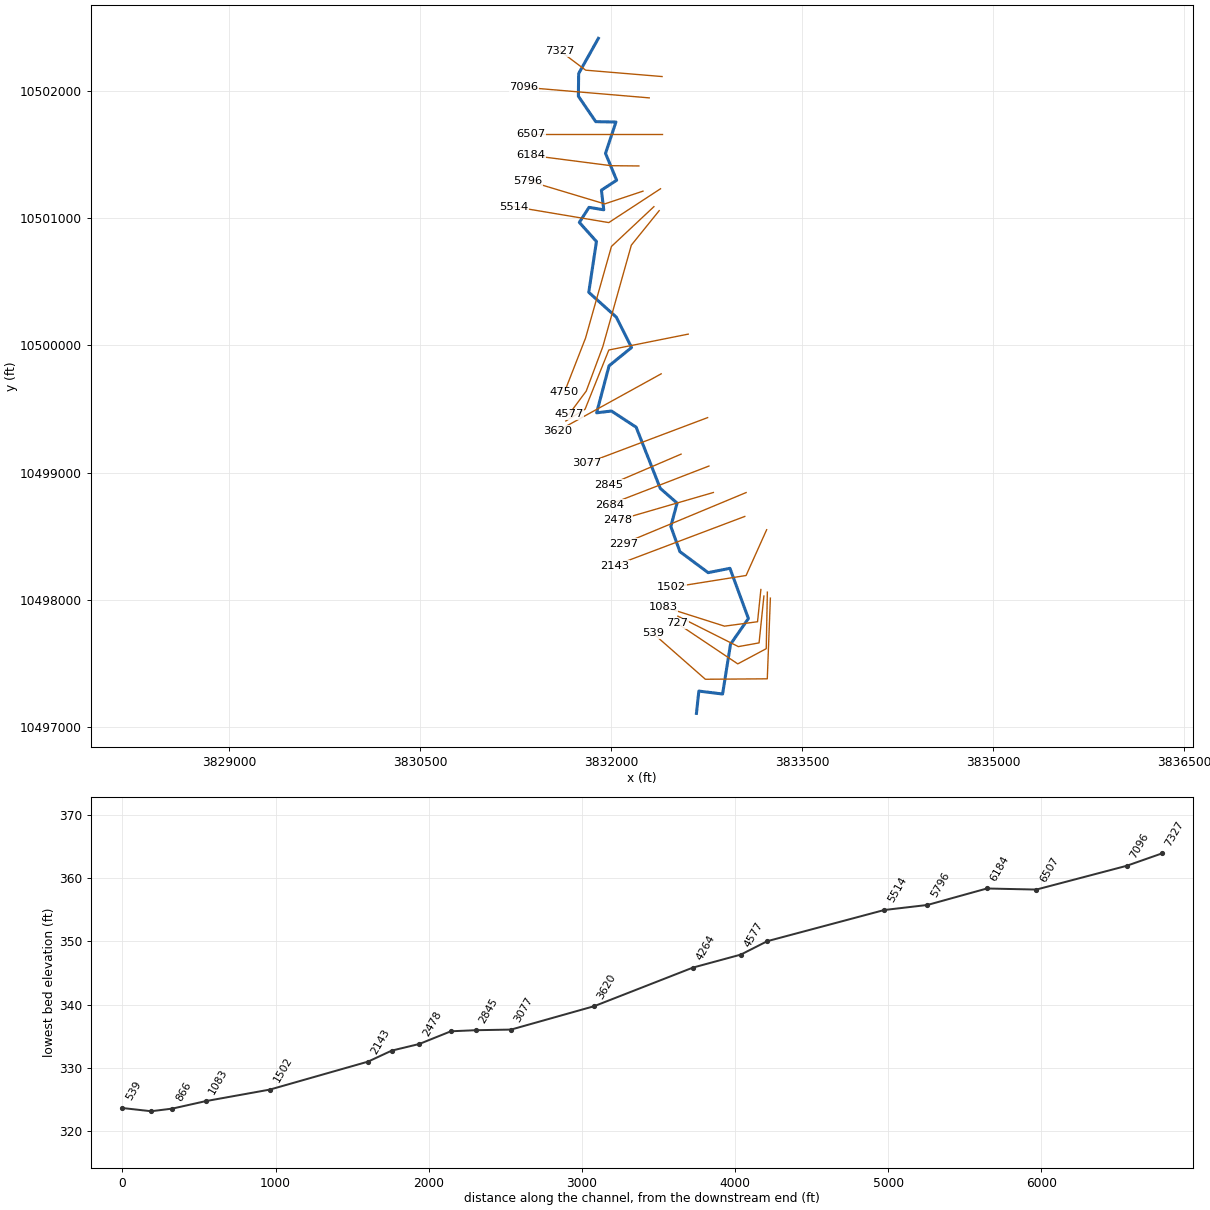
--- UNT019 IN BECR.prj (project) ---

Proj Title=UNT019 IN BECR Base Level Engineering
Current Plan=p01
Default Exp/Contr=0.3,0.1
English Units
Geom File=g01
Flow File=f01
Plan File=p01
Y Axis Title=Elevation
X Axis Title(PF)=Main Channel Distance
X Axis Title(XS)=Station
BEGIN DESCRIPTION:
UNT019 IN BECR
END DESCRIPTION:
DSS Export Rating Curves= 0
DSS Export Rating Curve Sorted= 0
DSS Export Volume Flow Curves= 0
DXF OffsetX= 0
DXF OffsetY= 0
DXF ScaleX= 1
DXF ScaleY= 10

--- UNT019 IN BECR.p01 (plan) ---

Plan Title=Multiple Run
Short Identifier=Multiple
Geom File=g01
Flow File=f01
Subcritical Flow
K Sum by GR= 0
Std Step Tol= 0.01
Critical Tol= 0.01
Num of Std Step Trials= 20
Max Error Tol= 0.3
Flow Tol Ratio= 0.001
Split Flow NTrial= 30
Split Flow Tol= 0.02
Split Flow Ratio= 0.02
Log Output Level= 0
Friction Slope Method= 1
Unsteady Friction Slope Method= 2
Unsteady Bridges Friction Slope Method= 1
Parabolic Critical Depth
Global Vel Dist=  1 , 1 , 1
Global Log Level= 0
CheckData=True
Encroach Param= -1, 0, 0, 0
BEGIN DESCRIPTION:
Multiple Run
END DESCRIPTION:

--- UNT019 IN BECR.f01 (steady flow) ---

Flow Title=Multiple
Program Version=4.10
Number of Profiles= 7
Profile Names=10-year,25-year,50-year,1pct_min,100-year,1pct_plu,500-year
River Rch & RM=UNT019 IN BECR,Reach-1         ,7327
     382     499     591     515     697     943     972
Boundary for River Rch & Prof#=UNT019 IN BECR,Reach-1         , 1
Up Type= 0
Dn Type= 3
Dn Slope=0.0056
Boundary for River Rch & Prof#=UNT019 IN BECR,Reach-1         , 2
Up Type= 0
Dn Type= 3
Dn Slope=0.0056
Boundary for River Rch & Prof#=UNT019 IN BECR,Reach-1         , 3
Up Type= 0
Dn Type= 3
Dn Slope=0.0056
Boundary for River Rch & Prof#=UNT019 IN BECR,Reach-1         , 4
Up Type= 0
Dn Type= 3
Dn Slope=0.0056
Boundary for River Rch & Prof#=UNT019 IN BECR,Reach-1         , 5
Up Type= 0
Dn Type= 3
Dn Slope=0.0056
Boundary for River Rch & Prof#=UNT019 IN BECR,Reach-1         , 6
Up Type= 0
Dn Type= 3
Dn Slope=0.0056
Boundary for River Rch & Prof#=UNT019 IN BECR,Reach-1         , 7
Up Type= 0
Dn Type= 3
Dn Slope=0.0056
DSS Import GetInterval= 0
DSS Import GetPeak= 0
DSS Import FillOption= 0

--- UNT019 IN BECR.g01 (geometry) ---

Geom Title=Existing Conditions
Program Version=4.10

River Reach=UNT019 IN BECR  ,Reach-1
Reach XY= 30
      3831899.61     10502410.19      3831744.75       10502134.
      3831742.25       10501956.      3831878.75       10501756.
      3832037.25       10501753.       3831955.5       10501507.
        3832043.       10501296.      3831923.25       10501218.
      3831941.75       10501064.        3831826.       10501083.
        3831750.       10500965.      3831884.25       10500815.
        3831824.       10500416.        3832040.     10500221.47
      3832160.02      10499982.7       3831983.5       10499839.
      3831885.75       10499470.        3832002.       10499484.
        3832196.       10499357.      3832385.25       10498877.
       3832517.5       10498761.      3832468.25       10498578.
       3832539.5       10498380.       3832761.5       10498215.
       3832932.5       10498249.       3833077.5       10497855.
        3832937.       10497653.      3832874.75       10497262.
      3832688.25       10497285.       3832669.5       10497110.

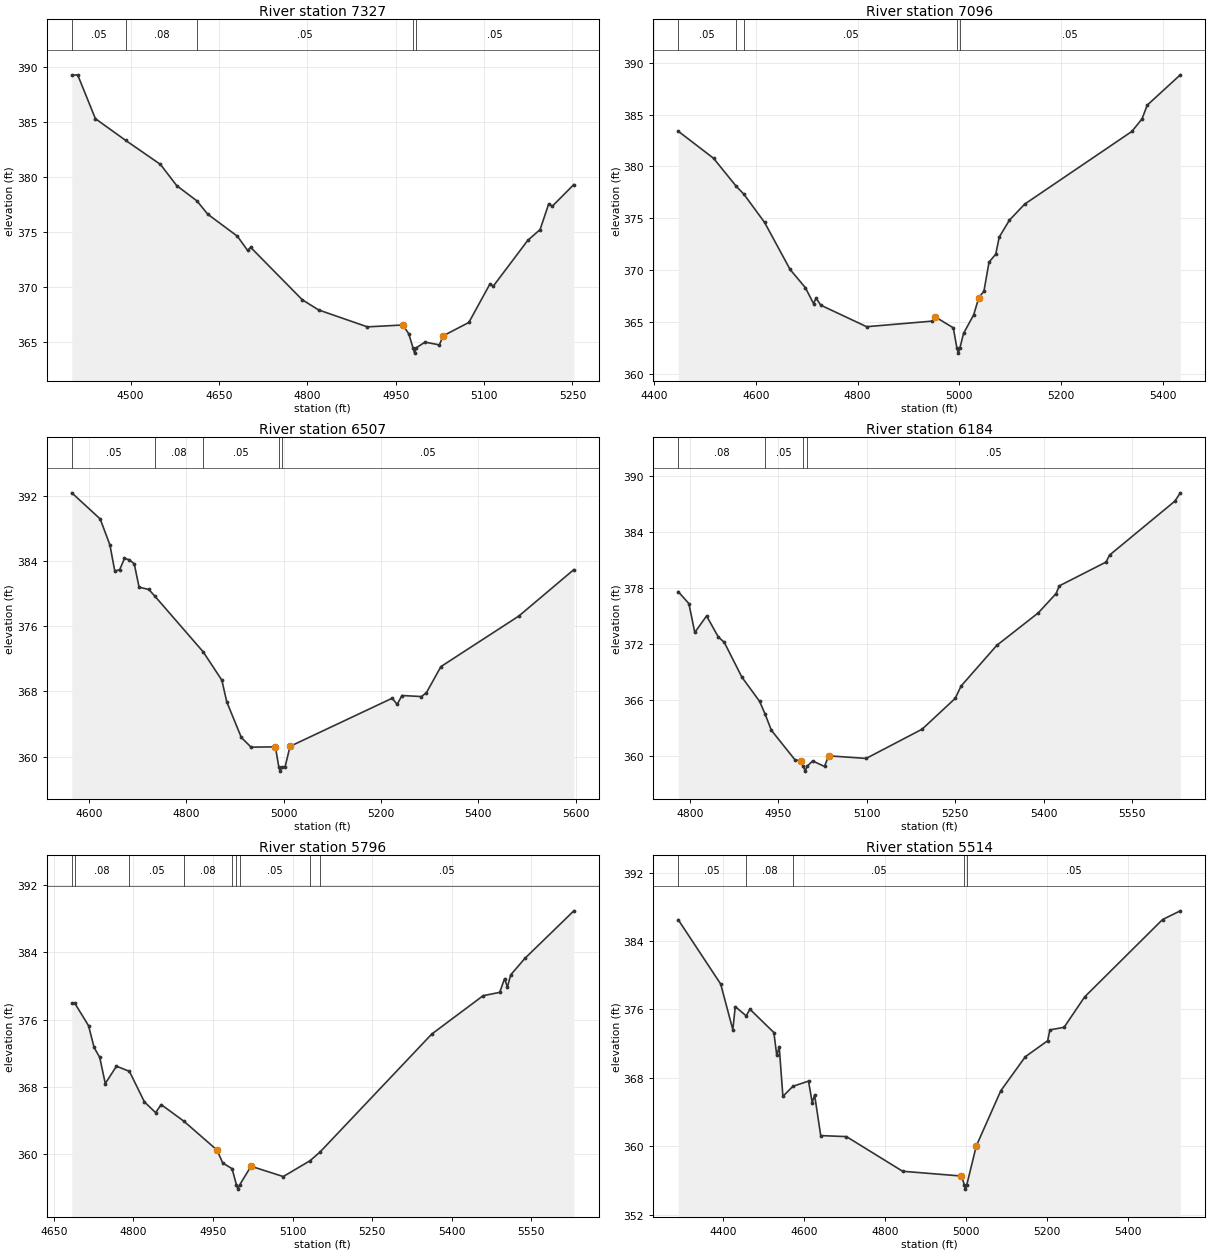
Type RM Length L Ch R = 1 ,7327    ,231,231,231
BEGIN DESCRIPTION:
UNT019 IN BECR 13.0
END DESCRIPTION:
XS GIS Cut Line= 3
       3832399.6     10502110.19      3831799.61     10502160.19
      3831599.59     10502310.21
#Sta/Elev= 30
  4400.3  389.23  4410.3  389.27  4440.4  385.28  4491.9   383.3  4550.8  381.12
  4578.4  379.19  4612.7   377.8  4631.1  376.59  4681.3  374.59  4698.8  373.29
  4703.8  373.58  4791.6   368.8  4819.2  367.88    4902  366.34  4962.2  366.51
  4972.3   365.7  4979.3  364.45  4982.1  363.95  4985.3  364.45  4999.9  364.95
  5024.2   364.7  5030.5  365.52  5074.2  366.74  5109.7  370.21  5115.9  370.06
  5174.2  374.21  5195.1  375.19  5209.7  377.52  5215.9  377.32  5252.4  379.29
#Mann= 5 ,-1 , 0
  4400.3     .05       0  4491.9     .08       0  4612.7     .05       0
  4979.3     .03       0  4985.3     .05       0
Bank Sta=4962.2,5030.5
XS Rating Curve= 0 ,0
Exp/Cntr=0.3,0.1

Type RM Length L Ch R = 1 ,7096    ,589,589,589
BEGIN DESCRIPTION:
UNT019 IN BECR 12.0
END DESCRIPTION:
XS GIS Cut Line= 2
      3832298.88     10501942.65      3831314.61     10502025.97
#Sta/Elev= 30
  4447.1  383.39  4516.6  380.78  4560.6  378.11  4576.3  377.31    4617  374.59
  4667.2  370.05  4697.3  368.29  4713.3  366.76  4718.3   367.3  4727.4  366.61
  4817.7  364.53  4947.3  365.07  4952.3  365.49  4988.3  364.42  4995.3  362.48
  4998.1  361.98  5001.3  362.48  5008.4  363.88  5028.4  365.68  5038.5  367.34
  5048.5  367.95  5058.6  370.76  5071.8  371.53  5078.6  373.17  5098.7  374.81
  5128.8  376.36  5339.6  383.37  5359.6  384.58  5369.7   385.9  5434.9  388.83
#Mann= 5 ,-1 , 0
  4447.1     .05       0  4560.6     .08       0  4576.3     .05       0
  4995.3     .03       0  5001.3     .05       0
Bank Sta=4952.3,5038.5
XS Rating Curve= 0 ,0
Exp/Cntr=0.3,0.1

Type RM Length L Ch R = 1 ,6507    ,323,323,323
BEGIN DESCRIPTION:
Mapping XS 0499d069
END DESCRIPTION:
XS GIS Cut Line= 2
      3832397.86     10501661.39      3831366.56     10501661.39
#Sta/Elev= 30
  4564.9  392.37  4623.2  389.17  4643.2  385.99  4653.2  382.79  4663.2  382.93
  4673.2  384.32  4683.2  384.15  4693.2  383.66  4703.2  380.79  4723.2  380.51
  4735.9  379.67  4834.8  372.86  4873.2  369.38  4883.2  366.73  4913.2  362.35
  4933.2  361.16  4983.2   361.2  4990.2  358.72  4992.9  358.22  4996.2  358.72
  5003.2  358.77  5013.2  361.26  5223.2  367.17  5233.2   366.4  5243.2   367.5
  5283.2  367.37  5293.2  367.83  5323.2  371.05  5483.2  377.25  5596.2  382.95
#Mann= 5 ,-1 , 0
  4564.9     .05       0  4735.9     .08       0  4834.8     .05       0
  4990.2     .03       0  4996.2     .05       0
Bank Sta=4983.2,5013.2
XS Rating Curve= 0 ,0
Exp/Cntr=0.3,0.1

Type RM Length L Ch R = 1 ,6184    ,388,388,388
BEGIN DESCRIPTION:
UNT019 IN BECR 11.0
END DESCRIPTION:
XS GIS Cut Line= 3
      3832217.73     10501408.16      3831999.61     10501410.19
      3831370.47     10501491.49
#Sta/Elev= 30
  4779.8  377.62  4797.9  376.34  4807.9  373.25  4827.9  375.02  4847.9  372.76
  4857.9   372.2  4887.9  368.46  4917.9  365.87    4927  364.55  4937.9  362.77
  4977.9  359.61  4987.9  359.48  4992.4  358.89  4995.2  358.39  4998.4  358.89
    5008  359.48  5028.2  358.89  5035.1  360.03  5098.8  359.75  5193.8  362.88
    5250  366.18  5260.1  367.51  5320.6  371.86  5391.2  375.35  5421.4  377.42
  5426.8  378.24  5506.1  380.79  5512.2  381.54  5623.1  387.32  5632.3  388.21
#Mann= 4 ,-1 , 0
  4779.8     .08       0    4927     .05       0  4992.4     .03       0
  4998.4     .05       0
Bank Sta=4987.9,5035.1
XS Rating Curve= 0 ,0
Exp/Cntr=0.3,0.1

Type RM Length L Ch R = 1 ,5796    ,282,282,282
BEGIN DESCRIPTION:
UNT019 IN BECR 10.0
END DESCRIPTION:
XS GIS Cut Line= 3
      3832249.57     10501210.18      3831949.61     10501110.19
      3831345.76     10501291.61
#Sta/Elev= 30
  4683.7  377.94  4689.5  377.93  4715.3  375.27  4725.8  372.67  4736.4  371.49
  4746.9  368.37    4768  370.44  4792.4  369.82  4820.7  366.18  4841.8   364.9
  4852.3  365.86  4895.3  363.87  4957.7  360.43  4968.3   358.9  4985.9  358.22
  4994.3  356.28    4997  355.78  5000.3  356.28  5021.6  358.51  5082.5  357.28
  5132.8  359.16  5151.6  360.19  5362.5  374.27  5459.3  378.84  5490.6  379.24
  5499.8  380.88  5505.1  379.88  5511.5  381.34  5538.1  383.29  5630.4  388.96
#Mann= 9 ,-1 , 0
  4683.7     .05       0  4689.5     .08       0  4792.4     .05       0
  4895.3     .08       0  4985.9     .05       0  4994.3     .03       0
  5000.3     .05       0  5132.8     .08       0  5151.6     .05       0
Bank Sta=4957.7,5021.6
XS Rating Curve= 0 ,0
Exp/Cntr=0.3,0.1

Type RM Length L Ch R = 1 ,5514    ,764,764,764
BEGIN DESCRIPTION:
UNT019 IN BECR 9.0
END DESCRIPTION:
XS GIS Cut Line= 3
      3832387.42     10501229.09      3831981.19     10500963.48
      3831236.36     10501088.48
#Sta/Elev= 30
  4288.4  386.48  4393.3  378.96  4423.3  373.62  4429.3  376.32  4456.4  375.24
  4465.5  376.02  4524.7  373.29  4531.9  370.61  4537.9  371.64    4547  365.83
  4571.7     367  4610.3  367.61  4619.4   365.1  4625.4  365.98  4640.5  361.24
    4704  361.12  4842.9  357.07  4988.3  356.51  4995.4  355.48  4998.2  354.98
  5001.4  355.48  5024.8  360.02  5085.4  366.48    5146  370.46  5201.2  372.33
  5206.7   373.6  5241.8   373.9  5292.5  377.45  5485.1   386.5    5529  387.52
#Mann= 5 ,-1 , 0
  4288.4     .05       0  4456.4     .08       0  4571.7     .05       0
  4995.4     .03       0  5001.4     .05       0
Bank Sta=4988.3,5024.8
XS Rating Curve= 0 ,0
Exp/Cntr=0.3,0.1

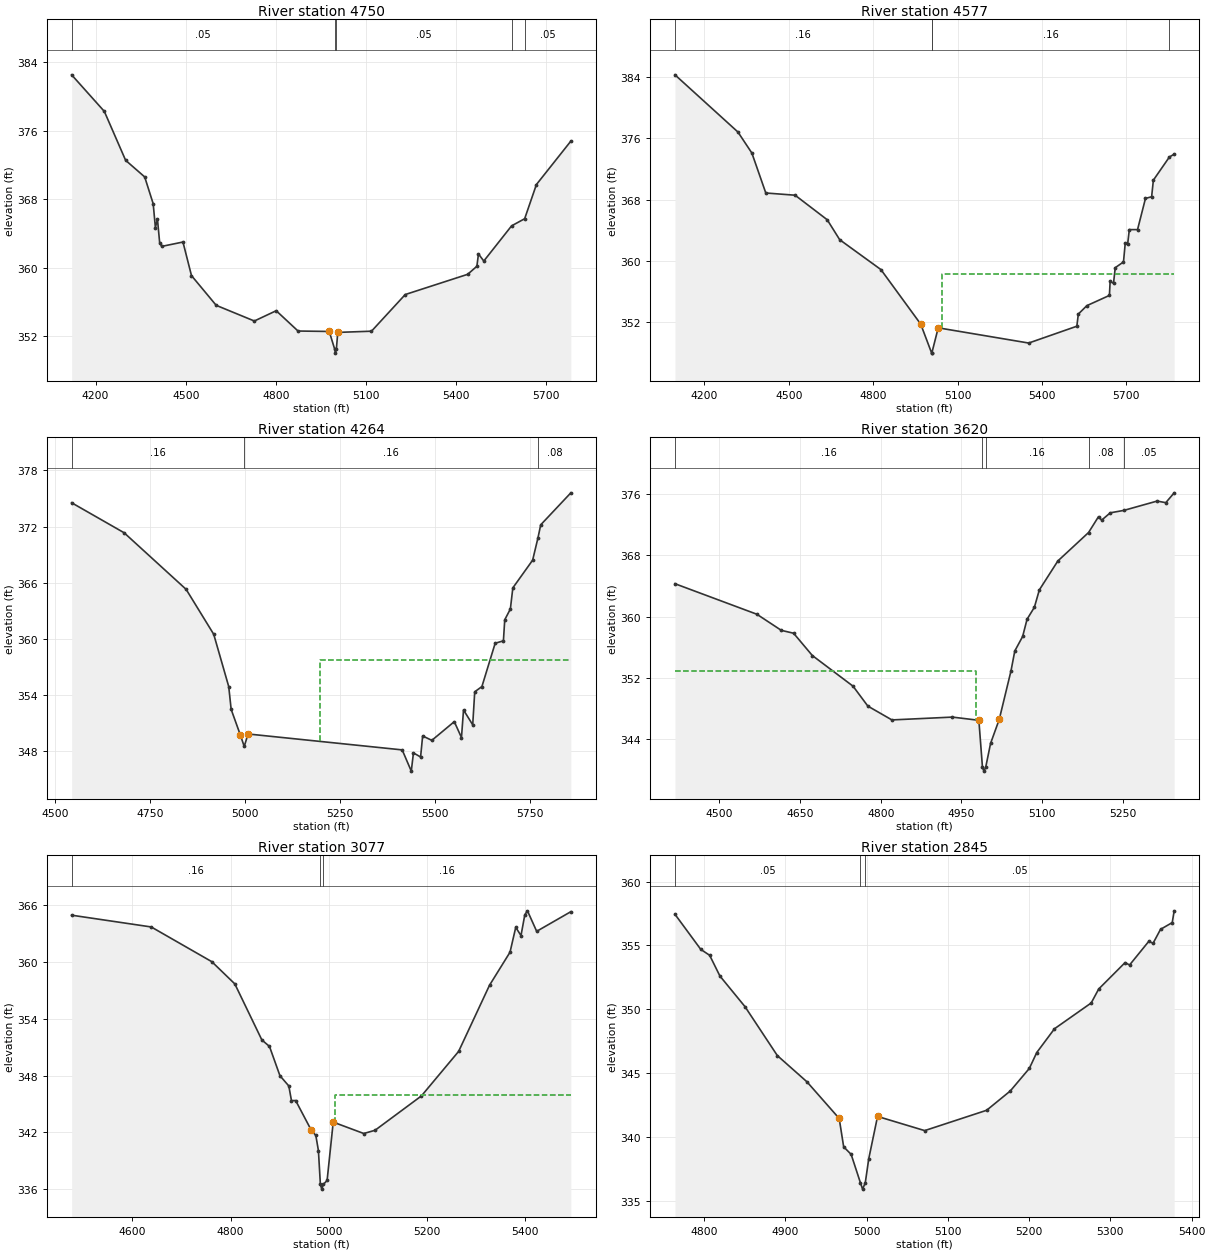
Type RM Length L Ch R = 1 ,4750    ,173,173,173
BEGIN DESCRIPTION:
UNT019 IN BECR 8.0
END DESCRIPTION:
XS GIS Cut Line= 4
      3832335.37     10501088.48      3832002.03     10500775.98
       3831798.9     10500057.23      3831632.22     10499630.12
#Sta/Elev= 30
  4120.2  382.53  4229.1  378.26    4300  372.55  4363.5  370.61  4391.8  367.48
  4399.1   364.7    4406  365.67  4413.3  362.95  4420.1   362.5  4490.9  363.01
  4519.3  359.09  4601.6  355.62  4728.6  353.79  4801.4  354.99  4874.1  352.62
    4978  352.57  4995.8  350.54  4998.6  350.04  5001.8  350.54  5006.4  352.46
  5118.7   352.6  5231.1  356.88  5438.9  359.24  5469.6  360.18  5474.9  361.62
  5492.6  360.79  5585.2   364.9  5628.7  365.73  5667.8  369.72  5782.5  374.79
#Mann= 5 ,-1 , 0
  4120.2     .05       0  4995.8     .03       0  5001.8     .05       0
  5585.2     .08       0  5628.7     .05       0
Bank Sta=4978,5006.4
XS Rating Curve= 0 ,0
Exp/Cntr=0.3,0.1

Type RM Length L Ch R = 1 ,4577    ,313,313,313
BEGIN DESCRIPTION:
UNT019 IN BECR 7.0
END DESCRIPTION:
XS GIS Cut Line= 5
      3832377.05     10501057.26      3832158.28     10500786.39
      3831934.32     10499989.52      3831804.11     10499640.56
      3831668.68     10499458.25
#Sta/Elev= 30
    4095  384.32  4318.9  376.84  4368.5  374.09  4418.1  368.86  4522.3  368.57
  4636.5  365.36  4680.9  362.75  4827.5  358.84    4969  351.71    5008  347.91
  5008.5  347.91  5031.3  351.22  5353.1  349.23  5524.3  351.43  5529.6  353.02
  5559.9  354.12  5640.2  355.46  5642.7   357.3  5654.7  357.04  5660.9  359.09
  5690.2  359.84  5696.4  362.28  5704.8  362.13    5711  364.07  5740.2  364.07
  5768.4  368.15  5790.3  368.37  5796.5  370.54  5853.5  373.57  5870.5  373.94
#Mann= 4 ,-1 , 0
    4095     .16       0    5008     .07       0  5008.5     .16       0
  5853.5     .08       0
#XS Ineff= 2 , 0
                         5044.32          358.27
Permanent Ineff=
       F       F
Bank Sta=4969,5031.3
XS Rating Curve= 0 ,0
Exp/Cntr=0.3,0.1

Type RM Length L Ch R = 1 ,4264    ,644,644,644
BEGIN DESCRIPTION:
Mapping XS 931ee75d
END DESCRIPTION:
XS GIS Cut Line= 4
      3832605.13     10500087.79      3831981.57     10499963.07
      3831795.19     10499498.48      3831643.82     10499405.75
#Sta/Elev= 30
  4543.9  374.54  4682.1  371.33  4845.3  365.28  4917.9  360.48  4957.4  354.89
  4963.8  352.45    4988  349.71  4998.2  348.49  5008.4  349.82    5414  348.12
  5437.9  345.85  5443.6   347.8  5462.4  347.36  5467.8  349.61    5492  349.14
  5551.1  351.14    5570  349.44  5575.4  352.39  5599.6   350.8  5604.9  354.33
  5623.8  354.89  5658.7  359.52  5680.4  359.78  5683.9  362.03  5698.7  363.18
  5705.2  365.44  5757.3   368.4  5771.2  370.76  5778.6  372.18  5857.9   375.6
#Mann= 3 ,-1 , 0
  4543.9     .16       0  4998.2     .16       0  5771.2     .08       0
#XS Ineff= 2 , 0
                         5196.36           357.7
Permanent Ineff=
       F       F
Bank Sta=4988,5008.4
XS Rating Curve= 0 ,0
Exp/Cntr=0.3,0.1

Type RM Length L Ch R = 1 ,3620    ,543,543,543
BEGIN DESCRIPTION:
UNT019 IN BECR 5.0
END DESCRIPTION:
XS GIS Cut Line= 2
      3832392.68       10499776.      3831580.17     10499328.07
#Sta/Elev= 30
  4417.5   364.3  4569.7   360.3  4615.1  358.19    4638  357.81  4672.8  354.89
  4748.5  350.87    4776  348.26  4820.7  346.45  4933.1  346.82  4982.3   346.4
    4989  340.24  4991.7  339.74    4995  340.24  5004.1  343.38  5020.2  346.52
    5042  352.87  5049.1  355.49  5063.7  357.39  5071.9  359.65  5085.5  361.21
  5094.7  363.49  5129.1  367.28  5186.2  371.01  5204.7  373.09  5210.5  372.63
  5226.5  373.59  5251.9  373.91  5313.6  375.13  5329.7  374.92  5345.3  376.21
#Mann= 5 ,-1 , 0
  4417.5     .16       0    4989     .07       0    4995     .16       0
  5186.2     .08       0  5251.9     .05       0
#XS Ineff= 2 , 0
         4977.84  352.85
Permanent Ineff=
       F       F
Bank Sta=4982.3,5020.2
XS Rating Curve= 0 ,0
Exp/Cntr=0.3,0.1

Type RM Length L Ch R = 1 ,3077    ,232,232,232
BEGIN DESCRIPTION:
UNT019 IN BECR 4.0
END DESCRIPTION:
XS GIS Cut Line= 2
      3832757.22     10499432.22       3831804.4     10499072.96
#Sta/Elev= 30
  4475.9  364.89  4638.3  363.65  4761.9  359.99  4808.8  357.65  4863.9  351.75
  4879.5  351.06  4900.8  347.98  4918.9   346.9  4924.3  345.36  4932.9  345.36
    4965  342.21    4974  341.69  4979.3  340.09  4983.3  336.53  4986.1  336.03
  4989.3  336.53    4997  336.94  5009.5  343.09  5071.8  341.89  5094.8  342.23
  5189.4  345.85  5265.3  350.54  5328.3  357.51  5370.1  360.99  5381.8  363.61
  5392.5  362.74  5400.3  364.94  5405.7  365.35  5424.5  363.19  5494.2  365.26
#Mann= 3 ,-1 , 0
  4475.9     .16       0  4983.3     .07       0  4989.3     .16       0
#XS Ineff= 2 , 0
                         5013.64          345.95
Permanent Ineff=
       F       F
Bank Sta=4965,5009.5
XS Rating Curve= 0 ,0
Exp/Cntr=0.3,0.1

Type RM Length L Ch R = 1 ,2845    ,161,161,161
BEGIN DESCRIPTION:
Mapping XS 7e46389a
END DESCRIPTION:
XS GIS Cut Line= 2
      3832548.83     10499145.49       3831984.2      10498903.5
#Sta/Elev= 30
  4764.2  357.44    4796  354.69  4806.9  354.23  4819.5  352.61  4850.4  350.21
  4890.2  346.38  4926.6  344.33  4966.3  341.46  4971.8  339.24    4981  338.65
  4992.4  336.43  4995.1  335.93  4998.4  336.43  5002.7  338.32  5013.5  341.62
  5071.5  340.51  5147.7   342.1  5176.8  343.61  5200.3  345.38  5209.4  346.62
  5231.2  348.48  5276.4   350.5  5285.6  351.59  5318.1  353.66  5323.6  353.47
  5347.1  355.31  5352.6  355.18  5361.7  356.26  5376.1  356.79  5378.5  357.71
#Mann= 3 ,-1 , 0
  4764.2     .05       0  4992.4     .03       0  4998.4     .05       0
Bank Sta=4966.3,5013.5
XS Rating Curve= 0 ,0
Exp/Cntr=0.3,0.1

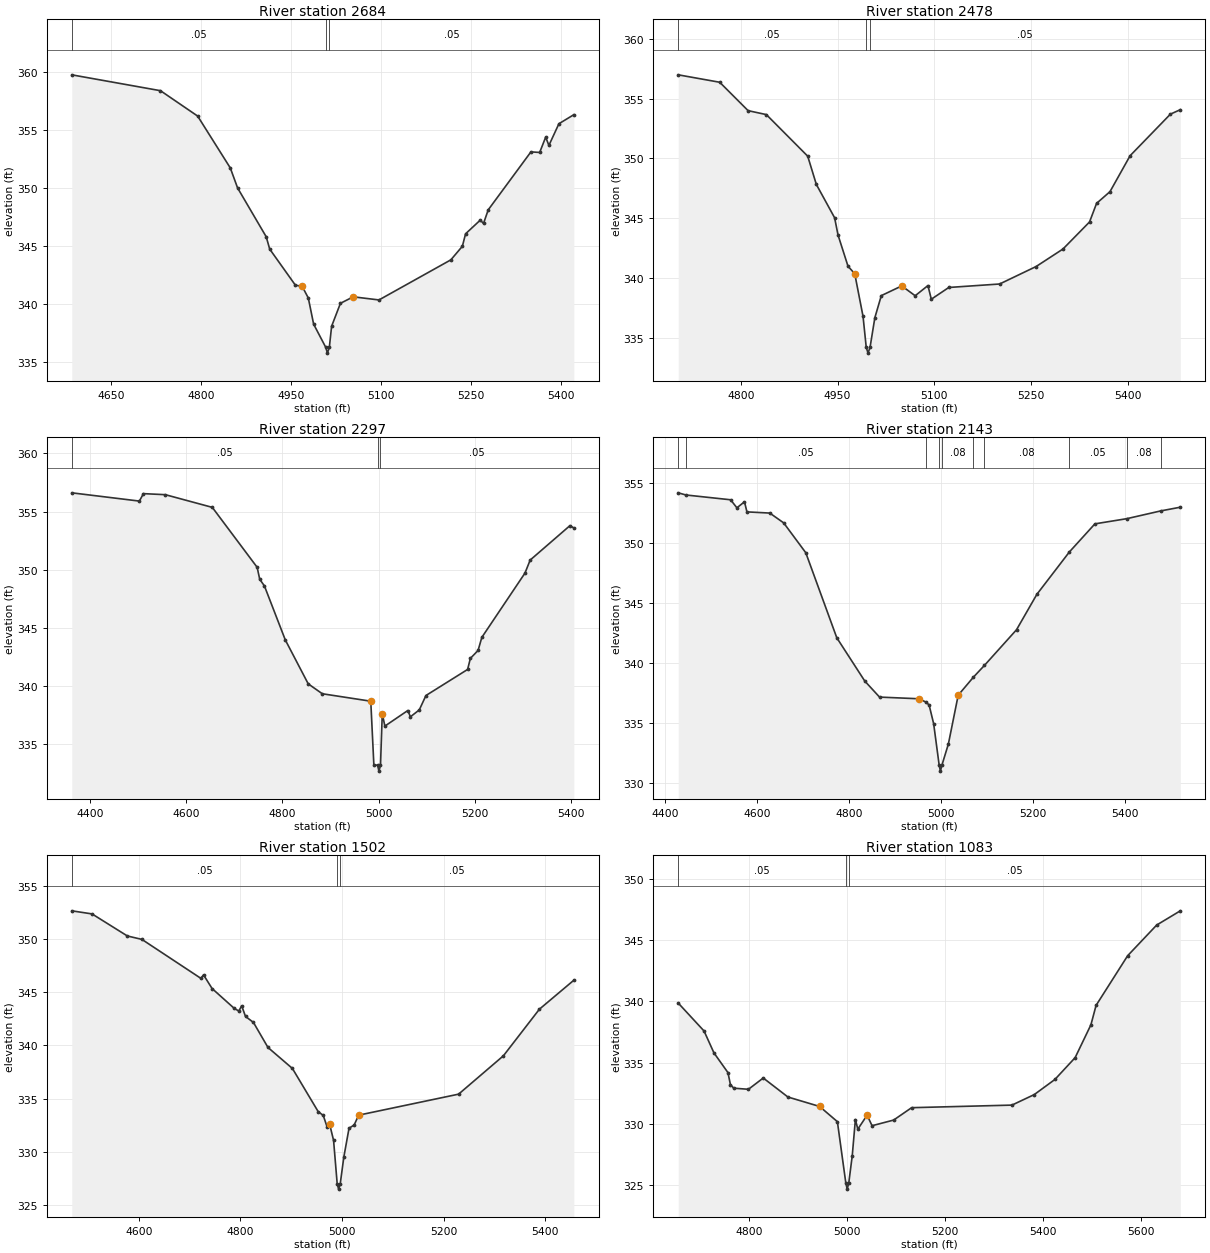
Type RM Length L Ch R = 1 ,2684    ,206,206,206
BEGIN DESCRIPTION:
UNT019 IN BECR 3.0
END DESCRIPTION:
XS GIS Cut Line= 2
      3832767.63     10499052.01       3831986.4     10498749.94
#Sta/Elev= 30
  4584.2  359.78  4732.2  358.41  4794.2  356.22  4848.7  351.74  4860.8  350.02
  4908.6   345.8  4914.4  344.74  4957.3  341.62  4968.5  341.53  4978.8  340.52
  4987.7  338.26  5007.9  336.26  5010.7  335.76  5013.9  336.26  5017.7  338.08
  5032.4  340.06  5053.8  340.62  5096.7  340.35  5216.6  343.81  5235.8  344.98
  5241.2  346.06  5265.7  347.24  5271.1  346.95    5279  348.13  5350.2  353.13
  5364.8  353.08  5374.8   354.4  5380.2  353.69  5396.9  355.56  5421.8  356.34
#Mann= 3 ,-1 , 0
  4584.2     .05       0  5007.9     .03       0  5013.9     .05       0
Bank Sta=4968.5,5053.8
XS Rating Curve= 0 ,0
Exp/Cntr=0.3,0.1

Type RM Length L Ch R = 1 ,2478    ,181,181,181
BEGIN DESCRIPTION:
Mapping XS b7d60bae
END DESCRIPTION:
XS GIS Cut Line= 2
      3832802.36     10498844.29      3832054.93     10498627.27
#Sta/Elev= 30
  4703.1  356.98  4767.4  356.36  4811.4  353.99  4839.7  353.66  4903.8  350.19
  4917.2  347.83  4945.5  345.05  4950.8  343.61  4966.3     341  4976.7  340.38
  4989.6  336.81  4994.5  334.25  4997.3  333.75  5000.5  334.25  5007.9  336.71
  5017.9  338.55  5049.6  339.36  5070.4  338.54  5090.2  339.39  5095.4  338.25
  5122.5  339.23  5201.3  339.52  5257.9  340.98  5299.5  342.44  5340.7   344.7
  5351.6  346.25  5372.4  347.23  5403.6  350.23  5466.1   353.7  5481.4  354.07
#Mann= 3 ,-1 , 0
  4703.1     .05       0  4994.5     .03       0  5000.5     .05       0
Bank Sta=4976.7,5049.6
XS Rating Curve= 0 ,0
Exp/Cntr=0.3,0.1

Type RM Length L Ch R = 1 ,2297    ,154,154,154
BEGIN DESCRIPTION:
Mapping XS 432ce89a
END DESCRIPTION:
XS GIS Cut Line= 2
      3833059.28     10498843.67      3832095.81     10498442.66
#Sta/Elev= 30
  4362.3  356.61  4502.8   355.9  4511.3  356.54  4556.9  356.45  4654.4  355.36
  4747.6  350.21    4753  349.18  4762.7  348.61  4806.1  343.97  4853.8  340.19
  4883.1  339.34  4983.8   338.7  4990.2  333.24    4998  333.19  5000.8  332.69
    5004  333.19  5007.7  337.63  5013.1  336.56  5060.8   337.9  5066.2  337.36
  5084.6  337.95  5098.5  339.19  5185.1  341.43  5190.8  342.38  5206.8  343.06
  5214.7  344.19  5304.3  349.71  5315.1  350.83  5397.8  353.79  5405.9  353.59
#Mann= 3 ,-1 , 0
  4362.3     .05       0    4998     .03       0    5004     .05       0
Bank Sta=4983.8,5007.7
XS Rating Curve= 0 ,0
Exp/Cntr=0.3,0.1

Type RM Length L Ch R = 1 ,2143    ,641,641,641
BEGIN DESCRIPTION:
UNT019 IN BECR 2.0
END DESCRIPTION:
XS GIS Cut Line= 2
      3833048.91     10498656.19      3832028.05     10498270.76
#Sta/Elev= 30
  4428.9  354.18  4445.6     354  4542.7   353.6  4556.4  352.93  4572.9  353.43
  4578.2  352.59  4627.9  352.49  4658.1  351.67  4706.1  349.18  4773.5  342.08
  4834.3  338.47  4866.4  337.13  4951.9  336.99  4966.4  336.73  4974.1  336.48
    4984  334.91    4996  331.45  4998.7  330.95    5002  331.45    5016  333.21
  5037.4  337.29  5070.6   338.8  5094.5  339.78  5164.1  342.75  5208.4  345.71
  5278.9  349.24  5334.5  351.59  5403.5  352.02  5477.5  352.67  5520.1  352.98
#Mann= 10 ,-1 , 0
  4428.9     .08       0  4445.6     .05       0  4966.4     .08       0
    4996     .07       0    5002     .08       0  5070.6     .05       0
  5094.5     .08       0  5278.9     .05       0  5403.5     .08       0
  5477.5     .05       0
Bank Sta=4951.9,5037.4
XS Rating Curve= 0 ,0
Exp/Cntr=0.3,0.1

Type RM Length L Ch R = 1 ,1502    ,419,419,419
BEGIN DESCRIPTION:
Mapping XS c139ce56
END DESCRIPTION:
XS GIS Cut Line= 3
      3833220.77     10498552.01      3833059.32     10498192.64
      3832472.69      10498099.2
#Sta/Elev= 30
  4468.2  352.63  4508.1  352.34  4577.6  350.27  4606.2  349.95  4722.1   346.3
  4727.5  346.62  4744.3  345.34  4788.1  343.47    4797  343.23  4802.5  343.72
  4810.1  342.72  4825.7  342.16  4854.3  339.81  4902.4  337.84    4953   333.8
  4963.1  333.43  4970.7  332.35  4975.7   332.6  4983.4  331.09  4990.5  327.02
  4993.3  326.52  4996.5  327.02  5003.6  329.54  5013.8  332.23  5023.9  332.54
  5032.8  333.46  5229.4  335.43  5317.6  339.03  5388.4   343.4  5456.2  346.12
#Mann= 3 ,-1 , 0
  4468.2     .05       0  4990.5     .03       0  4996.5     .05       0
Bank Sta=4975.7,5032.8
XS Rating Curve= 0 ,0
Exp/Cntr=0.3,0.1

Type RM Length L Ch R = 1 ,1083    ,217,217,217
BEGIN DESCRIPTION:
Mapping XS 86b04725
END DESCRIPTION:
XS GIS Cut Line= 4
      3833175.42     10498082.65      3833149.16     10497829.54
      3832889.83     10497794.82      3832405.88      10497948.9
#Sta/Elev= 30
  4655.8  339.86  4708.5  337.58  4728.6   335.8  4757.2  334.19  4762.2  333.22
  4768.9  332.92    4799  332.83  4829.2  333.75  4879.5   332.2  4944.1  331.43
  4980.4  330.19  4997.6  325.19  5000.4  324.69  5003.6  325.19  5010.7  327.41
  5017.1  330.36  5022.1  329.58    5041  330.72  5051.1  329.86  5095.1  330.32
  5131.8  331.33  5336.4  331.54    5382   332.4    5424  333.63  5465.3  335.41
  5497.5  338.09    5508  339.67  5572.4  343.72  5631.6  346.22  5679.8  347.38
#Mann= 3 ,-1 , 0
  4655.8     .05       0  4997.6     .03       0  5003.6     .05       0
Bank Sta=4944.1,5041
XS Rating Curve= 0 ,0
Exp/Cntr=0.3,0.1

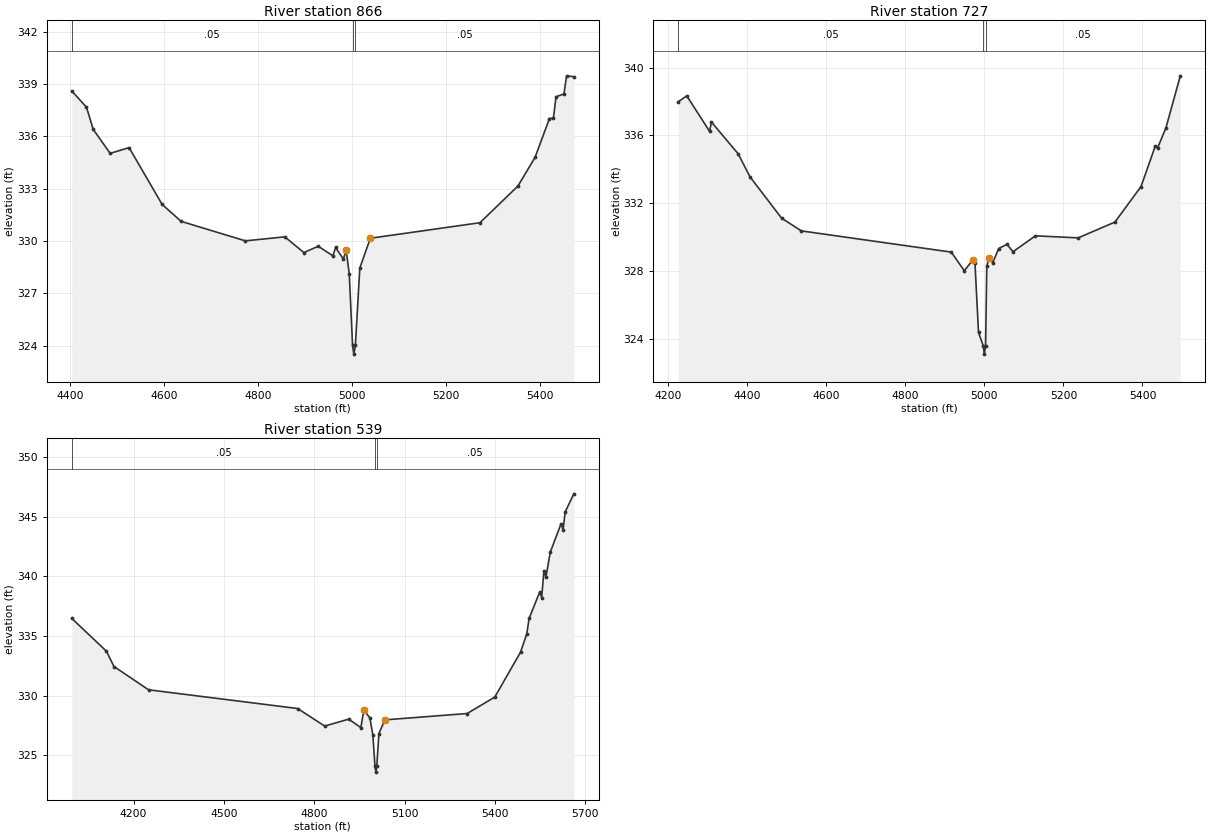
Type RM Length L Ch R = 1 ,866     ,139,139,139
BEGIN DESCRIPTION:
Mapping XS 167d8faf
END DESCRIPTION:
XS GIS Cut Line= 4
       3833199.2     10498031.31      3833161.22      10497663.5
      3832998.46      10497634.2      3832523.32     10497873.39
#Sta/Elev= 30
  4404.3  338.61  4435.6  337.68  4449.8  336.41  4485.9  335.03  4526.1  335.36
  4596.4   332.1  4636.6  331.13  4773.2  330.01    4857  330.24  4897.6  329.34
  4928.1   329.7  4959.4  329.15    4965  329.63  4981.7  328.96  4987.3  329.49
  4994.1  328.11  5001.1  324.01  5003.8  323.51  5007.1  324.01  5016.5  328.45
  5038.9  330.16  5271.8  331.05  5352.4  333.15    5389   334.8  5419.6  337.03
    5428  337.05  5433.6  338.28  5450.4  338.44    5456  339.48  5471.4  339.43
#Mann= 3 ,-1 , 0
  4404.3     .05       0  5001.1     .03       0  5007.1     .05       0
Bank Sta=4987.3,5038.9
XS Rating Curve= 0 ,0
Exp/Cntr=0.3,0.1

Type RM Length L Ch R = 1 ,727     ,188,188,188
BEGIN DESCRIPTION:
UNT019 IN BECR 1.0
END DESCRIPTION:
XS GIS Cut Line= 4
      3833226.21     10498061.78      3833217.52     10497617.95
        3832994.     10497498.59      3832517.68     10497817.63
#Sta/Elev= 30
  4225.2  337.98  4246.8  338.33  4304.3  336.24  4309.3  336.78  4376.8  334.91
  4406.8  333.55  4486.8  331.11  4536.8  330.36  4916.1  329.11  4949.1  328.01
  4970.1  328.63  4976.1  328.49  4985.1  324.37    4997  323.59  4999.8  323.09
    5003  323.59  5006.1  328.31  5012.1  328.76  5021.1  328.48  5036.1  329.32
  5057.2  329.57  5072.2  329.13  5129.2  330.07  5237.3  329.95  5330.3  330.88
  5396.4  332.98  5432.4  335.36  5438.4  335.26  5459.4  336.44  5495.8  339.51
#Mann= 3 ,-1 , 0
  4225.2     .05       0    4997     .03       0    5003     .05       0
Bank Sta=4970.1,5012.1
XS Rating Curve= 0 ,0
Exp/Cntr=0.3,0.1

Type RM Length L Ch R = 1 ,539     ,0,0,0
BEGIN DESCRIPTION:
Mapping XS 375b4f29
END DESCRIPTION:
XS GIS Cut Line= 4
      3833249.99     10498015.02      3833225.69     10497381.36
      3832739.58     10497377.88      3832328.12       10497739.
#Sta/Elev= 30
  3994.6  336.48  4109.5  333.74  4134.8  332.45  4249.6   330.5  4744.8  328.93
  4834.8  327.46  4914.8  328.04  4954.8  327.33  4964.8  328.79  4984.8  328.15
  4994.8  326.71  5001.8   324.1  5004.6   323.6  5007.8   324.1  5014.8  326.83
  5034.8  327.98  5307.8  328.51  5399.8  329.89  5485.2  333.65  5506.1  335.19
  5513.7  336.48  5548.8  338.68  5555.5  338.23    5563  340.49  5569.7  339.94
  5583.9  342.02    5620  344.42  5626.6   343.9  5633.7  345.41  5662.3  346.92
#Mann= 3 ,-1 , 0
  3994.6     .05       0  5001.8     .03       0  5007.8     .05       0
Bank Sta=4964.8,5034.8
XS Rating Curve= 0 ,0
Exp/Cntr=0.3,0.1

Chan Stop Cuts=-1
Use User Specified Reach Order=0
Composite Channel Slope=5