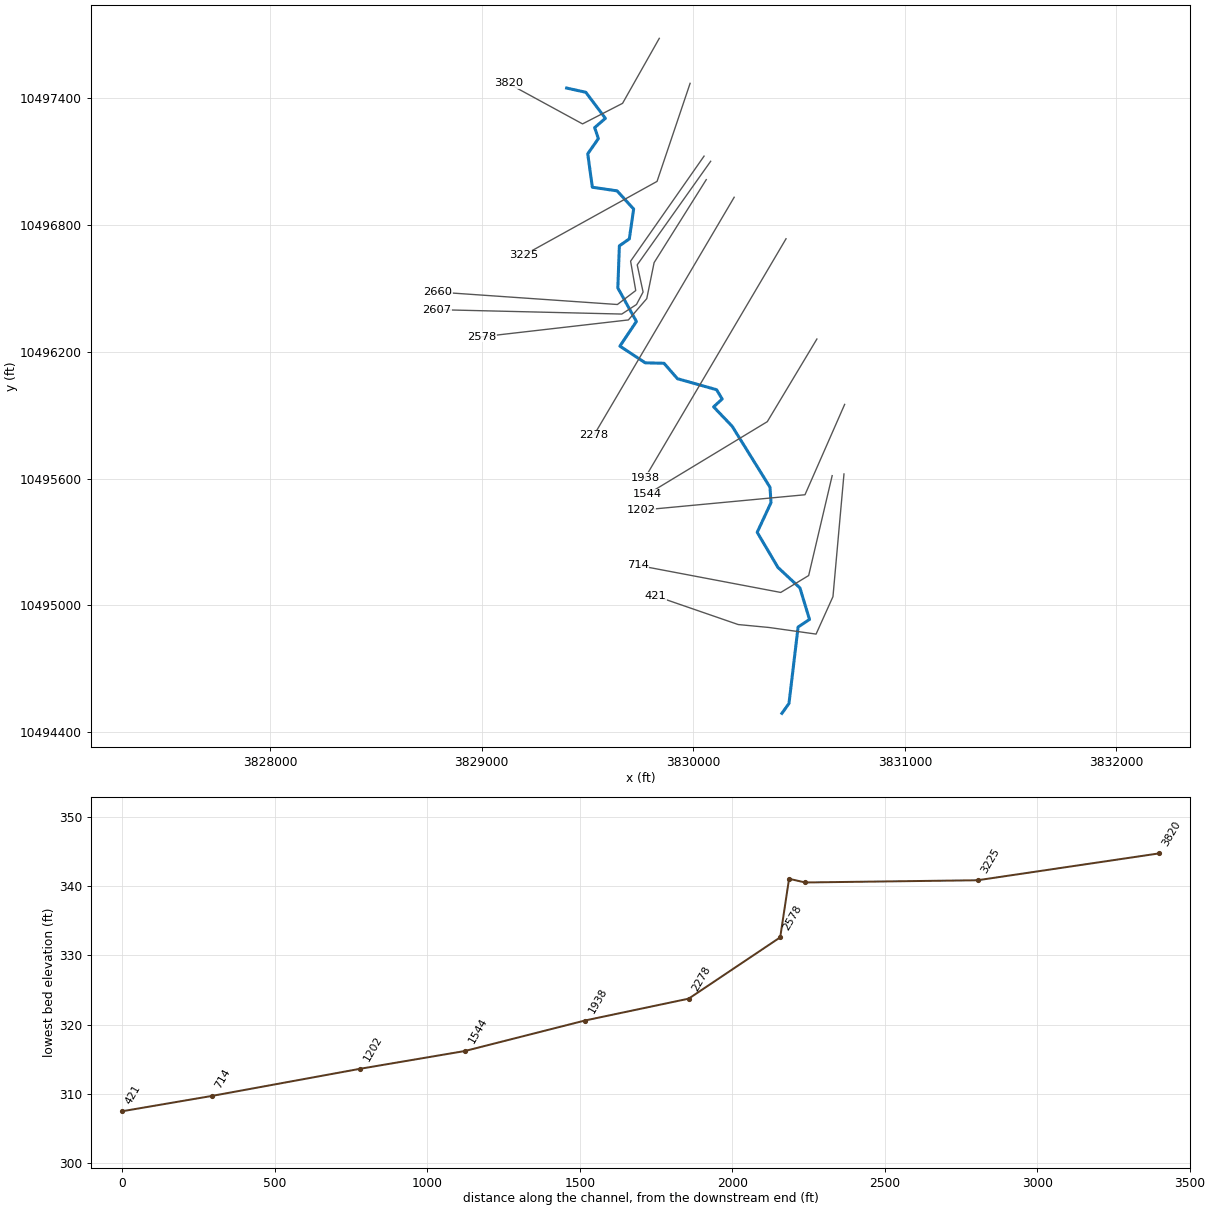
--- UNT020 IN BECR.prj (project) ---

Proj Title=UNT020 IN BECR Base Level Engineering
Current Plan=p01
Default Exp/Contr=0.3,0.1
English Units
Geom File=g01
Flow File=f01
Plan File=p01
BEGIN DESCRIPTION:
UNT020 IN BECR
END DESCRIPTION:

--- UNT020 IN BECR.p01 (plan) ---

Plan Title=Multiple Run
Short Identifier=Multiple
Geom File=g01
Flow File=f01
Subcritical Flow
K Sum by GR= 0
Std Step Tol= 0.01
Critical Tol= 0.01
Num of Std Step Trials= 20
Max Error Tol= 0.3
Flow Tol Ratio= 0.001
Split Flow NTrial= 30
Split Flow Tol= 0.02
Split Flow Ratio= 0.02
Log Output Level= 0
Friction Slope Method= 1
Unsteady Friction Slope Method= 2
Unsteady Bridges Friction Slope Method= 1
Parabolic Critical Depth
Global Vel Dist=  1 , 1 , 1
Global Log Level= 0
CheckData=True
Encroach Param= -1, 0, 0, 0
BEGIN DESCRIPTION:
Multiple Run
END DESCRIPTION:

--- UNT020 IN BECR.f01 (steady flow) ---

Flow Title=Multiple
Number of Profiles=7
Profile Names=10-year,25-year,50-year,1pct_min,100-year,1pct_plu,500-year
River Rch & RM= UNT020 IN BECR,Reach-1,3820
     356     464     550     481     650     879     908
Boundary for River Rch & Prof#=UNT020 IN BECR,Reach-1,1
Up Type=0
Dn Type=3
Dn Slope=0.005
Boundary for River Rch & Prof#=UNT020 IN BECR,Reach-1,2
Up Type=0
Dn Type=3
Dn Slope=0.005
Boundary for River Rch & Prof#=UNT020 IN BECR,Reach-1,3
Up Type=0
Dn Type=3
Dn Slope=0.005
Boundary for River Rch & Prof#=UNT020 IN BECR,Reach-1,4
Up Type=0
Dn Type=3
Dn Slope=0.005
Boundary for River Rch & Prof#=UNT020 IN BECR,Reach-1,5
Up Type=0
Dn Type=3
Dn Slope=0.005
Boundary for River Rch & Prof#=UNT020 IN BECR,Reach-1,6
Up Type=0
Dn Type=3
Dn Slope=0.005
Boundary for River Rch & Prof#=UNT020 IN BECR,Reach-1,7
Up Type=0
Dn Type=3
Dn Slope=0.005

--- UNT020 IN BECR.g01 (geometry) ---

Geom Title=Existing Conditions

River Reach=UNT020 IN BECR,Reach-1
Reach XY= 30
      3829401.50     10497446.00      3829492.00     10497426.00
      3829584.75     10497303.00      3829534.00     10497259.00
      3829551.50     10497207.00      3829501.25     10497135.00
      3829523.00     10496977.00      3829640.00     10496960.00
      3829718.25     10496874.00      3829697.75     10496733.00
      3829650.75     10496700.00      3829643.50     10496501.00
      3829731.28     10496342.50      3829653.25     10496226.00
      3829773.25     10496147.00      3829861.75     10496145.00
      3829925.25     10496072.00      3830110.25     10496020.00
      3830136.75     10495976.00      3830096.25     10495939.00
      3830184.03     10495847.07      3830362.68     10495559.05
      3830367.50     10495486.00      3830302.25     10495346.00
      3830400.25     10495180.00      3830504.25     10495083.00
      3830549.50     10494934.00      3830495.50     10494898.00
      3830452.50     10494537.00      3830419.00     10494490.00

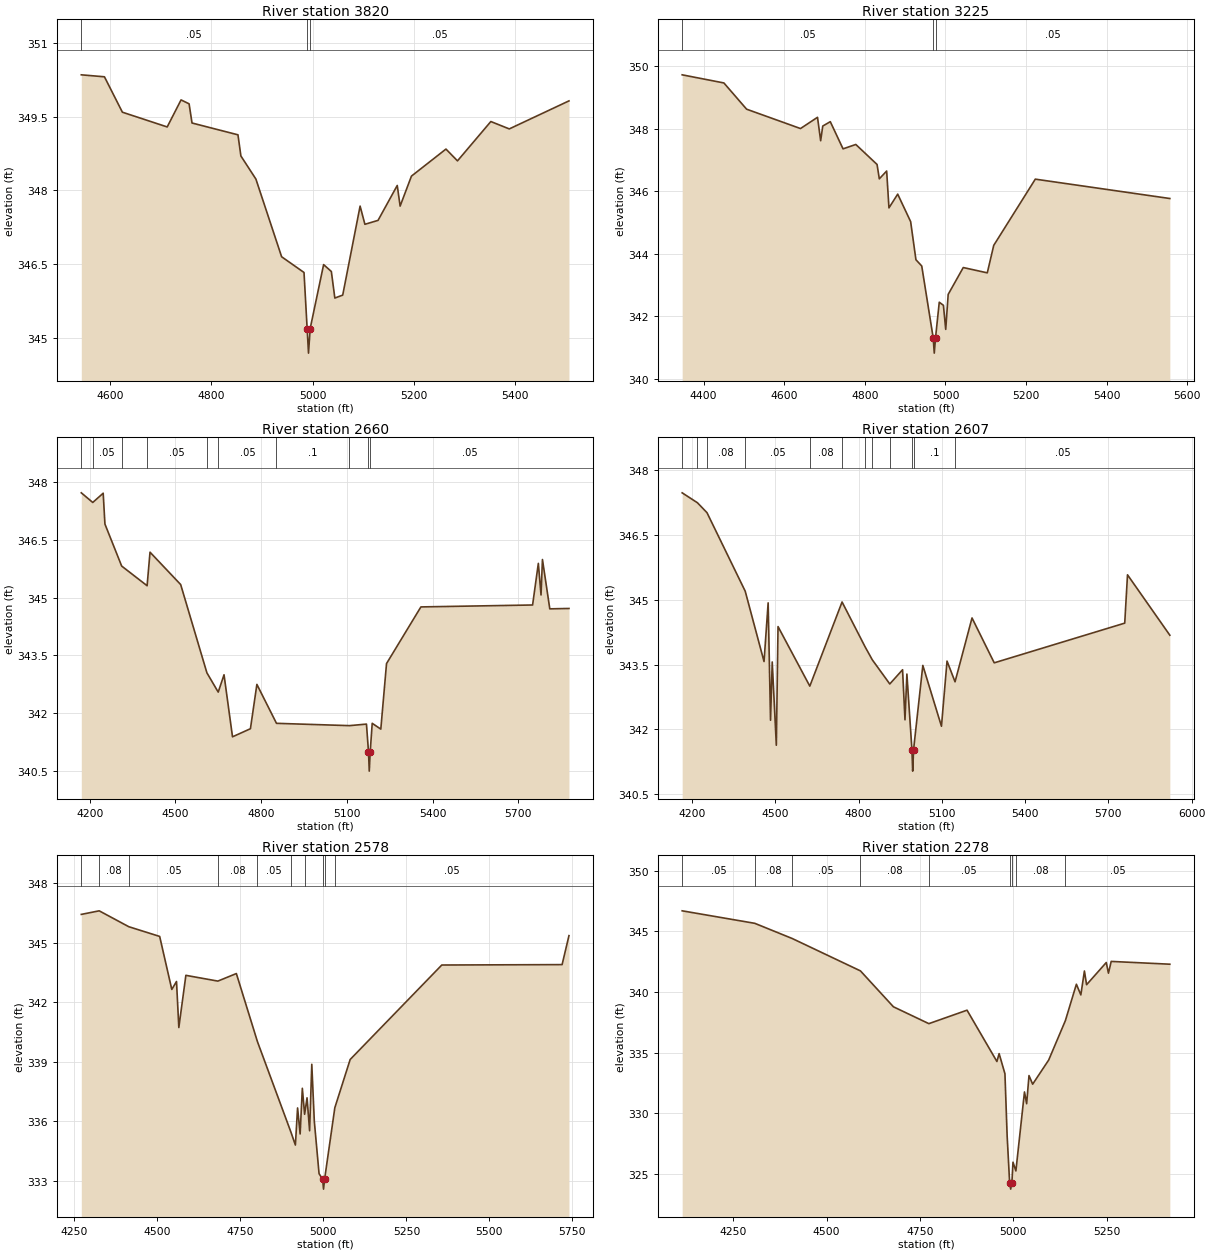
Type RM Length L Ch R = 1,3820,595,595,595
BEGIN DESCRIPTION:
UNT020 IN BECR 5.0
END DESCRIPTION:
XS GIS Cut Line= 4
      3829839.44     10497680.99      3829665.85     10497373.74
      3829476.61     10497276.51      3829125.89     10497467.50
#Sta/Elev= 30
  4542.5  350.35  4588.3  350.31  4623.8  349.59  4712.5  349.29  4739.9  349.84
  4755.8  349.76  4761.6  349.37  4852.5  349.13  4858.3  348.70  4888.0  348.23
  4938.9  346.65  4983.2  346.33  4989.4  345.19  4992.1  344.69  4995.4  345.19
  5022.0  346.49  5037.3  346.35  5044.2  345.81  5059.8  345.87  5094.2  347.68
  5103.7  347.31  5129.7  347.39  5167.7  348.10  5173.4  347.68  5195.8  348.29
  5264.1  348.84  5286.9  348.60  5352.9  349.40  5389.4  349.25  5507.5  349.82
#Mann=3,-1,0
  4542.5    0.05       0  4989.4    0.03       0  4995.4    0.05       0
Bank Sta=4989.4,4995.4
Exp/Cntr=0.3,0.1

Type RM Length L Ch R = 1,3225,565,565,565
BEGIN DESCRIPTION:
Mapping XS 7ada2ebc
END DESCRIPTION:
XS GIS Cut Line= 3
      3829985.11     10497468.30      3829828.85     10497004.71
      3829198.63     10496655.74
#Sta/Elev= 30
  4346.9  349.73  4450.4  349.47  4506.7  348.63  4640.4  348.01  4682.6  348.37
  4690.4  347.62  4695.6  348.09  4714.3  348.23  4745.9  347.36  4777.6  347.50
  4830.3  346.86  4835.9  346.40  4854.1  346.65  4859.8  345.47  4881.5  345.91
  4913.6  345.03  4926.7  343.81  4941.1  343.61  4969.4  341.32  4972.2  340.82
  4975.4  341.32  4984.6  342.45  4994.9  342.35  5000.6  341.58  5006.7  342.70
  5044.1  343.56  5103.7  343.39  5119.7  344.27  5222.8  346.39  5556.5  345.77
#Mann=3,-1,0
  4346.9    0.05       0  4969.4    0.03       0  4975.4    0.05       0
Bank Sta=4969.4,4975.4
Exp/Cntr=0.3,0.1

Type RM Length L Ch R = 1,2660,53,53,53
BEGIN DESCRIPTION:
Mapping XS c72ab0ce
END DESCRIPTION:
XS GIS Cut Line= 5
      3830051.10     10497124.19      3829703.85     10496627.63
      3829728.15     10496488.74      3829641.35     10496422.77
      3828792.66     10496481.65
#Sta/Elev= 30
  4170.7  347.72  4210.8  347.47  4247.3  347.71  4253.4  346.91  4312.0  345.82
  4401.0  345.31  4411.2  346.18  4518.5  345.34  4610.3  343.05  4649.9  342.55
  4670.2  343.00  4699.9  341.39  4762.6  341.60  4785.2  342.75  4853.8  341.74
  5109.2  341.68  5168.7  341.72  5175.8  341.00  5178.5  340.50  5181.8  341.00
  5188.8  341.74  5218.9  341.59  5238.9  343.29  5359.2  344.76  5750.1  344.81
  5770.2  345.89  5779.6  345.07  5784.6  345.99  5810.3  344.71  5877.4  344.72
#Mann=10,-1,0
  4170.7    0.08       0  4210.8    0.05       0  4312.0    0.08       0
  4401.0    0.05       0  4610.3    0.08       0  4649.9    0.05       0
  4853.8     0.1       0  5109.2    0.05       0  5175.8    0.07       0
  5181.8    0.05       0
Bank Sta=5175.8,5181.8
Exp/Cntr=0.3,0.1

Type RM Length L Ch R = 1,2607,29,29,29
BEGIN DESCRIPTION:
UNT020 IN BECR 4.0
END DESCRIPTION:
XS GIS Cut Line= 6
      3830082.30     10497099.82      3829735.10     10496610.27
      3829762.88     10496481.79      3829731.63     10496422.77
      3829662.18     10496377.63      3828787.14     10496398.46
#Sta/Elev= 30
  4164.7  347.48  4219.7  347.25  4254.1  347.02  4391.8  345.20  4459.6  343.57
  4474.4  344.93  4483.0  342.21  4489.1  343.56  4503.9  341.63  4510.0  344.38
  4624.5  343.00  4740.7  344.95  4823.7  343.91  4849.6  343.61  4912.6  343.05
  4958.6  343.38  4967.3  342.22  4974.2  343.28  4992.3  341.53  4995.1  341.03
  4998.3  341.53  5031.6  343.48  5098.7  342.07  5118.8  343.58  5147.7  343.10
  5208.8  344.58  5288.8  343.54  5758.9  344.46  5768.9  345.58  5921.4  344.18
#Mann=12,-1,0
  4164.7    0.08       0  4219.7    0.05       0  4254.1    0.08       0
  4391.8    0.05       0  4624.5    0.08       0  4740.7    0.05       0
  4823.7     0.1       0  4849.6    0.05       0  4912.6     0.1       0
  4992.3    0.07       0  4998.3     0.1       0  5147.7    0.05       0
Bank Sta=4992.3,4998.3
Exp/Cntr=0.3,0.1

Type RM Length L Ch R = 1,2578,300,300,300
BEGIN DESCRIPTION:
Mapping XS 2aa6cffe
END DESCRIPTION:
XS GIS Cut Line= 5
      3830061.50     10497013.07      3829814.96     10496620.68
      3829780.24     10496450.54      3829693.43     10496349.85
      3828999.01     10496269.99
#Sta/Elev= 30
  4270.7  346.43  4324.6  346.61  4413.7  345.81  4506.8  345.32  4543.3  342.65
  4557.5  343.05  4564.5  340.73  4585.7  343.36  4682.1  343.07  4737.8  343.45
  4801.3  340.02  4902.2  335.46  4915.6  334.81  4922.2  336.68  4929.9  335.37
  4936.5  337.67  4943.4  336.36  4950.7  337.19  4958.4  335.53  4965.0  338.88
  4972.6  336.01  4986.9  333.37  4997.6  333.09  5000.4  332.59  5003.6  333.09
  5034.4  336.69  5080.6  339.12  5356.6  343.88  5719.0  343.90  5739.7  345.36
#Mann=10,-1,0
  4270.7    0.05       0  4324.6    0.08       0  4413.7    0.05       0
  4682.1    0.08       0  4801.3    0.05       0  4902.2    0.08       0
  4943.4     0.1       0  4997.6    0.07       0  5003.6     0.1       0
  5034.4    0.05       0
Bank Sta=4997.6,5003.6
Exp/Cntr=0.3,0.1

Type RM Length L Ch R = 1,2278,340,340,340
BEGIN DESCRIPTION:
UNT020 IN BECR 3.0
END DESCRIPTION:
XS GIS Cut Line= 2
      3830193.44     10496929.72      3829530.36     10495804.92
#Sta/Elev= 30
  4113.2  346.69  4307.6  345.66  4407.7  344.41  4590.5  341.74  4678.8  338.78
  4773.7  337.39  4875.9  338.50  4955.9  334.27  4961.8  334.92  4977.4  333.26
  4983.3  328.13  4990.0  324.25  4992.8  323.75  4996.0  324.25  4998.9  325.97
  5006.7  325.25  5029.7  331.76  5035.5  330.79  5041.8  333.11  5051.6  332.40
  5094.5  334.39  5139.1  337.63  5168.7  340.64  5180.6  339.76  5190.2  341.73
  5196.0  340.60  5248.7  342.43  5254.5  341.55  5261.9  342.52  5418.9  342.29
#Mann=9,-1,0
  4113.2    0.05       0  4307.6    0.08       0  4407.7    0.05       0
  4590.5    0.08       0  4773.7    0.05       0  4990.0    0.04       0
  4996.0    0.05       0  5006.7    0.08       0  5139.1    0.05       0
Bank Sta=4990,4996
Exp/Cntr=0.3,0.1

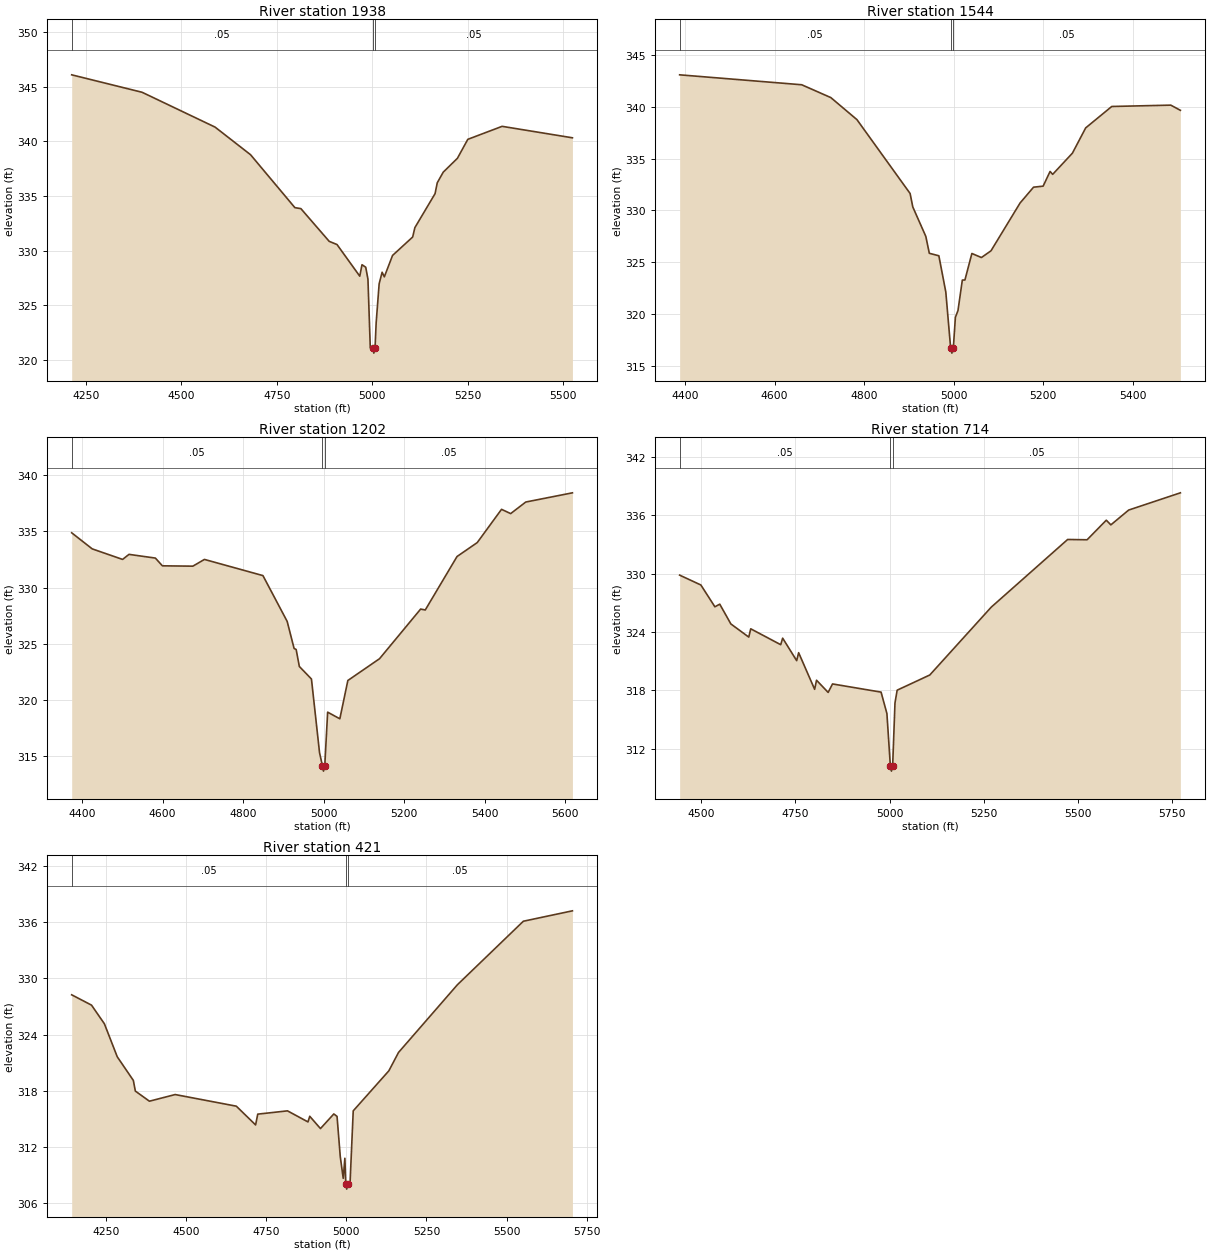
Type RM Length L Ch R = 1,1938,394,394,394
BEGIN DESCRIPTION:
Mapping XS 77e737ee
END DESCRIPTION:
XS GIS Cut Line= 2
      3830438.58     10496733.54      3829772.46     10495604.27
#Sta/Elev= 30
  4213.1  346.10  4397.5  344.50  4588.5  341.31  4681.4  338.78  4797.5  333.93
  4813.2  333.84  4887.4  330.84  4907.8  330.55  4967.4  327.65  4973.2  328.70
  4983.0  328.47  4988.8  327.37  4994.9  321.11  5001.4  321.10  5004.2  320.60
  5007.4  321.10  5010.3  323.38  5018.1  326.95  5025.9  328.01  5031.7  327.59
  5053.2  329.55  5105.9  331.24  5111.7  332.10  5164.5  335.21  5170.3  336.21
  5185.9  337.18  5223.0  338.45  5250.3  340.19  5340.1  341.38  5524.2  340.33
#Mann=3,-1,0
  4213.1    0.05       0  5001.4    0.03       0  5007.4    0.05       0
Bank Sta=5001.4,5007.4
Exp/Cntr=0.3,0.1

Type RM Length L Ch R = 1,1544,342,342,342
BEGIN DESCRIPTION:
UNT020 IN BECR 2.0
END DESCRIPTION:
XS GIS Cut Line= 3
      3830584.41     10496259.57      3830350.03     10495868.95
      3829783.45     10495525.88
#Sta/Elev= 30
  4388.1  343.10  4660.6  342.14  4725.6  340.90  4783.9  338.77  4902.6  331.63
  4908.6  330.33  4937.7  327.48  4945.5  325.85  4966.8  325.61  4982.3  322.11
  4993.1  316.70  4995.9  316.20  4999.1  316.70  5003.7  319.66  5009.5  320.32
  5019.2  323.26  5025.0  323.27  5040.5  325.83  5061.8  325.44  5083.2  326.09
  5148.1  330.71  5178.2  332.24  5199.6  332.34  5215.1  333.76  5220.9  333.48
  5265.0  335.53  5294.6  337.97  5352.8  340.04  5484.6  340.17  5506.0  339.67
#Mann=3,-1,0
  4388.1    0.05       0  4993.1    0.03       0  4999.1    0.05       0
Bank Sta=4993.1,4999.1
Exp/Cntr=0.3,0.1

Type RM Length L Ch R = 1,1202,488,488,488
BEGIN DESCRIPTION:
Mapping XS 6e8918d8
END DESCRIPTION:
XS GIS Cut Line= 3
      3830715.63     10495950.50      3830528.15     10495523.46
      3829754.26     10495450.58
#Sta/Elev= 30
  4374.4  334.87  4425.3  333.44  4500.8  332.50  4516.7  332.95  4582.2  332.62
  4599.7  331.93  4675.3  331.90  4704.1  332.50  4849.4  331.06  4909.6  326.98
  4926.8  324.57  4931.9  324.48  4939.8  322.97  4969.9  321.85  4990.0  315.29
  4997.0  314.15  4999.8  313.65  5003.0  314.15  5010.1  318.90  5040.4  318.31
  5060.3  321.72  5139.0  323.66  5241.1  328.08  5252.6  328.00  5331.5  332.76
  5381.7  334.00  5442.0  336.96  5464.7  336.58  5502.2  337.61  5618.1  338.43
#Mann=3,-1,0
  4374.4    0.05       0  4997.0    0.03       0  5003.0    0.05       0
Bank Sta=4997,5003
Exp/Cntr=0.3,0.1

Type RM Length L Ch R = 1,714,293,293,293
BEGIN DESCRIPTION:
Mapping XS 38fed5eb
END DESCRIPTION:
XS GIS Cut Line= 4
      3830656.62     10495613.72      3830545.52     10495141.52
      3830413.57     10495061.65      3829736.48     10495190.13
#Sta/Elev= 30
  4442.9  329.84  4499.2  328.83  4536.4  326.59  4549.3  326.86  4578.8  324.83
  4626.3  323.48  4631.5  324.33  4711.1  322.70  4716.2  323.37  4753.4  321.06
  4758.6  321.88  4801.0  318.12  4806.1  319.05  4836.9  317.80  4848.5  318.67
  4977.3  317.83  4992.8  315.63  5002.0  310.22  5004.8  309.72  5008.0  310.22
  5014.2  316.72  5020.0  318.03  5106.6  319.59  5269.5  326.55  5472.3  333.50
  5523.9  333.47  5574.8  335.48  5587.0  335.00  5634.2  336.52  5771.4  338.29
#Mann=3,-1,0
  4442.9    0.05       0  5002.0    0.03       0  5008.0    0.05       0
Bank Sta=5002,5008
Exp/Cntr=0.3,0.1

Type RM Length L Ch R = 1,421,0,0,0
BEGIN DESCRIPTION:
UNT020 IN BECR 1.0
END DESCRIPTION:
XS GIS Cut Line= 6
      3830712.48     10495621.73      3830660.40     10495041.84
      3830580.54     10494864.76      3830358.31     10494896.01
      3830212.48     10494909.90      3829820.27     10495045.26
#Sta/Elev= 30
  4143.3  328.25  4205.1  327.15  4245.3  325.16  4285.4  321.64  4335.6  319.12
  4341.9  317.98  4385.8  316.90  4466.1  317.61  4656.9  316.37  4717.1  314.37
  4723.8  315.52  4816.6  315.87  4880.5  314.69  4886.0  315.29  4919.5  313.98
  4961.1  315.54  4971.2  315.28  4981.3  310.97  4990.5  308.67  4995.6  310.81
  4998.5  308.02  5001.3  307.52  5004.5  308.02  5011.6  308.03  5021.7  315.87
  5132.8  320.14  5163.0  322.10  5346.6  329.32  5552.5  336.10  5705.6  337.21
#Mann=3,-1,0
  4143.3    0.05       0  4998.5    0.03       0  5004.5    0.05       0
Bank Sta=4998.5,5004.5
Exp/Cntr=0.3,0.1

Chan Stop Cuts=-1