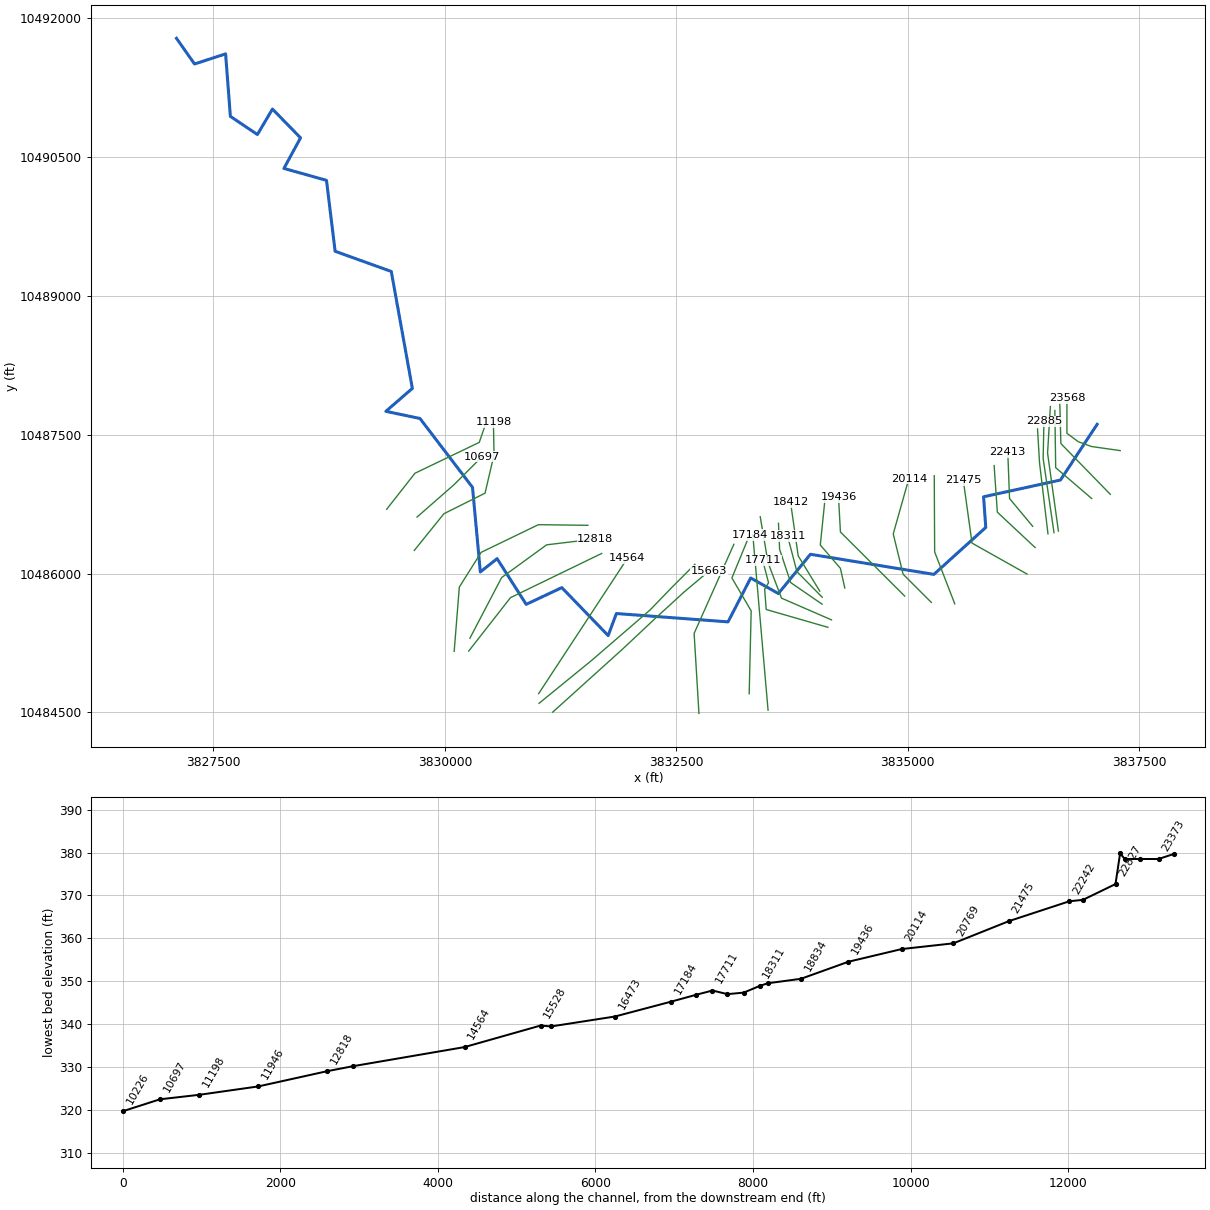
--- UNT021 IN BECR.prj (project) ---

Proj Title=UNT021 IN BECR Base Level Engineering
Current Plan=p01
Default Exp/Contr=0.3,0.1
English Units
Geom File=g01
Flow File=f01
Plan File=p01
Y Axis Title=Elevation
X Axis Title(PF)=Main Channel Distance
X Axis Title(XS)=Station
BEGIN DESCRIPTION:
UNT021 IN BECR
END DESCRIPTION:
DSS Export Rating Curves= 0
DSS Export Rating Curve Sorted= 0
DSS Export Volume Flow Curves= 0
DXF OffsetX= 0
DXF OffsetY= 0
DXF ScaleX= 1
DXF ScaleY= 10

--- UNT021 IN BECR.p01 (plan) ---

Plan Title=Multiple Run
Short Identifier=Multiple
Geom File=g01
Flow File=f01
Subcritical Flow
K Sum by GR= 0
Std Step Tol= 0.01
Critical Tol= 0.01
Num of Std Step Trials= 20
Max Error Tol= 0.3
Flow Tol Ratio= 0.001
Split Flow NTrial= 30
Split Flow Tol= 0.02
Split Flow Ratio= 0.02
Log Output Level= 0
Friction Slope Method= 1
Unsteady Friction Slope Method= 2
Unsteady Bridges Friction Slope Method= 1
Parabolic Critical Depth
Global Vel Dist=  1 , 1 , 1
Global Log Level= 0
CheckData=True
Encroach Param= -1, 0, 0, 0
BEGIN DESCRIPTION:
Multiple Run
END DESCRIPTION:

--- UNT021 IN BECR.f01 (steady flow) ---

Flow Title=Multiple
Program Version=4.10
Number of Profiles= 7
Profile Names=10-year,25-year,50-year,1pct_min,100-year,1pct_plu,500-year
River Rch & RM=UNT021 IN BECR,Reach-1         ,23568
     546     729     878     777    1051    1421    1510
River Rch & RM=UNT021 IN BECR,Reach-1         ,16473
     818    1110    1352    1207    1632    2207    2389
Boundary for River Rch & Prof#=UNT021 IN BECR,Reach-1         , 1
Up Type= 0
Dn Type= 3
Dn Slope=0.003
Boundary for River Rch & Prof#=UNT021 IN BECR,Reach-1         , 2
Up Type= 0
Dn Type= 3
Dn Slope=0.003
Boundary for River Rch & Prof#=UNT021 IN BECR,Reach-1         , 3
Up Type= 0
Dn Type= 3
Dn Slope=0.003
Boundary for River Rch & Prof#=UNT021 IN BECR,Reach-1         , 4
Up Type= 0
Dn Type= 3
Dn Slope=0.003
Boundary for River Rch & Prof#=UNT021 IN BECR,Reach-1         , 5
Up Type= 0
Dn Type= 3
Dn Slope=0.003
Boundary for River Rch & Prof#=UNT021 IN BECR,Reach-1         , 6
Up Type= 0
Dn Type= 3
Dn Slope=0.003
Boundary for River Rch & Prof#=UNT021 IN BECR,Reach-1         , 7
Up Type= 0
Dn Type= 3
Dn Slope=0.003
DSS Import GetInterval= 0
DSS Import GetPeak= 0
DSS Import FillOption= 0

--- UNT021 IN BECR.g01 (geometry) ---

Geom Title=Existing Conditions
Program Version=4.10

River Reach=UNT021 IN BECR  ,Reach-1
Reach XY= 30
       3837045.5       10487612.      3836649.61     10487010.19
        3835819.       10486829.      3835842.75       10486498.
      3835282.25       10485991.      3833948.75       10486208.
       3833602.5       10485784.       3833303.5       10485952.
      3833058.75       10485478.      3831852.75       10485568.
        3831764.       10485330.      3831263.25       10485848.
       3830878.5       10485667.       3830564.5       10486161.
      3830383.25       10486017.      3830298.75       10486931.
      3829731.25       10487675.        3829363.       10487752.
        3829649.       10488000.      3829421.25       10489263.
      3828814.75       10489481.       3828721.5       10490247.
      3828261.75       10490376.      3828441.25       10490706.
        3828138.       10491017.        3827975.       10490742.
       3827683.5       10490938.      3827631.75       10491613.
      3827296.25       10491504.       3827101.5       10491781.

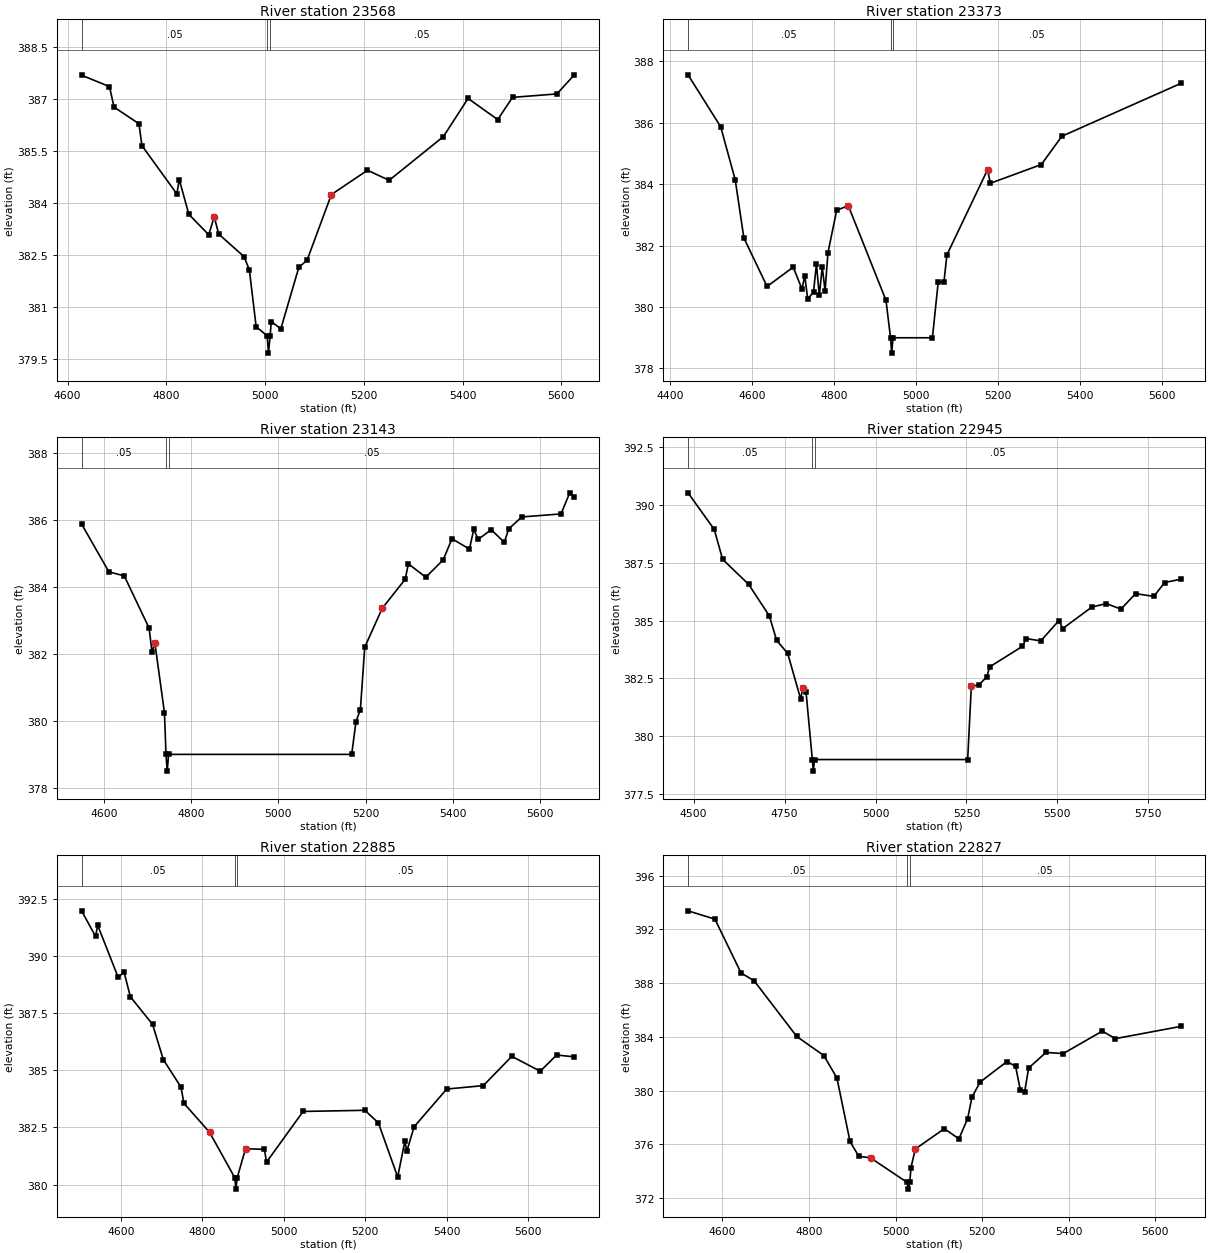
Type RM Length L Ch R = 1 ,23568   ,195,195,195
BEGIN DESCRIPTION:
UNT021 IN BECR 32.0
END DESCRIPTION:
XS GIS Cut Line= 5
      3837294.71     10487327.77      3836984.78     10487372.04
      3836841.55     10487424.13      3836719.15     10487515.27
      3836719.15     10487895.38
#Sta/Elev= 30
  4628.2  387.68  4684.8  387.35    4694  386.76  4744.5  386.28  4750.5  385.65
  4821.2  384.26  4826.2  384.67  4845.5  383.67  4885.9  383.08  4896.9   383.6
  4906.1   383.1  4957.4  382.45  4968.1  382.07  4981.9  380.43  5004.2  380.17
  5006.9  379.67  5010.2  380.17  5012.5  380.58  5031.9  380.37  5068.3  382.14
  5085.1  382.35  5134.3  384.24  5207.4  384.94  5251.3  384.65  5361.2  385.91
  5411.2  387.01  5471.2   386.4  5501.2  387.04  5591.2  387.14  5626.4  387.69
#Mann= 3 ,-1 , 0
  4628.2     .05       0  5004.2     .03       0  5010.2     .05       0
Bank Sta=4896.9,5134.3
XS Rating Curve= 0 ,0
Exp/Cntr=0.3,0.1

Type RM Length L Ch R = 1 ,23373   ,230,230,230
BEGIN DESCRIPTION:
Mapping XS 346ae86b
END DESCRIPTION:
XS GIS Cut Line= 3
      3837187.79     10486855.72      3836653.96     10487403.88
      3836642.24     10487840.07
#Sta/Elev= 30
  4444.3  387.56  4523.9  385.87  4559.4  384.14  4580.5  382.25  4637.1  380.67
  4700.8   381.3    4722  380.59  4729.1  381.01  4736.1  380.26  4750.3  380.49
  4757.4   381.4  4764.4  380.38  4771.6   381.3  4778.5  380.53  4785.5  381.77
  4806.8  383.15  4835.1   383.3    4927  380.22  4938.1     379  4940.9   378.5
  4944.1     379  5040.2     379  5054.3  380.81  5068.4  380.83  5075.6   381.7
  5174.6  384.47  5181.6  384.03  5305.8  384.64  5355.8  385.56  5645.8  387.28
#Mann= 3 ,-1 , 0
  4444.3     .05       0  4938.1    .035       0  4944.1     .05       0
Bank Sta=4835.1,5174.6
XS Rating Curve= 0 ,0
Exp/Cntr=0.3,0.1

Type RM Length L Ch R = 1 ,23143   ,198,198,198
BEGIN DESCRIPTION:
Mapping XS d3251001
END DESCRIPTION:
XS GIS Cut Line= 3
      3836987.29     10486810.13      3836597.97     10487143.46
      3836588.85     10487760.66
#Sta/Elev= 30
  4548.8  385.88  4611.5  384.45  4646.7  384.33  4703.7  382.77  4710.3  382.06
  4716.9  382.33  4738.9  380.24  4742.4     379  4745.2   378.5  4748.4     379
  5168.1     379  5178.1  379.98  5188.1  380.34  5198.1   382.2  5238.1  383.36
  5290.9  384.23  5298.1  384.69  5338.1  384.29  5378.1  384.81  5398.1  385.44
  5438.1  385.13  5448.1  385.72  5458.1  385.42  5488.1  385.71  5518.1  385.33
  5528.1  385.73  5558.1  386.09  5648.1  386.18  5668.1  386.81  5678.6  386.69
#Mann= 3 ,-1 , 0
  4548.8     .05       0  4742.4    .033       0  4748.4     .05       0
Bank Sta=4716.9,5238.1
XS Rating Curve= 0 ,0
Exp/Cntr=0.3,0.1

Type RM Length L Ch R = 1 ,22945   ,60,60,60
BEGIN DESCRIPTION:
Mapping XS fcc34788
END DESCRIPTION:
XS GIS Cut Line= 3
       3836627.4      10486458.8      3836510.21      10487300.8
       3836540.6     10487804.27
#Sta/Elev= 30
  4484.6  390.51  4556.7  388.93  4579.7  387.64  4651.3  386.56  4708.1   385.2
  4728.3  384.14  4758.6  383.58  4794.5   381.6  4799.5  382.07  4809.1   381.9
  4826.3     379    4829   378.5  4832.3     379  5253.3     379  5263.4  382.17
  5283.6  382.21  5305.8  382.57  5313.9     383  5403.4  383.88  5414.2  384.22
  5454.3  384.12  5504.4     385  5514.4  384.65  5594.6  385.58  5634.6  385.73
  5674.7  385.49  5714.8  386.16  5764.9  386.04  5794.9  386.64  5839.1  386.78
#Mann= 3 ,-1 , 0
  4484.6     .05       0  4826.3    .033       0  4832.3     .05       0
Bank Sta=4799.5,5263.4
XS Rating Curve= 0 ,0
Exp/Cntr=0.3,0.1

Type RM Length L Ch R = 1 ,22885   ,58,58,58
BEGIN DESCRIPTION:
Mapping XS 01ce064e
END DESCRIPTION:
XS GIS Cut Line= 3
      3836579.66     10486441.43      3836462.47     10487244.38
      3836471.15     10487643.73
#Sta/Elev= 30
    4503  391.98  4537.5  390.86  4542.6  391.35  4592.7  389.08  4607.5  389.29
    4623  388.22  4677.5  387.01  4703.9  385.47  4747.5  384.26  4754.4  383.56
  4817.5  382.29  4879.5   380.3  4882.2   379.8  4885.5   380.3    4906  381.57
  4952.4  381.54  4957.5  380.98  5047.5   383.2  5199.1  383.25  5232.4   382.7
  5279.9  380.33  5297.4  381.89  5302.4  381.47  5320.3  382.53  5400.3  384.18
  5490.3  384.33  5560.3  385.61  5630.3  384.96  5670.4  385.67  5713.9  385.59
#Mann= 3 ,-1 , 0
    4503     .05       0  4879.5     .03       0  4885.5     .05       0
Bank Sta=4817.5,4906
XS Rating Curve= 0 ,0
Exp/Cntr=0.3,0.1

Type RM Length L Ch R = 1 ,22827   ,414,414,414
BEGIN DESCRIPTION:
UNT021 IN BECR 31.0
END DESCRIPTION:
XS GIS Cut Line= 3
      3836514.55     10486428.44      3836423.41     10487196.64
      3836401.71     10487561.21
#Sta/Elev= 30
  4520.4  393.39  4582.6  392.77    4643  388.76  4673.2  388.18  4771.7  384.03
  4834.3  382.61  4864.5  380.94  4894.8  376.21  4914.9  375.11  4942.2  374.99
  5026.9  373.16  5029.7  372.66  5032.9  373.16  5035.7  374.27  5045.8  375.65
  5112.7  377.16  5146.5  376.41  5166.6  377.91  5176.7  379.52  5195.4  380.63
  5257.3  382.16  5277.4  381.81  5288.2  380.08  5298.3  379.89  5307.6  381.68
  5347.6  382.84  5387.7  382.76  5477.9  384.43  5507.9  383.87  5659.2  384.78
#Mann= 3 ,-1 , 0
  4520.4     .05       0  5026.9     .03       0  5032.9     .05       0
Bank Sta=4942.2,5045.8
XS Rating Curve= 0 ,0
Exp/Cntr=0.3,0.1

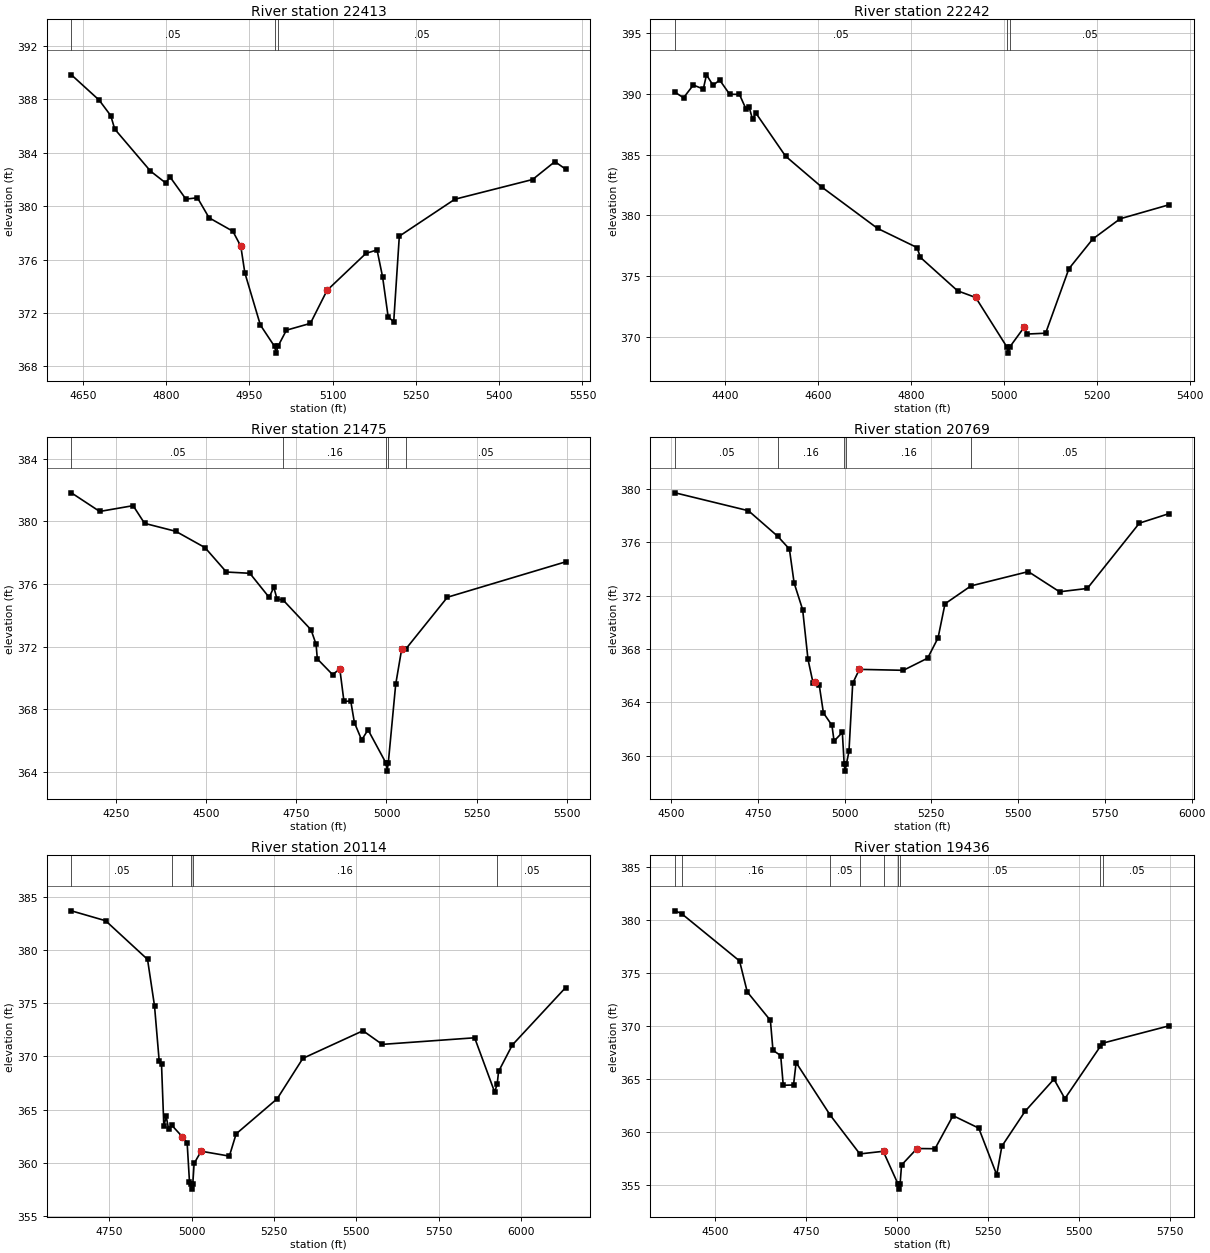
Type RM Length L Ch R = 1 ,22413   ,171,171,171
BEGIN DESCRIPTION:
UNT021 IN BECR 30.0
END DESCRIPTION:
XS GIS Cut Line= 3
      3836349.61     10486510.19      3836099.61     10486810.19
      3836080.53     10487309.51
#Sta/Elev= 30
  4629.4  389.85  4679.5  387.95  4700.3  386.79  4707.5  385.78  4771.9  382.63
  4799.3  381.74  4807.1  382.19  4835.7  380.53  4856.5  380.63  4877.4  379.13
  4920.3  378.12  4934.6  376.99  4941.8  375.01  4969.8  371.09  4995.4  369.48
  4998.2  368.98  5001.4  369.48  5016.7   370.7  5059.9  371.21    5090  373.69
    5160  376.46    5180  376.72    5190  374.69    5200   371.7    5210  371.33
  5220.1  377.75  5320.1  380.52  5460.2     382  5500.3  383.34  5519.6  382.78
#Mann= 3 ,-1 , 0
  4629.4     .05       0  4995.4     .03       0  5001.4     .05       0
Bank Sta=4934.6,5090
XS Rating Curve= 0 ,0
Exp/Cntr=0.3,0.1

Type RM Length L Ch R = 1 ,22242   ,767,767,767
BEGIN DESCRIPTION:
UNT021 IN BECR 29.0
END DESCRIPTION:
XS GIS Cut Line= 3
      3836375.69     10486280.82      3835967.68     10486662.78
        3835933.     10487165.69
#Sta/Elev= 30
  4293.2  390.13  4311.3  389.68  4332.3  390.73  4353.8   390.4  4360.6  391.57
  4374.8  390.71    4389  391.14  4410.5  389.97  4431.5  389.96  4445.6  388.76
  4452.5  388.89  4459.8   387.9  4466.7  388.43  4530.6  384.88  4608.3  382.34
  4728.5  378.93  4813.5  377.35  4820.8  376.54  4900.7  373.79  4939.7  373.24
  5006.9  369.16  5009.6  368.66  5012.9  369.16  5043.5  370.77    5050  370.23
  5090.1   370.3  5140.2  375.61  5191.4  378.05  5250.4  379.72  5356.2  380.88
#Mann= 3 ,-1 , 0
  4293.2     .05       0  5006.9     .03       0  5012.9     .05       0
Bank Sta=4939.7,5043.5
XS Rating Curve= 0 ,0
Exp/Cntr=0.3,0.1

Type RM Length L Ch R = 1 ,21475   ,706,706,706
BEGIN DESCRIPTION:
UNT021 IN BECR 28.0
END DESCRIPTION:
XS GIS Cut Line= 3
      3836288.89     10485994.36      3835694.24     10486328.58
      3835599.61     10487010.21
#Sta/Elev= 30
  4126.4  381.82  4204.9  380.63  4297.6     381  4329.3  379.87    4416  379.36
  4496.9  378.32  4556.2  376.76  4621.2  376.68  4674.8  375.14  4687.7  375.79
  4696.5  375.04  4713.9  374.96  4790.9  373.07  4804.9  372.14  4808.3  371.21
  4850.5  370.21  4870.7  370.56  4882.2  368.49    4901  368.52  4911.1  367.14
  4931.3  366.03  4948.9  366.68    4999  364.54  5001.7  364.04    5005  364.54
  5025.6  369.58  5042.4  371.86  5052.9  371.82    5169  375.15  5496.7  377.41
#Mann= 5 ,-1 , 0
  4126.4     .05       0  4713.9     .16       0    4999     .07       0
    5005     .16       0  5052.9     .05       0
Bank Sta=4870.7,5042.4
XS Rating Curve= 0 ,0
Exp/Cntr=0.3,0.1

Type RM Length L Ch R = 1 ,20769   ,655,655,655
BEGIN DESCRIPTION:
UNT021 IN BECR 27.0
END DESCRIPTION:
XS GIS Cut Line= 3
       3835507.6     10485673.24       3835290.6      10486233.1
      3835286.26     10487056.44
#Sta/Elev= 30
  4511.9   379.7  4723.1  378.36  4807.7  376.44  4841.1  375.49  4854.7  372.95
  4879.3  370.95  4894.7  367.23  4909.2  365.47  4916.2  365.51  4926.9  365.34
  4939.1  363.22  4963.7  362.29  4969.8  361.11  4993.6  361.76    4999  359.36
  5001.7  358.86    5005  359.36  5012.7  360.33  5023.5  365.44  5042.7  366.48
  5169.4  366.41  5239.4  367.32  5269.4  368.84  5289.4  371.39  5364.2  372.73
  5529.4   373.8  5619.4  372.29  5699.4  372.54  5849.4  377.43  5935.7  378.15
#Mann= 5 ,-1 , 0
  4511.9     .05       0  4807.7     .16       0    4999     .07       0
    5005     .16       0  5364.2     .05       0
Bank Sta=4916.2,5042.7
XS Rating Curve= 0 ,0
Exp/Cntr=0.3,0.1

Type RM Length L Ch R = 1 ,20114   ,678,678,678
BEGIN DESCRIPTION:
UNT021 IN BECR 25.0
END DESCRIPTION:
XS GIS Cut Line= 4
      3835254.58     10485688.17      3834949.88     10485992.86
      3834843.11     10486427.76      3835012.16     10487025.92
#Sta/Elev= 30
  4635.1  383.66    4739  382.73  4866.3   379.1  4887.5  374.73  4901.7  369.55
  4908.7  369.28  4915.8  363.43  4922.9  364.36    4930  363.21  4939.8  363.53
  4972.4  362.43  4986.5   361.9  4993.6  358.23  4997.7  358.03  5000.4  357.53
  5003.7  358.03  5007.7  359.94    5029  361.09  5114.7  360.63  5135.3  362.72
    5260  366.02  5337.9  369.81  5520.4   372.4  5578.7  371.12  5859.3  371.74
  5920.1  366.64  5927.8  367.41    5932  368.58  5973.6  371.06  6135.4  376.45
#Mann= 5 ,-1 , 0
  4635.1     .05       0  4939.8     .16       0  4997.7     .07       0
  5003.7     .16       0  5927.8     .05       0
Bank Sta=4972.4,5029
XS Rating Curve= 0 ,0
Exp/Cntr=0.3,0.1

Type RM Length L Ch R = 1 ,19436   ,602,602,602
BEGIN DESCRIPTION:
UNT021 IN BECR 24.0
END DESCRIPTION:
XS GIS Cut Line= 3
       3834966.8     10485756.98       3834272.8     10486448.59
      3834252.07     10486826.95
#Sta/Elev= 30
  4389.2  380.89  4406.8  380.63  4566.3  376.15  4587.5  373.22  4651.1  370.53
  4658.2   367.7  4679.4   367.2  4686.5  364.39  4714.7  364.42  4721.8  366.54
  4815.5  361.57    4897   357.9  4962.2  358.15  4962.6  358.05  5001.7  355.07
  5004.4  354.57  5007.7  355.07  5011.7  356.85  5054.2  358.41  5103.7  358.39
  5153.2  361.52  5223.9  360.34  5273.4  355.92  5287.5  358.63  5351.1  361.92
  5430.7  364.97  5460.7  363.13  5558.4  368.08  5566.4  368.39  5747.9  370.02
#Mann= 9 ,-1 , 0
  4389.2     .05       0  4406.8     .16       0  4815.5     .05       0
    4897     .16       0  4962.6     .05       0  5001.7     .03       0
  5007.7     .05       0  5558.4     .16       0  5566.4     .05       0
Bank Sta=4962.2,5054.2
XS Rating Curve= 0 ,0
Exp/Cntr=0.3,0.1

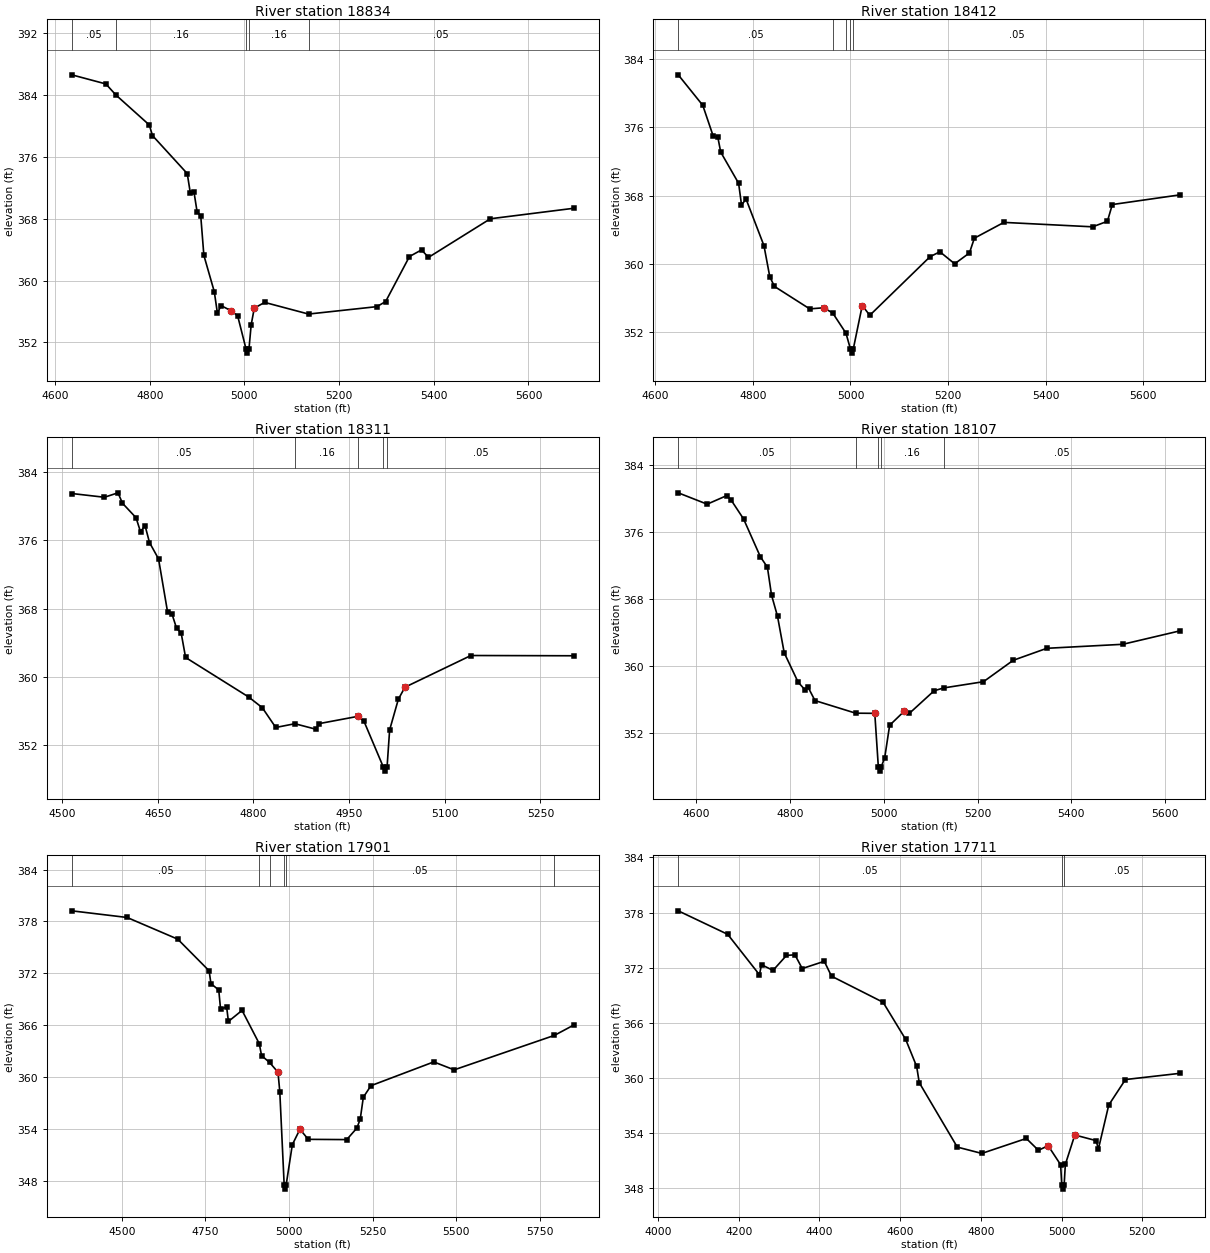
Type RM Length L Ch R = 1 ,18834   ,422,422,422
BEGIN DESCRIPTION:
UNT021 IN BECR 23.0
END DESCRIPTION:
XS GIS Cut Line= 4
      3834320.11     10485843.78      3834272.37     10486056.45
      3834055.35     10486308.18       3834107.4      10486815.6
#Sta/Elev= 30
  4635.4  386.64  4707.4  385.46  4728.6  384.03  4799.1  380.15  4805.9  378.77
  4879.3  373.85  4885.9  371.29  4893.6  371.43  4900.2  368.86  4907.8  368.37
  4914.4  363.26  4936.4  358.56    4943  355.77  4950.6  356.76  4971.5   356.1
  4985.7  355.44  5003.6   351.1  5006.4   350.6  5009.6   351.1  5014.3  354.27
  5020.9  356.43  5042.8  357.17  5135.4  355.66  5279.8  356.62  5298.3  357.28
  5348.6  363.11  5374.1  363.97  5388.8     363  5519.5     368  5695.8  369.36
#Mann= 5 ,-1 , 0
  4635.4     .05       0  4728.6     .16       0  5003.6     .07       0
  5009.6     .16       0  5135.4     .05       0
Bank Sta=4971.5,5020.9
XS Rating Curve= 0 ,0
Exp/Cntr=0.3,0.1

Type RM Length L Ch R = 1 ,18412   ,101,101,101
BEGIN DESCRIPTION:
UNT021 IN BECR 22.0
END DESCRIPTION:
XS GIS Cut Line= 3
      3834049.61     10485810.18      3833816.64     10486190.99
      3833734.18     10486768.21
#Sta/Elev= 30
  4646.9  382.15  4697.2  378.58  4718.5  374.99  4728.1  374.84    4734   373.1
  4770.7  369.45  4776.6  366.94  4786.2  367.57  4822.7  362.14  4834.6  358.51
  4844.2  357.37  4916.5  354.74  4944.9  354.87  4963.5  354.27  4990.8   351.9
  4999.9  350.06  5002.7  349.56  5005.9  350.06  5024.2  355.13  5039.7  353.99
  5163.2  360.85  5183.4  361.43  5213.7  360.02    5244  361.29  5254.1  363.02
  5314.7  364.87  5496.6  364.35  5526.9     365    5537  366.96  5676.4   368.1
#Mann= 5 ,-1 , 0
  4646.9     .05       0  4963.5     .16       0  4990.8     .05       0
  4999.9     .03       0  5005.9     .05       0
Bank Sta=4944.9,5024.2
XS Rating Curve= 0 ,0
Exp/Cntr=0.3,0.1

Type RM Length L Ch R = 1 ,18311   ,204,204,204
BEGIN DESCRIPTION:
Mapping XS 67059367
END DESCRIPTION:
XS GIS Cut Line= 3
      3834075.96     10485744.03      3833803.37     10486020.09
       3833701.2     10486406.24
#Sta/Elev= 30
    4515   381.5  4566.2  381.06  4587.5  381.58  4594.5  380.36  4615.8  378.66
  4622.8  377.01  4629.9  377.74  4636.9  375.75  4651.1  373.83  4665.2  367.62
  4672.3  367.34  4679.4  365.68  4686.5  365.16  4693.5  362.27  4792.5  357.63
  4813.8  356.38  4834.9  354.06  4864.9   354.5  4898.6  353.84  4902.1   354.5
  4964.1  355.37  4973.3  354.78  5003.5  349.44  5006.3  348.94  5009.5  349.44
  5013.5  353.77  5027.2  357.38  5037.5  358.78    5141   362.5  5302.4  362.47
#Mann= 5 ,-1 , 0
    4515     .05       0  4864.9     .16       0  4964.1     .05       0
  5003.5     .03       0  5009.5     .05       0
Bank Sta=4964.1,5037.5
XS Rating Curve= 0 ,0
Exp/Cntr=0.3,0.1

Type RM Length L Ch R = 1 ,18107   ,206,206,206
BEGIN DESCRIPTION:
Mapping XS 123f4ffa
END DESCRIPTION:
XS GIS Cut Line= 4
      3834074.19     10485669.41      3833735.66     10485902.04
      3833615.87     10486261.41      3833603.71     10486542.68
#Sta/Elev= 30
  4561.5  380.71  4623.2  379.35  4665.1  380.38  4673.9  379.88  4700.9  377.58
  4736.9  373.03  4751.7  371.81  4760.5  368.47  4773.3  365.92  4787.6  361.55
  4817.3  358.03  4832.2   357.1  4838.3  357.45  4853.2  355.83    4940  354.32
  4980.8   354.3  4988.4  347.88  4991.1  347.38  4994.4  347.88  5001.9  348.96
  5012.5  352.87  5044.1  354.58  5054.6   354.3  5107.3     357  5127.4  357.34
  5212.7  358.09    5276  360.65  5347.8  362.09    5510  362.57  5632.6  364.19
#Mann= 5 ,-1 , 0
  4561.5     .05       0    4940     .16       0  4988.4     .07       0
  4994.4     .16       0  5127.4     .05       0
Bank Sta=4980.8,5044.1
XS Rating Curve= 0 ,0
Exp/Cntr=0.3,0.1

Type RM Length L Ch R = 1 ,17901   ,190,190,190
BEGIN DESCRIPTION:
UNT021 IN BECR 21.0
END DESCRIPTION:
XS GIS Cut Line= 4
      3834176.72     10485499.27       3833636.2     10485734.43
      3833491.12     10486117.21       3833406.5     10486613.23
#Sta/Elev= 30
  4350.3  379.23  4515.9  378.46  4667.4  375.95  4761.2  372.29  4766.6  370.81
    4790  370.07  4795.5  367.83  4813.5  368.13  4818.9  366.43  4859.7  367.71
  4911.2  363.86  4918.1  362.48  4941.9  361.69  4967.2  360.56  4972.6  358.32
  4985.7  347.53  4988.4  347.03  4991.7  347.53  5010.1  352.17  5032.9  353.96
  5057.7  352.79  5172.9  352.76  5203.1  354.09  5213.3  355.13  5222.5  357.66
  5245.4     359  5433.3  361.75  5494.2  360.83  5794.2  364.82  5852.3  366.02
#Mann= 6 ,-1 , 0
  4350.3     .05       0  4911.2     .16       0  4941.9     .05       0
  4985.7     .03       0  4991.7     .05       0  5794.2     .08       0
Bank Sta=4967.2,5032.9
XS Rating Curve= 0 ,0
Exp/Cntr=0.3,0.1

Type RM Length L Ch R = 1 ,17711   ,207,207,207
BEGIN DESCRIPTION:
Mapping XS cf4be87a
END DESCRIPTION:
XS GIS Cut Line= 5
      3834137.44     10485419.29      3833471.04      10485611.5
       3833454.2     10485831.77      3833496.29     10485900.52
      3833433.16      10486141.8
#Sta/Elev= 30
  4049.9  378.19  4172.5  375.63  4251.1  371.23  4256.3  372.32  4284.8   371.7
  4318.2  373.33  4339.1   373.4  4357.3   371.9  4411.9  372.69  4429.8  371.07
  4557.6  368.23  4613.7  364.18  4640.9  361.23  4647.3  359.47  4741.6  352.45
  4802.3  351.76  4912.7  353.39  4942.7   352.1  4966.8   352.6  4997.7  350.53
  5000.5  348.37  5003.3  347.87  5006.5  348.37  5009.4  350.56  5032.9  353.77
    5086  353.15  5091.2  352.21    5117  357.03  5158.4  359.81  5294.4  360.49
#Mann= 3 ,-1 , 0
  4049.9     .05       0  5000.5     .03       0  5006.5     .05       0
Bank Sta=4966.8,5032.9
XS Rating Curve= 0 ,0
Exp/Cntr=0.3,0.1

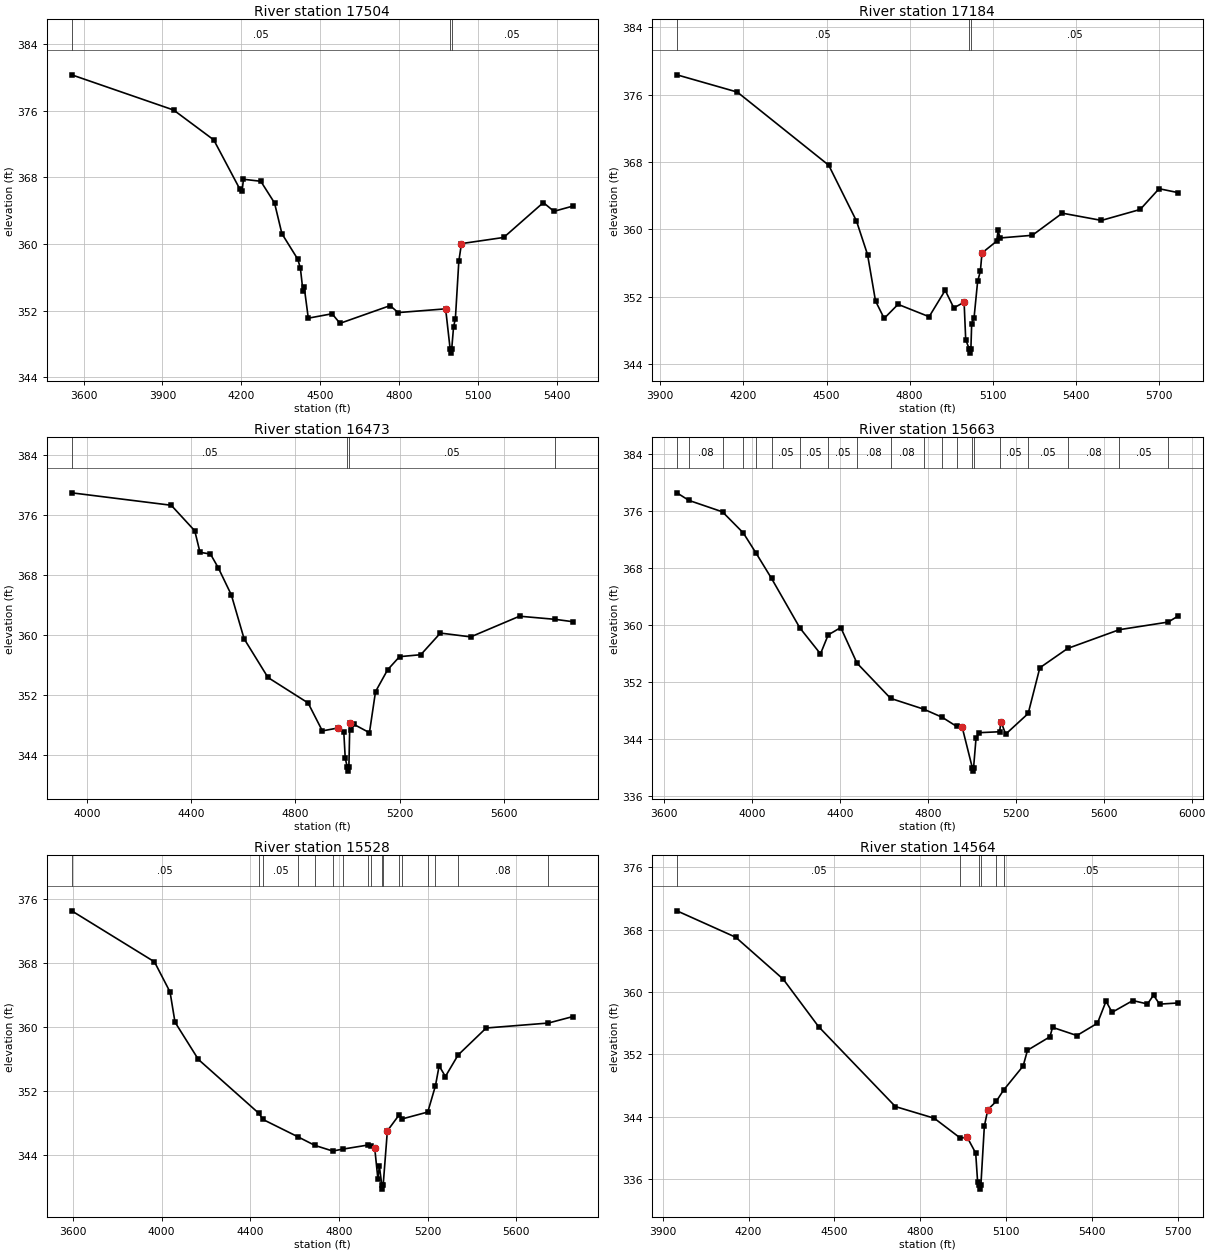
Type RM Length L Ch R = 1 ,17504   ,320,320,320
BEGIN DESCRIPTION:
UNT021 IN BECR 19.0
END DESCRIPTION:
XS GIS Cut Line= 2
      3833491.12     10484524.32      3833326.18     10486421.06
#Sta/Elev= 30
  3555.1  380.32  3942.4  376.09    4095   372.5  4193.4  366.63  4202.9  366.42
  4207.9  367.77  4273.7  367.53  4325.9  364.93    4354  361.23  4414.2  358.17
  4424.2   357.1  4433.8  354.39  4438.8   354.8  4454.3  351.08  4544.7  351.61
  4574.8  350.46  4765.5  352.59  4795.6  351.75  4976.3   352.2  4993.4  347.38
  4996.1  346.88  4999.4  347.38  5006.4  350.02  5013.4  351.04  5026.5  357.95
  5036.5  360.04  5197.1  360.78  5347.7  364.97  5387.9  363.92    5459  364.54
#Mann= 3 ,-1 , 0
  3555.1     .05       0  4993.4     .03       0  4999.4     .05       0
Bank Sta=4976.3,5036.5
XS Rating Curve= 0 ,0
Exp/Cntr=0.3,0.1

Type RM Length L Ch R = 1 ,17184   ,711,711,711
BEGIN DESCRIPTION:
UNT021 IN BECR 20.0
END DESCRIPTION:
XS GIS Cut Line= 4
      3833287.13     10484702.32      3833308.83     10485596.38
      3833100.49     10485952.28      3833291.14      10486415.9
#Sta/Elev= 30
  3959.9  378.36  4177.8  376.31  4507.9  367.61    4608  360.98    4648  356.98
  4676.7  351.47    4708   349.4    4758  351.07  4870.2   349.6  4928.2  352.74
  4959.3  350.65  4996.5  351.32  5002.3  346.86    5015  345.77  5017.7  345.27
    5021  345.77  5023.8  348.79  5032.4  349.48  5045.3   353.8  5055.2  355.02
    5061  357.18  5113.6  358.57  5119.6  359.89  5125.4  358.96  5242.7  359.28
  5350.9  361.91  5492.3  361.05    5632  362.35  5700.2  364.82  5767.9  364.36
#Mann= 3 ,-1 , 0
  3959.9     .05       0    5015     .03       0    5021     .05       0
Bank Sta=4996.5,5061
XS Rating Curve= 0 ,0
Exp/Cntr=0.3,0.1

Type RM Length L Ch R = 1 ,16473   ,810,810,810
BEGIN DESCRIPTION:
UNT021 IN BECR 18.0
END DESCRIPTION:
XS GIS Cut Line= 3
      3832744.59     10484489.57      3832692.51     10485353.32
      3833121.81     10486316.01
#Sta/Elev= 30
  3942.6  378.97  4323.9  377.31  4414.1   373.9  4434.1  371.03  4474.2   370.8
  4504.2  368.96  4554.3  365.34  4603.1  359.49  4694.6  354.32  4848.3  350.92
    4903  347.19  4961.8  347.57  4985.1  347.08  4990.6  343.58  4998.6  342.32
  5001.3  341.82  5004.6  342.32  5008.3  348.29  5013.8  347.28  5023.5  348.07
  5083.4  346.95  5106.7  352.43  5153.1  355.35  5198.7   357.1  5280.2  357.36
  5355.3  360.25  5471.5  359.74  5658.5   362.5  5795.7  362.08    5862  361.77
#Mann= 4 ,-1 , 0
  3942.6     .05       0  4998.6     .03       0  5004.6     .05       0
  5795.7     .08       0
Bank Sta=4961.8,5008.3
XS Rating Curve= 0 ,0
Exp/Cntr=0.3,0.1

Type RM Length L Ch R = 1 ,15663   ,135,135,135
BEGIN DESCRIPTION:
UNT021 IN BECR 17.0
END DESCRIPTION:
XS GIS Cut Line= 5
      3831164.71     10484502.61      3831919.94     10485184.05
      3832275.84     10485518.25        3832584.     10485800.37
      3832856.02     10486029.21
#Sta/Elev= 30
  3658.5  378.53    3713  377.47  3865.9  375.86  3960.4  372.91  4018.9  370.06
  4089.1  366.52  4217.8  359.59  4311.6  355.95  4346.6  358.61  4403.9  359.64
  4477.7  354.65  4630.6  349.71  4781.1   348.2  4864.6  347.07  4930.5  345.79
  4955.7  345.73  5002.1  340.01  5004.8  339.51  5008.1  340.01  5019.2  344.12
  5033.4   344.9  5126.5  345.03  5132.5  346.46    5154  344.69  5256.4  347.59
  5309.4     354  5435.9  356.71  5670.8  359.34  5893.1  360.41  5937.2  361.23
#Mann= 20 ,-1 , 0
  3658.5     .05       0    3713     .08       0  3865.9     .08       0
  3960.4     .05       0  4018.9     .08       0  4089.1     .05       0
  4217.8     .05       0  4346.6     .05       0  4477.7     .08       0
  4630.6     .08       0  4781.1     .08       0  4864.6     .05       0
  4930.5     .08       0  5002.1     .03       0  5008.1     .05       0
  5126.5     .05       0  5256.4     .05       0  5435.9     .08       0
  5670.8     .05       0  5893.1     .05       0
Bank Sta=4955.7,5132.5
XS Rating Curve= 0 ,0
Exp/Cntr=0.3,0.1

Type RM Length L Ch R = 1 ,15528   ,964,964,964
BEGIN DESCRIPTION:
UNT021 IN BECR 16.0
END DESCRIPTION:
XS GIS Cut Line= 5
      3831017.16     10484598.11       3831581.4     10485058.18
      3832215.08     10485605.06      3832466.81     10485865.47
      3832701.17     10486099.84
#Sta/Elev= 30
    3595  374.48    3968  368.11  4038.4  364.34  4060.7  360.57  4166.2  355.91
  4438.9  349.18  4457.6  348.41  4614.7  346.25  4691.7  345.17  4771.9  344.47
  4818.1  344.71    4929  345.21  4944.5  345.11  4961.3  344.83  4975.6  340.99
  4982.2  342.57  4993.4  340.21  4996.2  339.71  4999.4  340.21  5018.3  346.99
    5071  348.97  5086.1  348.49  5200.5  349.34  5235.1  352.62  5251.7  355.11
    5280  353.78  5337.3  356.47  5463.9  359.84  5744.2  360.46  5853.7  361.26
#Mann= 17 ,-1 , 0
    3595     .05       0  4438.9     .08       0  4457.6     .05       0
  4614.7     .12       0  4691.7     .05       0  4771.9     .12       0
  4818.1     .05       0    4929     .12       0  4944.5     .05       0
  4993.4     .04       0  4999.4     .05       0    5071     .08       0
  5086.1     .05       0  5200.5     .08       0  5235.1     .05       0
  5337.3     .08       0  5744.2     .05       0
Bank Sta=4961.3,5018.3
XS Rating Curve= 0 ,0
Exp/Cntr=0.3,0.1

Type RM Length L Ch R = 1 ,14564   ,1419,1419,1419
BEGIN DESCRIPTION:
UNT021 IN BECR 15.0
END DESCRIPTION:
XS GIS Cut Line= 2
      3831012.82     10484702.27        3831972.     10486164.92
#Sta/Elev= 30
  3949.8  370.43  4155.1  367.04  4320.9  361.66  4444.5  355.56  4712.7   345.3
  4848.4   343.8  4938.9  341.27  4963.8  341.33  4993.1  339.33  4999.7  335.67
  5005.2   335.2  5007.9   334.7  5011.2   335.2  5023.3  342.79  5035.5  344.91
  5064.6  345.96  5090.6  347.42  5158.8  350.51  5173.9  352.53  5252.3  354.26
  5261.4  355.47  5346.4  354.42  5418.2     356  5448.2  358.83  5469.3   357.4
  5541.7  358.91  5592.9  358.47    5614   359.6  5635.1  358.45  5698.9   358.6
#Mann= 6 ,-1 , 0
  3949.8     .05       0  4938.9     .12       0  5005.2     .07       0
  5011.2     .12       0  5064.6     .16       0  5090.6     .05       0
Bank Sta=4963.8,5035.5
XS Rating Curve= 0 ,0
Exp/Cntr=0.3,0.1

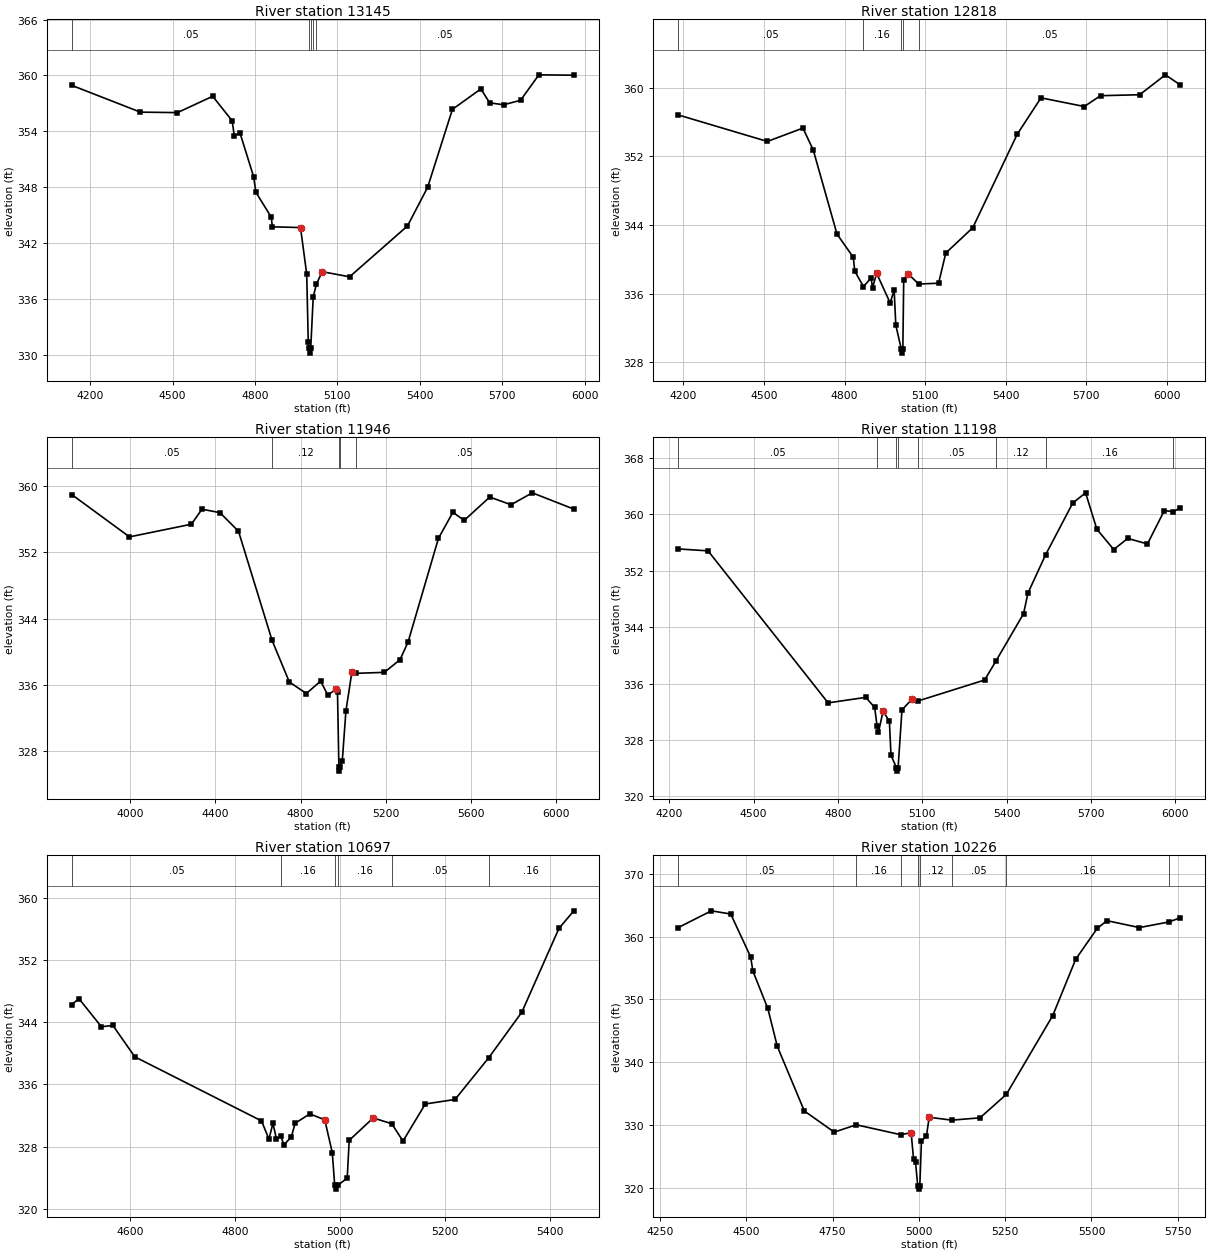
Type RM Length L Ch R = 1 ,13145   ,327,327,327
BEGIN DESCRIPTION:
UNT021 IN BECR 13.0
END DESCRIPTION:
XS GIS Cut Line= 3
       3830257.6     10485162.33        3830709.     10485739.61
      3831694.21     10486217.02
#Sta/Elev= 30
  4133.1  358.94    4383  356.07  4517.7  356.02  4646.1  357.77  4716.7  355.15
  4724.8  353.53  4745.6  353.82  4795.3  349.13  4803.2  347.49  4859.5   344.8
  4863.1  343.78  4965.7   343.7  4988.3  338.72  4993.9  331.43  4996.9  330.74
  4999.7  330.24  5002.9  330.74    5012  336.27  5023.5  337.62  5044.6  338.97
  5144.4  338.42  5355.1  343.87  5428.4  348.01  5518.7  356.37  5622.2  358.56
  5654.2  357.07  5704.9  356.86  5766.7  357.34  5833.4  360.07  5960.7  360.03
#Mann= 5 ,-1 , 0
  4133.1     .05       0  4996.9     .03       0  5002.9     .05       0
    5012     .16       0  5023.5     .05       0
Bank Sta=4965.7,5044.6
XS Rating Curve= 0 ,0
Exp/Cntr=0.3,0.1

Type RM Length L Ch R = 1 ,12818   ,872,872,872
BEGIN DESCRIPTION:
UNT021 IN BECR 12.0
END DESCRIPTION:
XS GIS Cut Line= 4
      3830270.64     10485301.25      3830613.51     10485956.62
      3831099.61     10486310.19       3831624.7     10486373.28
#Sta/Elev= 30
  4180.5  356.82  4512.4  353.73  4644.9  355.29  4683.4  352.72  4771.7  342.94
  4832.2  340.25  4837.9  338.63  4870.3  336.82  4898.4  337.84  4904.1  336.71
  4919.3  338.37  4969.8  334.92  4984.5  336.44  4990.7  332.33  5010.9  329.58
  5013.6  329.08  5016.9  329.58  5020.1  337.61  5034.8  338.35  5076.2  337.13
  5149.9  337.22  5176.9  340.74  5277.4  343.69  5442.8  354.57  5531.3  358.81
  5692.5   357.8  5752.9  359.06  5898.7  359.17  5994.6  361.49  6050.1  360.31
#Mann= 5 ,-1 , 0
  4180.5     .05       0  4870.3     .16       0  5010.9     .07       0
  5016.9     .16       0  5076.2     .05       0
Bank Sta=4919.3,5034.8
XS Rating Curve= 0 ,0
Exp/Cntr=0.3,0.1

Type RM Length L Ch R = 1 ,11946   ,748,748,748
BEGIN DESCRIPTION:
UNT021 IN BECR 11.0
END DESCRIPTION:
XS GIS Cut Line= 5
      3830100.78     10485159.78      3830156.34     10485854.19
      3830392.45     10486229.19       3831010.5      10486527.8
      3831544.88     10486520.86
#Sta/Elev= 30
  3724.4     359  3995.7  353.88  4286.6  355.41  4336.8  357.23    4421  356.81
  4508.3  354.56  4666.3  341.35  4747.2  336.33  4827.3  334.93  4894.3  336.43
  4928.6  334.73  4968.2  335.49  4973.8   335.1  4980.2  326.04  4982.9  325.54
  4986.2  326.04  4996.4  326.81  5013.4  332.83  5041.6  337.56    5060  337.37
  5194.2  337.49  5267.6  339.02  5305.3  341.14  5448.4   353.7  5516.2  356.85
  5569.7  355.88  5689.7   358.7  5789.7  357.77  5889.7  359.21    6085  357.24
#Mann= 5 ,-1 , 0
  3724.4     .05       0  4666.3     .12       0  4980.2     .07       0
  4986.2     .12       0    5060     .05       0
Bank Sta=4968.2,5041.6
XS Rating Curve= 0 ,0
Exp/Cntr=0.3,0.1

Type RM Length L Ch R = 1 ,11198   ,501,501,501
BEGIN DESCRIPTION:
UNT021 IN BECR 10.0
END DESCRIPTION:
XS GIS Cut Line= 5
       3829670.2     10486249.99      3829989.67     10486645.86
      3830434.12     10486868.08      3830531.34     10487284.74
      3830524.43     10487637.02
#Sta/Elev= 30
  4231.9  355.07  4337.9   354.8    4765  333.26  4899.1  334.04  4930.6  332.61
  4938.8  330.05  4943.9  329.08  4960.6  332.09    4983  330.63  4988.6  325.84
  5007.9  324.09  5010.7  323.59  5013.9  324.09  5027.7  332.26  5064.8  333.85
  5086.3  333.55  5321.8   336.5  5361.2  339.14  5460.1  345.89  5475.8  348.82
    5539  354.28  5635.4  361.59  5680.8  363.02  5720.8  357.87  5780.8  354.99
  5830.8  356.56  5900.8  355.78  5960.9  360.51  5992.6  360.34  6017.7  360.89
#Mann= 8 ,-1 , 0
  4231.9     .05       0  4938.8     .16       0  5007.9     .07       0
  5013.9     .16       0  5086.3     .05       0  5361.2     .12       0
    5539     .16       0  5992.6     .05       0
Bank Sta=4960.6,5064.8
XS Rating Curve= 0 ,0
Exp/Cntr=0.3,0.1

Type RM Length L Ch R = 1 ,10697   ,471,471,471
BEGIN DESCRIPTION:
UNT021 IN BECR 9.0
END DESCRIPTION:
XS GIS Cut Line= 3
      3829699.64     10486610.21      3830099.61     10486960.19
      3830399.59     10487260.17
#Sta/Elev= 30
  4488.9  346.26  4502.6  347.01  4545.3  343.41  4567.2  343.57  4608.9  339.54
    4850  331.31  4864.2  328.97  4871.8  330.99  4878.5  328.98    4887  329.33
  4892.7  328.21  4906.9  329.27  4914.1  331.01  4942.1  332.21  4970.5  331.44
  4984.8  327.22  4989.4  323.04  4992.1  322.54  4995.4  323.04  5013.2  323.95
    5017  328.81  5062.8  331.69    5098  330.94  5119.4  328.71  5161.8  333.48
  5218.4  334.06  5282.6  339.42  5345.6  345.28  5416.3  356.05  5444.6   358.3
#Mann= 6 ,-1 , 0
  4488.9     .05       0    4887     .16       0  4989.4     .07       0
  4995.4     .16       0    5098     .05       0  5282.6     .16       0
Bank Sta=4970.5,5062.8
XS Rating Curve= 0 ,0
Exp/Cntr=0.3,0.1

Type RM Length L Ch R = 1 ,10226   ,736,736,736
BEGIN DESCRIPTION:
UNT021 IN BECR 8.0
END DESCRIPTION:
XS GIS Cut Line= 4
      3829371.59     10486694.44      3829677.17     10487083.36
      3830371.62     10487416.69      3830433.76     10487596.23
#Sta/Elev= 30
  4302.5  361.47  4398.5  364.14  4454.6  363.63  4512.4  356.79  4518.7  354.55
  4562.1  348.57  4589.6  342.52  4667.9  332.22  4754.6  328.85  4818.4  330.02
    4948  328.43  4977.3  328.78  4984.5  324.52  4990.1  324.07  4996.5  320.26
  4999.2  319.76  5002.5  320.26  5007.2  327.39  5021.7  328.25  5029.8  331.22
    5095  330.76    5177  331.13  5253.3  334.87  5387.7  347.43  5454.3  356.42
  5516.5  361.33  5544.7  362.57  5638.8  361.47    5724  362.36  5757.4  363.03
#Mann= 8 ,-1 , 0
  4302.5     .05       0  4818.4     .16       0    4948     .12       0
  4996.5     .07       0  5002.5     .12       0    5095     .05       0
  5253.3     .16       0    5724     .05       0
Bank Sta=4977.3,5029.8
XS Rating Curve= 0 ,0
Exp/Cntr=0.3,0.1