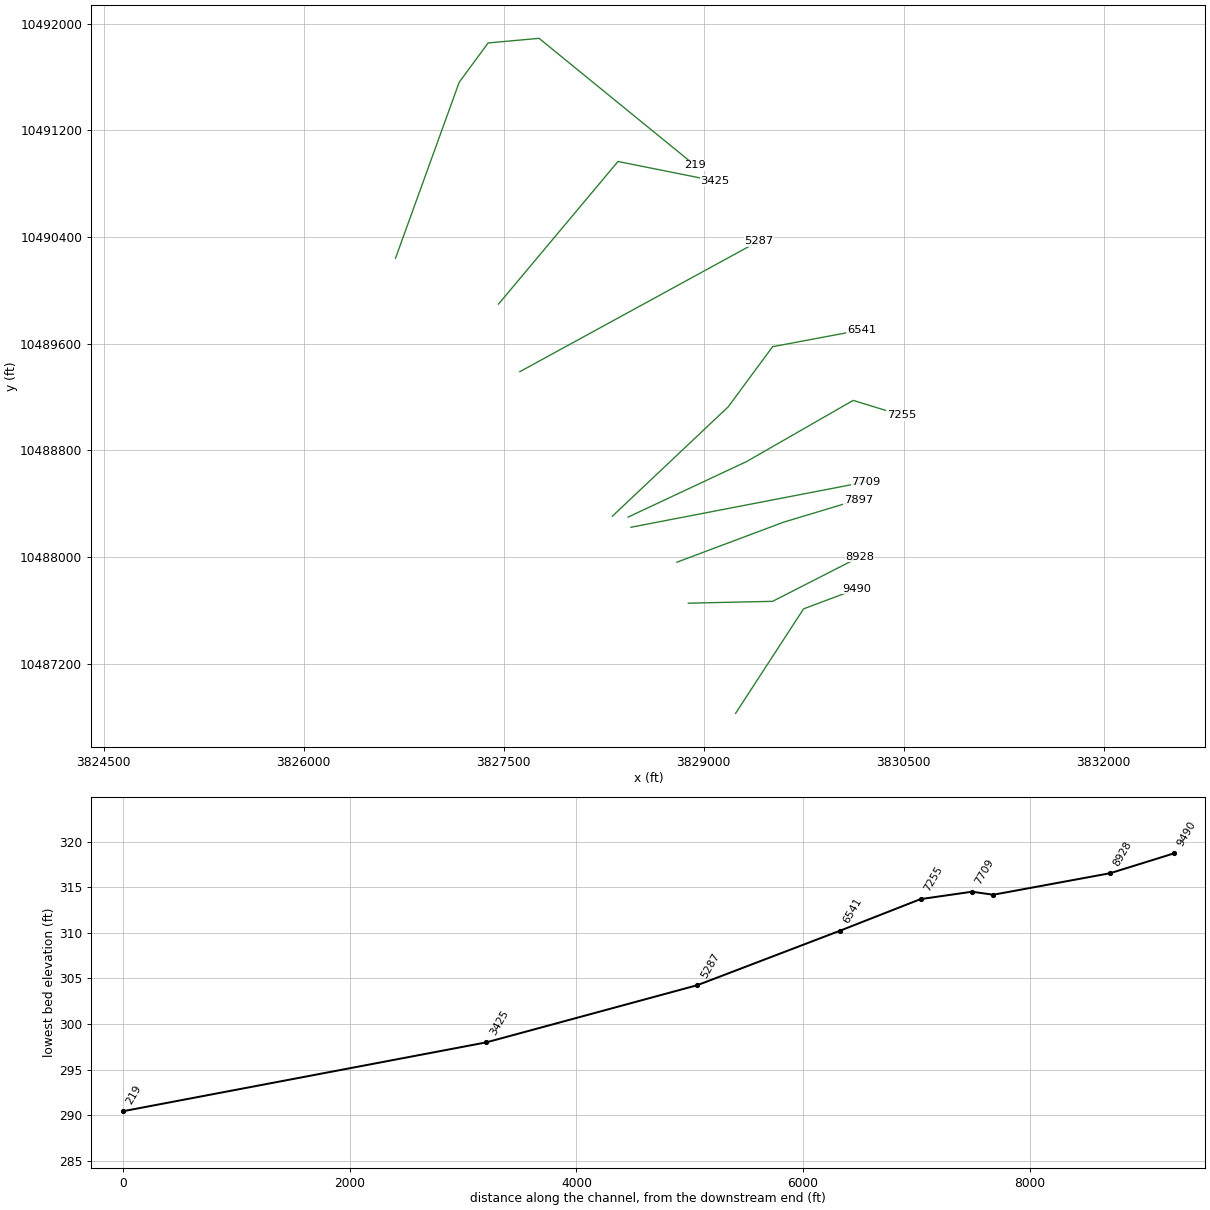
HEC-RAS study UNT021 IN BECR.prj: UNT021 IN BECR Base Level Engineering

--- UNT021 IN BECR.g01 (geometry) --- (continued)

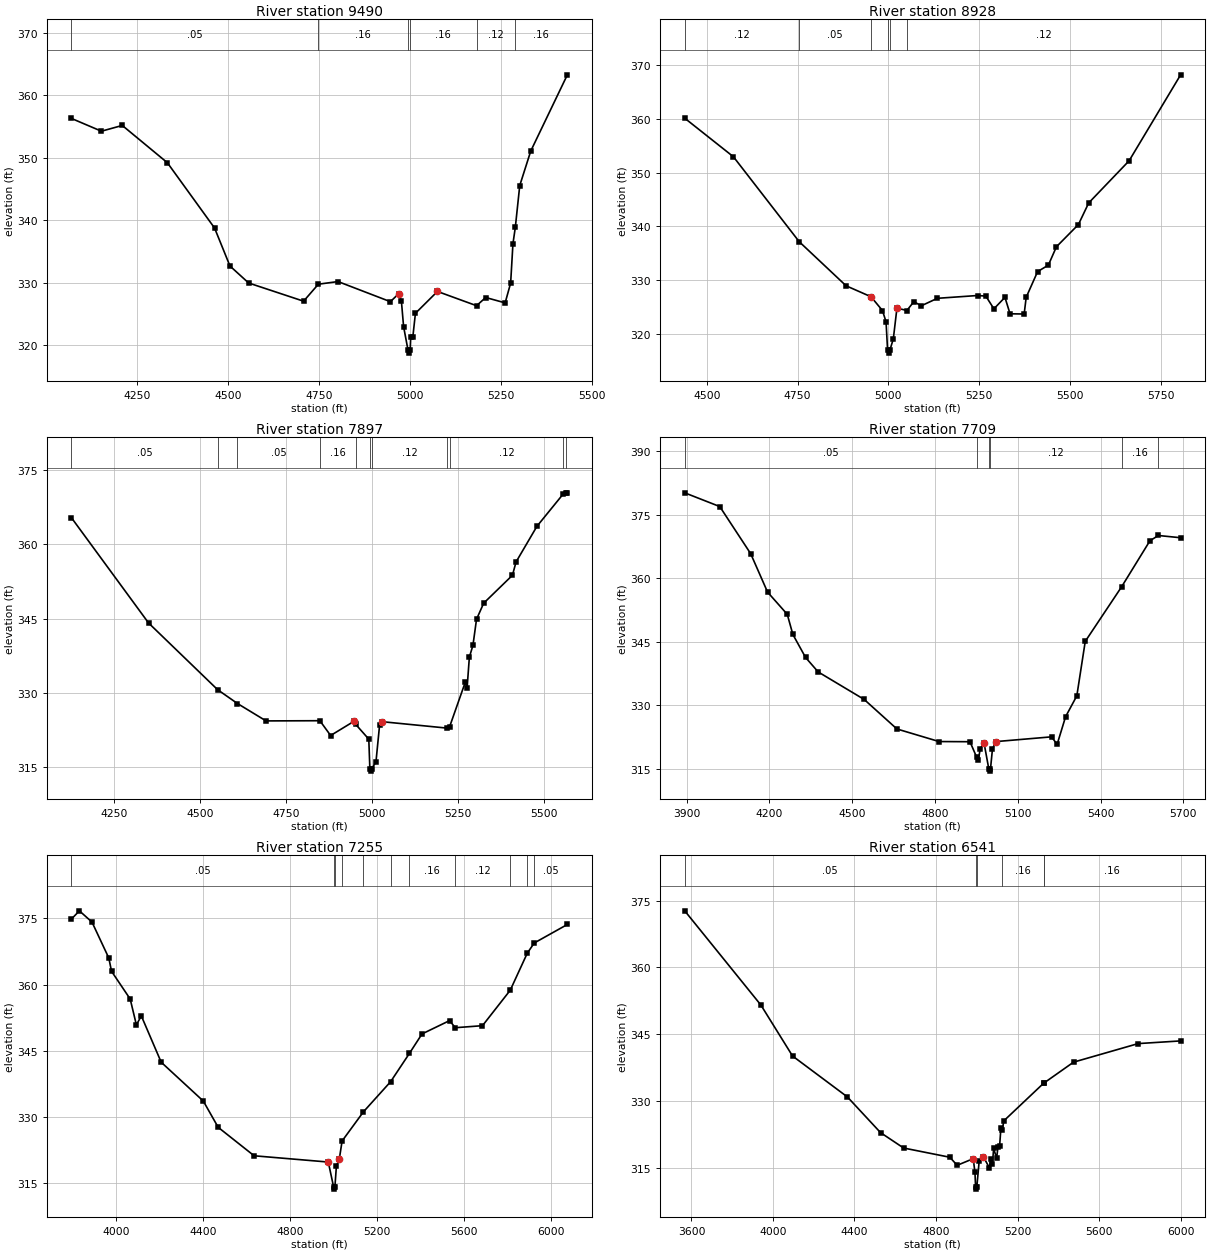
Type RM Length L Ch R = 1 ,9490    ,562,562,562
BEGIN DESCRIPTION:
UNT021 IN BECR 7.0
END DESCRIPTION:
XS GIS Cut Line= 3
      3829239.65     10486826.39      3829749.61     10487610.19
      3830149.61     10487760.19
#Sta/Elev= 30
    4070  356.25  4152.3  354.21  4209.6  355.13  4333.4  349.17  4463.2  338.71
  4505.4  332.64  4556.8  329.92  4707.7  327.01  4748.3  329.73  4802.3  330.15
  4946.2  326.93  4969.3  328.23  4976.4  327.03  4982.4  322.95  4994.5   319.2
  4997.3   318.7  5000.5   319.2  5002.1  321.29  5007.8  321.29  5014.9  325.07
  5075.4  328.57  5182.8  326.29    5208   327.6  5261.4  326.74  5276.5  329.91
  5282.8  336.19  5289.4  338.85  5301.5  345.51  5331.7  351.03  5432.3  363.23
#Mann= 6 ,-1 , 0
    4070     .05       0  4748.3     .16       0  4994.5     .07       0
  5000.5     .16       0  5182.8     .12       0  5289.4     .16       0
Bank Sta=4969.3,5075.4
XS Rating Curve= 0 ,0
Exp/Cntr=0.3,0.1

Type RM Length L Ch R = 1 ,8928    ,1031,1031,1031
BEGIN DESCRIPTION:
UNT021 IN BECR 6.0
END DESCRIPTION:
XS GIS Cut Line= 3
      3828885.51      10487652.8      3829517.45     10487666.69
      3830170.27     10488000.04
#Sta/Elev= 30
  4439.4  360.07  4573.5  352.92  4754.6  337.18  4883.6  329.01  4952.2  326.98
  4983.6  324.43  4993.6  322.34  4997.9  317.03  5000.7  316.53  5003.9  317.03
  5013.6  319.16  5023.6  324.88    5051  324.43  5070.1  326.07  5090.5   325.3
  5134.9  326.69    5246  327.21  5268.3   327.1  5290.5  324.74  5320.9  326.87
  5334.9  323.82  5373.8  323.78  5379.4  326.88  5410.8  331.64  5440.4  332.84
  5462.6  336.24  5523.1  340.36  5551.5  344.37  5662.7  352.18  5804.5  368.11
#Mann= 6 ,-1 , 0
  4439.4     .12       0  4754.6     .05       0  4952.2     .16       0
  4997.9     .07       0  5003.9     .16       0    5051     .12       0
Bank Sta=4952.2,5023.6
XS Rating Curve= 0 ,0
Exp/Cntr=0.3,0.1

Type RM Length L Ch R = 1 ,7897    ,188,188,188
BEGIN DESCRIPTION:
UNT021 IN BECR 4.0
END DESCRIPTION:
XS GIS Cut Line= 3
      3828799.62     10487960.19      3829599.61     10488260.19
      3830162.55      10488429.7
#Sta/Elev= 30
  4124.9  365.38  4349.2  344.11    4550  330.63  4607.8  327.83  4690.9  324.32
  4847.4  324.36  4878.7  321.37  4947.3  324.27  4951.5  323.63  4989.7  320.63
  4992.8  314.67  4995.5  314.17  4998.8  314.67  5010.6  316.08  5021.1  323.49
  5028.8  324.16  5216.7  322.87  5224.6  323.11  5270.3  332.14  5275.5  330.89
  5282.2  337.21  5292.6  339.59    5303  344.86  5323.9  348.12  5407.5  353.76
    5418  356.45  5478.8  363.66  5555.2  370.19  5563.8  370.42  5567.2  370.42
#Mann= 11 ,-1 , 0
  4124.9     .05       0    4550     .16       0  4607.8     .05       0
  4847.4     .16       0  4951.5     .12       0  4992.8     .07       0
  4998.8     .12       0  5216.7     .16       0  5224.6     .12       0
  5555.2     .16       0  5563.8     .05       0
Bank Sta=4947.3,5028.8
XS Rating Curve= 0 ,0
Exp/Cntr=0.3,0.1

Type RM Length L Ch R = 1 ,7709    ,454,454,454
BEGIN DESCRIPTION:
UNT021 IN BECR 3.0
END DESCRIPTION:
XS GIS Cut Line= 2
      3828454.96     10488222.25      3830218.84     10488562.52
#Sta/Elev= 30
  3893.4  380.18  4020.3  376.94  4132.4  365.81  4193.5  356.75  4264.8  351.51
  4285.1  346.76  4331.1  341.33  4376.8  337.91  4543.6  331.41    4662  324.45
  4814.7  321.48  4926.8  321.44  4950.5  317.84  4957.3  317.12  4963.6  319.77
  4977.7  321.13    4995     315  4997.8   314.5    5001     315  5008.2  319.73
  5020.5  321.47  5222.1  322.59  5242.5  320.82    5273  327.33  5313.8  332.27
  5344.3  345.12  5476.4  358.04  5578.6  368.86  5609.2  370.11  5689.8  369.58
#Mann= 6 ,-1 , 0
  3893.4     .05       0  4950.5     .12       0    4995     .07       0
    5001     .12       0  5476.4     .16       0  5609.2     .05       0
Bank Sta=4977.7,5020.5
XS Rating Curve= 0 ,0
Exp/Cntr=0.3,0.1

Type RM Length L Ch R = 1 ,7255    ,714,714,714
BEGIN DESCRIPTION:
Mapping XS 34f55c95
END DESCRIPTION:
XS GIS Cut Line= 4
      3828434.11     10488298.63        3829323.      10488715.3
      3830121.62     10489173.63      3830482.71     10489062.53
#Sta/Elev= 30
  3793.7  374.83  3830.1  376.69  3888.1  374.14  3965.4  366.01    3978     363
  4063.8  356.72  4092.2  350.88    4115   352.9  4206.3  342.42  4399.9  333.63
  4468.4  327.68  4633.7  321.24  4974.7  319.82  4999.1  314.19  5001.8  313.69
  5005.1  314.19  5012.1  318.98  5025.2  320.45  5038.2  324.59  5136.3  331.19
  5261.3  338.01  5347.5   344.4  5405.6  348.82  5532.5  351.84  5558.6  350.23
  5683.7  350.69  5811.4  358.72  5889.6  367.09  5921.7  369.41    6074   373.6
#Mann= 11 ,-1 , 0
  3793.7     .05       0  4999.1     .03       0  5005.1     .05       0
  5038.2     .12       0  5136.3     .16       0  5261.3     .12       0
  5347.5     .16       0  5558.6     .12       0  5811.4     .05       0
  5889.6     .16       0  5921.7     .05       0
Bank Sta=4974.7,5025.2
XS Rating Curve= 0 ,0
Exp/Cntr=0.3,0.1

Type RM Length L Ch R = 1 ,6541    ,1254,1254,1254
BEGIN DESCRIPTION:
Mapping XS 897d9364
END DESCRIPTION:
XS GIS Cut Line= 4
      3828316.04     10488305.56      3829184.12     10489125.02
      3829517.45     10489576.41      3830184.13     10489701.41
#Sta/Elev= 30
    3567   372.7  3940.8  351.54  4096.1   340.1  4365.2  330.91  4527.8   322.9
  4641.1  319.44  4867.7  317.37  4903.9  315.56  4982.6  317.05    4991  313.98
  4994.2  310.71    4997  310.21  5000.2  310.71  5011.9  316.59  5032.7  317.45
    5062  314.99  5068.2   316.9  5076.6  315.81  5082.8  319.34  5097.4  317.15
  5103.7  319.56  5112.1  319.93  5118.3  323.85  5124.5  323.43  5132.9  325.55
  5327.6  333.97  5327.7  333.97  5474.8  338.72  5792.1  342.89  6000.2  343.49
#Mann= 6 ,-1 , 0
    3567     .05       0  4994.2     .03       0  5000.2     .05       0
  5124.5     .16       0  5327.6     .05       0  5327.7     .16       0
Bank Sta=4982.6,5032.7
XS Rating Curve= 0 ,0
Exp/Cntr=0.3,0.1

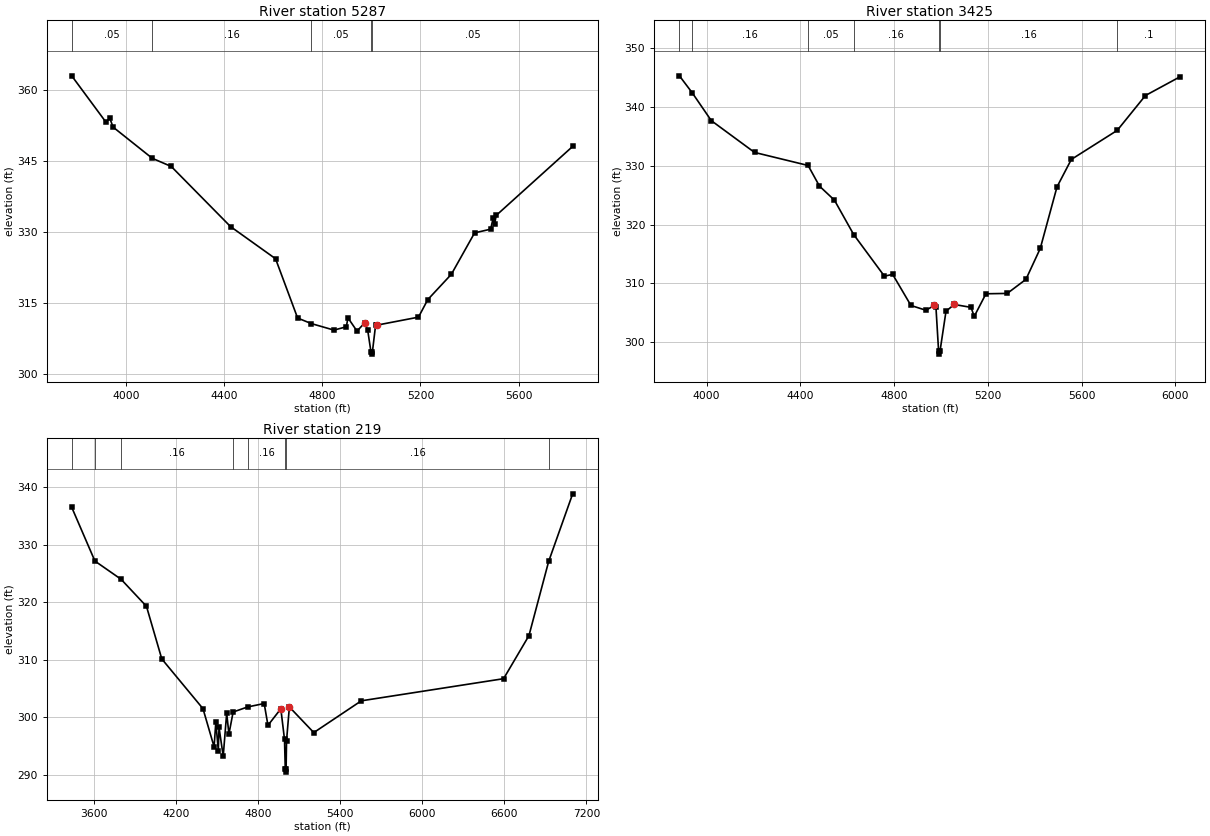
Type RM Length L Ch R = 1 ,5287    ,1862,1862,1862
BEGIN DESCRIPTION:
Mapping XS 5140b25d
END DESCRIPTION:
XS GIS Cut Line= 2
      3827621.65     10489388.93      3829413.25     10490368.06
#Sta/Elev= 30
  3778.8  362.88  3917.9  353.15  3934.1  353.93  3947.4  352.08  4107.3   345.5
  4184.5  343.79    4426  331.13  4609.6  324.35  4699.5  311.86  4755.6  310.69
  4847.7  309.32    4898  310.02  4904.7   311.9  4941.6  309.11    4973  310.86
  4985.3  309.24  4998.4  304.76  5001.2  304.26  5004.4  304.76  5017.5  310.44
  5023.2  310.37  5192.1  312.05  5230.1  315.75  5326.3  321.09  5420.8   329.8
  5486.2  330.58  5496.6  332.94  5502.3  331.59  5508.7  333.47  5820.5  348.01
#Mann= 5 ,-1 , 0
  3778.8     .05       0  4107.3     .16       0  4755.6     .05       0
  4998.4     .03       0  5004.4     .05       0
Bank Sta=4973,5023.2
XS Rating Curve= 0 ,0
Exp/Cntr=0.3,0.1

Type RM Length L Ch R = 1 ,3425    ,3206,3206,3206
BEGIN DESCRIPTION:
UNT021 IN BECR 2.0
END DESCRIPTION:
XS GIS Cut Line= 3
      3827461.92     10489895.88      3828357.73      10490965.3
      3829085.77     10490819.69
#Sta/Elev= 30
  3884.3   345.3  3939.2   342.4  4020.4  337.68  4204.7  332.28  4433.4  330.06
  4481.9  326.55  4545.6  324.17    4628  318.31    4759  311.24  4794.1  311.55
  4872.2  306.26    4936  305.45  4972.4  306.27  4978.9  305.95  4990.2  298.49
  4992.9  297.99  4996.2  298.49  5021.8  305.28  5056.9  306.43  5128.5  305.94
  5142.2   304.4  5192.2  308.25  5283.1  308.31  5362.8   310.7    5424  315.96
  5495.4  326.42  5556.6  331.09  5752.5  336.03  5872.7  341.95  6021.8  345.17
#Mann= 7 ,-1 , 0
  3884.3     .05       0  3939.2     .16       0  4433.4     .05       0
    4628     .16       0  4990.2     .07       0  4996.2     .16       0
  5752.5      .1       0
Bank Sta=4972.4,5056.9
XS Rating Curve= 0 ,0
Exp/Cntr=0.3,0.1

Type RM Length L Ch R = 1 ,219     ,0,0,0
BEGIN DESCRIPTION:
UNT021 IN BECR 1.0
END DESCRIPTION:
XS GIS Cut Line= 5
      3826689.31     10490239.57      3827166.75     10491559.05
      3827383.77     10491854.19      3827765.71     10491888.91
      3828935.42     10490935.82
#Sta/Elev= 30
  3437.1  336.53  3606.7  327.17    3798     324  3983.6  319.29  4095.5  310.14
  4396.7  301.48    4478  294.83  4490.6  299.18  4508.6  294.19  4513.9  298.22
  4544.6  293.21  4569.9  300.71  4586.3  297.06    4617   300.9  4722.9  301.78
  4844.1  302.38  4871.6  298.58  4965.7  301.46  4992.7  296.12  4998.2  290.94
  5000.9  290.44  5004.2  290.94  5007.4  295.88  5028.2  301.78  5206.6  297.32
    5554  302.85  6594.1   306.7  6779.4  314.19  6923.6  327.11    7099  338.87
#Mann= 8 ,-1 , 0
  3437.1     .16       0  3606.7     .05       0    3798     .16       0
    4617     .12       0  4722.9     .16       0  4998.2     .07       0
  5004.2     .16       0  6923.6      .1       0
Bank Sta=4965.7,5028.2
XS Rating Curve= 0 ,0
Exp/Cntr=0.3,0.1

Chan Stop Cuts=-1
Use User Specified Reach Order=0
Composite Channel Slope=5