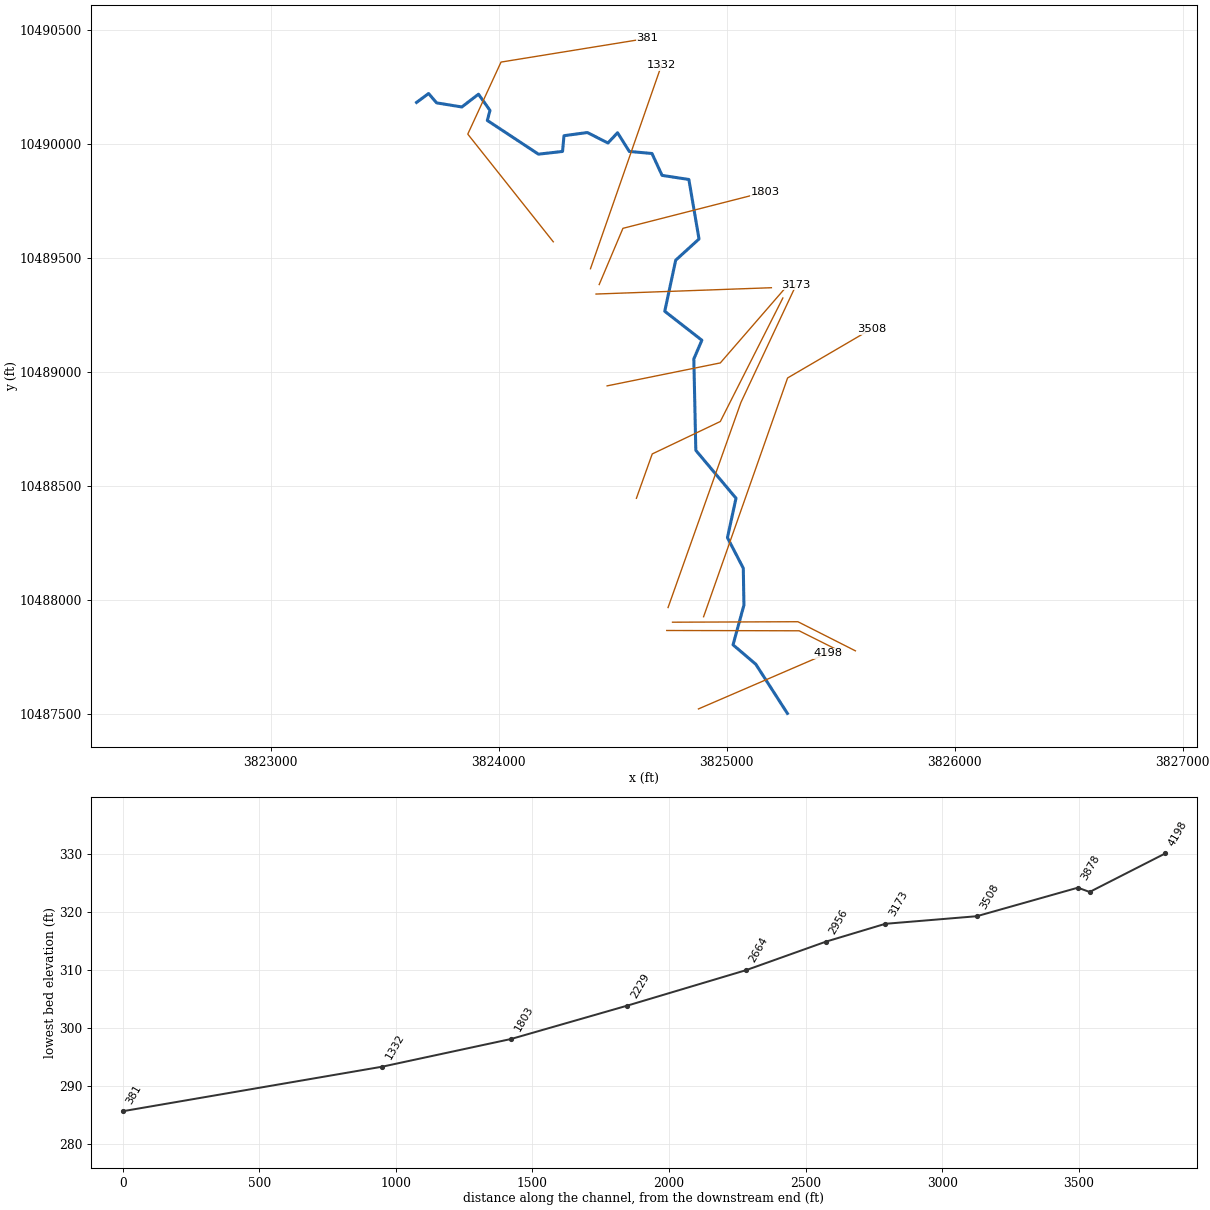
--- UNT023 IN BECR.prj (project) ---

Proj Title=UNT023 IN BECR Base Level Engineering
Current Plan=p01
Default Exp/Contr=0.3,0.1
English Units
Geom File=g01
Flow File=f01
Plan File=p01
BEGIN DESCRIPTION:
UNT023 IN BECR
END DESCRIPTION:

--- UNT023 IN BECR.p01 (plan) ---

Plan Title=Multiple Run
Short Identifier=Multiple
Geom File=g01
Flow File=f01
Subcritical Flow
K Sum by GR= 0
Std Step Tol= 0.01
Critical Tol= 0.01
Num of Std Step Trials= 20
Max Error Tol= 0.3
Flow Tol Ratio= 0.001
Split Flow NTrial= 30
Split Flow Tol= 0.02
Split Flow Ratio= 0.02
Log Output Level= 0
Friction Slope Method= 1
Unsteady Friction Slope Method= 2
Unsteady Bridges Friction Slope Method= 1
Parabolic Critical Depth
Global Vel Dist=  1 , 1 , 1
Global Log Level= 0
CheckData=True
Encroach Param= -1, 0, 0, 0
BEGIN DESCRIPTION:
Multiple Run
END DESCRIPTION:

--- UNT023 IN BECR.f01 (steady flow) ---

Flow Title=Multiple
Number of Profiles=7
Profile Names=10-year,25-year,50-year,1pct_min,100-year,1pct_plu,500-year
River Rch & RM= UNT023 IN BECR,Reach-1,4198
     130     158     180     151     204     276     264
Boundary for River Rch & Prof#=UNT023 IN BECR,Reach-1,1
Up Type=0
Dn Type=3
Dn Slope=0.005
Boundary for River Rch & Prof#=UNT023 IN BECR,Reach-1,2
Up Type=0
Dn Type=3
Dn Slope=0.005
Boundary for River Rch & Prof#=UNT023 IN BECR,Reach-1,3
Up Type=0
Dn Type=3
Dn Slope=0.005
Boundary for River Rch & Prof#=UNT023 IN BECR,Reach-1,4
Up Type=0
Dn Type=3
Dn Slope=0.005
Boundary for River Rch & Prof#=UNT023 IN BECR,Reach-1,5
Up Type=0
Dn Type=3
Dn Slope=0.005
Boundary for River Rch & Prof#=UNT023 IN BECR,Reach-1,6
Up Type=0
Dn Type=3
Dn Slope=0.005
Boundary for River Rch & Prof#=UNT023 IN BECR,Reach-1,7
Up Type=0
Dn Type=3
Dn Slope=0.005

--- UNT023 IN BECR.g01 (geometry) ---

Geom Title=Existing Conditions

River Reach=UNT023 IN BECR,Reach-1
Reach XY= 30
      3825266.59     10487501.34      3825128.00     10487717.00
      3825028.25     10487802.00      3825076.00     10487976.00
      3825073.25     10488138.00      3825003.75     10488272.00
      3825041.25     10488445.00      3824865.00     10488655.00
      3824856.25     10489056.00      3824891.50     10489138.00
      3824728.75     10489265.00      3824776.75     10489489.00
      3824879.00     10489582.00      3824834.50     10489843.00
      3824717.00     10489861.00      3824672.75     10489957.00
      3824573.25     10489966.00      3824521.75     10490048.00
      3824479.50     10490003.00      3824389.25     10490049.00
      3824286.75     10490035.00      3824280.50     10489966.00
      3824174.75     10489954.00      3823950.50     10490102.00
      3823962.25     10490146.00      3823911.75     10490217.00
      3823838.75     10490161.00      3823728.25     10490179.00
      3823693.00     10490220.00      3823640.25     10490181.00

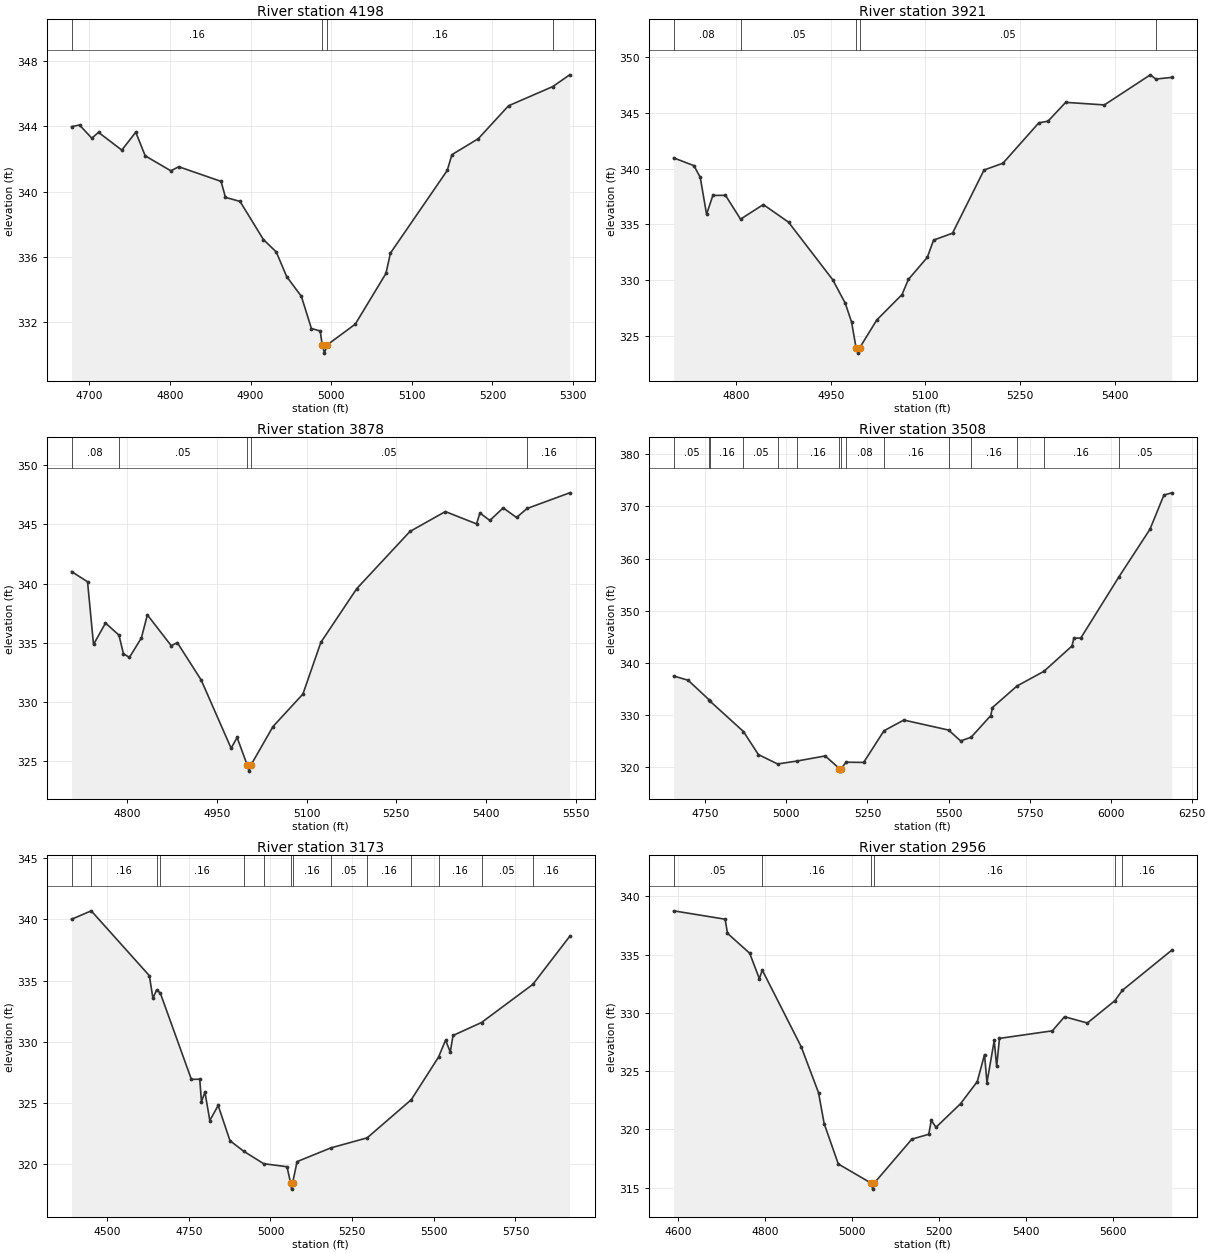
Type RM Length L Ch R = 1,4198,277,277,277
BEGIN DESCRIPTION:
UNT023 IN BECR 7.0
END DESCRIPTION:
XS GIS Cut Line= 2
      3824876.55     10487520.86      3825443.67     10487765.40
#Sta/Elev= 30
  4678.1  343.99  4688.0  344.09  4703.2  343.28  4711.5  343.64  4740.4  342.55
  4757.7  343.65  4769.4  342.20  4801.2  341.28  4811.0  341.53  4863.5  340.63
  4868.9  339.65  4887.0  339.40  4916.0  337.06  4931.9  336.30  4944.9  334.78
  4963.0  333.58  4975.5  331.60  4986.4  331.45  4988.9  330.59  4991.7  330.09
  4994.9  330.59  5029.9  331.87  5067.9  334.98  5073.5  336.23  5143.9  341.30
  5149.7  342.27  5182.4  343.25  5219.9  345.27  5274.8  346.45  5295.7  347.17
#Mann=4,-1,0
  4678.1    0.16       0  4988.9    0.07       0  4994.9    0.16       0
  5274.8    0.05       0
Bank Sta=4988.9,4994.9
Exp/Cntr=0.3,0.1

Type RM Length L Ch R = 1,3921,43,43,43
BEGIN DESCRIPTION:
Mapping XS c9fe11d2
END DESCRIPTION:
XS GIS Cut Line= 3
      3824737.39     10487864.87      3825318.15     10487863.57
      3825505.12     10487770.08
#Sta/Elev= 30
  4700.9  340.96  4733.1  340.26  4743.1  339.21  4753.1  335.90  4763.1  337.59
  4783.1  337.60  4807.0  335.46  4843.1  336.77  4883.1  335.19  4953.1  330.03
  4973.1  327.91  4983.1  326.22  4990.1  323.94  4992.9  323.44  4996.1  323.94
  5023.1  326.42  5063.1  328.70  5073.1  330.05  5103.1  332.03  5113.1  333.58
  5143.1  334.20  5193.1  339.87  5223.1  340.48  5279.9  344.10  5294.5  344.25
  5322.6  345.94  5383.9  345.71  5456.8  348.41  5465.5  348.03  5490.7  348.18
#Mann=5,-1,0
  4700.9    0.08       0  4807.0    0.05       0  4990.1    0.03       0
  4996.1    0.05       0  5465.5    0.16       0
Bank Sta=4990.1,4996.1
Exp/Cntr=0.3,0.1

Type RM Length L Ch R = 1,3878,370,370,370
BEGIN DESCRIPTION:
UNT023 IN BECR 6.0
END DESCRIPTION:
XS GIS Cut Line= 3
      3824762.87     10487901.25      3825312.85     10487903.33
      3825564.97     10487775.64
#Sta/Elev= 30
  4707.2  341.01  4733.9  340.15  4743.9  334.86  4763.9  336.67  4786.4  335.65
  4793.9  334.08  4803.9  333.77  4823.9  335.41  4833.9  337.36  4873.9  334.75
  4883.9  335.02  4923.9  331.86  4973.9  326.11  4983.9  327.02  5000.9  324.68
  5003.7  324.18  5006.9  324.68  5043.9  327.94  5093.9  330.68  5123.9  335.04
  5183.9  339.57  5272.8  344.39  5332.0  346.07  5384.2  345.03  5389.8  345.95
  5406.4  345.32  5428.7  346.38  5451.0  345.57  5468.7  346.33  5539.8  347.65
#Mann=5,-1,0
  4707.2    0.08       0  4786.4    0.05       0  5000.9    0.03       0
  5006.9    0.05       0  5468.7    0.16       0
Bank Sta=5000.9,5006.9
Exp/Cntr=0.3,0.1

Type RM Length L Ch R = 1,3508,335,335,335
BEGIN DESCRIPTION:
UNT023 IN BECR 5.0
END DESCRIPTION:
XS GIS Cut Line= 3
      3824899.09     10487925.17      3825267.59     10488972.51
      3825635.16     10489187.50
#Sta/Elev= 30
  4652.2  337.49  4696.8  336.68  4762.1  332.90  4763.5  332.72  4867.5  326.85
  4913.5  322.44  4972.9  320.63  5032.3  321.19  5119.7  322.17  5163.4  319.76
  5166.1  319.26  5169.4  319.76  5183.8  320.97  5238.3  320.93  5301.0  327.00
  5362.1  329.05  5500.1  327.13  5537.3  325.05  5569.8  325.76  5630.2  329.91
  5635.5  331.45  5711.0  335.57  5794.2  338.39  5880.7  343.24  5886.5  344.73
  5908.0  344.78  6025.1  356.46  6121.2  365.62  6164.2  372.17  6188.3  372.60
#Mann=15,-1,0
  4652.2    0.05       0  4762.1    0.08       0  4763.5    0.16       0
  4867.5    0.05       0  4972.9    0.08       0  5032.3    0.16       0
  5163.4    0.07       0  5169.4    0.16       0  5183.8    0.08       0
  5301.0    0.16       0  5500.1    0.08       0  5569.8    0.16       0
  5711.0    0.05       0  5794.2    0.16       0  6025.1    0.05       0
Bank Sta=5163.4,5169.4
Exp/Cntr=0.3,0.1

Type RM Length L Ch R = 1,3173,217,217,217
BEGIN DESCRIPTION:
UNT023 IN BECR 4.0
END DESCRIPTION:
XS GIS Cut Line= 3
      3824743.27     10487965.52      3825062.73     10488864.87
      3825305.19     10489380.95
#Sta/Elev= 30
  4391.2  340.01  4451.4  340.70  4629.3  335.40  4640.2  333.55  4651.3  334.22
  4662.5  334.00  4758.0  326.92  4783.5  326.94  4788.8  325.10  4799.4  325.88
  4814.4  323.56  4839.9  324.79  4876.1  321.91  4918.0  321.05  4979.2  320.03
  5050.6  319.78  5061.7  318.45  5064.5  317.95  5067.7  318.45  5081.5  320.20
  5184.7  321.32  5295.9  322.14  5431.0  325.26  5514.4  328.74  5536.0  330.13
  5550.4  329.16  5558.8  330.51  5646.0  331.57  5803.2  334.69  5915.8  338.61
#Mann=14,-1,0
  4391.2    0.05       0  4451.4    0.16       0  4651.3    0.05       0
  4662.5    0.16       0  4918.0    0.05       0  4979.2    0.16       0
  5061.7    0.07       0  5067.7    0.16       0  5184.7    0.05       0
  5295.9    0.16       0  5431.0    0.08       0  5514.4    0.16       0
  5646.0    0.05       0  5803.2    0.16       0
Bank Sta=5061.7,5067.7
Exp/Cntr=0.3,0.1

Type RM Length L Ch R = 1,2956,292,292,292
BEGIN DESCRIPTION:
Mapping XS 83853760
END DESCRIPTION:
XS GIS Cut Line= 4
      3824604.41     10488444.75      3824673.84     10488639.17
      3824972.45     10488781.53      3825246.75     10489323.18
#Sta/Elev= 30
  4590.0  338.77  4708.4  338.05  4713.7  336.84  4764.7  335.13  4786.9  332.95
  4793.7  333.68  4883.0  327.11  4922.9  323.16  4935.8  320.51  4968.3  317.04
  5044.5  315.38  5047.2  314.88  5050.5  315.38  5137.3  319.17  5176.2  319.59
  5181.9  320.78  5192.9  320.19  5249.1  322.21  5287.6  324.11  5304.3  326.43
  5309.9  324.03  5326.6  327.64  5332.2  325.41  5338.7  327.82  5460.2  328.47
  5488.1  329.68  5540.5  329.14  5603.9  331.06  5620.8  331.94  5734.4  335.39
#Mann=6,-1,0
  4590.0    0.05       0  4793.7    0.16       0  5044.5    0.07       0
  5050.5    0.16       0  5603.9    0.05       0  5620.8    0.16       0
Bank Sta=5044.5,5050.5
Exp/Cntr=0.3,0.1

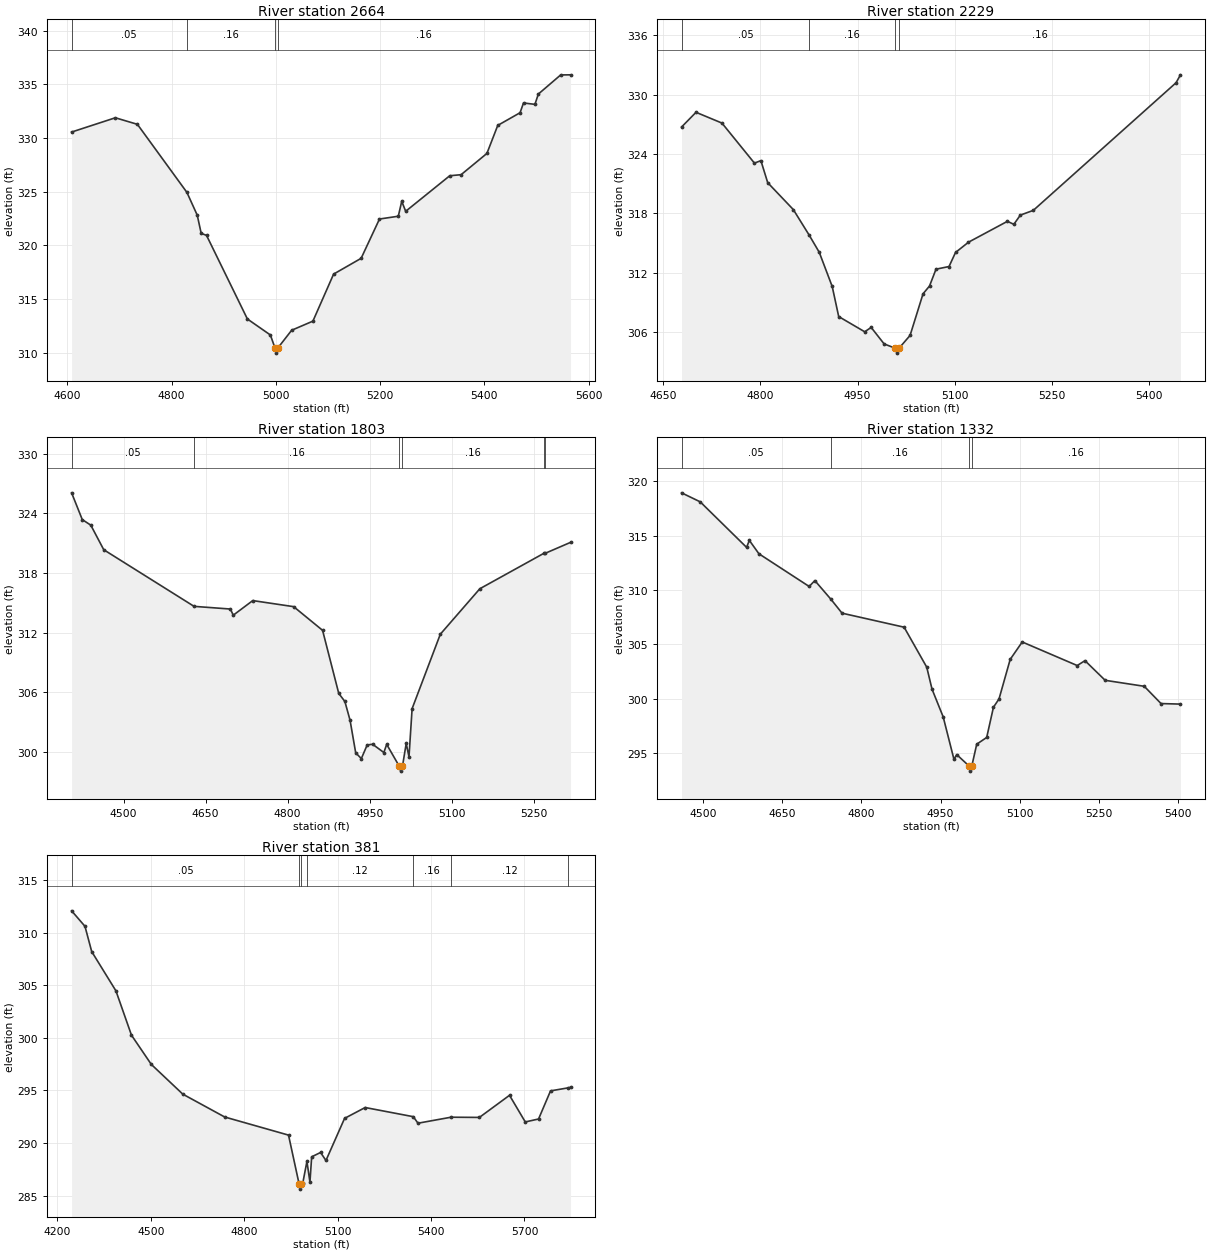
Type RM Length L Ch R = 1,2664,435,435,435
BEGIN DESCRIPTION:
UNT023 IN BECR 3.0
END DESCRIPTION:
XS GIS Cut Line= 3
      3824475.95     10488937.79      3824972.45     10489038.48
      3825267.62     10489378.79
#Sta/Elev= 30
  4608.1  330.56  4692.0  331.89  4734.3  331.28  4829.3  324.94  4849.1  322.82
  4856.7  321.12  4866.9  320.94  4945.3  313.15  4989.4  311.66  4998.1  310.47
  5000.9  309.97  5004.1  310.47  5030.2  312.10  5071.0  312.95  5110.7  317.33
  5163.5  318.80  5198.7  322.46  5234.8  322.72  5241.4  324.11  5249.0  323.18
  5333.5  326.49  5355.3  326.59  5404.8  328.57  5425.6  331.18  5468.4  332.36
  5475.0  333.27  5496.9  333.14  5503.5  334.10  5546.3  335.88  5565.2  335.89
#Mann=4,-1,0
  4608.1    0.05       0  4829.3    0.16       0  4998.1    0.07       0
  5004.1    0.16       0
Bank Sta=4998.1,5004.1
Exp/Cntr=0.3,0.1

Type RM Length L Ch R = 1,2229,426,426,426
BEGIN DESCRIPTION:
UNT023 IN BECR 2.0
END DESCRIPTION:
XS GIS Cut Line= 2
      3824427.32     10489340.56      3825196.43     10489368.28
#Sta/Elev= 30
  4678.5  326.72  4700.8  328.21  4740.8  327.12  4790.9  323.07  4800.9  323.32
  4811.4  321.09  4850.9  318.37  4875.6  315.76  4890.9  314.05  4910.9  310.59
  4920.9  307.55  4961.0  306.01  4971.0  306.45  4991.0  304.78  5008.0  304.35
  5010.7  303.85  5014.0  304.35  5031.0  305.64  5051.0  309.85  5061.0  310.64
  5071.0  312.34  5091.1  312.61  5101.1  314.03  5121.1  315.07  5181.1  317.18
  5191.1  316.88  5201.1  317.81  5221.1  318.29  5441.3  331.20  5448.1  332.00
#Mann=4,-1,0
  4678.5    0.05       0  4875.6    0.16       0  5008.0    0.07       0
  5014.0    0.16       0
Bank Sta=5008,5014
Exp/Cntr=0.3,0.1

Type RM Length L Ch R = 1,1803,471,471,471
BEGIN DESCRIPTION:
Mapping XS 049953b4
END DESCRIPTION:
XS GIS Cut Line= 3
      3824441.21     10489382.24      3824545.37     10489628.76
      3825170.36     10489788.48
#Sta/Elev= 30
  4404.8  326.06  4424.3  323.37  4439.9  322.81  4463.6  320.34  4628.8  314.65
  4695.3  314.38  4700.5  313.76  4736.2  315.23  4811.0  314.62  4863.9  312.24
  4893.5  305.90  4904.7  305.09  4914.2  303.20  4924.5  299.93  4934.8  299.35
  4945.5  300.72  4955.5  300.79  4976.0  299.96  4981.2  300.78  5004.1  298.59
  5006.8  298.09  5010.1  298.59  5016.9  300.87  5022.0  299.53  5027.7  304.37
  5079.3  311.85  5151.6  316.42  5268.7  319.98  5271.1  319.98  5317.5  321.08
#Mann=6,-1,0
  4404.8    0.05       0  4628.8    0.16       0  5004.1    0.07       0
  5010.1    0.16       0  5268.7    0.12       0  5271.1    0.16       0
Bank Sta=5004.1,5010.1
Exp/Cntr=0.3,0.1

Type RM Length L Ch R = 1,1332,951,951,951
BEGIN DESCRIPTION:
Mapping XS a56b9d62
END DESCRIPTION:
XS GIS Cut Line= 2
      3824403.00     10489451.65      3824714.65     10490345.05
#Sta/Elev= 30
  4458.9  318.94  4494.3  318.11  4582.2  313.92  4587.5  314.56  4605.6  313.33
  4700.9  310.32  4711.7  310.86  4742.2  309.14  4763.3  307.86  4881.0  306.57
  4923.9  302.89  4933.9  300.87  4955.1  298.31  4975.5  294.41  4980.8  294.84
  5003.5  293.82  5006.3  293.32  5009.5  293.82  5018.7  295.80  5037.6  296.42
  5050.4  299.20  5061.0  299.97  5082.2  303.61  5105.0  305.21  5209.3  303.04
  5224.0  303.49  5262.3  301.68  5336.4  301.13  5368.2  299.54  5405.1  299.49
#Mann=4,-1,0
  4458.9    0.05       0  4742.2    0.16       0  5003.5    0.07       0
  5009.5    0.16       0
Bank Sta=5003.5,5009.5
Exp/Cntr=0.3,0.1

Type RM Length L Ch R = 1,381,0,0,0
BEGIN DESCRIPTION:
UNT023 IN BECR 1.0
END DESCRIPTION:
XS GIS Cut Line= 4
      3824239.83     10489569.71      3823864.82     10490041.95
      3824010.65     10490357.92      3824653.02     10490462.09
#Sta/Elev= 30
  4246.1  312.06  4289.0  310.59  4310.6  308.19  4388.4  304.46  4438.3  300.25
  4502.1  297.47  4603.1  294.65  4737.6  292.48  4942.5  290.76  4976.4  286.13
  4979.1  285.63  4982.4  286.13  4988.3  286.21  5001.6  288.26  5011.3  286.30
  5016.8  288.70  5045.4  289.11  5062.7  288.35  5122.5  292.35  5188.6  293.38
  5343.0  292.51  5358.2  291.89  5464.3  292.46  5555.3  292.44  5652.0  294.54
  5702.6  292.01  5745.3  292.29  5783.7  294.96  5840.6  295.25  5847.9  295.30
#Mann=7,-1,0
  4246.1    0.05       0  4976.4    0.03       0  4982.4    0.05       0
  5001.6    0.12       0  5343.0    0.16       0  5464.3    0.12       0
  5840.6    0.16       0
Bank Sta=4976.4,4982.4
Exp/Cntr=0.3,0.1

Chan Stop Cuts=-1