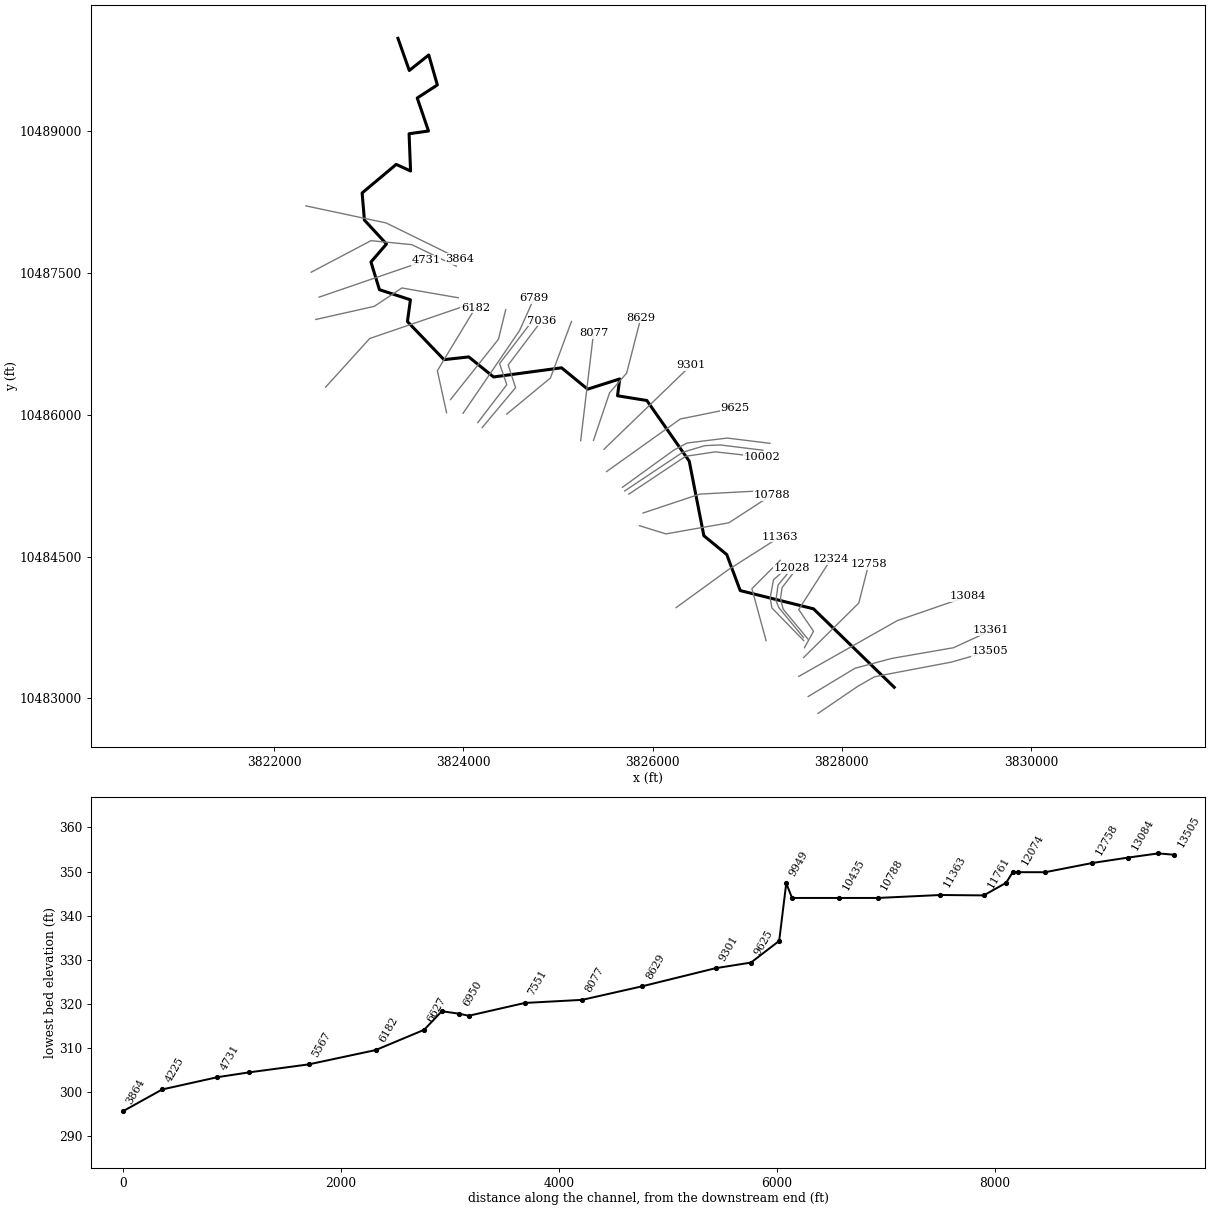
--- UNT024 IN BECR.prj (project) ---

Proj Title=UNT024 IN BECR Base Level Engineering
Current Plan=p01
Default Exp/Contr=0.3,0.1
English Units
Geom File=g01
Flow File=f01
Plan File=p01
Y Axis Title=Elevation
X Axis Title(PF)=Main Channel Distance
X Axis Title(XS)=Station
BEGIN DESCRIPTION:
UNT024 IN BECR
END DESCRIPTION:
DSS Export Rating Curves= 0
DSS Export Rating Curve Sorted= 0
DSS Export Volume Flow Curves= 0
DXF OffsetX= 0
DXF OffsetY= 0
DXF ScaleX= 1
DXF ScaleY= 10

--- UNT024 IN BECR.p01 (plan) ---

Plan Title=Multiple Run
Short Identifier=Multiple
Geom File=g01
Flow File=f01
Subcritical Flow
K Sum by GR= 0
Std Step Tol= 0.01
Critical Tol= 0.01
Num of Std Step Trials= 20
Max Error Tol= 0.3
Flow Tol Ratio= 0.001
Split Flow NTrial= 30
Split Flow Tol= 0.02
Split Flow Ratio= 0.02
Log Output Level= 0
Friction Slope Method= 1
Unsteady Friction Slope Method= 2
Unsteady Bridges Friction Slope Method= 1
Parabolic Critical Depth
Global Vel Dist=  1 , 1 , 1
Global Log Level= 0
CheckData=True
Encroach Param= -1, 0, 0, 0
BEGIN DESCRIPTION:
Multiple Run
END DESCRIPTION:

--- UNT024 IN BECR.f01 (steady flow) ---

Flow Title=Multiple
Number of Profiles=7
Profile Names=10-year,25-year,50-year,1pct_min,100-year,1pct_plu,500-year
River Rch & RM= UNT024 IN BECR,Reach-1,13505
     142     172     194     161     218     295     277
River Rch & RM= UNT024 IN BECR,Reach-1,13361
     428     559     664     579     783    1059    1094
River Rch & RM= UNT024 IN BECR,Reach-1,7036
     449     588     700     612     828    1119    1161
River Rch & RM= UNT024 IN BECR,Reach-1,5567
     586     781     940     830    1123    1518    1608
Boundary for River Rch & Prof#=UNT024 IN BECR,Reach-1,1
Up Type=0
Dn Type=3
Dn Slope=0.005
Boundary for River Rch & Prof#=UNT024 IN BECR,Reach-1,2
Up Type=0
Dn Type=3
Dn Slope=0.005
Boundary for River Rch & Prof#=UNT024 IN BECR,Reach-1,3
Up Type=0
Dn Type=3
Dn Slope=0.005
Boundary for River Rch & Prof#=UNT024 IN BECR,Reach-1,4
Up Type=0
Dn Type=3
Dn Slope=0.005
Boundary for River Rch & Prof#=UNT024 IN BECR,Reach-1,5
Up Type=0
Dn Type=3
Dn Slope=0.005
Boundary for River Rch & Prof#=UNT024 IN BECR,Reach-1,6
Up Type=0
Dn Type=3
Dn Slope=0.005
Boundary for River Rch & Prof#=UNT024 IN BECR,Reach-1,7
Up Type=0
Dn Type=3
Dn Slope=0.005

--- UNT024 IN BECR.g01 (geometry) ---

Geom Title=Existing Conditions
Program Version=4.10

River Reach=UNT024 IN BECR  ,Reach-1
Reach XY= 30
      3828553.51     10483117.35       3827700.5       10483947.
      3826926.25       10484140.        3826784.       10484521.
        3826542.       10484720.       3826387.5       10485509.
       3825939.5       10486150.      3825629.75       10486200.
      3825652.75       10486378.      3825313.75       10486270.
      3825038.25       10486496.      3824319.75       10486399.
      3824057.75       10486611.        3823796.       10486582.
       3823409.5       10486985.      3823441.25       10487215.
      3823113.75       10487322.      3823024.25       10487615.
      3823188.25       10487805.        3822955.       10488058.
        3822931.       10488345.      3823291.25       10488647.
      3823442.75       10488577.        3823427.       10488971.
      3823632.25       10489000.      3823513.25       10489349.
      3823725.75       10489487.        3823635.       10489804.
      3823429.25       10489640.       3823309.5       10489980.

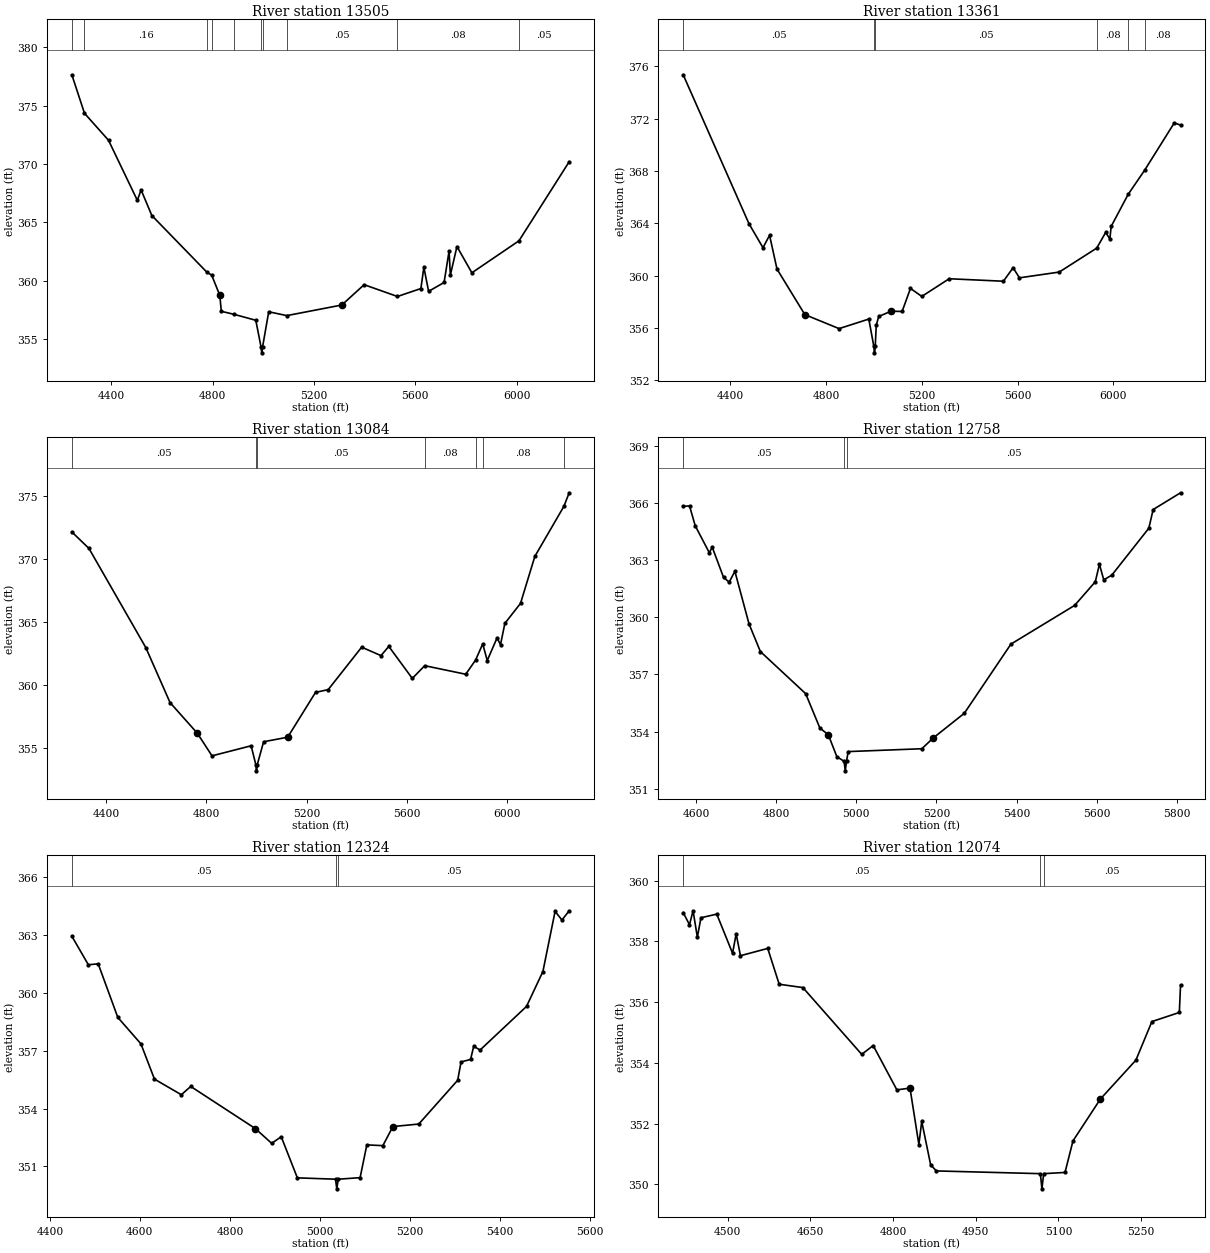
Type RM Length L Ch R = 1 ,13505   ,144,144,144
BEGIN DESCRIPTION:
UNT024 IN BECR 25.0
END DESCRIPTION:
XS GIS Cut Line= 6
      3827748.61     10482841.33      3828169.62     10483127.79
      3828343.23     10483227.61      3828495.14     10483257.99
       3829159.2     10483383.86      3829565.87     10483500.67
#Sta/Elev= 30
    4244  377.64  4293.9  374.34  4388.7  372.03  4502.5  366.88  4517.4  367.77
  4559.7  365.58  4777.6  360.71  4796.1  360.47  4828.2  358.73    4834  357.37
  4884.3  357.11  4970.2   356.6  4990.9  354.31  4993.7  353.81  4996.9  354.31
  5021.2  357.33  5092.7     357  5309.8  357.91  5397.9  359.65  5529.4  358.64
  5621.9  359.32  5633.7  361.14  5652.4  359.08  5713.5  359.84  5733.2  362.53
  5738.3  360.48  5764.3  362.92  5823.2  360.67  6009.1  363.41  6207.4  370.19
#Mann= 10 ,-1 , 0
    4244     .08       0  4293.9     .16       0  4777.6     .12       0
  4796.1     .08       0  4884.3     .12       0  4990.9     .07       0
  4996.9     .12       0  5092.7     .05       0  5529.4     .08       0
  6009.1     .05       0
Bank Sta=4828.2,5309.8
XS Rating Curve= 0 ,0
Exp/Cntr=0.3,0.1

Type RM Length L Ch R = 1 ,13361   ,277,277,277
BEGIN DESCRIPTION:
UNT024 IN BECR 24.0
END DESCRIPTION:
XS GIS Cut Line= 5
      3827644.43     10483019.27      3828139.24     10483318.76
      3828529.86     10483422.92       3829180.9     10483535.77
      3829575.23     10483717.77
#Sta/Elev= 30
  4203.4  375.35  4478.3  363.97  4536.7  362.14  4564.2  363.09  4595.2  360.51
  4711.6  357.03  4854.6  355.96  4978.8  356.69  4999.7  354.61  5002.5  354.11
  5005.7  354.61  5009.9  356.21  5020.2  356.89  5071.9  357.29  5117.9  357.27
  5152.8  359.03  5200.2  358.42  5314.5  359.77    5541  359.58  5581.6  360.61
  5608.1  359.84  5774.4  360.28    5931  362.11  5968.4  363.31  5985.8  362.81
  5991.3  363.77  6062.7  366.23  6131.5  368.07  6254.7  371.67  6281.1  371.51
#Mann= 6 ,-1 , 0
  4203.4     .05       0  4999.7     .03       0  5005.7     .05       0
    5931     .08       0  6062.7     .05       0  6131.5     .08       0
Bank Sta=4711.6,5071.9
XS Rating Curve= 0 ,0
Exp/Cntr=0.3,0.1

Type RM Length L Ch R = 1 ,13084   ,326,326,326
BEGIN DESCRIPTION:
Mapping XS 83b802f7
END DESCRIPTION:
XS GIS Cut Line= 3
      3827544.59     10483231.94      3828586.29     10483822.23
      3829328.44     10484078.29
#Sta/Elev= 30
  4263.8  372.13    4332  370.82  4558.5  362.95  4655.2  358.58  4763.8  356.15
  4822.5  354.35  4978.4  355.15    4997  353.66  4999.8  353.16    5003  353.66
  5028.2  355.47  5124.1  355.83  5235.1  359.39  5285.7  359.61    5419  362.98
    5496  362.31  5527.2  363.04  5620.8   360.5  5670.3  361.51  5833.8  360.83
  5873.2  361.96  5901.6  363.24  5919.5  361.92  5958.6  363.71  5972.4  363.18
  5989.8  364.87  6052.2  366.46  6109.3  370.19    6225  374.16  6246.2  375.24
#Mann= 7 ,-1 , 0
  4263.8     .05       0    4997     .03       0    5003     .05       0
  5670.3     .08       0  5873.2     .05       0  5901.6     .08       0
    6225     .05       0
Bank Sta=4763.8,5124.1
XS Rating Curve= 0 ,0
Exp/Cntr=0.3,0.1

Type RM Length L Ch R = 1 ,12758   ,434,434,434
BEGIN DESCRIPTION:
UNT024 IN BECR 23.0
END DESCRIPTION:
XS GIS Cut Line= 3
      3827595.83      10483431.6      3828179.17     10484007.99
      3828283.01     10484416.43
#Sta/Elev= 30
  4567.9  365.82  4583.7  365.84  4597.9   364.8  4633.2  363.38  4640.3  363.68
  4668.6  362.09  4682.7  361.84  4696.9  362.41  4732.2  359.65  4760.5   358.2
  4873.6  355.99    4909  354.19  4930.2  353.83  4951.5  352.68  4969.6  352.44
  4972.4  351.94  4975.6  352.44  4979.7  352.95  5163.6   353.1  5191.8  353.66
  5269.6  354.96    5386  358.59    5545  360.62  5596.6  361.86  5606.9  362.78
  5617.7  361.96  5637.9  362.21  5730.2  364.67    5741  365.65  5809.4  366.53
#Mann= 3 ,-1 , 0
  4567.9     .05       0  4969.6     .03       0  4975.6     .05       0
Bank Sta=4930.2,5191.8
XS Rating Curve= 0 ,0
Exp/Cntr=0.3,0.1

Type RM Length L Ch R = 1 ,12324   ,250,250,250
BEGIN DESCRIPTION:
UNT024 IN BECR 22.0
END DESCRIPTION:
XS GIS Cut Line= 4
      3827605.38     10483535.77      3827700.87     10483709.38
      3827544.62     10483939.42      3827883.15     10484468.92
#Sta/Elev= 30
  4448.9  362.94  4485.6  361.46  4507.4  361.51    4551  358.73  4602.3  357.36
  4632.4  355.53  4692.1  354.72    4713  355.15  4856.8  352.96  4892.7   352.2
    4914  352.54  4949.8  350.41  5034.6  350.34  5037.4  349.84  5040.6  350.34
  5089.2  350.42  5104.1  352.12  5139.7  352.08    5162  353.07  5219.5   353.2
  5305.9  355.47  5313.4  356.42  5334.5  356.55  5341.5  357.23  5355.7  357.04
  5458.8   359.3  5495.2  361.11  5522.3  364.23  5537.5  363.78  5553.6  364.26
#Mann= 3 ,-1 , 0
  4448.9     .05       0  5034.6     .03       0  5040.6     .05       0
Bank Sta=4856.8,5162
XS Rating Curve= 0 ,0
Exp/Cntr=0.3,0.1

Type RM Length L Ch R = 1 ,12074   ,46,46,46
BEGIN DESCRIPTION:
Mapping XS 4606621c
END DESCRIPTION:
XS GIS Cut Line= 5
       3827642.3     10483626.89      3827379.69     10483943.76
      3827351.48     10484054.44      3827368.84     10484171.62
      3827526.26     10484376.49
#Sta/Elev= 30
    4419  358.95  4430.4  358.55  4436.9  359.01  4444.7  358.14  4451.2  358.78
  4479.9   358.9  4508.6  357.61  4515.1  358.25  4522.9  357.53  4572.4  357.77
  4593.2  356.59  4636.2  356.48    4743  354.28  4763.8  354.57  4806.8  353.11
  4830.6  353.17  4846.7  351.31  4851.9  352.07  4868.1  350.64  4878.5  350.44
  5067.2  350.35    5070  349.85  5073.2  350.35  5111.9  350.39  5126.4  351.43
  5176.2  352.81  5240.6  354.09  5269.6  355.36  5319.4  355.66  5321.6  356.56
#Mann= 3 ,-1 , 0
    4419     .05       0  5067.2     .03       0  5073.2     .05       0
Bank Sta=4830.6,5176.2
XS Rating Curve= 0 ,0
Exp/Cntr=0.3,0.1

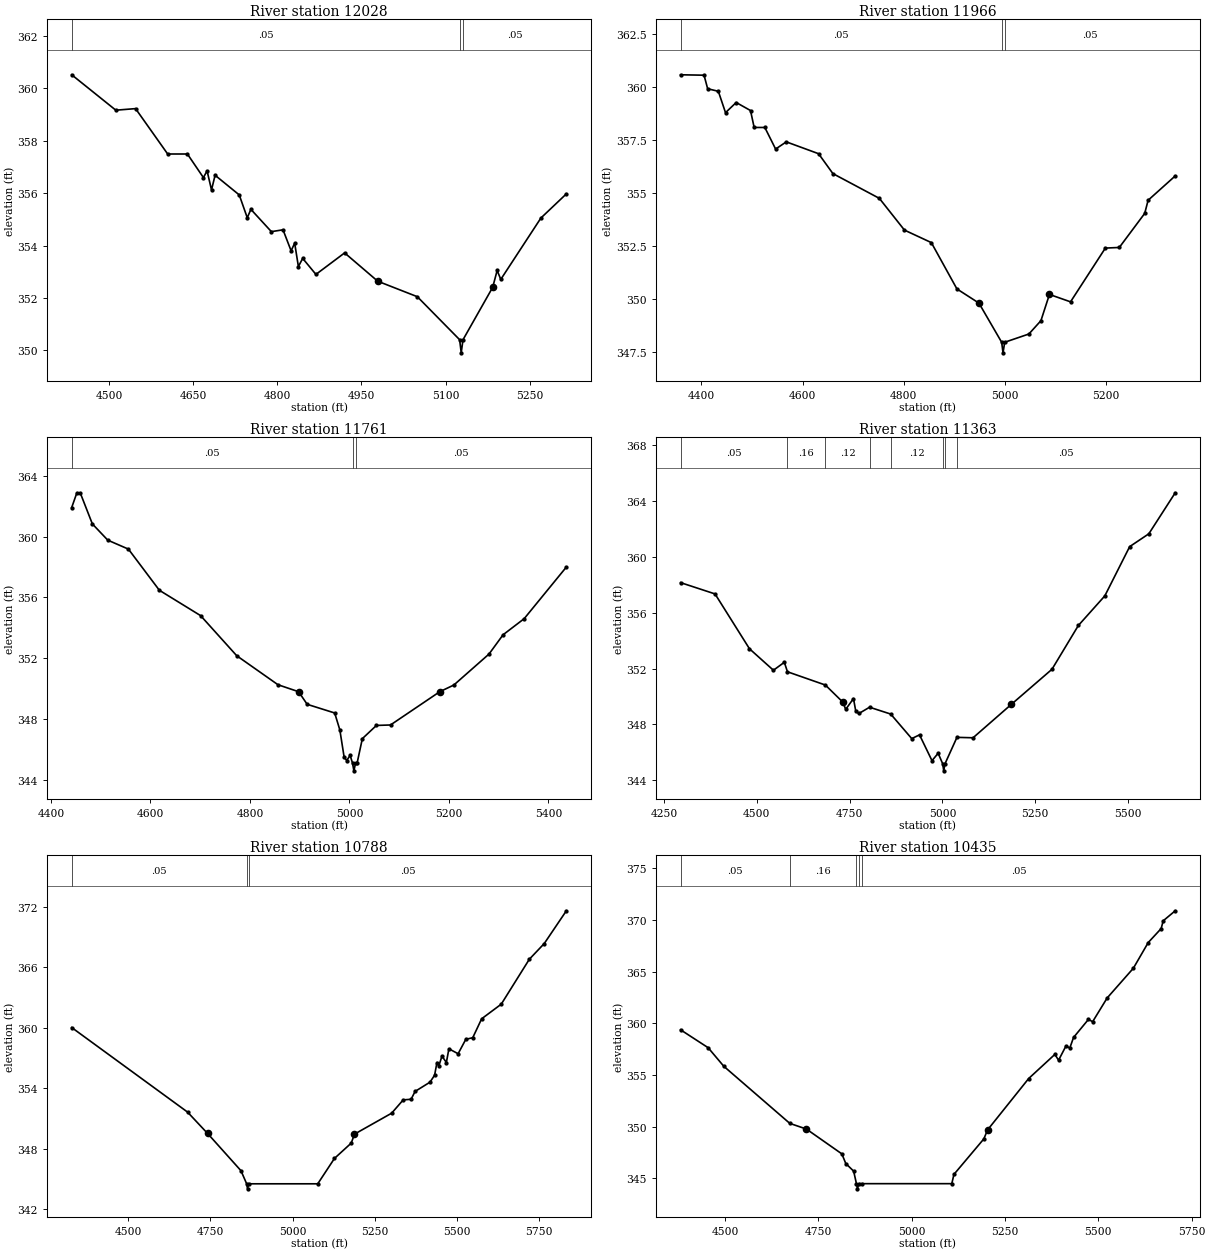
Type RM Length L Ch R = 1 ,12028   ,62,62,62
BEGIN DESCRIPTION:
Mapping XS 33fbd94f
END DESCRIPTION:
XS GIS Cut Line= 5
      3827594.54     10483644.27      3827336.29     10483956.78
      3827303.73     10484032.73      3827325.43     10484197.66
      3827470.82     10484373.43
#Sta/Elev= 30
    4433  360.51  4511.7  359.16  4546.9  359.22  4604.2  357.49  4639.4  357.49
    4668  356.59  4674.5  356.85  4682.4  356.12  4688.8  356.68  4731.9  355.93
  4746.2  355.06  4752.7  355.38  4789.2  354.53    4810   354.6  4824.4   353.8
  4830.8  354.09  4837.4   353.2  4845.1  353.51  4868.7   352.9  4919.9  353.72
    4979  352.64  5049.6  352.05  5125.1  350.41  5127.9  349.91  5131.1  350.41
  5184.1  352.41    5192  353.05  5198.5  352.71  5270.1  355.05  5315.5  355.97
#Mann= 3 ,-1 , 0
    4433     .05       0  5125.1     .03       0  5131.1     .05       0
Bank Sta=4979,5184.1
XS Rating Curve= 0 ,0
Exp/Cntr=0.3,0.1

Type RM Length L Ch R = 1 ,11966   ,205,205,205
BEGIN DESCRIPTION:
Mapping XS bd0488da
END DESCRIPTION:
XS GIS Cut Line= 5
       3827596.7     10483611.73      3827260.33     10483956.78
      3827242.97     10484063.12      3827277.69     10484254.09
      3827423.12     10484382.15
#Sta/Elev= 30
    4359  360.58  4405.4  360.56  4412.5  359.92  4433.6   359.8  4447.8  358.79
  4468.9  359.27  4497.2  358.89  4504.4  358.09  4525.5  358.09  4546.8  357.07
  4567.9  357.41  4631.7  356.85    4660  355.91  4751.8  354.74  4801.4  353.24
  4854.5  352.65  4905.1  350.46  4948.6  349.79  4993.5  347.94  4996.2  347.44
  4999.5  347.94  5047.3  348.33  5071.1  348.96  5087.9   350.2  5129.6  349.85
  5198.4  352.39    5226  352.42  5276.2  354.03  5282.9  354.65  5336.5   355.8
#Mann= 3 ,-1 , 0
    4359     .05       0  4993.5     .03       0  4999.5     .05       0
Bank Sta=4948.6,5087.9
XS Rating Curve= 0 ,0
Exp/Cntr=0.3,0.1

Type RM Length L Ch R = 1 ,11761   ,398,398,398
BEGIN DESCRIPTION:
UNT024 IN BECR 21.0
END DESCRIPTION:
XS GIS Cut Line= 3
      3827199.61      10483610.2      3827049.61     10484160.19
      3827349.58     10484460.16
#Sta/Elev= 30
  4441.7  361.92  4452.1  362.89    4459  362.87  4483.2  360.84  4514.2  359.77
  4555.7  359.18  4617.9  356.47  4700.8   354.8  4773.4  352.16  4856.3  350.25
  4897.8  349.79    4915  348.96  4970.3  348.39  4980.7  347.27  4989.3  345.48
  4994.5  345.26  5001.4   345.6  5006.2  345.08  5008.9  344.58  5012.2  345.08
  5015.3  345.08  5025.9   346.7  5054.2  347.57  5082.5   347.6  5181.5  349.79
  5209.8  350.23  5280.5  352.27  5308.8  353.54  5351.2   354.6    5436     358
#Mann= 3 ,-1 , 0
  4441.7     .05       0  5006.2     .03       0  5012.2     .05       0
Bank Sta=4897.8,5181.5
XS Rating Curve= 0 ,0
Exp/Cntr=0.3,0.1

Type RM Length L Ch R = 1 ,11363   ,575,575,575
BEGIN DESCRIPTION:
UNT024 IN BECR 20.0
END DESCRIPTION:
XS GIS Cut Line= 3
      3826249.59     10483960.18      3826799.61     10484360.19
       3827349.6     10484710.18
#Sta/Elev= 30
  4294.9  358.16  4387.7  357.35  4480.4  353.42  4544.9  351.88  4574.3  352.45
  4582.7  351.77  4684.8  350.82  4731.2  349.61  4739.7  349.08  4760.5  349.85
  4766.7  348.94  4775.2  348.78  4803.8  349.23  4860.7  348.74  4917.4  346.98
  4938.3  347.25  4971.9   345.4  4988.5  345.93  5000.8  345.17  5003.5  344.67
  5006.8  345.17  5039.1  347.07  5082.5  347.04  5185.8  349.44    5295  351.95
  5366.1  355.09  5437.3  357.21  5504.2  360.74  5555.8  361.66  5626.9   364.6
#Mann= 8 ,-1 , 0
  4294.9     .05       0  4582.7     .16       0  4684.8     .12       0
  4803.8     .16       0  4860.7     .12       0  5000.8     .07       0
  5006.8     .12       0  5039.1     .05       0
Bank Sta=4731.2,5185.8
XS Rating Curve= 0 ,0
Exp/Cntr=0.3,0.1

Type RM Length L Ch R = 1 ,10788   ,353,353,353
BEGIN DESCRIPTION:
UNT024 IN BECR 19.0
END DESCRIPTION:
XS GIS Cut Line= 4
      3825861.47     10484826.05       3826141.4     10484739.25
      3826805.46     10484856.44      3827255.73     10485148.68
#Sta/Elev= 30
  4328.5  360.01  4680.7  351.62  4741.6   349.5  4843.2   345.8  4860.5   344.5
  4863.2     344  4866.5   344.5  5076.7   344.5  5127.5  347.02  5178.5  348.54
  5188.4  349.43  5301.4  351.51  5336.6  352.83  5360.5  352.89  5372.7  353.67
  5418.1  354.59    5432  355.28  5439.2  356.54  5445.2  356.23  5454.4  357.18
  5467.8  356.54  5475.5   357.9  5503.5  357.41  5526.9  358.84    5548     359
  5575.1  360.88  5634.7  362.33  5720.1  366.79  5765.5  368.35  5832.7   371.6
#Mann= 3 ,-1 , 0
  4328.5     .05       0  4860.5    .033       0  4866.5     .05       0
Bank Sta=4741.6,5188.4
XS Rating Curve= 0 ,0
Exp/Cntr=0.3,0.1

Type RM Length L Ch R = 1 ,10435   ,433,433,433
BEGIN DESCRIPTION:
UNT024 IN BECR 18.0
END DESCRIPTION:
XS GIS Cut Line= 3
      3825899.61     10484960.19      3826499.61     10485160.19
      3827191.77     10485197.23
#Sta/Elev= 30
  4380.4  359.38  4454.2  357.65  4496.3  355.85  4673.1  350.33  4717.7  349.78
  4812.6  347.38  4823.1  346.45  4844.2  345.71  4851.7   344.5  4854.5     344
  4857.7   344.5  4867.1   344.5  5107.2   344.5    5113   345.4  5193.1  348.83
  5203.1   349.7  5313.3  354.67  5383.4     357  5393.4  356.44  5413.4  357.83
  5423.4  357.61  5433.5  358.64  5473.5  360.39  5484.6  360.16  5523.6  362.46
  5593.7  365.33  5633.7  367.82  5668.3  369.17  5673.8  369.92    5706  370.89
#Mann= 5 ,-1 , 0
  4380.4     .05       0  4673.1     .16       0  4851.7    .033       0
  4857.7     .16       0  4867.1     .05       0
Bank Sta=4717.7,5203.1
XS Rating Curve= 0 ,0
Exp/Cntr=0.3,0.1

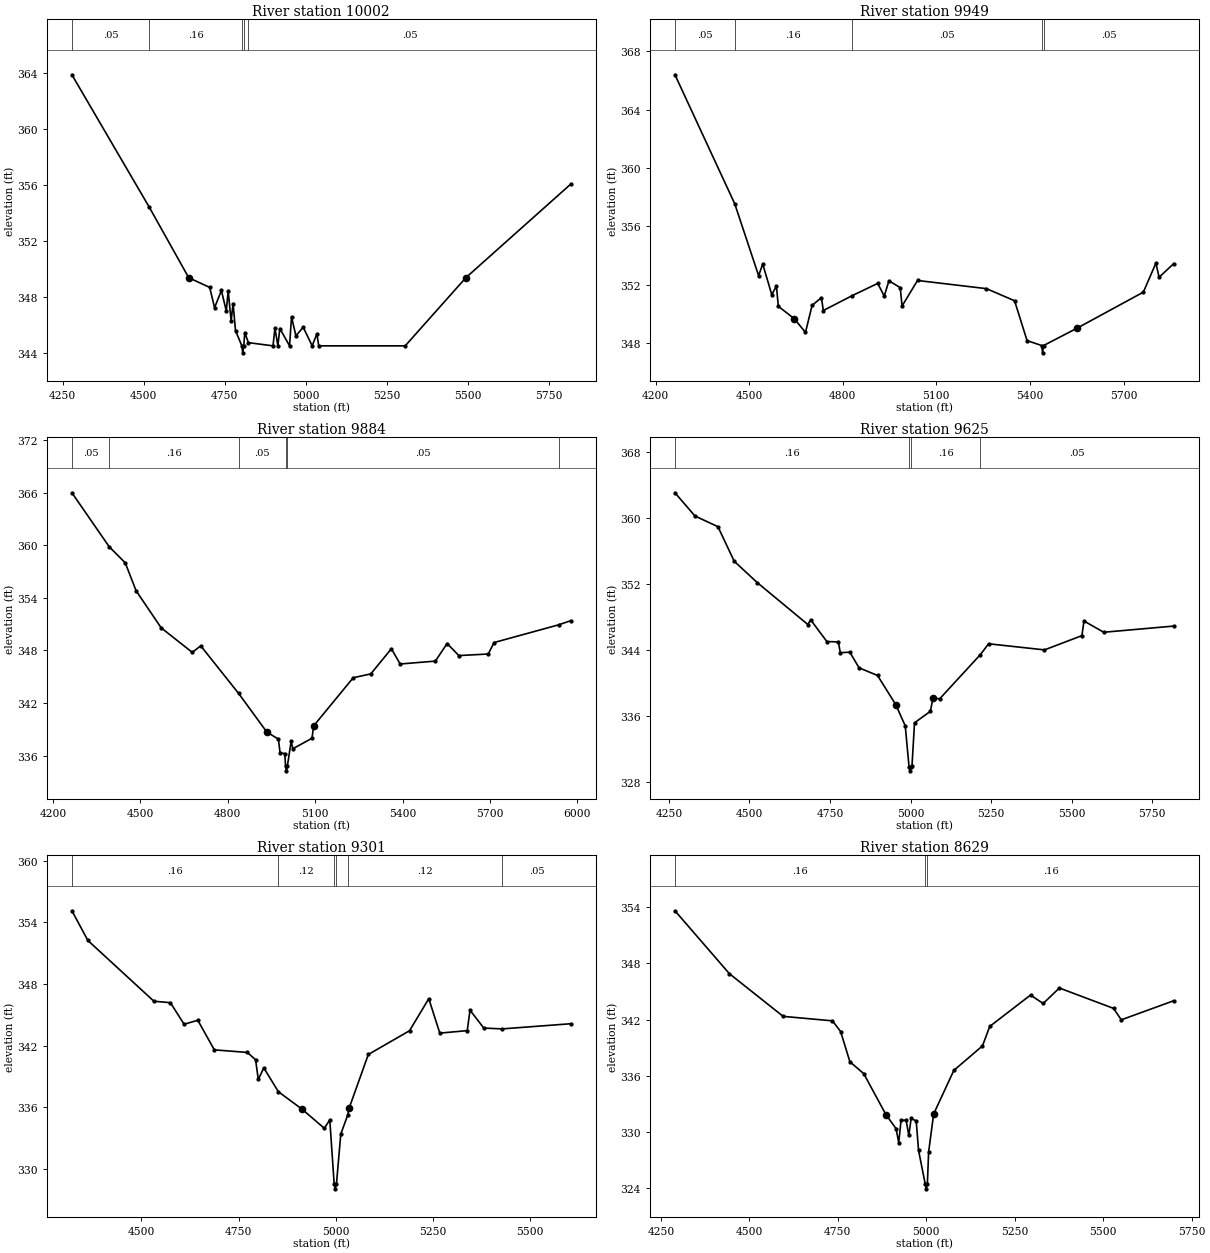
Type RM Length L Ch R = 1 ,10002   ,53,53,53
BEGIN DESCRIPTION:
UNT024 IN BECR 17.0
END DESCRIPTION:
XS GIS Cut Line= 4
      3825749.64     10485160.21      3826349.61     10485560.19
      3826663.98     10485606.95      3827160.48      10485551.4
#Sta/Elev= 30
  4278.2  363.89  4517.3   354.4  4638.7  349.37  4703.3  348.68  4718.3  347.23
  4739.4  348.46  4754.4     347  4760.4  348.41  4769.4  346.29  4775.4  347.52
  4782.9  345.59  4802.5   344.5  4805.2     344  4808.5   344.5  4811.5  345.45
  4822.7  344.73  4898.6   344.5  4904.6  345.77  4913.6   344.5  4919.7  345.74
  4949.7   344.5  4955.7  346.58  4969.2  345.22  4991.8  345.83  5019.5   344.5
    5034  345.36  5039.7   344.5  5306.4   344.5  5493.8  349.38  5816.7  356.06
#Mann= 5 ,-1 , 0
  4278.2     .05       0  4517.3     .16       0  4802.5     .03       0
  4808.5     .16       0  4822.7     .05       0
Bank Sta=4638.7,5493.8
XS Rating Curve= 0 ,0
Exp/Cntr=0.3,0.1

Type RM Length L Ch R = 1 ,9949    ,65,65,65
BEGIN DESCRIPTION:
Mapping XS 6a37aac6
END DESCRIPTION:
XS GIS Cut Line= 5
      3825705.61     10485193.74      3826319.38       10485603.
      3826552.86     10485672.92      3826716.06     10485679.87
      3827165.99     10485624.49
#Sta/Elev= 30
  4262.3  366.39    4454  357.54  4530.4  352.62  4543.5  353.42  4572.5  351.32
  4587.5   351.9  4593.5  350.52  4644.6  349.67  4680.6  348.73  4701.7  350.58
  4731.7  351.12  4737.7  350.23  4829.3  351.24    4912  352.09    4933  351.22
    4948  352.27  4984.1   351.8  4990.1  350.54  5039.6  352.29  5260.5  351.73
  5350.6   350.9  5390.6  348.17  5437.6  347.83  5440.4  347.33  5443.6  347.83
  5551.7  349.03  5763.3  351.49  5803.6  353.48  5813.7  352.51  5860.4  353.44
#Mann= 5 ,-1 , 0
  4262.3     .05       0    4454     .16       0  4829.3     .05       0
  5437.6     .03       0  5443.6     .05       0
Bank Sta=4644.6,5551.7
XS Rating Curve= 0 ,0
Exp/Cntr=0.3,0.1

Type RM Length L Ch R = 1 ,9884    ,259,259,259
BEGIN DESCRIPTION:
Mapping XS 17b83e23
END DESCRIPTION:
XS GIS Cut Line= 5
      3825681.31     10485231.93        3826223.     10485624.31
      3826365.37      10485700.7      3826788.98     10485752.79
      3827240.33     10485697.23
#Sta/Elev= 30
    4265     366    4393  359.84  4448.1     358  4485.2  354.82  4571.4  350.58
  4678.1  347.78  4707.4  348.52  4837.3  343.09  4933.9  338.69  4973.9  337.87
  4979.6   336.3  4995.8  336.22  4998.5  334.75  5001.2  334.25  5004.5  334.75
  5017.7  337.64  5023.4  336.77  5089.2  337.97    5095  339.39  5230.7  344.88
  5291.1  345.32  5361.7  348.19  5391.9  346.45  5512.8  346.78  5553.1  348.79
  5593.4  347.41  5694.2  347.59  5714.3   348.9  5935.7  350.92    5977  351.39
#Mann= 6 ,-1 , 0
    4265     .05       0    4393     .16       0  4837.3     .05       0
  4998.5     .03       0  5004.5     .05       0  5935.7     .08       0
Bank Sta=4933.9,5095
XS Rating Curve= 0 ,0
Exp/Cntr=0.3,0.1

Type RM Length L Ch R = 1 ,9625    ,324,324,324
BEGIN DESCRIPTION:
UNT024 IN BECR 16.0
END DESCRIPTION:
XS GIS Cut Line= 3
      3825514.67     10485398.62      3826292.45     10485954.17
      3826872.34     10486072.24
#Sta/Elev= 30
  4268.7   363.1  4330.8  360.28  4402.1  358.98  4452.5  354.79  4523.8   352.2
  4681.1   347.1  4689.7  347.68  4740.1  345.03  4775.7  344.99  4781.8  343.68
  4811.3  343.74  4840.1  341.84  4897.4  340.91  4953.9  337.37  4983.4  334.79
  4995.1  329.83  4997.9  329.33  5001.1  329.83  5004.3  329.91  5012.1  335.16
  5061.3  336.56  5069.4  338.16  5090.3  338.08  5216.6  343.45    5242  344.76
  5415.5  344.02  5531.6  345.75    5538  347.53  5599.2  346.16  5816.3  346.91
#Mann= 4 ,-1 , 0
  4268.7     .16       0  4995.1     .07       0  5001.1     .16       0
  5216.6     .05       0
Bank Sta=4953.9,5069.4
XS Rating Curve= 0 ,0
Exp/Cntr=0.3,0.1

Type RM Length L Ch R = 1 ,9301    ,672,672,672
BEGIN DESCRIPTION:
UNT024 IN BECR 15.0
END DESCRIPTION:
XS GIS Cut Line= 2
      3825486.92     10485634.76      3826409.55     10486526.17
#Sta/Elev= 30
  4321.4  355.11  4362.5  352.22  4532.3  346.31  4574.8  346.17    4610  344.07
  4645.3  344.46  4687.7  341.58  4772.6  341.33  4793.9  340.62  4800.9   338.7
    4815  339.83  4852.5  337.51  4914.1  335.79  4970.7  333.95  4984.8  334.77
    4996  328.56  4998.7  328.06    5002  328.56  5013.1  333.39  5030.6   335.2
  5034.3  335.88  5083.9  341.13  5189.9  343.44  5239.5  346.56  5267.8  343.21
  5338.5  343.45  5345.5  345.44    5381   343.7  5428.3  343.62  5604.3  344.12
#Mann= 6 ,-1 , 0
  4321.4     .16       0  4852.5     .12       0    4996     .07       0
    5002     .12       0  5030.6     .12       0  5428.3     .05       0
Bank Sta=4914.1,5034.3
XS Rating Curve= 0 ,0
Exp/Cntr=0.3,0.1

Type RM Length L Ch R = 1 ,8629    ,552,552,552
BEGIN DESCRIPTION:
UNT024 IN BECR 14.0
END DESCRIPTION:
XS GIS Cut Line= 4
      3825375.77     10485728.44      3825545.92     10486231.95
      3825726.48     10486440.29      3825875.78      10487023.6
#Sta/Elev= 30
  4289.8  353.59  4443.5  346.89  4595.5  342.34    4735  341.86    4758  340.72
  4784.2   337.5  4823.4  336.23    4886  331.87  4914.6  330.38  4922.2  328.89
  4928.8  331.28  4943.1  331.26  4950.7  329.65  4957.3  331.47  4971.6  331.19
  4978.2  328.06  4997.1  324.46  4999.8  323.96  5003.1  324.46  5006.7   327.9
  5020.9  331.94  5077.9  336.58  5158.8  339.19  5179.5  341.27  5294.6  344.61
  5330.3  343.71  5376.2  345.36  5529.2  343.19  5551.1  341.97  5699.1     344
#Mann= 3 ,-1 , 0
  4289.8     .16       0  4997.1     .07       0  5003.1     .16       0
Bank Sta=4886,5020.9
XS Rating Curve= 0 ,0
Exp/Cntr=0.3,0.1

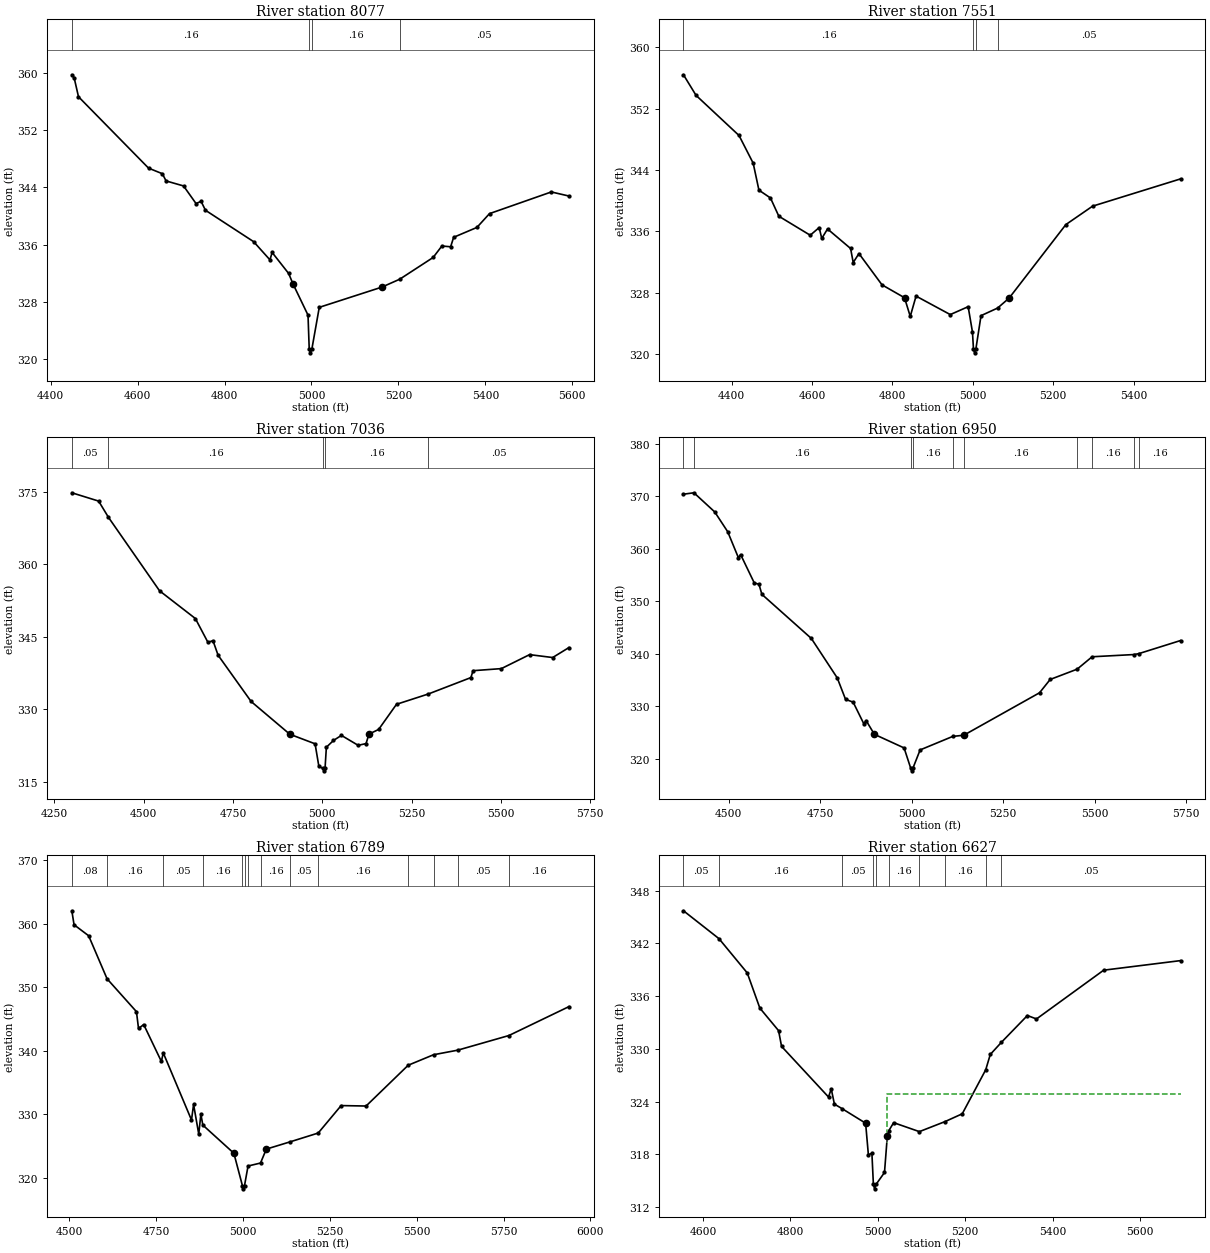
Type RM Length L Ch R = 1 ,8077    ,526,526,526
BEGIN DESCRIPTION:
UNT024 IN BECR 13.0
END DESCRIPTION:
XS GIS Cut Line= 2
      3825240.36     10485724.96      3825375.78     10486860.42
#Sta/Elev= 30
  4448.7  359.74    4454  359.33    4464  356.67  4625.2  346.69  4656.9  345.91
  4665.5   344.9  4705.7   344.2  4734.4  341.74    4746  342.05  4756.1   340.8
  4866.9  336.41  4904.4  333.87  4909.5   334.9  4947.4  331.97  4957.5   330.5
    4992  326.14  4994.8  321.37  4997.5  320.87  5000.8  321.37  5017.9  327.23
    5162  330.06  5202.9  331.16  5279.8   334.2  5299.9   335.8  5320.1   335.7
    5327  337.02  5380.5   338.4  5409.5  340.33  5551.7  343.36  5592.2  342.79
#Mann= 4 ,-1 , 0
  4448.7     .16       0  4994.8     .07       0  5000.8     .16       0
  5202.9     .05       0
Bank Sta=4957.5,5162
XS Rating Curve= 0 ,0
Exp/Cntr=0.3,0.1

Type RM Length L Ch R = 1 ,7551    ,515,515,515
BEGIN DESCRIPTION:
UNT024 IN BECR 12.0
END DESCRIPTION:
XS GIS Cut Line= 3
      3824459.13     10486006.27      3824920.92      10486388.2
      3825143.11     10486985.33
#Sta/Elev= 30
  4280.5  356.44  4311.9  353.75  4418.7  348.52  4453.9  344.91  4468.2  341.39
  4496.9  340.37  4517.7  337.99  4595.8  335.51    4618  336.51  4624.5  335.09
  4638.8  336.33  4696.2  333.78  4702.7  331.95    4717  333.12  4774.3  329.04
  4830.3  327.36  4844.6  324.92    4859  327.57  4944.1  325.16  4988.6  326.19
  4999.3  322.89  5001.8  320.67  5004.6  320.17  5007.8  320.67  5020.6  325.02
  5061.8  326.01  5090.5  327.31  5231.6   336.9    5298   339.3  5516.9  342.86
#Mann= 4 ,-1 , 0
  4280.5     .16       0  5001.8     .07       0  5007.8     .16       0
  5061.8     .05       0
Bank Sta=4830.3,5090.5
XS Rating Curve= 0 ,0
Exp/Cntr=0.3,0.1

Type RM Length L Ch R = 1 ,7036    ,86,86,86
BEGIN DESCRIPTION:
Mapping XS 94f1978e
END DESCRIPTION:
XS GIS Cut Line= 4
      3824199.63      10485863.9      3824552.51     10486285.97
       3824474.1     10486525.82      3824828.85     10486995.76
#Sta/Elev= 30
  4298.8  374.76  4373.8  373.04  4401.4  369.67  4544.3  354.49  4644.5  348.76
  4679.6  343.85  4693.9  344.17  4708.2  341.16  4800.6   331.6  4908.9  324.83
  4979.6  322.85  4990.2  318.19  5001.5  317.76  5004.3  317.26  5007.5  317.76
  5011.2  322.14  5031.1  323.54  5053.3  324.59  5100.1  322.54  5122.2  322.89
  5130.5  324.86  5157.5  325.82  5207.5  331.02  5296.9  333.16  5415.6  336.54
  5421.9  337.97    5501   338.4    5580  341.29  5644.6  340.69  5690.1  342.75
#Mann= 5 ,-1 , 0
  4298.8     .05       0  4401.4     .16       0  5001.5     .07       0
  5007.5     .16       0  5296.9     .05       0
Bank Sta=4908.9,5130.5
XS Rating Curve= 0 ,0
Exp/Cntr=0.3,0.1

Type RM Length L Ch R = 1 ,6950    ,161,161,161
BEGIN DESCRIPTION:
Mapping XS 6c268f72
END DESCRIPTION:
XS GIS Cut Line= 4
      3824153.41     10485916.27      3824459.64     10486317.08
      3824383.09     10486539.99      3824759.09     10487030.82
#Sta/Elev= 30
  4376.4  370.37    4405  370.64  4461.9  366.99  4497.3  363.23  4526.3  358.32
  4532.6  358.88  4569.9  353.48  4582.7  353.23  4590.7  351.31  4725.8  342.92
  4796.6  335.41  4819.3  331.33  4840.1  330.79  4869.2  326.68  4875.5  327.29
  4898.1  324.67  4979.3  322.08  4997.4  318.22  5000.2  317.72  5003.4  318.22
  5023.1   321.7  5112.2  324.27  5142.5   324.5  5349.5  332.58  5378.5  335.11
  5452.2  337.07  5493.1  339.43    5607  339.85  5620.4  340.02  5734.8  342.52
#Mann= 10 ,-1 , 0
  4376.4     .05       0    4405     .16       0  4997.4     .07       0
  5003.4     .16       0  5112.2     .05       0  5142.5     .16       0
  5452.2     .05       0  5493.1     .16       0    5607     .05       0
  5620.4     .16       0
Bank Sta=4898.1,5142.5
XS Rating Curve= 0 ,0
Exp/Cntr=0.3,0.1

Type RM Length L Ch R = 1 ,6789    ,162,162,162
BEGIN DESCRIPTION:
UNT024 IN BECR 11.0
END DESCRIPTION:
XS GIS Cut Line= 3
      3823997.52     10486014.91      3824594.03     10486888.85
       3824746.8     10487229.12
#Sta/Elev= 30
  4507.2  362.04  4513.6  359.84  4555.6  358.11  4608.6  351.34  4693.2  346.17
  4699.2  343.52  4714.1  344.14  4764.9  338.34  4770.5  339.67  4851.7  329.12
  4857.7  331.57  4872.6  326.89  4878.7  330.05  4884.3  328.32  4973.7  323.89
  4998.3  318.79  5001.1  318.29  5004.3  318.79  5014.5  321.88  5050.4  322.35
  5067.1  324.54  5136.5   325.7  5216.5  327.07  5282.5  331.39  5354.3  331.32
  5475.6  337.74  5548.6  339.39  5618.3  340.11  5765.4  342.41  5938.3  346.96
#Mann= 14 ,-1 , 0
  4507.2     .08       0  4608.6     .16       0  4770.5     .05       0
  4884.3     .16       0  4998.3     .07       0  5004.3     .16       0
  5014.5     .08       0  5050.4     .16       0  5136.5     .05       0
  5216.5     .16       0  5475.6     .05       0  5548.6     .16       0
  5618.3     .05       0  5765.4     .16       0
Bank Sta=4973.7,5067.1
XS Rating Curve= 0 ,0
Exp/Cntr=0.3,0.1

Type RM Length L Ch R = 1 ,6627    ,445,445,445
BEGIN DESCRIPTION:
UNT024 IN BECR 10.0
END DESCRIPTION:
XS GIS Cut Line= 3
      3823864.88     10486159.72       3824371.8     10486798.58
      3824448.18     10487111.04
#Sta/Elev= 30
  4555.4  345.71  4636.6  342.54  4701.3  338.64  4730.1  334.64    4773  332.07
  4779.8  330.28  4887.2  324.52  4893.5  325.44  4900.7  323.71  4918.1   323.2
  4972.1  321.54  4978.4  317.96  4986.5   318.1  4989.9  314.57  4992.6  314.07
  4995.9  314.57  5015.3  315.93  5021.7  320.04  5024.5  320.63  5036.2   321.6
  5095.1  320.58  5153.7  321.72  5193.2  322.61  5246.9  327.62  5257.3  329.36
  5282.9  330.75  5342.2  333.79    5363   333.4  5516.7  338.95  5692.6  340.04
#Mann= 10 ,-1 , 0
  4555.4     .05       0  4636.6     .16       0  4918.1     .05       0
  4989.9     .04       0  4995.9     .05       0  5024.5     .16       0
  5095.1     .05       0  5153.7     .16       0  5246.9     .08       0
  5282.9     .05       0
#XS Ineff= 2 , 0
                         5020.45          324.87
Permanent Ineff=
       F       F
Bank Sta=4972.1,5021.7
XS Rating Curve= 0 ,0
Exp/Cntr=0.3,0.1

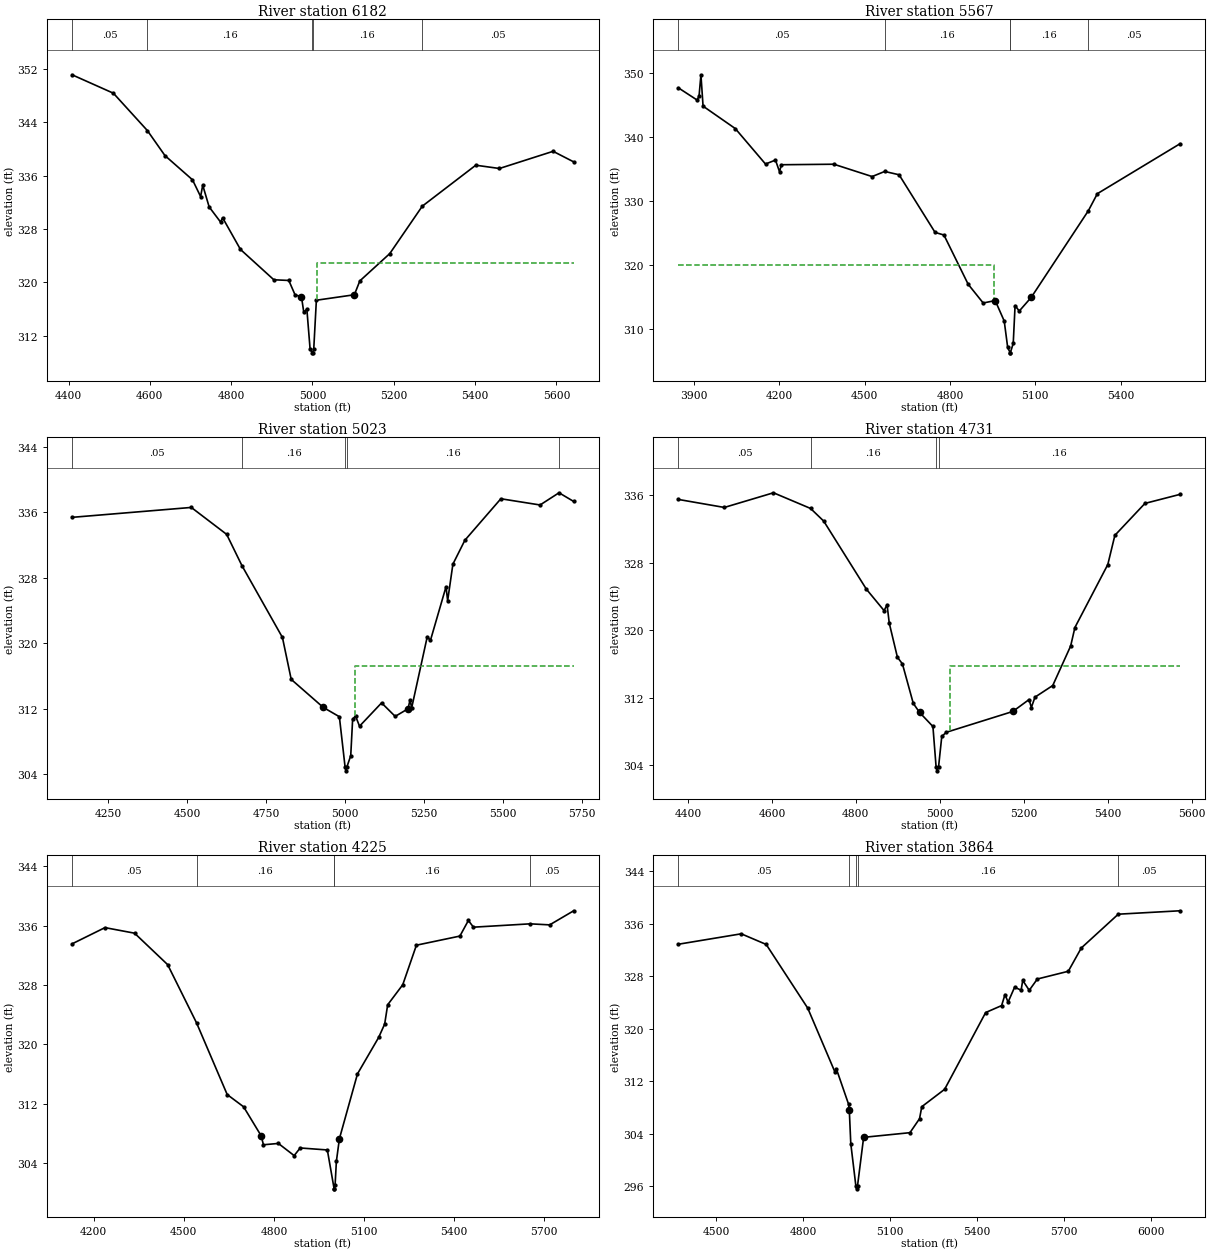
Type RM Length L Ch R = 1 ,6182    ,615,615,615
BEGIN DESCRIPTION:
UNT024 IN BECR 9.0
END DESCRIPTION:
XS GIS Cut Line= 3
      3823823.19     10486020.82      3823725.97     10486465.24
      3824128.74     10487131.89
#Sta/Elev= 30
  4408.7  351.07  4510.4  348.31    4594  342.72  4637.2  338.98  4704.9  335.36
  4724.9  332.85  4730.1  334.55  4745.9   331.3  4773.9  329.04    4779  329.68
  4822.9  324.94    4905   320.4  4941.8   320.3  4957.4  318.12  4972.9  317.89
  4978.7  315.52  4986.2  316.02  4994.2  310.02  4999.8  309.47  5000.3  309.47
  5003.1  309.97  5009.6  317.34  5103.1  318.16  5116.5  320.23  5190.2  324.32
  5270.1  331.41  5401.7  337.54  5459.9  337.05  5591.9  339.62  5642.5  338.04
#Mann= 5 ,-1 , 0
  4408.7     .05       0    4594     .16       0  4999.8     .07       0
  5000.3     .16       0  5270.1     .05       0
#XS Ineff= 2 , 0
                         5010.91          322.98
Permanent Ineff=
       F       F
Bank Sta=4972.9,5103.1
XS Rating Curve= 0 ,0
Exp/Cntr=0.3,0.1

Type RM Length L Ch R = 1 ,5567    ,544,544,544
BEGIN DESCRIPTION:
UNT024 IN BECR 8.0
END DESCRIPTION:
XS GIS Cut Line= 3
       3822545.4     10486291.61      3823010.69     10486805.52
      3824024.54     10487152.73
#Sta/Elev= 30
  3844.1   347.7  3909.6   345.8  3916.9  346.35  3923.6  349.74  3931.1  344.83
  4044.5  341.32  4150.8  335.77  4185.9  336.39  4200.1  334.57  4206.8  335.66
  4391.4  335.74  4525.9  333.81  4570.2  334.61  4620.8  334.09  4747.4  325.07
  4778.6  324.66  4863.9  316.95  4916.7  314.02    4959   314.4  4990.7   311.2
  5002.9  307.06  5011.6  306.22  5012.1  306.22  5022.4  307.69  5028.9  313.62
  5043.6  312.76  5085.9  314.91  5286.7  328.46  5318.4  331.13    5609  338.94
#Mann= 5 ,-1 , 0
  3844.1     .05       0  4570.2     .16       0  5011.6     .07       0
  5012.1     .16       0  5286.7     .05       0
#XS Ineff= 2 , 0
         4955.97  320.03
Permanent Ineff=
       F       F
Bank Sta=4959,5085.9
XS Rating Curve= 0 ,0
Exp/Cntr=0.3,0.1

Type RM Length L Ch R = 1 ,5023    ,292,292,292
BEGIN DESCRIPTION:
UNT024 IN BECR 7.0
END DESCRIPTION:
XS GIS Cut Line= 4
       3822441.2      10487006.9       3823059.3      10487145.8
      3823350.97     10487340.24      3823946.42     10487236.38
#Sta/Elev= 30
  4135.8  335.38  4513.4  336.59  4625.4   333.3  4673.8  329.48    4802  320.71
  4829.8  315.59  4931.2  312.17  4982.3  311.03  5000.3  304.92  5003.1  304.42
  5006.3  304.92  5018.3  306.27  5024.3  310.71  5033.4  311.13  5046.1  309.87
    5116  312.72  5159.1  311.07  5199.7     312  5206.1  313.08  5211.2   312.1
  5260.6   320.8  5270.7  320.35  5320.1  326.91  5325.2  325.19  5341.8  329.66
  5379.7  332.58  5493.7  337.65  5617.9  336.89  5677.9  338.38  5724.3  337.32
#Mann= 5 ,-1 , 0
  4135.8     .05       0  4673.8     .16       0  5000.3     .07       0
  5006.3     .16       0  5677.9     .05       0
#XS Ineff= 2 , 0
                         5031.93          317.27
Permanent Ineff=
       F       F
Bank Sta=4931.2,5199.7
XS Rating Curve= 0 ,0
Exp/Cntr=0.3,0.1

Type RM Length L Ch R = 1 ,4731    ,506,506,506
BEGIN DESCRIPTION:
UNT024 IN BECR 6.0
END DESCRIPTION:
XS GIS Cut Line= 2
      3822475.94     10487243.01      3823606.29     10487631.35
#Sta/Elev= 30
    4377  335.51  4486.6  334.56  4603.7   336.3  4692.1  334.44  4723.4  332.94
    4825  324.87  4867.3  322.32  4874.3  323.03  4879.6  320.83    4899  316.79
  4910.9  316.01  4936.8  311.32  4951.9  310.24  4983.6  308.58  4991.1  303.82
  4993.8  303.32  4997.1  303.82  5004.7   307.4  5015.3  307.89  5173.9  310.36
  5212.8  311.78  5218.1  310.83  5226.8  312.06  5269.1  313.44  5311.8  318.13
  5321.9  320.32  5400.3  327.79  5417.1  331.25  5488.8  335.04  5572.2  336.11
#Mann= 4 ,-1 , 0
    4377     .05       0  4692.1     .16       0  4991.1     .07       0
  4997.1     .16       0
#XS Ineff= 2 , 0
                         5024.89          315.72
Permanent Ineff=
       F       F
Bank Sta=4951.9,5173.9
XS Rating Curve= 0 ,0
Exp/Cntr=0.3,0.1

Type RM Length L Ch R = 1 ,4225    ,361,361,361
BEGIN DESCRIPTION:
UNT024 IN BECR 5.0
END DESCRIPTION:
XS GIS Cut Line= 4
      3822392.68     10487506.93      3823024.58     10487840.24
      3823455.14     10487798.58      3823926.03     10487570.05
#Sta/Elev= 30
  4127.7  333.56  4237.3  335.75  4335.8     335    4446  330.76  4542.5  322.89
  4644.3  313.25  4698.9   311.6  4757.4  307.69    4765  306.48  4814.7  306.66
  4867.3  305.02  4887.4  306.05  4977.8  305.78  5000.4  300.54  5000.9  300.54
  5003.6  301.04  5007.9  304.25    5018   307.3  5078.2  316.04  5148.6  320.94
  5168.7  322.75  5178.7  325.35  5228.9  328.05  5274.4  333.38  5419.2  334.61
  5447.4  336.71  5464.4  335.81    5653  336.26  5718.2  336.12  5798.1  338.02
#Mann= 5 ,-1 , 0
  4127.7     .05       0  4542.5     .16       0  5000.4     .07       0
  5000.9     .16       0    5653     .05       0
Bank Sta=4757.4,5018
XS Rating Curve= 0 ,0
Exp/Cntr=0.3,0.1

Type RM Length L Ch R = 1 ,3864    ,523,523,523
BEGIN DESCRIPTION:
UNT024 IN BECR 4.0
END DESCRIPTION:
XS GIS Cut Line= 3
      3822337.07      10488208.3       3823184.3     10488027.74
      3823962.11     10487645.78
#Sta/Elev= 30
  4368.9  332.87  4586.2  334.46  4672.4  332.84  4815.9  323.13  4909.9  313.39
    4915  313.85  4956.8  308.51  4959.5  307.58  4964.6  302.48    4982  296.09
  4984.7  295.59    4988  296.09    5009  303.44    5169  304.15  5202.1  306.28
  5209.9  308.11  5288.8  310.76  5430.5  322.46  5485.6  323.52  5497.3   325.2
    5508  324.05  5530.5  326.32    5553  325.87  5558.6  327.35  5581.1  325.85
  5609.1  327.57    5716  328.75  5760.9   332.3  5888.6  337.45  6101.7  337.97
#Mann= 5 ,-1 , 0
  4368.9     .05       0  4956.8     .16       0    4982     .07       0
    4988     .16       0  5888.6     .05       0
Bank Sta=4959.5,5009
XS Rating Curve= 0 ,0
Exp/Cntr=0.3,0.1