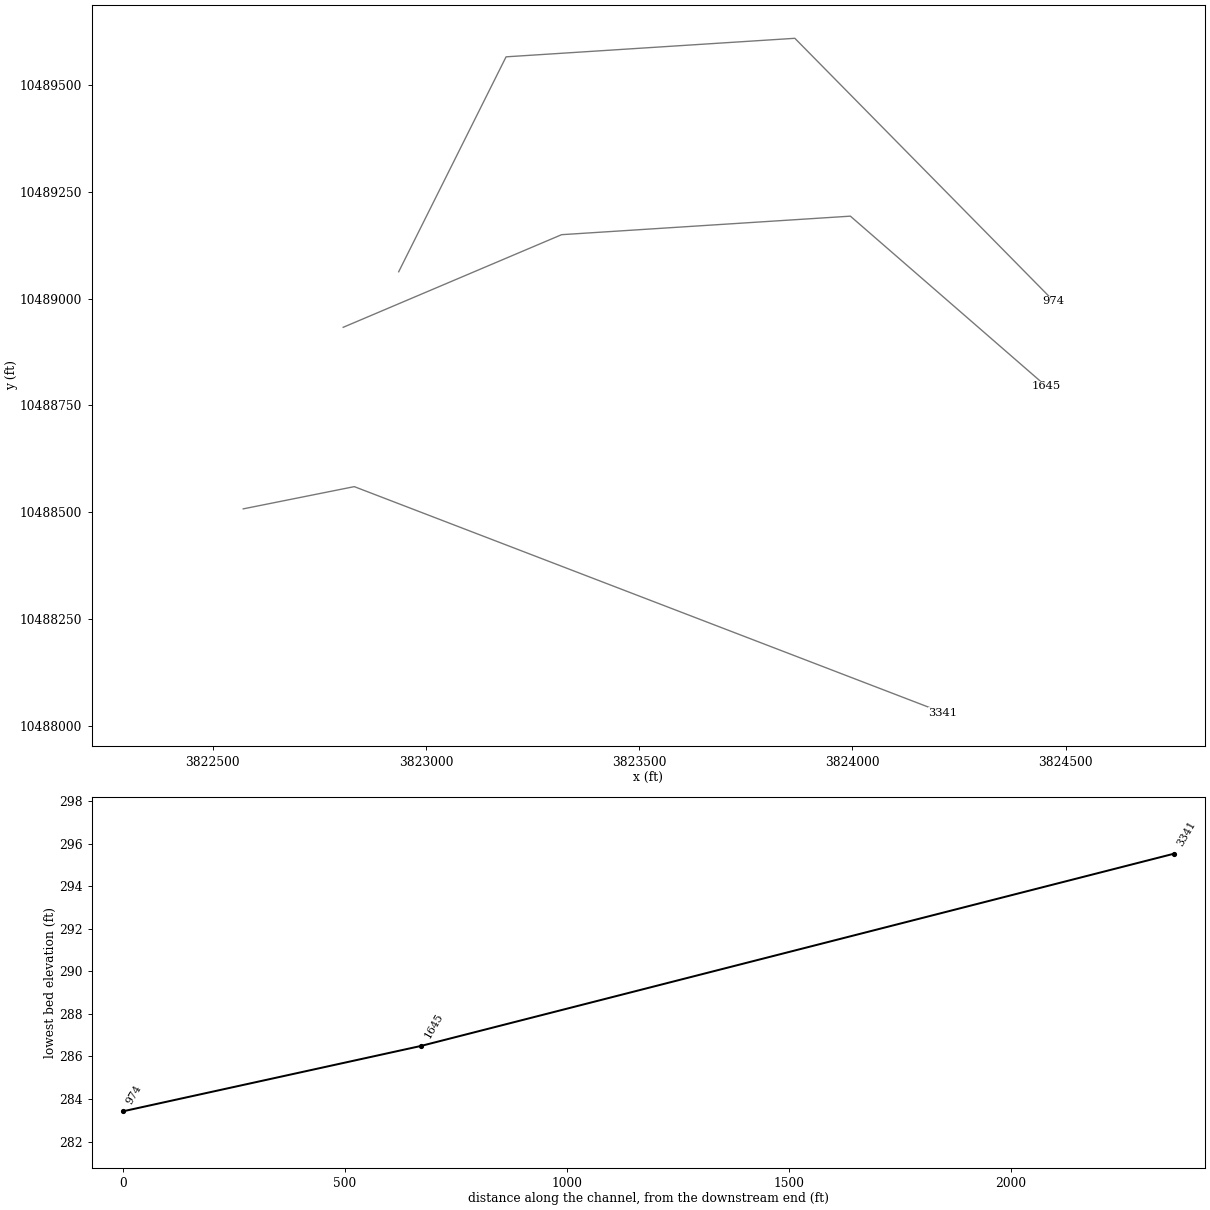
HEC-RAS study UNT024 IN BECR.prj: UNT024 IN BECR Base Level Engineering

--- UNT024 IN BECR.g01 (geometry) --- (continued)

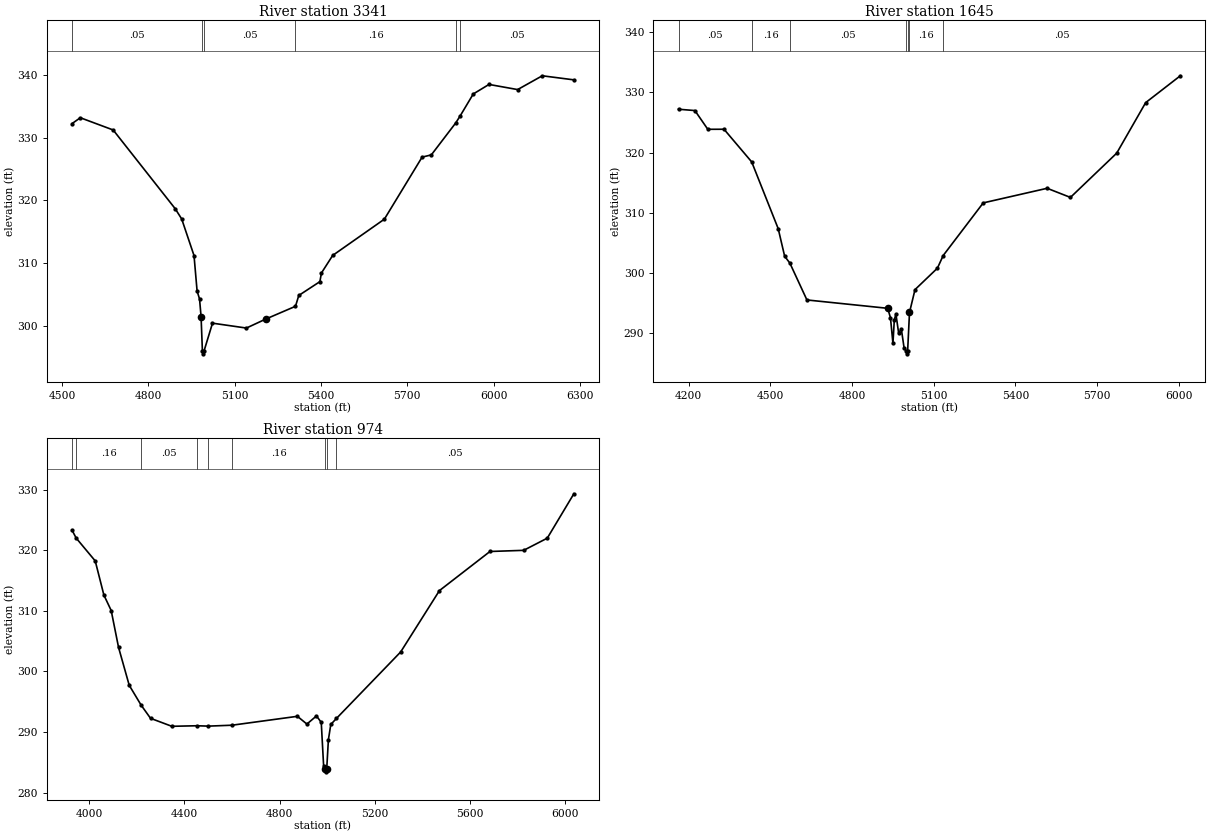
Type RM Length L Ch R = 1 ,3341    ,1696,1696,1696
BEGIN DESCRIPTION:
UNT024 IN BECR 3.0
END DESCRIPTION:
XS GIS Cut Line= 3
       3822571.5     10488507.79      3822831.87     10488559.86
      3824212.06     10488030.35
#Sta/Elev= 30
    4535  332.23  4563.7  333.16  4677.8  331.21  4893.2  318.67  4915.9  317.03
  4958.8  311.19  4969.5  305.52    4978  304.27  4983.3  301.46  4987.9  296.02
  4990.6  295.52  4993.9  296.02    5023  300.41  5140.8  299.63  5207.4  301.05
  5311.4   303.1  5322.9  304.83  5396.2  307.03  5401.6  308.41  5440.7  311.21
  5620.3  316.99  5751.4  326.88  5783.5  327.24  5868.4  332.34  5883.8  333.46
  5929.2  336.95  5983.9  338.47  6083.4  337.65  6169.1  339.85  6278.8   339.2
#Mann= 6 ,-1 , 0
    4535     .05       0  4987.9     .03       0  4993.9     .05       0
  5311.4     .16       0  5868.4      .1       0  5883.8     .05       0
Bank Sta=4983.3,5207.4
XS Rating Curve= 0 ,0
Exp/Cntr=0.3,0.1

Type RM Length L Ch R = 1 ,1645    ,671,671,671
BEGIN DESCRIPTION:
UNT024 IN BECR 2.0
END DESCRIPTION:
XS GIS Cut Line= 4
      3822805.88     10488933.14      3823317.98     10489150.14
      3823995.07     10489193.54      3824454.35     10488794.92
#Sta/Elev= 30
    4163  327.21  4223.1  326.99  4270.5  323.87    4330  323.88  4431.7  318.44
    4529  307.33  4552.7  302.74  4571.8   301.6  4634.5  295.46  4931.2  294.07
  4941.3   292.5  4950.4  288.23  4955.4  292.12  4961.3  293.12  4971.3  289.97
  4981.3   290.6  4991.4  287.46  4998.4  286.99  5001.1  286.49  5004.4  286.99
  5011.2  293.38  5031.4  297.18  5113.7  300.75    5135  302.86    5282  311.62
  5516.7  314.05  5602.2  312.53  5772.2   319.9  5878.5  328.31  6005.8  332.78
#Mann= 7 ,-1 , 0
    4163     .05       0  4431.7     .16       0  4571.8     .05       0
  4998.4     .03       0  5004.4     .05       0  5011.2     .16       0
    5135     .05       0
Bank Sta=4931.2,5011.2
XS Rating Curve= 0 ,0
Exp/Cntr=0.3,0.1

Type RM Length L Ch R = 1 ,974     ,0,0,0
BEGIN DESCRIPTION:
UNT024 IN BECR 1.0
END DESCRIPTION:
XS GIS Cut Line= 4
      3822936.02     10489063.29      3823187.78      10489566.8
      3823864.86     10489610.21      3824471.86     10488994.53
#Sta/Elev= 30
  3929.4  323.32  3946.7  322.02  4026.6  318.25    4063  312.61  4093.6  310.06
  4124.5  303.97  4169.3  297.71  4219.3  294.43  4258.7  292.26  4348.1  290.94
  4452.8  291.03  4501.7  290.97  4600.5  291.12    4875  292.59    4915  291.31
  4955.1  292.65  4975.2  291.59  4985.2  284.37  4992.2  283.92    4995  283.42
  4998.2  283.92  5005.2  288.72  5015.2  291.24    5039  292.24  5308.6  303.22
  5471.2  313.35  5683.3  319.81  5824.7     320  5923.8  322.01  6035.4  329.34
#Mann= 9 ,-1 , 0
  3929.4     .05       0  3946.7     .16       0  4219.3     .05       0
  4452.8     .12       0  4501.7     .05       0  4600.5     .16       0
  4992.2     .07       0  4998.2     .16       0    5039     .05       0
Bank Sta=4992.2,4998.2
XS Rating Curve= 0 ,0
Exp/Cntr=0.3,0.1

Chan Stop Cuts=-1
Use User Specified Reach Order=0
Composite Channel Slope=5