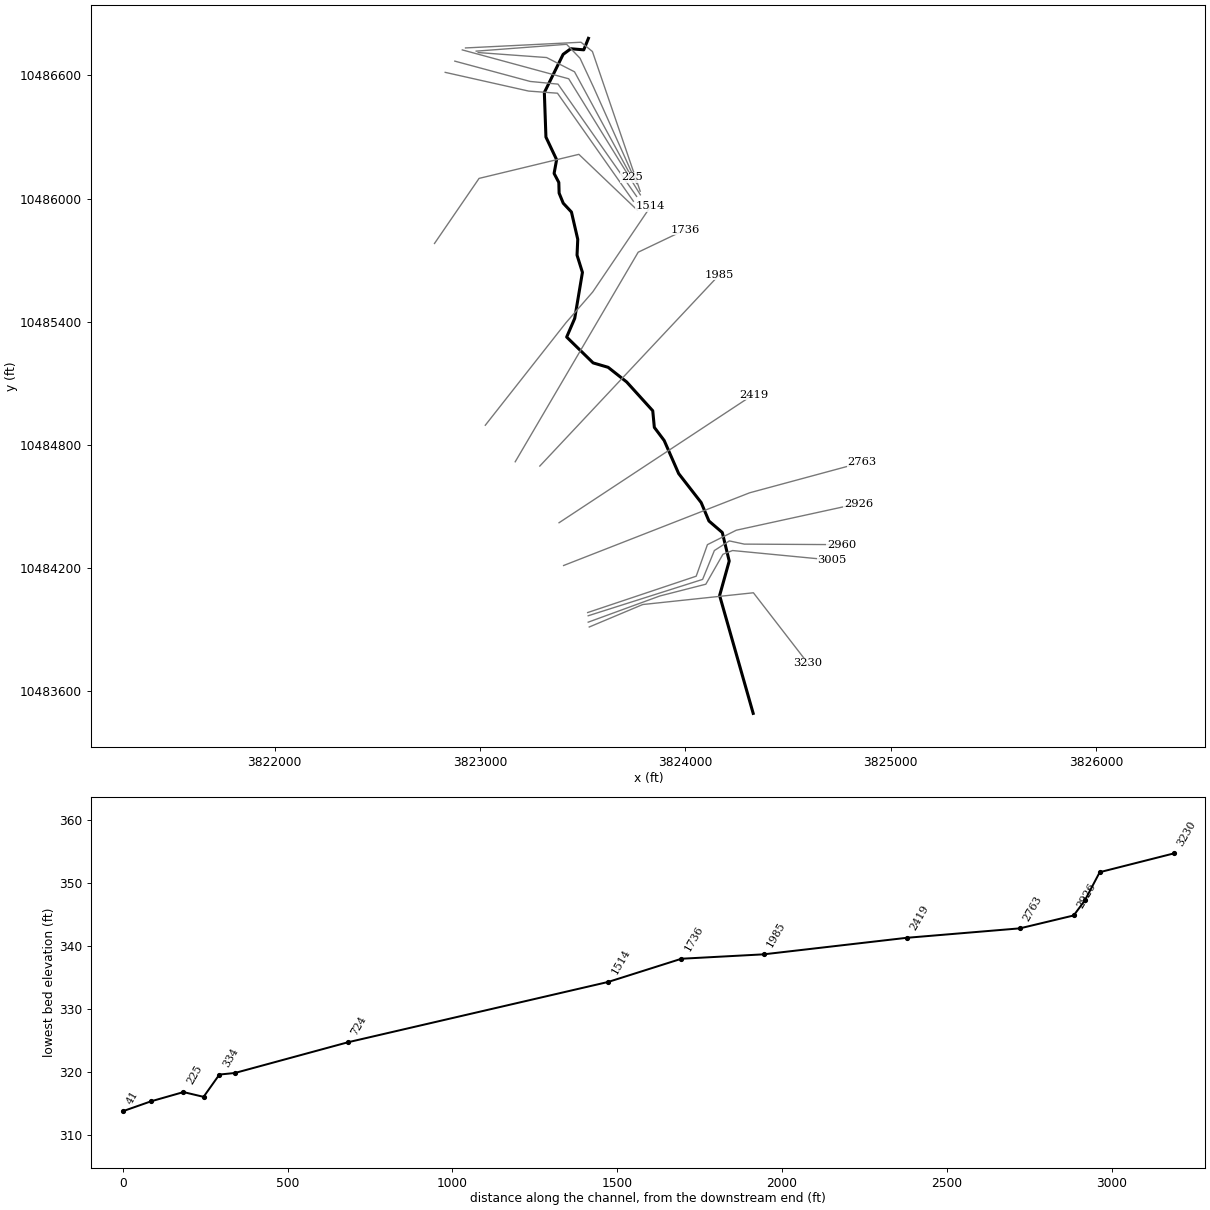
--- UNT025 IN BECR.prj (project) ---

Proj Title=UNT025 IN BECR Base Level Engineering
Current Plan=p01
Default Exp/Contr=0.3,0.1
English Units
Geom File=g01
Flow File=f01
Plan File=p01
Y Axis Title=Elevation
X Axis Title(PF)=Main Channel Distance
X Axis Title(XS)=Station
BEGIN DESCRIPTION:
UNT025 IN BECR
END DESCRIPTION:
DSS Export Rating Curves= 0
DSS Export Rating Curve Sorted= 0
DSS Export Volume Flow Curves= 0
DXF OffsetX= 0
DXF OffsetY= 0
DXF ScaleX= 1
DXF ScaleY= 10

--- UNT025 IN BECR.p01 (plan) ---

Plan Title=Multiple Run
Short Identifier=Multiple
Geom File=g01
Flow File=f01
Subcritical Flow
K Sum by GR= 0
Std Step Tol= 0.01
Critical Tol= 0.01
Num of Std Step Trials= 20
Max Error Tol= 0.3
Flow Tol Ratio= 0.001
Split Flow NTrial= 30
Split Flow Tol= 0.02
Split Flow Ratio= 0.02
Log Output Level= 0
Friction Slope Method= 1
Unsteady Friction Slope Method= 2
Unsteady Bridges Friction Slope Method= 1
Parabolic Critical Depth
Global Vel Dist=  1 , 1 , 1
Global Log Level= 0
CheckData=True
Encroach Param= -1, 0, 0, 0
BEGIN DESCRIPTION:
Multiple Run
END DESCRIPTION:

--- UNT025 IN BECR.f01 (steady flow) ---

Flow Title=Multiple
Program Version=4.10
Number of Profiles= 7
Profile Names=10-year,25-year,50-year,1pct_min,100-year,1pct_plu,500-year
River Rch & RM=UNT025 IN BECR,Reach-1         ,3230
     162     202     232     197     266     360     351
River Rch & RM=UNT025 IN BECR,Reach-1         ,41
     162     202     232     197     266     360     351
Boundary for River Rch & Prof#=UNT025 IN BECR,Reach-1         , 1
Up Type= 0
Dn Type= 3
Dn Slope=0.005
Boundary for River Rch & Prof#=UNT025 IN BECR,Reach-1         , 2
Up Type= 0
Dn Type= 3
Dn Slope=0.005
Boundary for River Rch & Prof#=UNT025 IN BECR,Reach-1         , 3
Up Type= 0
Dn Type= 3
Dn Slope=0.005
Boundary for River Rch & Prof#=UNT025 IN BECR,Reach-1         , 4
Up Type= 0
Dn Type= 3
Dn Slope=0.005
Boundary for River Rch & Prof#=UNT025 IN BECR,Reach-1         , 5
Up Type= 0
Dn Type= 3
Dn Slope=0.005
Boundary for River Rch & Prof#=UNT025 IN BECR,Reach-1         , 6
Up Type= 0
Dn Type= 3
Dn Slope=0.005
Boundary for River Rch & Prof#=UNT025 IN BECR,Reach-1         , 7
Up Type= 0
Dn Type= 3
Dn Slope=0.005
DSS Import GetInterval= 0
DSS Import GetPeak= 0
DSS Import FillOption= 0

--- UNT025 IN BECR.g01 (geometry) ---

Geom Title=Existing Conditions
Program Version=4.10

River Reach=UNT025 IN BECR  ,Reach-1
Reach XY= 30
      3824330.97     10483493.03       3824167.5       10484067.
      3824214.25       10484235.       3824180.5       10484374.
       3824115.5       10484430.       3824077.5       10484520.
        3823968.       10484661.       3823897.5       10484822.
       3823849.5       10484886.      3823841.75       10484967.
      3823714.75     10485107.24      3823624.52     10485178.59
      3823551.36     10485200.09       3823422.5       10485326.
      3823461.75       10485417.      3823499.25       10485641.
        3823473.       10485725.       3823476.5       10485802.
      3823445.75       10485935.      3823405.75       10485978.
      3823385.75       10486027.      3823384.25       10486079.
      3823361.25       10486123.       3823373.5       10486190.
       3823321.5       10486300.      3823313.75       10486517.
      3823405.25       10486703.      3823442.41     10486730.28
      3823505.75       10486725.       3823528.5       10486781.

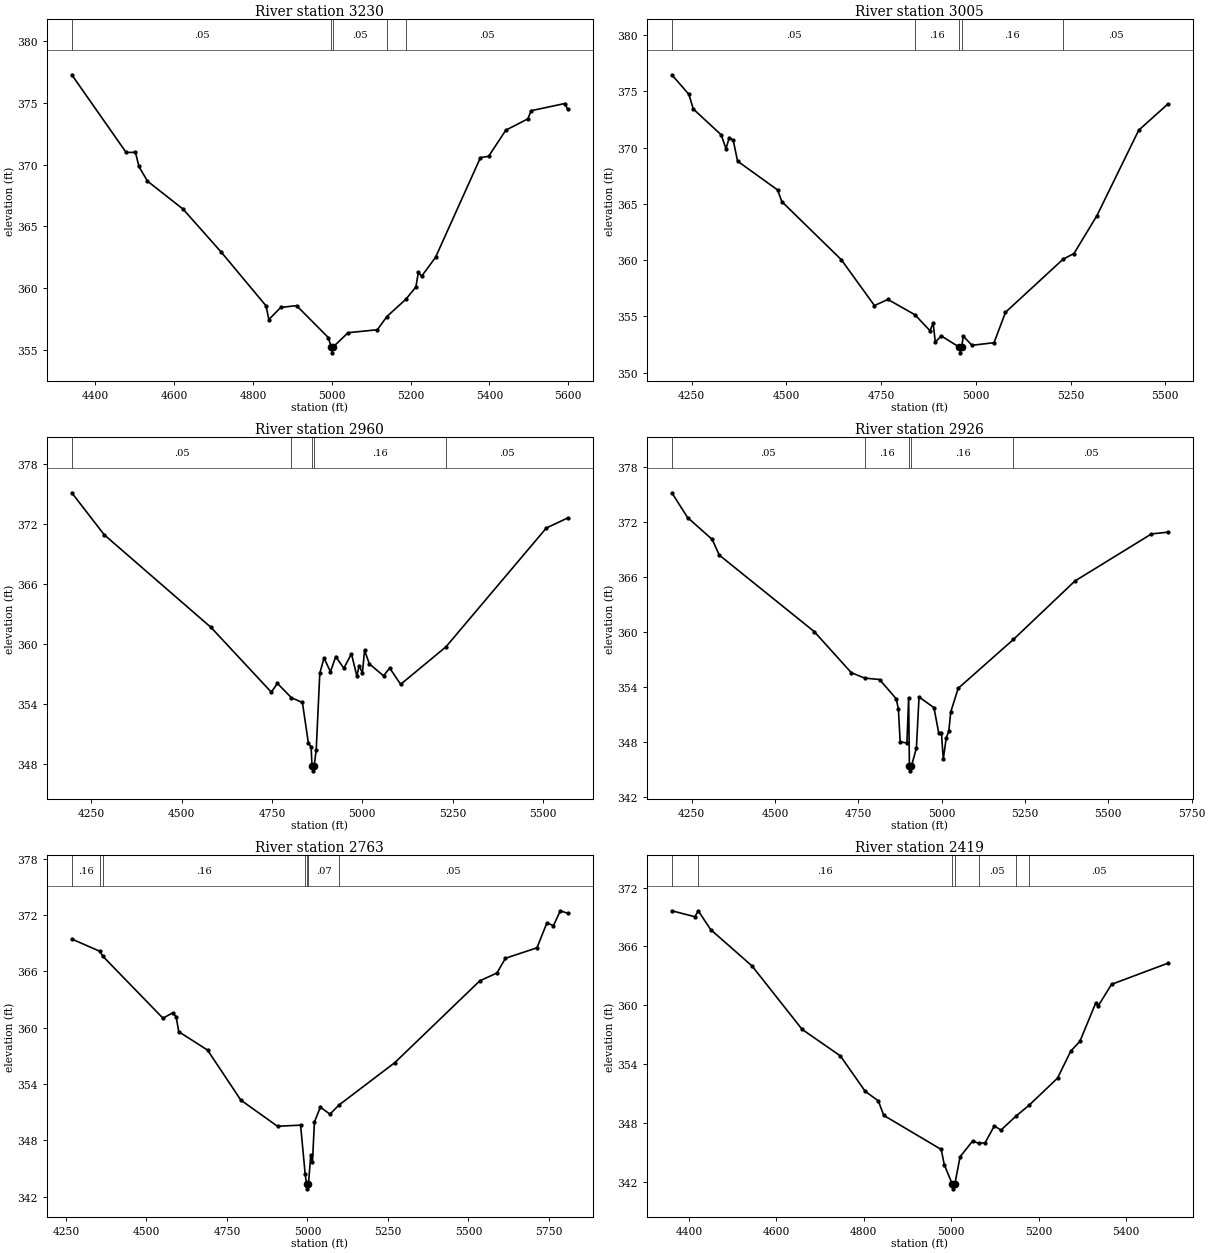
Type RM Length L Ch R = 1 ,3230    ,225,225,225
BEGIN DESCRIPTION:
UNT025 IN BECR 7.0
END DESCRIPTION:
XS GIS Cut Line= 4
      3823532.56      10483913.8      3823792.99     10484023.19
      3824332.05     10484080.48      3824597.69     10483736.71
#Sta/Elev= 30
  4339.8  377.28  4477.8  370.99  4501.5     371  4510.1  369.86  4531.8  368.67
  4622.3   366.4  4719.4  362.91  4832.8  358.57  4840.1  357.46  4870.3  358.44
  4910.5  358.58  4990.9     356    4998  355.26  5000.8  354.76    5004  355.26
  5041.2  356.39  5115.5  356.63  5139.7   357.7  5188.2  359.11  5213.3   360.1
  5219.6  361.28  5227.8  360.96  5263.1  362.49  5377.2  370.57    5398  370.68
  5441.5  372.79  5497.6  373.71  5505.8  374.37  5590.9  374.95  5598.8  374.48
#Mann= 5 ,-1 , 0
  4339.8     .05       0    4998     .03       0    5004     .05       0
  5139.7     .16       0  5188.2     .05       0
Bank Sta=4998,5004
XS Rating Curve= 0 ,0
Exp/Cntr=0.3,0.1

Type RM Length L Ch R = 1 ,3005    ,45,45,45
BEGIN DESCRIPTION:
Mapping XS 1355bba4
END DESCRIPTION:
XS GIS Cut Line= 6
      3823527.36     10483937.25      3823876.32     10484064.85
      3824100.28     10484122.14      3824183.62     10484267.98
      3824230.49     10484286.21      3824716.05     10484239.47
#Sta/Elev= 30
  4197.7  376.46  4242.7  374.72  4254.3  373.42  4327.9  371.13  4340.6  369.89
  4349.2  370.89  4359.8  370.63  4371.1  368.79  4476.9  366.23  4487.9   365.2
  4644.9  360.04  4732.3  355.97    4768  356.51  4839.3  355.15  4878.8  353.74
  4887.2   354.4  4892.9  352.73  4908.8  353.27  4956.4  352.27  4959.2  351.77
  4962.4  352.27  4966.8  353.25  4989.6  352.44  5047.9  352.67  5078.1  355.37
  5230.3  360.09  5258.9  360.59  5319.2  363.94  5429.7  371.54  5506.5  373.86
#Mann= 5 ,-1 , 0
  4197.7     .05       0  4839.3     .16       0  4956.4     .07       0
  4962.4     .16       0  5230.3     .05       0
Bank Sta=4956.4,4962.4
XS Rating Curve= 0 ,0
Exp/Cntr=0.3,0.1

Type RM Length L Ch R = 1 ,2960    ,34,34,34
BEGIN DESCRIPTION:
Mapping XS c93f09c9
END DESCRIPTION:
XS GIS Cut Line= 6
      3823527.41     10483968.51      3824084.66     10484145.58
      3824141.95     10484286.21      3824214.87     10484333.08
      3824287.78     10484317.46      3824761.77     10484314.85
#Sta/Elev= 30
  4196.5  375.16  4286.3  370.95  4581.8  361.66  4748.3  355.18  4765.4  356.05
  4804.2  354.61  4834.4  354.14    4851  350.05  4858.5  349.69  4860.9  347.79
  4863.6  347.29  4866.9  347.79  4872.6   349.4  4882.5  357.08  4894.2   358.6
    4912  357.22  4926.6  358.75  4948.9  357.57    4970  359.02  4985.2  356.77
  4991.1  357.83  5000.4  357.11  5006.3  359.38  5019.6  358.01  5058.9  356.81
  5075.7   357.6  5106.1  355.96  5231.2  359.71  5509.1  371.63  5568.3  372.64
#Mann= 5 ,-1 , 0
  4196.5     .05       0  4804.2     .16       0  4860.9     .07       0
  4866.9     .16       0  5231.2     .05       0
Bank Sta=4860.9,4866.9
XS Rating Curve= 0 ,0
Exp/Cntr=0.3,0.1

Type RM Length L Ch R = 1 ,2926    ,163,163,163
BEGIN DESCRIPTION:
Mapping XS 68966393
END DESCRIPTION:
XS GIS Cut Line= 5
      3823524.76     10483984.12      3824053.41     10484161.21
       3824108.1     10484314.85      3824248.72     10484385.16
      3824844.45     10484515.24
#Sta/Elev= 30
  4190.9  375.15  4238.2  372.45    4312  370.07  4333.1  368.37  4617.9  360.04
    4729  355.57    4769  354.98    4814  354.82  4864.1  352.71  4870.4  351.59
  4875.7  348.04  4895.9  347.91  4901.2  352.84  4903.4  345.38  4906.1  344.88
  4909.4  345.38  4924.4  347.37  4932.3  352.92    4977  351.76  4991.5  348.98
  4999.4  349.04    5005  346.14  5013.8  348.46  5021.7  349.22  5027.3  351.28
  5049.7  353.86  5215.6  359.19  5399.7  365.54  5629.4  370.67  5678.5  370.86
#Mann= 5 ,-1 , 0
  4190.9     .05       0    4769     .16       0  4903.4     .07       0
  4909.4     .16       0  5215.6     .05       0
Bank Sta=4903.4,4909.4
XS Rating Curve= 0 ,0
Exp/Cntr=0.3,0.1

Type RM Length L Ch R = 1 ,2763    ,344,344,344
BEGIN DESCRIPTION:
UNT025 IN BECR 6.0
END DESCRIPTION:
XS GIS Cut Line= 3
      3823407.56     10484213.28      3824313.82     10484567.46
      3824861.96     10484715.53
#Sta/Elev= 30
  4267.9  369.46  4354.5  368.16  4364.5  367.62  4551.2  361.02  4581.5  361.59
  4592.2  361.17  4600.2  359.58  4689.7  357.62    4793  352.29    4907   349.5
  4978.7  349.62  4992.9  344.42  4997.2  343.33  4999.9  342.83  5003.2  343.33
  5010.2   346.4  5015.6   345.7  5021.7  349.95  5040.1  351.54  5069.9  350.79
  5097.5  351.75  5271.7  356.29  5535.4     365  5588.7  365.84  5615.2  367.41
    5713  368.52  5744.1  371.19  5764.3  370.88  5785.5  372.47  5808.7   372.2
#Mann= 7 ,-1 , 0
  4267.9     .16       0  4354.5     .05       0  4364.5     .16       0
  4992.9     .07       0  4997.2     .07       0  5003.2     .07       0
  5097.5     .05       0
Bank Sta=4997.2,5003.2
XS Rating Curve= 0 ,0
Exp/Cntr=0.3,0.1

Type RM Length L Ch R = 1 ,2419    ,434,434,434
BEGIN DESCRIPTION:
UNT025 IN BECR 5.0
END DESCRIPTION:
XS GIS Cut Line= 2
      3823385.43     10484421.62      3824332.25     10485045.89
#Sta/Elev= 30
  4361.1  369.63    4414  369.02  4421.4  369.63    4450  367.71  4544.5  364.01
  4658.9  357.56  4746.3  354.86  4803.4  351.24  4833.2  350.28  4845.6   348.8
    4977  345.33  4984.1  343.77  5002.2  341.82  5004.9  341.32  5008.2  341.82
  5020.2  344.59  5048.9  346.19  5062.9  345.95  5077.4  346.01  5098.5  347.73
  5113.6   347.3  5147.9  348.72  5178.4  349.85    5243  352.59  5273.2  355.34
  5294.2  356.34  5330.4  360.25  5336.4  359.97  5366.5  362.14  5495.2  364.29
#Mann= 7 ,-1 , 0
  4361.1     .05       0  4421.4     .16       0  5002.2     .07       0
  5008.2     .16       0  5062.9     .05       0  5147.9      .1       0
  5178.4     .05       0
Bank Sta=5002.2,5008.2
XS Rating Curve= 0 ,0
Exp/Cntr=0.3,0.1

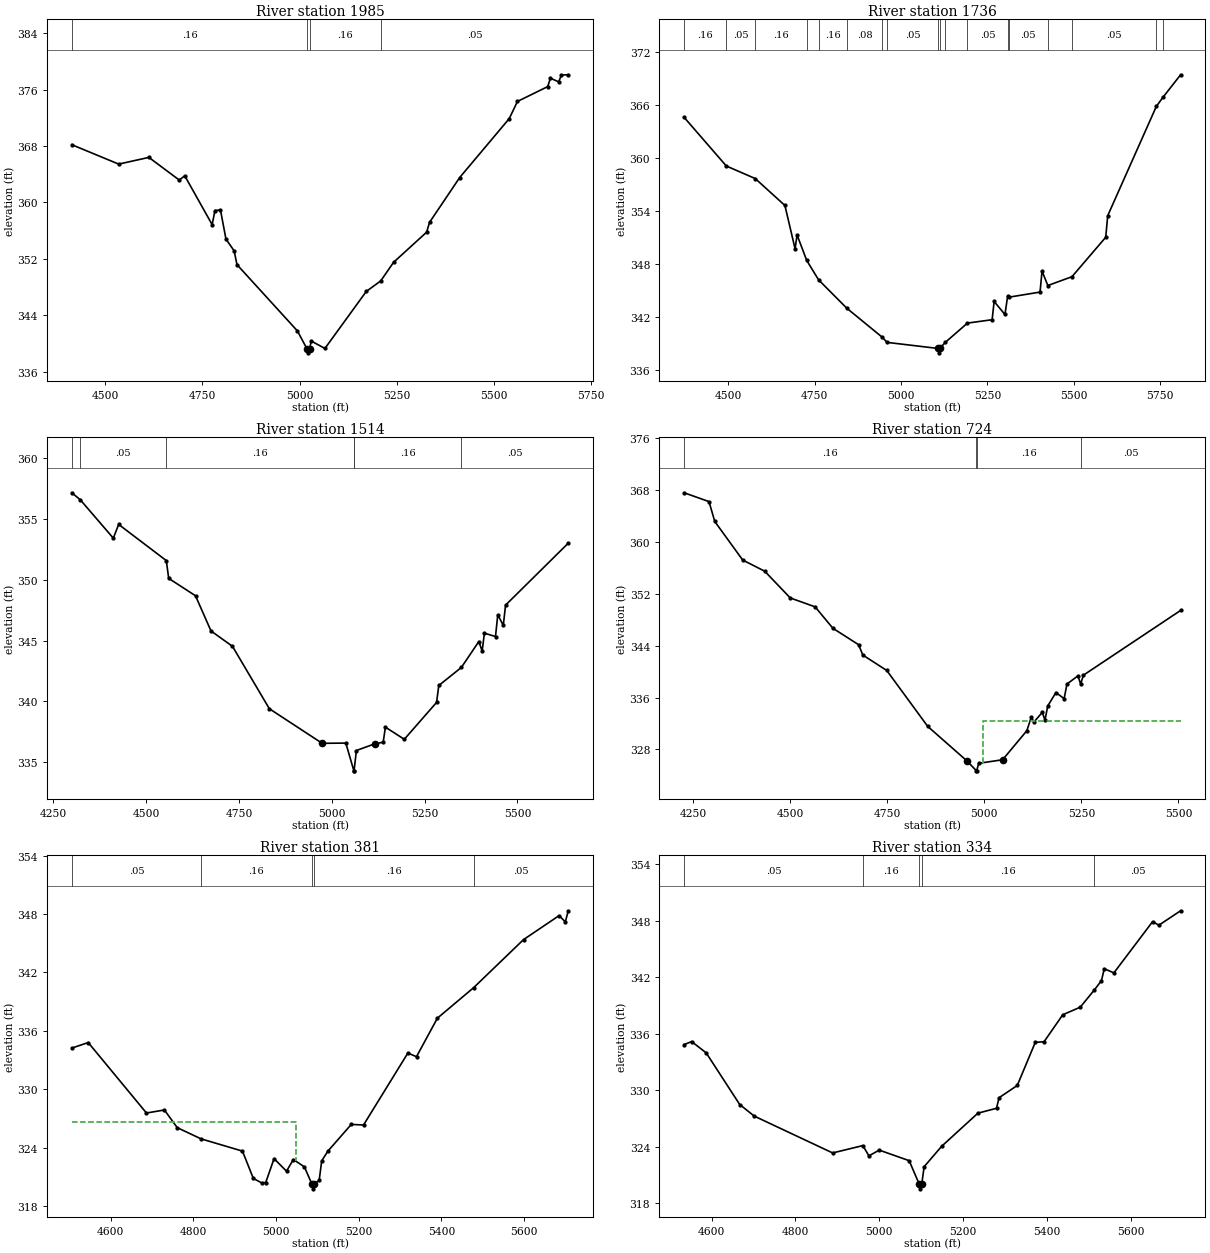
Type RM Length L Ch R = 1 ,1985    ,249,249,249
BEGIN DESCRIPTION:
Mapping XS 5f377a75
END DESCRIPTION:
XS GIS Cut Line= 2
      3823291.67     10484697.65      3824165.65     10485628.85
#Sta/Elev= 30
  4414.2  368.19  4534.8  365.44  4612.5  366.39  4690.6  363.18  4704.8  363.78
  4775.2  356.86  4782.5  358.85  4796.6  358.95  4810.8   354.8  4831.8  353.15
  4839.1  351.19  4994.5   341.8  5019.8  339.19  5022.5  338.69  5025.8  339.19
  5030.1  340.37  5065.3  339.31  5171.7  347.39  5208.8  348.88  5242.1  351.53
  5327.1   355.8  5334.4  357.18  5412.1  363.54  5539.5  371.89  5560.6  374.32
  5638.3  376.42  5645.5  377.61  5666.6   377.1  5673.9  378.07  5691.3   378.1
#Mann= 4 ,-1 , 0
  4414.2     .16       0  5019.8     .07       0  5025.8     .16       0
  5208.8     .05       0
Bank Sta=5019.8,5025.8
XS Rating Curve= 0 ,0
Exp/Cntr=0.3,0.1

Type RM Length L Ch R = 1 ,1736    ,222,222,222
BEGIN DESCRIPTION:
UNT025 IN BECR 4.0
END DESCRIPTION:
XS GIS Cut Line= 3
       3823171.9      10484718.5      3823770.86     10485739.33
      3824000.02      10485848.7
#Sta/Elev= 30
  4371.7  364.58  4493.8  359.09  4577.6  357.67  4663.5  354.63  4692.9  349.74
  4698.7   351.3  4726.6  348.43    4761  346.23    4843  343.02  4944.4  339.78
  4959.3  339.17    5106  338.49  5108.8  337.99    5112  338.49  5127.8  339.17
  5192.1  341.35  5263.5  341.73  5269.3  343.79  5300.6  342.32  5308.5  344.41
  5311.3  344.27  5402.2  344.85    5408  347.22  5424.8  345.59  5494.7  346.59
  5592.4  351.04  5598.2  353.48    5739  365.82    5758  366.84  5809.2  369.39
#Mann= 18 ,-1 , 0
  4371.7     .16       0  4493.8     .05       0  4577.6     .16       0
  4726.6     .05       0    4761     .16       0    4843     .08       0
  4944.4     .16       0  4959.3     .05       0    5106     .04       0
    5112     .05       0  5127.8     .16       0  5192.1     .05       0
  5308.5     .08       0  5311.3     .05       0  5424.8     .08       0
  5494.7     .05       0    5739     .08       0    5758     .05       0
Bank Sta=5106,5112
XS Rating Curve= 0 ,0
Exp/Cntr=0.3,0.1

Type RM Length L Ch R = 1 ,1514    ,790,790,790
BEGIN DESCRIPTION:
UNT025 IN BECR 3.0
END DESCRIPTION:
XS GIS Cut Line= 4
      3823026.15     10484896.49      3823418.97     10485395.65
      3823549.18     10485545.39      3823831.28     10485962.04
#Sta/Elev= 30
    4300  357.14    4323  356.56  4411.8  353.41  4426.2  354.54  4554.5  351.57
  4560.9  350.11  4633.1  348.68  4674.8  345.79  4732.6  344.53    4832   339.4
  4974.3  336.56  5037.9  336.58  5059.5   334.3    5060   334.3  5066.4  335.97
  5115.8  336.52  5138.5  336.65  5144.4  337.89  5195.3  336.89  5282.2  339.92
  5288.2  341.31  5348.9  342.79    5396  344.92    5405  344.14    5411  345.61
  5440.9  345.33    5447  347.12  5461.9  346.25    5468  347.91  5636.8     353
#Mann= 6 ,-1 , 0
    4300     .08       0    4323     .05       0  4554.5     .16       0
  5059.5     .07       0    5060     .16       0  5348.9     .05       0
Bank Sta=4974.3,5115.8
XS Rating Curve= 0 ,0
Exp/Cntr=0.3,0.1

Type RM Length L Ch R = 1 ,724     ,343,343,343
BEGIN DESCRIPTION:
UNT025 IN BECR 2.0
END DESCRIPTION:
XS GIS Cut Line= 4
      3822778.76     10485781.91      3822995.79     10486098.78
       3823481.9     10486215.97      3823766.97     10485943.85
#Sta/Elev= 30
  4227.4  367.58  4291.4  366.22  4306.3  363.15  4378.1  357.21  4434.9  355.48
  4500.6  351.36  4564.7  349.98  4610.4  346.68  4676.7  344.14  4687.4  342.55
  4749.1  340.17  4854.6  331.54  4954.8  326.26  4980.1  324.69  4980.6  324.69
  4985.7  325.85  5047.4   326.4  5109.8  330.89  5121.2  332.97  5128.1  332.22
  5149.5  333.71  5156.4  332.53  5163.6   334.7  5184.7  336.77  5205.8  335.82
    5213  338.08  5241.3  339.34  5248.2  338.08  5255.5  339.45  5505.6  349.43
#Mann= 4 ,-1 , 0
  4227.4     .16       0  4980.1     .07       0  4980.6     .16       0
  5248.2     .05       0
#XS Ineff= 2 , 0
                         4996.25          332.45
Permanent Ineff=
       F       F
Bank Sta=4954.8,5047.4
XS Rating Curve= 0 ,0
Exp/Cntr=0.3,0.1

Type RM Length L Ch R = 1 ,381     ,47,47,47
BEGIN DESCRIPTION:
Mapping XS cad8b7f5
END DESCRIPTION:
XS GIS Cut Line= 4
      3822830.91     10486615.26      3823237.11     10486524.13
      3823377.73     10486513.71      3823747.51     10485987.69
#Sta/Elev= 30
  4506.4  334.24  4546.1  334.81  4686.9  327.58  4730.3  327.89  4761.3  326.08
  4818.8  324.93    4919  323.67  4945.3  320.87  4965.3  320.41  4975.3  320.45
  4995.4   322.9  5025.5  321.61  5042.1  322.81  5068.9  322.05  5086.7   320.3
  5089.5   319.8  5092.7   320.3  5104.5  320.67  5110.6  322.67  5125.4  323.66
  5182.1  326.41  5211.7  326.35  5318.9  333.73  5339.8  333.36  5390.3  337.31
  5478.2  340.45  5598.5  345.37  5684.8  347.84  5699.6  347.18  5706.7  348.33
#Mann= 5 ,-1 , 0
  4506.4     .05       0  4818.8     .16       0  5086.7     .07       0
  5092.7     .16       0  5478.2     .05       0
#XS Ineff= 2 , 0
          5048.3  326.65
Permanent Ineff=
       F       F
Bank Sta=5086.7,5092.7
XS Rating Curve= 0 ,0
Exp/Cntr=0.3,0.1

Type RM Length L Ch R = 1 ,334     ,48,48,48
BEGIN DESCRIPTION:
Mapping XS 4a3267c0
END DESCRIPTION:
XS GIS Cut Line= 4
      3822877.75     10486669.95      3823244.92       10486571.
      3823380.34     10486557.98      3823763.17     10486011.07
#Sta/Elev= 30
  4534.7  334.86  4552.6  335.18  4587.3  333.98  4667.2   328.5  4701.9  327.27
  4888.8  323.36  4960.9  324.14  4975.3  323.05    5000  323.66  5071.3  322.54
  5095.3  320.05    5098  319.55  5101.3  320.05    5107   321.9  5148.9  324.07
  5235.2  327.58  5279.6   328.1  5285.7  329.22  5329.1  330.52  5372.1   335.1
    5393  335.16  5437.5  338.02  5479.3  338.83  5513.2  340.67  5529.9  341.65
  5536.6  342.91  5559.5  342.47  5651.9  347.91  5666.8  347.53  5718.6  349.06
#Mann= 5 ,-1 , 0
  4534.7     .05       0  4960.9     .16       0  5095.3     .07       0
  5101.3     .16       0  5513.2     .05       0
Bank Sta=5095.3,5101.3
XS Rating Curve= 0 ,0
Exp/Cntr=0.3,0.1

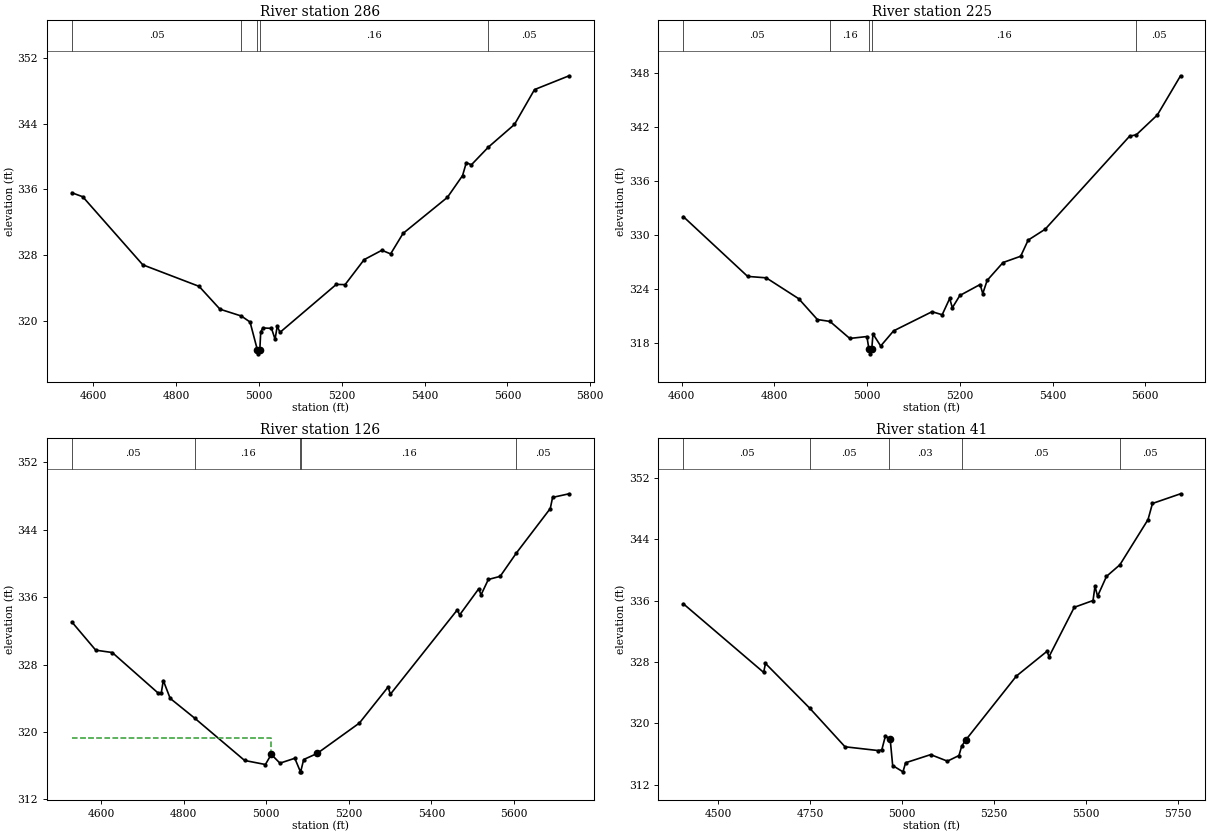
Type RM Length L Ch R = 1 ,286     ,61,61,61
BEGIN DESCRIPTION:
Mapping XS 1b95e765
END DESCRIPTION:
XS GIS Cut Line= 3
      3822914.16     10486724.66      3823432.42     10486584.02
       3823781.4     10486018.89
#Sta/Elev= 30
  4547.8   335.6  4574.2  335.11  4719.2  326.83  4855.2  324.21  4905.7  321.43
  4957.3   320.6  4978.3  319.87  4995.9   316.5  4998.6     316  5001.9   316.5
  5004.1  318.66  5009.4  319.15  5030.1   319.1  5038.7  317.78  5043.9  319.34
  5050.8  318.62  5186.7  324.45  5207.9  324.42  5253.9  327.46  5296.7   328.6
  5317.9  328.16  5347.9  330.65  5455.1  335.04  5491.7  337.69  5500.7  339.26
    5513     339    5554  341.15  5617.1  343.91  5665.5  348.15    5749  349.83
#Mann= 5 ,-1 , 0
  4547.8     .05       0  4957.3     .16       0  4995.9     .07       0
  5001.9     .16       0    5554     .05       0
Bank Sta=4995.9,5001.9
XS Rating Curve= 0 ,0
Exp/Cntr=0.3,0.1

Type RM Length L Ch R = 1 ,225     ,99,99,99
BEGIN DESCRIPTION:
Mapping XS 7ba5c051
END DESCRIPTION:
XS GIS Cut Line= 4
      3822991.32     10486711.74      3823324.65     10486687.43
      3823460.76     10486617.99      3823739.76      10486103.6
#Sta/Elev= 30
  4603.7     332  4742.4  325.36  4782.5   325.2  4852.6  322.88  4892.8  320.57
  4919.9  320.36  4962.6  318.47  4999.6  318.68    5004  317.26  5006.8  316.76
    5010  317.26  5012.7  318.97  5029.3  317.63  5057.1  319.31  5140.1  321.44
  5161.9   321.1  5178.1  322.91  5183.8  321.88    5200  323.24  5243.7  324.46
  5249.4  323.45  5258.9  324.92  5293.1   326.9  5331.2   327.6  5347.3  329.39
    5384   330.6    5566  340.93  5580.6  341.09  5625.9  343.29  5675.9  347.64
#Mann= 5 ,-1 , 0
  4603.7     .05       0  4919.9     .16       0    5004     .07       0
    5010     .16       0  5580.6     .05       0
Bank Sta=5004,5010
XS Rating Curve= 0 ,0
Exp/Cntr=0.3,0.1

Type RM Length L Ch R = 1 ,126     ,85,85,85
BEGIN DESCRIPTION:
Mapping XS 085ed6ab
END DESCRIPTION:
XS GIS Cut Line= 5
      3822981.88     10486718.59      3823422.21      10486751.9
      3823487.48      10486684.2      3823553.11     10486543.57
      3823763.31     10486073.66
#Sta/Elev= 30
  4528.4  333.07  4586.3  329.72  4626.4  329.44  4736.7  324.67  4745.1   324.6
  4750.1  326.12  4766.8     324  4826.5  321.64  4947.3  316.63  4997.7  316.15
  5011.9  317.35    5033  316.31    5069  316.89  5082.7  315.28  5083.2  315.28
  5090.5  316.74  5123.1  317.46  5225.6  321.07  5295.2  325.35  5300.7  324.49
  5463.1  334.51  5468.6   333.9    5515  337.01  5520.5  336.28  5538.2  338.11
  5566.9  338.48  5606.5  341.27  5688.4  346.53    5694  347.85    5734  348.28
#Mann= 5 ,-1 , 0
  4528.4     .05       0  4826.5     .16       0  5082.7     .07       0
  5083.2     .16       0  5606.5     .05       0
#XS Ineff= 2 , 0
         5010.11  319.25
Permanent Ineff=
       F       F
Bank Sta=5011.9,5123.1
XS Rating Curve= 0 ,0
Exp/Cntr=0.3,0.1

Type RM Length L Ch R = 1 ,41      ,0,0,0
BEGIN DESCRIPTION:
UNT025 IN BECR 1.0
END DESCRIPTION:
XS GIS Cut Line= 4
       3822929.8     10486734.22      3823492.34       10486762.
       3823547.9     10486716.86      3823780.53     10486036.33
#Sta/Elev= 30
  4404.2  335.58  4622.9  326.65    4628  327.81  4748.3     322  4844.5  316.97
  4934.7  316.48  4944.7  316.57  4954.7  318.42  4963.6  318.01  4967.4  318.01
  4974.3  314.53  5002.3  313.71  5009.5  314.89  5077.8  315.95  5123.4   315.1
  5154.8  315.83  5162.3  317.06  5172.9  317.83  5311.3  326.18  5394.7   329.4
    5400  328.69  5468.8  335.12  5519.9     336  5525.2  337.86  5532.2  336.56
  5556.5  339.14    5593  340.65  5669.6  346.53  5681.7  348.63  5758.2  349.89
#Mann= 5 ,-1 , 0
  4404.2     .05       0  4748.3     .05       0  4963.6     .03       0
  5162.3     .05       0    5593     .05       0
Bank Sta=4967.4,5172.9
XS Rating Curve= 0 ,0
Exp/Cntr=0.3,0.1

Chan Stop Cuts=-1
Use User Specified Reach Order=0
Composite Channel Slope=5