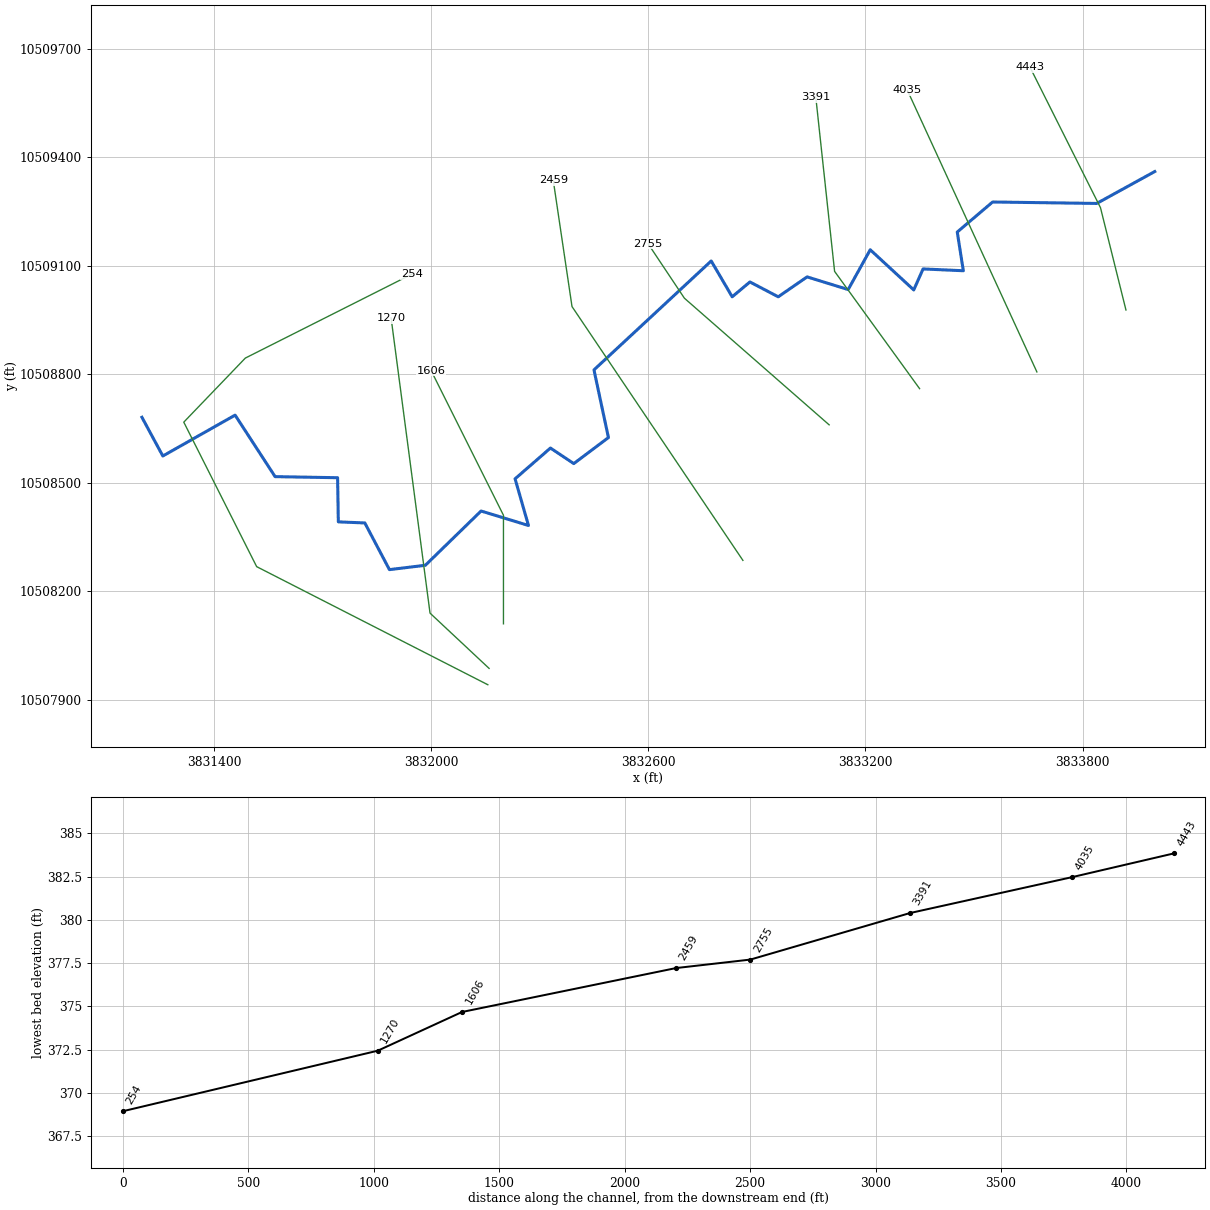
--- UNT027 IN BECR.prj (project) ---

Proj Title=UNT027 IN BECR Base Level Engineering
Current Plan=p01
Default Exp/Contr=0.3,0.1
English Units
Geom File=g01
Flow File=f01
Plan File=p01
BEGIN DESCRIPTION:
UNT027 IN BECR
END DESCRIPTION:

--- UNT027 IN BECR.p01 (plan) ---

Plan Title=Multiple Run
Short Identifier=Multiple
Geom File=g01
Flow File=f01
Subcritical Flow
K Sum by GR= 0
Std Step Tol= 0.01
Critical Tol= 0.01
Num of Std Step Trials= 20
Max Error Tol= 0.3
Flow Tol Ratio= 0.001
Split Flow NTrial= 30
Split Flow Tol= 0.02
Split Flow Ratio= 0.02
Log Output Level= 0
Friction Slope Method= 1
Unsteady Friction Slope Method= 2
Unsteady Bridges Friction Slope Method= 1
Parabolic Critical Depth
Global Vel Dist=  1 , 1 , 1
Global Log Level= 0
CheckData=True
Encroach Param= -1, 0, 0, 0
BEGIN DESCRIPTION:
Multiple Run
END DESCRIPTION:

--- UNT027 IN BECR.f01 (steady flow) ---

Flow Title=Multiple
Number of Profiles=7
Profile Names=10-year,25-year,50-year,1pct_min,100-year,1pct_plu,500-year
River Rch & RM= UNT027 IN BECR,Reach-1,4443
     505     669     803     707     956    1293    1362
Boundary for River Rch & Prof#=UNT027 IN BECR,Reach-1,1
Up Type=0
Dn Type=3
Dn Slope=0.005
Boundary for River Rch & Prof#=UNT027 IN BECR,Reach-1,2
Up Type=0
Dn Type=3
Dn Slope=0.005
Boundary for River Rch & Prof#=UNT027 IN BECR,Reach-1,3
Up Type=0
Dn Type=3
Dn Slope=0.005
Boundary for River Rch & Prof#=UNT027 IN BECR,Reach-1,4
Up Type=0
Dn Type=3
Dn Slope=0.005
Boundary for River Rch & Prof#=UNT027 IN BECR,Reach-1,5
Up Type=0
Dn Type=3
Dn Slope=0.005
Boundary for River Rch & Prof#=UNT027 IN BECR,Reach-1,6
Up Type=0
Dn Type=3
Dn Slope=0.005
Boundary for River Rch & Prof#=UNT027 IN BECR,Reach-1,7
Up Type=0
Dn Type=3
Dn Slope=0.005

--- UNT027 IN BECR.g01 (geometry) ---

Geom Title=Existing Conditions

River Reach=UNT027 IN BECR,Reach-1
Reach XY= 30
      3833999.61     10509360.19      3833839.25     10509272.00
      3833551.50     10509276.00      3833453.75     10509193.00
      3833470.50     10509086.00      3833359.25     10509091.00
      3833333.50     10509033.00      3833213.25     10509144.00
      3833152.25     10509034.00      3833038.75     10509069.00
      3832959.00     10509014.00      3832880.75     10509055.00
      3832831.75     10509014.00      3832773.75     10509113.00
      3832449.75     10508812.00      3832489.75     10508625.00
      3832394.00     10508553.00      3832329.50     10508596.00
      3832231.75     10508511.00      3832268.75     10508382.00
      3832137.75     10508422.00      3831983.75     10508272.00
      3831884.50     10508260.00      3831816.50     10508389.00
      3831743.25     10508392.00      3831741.25     10508514.00
      3831568.50     10508517.00      3831458.00     10508687.00
      3831258.25     10508574.00      3831200.50     10508681.00

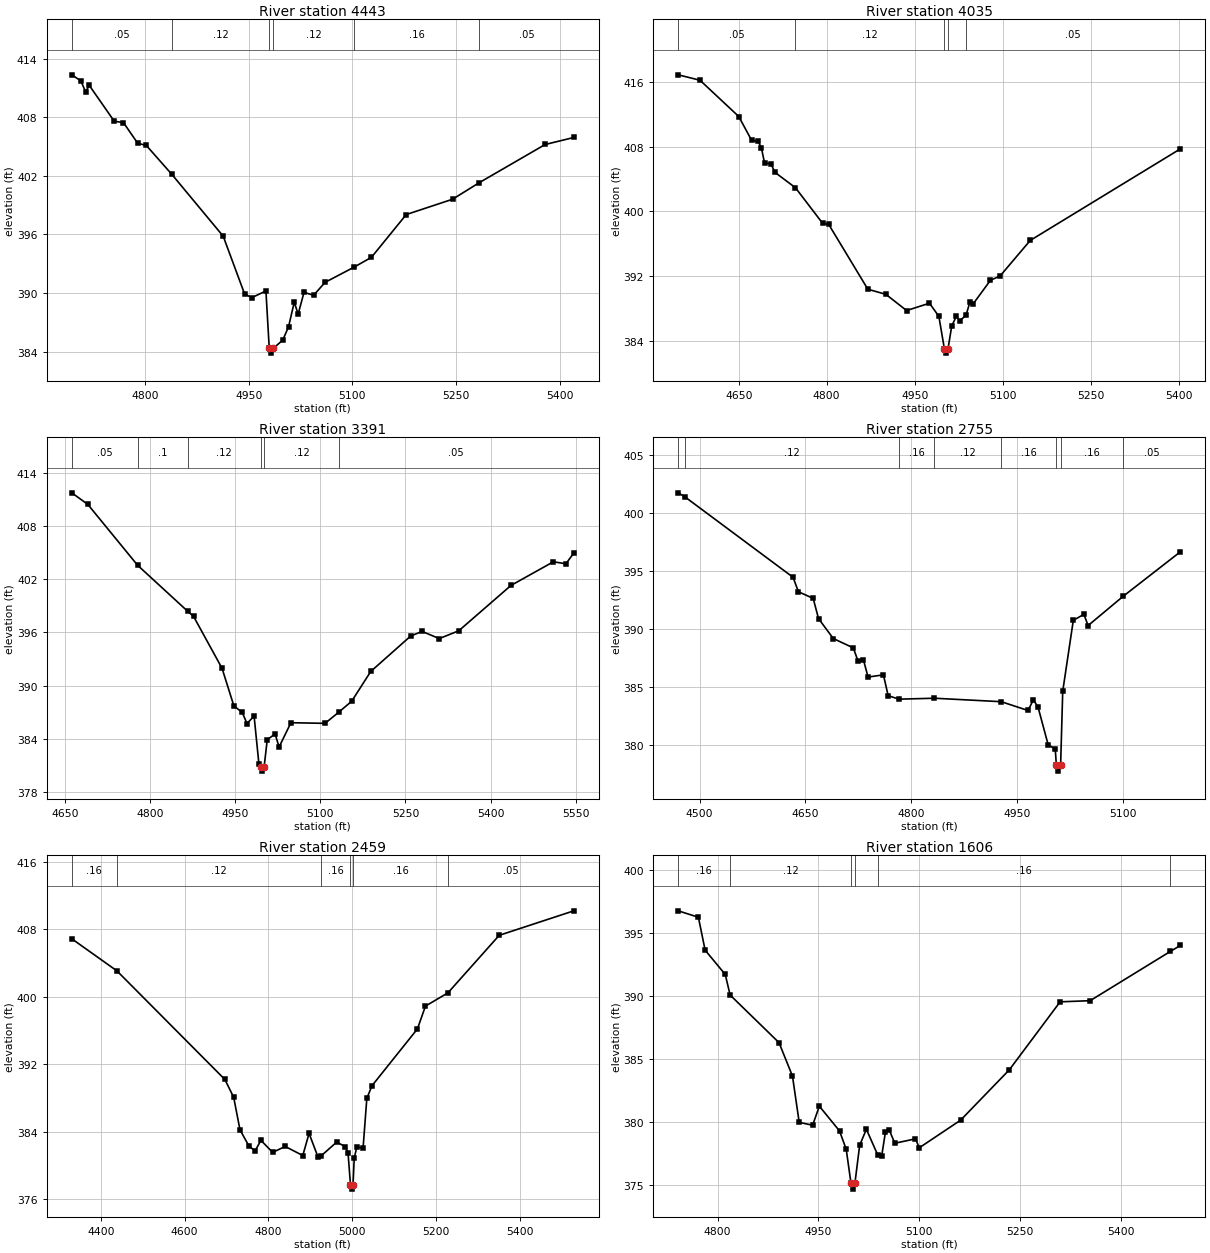
Type RM Length L Ch R = 1,4443,408,408,408
BEGIN DESCRIPTION:
UNT027 IN BECR 7.0
END DESCRIPTION:
XS GIS Cut Line= 3
      3833919.94     10508977.57      3833849.61     10509260.19
      3833654.47     10509649.14
#Sta/Elev= 30
  4694.0  412.36  4707.0  411.75  4714.1  410.62  4719.3  411.28  4755.4  407.61
  4768.8  407.46  4789.4  405.35  4801.9  405.12  4838.9  402.15  4913.1  395.82
  4944.0  389.91  4954.3  389.52  4974.9  390.21  4979.7  384.34  4982.4  383.84
  4985.7  384.34  4999.2  385.17  5007.6  386.53  5015.9  389.07  5021.5  387.83
  5030.0  390.07  5043.9  389.77  5060.6  391.10  5101.9  392.63  5127.6  393.66
  5177.9  398.04  5244.9  399.61  5283.6  401.31  5378.9  405.22  5420.4  405.94
#Mann=6,-1,0
  4694.0    0.05       0  4838.9    0.12       0  4979.7    0.07       0
  4985.7    0.12       0  5101.9    0.16       0  5283.6    0.05       0
Bank Sta=4979.7,4985.7
Exp/Cntr=0.3,0.1

Type RM Length L Ch R = 1,4035,644,644,644
BEGIN DESCRIPTION:
UNT027 IN BECR 6.0
END DESCRIPTION:
XS GIS Cut Line= 2
      3833673.79     10508806.44      3833316.14     10509584.25
#Sta/Elev= 30
  4546.9  416.91  4584.0  416.24  4650.1  411.75  4672.1  408.79  4683.1  408.67
  4688.6  407.90  4694.1  405.99  4705.1  405.89  4711.6  404.85  4746.8  402.93
  4793.2  398.52  4803.5  398.39  4870.2  390.37  4900.9  389.74  4936.3  387.73
  4975.3  388.64  4991.3  387.01  5000.8  382.96  5003.5  382.46  5006.8  382.96
  5013.3  385.83  5021.2  387.03  5026.7  386.46  5037.5  387.13  5044.2  388.76
  5049.7  388.55  5079.3  391.48  5095.7  392.01  5147.1  396.41  5403.0  407.74
#Mann=5,-1,0
  4546.9    0.05       0  4746.8    0.12       0  5000.8    0.07       0
  5006.8    0.12       0  5037.5    0.05       0
Bank Sta=5000.8,5006.8
Exp/Cntr=0.3,0.1

Type RM Length L Ch R = 1,3391,636,636,636
BEGIN DESCRIPTION:
UNT027 IN BECR 5.0
END DESCRIPTION:
XS GIS Cut Line= 3
      3833349.61     10508760.18      3833114.76     10509084.24
      3833062.77     10509566.03
#Sta/Elev= 30
  4662.0  411.72  4690.2  410.42  4778.1  403.56  4866.2  398.39  4876.6  397.81
  4926.8  391.97  4947.7  387.73  4962.4  387.00  4970.8  385.75  4983.3  386.59
  4991.8  381.20  4995.0  380.89  4997.7  380.39  5001.0  380.89  5006.5  383.93
  5020.2  384.57  5027.4  383.11  5048.2  385.84  5108.4  385.77  5132.4  387.02
  5155.2  388.25  5188.9  391.61  5259.3  395.60  5279.4  396.12  5309.6  395.31
  5344.0  396.19  5435.9  401.29  5510.8  403.96  5532.8  403.73  5546.8  404.95
#Mann=6,-1,0
  4662.0    0.05       0  4778.1     0.1       0  4866.2    0.12       0
  4995.0    0.07       0  5001.0    0.12       0  5132.4    0.05       0
Bank Sta=4995,5001
Exp/Cntr=0.3,0.1

Type RM Length L Ch R = 1,2755,296,296,296
BEGIN DESCRIPTION:
UNT027 IN BECR 4.0
END DESCRIPTION:
XS GIS Cut Line= 3
      3833099.63     10508660.17      3832699.61     10509010.19
      3832599.62     10509160.17
#Sta/Elev= 30
  4469.7  401.75  4479.2  401.40  4632.5  394.45  4640.1  393.20  4661.0  392.63
  4668.6  390.88  4689.5  389.16  4717.9  388.35  4724.6  387.21  4732.2  387.33
  4738.8  385.83  4760.6  386.02  4767.3  384.22  4782.7  383.92  4833.0  384.00
  4927.7  383.70  4965.6  382.94  4973.2  383.87  4979.9  383.21  4994.1  379.99
  5004.2  379.59  5005.8  378.20  5008.5  377.70  5011.8  378.20  5014.8  384.60
  5029.8  390.73  5044.8  391.25  5050.8  390.28  5100.7  392.82  5181.5  396.65
#Mann=8,-1,0
  4469.7     0.1       0  4479.2    0.12       0  4782.7    0.16       0
  4833.0    0.12       0  4927.7    0.16       0  5005.8    0.07       0
  5011.8    0.16       0  5100.7    0.05       0
Bank Sta=5005.8,5011.8
Exp/Cntr=0.3,0.1

Type RM Length L Ch R = 1,2459,853,853,853
BEGIN DESCRIPTION:
UNT027 IN BECR 3.0
END DESCRIPTION:
XS GIS Cut Line= 3
      3832861.30     10508285.60      3832389.06     10508987.02
      3832337.17     10509336.41
#Sta/Elev= 30
  4330.4  406.85  4438.2  403.05  4696.0  390.19  4717.0  388.08  4732.0  384.24
  4753.0  382.35  4768.0  381.72  4782.0  382.99  4810.0  381.56  4840.0  382.26
  4882.0  381.19  4897.0  383.81  4918.0  381.05  4925.6  381.14  4962.8  382.77
  4983.9  382.24  4990.0  381.51  4995.9  377.71  4998.7  377.21  5001.9  377.71
  5004.9  380.92  5011.0  382.18  5026.0  382.10  5034.9  387.95  5047.2  389.45
  5155.7  396.18  5174.9  398.88  5228.6  400.45  5351.0  407.26  5529.2  410.16
#Mann=6,-1,0
  4330.4    0.16       0  4438.2    0.12       0  4925.6    0.16       0
  4995.9    0.07       0  5001.9    0.16       0  5228.6    0.05       0
Bank Sta=4995.9,5001.9
Exp/Cntr=0.3,0.1

Type RM Length L Ch R = 1,1606,336,336,336
BEGIN DESCRIPTION:
UNT027 IN BECR 2.0
END DESCRIPTION:
XS GIS Cut Line= 3
      3832199.61     10508110.21      3832199.61     10508410.19
      3831999.61     10508810.19
#Sta/Elev= 30
  4741.3  396.75  4771.3  396.24  4781.3  393.63  4811.3  391.70  4818.5  390.07
  4891.3  386.29  4911.3  383.64  4921.3  379.97  4941.3  379.74  4951.3  381.25
  4981.3  379.29  4991.3  377.83  4998.3  375.17  5001.0  374.67  5004.3  375.17
  5011.3  378.15  5021.3  379.42  5038.1  377.39  5044.1  377.31  5049.7  379.21
  5055.3  379.37  5063.6  378.31  5094.4  378.66  5100.0  377.95  5161.5  380.14
  5234.1  384.14  5309.6  389.53  5354.3  389.62  5473.7  393.53  5488.5  394.00
#Mann=6,-1,0
  4741.3    0.16       0  4818.5    0.12       0  4998.3    0.07       0
  5004.3    0.12       0  5038.1    0.16       0  5473.7    0.12       0
Bank Sta=4998.3,5004.3
Exp/Cntr=0.3,0.1

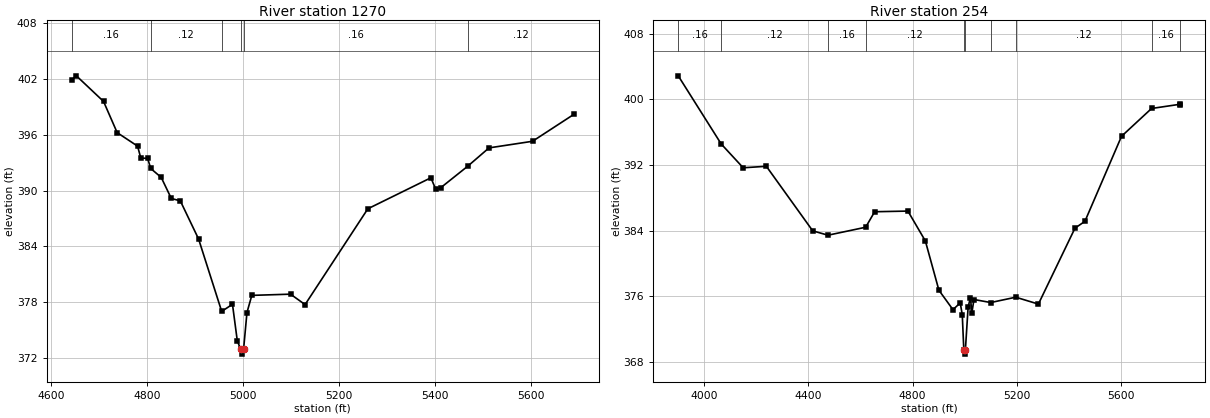
Type RM Length L Ch R = 1,1270,1016,1016,1016
BEGIN DESCRIPTION:
Mapping XS 15ead765
END DESCRIPTION:
XS GIS Cut Line= 3
      3832159.87     10507987.04      3831996.70     10508139.79
      3831889.10     10508955.51
#Sta/Elev= 30
  4643.6  401.90  4653.2  402.32  4709.8  399.57  4738.2  396.22  4780.7  394.77
  4787.5  393.48  4801.7  393.46  4808.1  392.37  4830.0  391.41  4851.0  389.15
  4869.8  388.89  4907.9  384.79  4956.0  377.02  4978.5  377.78  4988.5  373.88
  4995.6  372.93  4998.4  372.43  5001.6  372.93  5008.7  376.90  5018.8  378.74
  5099.5  378.87  5129.8  377.75  5260.6  388.04  5392.0  391.37  5402.1  390.13
  5412.2  390.29  5468.9  392.62  5513.1  394.58  5603.8  395.29  5689.9  398.18
#Mann=6,-1,0
  4643.6    0.16       0  4808.1    0.12       0  4956.0    0.16       0
  4995.6    0.07       0  5001.6    0.16       0  5468.9    0.12       0
Bank Sta=4995.6,5001.6
Exp/Cntr=0.3,0.1

Type RM Length L Ch R = 1,254,0,0,0
BEGIN DESCRIPTION:
UNT027 IN BECR 1.0
END DESCRIPTION:
XS GIS Cut Line= 5
      3832156.40     10507941.89      3831517.54     10508268.27
      3831316.15     10508667.57      3831486.29     10508844.65
      3831946.32     10509076.40
#Sta/Elev= 30
  3901.3  402.86  4066.1  394.55  4150.4  391.65  4239.2  391.83  4417.0  383.96
  4475.6  383.43  4620.0  384.40  4654.5  386.29  4782.0  386.37  4848.9  382.73
  4900.9  376.72  4954.8  374.35  4982.7  375.18  4990.5  373.72  4996.4  369.43
  4999.1  368.93  5002.4  369.43  5012.9  374.66  5021.7  375.82  5027.3  373.97
  5035.3  375.59  5099.7  375.22  5195.6  375.87  5282.4  375.03  5422.7  384.29
  5460.8  385.12  5601.2  395.49  5716.4  398.88  5825.0  399.39  5826.6  399.35
#Mann=10,-1,0
  3901.3    0.16       0  4066.1    0.12       0  4475.6    0.16       0
  4620.0    0.12       0  4996.4    0.07       0  5002.4    0.12       0
  5099.7    0.16       0  5195.6    0.12       0  5716.4    0.16       0
  5825.0    0.12       0
Bank Sta=4996.4,5002.4
Exp/Cntr=0.3,0.1

Chan Stop Cuts=-1