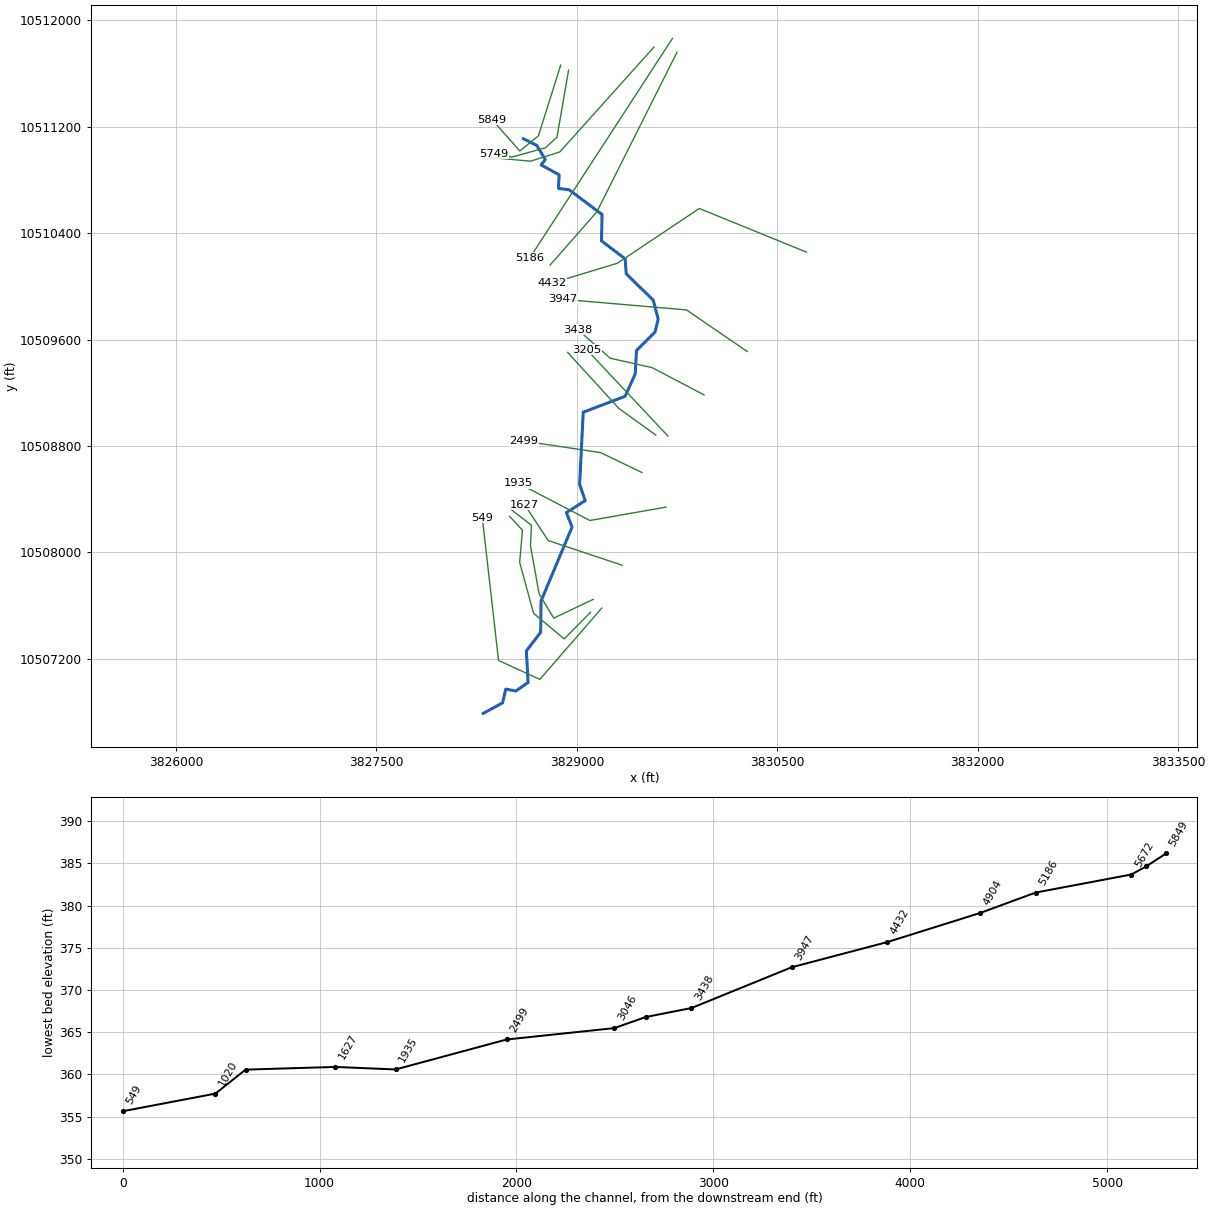
--- UNT028 IN BECR.prj (project) ---

Proj Title=UNT028 IN BECR Base Level Engineering
Current Plan=p01
Default Exp/Contr=0.3,0.1
English Units
Geom File=g01
Flow File=f01
Plan File=p01
BEGIN DESCRIPTION:
UNT028 IN BECR
END DESCRIPTION:

--- UNT028 IN BECR.p01 (plan) ---

Plan Title=Multiple Run
Short Identifier=Multiple
Geom File=g01
Flow File=f01
Subcritical Flow
K Sum by GR= 0
Std Step Tol= 0.01
Critical Tol= 0.01
Num of Std Step Trials= 20
Max Error Tol= 0.3
Flow Tol Ratio= 0.001
Split Flow NTrial= 30
Split Flow Tol= 0.02
Split Flow Ratio= 0.02
Log Output Level= 0
Friction Slope Method= 1
Unsteady Friction Slope Method= 2
Unsteady Bridges Friction Slope Method= 1
Parabolic Critical Depth
Global Vel Dist=  1 , 1 , 1
Global Log Level= 0
CheckData=True
Encroach Param= -1, 0, 0, 0
BEGIN DESCRIPTION:
Multiple Run
END DESCRIPTION:

--- UNT028 IN BECR.f01 (steady flow) ---

Flow Title=Multiple
Number of Profiles=7
Profile Names=10-year,25-year,50-year,1pct_min,100-year,1pct_plu,500-year
River Rch & RM= UNT028 IN BECR,Reach-1,5849
     683     924    1123    1002    1355    1833    1981
Boundary for River Rch & Prof#=UNT028 IN BECR,Reach-1,1
Up Type=0
Dn Type=3
Dn Slope=0.005
Boundary for River Rch & Prof#=UNT028 IN BECR,Reach-1,2
Up Type=0
Dn Type=3
Dn Slope=0.005
Boundary for River Rch & Prof#=UNT028 IN BECR,Reach-1,3
Up Type=0
Dn Type=3
Dn Slope=0.005
Boundary for River Rch & Prof#=UNT028 IN BECR,Reach-1,4
Up Type=0
Dn Type=3
Dn Slope=0.005
Boundary for River Rch & Prof#=UNT028 IN BECR,Reach-1,5
Up Type=0
Dn Type=3
Dn Slope=0.005
Boundary for River Rch & Prof#=UNT028 IN BECR,Reach-1,6
Up Type=0
Dn Type=3
Dn Slope=0.005
Boundary for River Rch & Prof#=UNT028 IN BECR,Reach-1,7
Up Type=0
Dn Type=3
Dn Slope=0.005

--- UNT028 IN BECR.g01 (geometry) ---

Geom Title=Existing Conditions

River Reach=UNT028 IN BECR,Reach-1
Reach XY= 30
      3828599.61     10511110.19      3828699.61     10511060.19
      3828764.00     10510954.00      3828733.50     10510913.00
      3828867.50     10510839.00      3828862.50     10510737.00
      3828943.00     10510726.00      3829188.75     10510541.00
      3829184.75     10510342.00      3829362.00     10510207.00
      3829369.25     10510095.00      3829571.75     10509897.00
      3829609.00     10509754.00      3829585.25     10509657.00
      3829446.50     10509517.00      3829436.75     10509341.00
      3829361.50     10509174.00      3829047.75     10509054.00
      3829021.00     10508511.00      3829063.00     10508390.00
      3828922.00     10508299.00      3828964.50     10508191.00
      3828732.25     10507635.00      3828729.50     10507400.00
      3828622.25     10507259.00      3828635.25     10507022.00
      3828542.50     10506958.00      3828468.25     10506973.00
      3828444.50     10506869.00      3828299.50     10506790.00

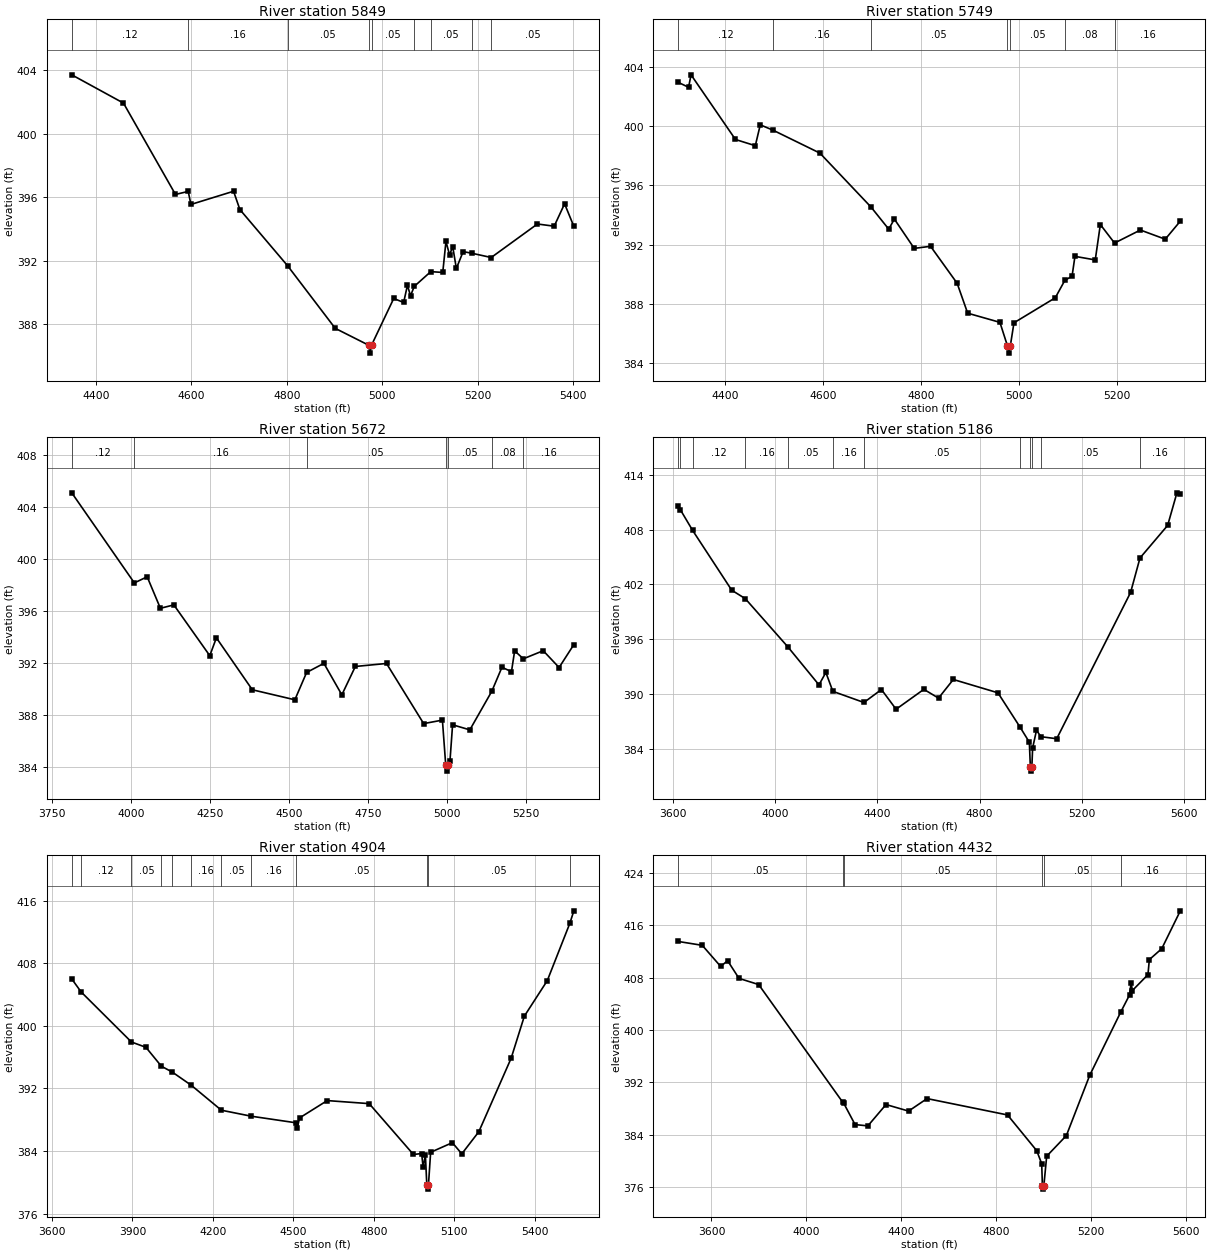
Type RM Length L Ch R = 1,5849,100,100,100
BEGIN DESCRIPTION:
UNT028 IN BECR 9.0
END DESCRIPTION:
XS GIS Cut Line= 4
      3828879.28     10511663.56      3828712.62     10511132.33
      3828573.73     10511017.75      3828365.39     10511253.86
#Sta/Elev= 30
  4349.7  403.71  4458.0  401.93  4566.9  396.18  4593.6  396.37  4599.3  395.55
  4688.6  396.38  4701.8  395.23  4801.8  391.69  4901.6  387.75  4971.6  386.69
  4974.4  386.19  4977.6  386.69  5024.1  389.63  5044.9  389.38  5052.8  390.46
  5059.3  389.80  5067.1  390.39  5101.7  391.32  5126.8  391.27  5133.5  393.22
  5141.0  392.38  5147.7  392.89  5155.3  391.52  5169.5  392.58  5187.5  392.48
  5228.3  392.21  5325.1  394.32  5360.2  394.18  5382.0  395.59  5401.4  394.17
#Mann=9,-1,0
  4349.7    0.12       0  4593.6    0.16       0  4801.8    0.05       0
  4971.6    0.03       0  4977.6    0.05       0  5067.1    0.08       0
  5101.7    0.05       0  5187.5    0.08       0  5228.3    0.05       0
Bank Sta=4971.6,4977.6
Exp/Cntr=0.3,0.1

Type RM Length L Ch R = 1,5749,77,77,77
BEGIN DESCRIPTION:
Mapping XS 40644237
END DESCRIPTION:
XS GIS Cut Line= 5
      3828938.31     10511625.38      3828851.51     10511121.91
      3828764.70     10511042.05      3828514.70     10510972.61
      3828379.27     10510996.91
#Sta/Elev= 30
  4303.6  402.97  4324.7  402.64  4329.8  403.48  4420.5  399.11  4461.1  398.69
  4471.2  400.10  4497.2  399.74  4593.0  398.19  4697.6  394.54  4733.7  393.05
  4745.2  393.73  4785.8  391.75  4819.2  391.89  4873.5  389.39  4895.0  387.37
  4960.9  386.75  4976.2  385.17  4979.0  384.67  4982.2  385.17  4989.6  386.72
  5074.0  388.41  5093.6  389.59  5108.3  389.87  5114.2  391.21  5155.7  390.97
  5166.1  393.36  5195.1  392.11  5247.9  392.99  5298.7  392.37  5329.5  393.59
#Mann=7,-1,0
  4303.6    0.12       0  4497.2    0.16       0  4697.6    0.05       0
  4976.2    0.03       0  4982.2    0.05       0  5093.6    0.08       0
  5195.1    0.16       0
Bank Sta=4976.2,4982.2
Exp/Cntr=0.3,0.1

Type RM Length L Ch R = 1,5672,486,486,486
BEGIN DESCRIPTION:
Mapping XS ee43614c
END DESCRIPTION:
XS GIS Cut Line= 4
      3829577.21     10511799.01      3828872.34     10511010.80
      3828653.59     10510941.36      3828353.08     10510968.99
#Sta/Elev= 30
  3812.7  405.07  4010.7  398.15  4051.3  398.62  4093.1  396.20  4135.7  396.46
  4249.4  392.56  4270.3  393.93  4384.0  389.94  4518.6  389.17  4555.8  391.27
  4610.5  391.97  4667.3  389.55  4710.0  391.73  4808.6  391.96  4926.2  387.34
  4985.5  387.61  4995.9  384.19  4998.6  383.69  5001.9  384.19  5009.4  384.46
  5017.7  387.25  5072.3  386.86  5141.9  389.83  5173.9  391.67  5204.0  391.33
  5214.1  392.93  5241.6  392.32  5304.5  392.94  5354.7  391.65  5401.4  393.41
#Mann=7,-1,0
  3812.7    0.12       0  4010.7    0.16       0  4555.8    0.05       0
  4995.9    0.03       0  5001.9    0.05       0  5141.9    0.08       0
  5241.6    0.16       0
Bank Sta=4995.9,5001.9
Exp/Cntr=0.3,0.1

Type RM Length L Ch R = 1,5186,282,282,282
BEGIN DESCRIPTION:
Mapping XS de3b96b6
END DESCRIPTION:
XS GIS Cut Line= 2
      3829716.07     10511864.93      3828647.60     10510213.67
#Sta/Elev= 30
  3619.5  410.55  3628.0  410.18  3675.9  407.92  3829.1  401.37  3882.0  400.45
  4049.3  395.15  4170.8  391.00  4197.8  392.36  4225.2  390.29  4346.9  389.07
  4415.5  390.49  4472.9  388.33  4581.7  390.51  4639.1  389.55  4697.1  391.59
  4871.9  390.13  4957.6  386.41  4994.9  384.72  4998.8  382.05  5001.6  381.55
  5004.8  382.05  5007.8  384.09  5022.9  386.02  5040.5  385.32  5102.1  385.10
  5391.6  401.13  5428.3  404.90  5536.7  408.47  5573.0  412.04  5586.3  411.93
#Mann=12,-1,0
  3619.5    0.12       0  3628.0    0.05       0  3675.9    0.12       0
  3882.0    0.16       0  4049.3    0.05       0  4225.2    0.16       0
  4346.9    0.05       0  4957.6    0.16       0  4998.8    0.07       0
  5004.8    0.16       0  5040.5    0.05       0  5428.3    0.16       0
Bank Sta=4998.8,5004.8
Exp/Cntr=0.3,0.1

Type RM Length L Ch R = 1,4904,472,472,472
BEGIN DESCRIPTION:
UNT028 IN BECR 8.0
END DESCRIPTION:
XS GIS Cut Line= 3
      3829749.62     10511760.21      3829149.61     10510560.19
      3828799.59     10510160.17
#Sta/Elev= 30
  3673.5  406.00  3708.4  404.34  3896.1  397.94  3950.2  397.26  4007.9  394.84
  4048.7  394.09  4119.7  392.40  4231.6  389.22  4343.4  388.45  4510.1  387.61
  4514.8  386.91  4523.2  388.23  4626.6  390.45  4783.2  390.06  4948.1  383.56
  4978.8  383.68  4984.4  381.91  4992.8  383.49  4998.2  379.63  5000.9  379.13
  5004.2  379.63  5012.4  383.84  5093.5  385.07  5128.6  383.64  5192.2  386.47
  5312.7  395.86  5362.1  401.25  5447.5  405.78  5531.8  413.12  5546.7  414.71
#Mann=12,-1,0
  3673.5    0.05       0  3708.4    0.12       0  3896.1    0.05       0
  4007.9    0.16       0  4048.7    0.05       0  4119.7    0.16       0
  4231.6    0.05       0  4343.4    0.16       0  4510.1    0.05       0
  4998.2    0.03       0  5004.2    0.05       0  5531.8    0.16       0
Bank Sta=4998.2,5004.2
Exp/Cntr=0.3,0.1

Type RM Length L Ch R = 1,4432,485,485,485
BEGIN DESCRIPTION:
UNT028 IN BECR 7.0
END DESCRIPTION:
XS GIS Cut Line= 4
      3830719.60     10510257.31      3829916.89     10510585.65
      3829302.89     10510174.00      3828814.78     10510025.14
#Sta/Elev= 30
  3459.9  413.51  3561.2  412.92  3638.7  409.70  3668.1  410.57  3716.1  407.87
  3798.9  406.93  4152.9  388.98  4158.1  388.77  4205.4  385.54  4259.4  385.34
  4335.9  388.60  4431.0  387.60  4509.0  389.51  4848.2  387.01  4971.2  381.56
  4992.3  379.56  4995.3  376.18  4998.0  375.68  5001.3  376.18  5013.3  380.71
  5096.3  383.86  5194.7  393.06  5324.6  402.66  5362.6  405.34  5369.3  407.23
  5374.5  406.01  5440.2  408.44  5446.2  410.74  5498.5  412.41  5576.7  418.19
#Mann=6,-1,0
  3459.9    0.05       0  4152.9    0.16       0  4158.1    0.05       0
  4995.3    0.03       0  5001.3    0.05       0  5324.6    0.16       0
Bank Sta=4995.3,5001.3
Exp/Cntr=0.3,0.1

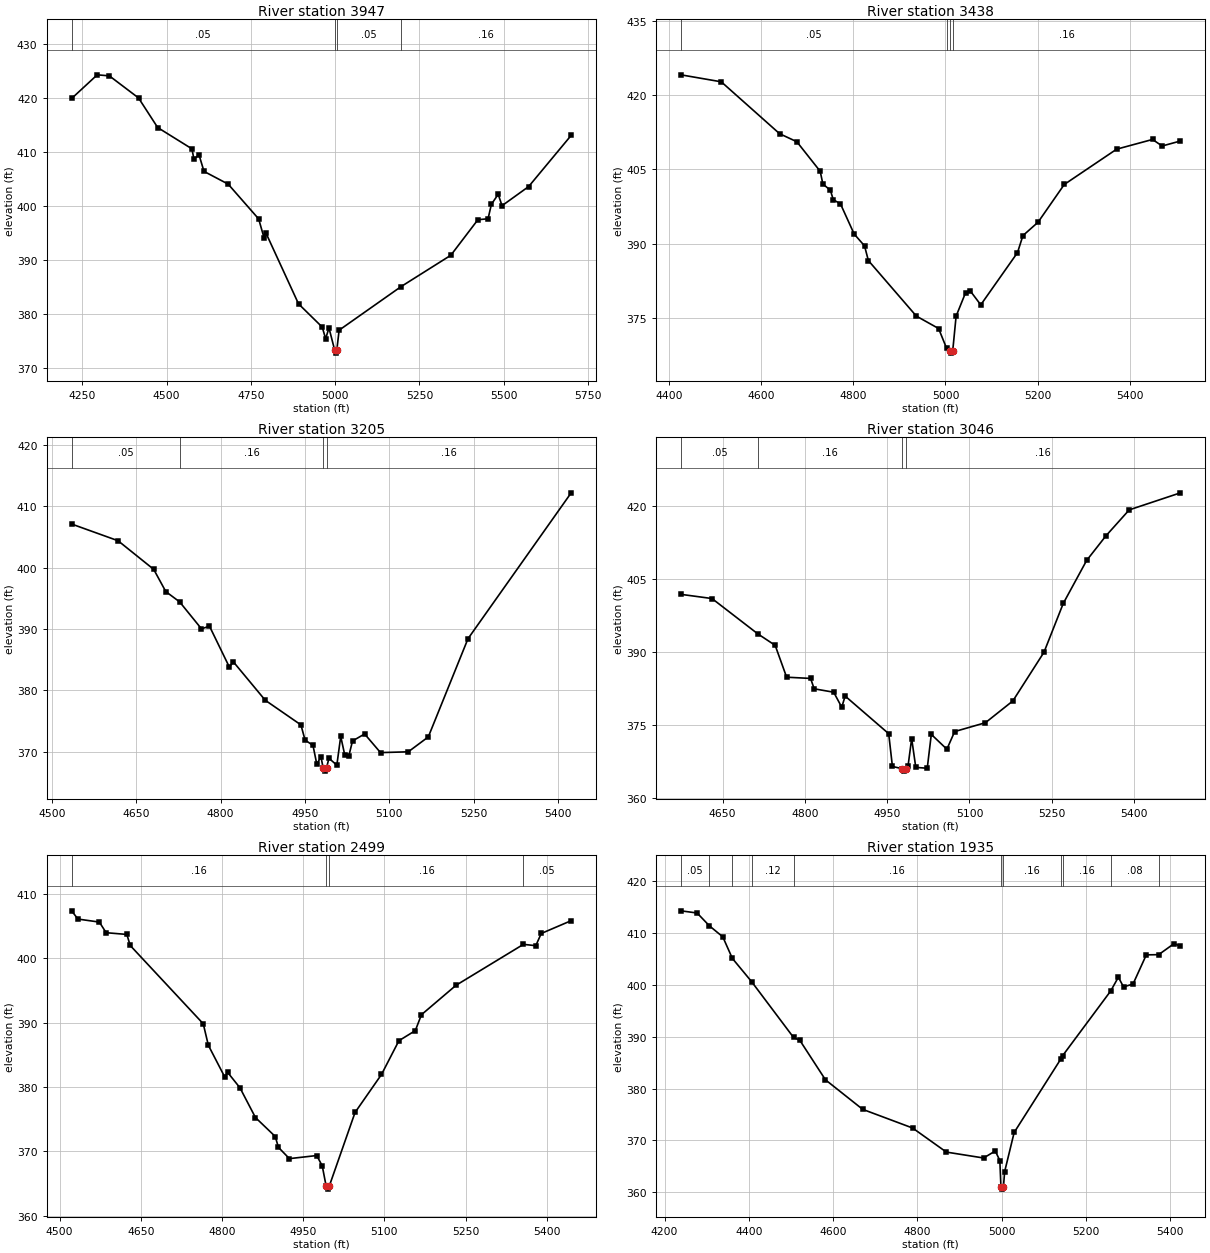
Type RM Length L Ch R = 1,3947,509,509,509
BEGIN DESCRIPTION:
UNT028 IN BECR 6.0
END DESCRIPTION:
XS GIS Cut Line= 3
      3830275.15     10509510.77      3829820.26     10509823.30
      3828893.90     10509903.10
#Sta/Elev= 30
  4218.5  419.85  4294.4  424.23  4330.3  424.04  4416.9  419.95  4473.7  414.47
  4575.2  410.53  4581.3  408.61  4596.2  409.43  4611.1  406.35  4682.8  403.99
  4773.2  397.55  4789.3  394.03  4794.3  395.01  4891.5  381.82  4961.8  377.52
  4971.8  375.37  4981.8  377.36  4998.9  373.20  5001.7  372.70  5004.9  373.20
  5011.9  376.95  5195.9  385.03  5343.2  390.82  5423.5  397.40  5453.6  397.58
  5463.6  400.26  5483.7  402.11  5495.1  400.00  5574.0  403.54  5700.2  413.02
#Mann=4,-1,0
  4218.5    0.05       0  4998.9    0.03       0  5004.9    0.05       0
  5195.9    0.16       0
Bank Sta=4998.9,5004.9
Exp/Cntr=0.3,0.1

Type RM Length L Ch R = 1,3438,233,233,233
BEGIN DESCRIPTION:
UNT028 IN BECR 5.0
END DESCRIPTION:
XS GIS Cut Line= 4
      3829952.22     10509184.40      3829563.31     10509389.27
      3829249.61     10509460.19      3829007.76     10509673.99
#Sta/Elev= 30
  4425.9  424.06  4513.5  422.65  4640.1  412.17  4677.5  410.55  4728.2  404.58
  4734.0  402.01  4750.2  400.77  4756.6  398.85  4772.2  398.00  4801.8  391.93
  4824.4  389.52  4832.7  386.56  4936.8  375.35  4985.1  372.84  5002.3  368.88
  5009.8  368.37  5012.6  367.87  5015.8  368.37  5023.1  375.33  5043.6  380.06
  5053.8  380.43  5076.6  377.62  5156.3  388.16  5168.1  391.60  5200.9  394.30
  5257.8  401.92  5371.5  409.05  5449.3  411.01  5470.2  409.69  5509.9  410.70
#Mann=4,-1,0
  4425.9    0.05       0  5002.3    0.16       0  5009.8    0.03       0
  5015.8    0.16       0
Bank Sta=5009.8,5015.8
Exp/Cntr=0.3,0.1

Type RM Length L Ch R = 1,3205,159,159,159
BEGIN DESCRIPTION:
Mapping XS ff460bcf
END DESCRIPTION:
XS GIS Cut Line= 2
      3829681.40     10508875.35      3829074.16     10509524.23
#Sta/Elev= 30
  4535.0  407.09  4617.5  404.37  4681.0  399.70  4702.5  396.08  4727.1  394.40
  4766.0  390.00  4780.2  390.44  4815.5  383.78  4822.7  384.62  4879.4  378.36
  4942.9  374.34  4950.2  371.88  4964.4  370.98  4971.2  367.90  4978.5  369.18
  4982.4  367.30  4985.1  366.80  4988.4  367.30  4992.7  368.90  5006.8  367.77
  5013.7  372.46  5021.0  369.38  5027.9  369.21  5034.7  371.72  5056.2  372.86
  5084.5  369.82  5133.9  369.95  5169.5  372.38  5240.1  388.39  5423.7  412.18
#Mann=4,-1,0
  4535.0    0.05       0  4727.1    0.16       0  4982.4    0.07       0
  4988.4    0.16       0
Bank Sta=4982.4,4988.4
Exp/Cntr=0.3,0.1

Type RM Length L Ch R = 1,3046,547,547,547
BEGIN DESCRIPTION:
UNT028 IN BECR 4.0
END DESCRIPTION:
XS GIS Cut Line= 3
      3829591.08     10508882.33      3829313.31     10509083.72
      3828931.36     10509503.86
#Sta/Elev= 30
  4573.8  401.78  4630.5  400.92  4713.9  393.68  4745.7  391.31  4766.6  384.77
  4810.3  384.52  4816.8  382.39  4852.4  381.69  4867.1  378.61  4873.3  380.90
  4952.7  373.18  4959.5  366.45  4977.4  365.99  4980.2  365.49  4983.4  365.99
  4987.9  366.47  4994.6  372.17  5002.1  366.26  5023.0  366.08  5030.4  373.03
  5058.8  369.99  5073.0  373.61  5129.1  375.43  5179.1  379.90  5235.9  389.90
  5271.0  399.91  5313.6  408.73  5348.7  413.77  5391.3  419.12  5484.7  422.62
#Mann=4,-1,0
  4573.8    0.05       0  4713.9    0.16       0  4977.4    0.07       0
  4983.4    0.16       0
Bank Sta=4977.4,4983.4
Exp/Cntr=0.3,0.1

Type RM Length L Ch R = 1,2499,564,564,564
BEGIN DESCRIPTION:
UNT028 IN BECR 3.0
END DESCRIPTION:
XS GIS Cut Line= 3
      3829486.93     10508601.07      3829177.89     10508750.38
      3828604.95     10508837.19
#Sta/Elev= 30
  4522.3  407.40  4533.9  406.12  4573.5  405.65  4586.0  404.00  4624.3  403.73
  4630.4  402.02  4765.4  389.84  4774.8  386.50  4805.1  381.57  4810.6  382.27
  4833.2  379.89  4861.8  375.27  4898.4  372.32  4904.2  370.64  4924.5  368.88
  4975.0  369.36  4985.2  367.75  4992.3  364.64  4995.0  364.14  4998.3  364.64
  5045.8  376.06  5094.6  381.96  5126.8  387.21  5157.1  388.78  5168.4  391.25
  5232.2  395.82  5356.8  402.19  5379.6  401.98  5389.7  403.88  5445.0  405.87
#Mann=4,-1,0
  4522.3    0.16       0  4992.3    0.07       0  4998.3    0.16       0
  5356.8    0.05       0
Bank Sta=4992.3,4998.3
Exp/Cntr=0.3,0.1

Type RM Length L Ch R = 1,1935,308,308,308
BEGIN DESCRIPTION:
UNT028 IN BECR 2.0
END DESCRIPTION:
XS GIS Cut Line= 3
      3829667.49     10508340.67      3829098.03     10508239.97
      3828559.88     10508521.19
#Sta/Elev= 30
  4238.9  414.31  4277.4  413.89  4306.7  411.40  4338.3  409.29  4361.0  405.13
  4406.5  400.66  4506.2  389.87  4521.1  389.32  4582.0  381.69  4670.3  375.99
  4788.7  372.39  4868.9  367.74  4957.2  366.60  4985.0  367.95  4995.8  366.11
  4998.4  361.09  5001.1  360.59  5004.4  361.09  5007.2  363.96  5029.8  371.53
  5140.0  385.64  5145.1  386.38  5258.9  398.84  5277.1  401.50  5289.3  399.63
  5311.9  400.18  5343.4  405.81  5372.7  405.85  5409.6  408.00  5424.4  407.45
#Mann=11,-1,0
  4238.9    0.05       0  4306.7    0.16       0  4361.0    0.05       0
  4406.5    0.12       0  4506.2    0.16       0  4998.4    0.07       0
  5004.4    0.16       0  5140.0    0.12       0  5145.1    0.16       0
  5258.9    0.08       0  5372.7    0.05       0
Bank Sta=4998.4,5004.4
Exp/Cntr=0.3,0.1

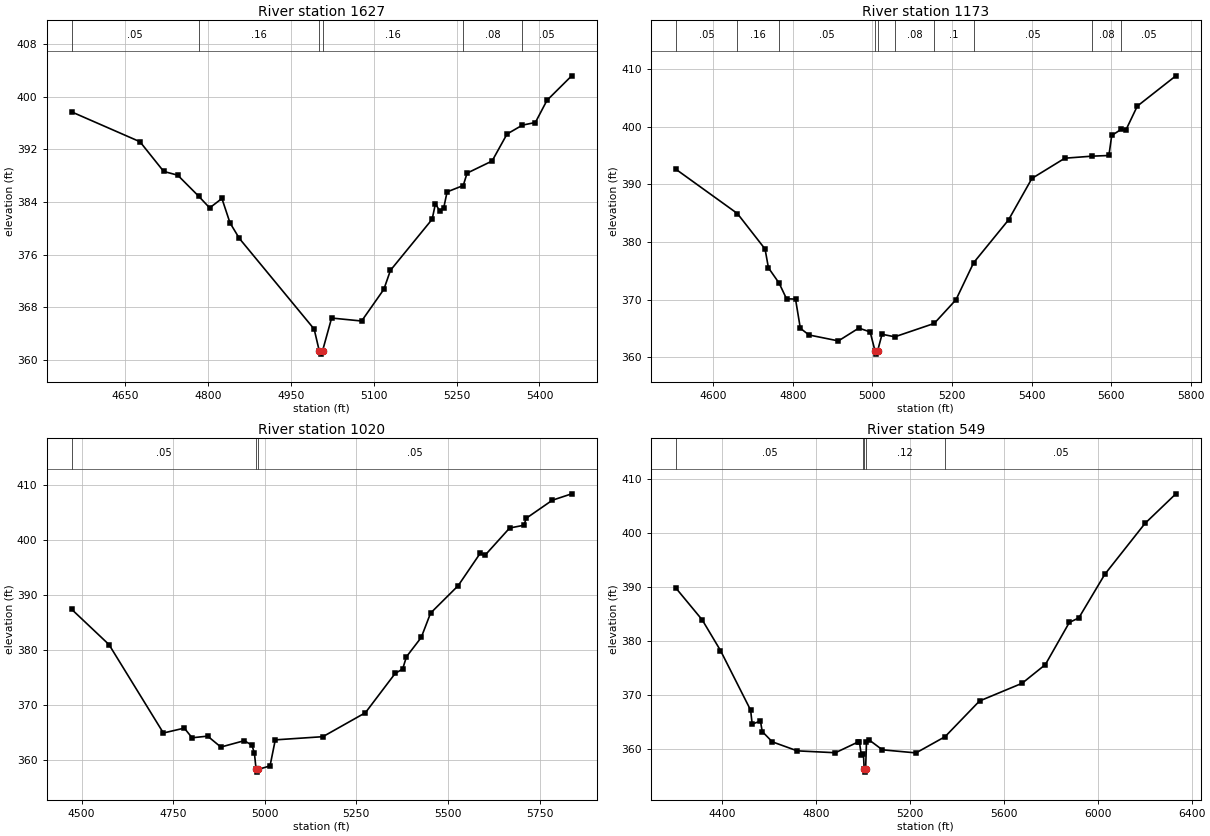
Type RM Length L Ch R = 1,1627,454,454,454
BEGIN DESCRIPTION:
Mapping XS d0aa87b3
END DESCRIPTION:
XS GIS Cut Line= 3
      3829337.71     10507904.49      3828785.65     10508089.38
      3828608.56     10508360.23
#Sta/Elev= 30
  4552.5  397.68  4676.2  393.15  4719.2  388.64  4744.6  388.07  4782.3  384.90
  4802.5  383.10  4824.7  384.53  4839.3  380.83  4856.3  378.46  4991.8  364.69
  5001.0  361.39  5003.7  360.89  5007.0  361.39  5023.4  366.37  5077.8  365.92
  5118.1  370.74  5130.0  373.62  5205.5  381.37  5211.5  383.73  5219.3  382.63
  5226.6  383.14  5232.6  385.53  5261.9  386.50  5268.8  388.38  5314.1  390.22
  5341.2  394.32  5369.0  395.67  5392.5  396.07  5413.6  399.44  5458.3  403.16
#Mann=6,-1,0
  4552.5    0.05       0  4782.3    0.16       0  5001.0    0.07       0
  5007.0    0.16       0  5261.9    0.08       0  5369.0    0.05       0
Bank Sta=5001,5007
Exp/Cntr=0.3,0.1

Type RM Length L Ch R = 1,1173,153,153,153
BEGIN DESCRIPTION:
Mapping XS f05b375e
END DESCRIPTION:
XS GIS Cut Line= 6
      3829121.61     10507646.68      3828827.32     10507506.05
      3828717.94     10507688.34      3828652.84     10508050.32
      3828660.65     10508203.96      3828507.02     10508323.75
#Sta/Elev= 30
  4506.6  392.60  4661.0  384.93  4730.5  378.78  4739.0  375.52  4765.7  372.88
  4784.4  370.16  4807.0  370.10  4819.1  365.05  4840.7  363.89  4914.6  362.86
  4965.9  365.08  4994.3  364.42  5006.8  361.07  5009.6  360.57  5012.8  361.07
  5024.2  364.01  5056.2  363.57  5155.2  365.89  5209.8  369.99  5254.2  376.41
  5341.7  383.82  5400.5  391.01  5483.1  394.51  5550.5  394.86  5593.7  394.98
  5600.8  398.45  5624.2  399.49  5636.0  399.34  5665.0  403.53  5761.8  408.78
#Mann=10,-1,0
  4506.6    0.05       0  4661.0    0.16       0  4765.7    0.05       0
  5006.8    0.04       0  5012.8    0.05       0  5056.2    0.08       0
  5155.2     0.1       0  5254.2    0.05       0  5550.5    0.08       0
  5624.2    0.05       0
Bank Sta=5006.8,5012.8
Exp/Cntr=0.3,0.1

Type RM Length L Ch R = 1,1020,471,471,471
BEGIN DESCRIPTION:
Mapping XS feac3aaa
END DESCRIPTION:
XS GIS Cut Line= 6
      3829103.38     10507550.34      3828905.44     10507349.80
      3828676.28     10507542.51      3828572.11     10507925.32
      3828592.94     10508167.51      3828496.57     10508271.69
#Sta/Elev= 30
  4473.0  387.40  4574.8  380.98  4723.3  364.86  4780.3  365.75  4801.7  363.99
  4844.1  364.29  4880.2  362.30  4944.1  363.46  4965.0  362.63  4971.8  361.17
  4976.3  358.23  4979.0  357.73  4982.3  358.23  5014.4  358.87  5028.7  363.61
  5158.6  364.19  5274.7  368.56  5355.9  375.72  5376.3  376.52  5386.7  378.76
  5427.1  382.28  5452.5  386.71  5527.7  391.70  5588.0  397.62  5600.7  397.22
  5668.3  402.22  5707.0  402.72  5713.9  404.01  5784.7  407.28  5837.6  408.45
#Mann=3,-1,0
  4473.0    0.05       0  4976.3    0.04       0  4982.3    0.05       0
Bank Sta=4976.3,4982.3
Exp/Cntr=0.3,0.1

Type RM Length L Ch R = 1,549,0,0,0
BEGIN DESCRIPTION:
UNT028 IN BECR 1.0
END DESCRIPTION:
XS GIS Cut Line= 4
      3829186.66     10507581.54      3828723.03     10507045.52
      3828414.01     10507187.88      3828292.48     10508260.77
#Sta/Elev= 30
  4204.1  389.73  4316.3  383.83  4394.1  378.16  4522.4  367.12  4529.0  364.52
  4564.2  365.11  4571.8  363.16  4614.6  361.25  4720.9  359.58  4883.3  359.23
  4980.4  361.23  4985.9  361.17  4993.6  358.77  5002.8  358.94  5005.9  356.14
  5008.6  355.64  5011.9  356.14  5015.7  361.18  5026.3  361.62  5083.3  359.77
  5226.5  359.20  5350.2  362.20  5496.9  368.81  5678.1  372.09  5777.2  375.55
  5879.3  383.36  5919.6  384.19  6030.3  392.27  6201.4  401.69  6332.8  407.17
#Mann=5,-1,0
  4204.1    0.05       0  5002.8    0.12       0  5005.9    0.03       0
  5011.9    0.12       0  5350.2    0.05       0
Bank Sta=5005.9,5011.9
Exp/Cntr=0.3,0.1

Chan Stop Cuts=-1