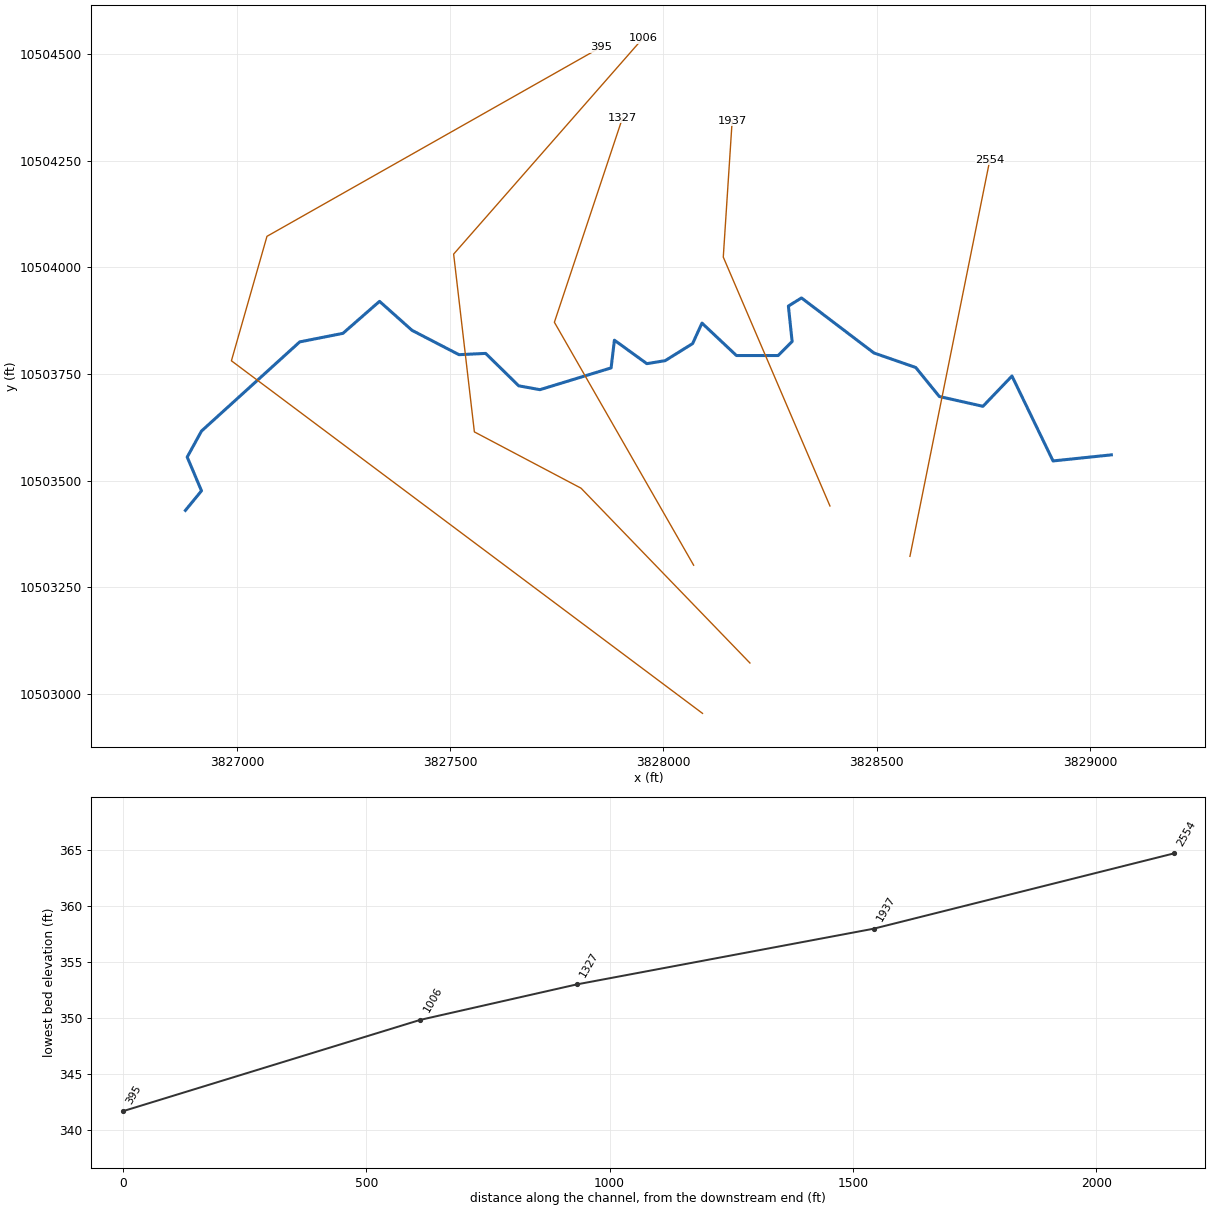
--- UNT030 IN BECR.prj (project) ---

Proj Title=UNT030 IN BECR Base Level Engineering
Current Plan=p01
Default Exp/Contr=0.3,0.1
English Units
Geom File=g01
Flow File=f01
Plan File=p01
BEGIN DESCRIPTION:
UNT030 IN BECR
END DESCRIPTION:

--- UNT030 IN BECR.p01 (plan) ---

Plan Title=Multiple Run
Short Identifier=Multiple
Geom File=g01
Flow File=f01
Subcritical Flow
K Sum by GR= 0
Std Step Tol= 0.01
Critical Tol= 0.01
Num of Std Step Trials= 20
Max Error Tol= 0.3
Flow Tol Ratio= 0.001
Split Flow NTrial= 30
Split Flow Tol= 0.02
Split Flow Ratio= 0.02
Log Output Level= 0
Friction Slope Method= 1
Unsteady Friction Slope Method= 2
Unsteady Bridges Friction Slope Method= 1
Parabolic Critical Depth
Global Vel Dist=  1 , 1 , 1
Global Log Level= 0
CheckData=True
Encroach Param= -1, 0, 0, 0
BEGIN DESCRIPTION:
Multiple Run
END DESCRIPTION:

--- UNT030 IN BECR.f01 (steady flow) ---

Flow Title=Multiple
Number of Profiles=7
Profile Names=10-year,25-year,50-year,1pct_min,100-year,1pct_plu,500-year
River Rch & RM= UNT030 IN BECR,Reach-1,2554
     249     317     371     319     432     584     588
Boundary for River Rch & Prof#=UNT030 IN BECR,Reach-1,1
Up Type=0
Dn Type=3
Dn Slope=0.005
Boundary for River Rch & Prof#=UNT030 IN BECR,Reach-1,2
Up Type=0
Dn Type=3
Dn Slope=0.005
Boundary for River Rch & Prof#=UNT030 IN BECR,Reach-1,3
Up Type=0
Dn Type=3
Dn Slope=0.005
Boundary for River Rch & Prof#=UNT030 IN BECR,Reach-1,4
Up Type=0
Dn Type=3
Dn Slope=0.005
Boundary for River Rch & Prof#=UNT030 IN BECR,Reach-1,5
Up Type=0
Dn Type=3
Dn Slope=0.005
Boundary for River Rch & Prof#=UNT030 IN BECR,Reach-1,6
Up Type=0
Dn Type=3
Dn Slope=0.005
Boundary for River Rch & Prof#=UNT030 IN BECR,Reach-1,7
Up Type=0
Dn Type=3
Dn Slope=0.005

--- UNT030 IN BECR.g01 (geometry) ---

Geom Title=Existing Conditions

River Reach=UNT030 IN BECR,Reach-1
Reach XY= 30
      3829049.61     10503560.19      3828913.00     10503546.00
      3828816.75     10503745.00      3828748.75     10503674.00
      3828646.50     10503697.00      3828591.25     10503765.00
      3828493.25     10503799.00      3828323.50     10503928.00
      3828292.75     10503909.00      3828301.50     10503826.00
      3828268.75     10503793.00      3828171.00     10503793.00
      3828090.25     10503869.00      3828068.25     10503821.00
      3828004.00     10503781.00      3827961.00     10503774.00
      3827885.00     10503829.00      3827877.25     10503764.00
      3827710.50     10503713.00      3827660.75     10503722.00
      3827583.25     10503798.00      3827520.75     10503795.00
      3827410.75     10503852.00      3827334.50     10503920.00
      3827248.75     10503845.00      3827147.50     10503825.00
      3826917.25     10503616.00      3826883.75     10503555.00
      3826917.25     10503476.00      3826879.50     10503430.00

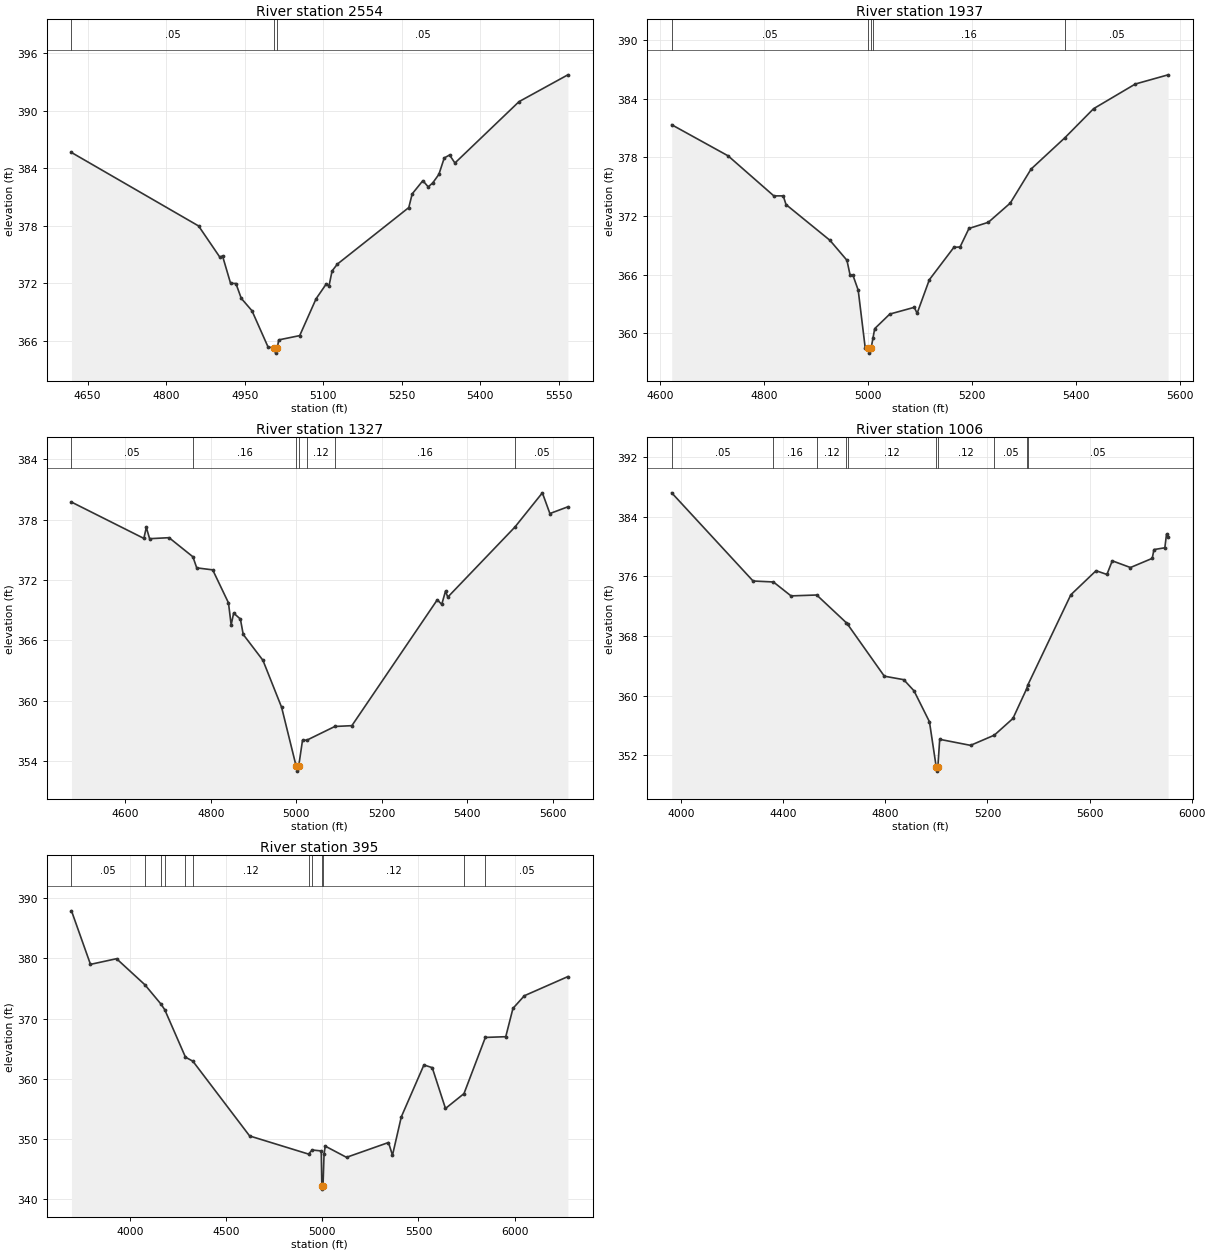
Type RM Length L Ch R = 1,2554,617,617,617
BEGIN DESCRIPTION:
UNT030 IN BECR 5.0
END DESCRIPTION:
XS GIS Cut Line= 2
      3828577.65     10503322.40      3828764.89     10504251.63
#Sta/Elev= 30
  4619.1  385.65  4861.8  377.98  4902.4  374.72  4907.5  374.85  4922.9  371.99
  4933.1  371.97  4943.3  370.42  4963.7  369.13  4994.3  365.36  5006.1  365.20
  5008.9  364.70  5012.1  365.20  5014.7  366.08  5054.9  366.53  5086.1  370.37
  5105.7  371.93  5110.8  371.70  5116.7  373.28  5126.9  374.00  5263.2  379.90
  5269.7  381.33  5290.1  382.71  5300.3  382.06  5308.9  382.47  5320.7  383.37
  5330.9  385.08  5341.1  385.39  5351.3  384.55  5473.7  390.96  5567.0  393.76
#Mann=3,-1,0
  4619.1    0.05       0  5006.1    0.03       0  5012.1    0.05       0
Bank Sta=5006.1,5012.1
Exp/Cntr=0.3,0.1

Type RM Length L Ch R = 1,1937,610,610,610
BEGIN DESCRIPTION:
UNT030 IN BECR 4.0
END DESCRIPTION:
XS GIS Cut Line= 3
      3828390.14     10503440.46      3828140.15     10504023.76
      3828160.98     10504343.17
#Sta/Elev= 30
  4622.0  381.32  4730.5  378.14  4818.4  374.05  4836.5  374.05  4841.9  373.16
  4926.3  369.51  4959.0  367.47  4965.2  365.93  4970.7  365.92  4980.7  364.41
  4994.2  358.50  4999.5  358.48  5002.2  357.98  5005.5  358.48  5009.0  359.49
  5012.4  360.48  5041.4  361.97  5088.5  362.66  5094.0  362.05  5117.5  365.48
  5164.7  368.79  5176.6  368.83  5193.7  370.72  5231.0  371.35  5273.1  373.31
  5313.2  376.79  5378.2  379.99  5433.4  382.96  5513.6  385.48  5576.7  386.42
#Mann=5,-1,0
  4622.0    0.05       0  4999.5    0.03       0  5005.5    0.05       0
  5009.0    0.16       0  5378.2    0.05       0
Bank Sta=4999.5,5005.5
Exp/Cntr=0.3,0.1

Type RM Length L Ch R = 1,1327,321,321,321
BEGIN DESCRIPTION:
UNT030 IN BECR 3.0
END DESCRIPTION:
XS GIS Cut Line= 3
      3828070.69     10503301.56      3827744.31     10503870.99
      3827904.03     10504350.14
#Sta/Elev= 30
  4474.3  379.76  4643.6  376.15  4649.4  377.24  4657.1  376.12  4702.6  376.22
  4758.4  374.32  4767.3  373.22  4804.7  373.02  4841.6  369.74  4847.9  367.55
  4853.7  368.72  4869.5  368.13  4876.1  366.60  4922.2  364.03  4965.9  359.36
  4999.9  353.51  5002.7  353.01  5005.9  353.51  5014.8  356.07  5025.5  356.10
  5090.5  357.45  5130.3  357.53  5330.1  370.04  5340.6  369.59  5349.4  370.91
  5354.7  370.31  5511.6  377.27  5576.0  380.68  5593.6  378.62  5635.7  379.29
#Mann=7,-1,0
  4474.3    0.05       0  4758.4    0.16       0  4999.9    0.07       0
  5005.9    0.16       0  5025.5    0.12       0  5090.5    0.16       0
  5511.6    0.05       0
Bank Sta=4999.9,5005.9
Exp/Cntr=0.3,0.1

Type RM Length L Ch R = 1,1006,611,611,611
BEGIN DESCRIPTION:
UNT030 IN BECR 2.0
END DESCRIPTION:
XS GIS Cut Line= 5
      3828202.63     10503072.39      3827806.81     10503482.10
      3827556.81     10503614.04      3827508.20     10504030.71
      3827951.57     10504536.43
#Sta/Elev= 30
  3963.3  387.22  4282.0  375.38  4361.7  375.25  4430.7  373.38  4531.3  373.50
  4647.2  369.78  4652.3  369.57  4796.1  362.60  4872.2  362.13  4912.5  360.63
  4972.9  356.48  4999.7  350.35  5002.4  349.85  5005.7  350.35  5013.1  354.12
  5133.9  353.31  5227.0  354.68  5299.9  356.92  5353.1  360.87  5359.0  361.47
  5526.7  373.53  5625.4  376.76  5668.1  376.26  5689.0  378.09  5760.2  377.19
  5845.6  378.42  5852.2  379.60  5894.9  379.84  5901.6  381.69  5907.7  381.24
#Mann=10,-1,0
  3963.3    0.05       0  4361.7    0.16       0  4531.3    0.12       0
  4647.2    0.16       0  4652.3    0.12       0  4999.7    0.07       0
  5005.7    0.12       0  5227.0    0.05       0  5353.1    0.12       0
  5359.0    0.05       0
Bank Sta=4999.7,5005.7
Exp/Cntr=0.3,0.1

Type RM Length L Ch R = 1,395,0,0,0
BEGIN DESCRIPTION:
UNT030 IN BECR 1.0
END DESCRIPTION:
XS GIS Cut Line= 4
      3828091.51     10502954.34      3826987.37     10503780.71
      3827070.70     10504072.37      3827853.58     10504515.77
#Sta/Elev= 30
  3694.9  387.91  3793.7  379.02  3929.2  379.96  4076.6  375.64  4160.8  372.41
  4180.2  371.48  4287.9  363.61  4326.4  362.94  4621.6  350.53  4927.9  347.52
  4946.9  348.20  4994.1  348.04  4997.3  342.20  5000.1  341.70  5003.3  342.20
  5008.7  347.54  5014.9  348.84  5125.5  346.98  5343.9  349.44  5364.7  347.33
  5410.6  353.70  5528.2  362.32  5571.5  361.87  5640.4  355.09  5736.6  357.56
  5847.8  366.89  5953.9  367.01  5991.4  371.71  6050.6  373.81  6277.1  376.99
#Mann=12,-1,0
  3694.9    0.05       0  4076.6    0.16       0  4160.8    0.12       0
  4180.2    0.16       0  4287.9     0.1       0  4326.4    0.12       0
  4927.9    0.16       0  4946.9    0.12       0  4997.3    0.07       0
  5003.3    0.12       0  5736.6     0.1       0  5847.8    0.05       0
Bank Sta=4997.3,5003.3
Exp/Cntr=0.3,0.1

Chan Stop Cuts=-1