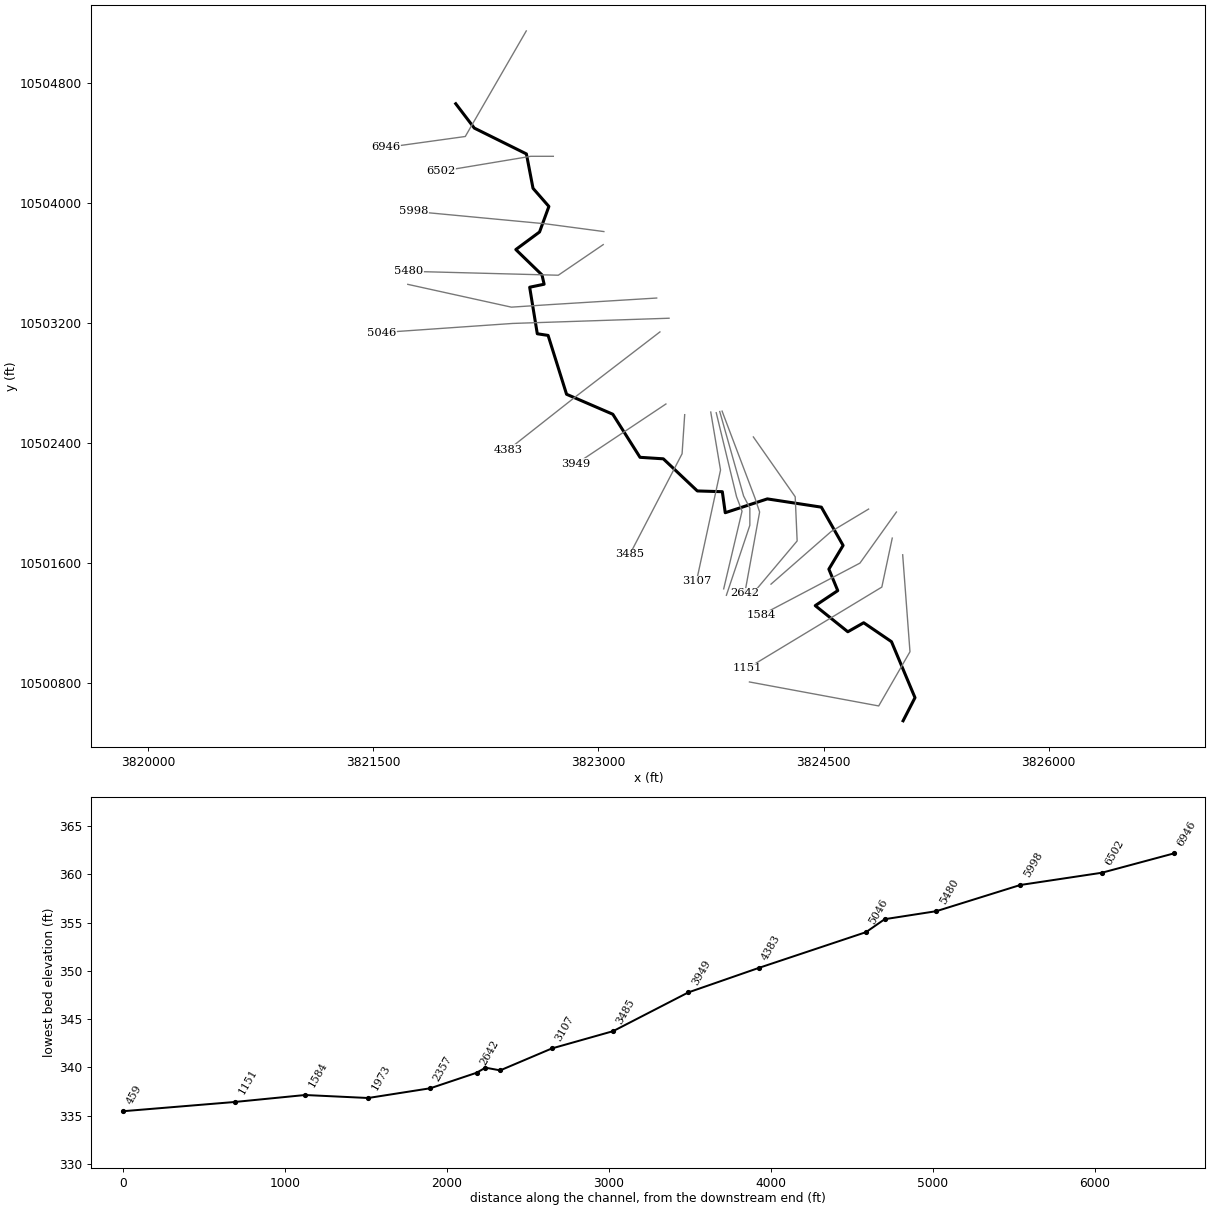
--- UNT031 IN BECR.prj (project) ---

Proj Title=UNT031 IN BECR Base Level Engineering
Current Plan=p01
Default Exp/Contr=0.3,0.1
English Units
Geom File=g01
Flow File=f01
Plan File=p01
Y Axis Title=Elevation
X Axis Title(PF)=Main Channel Distance
X Axis Title(XS)=Station
BEGIN DESCRIPTION:
UNT031 IN BECR
END DESCRIPTION:
DSS Export Rating Curves= 0
DSS Export Rating Curve Sorted= 0
DSS Export Volume Flow Curves= 0
DXF OffsetX= 0
DXF OffsetY= 0
DXF ScaleX= 1
DXF ScaleY= 10

--- UNT031 IN BECR.p01 (plan) ---

Plan Title=Multiple Run
Short Identifier=Multiple
Geom File=g01
Flow File=f01
Subcritical Flow
K Sum by GR= 0
Std Step Tol= 0.01
Critical Tol= 0.01
Num of Std Step Trials= 20
Max Error Tol= 0.3
Flow Tol Ratio= 0.001
Split Flow NTrial= 30
Split Flow Tol= 0.02
Split Flow Ratio= 0.02
Log Output Level= 0
Friction Slope Method= 1
Unsteady Friction Slope Method= 2
Unsteady Bridges Friction Slope Method= 1
Parabolic Critical Depth
Global Vel Dist=  1 , 1 , 1
Global Log Level= 0
CheckData=True
Encroach Param= -1, 0, 0, 0
BEGIN DESCRIPTION:
Multiple Run
END DESCRIPTION:

--- UNT031 IN BECR.f01 (steady flow) ---

Flow Title=Multiple
Program Version=4.10
Number of Profiles= 7
Profile Names=10-year,25-year,50-year,1pct_min,100-year,1pct_plu,500-year
River Rch & RM=UNT031 IN BECR,Reach-1         ,6946
     494     655     786     693     937    1267    1336
River Rch & RM=UNT031 IN BECR,Reach-1         ,5480
     567     758     914     809    1095    1481    1575
River Rch & RM=UNT031 IN BECR,Reach-1         ,1973
     821    1119    1367    1225    1656    2240    2442
Boundary for River Rch & Prof#=UNT031 IN BECR,Reach-1         , 1
Up Type= 0
Dn Type= 3
Dn Slope=0.0025
Boundary for River Rch & Prof#=UNT031 IN BECR,Reach-1         , 2
Up Type= 0
Dn Type= 3
Dn Slope=0.0025
Boundary for River Rch & Prof#=UNT031 IN BECR,Reach-1         , 3
Up Type= 0
Dn Type= 3
Dn Slope=0.0025
Boundary for River Rch & Prof#=UNT031 IN BECR,Reach-1         , 4
Up Type= 0
Dn Type= 3
Dn Slope=0.0025
Boundary for River Rch & Prof#=UNT031 IN BECR,Reach-1         , 5
Up Type= 0
Dn Type= 3
Dn Slope=0.0025
Boundary for River Rch & Prof#=UNT031 IN BECR,Reach-1         , 6
Up Type= 0
Dn Type= 3
Dn Slope=0.0025
Boundary for River Rch & Prof#=UNT031 IN BECR,Reach-1         , 7
Up Type= 0
Dn Type= 3
Dn Slope=0.0025
DSS Import GetInterval= 0
DSS Import GetPeak= 0
DSS Import FillOption= 0

--- UNT031 IN BECR.g01 (geometry) ---

Geom Title=Existing Conditions
Program Version=4.10

River Reach=UNT031 IN BECR  ,Reach-1
Reach XY= 30
      3822049.61     10504660.19      3822173.25       10504498.
      3822520.25       10504326.      3822564.25       10504097.
        3822670.       10503976.      3822607.75       10503806.
      3822449.75       10503689.        3822624.       10503520.
      3822638.25       10503458.        3822542.       10503438.
      3822592.75       10503128.      3822664.75       10503117.
      3822787.75       10502725.      3823095.75       10502592.
        3823277.       10502305.      3823432.25       10502295.
      3823658.75       10502081.      3823825.25       10502076.
      3823844.75       10501936.        3824125.       10502028.
        3824485.       10501973.      3824629.75       10501718.
        3824535.       10501560.      3824594.25       10501417.
      3824444.25       10501317.      3824661.25       10501143.
        3824767.       10501203.        3824952.       10501077.
      3825108.75       10500704.       3825029.5       10500550.

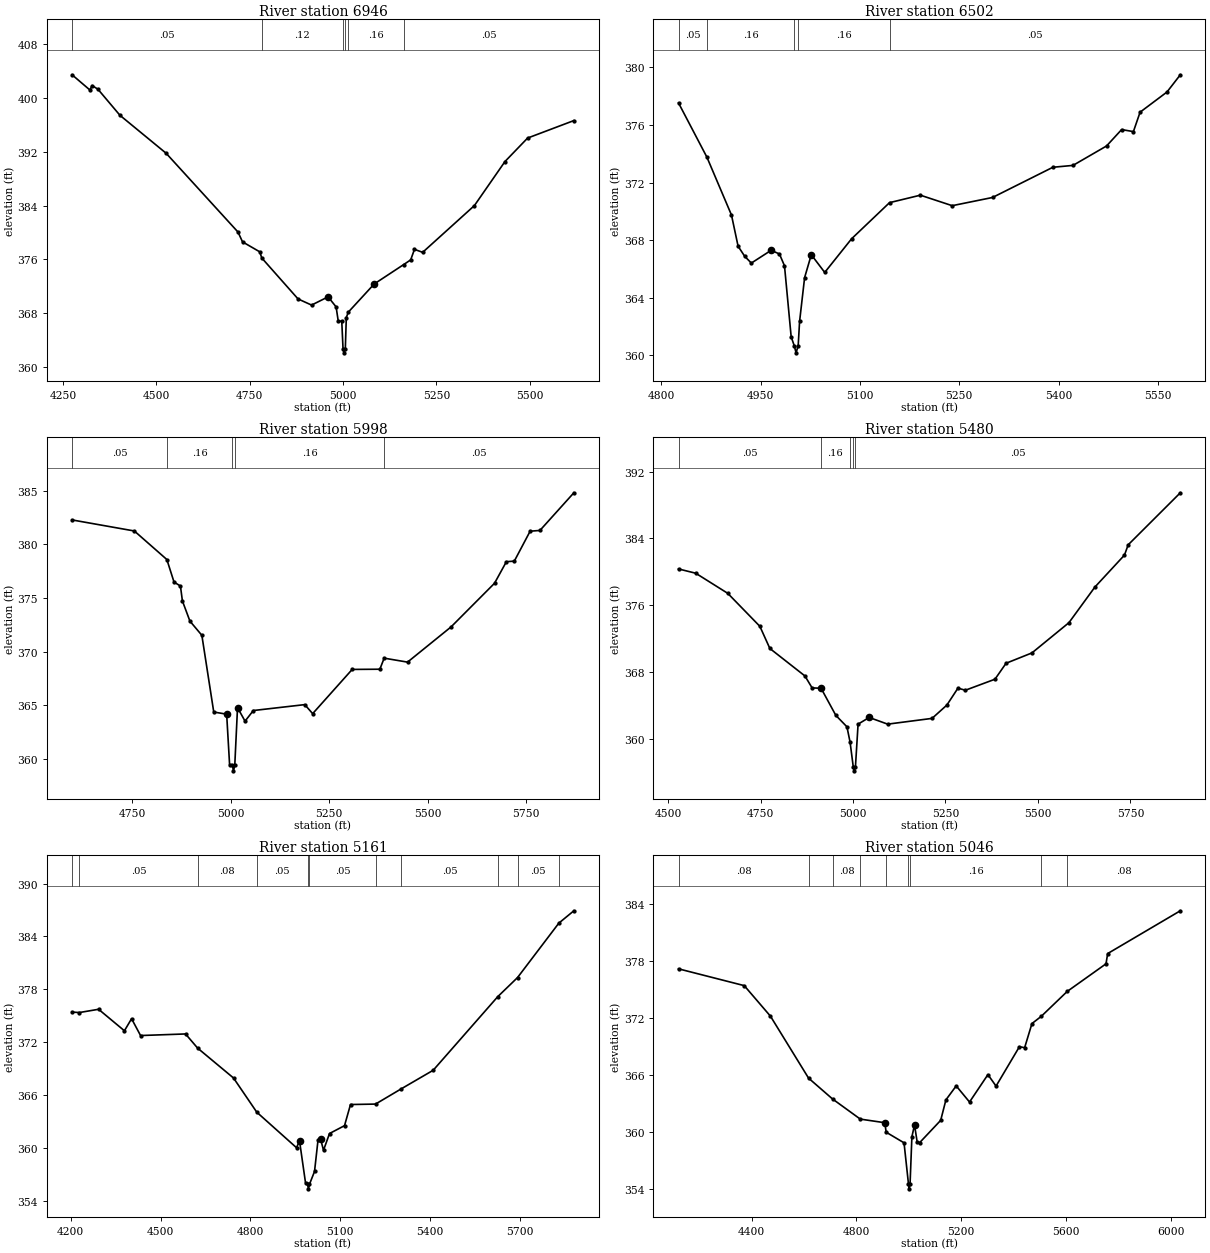
Type RM Length L Ch R = 1 ,6946    ,444,444,444
BEGIN DESCRIPTION:
UNT031 IN BECR 13.0
END DESCRIPTION:
XS GIS Cut Line= 3
      3822519.32     10505145.26      3822113.05     10504442.09
      3821586.98     10504369.17
#Sta/Elev= 30
  4274.5  403.38  4322.3  401.12  4328.1  401.79  4343.9  401.23  4402.7  397.37
  4526.2  391.75  4718.6  380.07  4730.8  378.61    4777  377.13  4782.2  376.23
  4879.4  370.15  4915.6  369.24  4959.8  370.46  4981.3  368.97  4987.1  366.83
  4996.4  366.87  4999.9  362.66  5002.6  362.16  5005.9  362.66  5008.6  367.39
  5013.9  368.19  5083.3  372.37  5162.3  375.25  5180.9  375.94    5191   377.5
    5213  377.06  5351.5  383.99  5433.3  390.52  5493.9     394  5617.7  396.59
#Mann= 6 ,-1 , 0
  4274.5     .05       0  4782.2     .12       0  4999.9     .07       0
  5005.9     .12       0  5013.9     .16       0  5162.3     .05       0
Bank Sta=4959.8,5083.3
XS Rating Curve= 0 ,0
Exp/Cntr=0.3,0.1

Type RM Length L Ch R = 1 ,6502    ,504,504,504
BEGIN DESCRIPTION:
UNT031 IN BECR 12.0
END DESCRIPTION:
XS GIS Cut Line= 3
      3822699.56     10504310.19      3822549.61     10504310.19
      3821949.64     10504210.19
#Sta/Elev= 30
  4825.8  377.53  4868.7  373.76  4905.8  369.74  4915.8  367.57  4925.8  366.87
  4935.8   366.4  4965.8  367.29  4978.3  367.03  4985.9  366.21    4996  361.27
  5000.6  360.66  5003.4  360.16  5006.6  360.66  5008.7  362.34  5016.3  365.39
  5026.4  366.98  5046.7  365.75  5087.3  368.09  5144.6   370.6  5191.2  371.12
  5239.3  370.39  5300.2  370.96  5391.4  373.06  5421.8  373.19  5472.5  374.54
  5495.3  375.68  5513.1  375.54  5523.2  376.89  5563.8  378.29    5584  379.49
#Mann= 5 ,-1 , 0
  4825.8     .05       0  4868.7     .16       0  5000.6     .07       0
  5006.6     .16       0  5144.6     .05       0
Bank Sta=4965.8,5026.4
XS Rating Curve= 0 ,0
Exp/Cntr=0.3,0.1

Type RM Length L Ch R = 1 ,5998    ,518,518,518
BEGIN DESCRIPTION:
UNT031 IN BECR 11.0
END DESCRIPTION:
XS GIS Cut Line= 3
      3823036.39     10503808.75      3822649.61     10503860.19
        3821769.      10503943.3
#Sta/Elev= 30
    4597  382.27  4755.2  381.24  4837.8  378.58    4856  376.48  4872.3  376.11
  4877.3  374.72  4896.4  372.84  4926.7  371.52  4956.9  364.37  4989.7  364.17
  4997.2  359.44  5004.3  359.39    5007  358.89  5010.3  359.39  5017.3  364.78
  5036.4  363.52  5057.5  364.51  5188.1  365.06  5208.2  364.22  5308.6  368.34
  5378.9  368.36  5389.8  369.39  5449.2  369.02  5559.7   372.3  5670.2  376.37
  5700.3  378.38  5720.4  378.43  5760.6  381.22  5785.5  381.29  5871.7   384.8
#Mann= 5 ,-1 , 0
    4597     .05       0  4837.8     .16       0  5004.3     .07       0
  5010.3     .16       0  5389.8     .05       0
Bank Sta=4989.7,5017.3
XS Rating Curve= 0 ,0
Exp/Cntr=0.3,0.1

Type RM Length L Ch R = 1 ,5480    ,319,319,319
BEGIN DESCRIPTION:
UNT031 IN BECR 10.0
END DESCRIPTION:
XS GIS Cut Line= 3
      3823032.05     10503721.92       3822732.6     10503517.95
      3821738.66     10503543.99
#Sta/Elev= 30
  4528.3  380.35  4574.7  379.84  4661.4  377.43  4748.2  373.48  4775.2  370.83
    4870  367.54  4889.4  366.11  4912.5  366.07  4913.6  366.07  4953.6  362.82
  4983.6  361.45  4992.1  359.61  5000.6  356.68  5003.4  356.18  5006.6  356.68
  5013.7  361.77  5043.7  362.57  5093.7  361.77  5213.7  362.46  5253.7  364.05
  5283.7  366.08  5303.8  365.83  5383.8  367.15  5413.8  369.06  5483.8   370.3
  5583.8  373.92  5653.9  378.18  5733.9  382.01  5743.9  383.24  5884.9  389.47
#Mann= 5 ,-1 , 0
  4528.3     .05       0  4912.5     .16       0  4992.1     .05       0
  5000.6     .03       0  5006.6     .05       0
Bank Sta=4913.6,5043.7
XS Rating Curve= 0 ,0
Exp/Cntr=0.3,0.1

Type RM Length L Ch R = 1 ,5161    ,115,115,115
BEGIN DESCRIPTION:
Mapping XS 2e40f47f
END DESCRIPTION:
XS GIS Cut Line= 4
      3823388.01     10503366.04      3822684.85     10503322.64
       3822420.1     10503305.27      3821730.03     10503457.17
#Sta/Elev= 30
  4204.2  375.41  4228.5  375.36  4292.8  375.73  4379.1  373.29    4403  374.66
    4433  372.75  4583.3  372.93  4623.7  371.32  4743.6  367.93  4821.3  364.05
    4954  360.02  4964.1  360.79  4984.1  356.04  4991.1  355.85  4993.9  355.35
  4997.1  355.85  5014.2  357.32  5025.8  360.86  5034.2  361.03  5044.2  359.73
  5064.3  361.63  5114.4  362.52  5134.4  364.92    5218  364.97  5303.4  366.69
  5410.7  368.81  5626.3  377.16  5692.4  379.33  5830.5  385.51  5880.6  386.91
#Mann= 11 ,-1 , 0
  4204.2     .08       0  4228.5     .05       0  4623.7     .08       0
  4821.3     .05       0  4991.1     .04       0  4997.1     .05       0
    5218     .08       0  5303.4     .05       0  5626.3     .08       0
  5692.4     .05       0  5830.5     .08       0
Bank Sta=4964.1,5034.2
XS Rating Curve= 0 ,0
Exp/Cntr=0.3,0.1

Type RM Length L Ch R = 1 ,5046    ,663,663,663
BEGIN DESCRIPTION:
UNT031 IN BECR 9.0
END DESCRIPTION:
XS GIS Cut Line= 3
      3823470.49     10503231.49      3822428.78     10503196.77
      3821556.38       10503136.
#Sta/Elev= 30
  4120.2   377.2  4371.2  375.43  4471.3  372.21  4616.9  365.68  4708.6  363.48
  4814.5  361.36  4908.1  360.98  4913.3  359.98  4981.6  358.86  4998.6  354.51
  5001.3  354.01  5004.6  354.51  5011.6  359.49  5021.6  360.75  5031.6  358.98
  5041.6  358.89  5121.6  361.23  5141.6  363.39  5180.9  364.86  5231.8  363.16
    5302  366.05  5333.1  364.84  5422.3  368.99  5442.3  368.89  5470.2  371.43
  5506.1   372.2    5605  374.82  5753.1  377.73  5759.5  378.81    6037  383.32
#Mann= 9 ,-1 , 0
  4120.2     .08       0  4616.9     .16       0  4708.6     .08       0
  4814.5     .05       0  4913.3     .16       0  4998.6     .07       0
  5004.6     .16       0  5506.1     .05       0    5605     .08       0
Bank Sta=4908.1,5021.6
XS Rating Curve= 0 ,0
Exp/Cntr=0.3,0.1

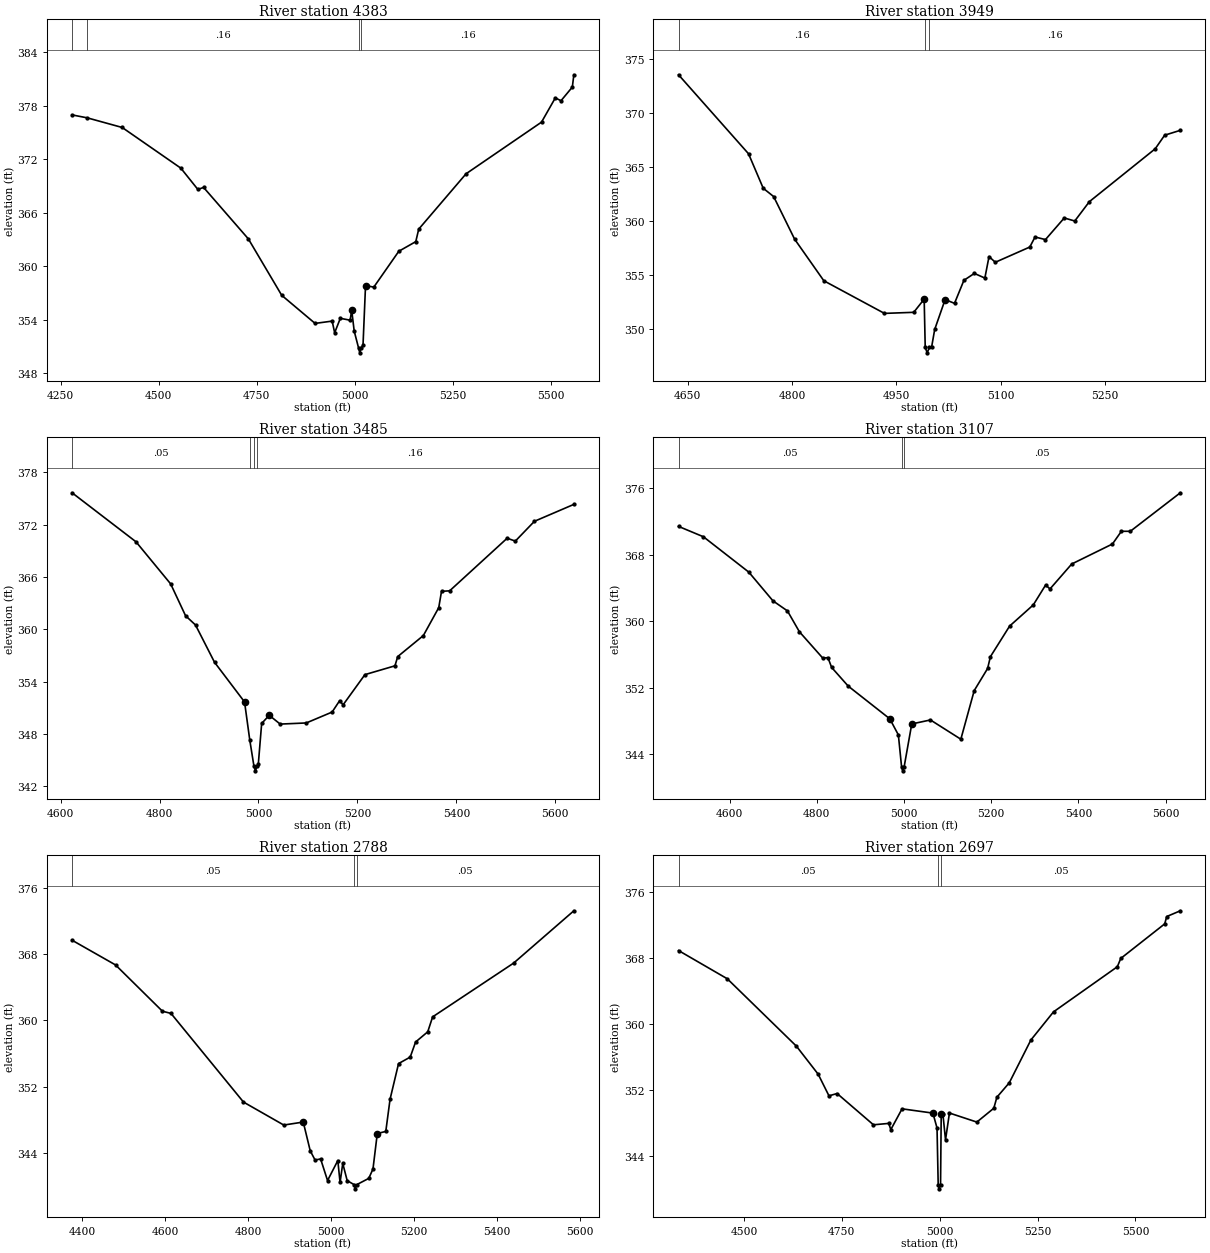
Type RM Length L Ch R = 1 ,4383    ,434,434,434
BEGIN DESCRIPTION:
UNT031 IN BECR 8.0
END DESCRIPTION:
XS GIS Cut Line= 3
      3823409.66     10503140.33      3822849.61     10502710.19
      3822398.68     10502354.98
#Sta/Elev= 30
  4278.9  376.98  4317.7  376.65  4406.8  375.57  4556.4  371.01  4599.9  368.62
  4614.4  368.85  4728.6  363.08  4813.8  356.75  4898.9   353.6  4942.5  353.86
  4948.8  352.55  4963.3  354.17  4988.3  353.96  4992.3  355.07  4998.7  352.74
  5010.1   350.8  5012.9   350.3  5016.1   350.8  5021.2  351.18  5027.6  357.84
  5048.7  357.67  5112.5  361.69  5155.8  362.77  5163.3  364.17  5284.1  370.38
  5476.6  376.17  5511.8  378.89  5526.3  378.57  5555.2   380.1  5559.1  381.48
#Mann= 4 ,-1 , 0
  4278.9     .05       0  4317.7     .16       0  5010.1     .07       0
  5016.1     .16       0
Bank Sta=4992.3,5027.6
XS Rating Curve= 0 ,0
Exp/Cntr=0.3,0.1

Type RM Length L Ch R = 1 ,3949    ,464,464,464
BEGIN DESCRIPTION:
UNT031 IN BECR 7.0
END DESCRIPTION:
XS GIS Cut Line= 3
       3823449.6     10502660.18      3823149.61     10502460.19
      3822849.61     10502260.19
#Sta/Elev= 30
  4636.9   373.5  4737.5  366.19  4758.6     363  4773.6  362.23  4803.7  358.29
  4845.7  354.44  4932.8  351.42  4974.9  351.52  4989.9  352.74  4991.4  348.27
  4994.2  347.77  4997.4  348.27  5000.5  348.27    5005  349.93    5020   352.7
  5033.5  352.35    5047  354.48    5062  355.12  5077.1  354.69  5083.1  356.68
  5092.1  356.15  5141.7  357.56  5149.2  358.49  5164.2  358.25  5191.2  360.25
  5206.3  359.97  5227.3  361.76  5321.9  366.65  5335.5  367.91    5358  368.36
#Mann= 3 ,-1 , 0
  4636.9     .16       0  4991.4     .07       0  4997.4     .16       0
Bank Sta=4989.9,5020
XS Rating Curve= 0 ,0
Exp/Cntr=0.3,0.1

Type RM Length L Ch R = 1 ,3485    ,378,378,378
BEGIN DESCRIPTION:
UNT031 IN BECR 6.0
END DESCRIPTION:
XS GIS Cut Line= 3
      3823574.61     10502589.09      3823557.25     10502328.71
      3823210.01     10501660.28
#Sta/Elev= 30
  4623.2  375.64  4752.4  370.02  4822.5  365.19  4852.6  361.54  4872.7  360.48
  4911.1  356.21  4971.8  351.66  4982.4  347.28  4990.9  344.26  4993.7  343.76
  4996.9  344.26  4999.6  344.51  5006.4  349.19  5021.7  350.13  5043.8  349.12
  5096.6  349.25  5148.8   350.5  5164.2  351.82  5170.9  351.32  5215.1  354.79
  5275.8   355.8  5281.4  356.86  5333.2  359.27  5364.3  362.47  5369.9  364.34
  5386.4   364.4  5502.6  370.43  5519.1   370.1  5557.7  372.37  5637.4  374.31
#Mann= 4 ,-1 , 0
  4623.2     .05       0  4982.4     .16       0  4990.9     .07       0
  4996.9     .16       0
Bank Sta=4971.8,5021.7
XS Rating Curve= 0 ,0
Exp/Cntr=0.3,0.1

Type RM Length L Ch R = 1 ,3107    ,319,319,319
BEGIN DESCRIPTION:
UNT031 IN BECR 5.0
END DESCRIPTION:
XS GIS Cut Line= 3
      3823748.22     10502606.52      3823813.33      10502220.2
      3823652.74     10501478.04
#Sta/Elev= 30
  4482.9  371.42    4540  370.17  4644.1  365.91  4699.5  362.45  4732.7  361.24
  4760.1  358.73  4813.8  355.55  4825.6  355.61  4834.1  354.43  4872.1  352.18
  4967.5  348.24  4987.2   346.3  4994.5  342.47  4997.2  341.97  5000.5  342.47
  5017.9  347.62  5060.8   348.1  5130.5  345.78  5161.2  351.64  5191.9   354.3
  5198.3  355.72  5242.4  359.41  5296.7  361.96  5324.9  364.35  5335.1  363.89
  5384.9  366.89  5478.3   369.3  5498.8  370.83  5519.3  370.83    5634  375.47
#Mann= 3 ,-1 , 0
  4482.9     .05       0  4994.5     .03       0  5000.5     .05       0
Bank Sta=4967.5,5017.9
XS Rating Curve= 0 ,0
Exp/Cntr=0.3,0.1

Type RM Length L Ch R = 1 ,2788    ,91,91,91
BEGIN DESCRIPTION:
Mapping XS 75097f7e
END DESCRIPTION:
XS GIS Cut Line= 4
      3823784.69      10502602.1       3823920.1     10502042.25
      3823956.55      10501945.9      3823834.39     10501428.64
#Sta/Elev= 30
  4375.3  369.67  4480.2  366.69  4593.3  361.11  4613.9  360.85  4788.8  350.16
    4886  347.39    4933  347.75  4949.8  344.29  4961.4  343.18  4974.9   343.3
  4991.6   340.7  5016.4  343.11  5021.8  340.47  5028.3  342.76    5039  340.69
  5055.9   340.2  5058.7   339.7  5061.9   340.2    5091  340.96  5101.2  342.09
  5111.6  346.37  5132.1  346.62  5142.4   350.5  5162.9   354.8    5191  355.58
    5204   357.4  5233.3  358.63  5245.1  360.43  5440.4  366.91  5585.8  373.22
#Mann= 3 ,-1 , 0
  4375.3     .05       0  5055.9     .03       0  5061.9     .05       0
Bank Sta=4933,5111.6
XS Rating Curve= 0 ,0
Exp/Cntr=0.3,0.1

Type RM Length L Ch R = 1 ,2697    ,55,55,55
BEGIN DESCRIPTION:
Mapping XS 60d3f682
END DESCRIPTION:
XS GIS Cut Line= 5
      3823808.12     10502609.96      3823966.97     10502047.46
      3824008.64     10501966.73      3824008.64     10501852.15
      3823852.38     10501385.97
#Sta/Elev= 30
  4333.1  368.93  4457.6   365.5  4634.2  357.31  4689.7  353.91  4717.3  351.28
  4738.1  351.56  4830.9  347.76  4870.1  347.93  4875.2  347.17    4904   349.7
  4982.8  349.18  4993.3  347.37  4996.3  340.48    4999  339.98  5002.3  340.48
    5004  349.02  5008.4  349.02    5015  345.93    5025  349.19    5095  348.09
  5138.3  349.77  5146.2  351.11  5177.8  352.86    5233  358.06  5290.8  361.48
  5453.8  366.96  5462.6  367.97  5574.8  372.17    5580  373.06  5614.7  373.76
#Mann= 3 ,-1 , 0
  4333.1     .05       0  4996.3     .03       0  5002.3     .05       0
Bank Sta=4982.8,5004
XS Rating Curve= 0 ,0
Exp/Cntr=0.3,0.1

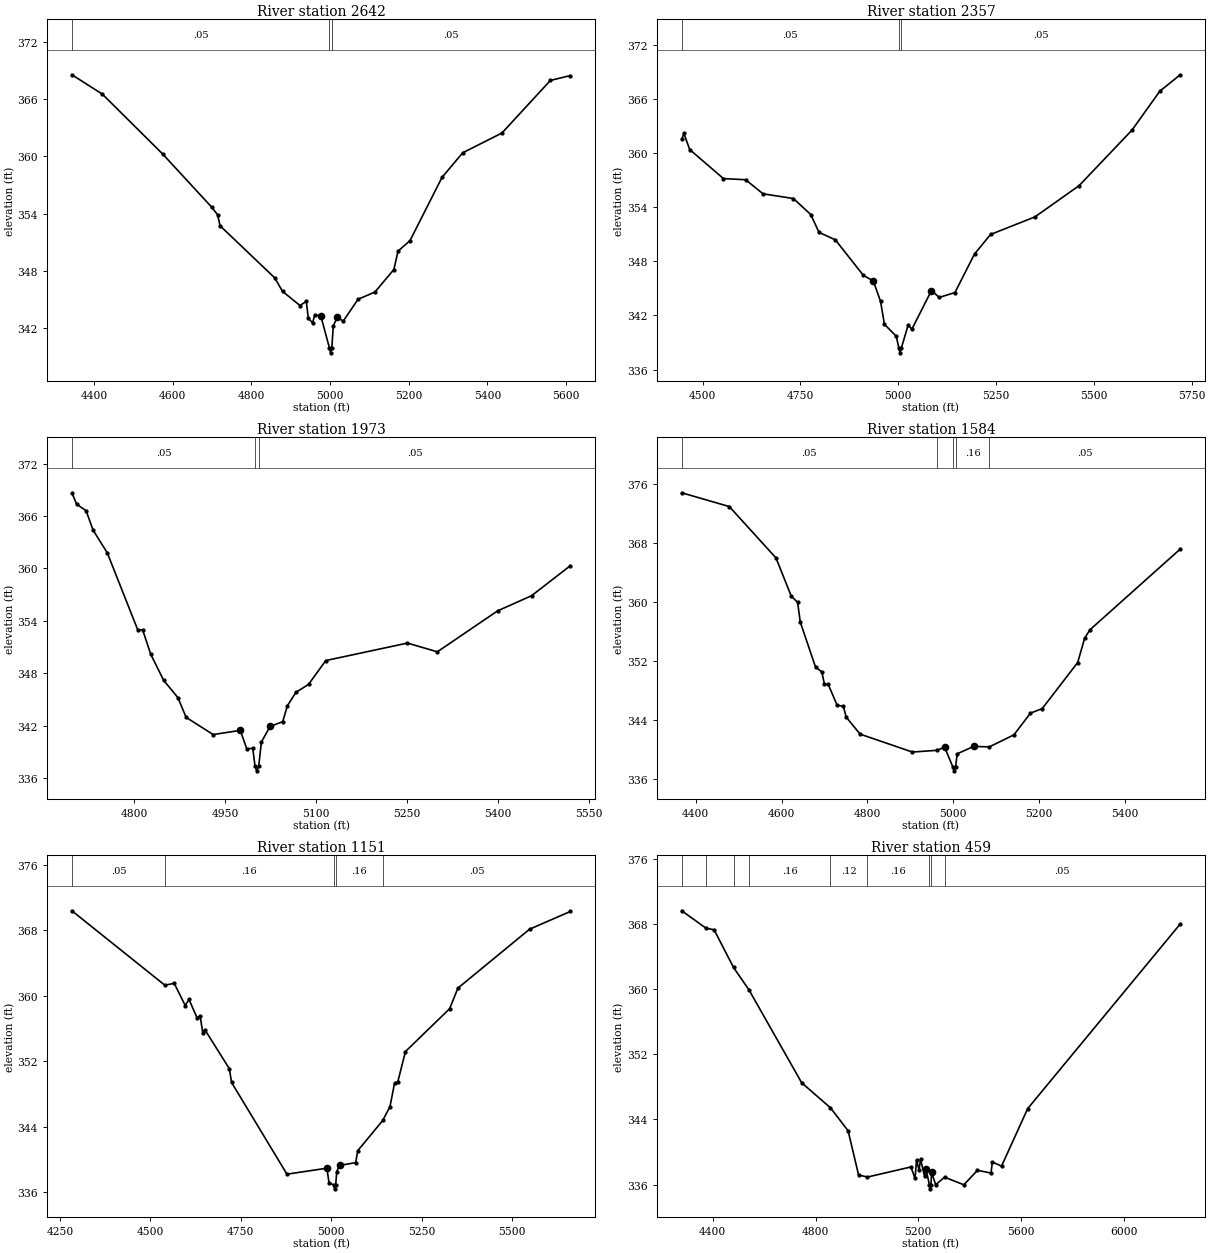
Type RM Length L Ch R = 1 ,2642    ,285,285,285
BEGIN DESCRIPTION:
Mapping XS 8c5b403f
END DESCRIPTION:
XS GIS Cut Line= 4
      3823823.76     10502612.53      3824042.49     10502034.44
      3824073.74     10501940.69      3823974.79     10501399.06
#Sta/Elev= 30
  4343.4  368.53  4420.7  366.51  4573.8  360.26  4698.7  354.69    4714  353.88
  4720.1  352.74  4859.4  347.28  4878.9  345.88  4923.3   344.4  4939.3  344.83
  4944.6  343.05  4955.3  342.59  4961.1  343.43  4976.5  343.28  4998.3  339.95
  5001.1  339.45  5004.3  339.95  5008.1  342.29  5018.7  343.19    5033  342.75
    5071  345.05  5113.9  345.81  5162.1  348.16  5172.6  350.08  5203.1  351.19
  5284.5   357.8    5337  360.37  5436.9  362.44  5560.1  367.94  5610.9  368.45
#Mann= 3 ,-1 , 0
  4343.4     .05       0  4998.3     .03       0  5004.3     .05       0
Bank Sta=4976.5,5018.7
XS Rating Curve= 0 ,0
Exp/Cntr=0.3,0.1

Type RM Length L Ch R = 1 ,2357    ,384,384,384
BEGIN DESCRIPTION:
UNT031 IN BECR 4.0
END DESCRIPTION:
XS GIS Cut Line= 4
      3824032.07      10502440.7      3824310.72     10502042.25
      3824323.74     10501747.98        3824006.     10501370.34
#Sta/Elev= 30
  4446.5  361.49  4452.1  362.17  4466.9  360.38  4553.2  357.16  4609.9  357.03
  4654.4  355.47    4732  354.95  4776.5  353.17  4797.4   351.2  4839.3  350.37
  4910.8  346.44  4936.2  345.82  4954.8  343.56  4964.8  341.01  4994.8   339.7
  5001.8  338.35  5004.6  337.85  5007.8  338.35  5025.3  340.92  5034.9  340.47
  5084.9  344.75  5104.9  343.99    5145  344.53    5195   348.8  5236.2  350.97
  5349.4  352.91  5462.5  356.38  5597.8  362.54  5668.7  366.84  5720.8  368.66
#Mann= 3 ,-1 , 0
  4446.5     .05       0  5001.8     .03       0  5007.8     .05       0
Bank Sta=4936.2,5084.9
XS Rating Curve= 0 ,0
Exp/Cntr=0.3,0.1

Type RM Length L Ch R = 1 ,1973    ,389,389,389
BEGIN DESCRIPTION:
UNT031 IN BECR 3.0
END DESCRIPTION:
XS GIS Cut Line= 3
      3824799.64     10501960.21      3824549.61     10501810.19
      3824149.61     10501460.19
#Sta/Elev= 30
    4697  368.66  4704.8  367.35  4720.4  366.61    4732  364.38  4755.4  361.79
  4805.9  352.94  4813.7  352.99  4827.3  350.16  4848.6  347.19    4872  345.22
  4885.6  342.96  4930.3  340.99    4975  341.47  4985.7  339.37  4995.7   339.4
  4999.4  337.34  5002.1  336.84  5005.4  337.34  5009.9  340.14  5024.2  341.92
  5045.1  342.47  5052.7  344.28  5066.9  345.82  5087.8  346.74  5116.2  349.46
    5251  351.46  5300.4  350.46    5400  355.15    5456  356.88  5520.1  360.32
#Mann= 3 ,-1 , 0
    4697     .05       0  4999.4     .03       0  5005.4     .05       0
Bank Sta=4975,5024.2
XS Rating Curve= 0 ,0
Exp/Cntr=0.3,0.1

Type RM Length L Ch R = 1 ,1584    ,433,433,433
BEGIN DESCRIPTION:
UNT031 IN BECR 2.0
END DESCRIPTION:
XS GIS Cut Line= 3
        3824985.     10501940.48      3824741.97     10501600.24
      3824083.44     10501253.64
#Sta/Elev= 30
  4367.3  374.86  4478.3  372.99  4587.2  366.02  4622.8  360.83  4637.6  360.01
  4643.7  357.34  4679.3  351.23  4694.1  350.56  4700.2  348.86  4708.8  348.89
  4729.7  346.05  4744.5  345.88  4750.6  344.45  4783.2  342.13  4905.2   339.7
  4962.1  339.93  4980.2  340.36  4999.8  337.65  5002.6  337.15  5005.8  337.65
  5009.7  339.46    5048  340.46  5084.6   340.4  5141.9  342.03  5180.4  344.97
    5208   345.6  5290.5  351.83  5306.9  355.15  5319.2  356.28  5529.6  367.22
#Mann= 5 ,-1 , 0
  4367.3     .05       0  4962.1     .16       0  4999.8     .07       0
  5005.8     .16       0  5084.6     .05       0
Bank Sta=4980.2,5048
XS Rating Curve= 0 ,0
Exp/Cntr=0.3,0.1

Type RM Length L Ch R = 1 ,1151    ,692,692,692
BEGIN DESCRIPTION:
Mapping XS b7618efd
END DESCRIPTION:
XS GIS Cut Line= 3
      3824957.24     10501766.88       3824887.8     10501440.52
      3823993.28     10500899.64
#Sta/Elev= 30
  4282.6  370.37  4539.9  361.28  4565.5  361.52  4596.2   358.8  4606.4  359.56
  4629.1  357.28  4637.5  357.51  4644.6  355.47  4650.5  355.85  4718.3  351.08
  4724.2  349.42  4877.5  338.22    4988  338.95  4993.9  337.15  5006.4  336.93
  5009.1  336.43  5012.4  336.93  5015.2  338.53  5023.2  339.29  5067.6  339.63
  5073.4  341.09  5142.6  344.78  5162.6  346.48  5175.1  349.32    5184  349.47
  5205.3  353.19  5327.6  358.42  5350.4  360.93  5548.7  368.12  5661.6  370.29
#Mann= 5 ,-1 , 0
  4282.6     .05       0  4539.9     .16       0  5006.4     .07       0
  5012.4     .16       0  5142.6     .05       0
Bank Sta=4988,5023.2
XS Rating Curve= 0 ,0
Exp/Cntr=0.3,0.1

Type RM Length L Ch R = 1 ,459     ,0,0,0
BEGIN DESCRIPTION:
UNT031 IN BECR 1.0
END DESCRIPTION:
XS GIS Cut Line= 4
      3825026.69     10501655.82       3825075.3     10501009.96
      3824866.97     10500648.85      3824005.85     10500808.58
#Sta/Elev= 30
    4279  369.65  4374.1   367.5    4405  367.32  4480.8  362.68  4540.6  359.94
    4746  348.51  4858.1  345.43  4926.7  342.61  4967.5  337.18  5002.1  336.92
  5171.4  338.16  5187.2  336.75    5193  338.96    5203  337.82  5208.8  339.11
  5224.5  336.99  5230.3  337.87  5243.1  335.97  5245.8  335.47  5249.1  335.97
  5251.9  337.49  5267.6  335.97  5302.1   336.9  5377.4  335.97  5430.3  337.75
  5483.1  337.41  5488.2  338.77    5524  338.26  5625.7  345.33  6219.4  368.02
#Mann= 9 ,-1 , 0
    4279     .05       0  4374.1     .16       0  4480.8     .05       0
  4540.6     .16       0  4858.1     .12       0  5002.1     .16       0
  5243.1     .07       0  5249.1     .16       0  5302.1     .05       0
Bank Sta=5230.3,5251.9
XS Rating Curve= 0 ,0
Exp/Cntr=0.3,0.1

Chan Stop Cuts=-1
Use User Specified Reach Order=0
Composite Channel Slope=5