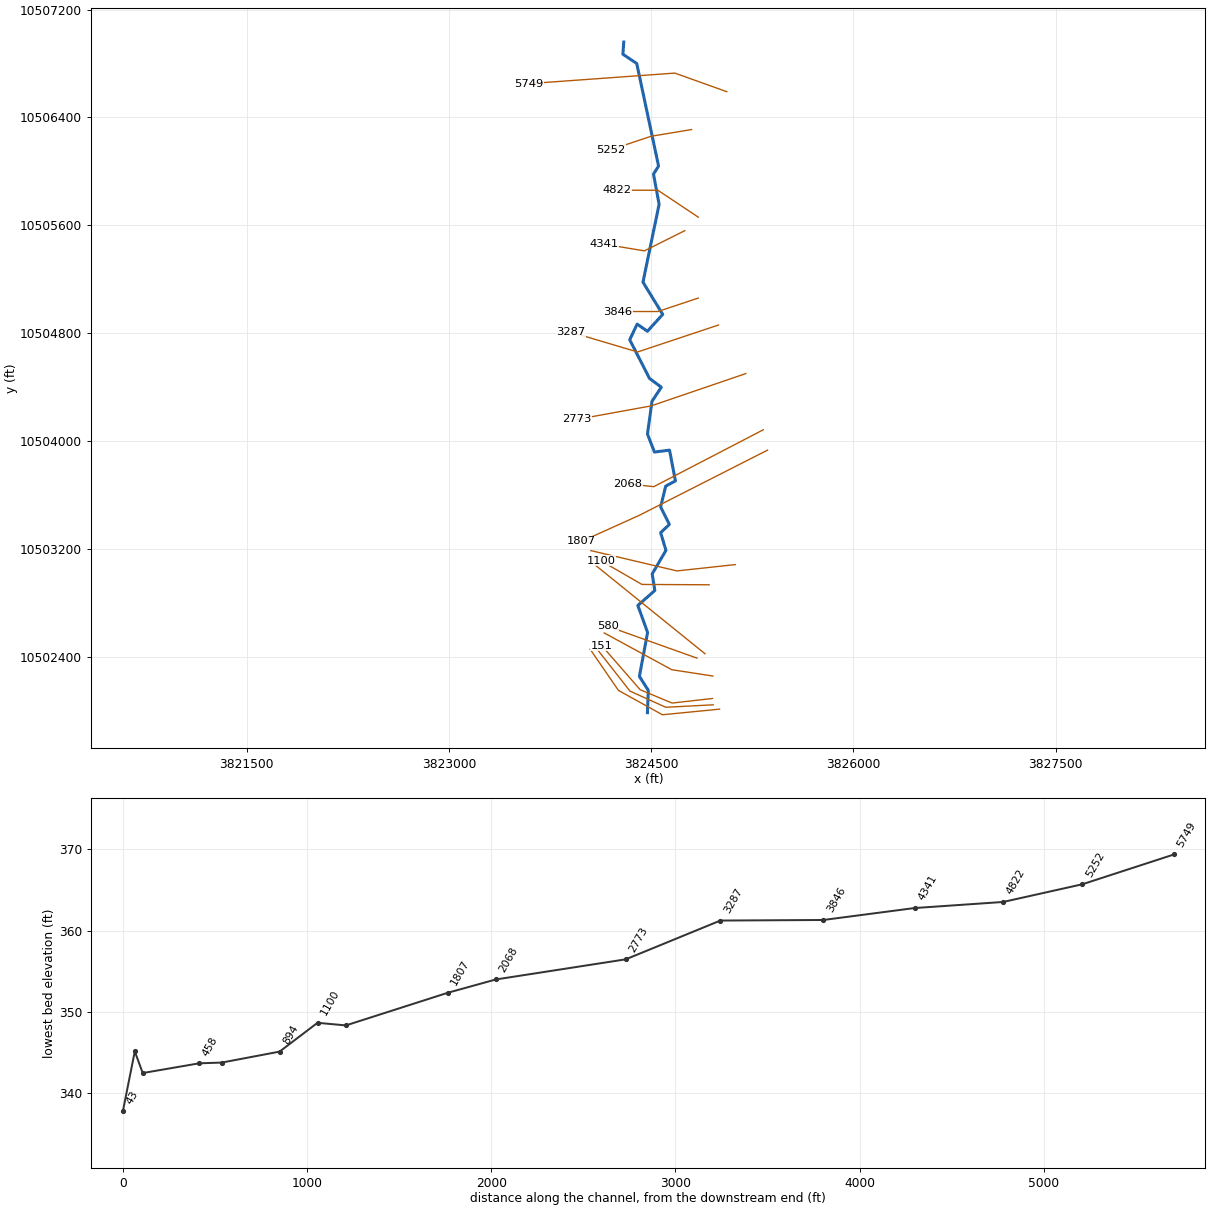
--- UNT032 IN BECR.prj (project) ---

Proj Title=UNT032 IN BECR Base Level Engineering
Current Plan=p01
Default Exp/Contr=0.3,0.1
English Units
Geom File=g01
Flow File=f01
Plan File=p01
Y Axis Title=Elevation
X Axis Title(PF)=Main Channel Distance
X Axis Title(XS)=Station
BEGIN DESCRIPTION:
UNT032 IN BECR
END DESCRIPTION:
DSS Export Rating Curves= 0
DSS Export Rating Curve Sorted= 0
DSS Export Volume Flow Curves= 0
DXF OffsetX= 0
DXF OffsetY= 0
DXF ScaleX= 1
DXF ScaleY= 10

--- UNT032 IN BECR.p01 (plan) ---

Plan Title=Multiple Run
Short Identifier=Multiple
Geom File=g01
Flow File=f01
Subcritical Flow
K Sum by GR= 0
Std Step Tol= 0.01
Critical Tol= 0.01
Num of Std Step Trials= 20
Max Error Tol= 0.3
Flow Tol Ratio= 0.001
Split Flow NTrial= 30
Split Flow Tol= 0.02
Split Flow Ratio= 0.02
Log Output Level= 0
Friction Slope Method= 1
Unsteady Friction Slope Method= 2
Unsteady Bridges Friction Slope Method= 1
Parabolic Critical Depth
Global Vel Dist=  1 , 1 , 1
Global Log Level= 0
CheckData=True
Encroach Param= -1, 0, 0, 0
BEGIN DESCRIPTION:
Multiple Run
END DESCRIPTION:

--- UNT032 IN BECR.f01 (steady flow) ---

Flow Title=Multiple
Number of Profiles=7
Profile Names=10-year,25-year,50-year,1pct_min,100-year,1pct_plu,500-year
River Rch & RM= UNT032 IN BECR,Reach-1,5749
     408     537     640     561     759    1026    1070
Boundary for River Rch & Prof#=UNT032 IN BECR,Reach-1,1
Up Type=0
Dn Type=3
Dn Slope=0.005
Boundary for River Rch & Prof#=UNT032 IN BECR,Reach-1,2
Up Type=0
Dn Type=3
Dn Slope=0.005
Boundary for River Rch & Prof#=UNT032 IN BECR,Reach-1,3
Up Type=0
Dn Type=3
Dn Slope=0.005
Boundary for River Rch & Prof#=UNT032 IN BECR,Reach-1,4
Up Type=0
Dn Type=3
Dn Slope=0.005
Boundary for River Rch & Prof#=UNT032 IN BECR,Reach-1,5
Up Type=0
Dn Type=3
Dn Slope=0.005
Boundary for River Rch & Prof#=UNT032 IN BECR,Reach-1,6
Up Type=0
Dn Type=3
Dn Slope=0.005
Boundary for River Rch & Prof#=UNT032 IN BECR,Reach-1,7
Up Type=0
Dn Type=3
Dn Slope=0.005

--- UNT032 IN BECR.g01 (geometry) ---

Geom Title=Existing Conditions
Program Version=4.10

River Reach=UNT032 IN BECR  ,Reach-1
Reach XY= 30
      3824296.68     10506959.21      3824290.25       10506869.
        3824393.       10506800.        3824555.       10506039.
      3824517.25       10505980.        3824559.       10505756.
      3824439.25       10505178.      3824585.75       10504939.
      3824472.25       10504814.        3824396.       10504867.
        3824341.       10504751.      3824487.75       10504464.
      3824575.25       10504399.        3824506.       10504294.
      3824472.75       10504051.      3824524.25       10503918.
      3824636.25       10503932.        3824680.       10503704.
        3824608.       10503665.      3824570.25       10503511.
        3824635.       10503381.      3824570.25       10503320.
      3824609.75       10503189.      3824507.75       10503014.
      3824527.25       10502891.      3824401.25       10502780.
       3824473.5       10502580.      3824412.75       10502254.
        3824479.       10502150.      3824472.25       10501985.

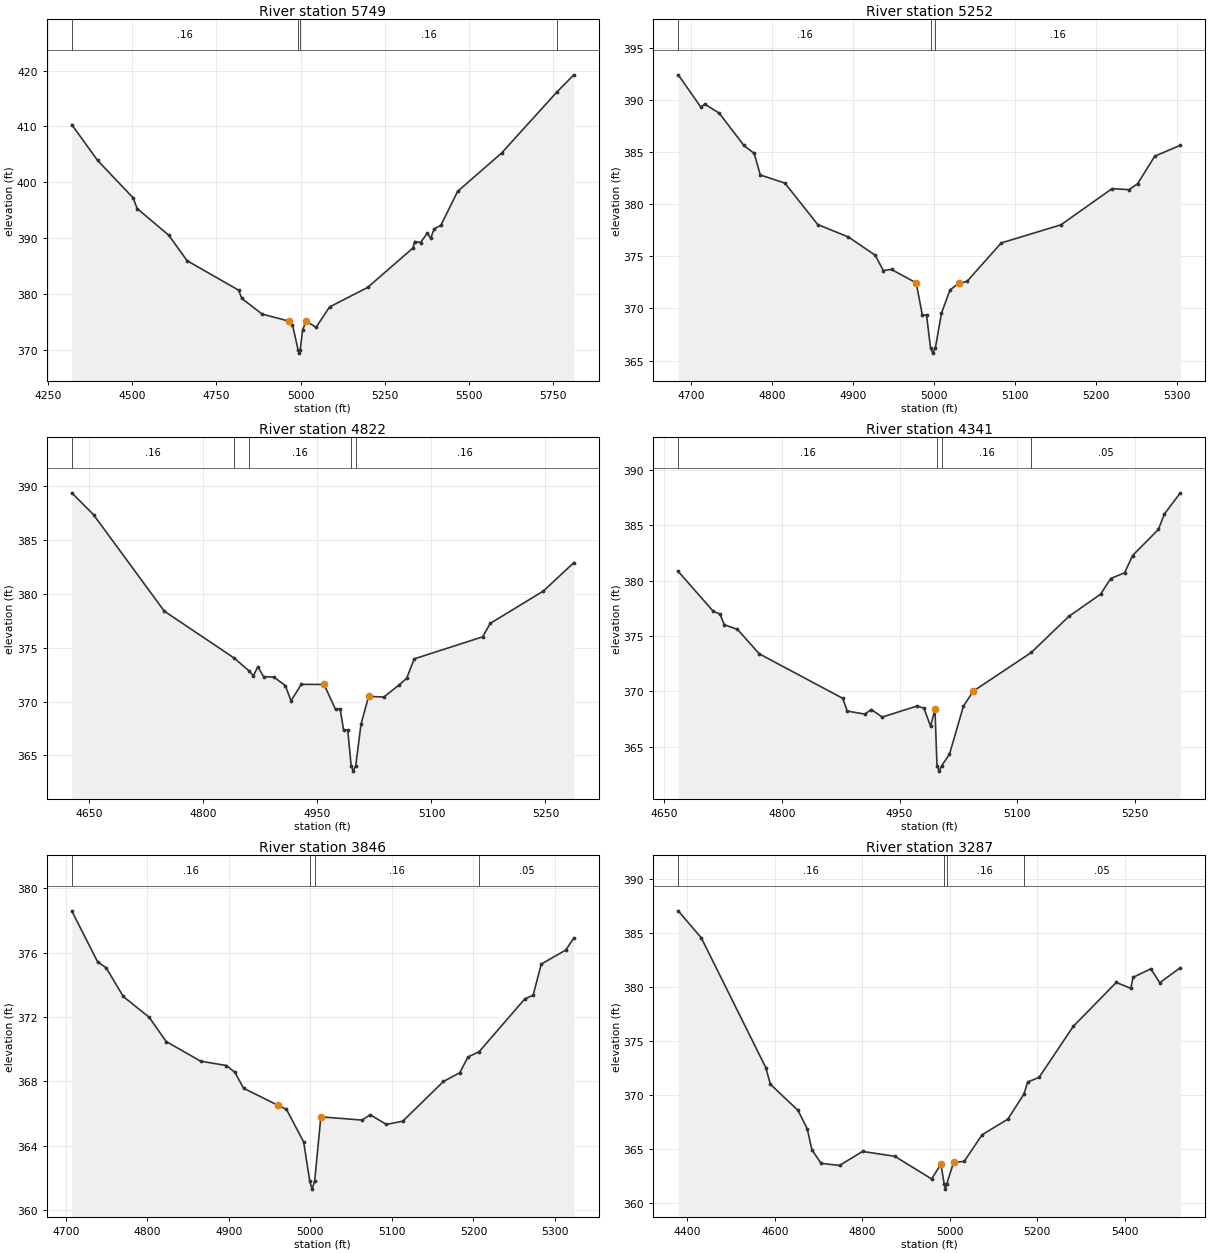
Type RM Length L Ch R = 1 ,5749    ,497,497,497
BEGIN DESCRIPTION:
UNT032 IN BECR 12.0
END DESCRIPTION:
XS GIS Cut Line= 3
      3825061.17     10506590.95      3824675.74     10506728.97
      3823595.06     10506650.85
#Sta/Elev= 30
  4319.7  410.33  4396.3  403.93  4501.9  397.22  4514.1  395.29  4608.1  390.51
  4662.6  385.94  4815.5  380.67  4825.5  379.17  4885.6  376.38  4965.8  375.11
  4975.9   374.5  4992.9  369.88  4995.7  369.38  4998.9  369.88  5005.9  373.47
    5016  375.13  5046.1     374  5086.2  377.65  5199.6  381.16  5334.1  388.21
  5339.1  389.38  5356.9   389.2  5376.9   390.9  5386.9  389.93    5397  391.64
    5417  392.27  5467.1  398.37  5597.5  405.22  5762.6   416.2  5812.6  419.25
#Mann= 4 ,-1 , 0
  4319.7     .16       0  4992.9     .07       0  4998.9     .16       0
  5762.6     .05       0
Bank Sta=4965.8,5016
XS Rating Curve= 0 ,0
Exp/Cntr=0.3,0.1

Type RM Length L Ch R = 1 ,5252    ,430,430,430
BEGIN DESCRIPTION:
UNT032 IN BECR 11.0
END DESCRIPTION:
XS GIS Cut Line= 3
      3824799.59     10506310.18      3824499.61     10506260.19
      3824199.65      10506160.2
#Sta/Elev= 30
  4683.8  392.39  4711.7   389.3  4716.7  389.58  4734.5  388.71  4764.9  385.62
  4777.6  384.86  4785.2  382.79  4815.6  382.01  4856.1  378.04  4894.1  376.84
  4927.1   375.1  4937.2  373.63  4947.4  373.73  4977.8  372.44  4985.4  369.35
  4990.6  369.35  4995.5  366.21  4998.2  365.71  5001.5  366.21    5009  369.53
  5019.5  371.76  5030.1  372.39  5040.6  372.59  5082.8  376.27  5156.6  378.01
  5219.8  381.48  5240.9  381.38  5251.4  381.96  5272.5  384.59  5304.1  385.63
#Mann= 3 ,-1 , 0
  4683.8     .16       0  4995.5     .07       0  5001.5     .16       0
Bank Sta=4977.8,5030.1
XS Rating Curve= 0 ,0
Exp/Cntr=0.3,0.1

Type RM Length L Ch R = 1 ,4822    ,481,481,481
BEGIN DESCRIPTION:
UNT032 IN BECR 10.0
END DESCRIPTION:
XS GIS Cut Line= 3
      3824849.62     10505660.18      3824549.61     10505860.19
      3824249.57     10505860.19
#Sta/Elev= 30
  4626.7  389.41  4655.3  387.38  4748.4  378.41  4840.3  374.05    4860  372.85
  4865.6   372.4  4871.6  373.24  4879.1  372.31  4892.6  372.28  4907.6  371.49
  4915.2  370.07  4928.7   371.6  4958.7  371.59  4973.7  369.27  4979.8  369.32
  4984.3  367.36  4989.8  367.36  4994.3  364.03    4997  363.53  5000.3  364.03
  5007.3  367.91  5017.3  370.48  5037.3  370.42  5057.3  371.54  5067.3  372.16
  5077.3  373.97  5167.3  376.02  5177.3  377.27  5247.3  380.28  5287.3  382.92
#Mann= 5 ,-1 , 0
  4626.7     .16       0  4840.3     .12       0    4860     .16       0
  4994.3     .07       0  5000.3     .16       0
Bank Sta=4958.7,5017.3
XS Rating Curve= 0 ,0
Exp/Cntr=0.3,0.1

Type RM Length L Ch R = 1 ,4341    ,495,495,495
BEGIN DESCRIPTION:
UNT032 IN BECR 9.0
END DESCRIPTION:
XS GIS Cut Line= 3
      3824749.58     10505560.17      3824449.61     10505410.19
      3824149.63     10505460.19
#Sta/Elev= 30
  4668.1  380.84  4712.8  377.23  4721.2  376.99  4726.8  376.02  4743.5   375.6
  4771.5  373.38  4877.7  369.36  4883.3  368.21  4905.7  367.94    4914  368.35
    4928  367.67  4972.7  368.68  4981.1  368.46  4989.5  366.84  4995.1  368.38
  4997.7  363.28  5000.4  362.78  5003.7  363.28  5013.6  364.31  5031.4  368.67
    5044  370.02  5117.8  373.51  5165.7  376.78  5206.2  378.79  5218.9   380.2
  5236.7  380.72  5246.8  382.28  5279.7  384.64  5287.3  386.03  5307.6  387.95
#Mann= 4 ,-1 , 0
  4668.1     .16       0  4997.7     .07       0  5003.7     .16       0
  5117.8     .05       0
Bank Sta=4995.1,5044
XS Rating Curve= 0 ,0
Exp/Cntr=0.3,0.1

Type RM Length L Ch R = 1 ,3846    ,559,559,559
BEGIN DESCRIPTION:
UNT032 IN BECR 8.0
END DESCRIPTION:
XS GIS Cut Line= 3
      3824849.61     10505060.19      3824549.61     10504960.19
      3824249.63     10504960.19
#Sta/Elev= 30
  4707.1   378.6  4738.7  375.44  4749.3  375.06  4770.3  373.28    4802  371.99
    4823  370.48  4865.2  369.26  4896.8  368.99  4907.4  368.56  4917.9  367.58
  4960.1  366.52  4970.6  366.27  4991.7  364.24  4999.2  361.81    5002  361.31
  5005.2  361.81  5012.8   365.8  5063.3   365.6  5073.3  365.93  5093.3  365.33
  5113.3  365.53  5163.3     368  5183.3  368.54  5193.3  369.52  5207.1  369.85
  5263.3  373.14  5273.3  373.35  5283.3  375.29  5313.3  376.16  5323.3  376.91
#Mann= 4 ,-1 , 0
  4707.1     .16       0  4999.2     .07       0  5005.2     .16       0
  5207.1     .05       0
Bank Sta=4960.1,5012.8
XS Rating Curve= 0 ,0
Exp/Cntr=0.3,0.1

Type RM Length L Ch R = 1 ,3287    ,514,514,514
BEGIN DESCRIPTION:
UNT032 IN BECR 7.0
END DESCRIPTION:
XS GIS Cut Line= 3
      3824999.57     10504860.17      3824399.61     10504660.19
      3823904.87     10504807.11
#Sta/Elev= 30
  4379.1  387.01  4431.8  384.51  4579.3   372.5  4589.9  370.95  4653.1  368.53
  4674.2  366.83  4684.7   364.9  4705.8  363.63    4748  363.43  4800.7  364.73
  4874.5  364.28  4958.8  362.18  4979.9  363.56  4987.4  361.74  4990.2  361.24
  4993.4  361.74  5008.9  363.71  5033.3  363.81  5074.1  366.27    5133  367.72
  5169.9  370.04  5178.4  371.16  5204.6  371.59  5282.7  376.31  5381.1  380.38
  5414.3  379.83  5419.5  380.85  5460.1  381.64  5480.7  380.35  5527.6  381.75
#Mann= 4 ,-1 , 0
  4379.1     .16       0  4987.4     .07       0  4993.4     .16       0
  5169.9     .05       0
Bank Sta=4979.9,5008.9
XS Rating Curve= 0 ,0
Exp/Cntr=0.3,0.1

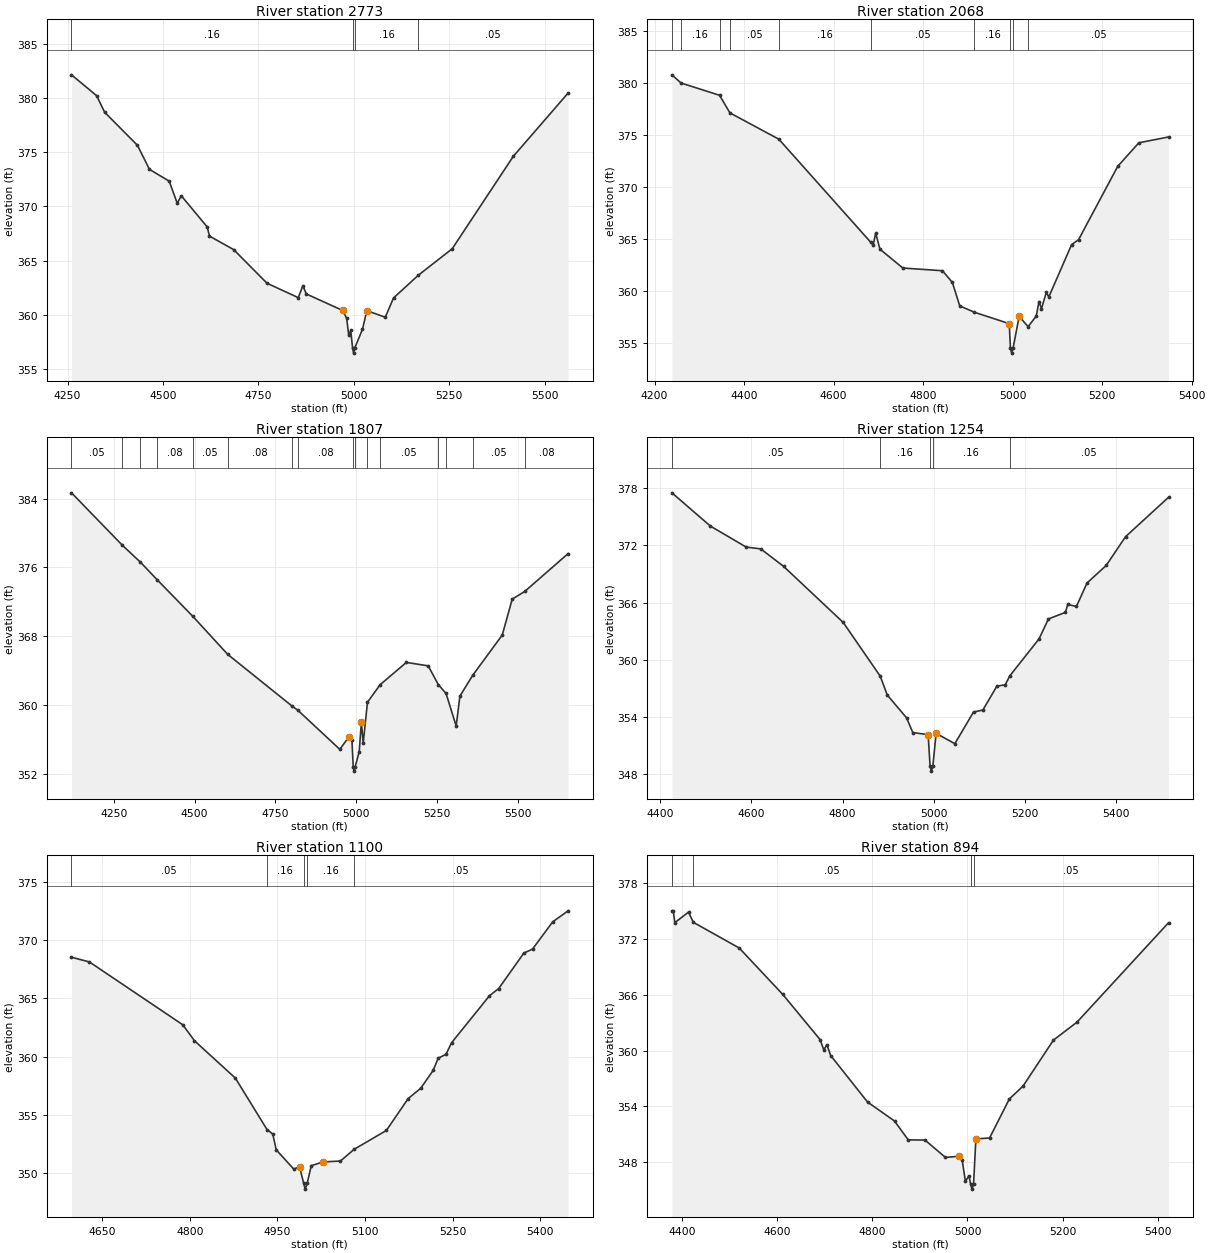
Type RM Length L Ch R = 1 ,2773    ,705,705,705
BEGIN DESCRIPTION:
UNT032 IN BECR 6.0
END DESCRIPTION:
XS GIS Cut Line= 3
      3825201.77      10504499.8      3824499.61     10504260.19
      3823949.65      10504160.2
#Sta/Elev= 30
  4260.2  382.14  4325.9  380.22    4347  378.69  4433.1  375.63  4464.4  373.42
  4516.1  372.33  4537.2  370.29  4547.8  370.98  4615.8   368.1  4621.7  367.26
  4685.1  366.01  4772.4  362.91  4854.2  361.58  4866.4  362.68  4875.3  361.92
  4970.4   360.4    4981  359.68  4986.5   358.1  4991.7  358.55  4996.5  356.96
  4999.2  356.46  5002.5  356.96  5022.4  358.65  5033.9  360.38  5082.2  359.77
  5103.8  361.55  5168.5  363.64  5257.5  366.09  5417.6  374.62  5561.1  380.46
#Mann= 4 ,-1 , 0
  4260.2     .16       0  4996.5     .07       0  5002.5     .16       0
  5168.5     .05       0
Bank Sta=4970.4,5033.9
XS Rating Curve= 0 ,0
Exp/Cntr=0.3,0.1

Type RM Length L Ch R = 1 ,2068    ,261,261,261
BEGIN DESCRIPTION:
UNT032 IN BECR 5.0
END DESCRIPTION:
XS GIS Cut Line= 3
      3825332.03     10504083.16      3824519.49     10503661.26
      3824326.75      10503682.1
#Sta/Elev= 30
  4238.9   380.8  4259.3  380.01  4345.3  378.83  4368.5  377.13  4477.7   374.6
  4683.1  364.66  4688.5  364.41  4694.1  365.55  4703.6     364  4754.8  362.18
  4843.3  361.92  4865.4  360.79  4881.9  358.53  4914.6  357.92  4992.5  356.82
  4995.1  354.48  4997.9  353.98  5001.1  354.48  5014.6  357.52  5034.7  356.53
  5052.9  357.56  5058.8  358.94  5064.5  358.27  5075.3  359.83  5080.9   359.4
  5131.8  364.44  5147.3  364.91  5234.8  371.98    5282  374.25  5348.3  374.81
#Mann= 10 ,-1 , 0
  4238.9     .05       0  4259.3     .16       0  4345.3     .08       0
  4368.5     .05       0  4477.7     .16       0  4683.1     .05       0
  4914.6     .16       0  4995.1     .07       0  5001.1     .16       0
  5034.7     .05       0
Bank Sta=4992.5,5014.6
XS Rating Curve= 0 ,0
Exp/Cntr=0.3,0.1

Type RM Length L Ch R = 1 ,1807    ,553,553,553
BEGIN DESCRIPTION:
UNT032 IN BECR 4.0
END DESCRIPTION:
XS GIS Cut Line= 3
      3825363.28     10503932.12      3824410.11     10503447.72
      3823983.98     10503255.44
#Sta/Elev= 30
  4119.3  384.67  4276.4  378.59  4332.7  376.61  4385.2  374.54    4494  370.35
  4602.8   365.9    4801  359.92  4820.4  359.39  4949.6  354.87  4977.4  356.31
  4987.1  355.93  4991.1  352.84  4993.8  352.34  4997.1  352.84  5009.6   354.6
  5016.3  358.01    5022   355.6  5035.2  360.34  5074.4  362.38  5155.5  364.97
  5223.2  364.57  5254.2   362.4  5278.4  361.36  5309.7  357.58  5321.2  361.05
  5360.8  363.47  5452.3  368.15  5483.1  372.32  5522.1  373.22    5656  377.61
#Mann= 16 ,-1 , 0
  4119.3     .05       0  4276.4     .08       0  4332.7     .05       0
  4385.2     .08       0    4494     .05       0  4602.8     .08       0
    4801     .05       0  4820.4     .08       0  4991.1     .07       0
  4997.1     .08       0  5035.2     .16       0  5074.4     .05       0
  5254.2     .08       0  5278.4     .16       0  5360.8     .05       0
  5522.1     .08       0
Bank Sta=4977.4,5016.3
XS Rating Curve= 0 ,0
Exp/Cntr=0.3,0.1

Type RM Length L Ch R = 1 ,1254    ,154,154,154
BEGIN DESCRIPTION:
UNT032 IN BECR 3.0
END DESCRIPTION:
XS GIS Cut Line= 3
      3825123.63     10503083.14      3824691.36     10503036.26
      3824052.68     10503186.85
#Sta/Elev= 30
  4425.2  377.51  4509.7  374.02  4588.4  371.82  4620.4  371.63  4670.7  369.79
  4801.4  363.92    4883  358.27  4898.3   356.3  4940.7  353.91  4954.3  352.37
  4988.1  352.14  4992.4  348.82  4995.1  348.32  4998.4  348.82  5005.6  352.28
  5046.7   351.2  5087.8  354.52  5108.4  354.73  5139.2  357.24  5157.5  357.37
  5167.3   358.3  5231.7  362.19  5252.4  364.28  5289.6  364.97  5294.8   365.8
  5313.9  365.59  5337.1  368.05  5379.4   369.9  5421.8  372.91  5516.2  377.04
#Mann= 5 ,-1 , 0
  4425.2     .05       0    4883     .16       0  4992.4     .07       0
  4998.4     .16       0  5167.3     .05       0
Bank Sta=4988.1,5005.6
XS Rating Curve= 0 ,0
Exp/Cntr=0.3,0.1

Type RM Length L Ch R = 1 ,1100    ,206,206,206
BEGIN DESCRIPTION:
Mapping XS ccc8209e
END DESCRIPTION:
XS GIS Cut Line= 3
      3824930.19     10502933.39      3824431.53       10502936.
      3824126.86     10503111.77
#Sta/Elev= 30
  4597.3  368.52  4627.9  368.12  4787.9  362.73  4807.9  361.36  4877.9  358.16
  4932.1  353.75    4942  353.36  4947.9  352.01  4977.9  350.36  4987.9  350.55
  4994.9  349.14  4997.6  348.64  5000.9  349.14  5007.9  350.65  5027.9  350.97
  5057.9  351.05  5081.5  352.06  5136.5  353.67  5173.8   356.4  5195.4  357.29
  5216.9  358.84  5225.2  359.87  5238.5  360.19  5248.3   361.2  5313.1  365.22
  5328.9  365.84    5372  368.88  5386.8  369.22  5421.4  371.56  5447.7   372.5
#Mann= 5 ,-1 , 0
  4597.3     .05       0  4932.1     .16       0  4994.9     .07       0
  5000.9     .16       0  5081.5     .05       0
Bank Sta=4987.9,5027.9
XS Rating Curve= 0 ,0
Exp/Cntr=0.3,0.1

Type RM Length L Ch R = 1 ,894     ,314,314,314
BEGIN DESCRIPTION:
UNT032 IN BECR 2.0
END DESCRIPTION:
XS GIS Cut Line= 2
      3824899.72     10502421.66      3824087.16     10503077.96
#Sta/Elev= 30
  4378.4  375.04  4381.2  375.04  4384.5  373.77  4413.3   374.9  4423.5   373.8
  4519.9  371.04  4611.6  366.04  4689.9  361.19  4697.9  360.07  4704.3  360.64
  4712.3  359.47  4789.9  354.46  4846.6  352.42  4875.4  350.39  4910.6  350.37
  4953.8   348.5  4982.5  348.63    4989  348.18  4995.6  345.95  5003.3  346.52
  5006.8  345.59  5009.5  345.09  5012.8  345.59  5017.7   350.5  5046.5  350.59
  5088.1  354.79  5116.9  356.18  5180.9  361.13  5230.4  363.06  5422.9  373.76
#Mann= 4 ,-1 , 0
  4378.4     .16       0  4423.5     .05       0  5006.8     .03       0
  5012.8     .05       0
Bank Sta=4982.5,5017.7
XS Rating Curve= 0 ,0
Exp/Cntr=0.3,0.1

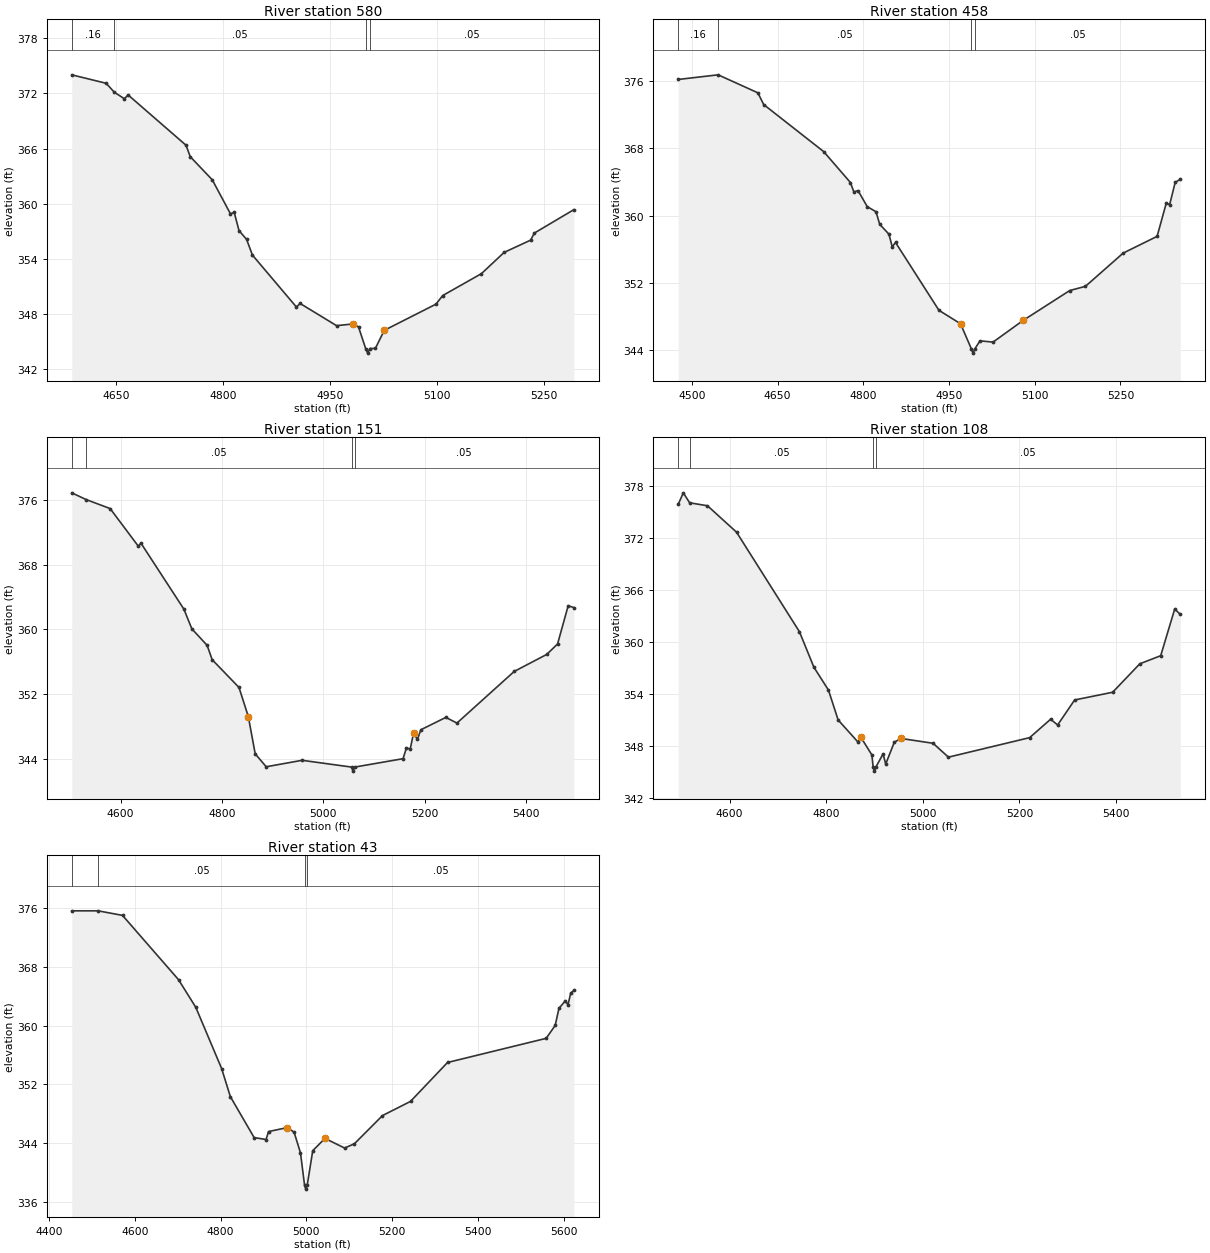
Type RM Length L Ch R = 1 ,580     ,122,122,122
BEGIN DESCRIPTION:
Mapping XS 666783c3
END DESCRIPTION:
XS GIS Cut Line= 2
      3824840.39     10502389.12      3824177.62     10502625.64
#Sta/Elev= 30
  4588.3  374.02  4636.5   373.1    4648  372.12    4662  371.42  4667.3  371.83
  4748.4  366.36  4754.4  365.11  4785.2   362.6  4810.7   358.9    4816  359.05
  4822.7  357.07  4833.3  356.12  4841.5  354.41  4903.1  348.76  4908.4  349.14
  4959.4  346.73    4982  346.91  4990.2  346.59  5000.2  344.24    5003  343.74
  5006.2  344.24  5013.8  344.25  5026.3  346.22  5098.8  349.07  5108.1     350
  5162.5  352.39  5194.3   354.7  5231.3  356.03  5236.8  356.81    5292  359.35
#Mann= 4 ,-1 , 0
  4588.3     .16       0    4648     .05       0  5000.2     .03       0
  5006.2     .05       0
Bank Sta=4982,5026.3
XS Rating Curve= 0 ,0
Exp/Cntr=0.3,0.1

Type RM Length L Ch R = 1 ,458     ,307,307,307
BEGIN DESCRIPTION:
Mapping XS 08effd4f
END DESCRIPTION:
XS GIS Cut Line= 3
      3824957.42     10502256.66      3824652.73     10502303.54
      3824151.74      10502576.1
#Sta/Elev= 30
  4476.1  376.18  4545.9  376.73  4615.5  374.59  4625.6   373.2  4730.7   367.6
  4777.4  363.93  4783.4  362.81  4790.7  362.97  4806.9  361.06  4822.1  360.46
  4828.7  358.96  4844.8  357.79  4850.6  356.28  4856.3  356.81  4932.3  348.74
  4970.1  347.14  4989.1  344.15  4991.9  343.65  4995.1  344.15  5004.2  345.11
    5027  344.96  5079.5  347.53  5161.2  351.09  5188.7  351.59  5254.7  355.54
  5314.1  357.53  5330.3  361.52    5336  361.28  5345.7  363.94  5354.7  364.32
#Mann= 4 ,-1 , 0
  4476.1     .16       0  4545.9     .05       0  4989.1     .03       0
  4995.1     .05       0
Bank Sta=4970.1,5079.5
XS Rating Curve= 0 ,0
Exp/Cntr=0.3,0.1

Type RM Length L Ch R = 1 ,151     ,43,43,43
BEGIN DESCRIPTION:
Mapping XS d9413dea
END DESCRIPTION:
XS GIS Cut Line= 4
      3824954.79     10502089.99      3824655.34     10502056.14
      3824418.36      10502155.1      3824134.55     10502480.57
#Sta/Elev= 30
  4503.9   376.9  4532.5  376.06  4579.6  374.95  4635.3  370.28  4640.3  370.67
  4725.1  362.49  4740.6  360.07  4770.8  358.02  4780.8  356.24  4833.6  352.81
    4852  349.21  4865.6  344.59  4887.3  342.99  4958.1  343.79  5055.7  342.95
  5058.4  342.45  5061.7  342.95  5157.1  343.99  5163.7   345.3  5171.3   345.2
  5177.9  347.18  5185.5  346.37  5192.2  347.57  5241.5   349.1  5263.4   348.4
  5376.3  354.79  5440.3  356.89  5461.8  358.19  5482.7  362.92  5493.9   362.7
#Mann= 4 ,-1 , 0
  4503.9     .16       0  4532.5     .05       0  5055.7     .03       0
  5061.7     .05       0
Bank Sta=4852,5177.9
XS Rating Curve= 0 ,0
Exp/Cntr=0.3,0.1

Type RM Length L Ch R = 1 ,108     ,65,65,65
BEGIN DESCRIPTION:
Mapping XS c9b79d08
END DESCRIPTION:
XS GIS Cut Line= 4
      3824960.05     10502043.12      3824608.46     10502024.89
      3824342.84     10502144.68      3824098.85     10502456.16
#Sta/Elev= 30
  4493.8  375.87  4504.3  377.19  4517.4  376.04  4554.3   375.7  4614.4  372.66
  4744.6  361.19  4774.6  357.09  4804.7  354.46  4824.7  351.02    4866  348.46
  4871.5  349.05  4894.6  346.98  4897.1  345.62  4899.8  345.12  4903.1  345.62
  4917.7   347.1  4923.2  345.94  4940.9  348.44  4954.3  348.89  5021.2  348.33
    5053  346.73  5221.1  348.98  5264.5   351.1    5279  350.44  5314.2  353.32
  5392.9  354.21  5449.1  357.49  5492.3  358.42  5521.3   363.8  5532.9  363.18
#Mann= 4 ,-1 , 0
  4493.8     .16       0  4517.4     .05       0  4897.1     .03       0
  4903.1     .05       0
Bank Sta=4871.5,4954.3
XS Rating Curve= 0 ,0
Exp/Cntr=0.3,0.1

Type RM Length L Ch R = 1 ,43      ,0,0,0
BEGIN DESCRIPTION:
UNT032 IN BECR 1.0
END DESCRIPTION:
XS GIS Cut Line= 4
      3825007.31     10502010.91      3824583.72     10501969.25
      3824257.34     10502149.81      3824046.63     10502456.22
#Sta/Elev= 30
  4453.2  375.63  4514.5  375.63  4571.5  375.01  4702.1  366.25  4742.3  362.49
  4802.6  354.14  4822.9  350.32  4878.4  344.74  4906.2  344.48  4911.9  345.56
  4955.4   346.1  4971.5  345.48  4986.4  342.66    4996  338.22  4998.7  337.72
    5002  338.22    5015  342.96  5043.5  344.63  5089.2  343.32  5112.1   343.9
  5177.6  347.74  5242.9  349.67  5329.2  354.97  5559.2  358.26  5580.2  360.02
    5589  362.35  5603.9  363.37    5610  362.82  5616.4  364.41  5623.7  364.78
#Mann= 4 ,-1 , 0
  4453.2     .16       0  4514.5     .05       0    4996     .03       0
    5002     .05       0
Bank Sta=4955.4,5043.5
XS Rating Curve= 0 ,0
Exp/Cntr=0.3,0.1

Chan Stop Cuts=-1
Use User Specified Reach Order=0
Composite Channel Slope=5