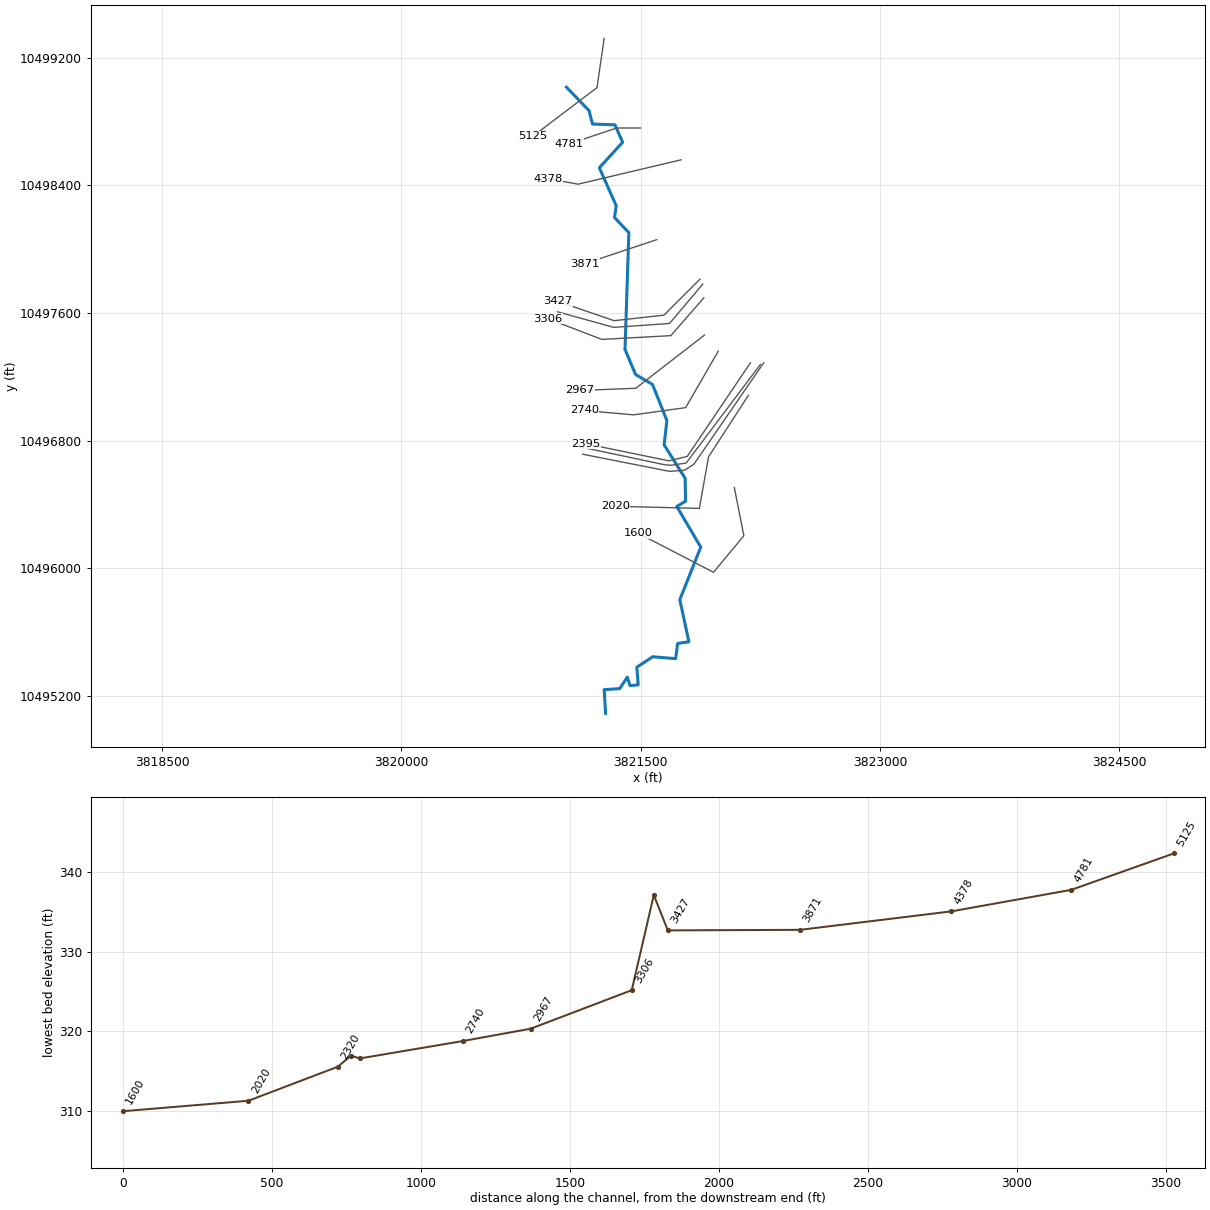
--- UNT033 IN BECR.prj (project) ---

Proj Title=UNT033 IN BECR Base Level Engineering
Current Plan=p01
Default Exp/Contr=0.3,0.1
English Units
Geom File=g01
Flow File=f01
Plan File=p01
Y Axis Title=Elevation
X Axis Title(PF)=Main Channel Distance
X Axis Title(XS)=Station
BEGIN DESCRIPTION:
UNT033 IN BECR
END DESCRIPTION:
DSS Export Rating Curves= 0
DSS Export Rating Curve Sorted= 0
DSS Export Volume Flow Curves= 0
DXF OffsetX= 0
DXF OffsetY= 0
DXF ScaleX= 1
DXF ScaleY= 10

--- UNT033 IN BECR.p01 (plan) ---

Plan Title=Multiple Run
Short Identifier=Multiple
Geom File=g01
Flow File=f01
Subcritical Flow
K Sum by GR= 0
Std Step Tol= 0.01
Critical Tol= 0.01
Num of Std Step Trials= 20
Max Error Tol= 0.3
Flow Tol Ratio= 0.001
Split Flow NTrial= 30
Split Flow Tol= 0.02
Split Flow Ratio= 0.02
Log Output Level= 0
Friction Slope Method= 1
Unsteady Friction Slope Method= 2
Unsteady Bridges Friction Slope Method= 1
Parabolic Critical Depth
Global Vel Dist=  1 , 1 , 1
Global Log Level= 0
CheckData=True
Encroach Param= -1, 0, 0, 0
BEGIN DESCRIPTION:
Multiple Run
END DESCRIPTION:

--- UNT033 IN BECR.f01 (steady flow) ---

Flow Title=Multiple
Program Version=4.10
Number of Profiles= 7
Profile Names=10-year,25-year,50-year,1pct_min,100-year,1pct_plu,500-year
River Rch & RM=UNT033 IN BECR,Reach-1         ,5125
     276     354     414     358     484     654     661
Boundary for River Rch & Prof#=UNT033 IN BECR,Reach-1         , 1
Up Type= 0
Dn Type= 3
Dn Slope=0.027
Boundary for River Rch & Prof#=UNT033 IN BECR,Reach-1         , 2
Up Type= 0
Dn Type= 3
Dn Slope=0.027
Boundary for River Rch & Prof#=UNT033 IN BECR,Reach-1         , 3
Up Type= 0
Dn Type= 3
Dn Slope=0.027
Boundary for River Rch & Prof#=UNT033 IN BECR,Reach-1         , 4
Up Type= 0
Dn Type= 3
Dn Slope=0.027
Boundary for River Rch & Prof#=UNT033 IN BECR,Reach-1         , 5
Up Type= 0
Dn Type= 3
Dn Slope=0.027
Boundary for River Rch & Prof#=UNT033 IN BECR,Reach-1         , 6
Up Type= 0
Dn Type= 3
Dn Slope=0.027
Boundary for River Rch & Prof#=UNT033 IN BECR,Reach-1         , 7
Up Type= 0
Dn Type= 3
Dn Slope=0.027
DSS Import GetInterval= 0
DSS Import GetPeak= 0
DSS Import FillOption= 0

--- UNT033 IN BECR.g01 (geometry) ---

Geom Title=Existing Conditions
Program Version=4.10

River Reach=UNT033 IN BECR  ,Reach-1
Reach XY= 30
      3821034.28     10499015.72      3821175.75       10498869.
       3821197.5       10498785.      3821338.25       10498780.
       3821386.5       10498671.      3821240.25       10498511.
        3821346.       10498273.       3821335.5       10498199.
      3821425.25       10498104.      3821401.25       10497372.
       3821467.5       10497215.       3821573.5       10497153.
      3821663.75       10496926.      3821646.25       10496774.
      3821778.25       10496564.      3821780.75       10496421.
      3821725.75       10496388.        3821876.       10496133.
      3821744.75       10495804.       3821801.5       10495540.
        3821731.       10495529.       3821718.5       10495434.
      3821574.75       10495446.      3821475.25       10495380.
        3821484.       10495270.       3821432.5       10495265.
      3821415.25       10495318.      3821367.75       10495246.
       3821270.5       10495240.       3821279.5       10495091.

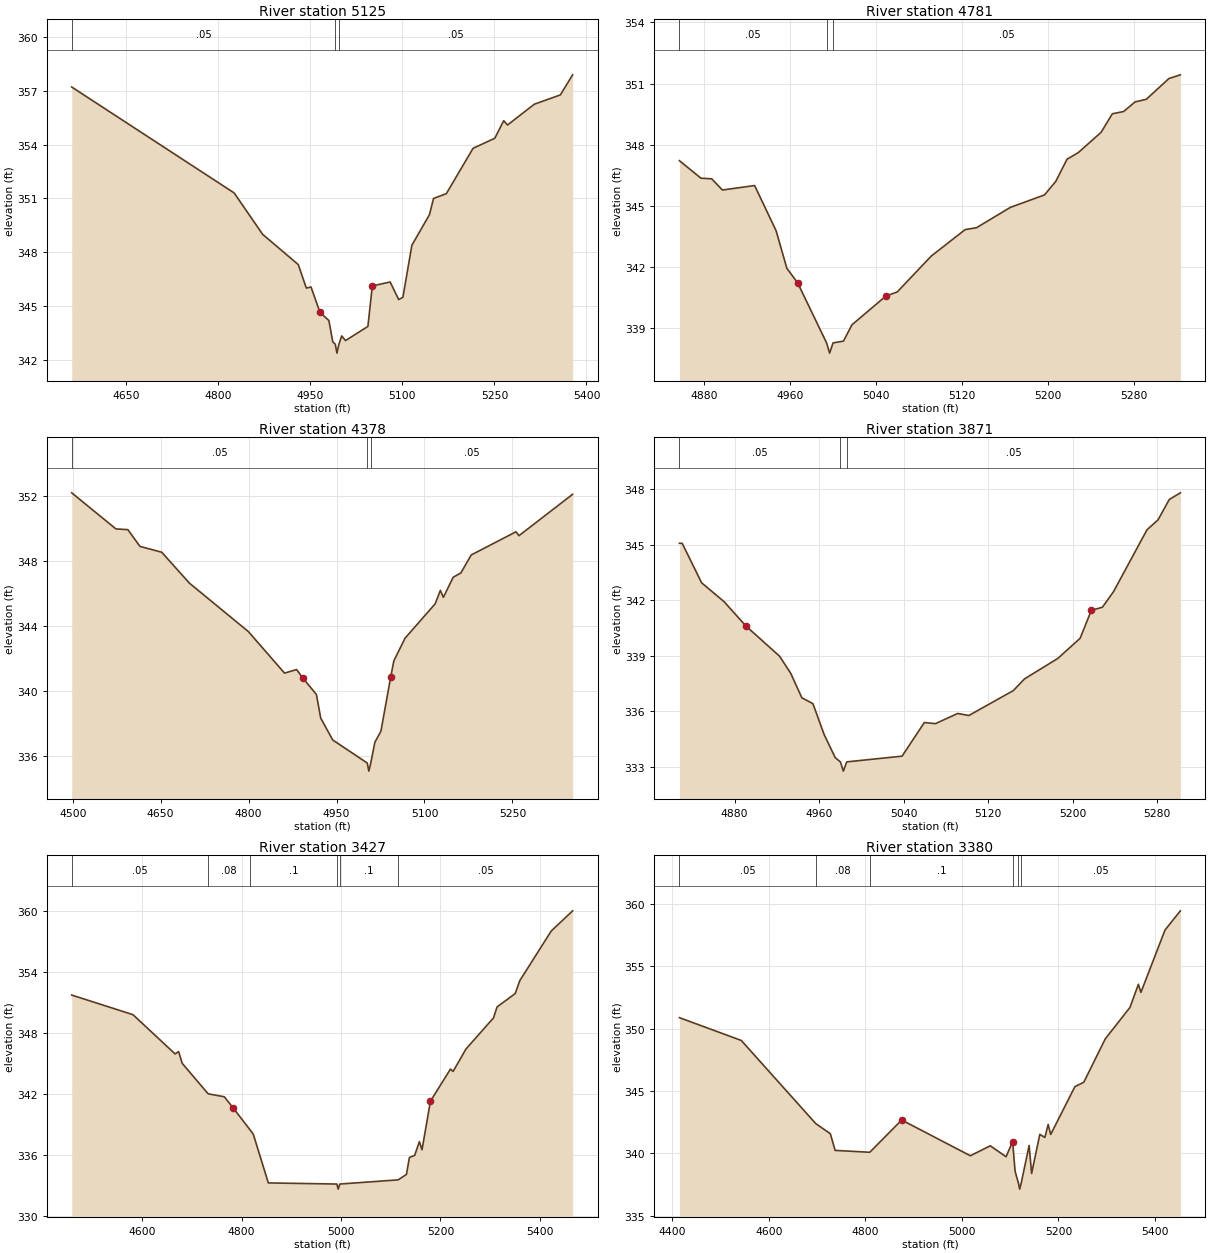
Type RM Length L Ch R = 1 ,5125    ,344,344,344
BEGIN DESCRIPTION:
UNT033 IN BECR 7.0
END DESCRIPTION:
XS GIS Cut Line= 3
      3821270.67      10499322.2      3821225.54      10499013.2
      3820823.67     10498708.34
#Sta/Elev= 30
  4560.8  357.21  4825.6   351.3  4872.1  348.99  4930.2   347.3  4943.3  345.99
    4951  346.05  4965.6  344.63  4980.1  344.18  4986.4  342.99  4990.5  342.86
  4993.2  342.36  4996.5  342.86    5001  343.32  5007.2  343.06  5043.7  343.85
  5050.9  346.11    5080  346.33  5093.9  345.35  5100.8  345.48  5115.4  348.38
  5144.1  350.09  5150.7  350.99  5171.6  351.26  5215.2  353.79  5250.6  354.35
  5265.1  355.33  5271.4  355.09    5315  356.25  5357.5  356.77  5377.5  357.89
#Mann= 3 ,-1 , 0
  4560.8     .05       0  4990.5     .03       0  4996.5     .05       0
Bank Sta=4965.6,5050.9
XS Rating Curve= 0 ,0
Exp/Cntr=0.3,0.1

Type RM Length L Ch R = 1 ,4781    ,403,403,403
BEGIN DESCRIPTION:
UNT033 IN BECR 6.0
END DESCRIPTION:
XS GIS Cut Line= 3
      3821499.63     10498760.19      3821349.61     10498760.19
      3821049.56     10498660.17
#Sta/Elev= 30
    4857  347.22    4877  346.36    4887  346.33    4897  345.78    4927     346
    4947  343.78    4957  341.94    4967  341.23    4994  338.28  4996.8  337.78
    5000  338.28  5009.7  338.37  5017.6  339.17  5049.2  340.58  5059.7  340.78
  5091.4  342.54    5123  343.84  5133.5  343.93  5165.1  344.93  5196.8  345.54
  5207.3   346.2  5217.8  347.29  5228.4  347.62  5249.5  348.61    5260  349.52
  5270.5  349.63  5281.1   350.1  5291.6  350.23  5312.7  351.25  5323.3  351.43
#Mann= 3 ,-1 , 0
    4857     .05       0    4994     .03       0    5000     .05       0
Bank Sta=4967,5049.2
XS Rating Curve= 0 ,0
Exp/Cntr=0.3,0.1

Type RM Length L Ch R = 1 ,4378    ,507,507,507
BEGIN DESCRIPTION:
UNT033 IN BECR 5.0
END DESCRIPTION:
XS GIS Cut Line= 3
      3821752.86     10498560.79        3821107.     10498408.01
      3820919.48     10498442.74
#Sta/Elev= 30
  4498.3  352.22  4573.6     350  4594.1  349.95  4614.7  348.92  4651.8  348.56
  4699.2  346.65  4799.6  343.67  4861.3  341.11  4881.9  341.33  4892.1  340.83
  4915.7  339.79    4923  338.34  4943.5  336.99  5002.4  335.57  5005.1  335.07
  5008.4  335.57  5015.4  336.85  5025.7  337.53  5042.5  340.89  5047.7  341.86
  5066.8  343.26  5118.2  345.38  5127.1  346.21  5132.2  345.78    5149  347.02
    5162  347.28  5179.7  348.39  5256.1  349.82  5261.2  349.58  5352.7  352.13
#Mann= 3 ,-1 , 0
  4498.3     .05       0  5002.4     .03       0  5008.4     .05       0
Bank Sta=4892.1,5042.5
XS Rating Curve= 0 ,0
Exp/Cntr=0.3,0.1

Type RM Length L Ch R = 1 ,3871    ,444,444,444
BEGIN DESCRIPTION:
UNT033 IN BECR 4.0
END DESCRIPTION:
XS GIS Cut Line= 3
      3821599.56     10498060.17      3821449.61     10498010.19
       3821149.6     10497910.19
#Sta/Elev= 30
  4827.8  345.08  4830.4  345.08  4848.8  342.94  4869.9  341.93    4891  340.59
  4922.6  338.97  4933.2  338.04  4943.7  336.72  4954.2   336.4  4964.8  334.73
  4975.3  333.48  4980.2  333.25    4983  332.75  4986.2  333.25  5038.6  333.56
  5059.7  335.38  5070.2  335.32  5091.3  335.87  5101.8  335.76    5144  337.11
  5154.5  337.74  5186.1  338.85  5207.2  339.94  5217.8  341.45  5228.3  341.62
  5238.8  342.46  5270.5  345.81    5281  346.35  5291.6  347.45  5302.1  347.81
#Mann= 3 ,-1 , 0
  4827.8     .05       0  4980.2     .03       0  4986.2     .05       0
Bank Sta=4891,5217.8
XS Rating Curve= 0 ,0
Exp/Cntr=0.3,0.1

Type RM Length L Ch R = 1 ,3427    ,47,47,47
BEGIN DESCRIPTION:
Mapping XS a41ecd84
END DESCRIPTION:
XS GIS Cut Line= 4
      3821871.34      10497812.8      3821645.63     10497587.09
      3821333.13     10497552.37      3820978.93     10497673.91
#Sta/Elev= 30
    4458  351.76  4581.3  349.83  4666.1  345.97  4673.2   346.2  4680.3  345.05
  4732.6  342.05  4765.1  341.76  4783.3  340.64  4816.3  338.55  4823.5  338.07
  4853.7  333.29  4991.6  333.18  4994.3  332.68  4997.6  333.18  5114.9  333.59
  5131.7  334.13  5137.6  335.79  5148.2     336  5157.7  337.35    5163  336.55
  5179.9  341.32  5220.2  344.48  5225.5  344.25  5251.5  346.46  5306.8  349.51
    5314  350.59  5350.6  351.91  5359.7  353.17  5423.1  358.06  5466.1  360.04
#Mann= 6 ,-1 , 0
    4458     .05       0  4732.6     .08       0  4816.3      .1       0
  4991.6     .07       0  4997.6      .1       0  5114.9     .05       0
Bank Sta=4783.3,5179.9
XS Rating Curve= 0 ,0
Exp/Cntr=0.3,0.1

Type RM Length L Ch R = 1 ,3380    ,74,74,74
BEGIN DESCRIPTION:
UNT033 IN BECR 3.0
END DESCRIPTION:
XS GIS Cut Line= 5
      3821888.71     10497781.56      3821680.35     10497535.01
      3821433.83     10497517.64      3821329.66      10497510.7
      3820978.93     10497607.93
#Sta/Elev= 30
  4414.4  350.89  4542.6  349.06    4697  342.38  4727.2  341.57  4737.1  340.23
  4808.9  340.08  4875.1  342.67  5017.4   339.8  5058.7   340.6  5091.4  339.72
    5105  340.94  5106.2  340.38  5110.1  338.56  5116.9  337.62  5119.7  337.12
  5122.9  337.62  5139.2  340.63  5144.4  338.38  5161.4  341.52  5171.8  341.27
  5178.7  342.31  5183.9  341.51  5234.1  345.35  5252.5   345.7  5297.1  349.19
  5348.2  351.71  5365.7  353.57  5370.9  352.92  5420.9  357.93  5452.7  359.47
#Mann= 6 ,-1 , 0
  4414.4     .05       0    4697     .08       0  4808.9      .1       0
  5106.2     .05       0  5116.9     .07       0  5122.9     .05       0
Bank Sta=4875.1,5105
XS Rating Curve= 0 ,0
Exp/Cntr=0.3,0.1

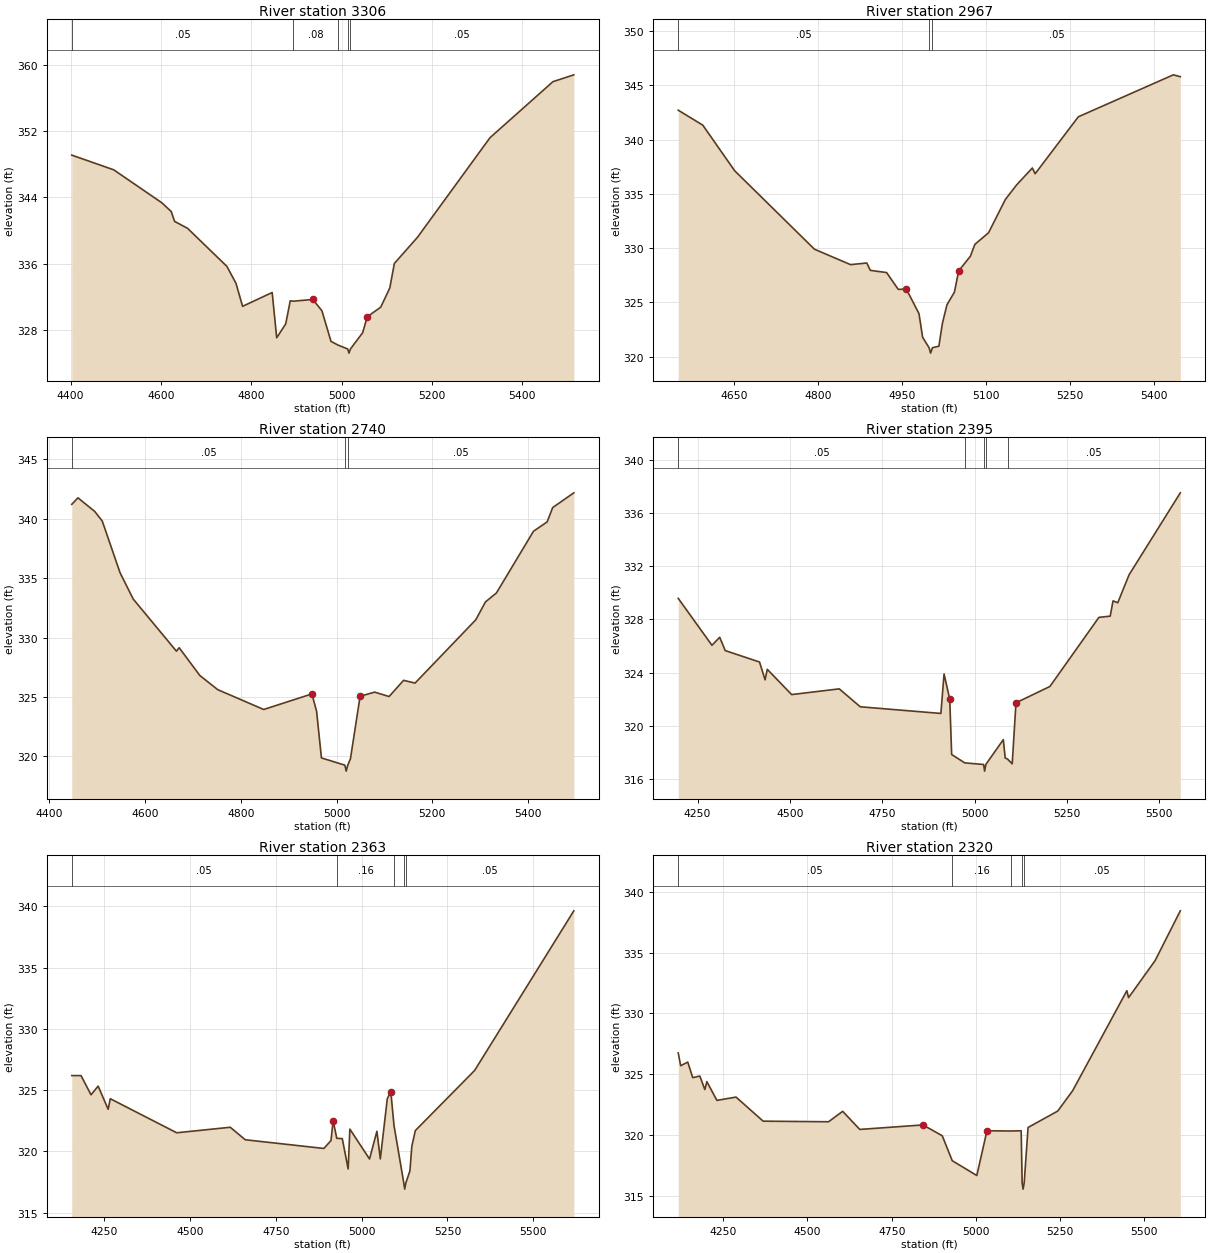
Type RM Length L Ch R = 1 ,3306    ,339,339,339
BEGIN DESCRIPTION:
Mapping XS f13e9d54
END DESCRIPTION:
XS GIS Cut Line= 4
      3821895.35     10497695.57      3821688.32      10497458.6
      3821256.03     10497435.16       3820916.4     10497565.29
#Sta/Elev= 30
  4402.5  349.11  4495.4  347.33  4601.7  343.35  4622.6  342.29  4630.2  341.09
  4658.7  340.26  4745.9  335.65    4766   333.6  4780.6  330.82  4846.1  332.49
  4856.1  327.02  4876.1   328.7  4886.1  331.49  4892.7  331.44  4936.2  331.65
  4956.2  330.28  4976.3  326.58  4991.5  326.14  5013.3  325.66  5016.1  325.16
  5019.3  325.66  5046.4  327.63  5056.4  329.55  5086.4  330.72  5106.5  333.05
  5116.5     336  5167.7  339.17  5328.3  351.22  5467.5  357.99  5513.8  358.82
#Mann= 5 ,-1 , 0
  4402.5     .05       0  4892.7     .08       0  4991.5     .05       0
  5013.3     .04       0  5019.3     .05       0
Bank Sta=4936.2,5056.4
XS Rating Curve= 0 ,0
Exp/Cntr=0.3,0.1

Type RM Length L Ch R = 1 ,2967    ,227,227,227
BEGIN DESCRIPTION:
UNT033 IN BECR 2.0
END DESCRIPTION:
XS GIS Cut Line= 3
      3821899.14     10497462.12      3821468.55     10497128.76
      3821117.88     10497114.87
#Sta/Elev= 30
  4550.8  342.72  4594.6  341.34  4651.4  337.14  4793.8   329.9  4858.1  328.48
  4887.1  328.63  4893.4  327.95  4922.4  327.75  4943.2   326.2  4957.7  326.22
  4980.2  323.96  4986.7  321.78  4998.2  320.82  5000.9  320.32  5004.2  320.82
  5015.7  320.96    5022  323.07  5030.1  324.78  5043.4  325.94    5051   327.9
  5071.8  329.25  5079.9  330.35  5104.3  331.42  5134.3  334.49  5154.3  335.83
  5182.4  337.39  5187.4  336.86  5264.4  342.11  5433.9  345.98  5446.3  345.81
#Mann= 3 ,-1 , 0
  4550.8     .05       0  4998.2     .03       0  5004.2     .05       0
Bank Sta=4957.7,5051
XS Rating Curve= 0 ,0
Exp/Cntr=0.3,0.1

Type RM Length L Ch R = 1 ,2740    ,345,345,345
BEGIN DESCRIPTION:
Mapping XS 72e0a17f
END DESCRIPTION:
XS GIS Cut Line= 4
      3821985.89     10497361.37      3821781.05     10497007.23
      3821454.66     10496962.09      3821145.62     10496989.87
#Sta/Elev= 30
  4446.8  341.19  4459.7  341.74  4494.7   340.6  4510.5  339.79  4547.8  335.43
  4575.2  333.23  4665.5  328.85  4671.2  329.14  4714.3  326.81  4751.6  325.62
  4847.8  323.95  4948.5  325.26  4958.3  323.79  4968.4  319.88  5017.4  319.27
  5020.1  318.77  5023.4  319.27    5029  319.81  5049.2  325.06  5079.5  325.41
  5109.7  325.04    5140   326.4    5164  326.17  5290.9  331.49    5311  332.99
  5333.9  333.74  5411.4  338.93    5440  339.72  5451.5  340.92  5495.7  342.16
#Mann= 3 ,-1 , 0
  4446.8     .05       0  5017.4     .03       0  5023.4     .05       0
Bank Sta=4948.5,5049.2
XS Rating Curve= 0 ,0
Exp/Cntr=0.3,0.1

Type RM Length L Ch R = 1 ,2395    ,32,32,32
BEGIN DESCRIPTION:
Mapping XS ac20a897
END DESCRIPTION:
XS GIS Cut Line= 4
       3822187.3     10497288.47      3821791.46     10496701.67
      3821676.88     10496673.89      3821153.62     10496781.32
#Sta/Elev= 30
  4197.5  329.59  4288.8  326.06  4309.8  326.66  4324.8  325.66  4417.7   324.8
  4432.7  323.46  4438.7  324.25  4504.7  322.35  4633.6  322.78  4690.6  321.43
  4908.9  320.93  4917.5   323.9  4932.9     322  4938.1  317.84  4973.6  317.21
  5024.6  317.09  5027.4  316.59  5030.6  317.09    5078  318.96  5083.1  317.58
  5089.4   317.5  5102.1  317.14  5112.3  321.73  5204.2  322.96  5336.9  328.16
  5367.5  328.25  5375.2   329.4    5388  329.26  5418.6  331.36  5557.4  337.53
#Mann= 5 ,-1 , 0
  4197.5     .05       0  4973.6     .16       0  5024.6     .07       0
  5030.6     .16       0  5089.4     .05       0
Bank Sta=4932.9,5112.3
XS Rating Curve= 0 ,0
Exp/Cntr=0.3,0.1

Type RM Length L Ch R = 1 ,2363    ,43,43,43
BEGIN DESCRIPTION:
Mapping XS b9d75efe
END DESCRIPTION:
XS GIS Cut Line= 5
       3822249.8     10497278.07      3821784.52     10496660.01
       3821687.3     10496646.12       3821649.1     10496649.59
      3821107.47     10496764.16
#Sta/Elev= 30
  4154.9  326.18  4181.9  326.18    4211  324.61  4231.8  325.32    4261  323.43
  4267.2  324.29  4460.9  321.51    4617  321.96  4660.8  320.94  4889.8  320.23
  4910.6  320.87  4916.9   322.5  4927.5  321.06  4943.6  321.03  4960.7  318.56
  4965.7  321.81    5023  319.37  5044.5  321.63  5054.5  319.38  5074.8  324.29
    5085  324.88  5094.4   322.1  5122.9  317.41  5125.6  316.91  5128.9  317.41
  5140.8   318.4  5146.3   320.4  5156.6  321.69  5329.5   326.6  5618.7  339.63
#Mann= 5 ,-1 , 0
  4154.9     .05       0  4927.5     .16       0  5094.4     .05       0
  5122.9     .07       0  5128.9     .05       0
Bank Sta=4916.9,5085
XS Rating Curve= 0 ,0
Exp/Cntr=0.3,0.1

Type RM Length L Ch R = 1 ,2320    ,300,300,300
BEGIN DESCRIPTION:
Mapping XS fcd42d5c
END DESCRIPTION:
XS GIS Cut Line= 5
      3822270.62     10497288.46      3821833.13     10496653.06
       3821774.1     10496614.87      3821680.35     10496607.92
      3821136.12     10496715.38
#Sta/Elev= 30
  4116.3  326.74  4123.6  325.69  4144.5  325.99  4159.4  324.71  4180.4  324.84
  4195.3  323.73  4201.3  324.38  4231.1  322.84  4287.9  323.11  4368.4  321.13
  4562.5  321.08  4604.5  321.94  4655.2  320.45  4842.7  320.82  4900.1  319.93
  4929.7  317.88  5002.7  316.66  5032.8  320.34  5102.8  320.32  5134.4  320.34
  5137.3  316.04  5140.1  315.54  5143.3  316.04  5154.8  320.61  5242.9  321.96
  5287.3  323.64  5448.1  331.86  5453.2  331.29  5531.9  334.33  5606.8  338.43
#Mann= 5 ,-1 , 0
  4116.3     .05       0  4929.7     .16       0  5102.8     .05       0
  5137.3     .07       0  5143.3     .05       0
Bank Sta=4842.7,5032.8
XS Rating Curve= 0 ,0
Exp/Cntr=0.3,0.1

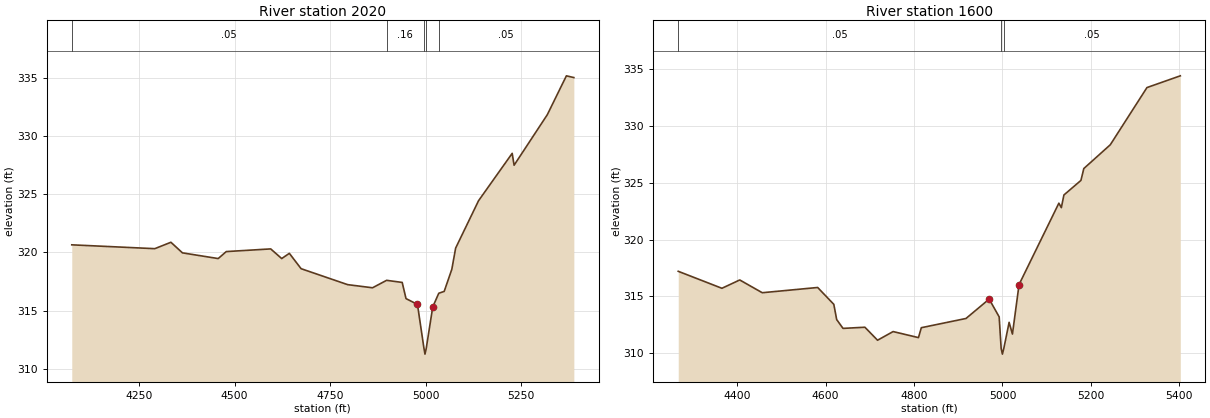
Type RM Length L Ch R = 1 ,2020    ,422,422,422
BEGIN DESCRIPTION:
Mapping XS ca16339f
END DESCRIPTION:
XS GIS Cut Line= 4
      3822174.83      10497084.7      3821924.83     10496699.29
       3821867.2     10496375.93      3821340.11     10496389.17
#Sta/Elev= 30
  4073.3  320.65  4290.7  320.32    4333  320.87  4363.2  319.96  4456.9  319.47
    4478  320.07  4594.4   320.3  4623.2  319.47  4643.2  319.92    4674   318.6
  4795.9  317.23  4861.1  316.96    4898   317.6  4938.8  317.42  4948.8  316.03
  4978.8  315.53  4995.8  311.76  4998.5  311.26  5001.8  311.76  5018.8  315.31
  5034.6  316.49  5048.8  316.65  5068.8  318.55  5078.8  320.37  5138.8  324.44
  5226.9  328.51  5231.9  327.49  5318.9  331.83  5368.9  335.17  5388.4  335.02
#Mann= 5 ,-1 , 0
  4073.3     .05       0    4898     .16       0  4995.8     .07       0
  5001.8     .16       0  5034.6     .05       0
Bank Sta=4978.8,5018.8
XS Rating Curve= 0 ,0
Exp/Cntr=0.3,0.1

Type RM Length L Ch R = 1 ,1600    ,0,0,0
BEGIN DESCRIPTION:
UNT033 IN BECR 1.0
END DESCRIPTION:
XS GIS Cut Line= 4
      3822086.29     10496506.61      3822146.19      10496204.5
      3821956.08     10495975.33      3821485.92     10496219.02
#Sta/Elev= 30
  4266.8  317.21  4365.6  315.72  4405.9  316.45  4456.8  315.33  4582.1  315.79
  4618.6  314.31  4625.1  312.97  4639.4   312.2  4688.9   312.3  4717.5  311.16
  4752.7  311.92    4810  311.39  4816.5  312.26  4917.5  313.07  4969.9  314.77
  4992.5  313.21    4997  310.44  4999.8  309.94    5003  310.44    5015  312.73
  5022.5   311.7  5037.5  316.05  5127.5  323.19  5133.1   322.8  5138.9  323.91
  5177.4  325.19  5183.9  326.23  5243.8  328.32  5326.7  333.34  5402.1  334.37
#Mann= 3 ,-1 , 0
  4266.8     .05       0    4997     .03       0    5003     .05       0
Bank Sta=4969.9,5037.5
XS Rating Curve= 0 ,0
Exp/Cntr=0.3,0.1

Chan Stop Cuts=-1
Use User Specified Reach Order=0
Composite Channel Slope=5