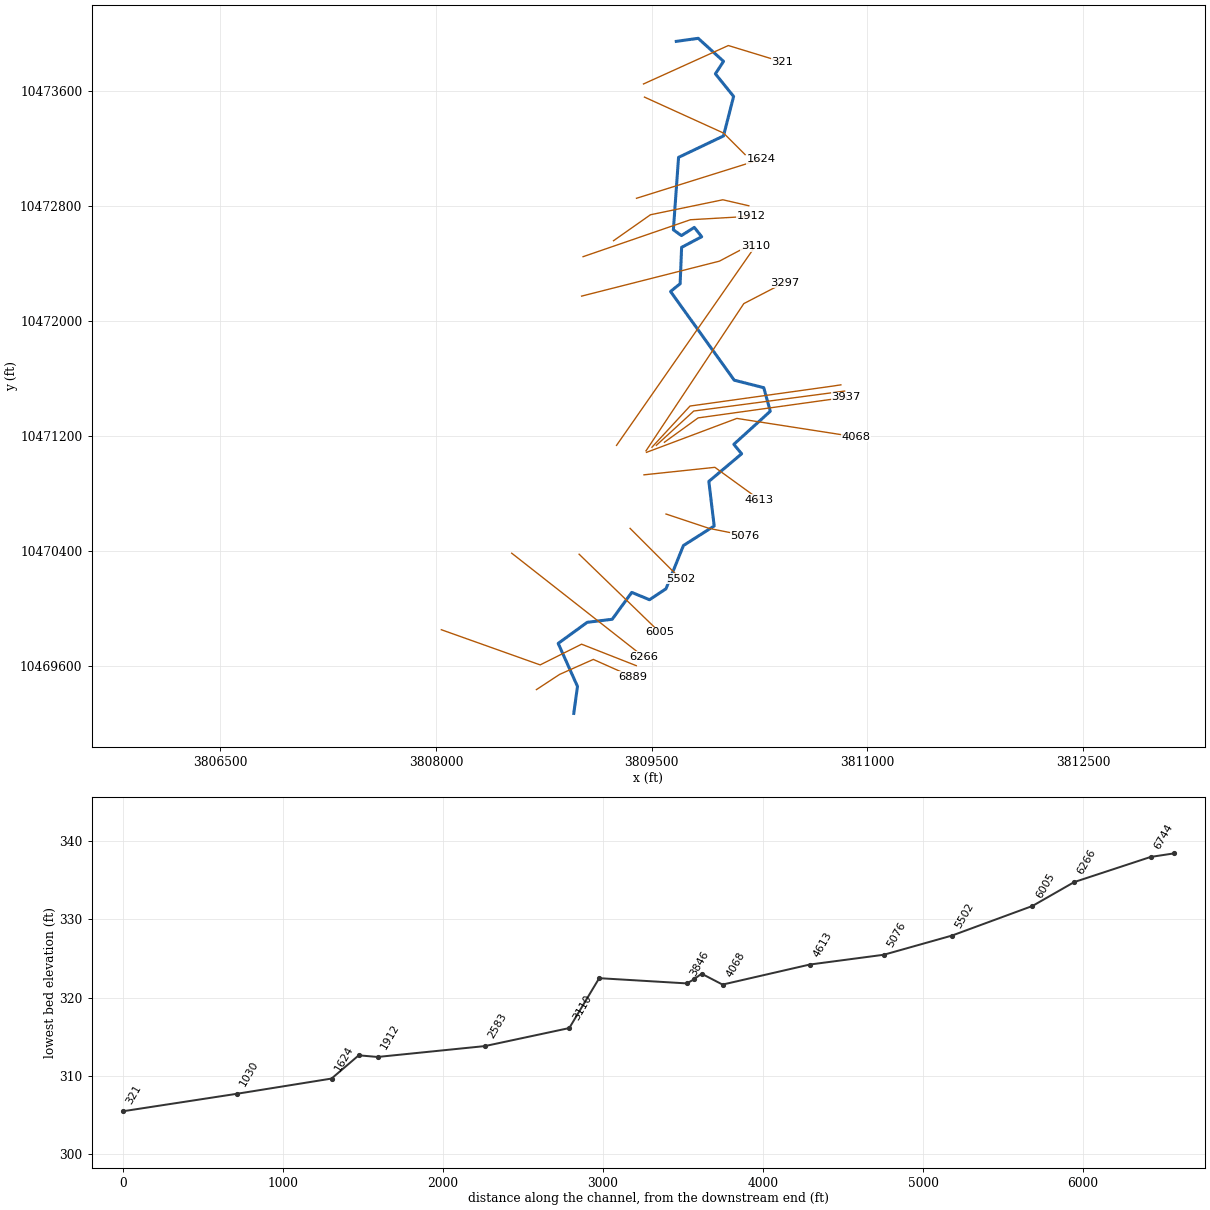
--- UNT038 IN BECR.prj (project) ---

Proj Title=UNT038 IN BECR Base Level Engineering
Current Plan=p01
Default Exp/Contr=0.3,0.1
English Units
Geom File=g01
Flow File=f01
Plan File=p01
BEGIN DESCRIPTION:
UNT038 IN BECR
END DESCRIPTION:

--- UNT038 IN BECR.p01 (plan) ---

Plan Title=Multiple Run
Short Identifier=Multiple
Geom File=g01
Flow File=f01
Subcritical Flow
K Sum by GR= 0
Std Step Tol= 0.01
Critical Tol= 0.01
Num of Std Step Trials= 20
Max Error Tol= 0.3
Flow Tol Ratio= 0.001
Split Flow NTrial= 30
Split Flow Tol= 0.02
Split Flow Ratio= 0.02
Log Output Level= 0
Friction Slope Method= 1
Unsteady Friction Slope Method= 2
Unsteady Bridges Friction Slope Method= 1
Parabolic Critical Depth
Global Vel Dist=  1 , 1 , 1
Global Log Level= 0
CheckData=True
Encroach Param= -1, 0, 0, 0
BEGIN DESCRIPTION:
Multiple Run
END DESCRIPTION:

--- UNT038 IN BECR.f01 (steady flow) ---

Flow Title=Multiple
Number of Profiles=7
Profile Names=10-year,25-year,50-year,1pct_min,100-year,1pct_plu,500-year
River Rch & RM= UNT038 IN BECR,Reach-1,6889
     762    1040    1271    1141    1543    2087    2283
Boundary for River Rch & Prof#=UNT038 IN BECR,Reach-1,1
Up Type=0
Dn Type=3
Dn Slope=0.005
Boundary for River Rch & Prof#=UNT038 IN BECR,Reach-1,2
Up Type=0
Dn Type=3
Dn Slope=0.005
Boundary for River Rch & Prof#=UNT038 IN BECR,Reach-1,3
Up Type=0
Dn Type=3
Dn Slope=0.005
Boundary for River Rch & Prof#=UNT038 IN BECR,Reach-1,4
Up Type=0
Dn Type=3
Dn Slope=0.005
Boundary for River Rch & Prof#=UNT038 IN BECR,Reach-1,5
Up Type=0
Dn Type=3
Dn Slope=0.005
Boundary for River Rch & Prof#=UNT038 IN BECR,Reach-1,6
Up Type=0
Dn Type=3
Dn Slope=0.005
Boundary for River Rch & Prof#=UNT038 IN BECR,Reach-1,7
Up Type=0
Dn Type=3
Dn Slope=0.005

--- UNT038 IN BECR.g01 (geometry) ---

Geom Title=Existing Conditions

River Reach=UNT038 IN BECR,Reach-1
Reach XY= 30
      3808957.88     10469273.50      3808983.75     10469461.00
      3808849.61     10469760.19      3809051.75     10469907.00
      3809225.25     10469928.00      3809361.25     10470115.00
      3809484.50     10470064.00      3809599.25     10470140.00
      3809720.75     10470441.00      3809934.50     10470577.00
      3809897.50     10470887.00      3810125.50     10471079.00
      3810071.25     10471145.00      3810324.75     10471375.00
      3810279.25     10471539.00      3810074.25     10471591.00
      3809631.00     10472208.00      3809697.75     10472262.00
      3809708.00     10472515.00      3809847.50     10472589.00
      3809796.50     10472654.00      3809706.50     10472597.00
      3809650.75     10472637.00      3809686.75     10473141.00
      3809999.25     10473290.00      3810069.75     10473565.00
      3809943.00     10473722.00      3809999.50     10473809.00
      3809823.50     10473969.00      3809671.00     10473948.00

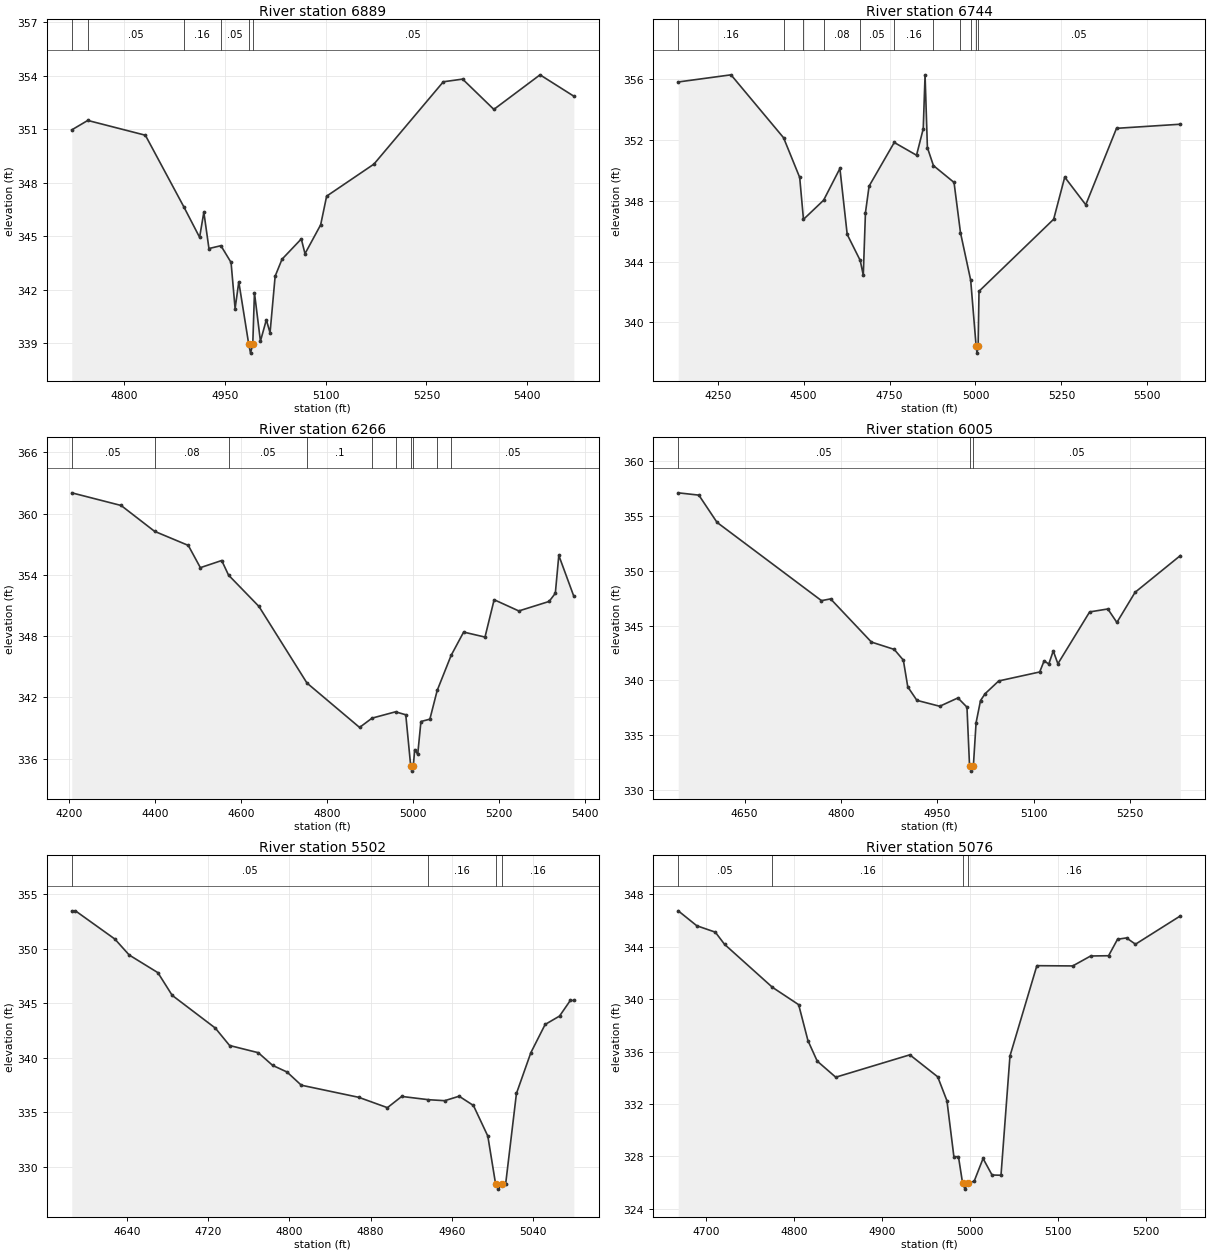
Type RM Length L Ch R = 1,6889,145,145,145
BEGIN DESCRIPTION:
UNT038 IN BECR 14.0
END DESCRIPTION:
XS GIS Cut Line= 4
      3808698.07     10469438.75      3808859.54     10469544.66
      3809093.92     10469648.83      3809365.55     10469527.71
#Sta/Elev= 30
  4722.4  350.96  4746.2  351.49  4831.9  350.66  4889.0  346.65  4912.6  344.93
  4918.9  346.34  4926.5  344.30  4944.3  344.46  4959.4  343.52  4965.4  340.93
  4970.9  342.43  4985.7  338.93  4988.4  338.43  4991.7  338.93  4994.2  341.82
  5003.1  339.10  5011.9  340.30  5017.4  339.57  5025.0  342.75  5035.2  343.70
  5063.9  344.84  5069.4  344.01  5092.7  345.63  5101.6  347.24  5172.0  349.04
  5275.2  353.66  5303.9  353.81  5350.4  352.11  5419.1  354.05  5469.4  352.85
#Mann=6,-1,0
  4722.4    0.16       0  4746.2    0.05       0  4889.0    0.16       0
  4944.3    0.05       0  4985.7    0.04       0  4991.7    0.05       0
Bank Sta=4985.7,4991.7
Exp/Cntr=0.3,0.1

Type RM Length L Ch R = 1,6744,478,478,478
BEGIN DESCRIPTION:
UNT038 IN BECR 13.0
END DESCRIPTION:
XS GIS Cut Line= 4
      3808036.58     10469855.44      3808724.13     10469610.63
      3809012.32     10469754.73      3809392.52     10469605.43
#Sta/Elev= 30
  4135.3  355.82  4288.8  356.29  4441.7  352.15  4488.6  349.54  4499.6  346.78
  4558.2  348.04  4605.6  350.13  4626.8  345.79  4664.6  344.08  4673.6  343.11
  4679.9  347.22  4690.5  348.97  4763.7  351.84  4828.5  351.00  4848.0  352.74
  4853.3  356.27  4860.1  351.50  4877.6  350.32  4937.6  349.21  4956.3  345.91
  4986.0  342.78  5001.7  338.48  5004.4  337.98  5007.7  338.48  5010.2  342.05
  5227.4  346.79  5259.6  349.56  5320.8  347.74  5410.2  352.77  5595.8  353.04
#Mann=11,-1,0
  4135.3    0.16       0  4441.7    0.12       0  4499.6    0.05       0
  4558.2    0.08       0  4664.6    0.05       0  4763.7    0.16       0
  4877.6    0.08       0  4956.3    0.16       0  4986.0    0.05       0
  5001.7    0.03       0  5007.7    0.05       0
Bank Sta=5001.7,5007.7
Exp/Cntr=0.3,0.1

Type RM Length L Ch R = 1,6266,261,261,261
BEGIN DESCRIPTION:
Mapping XS 06073c59
END DESCRIPTION:
XS GIS Cut Line= 2
      3808526.24     10470387.69      3809445.50     10469666.16
#Sta/Elev= 30
  4206.1  362.03  4321.0  360.79  4398.8  358.26  4477.3  356.88  4505.4  354.70
  4555.1  355.40  4571.0  353.97  4641.8  350.90  4753.5  343.40  4876.0  339.05
  4905.0  339.96  4959.6  340.58  4983.5  340.29  4995.0  335.27  4997.7  334.77
  5001.0  335.27  5004.3  336.88  5011.3  336.41  5018.8  339.63  5039.6  339.86
  5056.6  342.67  5089.1  346.11  5118.2  348.39  5167.9  347.90  5189.2  351.56
  5246.6  350.46  5317.1  351.39  5331.6  352.19  5339.7  355.90  5374.7  351.89
#Mann=10,-1,0
  4206.1    0.05       0  4398.8    0.08       0  4571.0    0.05       0
  4753.5     0.1       0  4905.0    0.16       0  4959.6    0.05       0
  4995.0    0.03       0  5001.0    0.05       0  5056.6    0.08       0
  5089.1    0.05       0
Bank Sta=4995,5001
Exp/Cntr=0.3,0.1

Type RM Length L Ch R = 1,6005,503,503,503
BEGIN DESCRIPTION:
UNT038 IN BECR 12.0
END DESCRIPTION:
XS GIS Cut Line= 2
      3808994.95     10470380.78      3809556.00     10469837.04
#Sta/Elev= 30
  4546.6  357.12  4578.7  356.91  4607.0  354.42  4769.5  347.28  4783.7  347.44
  4847.2  343.50  4882.7  342.83  4896.9  341.85  4903.8  339.41  4918.0  338.18
  4953.5  337.64  4981.8  338.40  4995.9  337.56  4999.9  332.22  5002.6  331.72
  5005.9  332.22  5010.1  336.14  5017.0  338.16  5024.2  338.79  5045.3  339.95
  5109.1  340.77  5116.0  341.79  5123.2  341.49  5130.2  342.69  5137.4  341.52
  5186.8  346.25  5215.1  346.52  5229.2  345.29  5257.5  348.04  5327.9  351.39
#Mann=3,-1,0
  4546.6    0.05       0  4999.9    0.03       0  5005.9    0.05       0
Bank Sta=4999.9,5005.9
Exp/Cntr=0.3,0.1

Type RM Length L Ch R = 1,5502,426,426,426
BEGIN DESCRIPTION:
UNT038 IN BECR 11.0
END DESCRIPTION:
XS GIS Cut Line= 3
      3809349.58     10470560.22      3809649.61     10470260.19
      3809699.60     10470210.20
#Sta/Elev= 30
  4585.4  353.46  4589.0  353.46  4627.9  350.87  4642.0  349.41  4670.3  347.79
  4684.4  345.71  4726.9  342.71  4741.0  341.11  4769.3  340.45  4783.4  339.29
  4797.6  338.68  4811.7  337.47  4868.3  336.36  4896.6  335.41  4910.7  336.44
  4937.1  336.14  4953.1  336.05  4967.3  336.46  4981.4  335.61  4995.6  332.80
  5003.2  328.44  5005.9  327.94  5009.2  328.44  5013.2  328.44  5023.8  336.71
  5038.0  340.45  5052.1  343.04  5066.3  343.81  5076.9  345.24  5080.4  345.24
#Mann=4,-1,0
  4585.4    0.05       0  4937.1    0.16       0  5003.2    0.07       0
  5009.2    0.16       0
Bank Sta=5003.2,5009.2
Exp/Cntr=0.3,0.1

Type RM Length L Ch R = 1,5076,463,463,463
BEGIN DESCRIPTION:
UNT038 IN BECR 10.0
END DESCRIPTION:
XS GIS Cut Line= 3
      3809599.60     10470660.19      3809899.61     10470560.19
      3810149.62     10470510.19
#Sta/Elev= 30
  4668.4  346.75  4689.5  345.61  4710.6  345.12  4721.1  344.19  4775.5  340.91
  4805.4  339.58  4816.0  336.83  4826.5  335.27  4847.6  334.04  4931.9  335.75
  4963.6  334.07  4974.1  332.24  4982.0  327.97  4987.2  327.97  4991.8  325.99
  4994.6  325.49  4997.8  325.99  5005.0  326.08  5015.2  327.83  5025.4  326.57
  5035.6  326.55  5045.8  335.66  5076.4  342.56  5117.2  342.54  5137.6  343.30
  5158.0  343.32  5168.2  344.58  5178.4  344.68  5188.6  344.20  5239.6  346.36
#Mann=4,-1,0
  4668.4    0.05       0  4775.5    0.16       0  4991.8    0.07       0
  4997.8    0.16       0
Bank Sta=4991.8,4997.8
Exp/Cntr=0.3,0.1

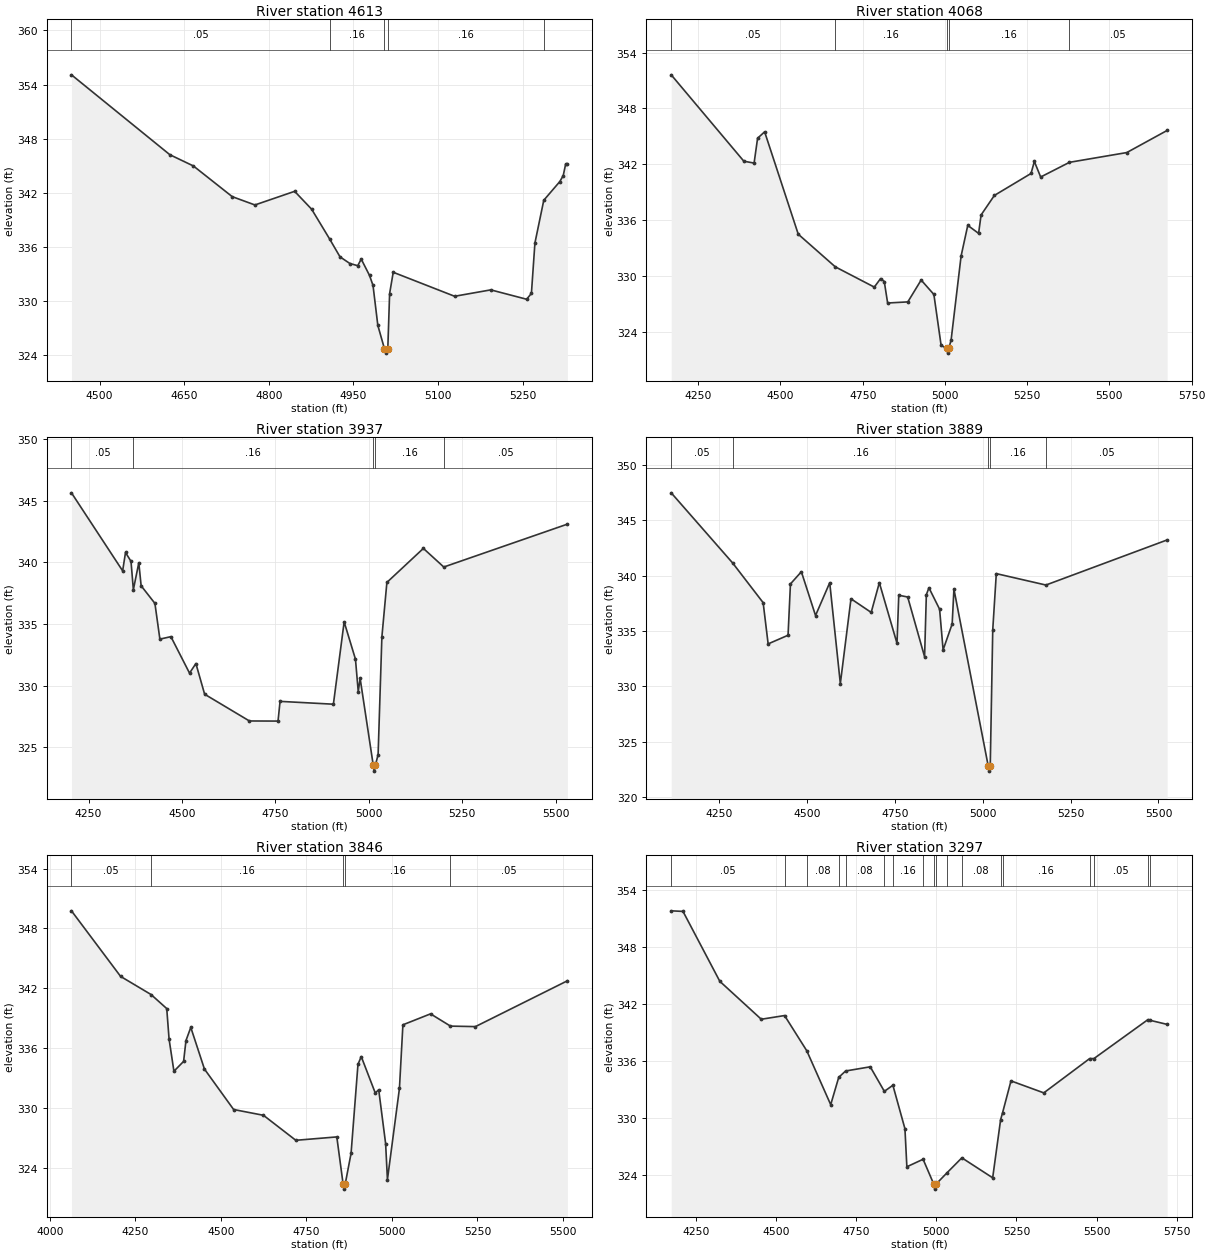
Type RM Length L Ch R = 1,4613,545,545,545
BEGIN DESCRIPTION:
UNT038 IN BECR 9.0
END DESCRIPTION:
XS GIS Cut Line= 3
      3809446.32     10470932.85      3809939.40     10470984.94
      3810249.62     10470760.18
#Sta/Elev= 30
  4450.2  355.08  4624.5  346.23  4666.3  344.98  4735.1  341.58  4775.3  340.66
  4845.7  342.17  4875.8  340.19  4907.5  336.91  4926.1  334.91  4943.6  334.17
  4957.5  333.93  4963.7  334.66  4978.4  332.85  4984.6  331.74  4993.1  327.32
  5004.8  324.74  5007.6  324.24  5010.8  324.74  5014.0  330.83  5020.4  333.20
  5129.2  330.54  5193.3  331.25  5256.8  330.21  5265.3  330.86  5271.5  336.44
  5287.2  341.18  5315.6  343.25  5321.7  343.92  5326.0  345.20  5329.1  345.20
#Mann=5,-1,0
  4450.2    0.05       0  4907.5    0.16       0  5004.8    0.07       0
  5010.8    0.16       0  5287.2     0.1       0
Bank Sta=5004.8,5010.8
Exp/Cntr=0.3,0.1

Type RM Length L Ch R = 1,4068,131,131,131
BEGIN DESCRIPTION:
UNT038 IN BECR 8.0
END DESCRIPTION:
XS GIS Cut Line= 3
      3809463.74     10471089.12      3810092.18     10471325.21
      3810918.53     10471196.75
#Sta/Elev= 30
  4167.9  351.61  4388.7  342.32  4419.9  342.12  4430.5  344.79  4451.9  345.48
  4554.1  334.47  4666.7  330.96  4785.3  328.78  4804.4  329.70  4815.6  329.38
  4825.8  327.07  4887.2  327.19  4927.7  329.54  4966.4  327.99  4988.4  322.51
  5005.7  322.18  5008.4  321.68  5011.7  322.18  5018.8  323.10  5049.1  332.12
  5069.4  335.42  5102.3  334.56  5109.9  336.54  5150.3  338.64  5261.7  341.00
  5271.8  342.29  5291.0  340.62  5378.5  342.20  5552.8  343.25  5675.5  345.63
#Mann=5,-1,0
  4167.9    0.05       0  4666.7    0.16       0  5005.7    0.07       0
  5011.7    0.16       0  5378.5    0.05       0
Bank Sta=5005.7,5011.7
Exp/Cntr=0.3,0.1

Type RM Length L Ch R = 1,3937,48,48,48
BEGIN DESCRIPTION:
Mapping XS 6ec2dac9
END DESCRIPTION:
XS GIS Cut Line= 3
      3809588.53     10471159.58      3809822.92     10471328.86
      3810851.57     10471472.09
#Sta/Elev= 30
  4204.2  345.65  4341.2  339.32  4348.9  340.81  4363.6  340.09  4369.9  337.79
  4384.5  339.98  4390.7  338.11  4427.6  336.68  4440.9  333.78  4470.4  333.98
  4520.3  331.02  4537.3  331.80  4560.7  329.31  4680.5  327.14  4757.2  327.13
  4762.6  328.73  4905.4  328.50  4934.2  335.18  4964.5  332.15  4971.9  329.53
  4977.0  330.59  5012.0  323.57  5014.8  323.07  5018.0  323.57  5025.1  324.41
  5035.2  333.96  5048.6  338.38  5146.3  341.14  5200.9  339.63  5531.9  343.11
#Mann=5,-1,0
  4204.2    0.05       0  4369.9    0.16       0  5012.0    0.07       0
  5018.0    0.16       0  5200.9    0.05       0
Bank Sta=5012,5018
Exp/Cntr=0.3,0.1

Type RM Length L Ch R = 1,3889,43,43,43
BEGIN DESCRIPTION:
Mapping XS e6df9247
END DESCRIPTION:
XS GIS Cut Line= 3
      3809532.14     10471137.90      3809792.54     10471376.60
      3810841.76     10471515.34
#Sta/Elev= 30
  4113.2  347.47  4288.1  341.14  4374.9  337.56  4389.1  333.84  4445.8  334.62
  4452.6  339.25  4483.7  340.35  4524.0  336.40  4564.4  339.36  4594.6  330.26
  4624.9  337.91  4682.4  336.68  4705.6  339.36  4755.9  333.89  4760.9  338.23
  4786.3  338.07  4834.4  332.68  4839.4  338.28  4846.8  338.90  4877.1  336.97
  4887.1  333.30  4912.9  335.64  4917.9  338.78  5015.3  322.86  5018.0  322.36
  5021.3  322.86  5028.4  335.11  5038.5  340.18  5179.7  339.15  5524.8  343.22
#Mann=5,-1,0
  4113.2    0.05       0  4288.1    0.16       0  5015.3    0.07       0
  5021.3    0.16       0  5179.7    0.05       0
Bank Sta=5015.3,5021.3
Exp/Cntr=0.3,0.1

Type RM Length L Ch R = 1,3846,549,549,549
BEGIN DESCRIPTION:
Mapping XS 2d5367a3
END DESCRIPTION:
XS GIS Cut Line= 4
      3809501.71     10471124.83      3809766.50     10471411.32
      3810760.42     10471550.21      3810815.77     10471558.73
#Sta/Elev= 30
  4063.3  349.76  4206.9  343.18  4295.9  341.36  4341.8  339.95  4348.6  336.89
  4362.8  333.66  4391.1  334.65  4398.0  336.74  4412.1  338.06  4452.0  333.88
  4537.3  329.82  4624.5  329.24  4719.1  326.73  4838.9  327.07  4857.4  322.33
  4860.2  321.83  4863.4  322.33  4880.6  325.42  4900.8  334.36  4910.4  335.13
  4951.3  331.48  4961.4  331.80  4981.6  326.40  4986.9  322.79  5022.0  331.94
  5032.1  338.32  5112.9  339.42  5171.2  338.19  5244.1  338.14  5513.0  342.74
#Mann=5,-1,0
  4063.3    0.05       0  4295.9    0.16       0  4857.4    0.07       0
  4863.4    0.16       0  5171.2    0.05       0
Bank Sta=4857.4,4863.4
Exp/Cntr=0.3,0.1

Type RM Length L Ch R = 1,3297,187,187,187
BEGIN DESCRIPTION:
UNT038 IN BECR 7.0
END DESCRIPTION:
XS GIS Cut Line= 3
      3809460.25     10471099.54      3810140.79     10472123.83
      3810422.07     10472269.68
#Sta/Elev= 30
  4173.5  351.76  4210.3  351.70  4325.1  344.35  4454.4  340.36  4527.0  340.75
  4596.4  337.04  4670.9  331.38  4695.9  334.25  4717.3  334.92  4794.2  335.36
  4838.2  332.78  4864.8  333.42  4902.4  328.85  4908.4  324.85  4959.0  325.64
  4992.6  323.00  4995.4  322.50  4998.6  323.00  5033.7  324.22  5079.9  325.79
  5176.0  323.69  5200.8  329.81  5206.7  330.51  5233.1  333.88  5335.4  332.62
  5478.2  336.22  5491.9  336.23  5660.1  340.32  5666.8  340.25  5720.1  339.82
#Mann=18,-1,0
  4173.5    0.05       0  4527.0    0.16       0  4596.4    0.08       0
  4695.9    0.16       0  4717.3    0.08       0  4838.2    0.05       0
  4864.8    0.16       0  4959.0    0.08       0  4992.6    0.07       0
  4998.6    0.08       0  5033.7    0.16       0  5079.9    0.08       0
  5200.8    0.05       0  5206.7    0.16       0  5478.2    0.08       0
  5491.9    0.05       0  5660.1    0.16       0  5666.8    0.05       0
Bank Sta=4992.6,4998.6
Exp/Cntr=0.3,0.1

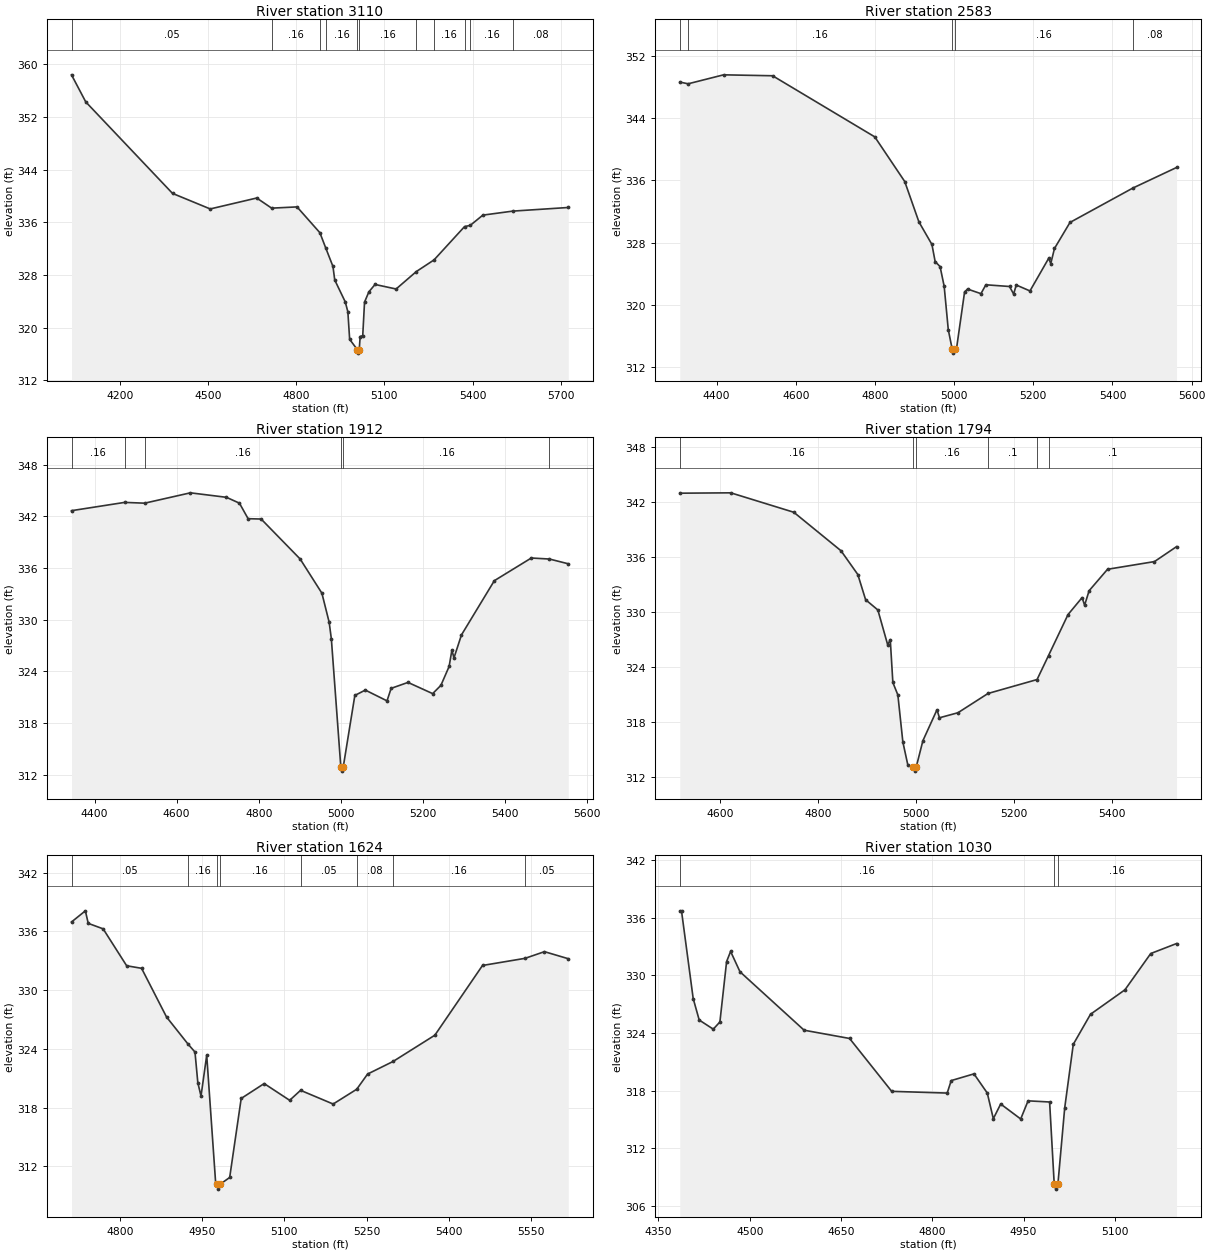
Type RM Length L Ch R = 1,3110,527,527,527
BEGIN DESCRIPTION:
UNT038 IN BECR 6.0
END DESCRIPTION:
XS GIS Cut Line= 2
      3809255.35     10471137.68      3810220.67     10472523.15
#Sta/Elev= 30
  4036.4  358.40  4084.8  354.29  4379.8  340.39  4508.0  338.03  4666.0  339.69
  4716.8  338.15  4803.0  338.34  4880.7  334.42  4900.2  332.15  4925.2  329.29
  4931.2  327.24  4967.0  323.91  4975.8  322.41  4981.9  318.23  5008.5  316.63
  5011.3  316.13  5014.5  316.63  5017.6  318.65  5026.4  318.79  5032.5  323.88
  5047.3  325.44  5068.2  326.56  5139.8  325.87  5208.6  328.52  5268.8  330.29
  5372.5  335.35  5391.7  335.53  5434.7  337.09  5536.5  337.70  5725.0  338.25
#Mann=11,-1,0
  4036.4    0.05       0  4716.8    0.16       0  4880.7    0.05       0
  4900.2    0.16       0  5008.5    0.07       0  5014.5    0.16       0
  5208.6    0.05       0  5268.8    0.16       0  5372.5    0.05       0
  5391.7    0.16       0  5536.5    0.08       0
Bank Sta=5008.5,5014.5
Exp/Cntr=0.3,0.1

Type RM Length L Ch R = 1,2583,671,671,671
BEGIN DESCRIPTION:
UNT038 IN BECR 5.0
END DESCRIPTION:
XS GIS Cut Line= 3
      3809012.36     10472175.92      3809970.65     10472418.96
      3810205.72     10472543.41
#Sta/Elev= 30
  4307.3  348.61  4328.4  348.39  4417.9  349.54  4541.7  349.42  4799.7  341.58
  4875.4  335.85  4911.2  330.67  4944.1  327.77  4952.2  325.58  4964.7  324.93
  4975.0  322.41  4985.4  316.83  4995.3  314.33  4998.1  313.83  5001.3  314.33
  5006.0  314.35  5026.6  321.69  5034.1  322.05  5067.9  321.46  5080.3  322.60
  5140.1  322.38  5150.4  321.41  5157.1  322.57  5191.7  321.81  5239.0  326.00
  5244.2  325.32  5253.6  327.26  5292.8  330.60  5451.5  335.01  5561.9  337.65
#Mann=5,-1,0
  4307.3    0.05       0  4328.4    0.16       0  4995.3    0.07       0
  5001.3    0.16       0  5451.5    0.08       0
Bank Sta=4995.3,5001.3
Exp/Cntr=0.3,0.1

Type RM Length L Ch R = 1,1912,118,118,118
BEGIN DESCRIPTION:
UNT038 IN BECR 4.0
END DESCRIPTION:
XS GIS Cut Line= 3
      3809022.70     10472450.20      3809769.26     10472707.16
      3810189.41     10472731.46
#Sta/Elev= 30
  4343.9  342.65  4473.3  343.61  4522.2  343.52  4633.6  344.72  4721.4  344.20
  4753.1  343.52  4774.2  341.72  4806.0  341.68  4901.1  337.04  4954.0  333.08
  4971.8  329.69  4977.1  327.76  5000.1  312.94  5002.8  312.44  5006.1  312.94
  5034.3  321.22  5059.8  321.84  5112.7  320.59  5122.7  322.04  5163.8  322.73
  5223.9  321.43  5244.0  322.39  5264.0  324.58  5270.8  326.48  5275.8  325.57
  5294.1  328.24  5374.2  334.53  5464.3  337.16  5508.6  337.04  5554.3  336.49
#Mann=6,-1,0
  4343.9    0.16       0  4473.3    0.08       0  4522.2    0.16       0
  5000.1    0.07       0  5006.1    0.16       0  5508.6     0.1       0
Bank Sta=5000.1,5006.1
Exp/Cntr=0.3,0.1

Type RM Length L Ch R = 1,1794,170,170,170
BEGIN DESCRIPTION:
Mapping XS 17161bd0
END DESCRIPTION:
XS GIS Cut Line= 4
      3809234.51     10472561.30      3809491.49     10472741.88
      3809994.96     10472846.05      3810175.50     10472804.38
#Sta/Elev= 30
  4518.1  342.97  4622.1  343.01  4750.7  340.89  4847.0  336.69  4881.3  334.10
  4897.2  331.35  4922.2  330.23  4942.3  326.42  4947.5  327.00  4952.8  322.32
  4963.0  320.96  4973.2  315.83  4983.4  313.31  4994.7  313.15  4997.4  312.65
  5000.7  313.15  5014.1  315.97  5042.8  319.34  5047.9  318.47  5085.6  319.02
  5146.9  321.12  5247.0  322.64  5270.4  325.26  5310.2  329.73  5338.9  331.58
  5344.0  330.75  5353.2  332.33  5390.8  334.67  5486.6  335.51  5531.6  337.14
#Mann=6,-1,0
  4518.1    0.16       0  4994.7    0.07       0  5000.7    0.16       0
  5146.9     0.1       0  5247.0    0.16       0  5270.4     0.1       0
Bank Sta=4994.7,5000.7
Exp/Cntr=0.3,0.1

Type RM Length L Ch R = 1,1624,594,594,594
BEGIN DESCRIPTION:
UNT038 IN BECR 3.0
END DESCRIPTION:
XS GIS Cut Line= 2
      3809394.25     10472856.46      3810258.83     10473127.29
#Sta/Elev= 30
  4711.9  336.96  4737.2  338.10  4742.4  336.82  4769.6  336.26  4812.5  332.49
  4839.7  332.23  4885.2  327.26  4924.6  324.48  4937.1  323.68  4942.3  320.55
  4948.1  319.18  4958.5  323.35  4974.8  310.32  4977.0  310.18  4979.7  309.68
  4983.0  310.18  5000.4  310.87  5021.4  318.94  5063.3  320.46  5109.8  318.75
  5129.7  319.77  5189.1  318.37  5232.1  319.88  5251.9  321.43  5298.5  322.72
  5374.6  325.40  5461.5  332.52  5539.2  333.25  5574.5  333.93  5617.9  333.21
#Mann=8,-1,0
  4711.9    0.05       0  4924.6    0.16       0  4977.0    0.07       0
  4983.0    0.16       0  5129.7    0.05       0  5232.1    0.08       0
  5298.5    0.16       0  5539.2    0.05       0
Bank Sta=4977,4983
Exp/Cntr=0.3,0.1

Type RM Length L Ch R = 1,1030,709,709,709
BEGIN DESCRIPTION:
UNT038 IN BECR 2.0
END DESCRIPTION:
XS GIS Cut Line= 3
      3809449.58     10473560.20      3809999.61     10473310.19
      3810149.60     10473160.20
#Sta/Elev= 30
  4385.1  336.73  4387.9  336.73  4407.1  327.59  4417.0  325.35  4440.1  324.40
  4451.0  325.15  4462.0  331.44  4468.6  332.50  4484.0  330.38  4589.4  324.29
  4664.1  323.43  4733.3  317.92  4824.5  317.74  4831.1  319.04  4868.5  319.74
  4890.4  317.74  4900.3  315.07  4912.4  316.60  4945.3  315.04  4957.4  316.93
  4992.8  316.81  5000.4  308.23  5003.2  307.73  5006.4  308.23  5017.6  316.19
  5031.7  322.82  5060.0  325.95  5116.6  328.50  5159.0  332.28  5201.4  333.32
#Mann=3,-1,0
  4385.1    0.16       0  5000.4    0.07       0  5006.4    0.16       0
Bank Sta=5000.4,5006.4
Exp/Cntr=0.3,0.1

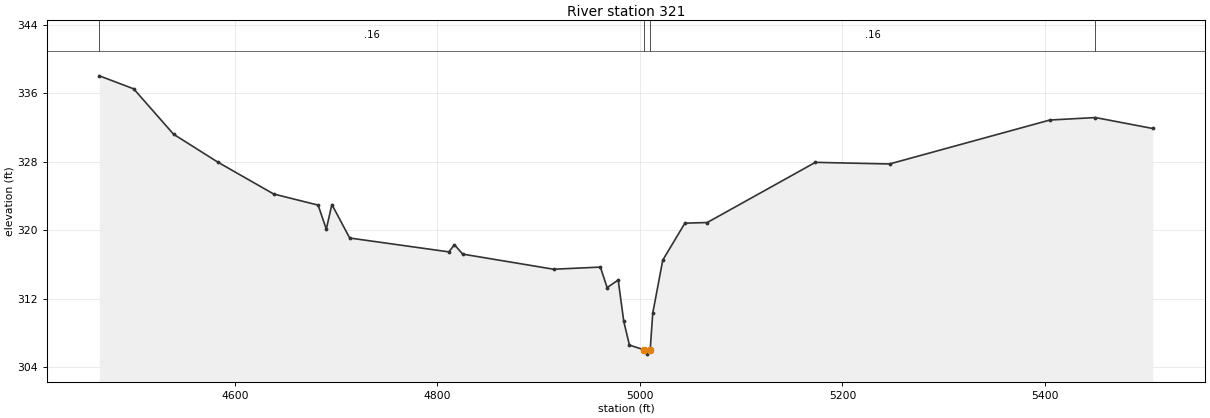
Type RM Length L Ch R = 1,321,0,0,0
BEGIN DESCRIPTION:
UNT038 IN BECR 1.0
END DESCRIPTION:
XS GIS Cut Line= 3
      3809442.88     10473651.60      3810033.15     10473918.96
      3810408.14     10473804.39
#Sta/Elev= 30
  4466.3  338.06  4500.2  336.54  4539.6  331.23  4583.5  327.95  4638.4  324.24
  4682.3  322.94  4690.4  320.13  4695.9  323.01  4713.5  319.09  4811.4  317.47
  4816.9  318.31  4825.0  317.21  4914.8  315.44  4961.0  315.69  4967.7  313.29
  4978.6  314.18  4984.1  309.34  4989.7  306.57  5004.2  306.01  5006.9  305.51
  5010.2  306.01  5012.7  310.28  5022.6  316.50  5044.5  320.83  5066.5  320.90
  5173.3  327.94  5246.5  327.75  5404.8  332.89  5449.8  333.18  5506.4  331.90
#Mann=4,-1,0
  4466.3    0.16       0  5004.2    0.07       0  5010.2    0.16       0
  5449.8     0.1       0
Bank Sta=5004.2,5010.2
Exp/Cntr=0.3,0.1

Chan Stop Cuts=-1