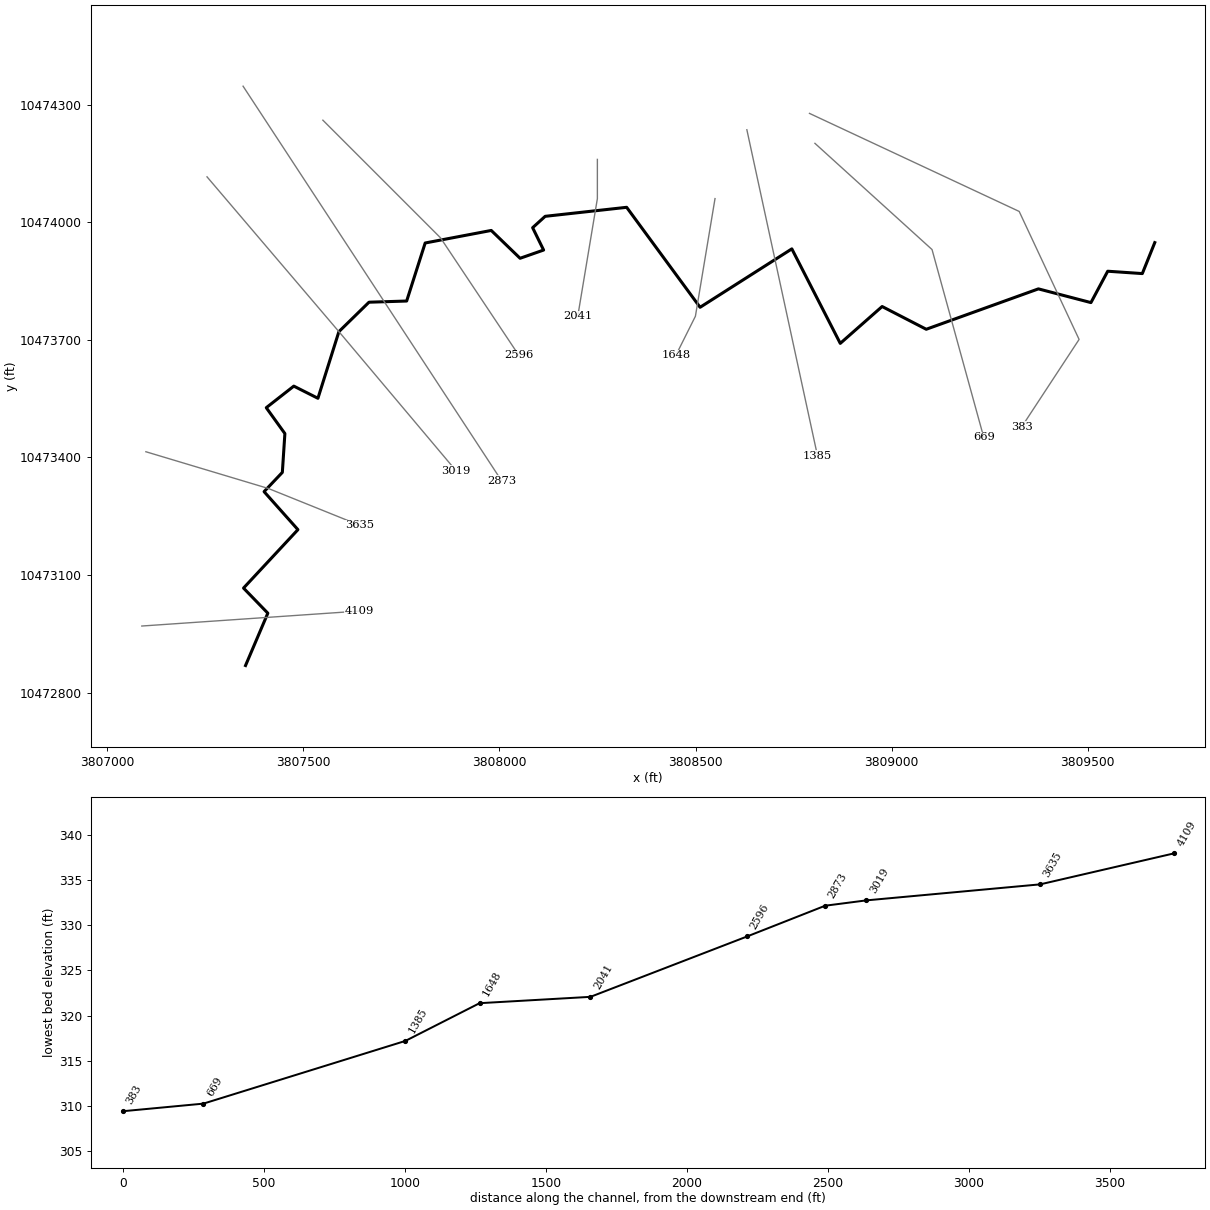
--- UNT040 IN BECR.prj (project) ---

Proj Title=UNT040 IN BECR Base Level Engineering
Current Plan=p01
Default Exp/Contr=0.3,0.1
English Units
Geom File=g01
Flow File=f01
Plan File=p01
BEGIN DESCRIPTION:
UNT040 IN BECR
END DESCRIPTION:

--- UNT040 IN BECR.p01 (plan) ---

Plan Title=Multiple Run
Short Identifier=Multiple
Geom File=g01
Flow File=f01
Subcritical Flow
K Sum by GR= 0
Std Step Tol= 0.01
Critical Tol= 0.01
Num of Std Step Trials= 20
Max Error Tol= 0.3
Flow Tol Ratio= 0.001
Split Flow NTrial= 30
Split Flow Tol= 0.02
Split Flow Ratio= 0.02
Log Output Level= 0
Friction Slope Method= 1
Unsteady Friction Slope Method= 2
Unsteady Bridges Friction Slope Method= 1
Parabolic Critical Depth
Global Vel Dist=  1 , 1 , 1
Global Log Level= 0
CheckData=True
Encroach Param= -1, 0, 0, 0
BEGIN DESCRIPTION:
Multiple Run
END DESCRIPTION:

--- UNT040 IN BECR.f01 (steady flow) ---

Flow Title=Multiple
Number of Profiles=7
Profile Names=10-year,25-year,50-year,1pct_min,100-year,1pct_plu,500-year
River Rch & RM= UNT040 IN BECR,Reach-1,4109
     268     341     398     341     462     624     623
Boundary for River Rch & Prof#=UNT040 IN BECR,Reach-1,1
Up Type=0
Dn Type=3
Dn Slope=0.005
Boundary for River Rch & Prof#=UNT040 IN BECR,Reach-1,2
Up Type=0
Dn Type=3
Dn Slope=0.005
Boundary for River Rch & Prof#=UNT040 IN BECR,Reach-1,3
Up Type=0
Dn Type=3
Dn Slope=0.005
Boundary for River Rch & Prof#=UNT040 IN BECR,Reach-1,4
Up Type=0
Dn Type=3
Dn Slope=0.005
Boundary for River Rch & Prof#=UNT040 IN BECR,Reach-1,5
Up Type=0
Dn Type=3
Dn Slope=0.005
Boundary for River Rch & Prof#=UNT040 IN BECR,Reach-1,6
Up Type=0
Dn Type=3
Dn Slope=0.005
Boundary for River Rch & Prof#=UNT040 IN BECR,Reach-1,7
Up Type=0
Dn Type=3
Dn Slope=0.005

--- UNT040 IN BECR.g01 (geometry) ---

Geom Title=Existing Conditions

River Reach=UNT040 IN BECR,Reach-1
Reach XY= 30
      3807352.38     10472869.50      3807409.25     10473003.00
      3807347.25     10473067.00      3807486.00     10473216.00
      3807399.65     10473312.93      3807446.25     10473362.00
      3807452.75     10473461.00      3807405.25     10473527.00
      3807475.50     10473582.00      3807537.00     10473551.00
      3807590.50     10473721.00      3807667.25     10473796.00
      3807763.25     10473799.00      3807810.50     10473947.00
      3807979.00     10473979.00      3808052.50     10473908.00
      3808112.50     10473929.00      3808084.50     10473986.00
      3808116.50     10474015.00      3808324.25     10474038.00
      3808511.50     10473783.00      3808745.50     10473932.00
      3808869.00     10473691.00      3808975.75     10473785.00
      3809088.25     10473727.00      3809374.25     10473830.00
      3809508.25     10473795.00      3809551.00     10473875.00
      3809639.25     10473869.00      3809671.00     10473948.00

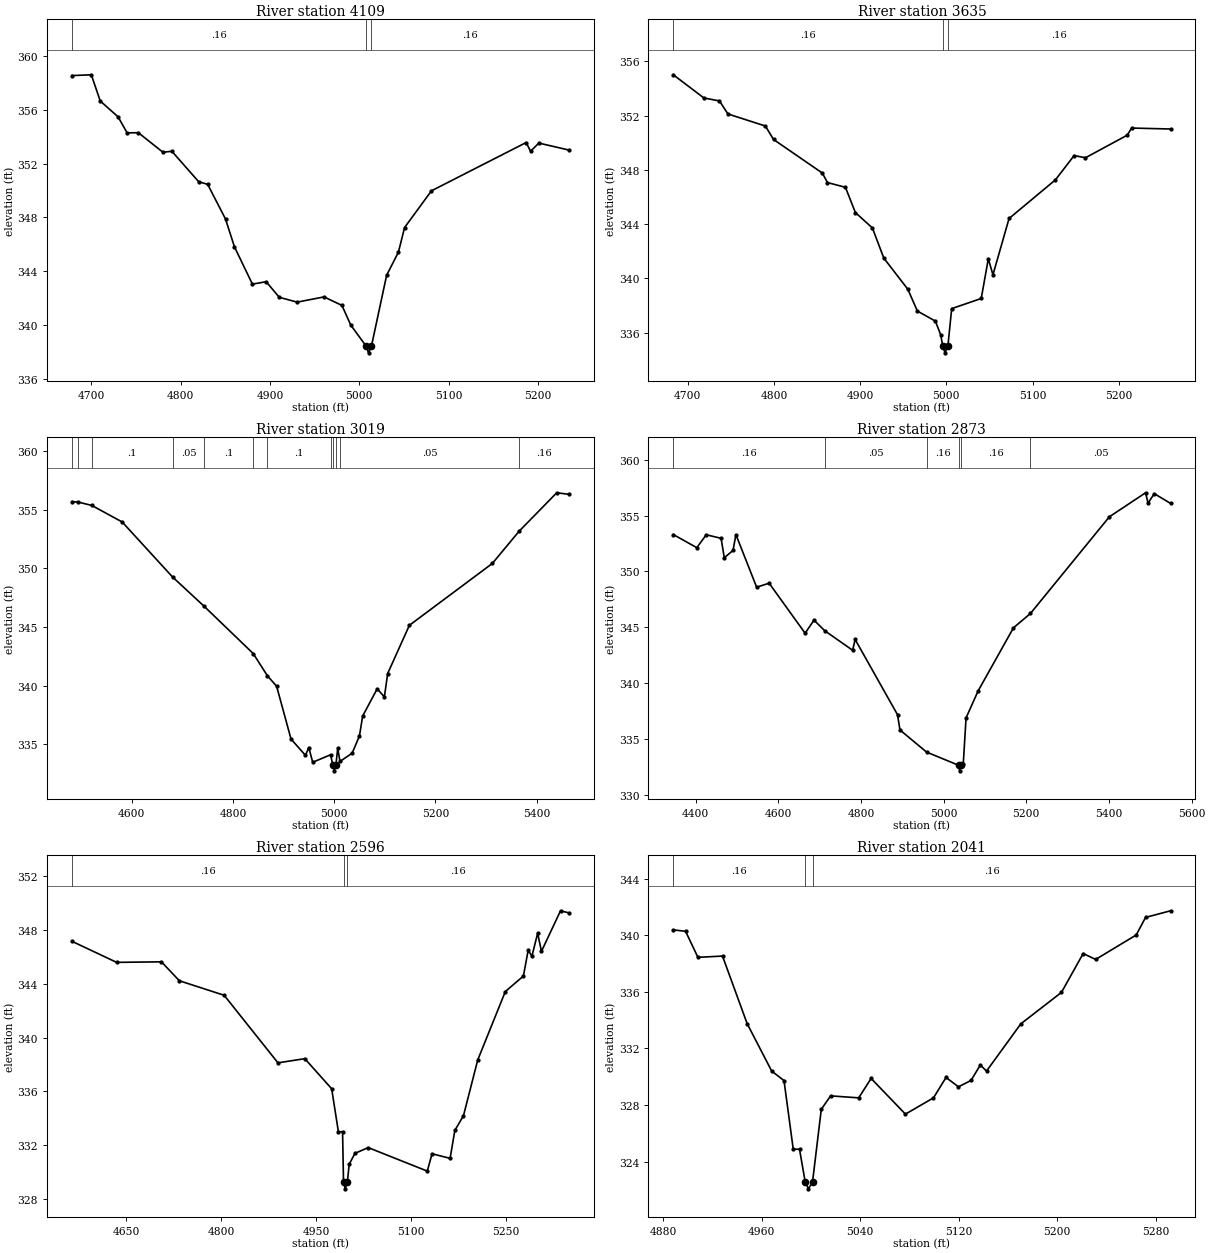
Type RM Length L Ch R = 1,4109,474,474,474
BEGIN DESCRIPTION:
UNT040 IN BECR 8.0
END DESCRIPTION:
XS GIS Cut Line= 2
      3807087.90     10472970.24      3807643.39     10473008.43
#Sta/Elev= 30
  4678.1  358.54  4699.9  358.60  4709.9  356.65  4729.9  355.47  4740.0  354.28
  4752.6  354.29  4780.1  352.84  4790.1  352.91  4820.1  350.65  4830.2  350.45
  4850.2  347.87  4860.2  345.80  4880.3  343.03  4895.7  343.21  4910.4  342.05
  4930.4  341.69  4960.5  342.08  4980.5  341.45  4990.5  339.98  5007.6  338.42
  5010.3  337.92  5013.6  338.42  5030.6  343.69  5043.8  345.41  5050.7  347.24
  5080.8  349.97  5186.8  353.56  5191.8  352.91  5201.0  353.52  5234.9  353.00
#Mann=3,-1,0
  4678.1    0.16       0  5007.6    0.07       0  5013.6    0.16       0
Bank Sta=5007.6,5013.6
Exp/Cntr=0.3,0.1

Type RM Length L Ch R = 1,3635,616,616,616
BEGIN DESCRIPTION:
UNT040 IN BECR 7.0
END DESCRIPTION:
XS GIS Cut Line= 3
      3807098.24     10473414.69      3807410.77     10473320.93
      3807643.40     10473227.18
#Sta/Elev= 30
  4683.1  355.01  4718.6  353.30  4736.7  353.08  4746.5  352.12  4790.0  351.23
  4799.4  350.24  4856.1  347.76  4862.0  347.06  4882.9  346.71  4894.4  344.85
  4914.2  343.71  4927.4  341.49  4955.3  339.19  4966.4  337.58  4987.3  336.84
  4993.5  335.82  4995.8  335.00  4998.5  334.50  5001.8  335.00  5006.2  337.76
  5040.5  338.51  5048.7  341.43  5054.1  340.26  5072.8  344.41  5126.6  347.26
  5148.3  349.05  5161.5  348.89  5209.8  350.55  5215.2  351.08  5260.2  351.01
#Mann=3,-1,0
  4683.1    0.16       0  4995.8    0.07       0  5001.8    0.16       0
Bank Sta=4995.8,5001.8
Exp/Cntr=0.3,0.1

Type RM Length L Ch R = 1,3019,146,146,146
BEGIN DESCRIPTION:
UNT040 IN BECR 6.0
END DESCRIPTION:
XS GIS Cut Line= 3
      3807254.18     10474115.71      3807599.61     10473710.19
      3807889.61     10473365.70
#Sta/Elev= 30
  4481.4  355.68  4493.5  355.65  4520.9  355.36  4580.9  353.95  4680.5  349.26
  4743.2  346.75  4840.0  342.73  4868.1  340.83  4886.2  339.95  4914.7  335.44
  4943.3  334.05  4949.8  334.72  4957.6  333.46  4992.9  334.10  4997.4  333.23
  5000.1  332.73  5003.4  333.23  5007.0  334.65  5011.5  333.53  5035.6  334.24
  5049.9  335.70  5056.4  337.41  5085.0  339.72  5099.3  339.04  5105.8  341.03
  5148.7  345.14  5312.6  350.41  5365.8  353.17  5440.0  356.44  5464.4  356.31
#Mann=12,-1,0
  4481.4     0.1       0  4493.5    0.16       0  4520.9     0.1       0
  4680.5    0.05       0  4743.2     0.1       0  4840.0    0.05       0
  4868.1     0.1       0  4992.9    0.16       0  4997.4    0.07       0
  5003.4    0.16       0  5011.5    0.05       0  5365.8    0.16       0
Bank Sta=4997.4,5003.4
Exp/Cntr=0.3,0.1

Type RM Length L Ch R = 1,2873,277,277,277
BEGIN DESCRIPTION:
Mapping XS b6bdad34
END DESCRIPTION:
XS GIS Cut Line= 2
      3807346.11     10474346.88      3808005.22     10473340.87
#Sta/Elev= 30
  4346.2  353.31  4403.1  352.13  4425.9  353.29  4461.8  352.97  4469.5  351.23
  4490.6  351.88  4497.7  353.30  4547.8  348.59  4578.0  348.95  4665.0  344.47
  4686.6  345.64  4712.2  344.70  4780.0  342.94  4786.0  343.91  4888.5  337.17
  4894.5  335.80  4958.8  333.82  5036.2  332.64  5039.0  332.14  5042.2  332.64
  5047.6  332.77  5054.3  336.88  5083.5  339.30  5168.9  344.95  5210.1  346.24
  5401.0  354.90  5488.5  357.05  5494.5  356.12  5509.6  356.97  5548.9  356.10
#Mann=6,-1,0
  4346.2    0.16       0  4712.2    0.05       0  4958.8    0.16       0
  5036.2    0.07       0  5042.2    0.16       0  5210.1    0.05       0
Bank Sta=5036.2,5042.2
Exp/Cntr=0.3,0.1

Type RM Length L Ch R = 1,2596,555,555,555
BEGIN DESCRIPTION:
UNT040 IN BECR 5.0
END DESCRIPTION:
XS GIS Cut Line= 3
      3807549.61     10474260.18      3807849.61     10473960.19
      3808049.60     10473660.20
#Sta/Elev= 30
  4564.7  347.17  4635.4  345.60  4706.1  345.64  4734.4  344.23  4805.1  343.15
  4890.0  338.12  4932.4  338.43  4974.8  336.19  4985.4  332.99  4992.0  332.99
  4993.5  329.24  4996.2  328.74  4999.5  329.24  5002.5  330.57  5011.5  331.38
  5032.5  331.81  5125.7  330.06  5133.2  331.35  5161.7  331.01  5169.2  333.09
  5182.8  334.18  5205.3  338.33  5248.9  343.43  5277.4  344.58  5284.9  346.49
  5290.9  346.07  5299.9  347.77  5305.9  346.42  5336.0  349.44  5349.5  349.28
#Mann=3,-1,0
  4564.7    0.16       0  4993.5    0.07       0  4999.5    0.16       0
Bank Sta=4993.5,4999.5
Exp/Cntr=0.3,0.1

Type RM Length L Ch R = 1,2041,393,393,393
BEGIN DESCRIPTION:
UNT040 IN BECR 4.0
END DESCRIPTION:
XS GIS Cut Line= 3
      3808249.61     10474160.21      3808249.61     10474060.19
      3808199.60     10473760.15
#Sta/Elev= 30
  4888.0  340.37  4898.0  340.27  4908.0  338.43  4928.0  338.52  4948.0  333.75
  4968.0  330.39  4978.0  329.72  4985.5  324.87  4990.6  324.87  4995.2  322.57
  4997.9  322.07  5001.2  322.57  5008.3  327.69  5015.9  328.64  5038.7  328.50
  5048.8  329.87  5076.7  327.35  5099.5  328.50  5109.7  329.94  5119.8  329.28
  5130.0  329.73  5137.6  330.82  5142.6  330.39  5170.5  333.73  5203.5  335.95
  5221.2  338.70  5231.3  338.28  5264.3  340.01  5271.9  341.25  5292.2  341.72
#Mann=3,-1,0
  4888.0    0.16       0  4995.2    0.07       0  5001.2    0.16       0
Bank Sta=4995.2,5001.2
Exp/Cntr=0.3,0.1

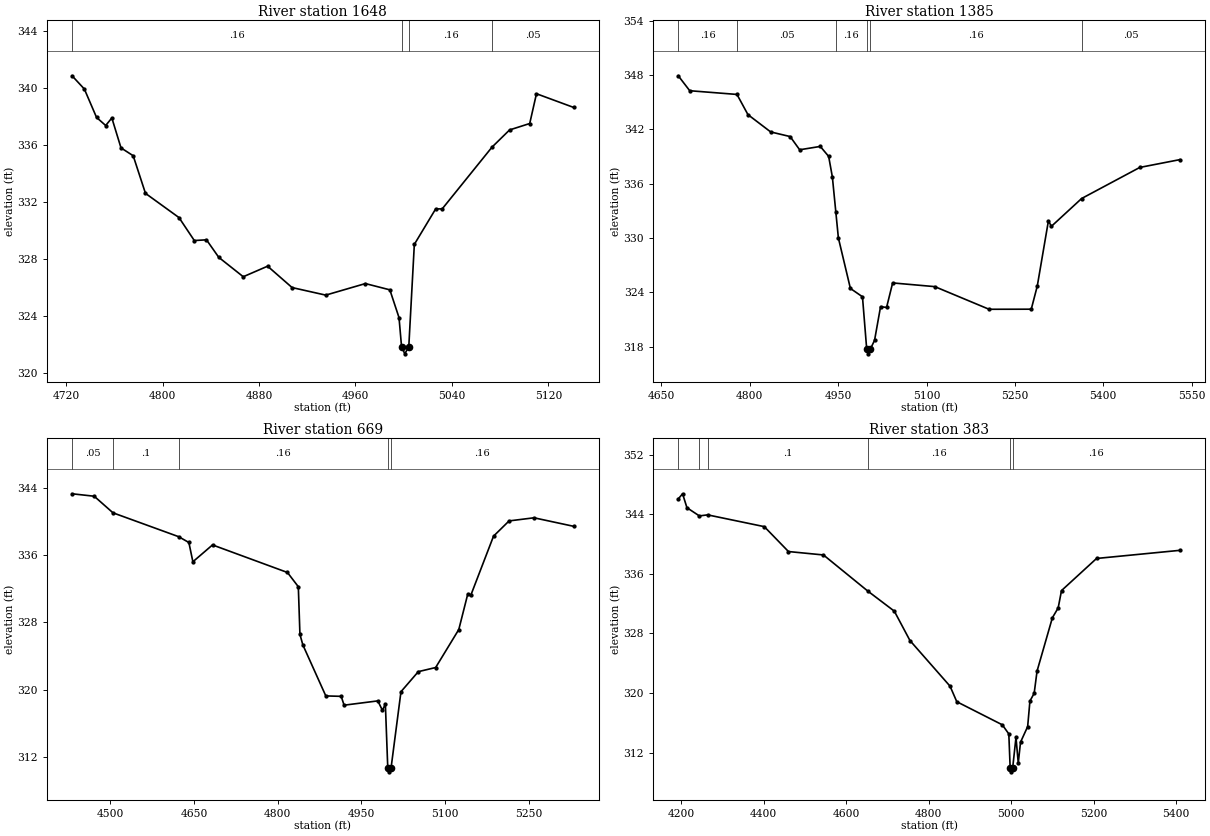
Type RM Length L Ch R = 1,1648,263,263,263
BEGIN DESCRIPTION:
UNT040 IN BECR 3.0
END DESCRIPTION:
XS GIS Cut Line= 3
      3808549.61     10474060.21      3808499.61     10473760.19
      3808449.59     10473660.16
#Sta/Elev= 30
  4724.9  340.88  4735.1  339.95  4745.2  337.96  4752.8  337.39  4757.9  337.92
  4765.5  335.82  4775.6  335.27  4785.8  332.63  4813.6  330.93  4826.3  329.32
  4836.4  329.37  4846.6  328.14  4866.9  326.78  4887.1  327.52  4907.4  326.02
  4935.3  325.49  4968.2  326.30  4988.5  325.86  4996.1  323.91  4998.2  321.87
  5000.9  321.37  5004.2  321.87  5008.8  329.05  5026.5  331.54  5031.9  331.54
  5073.3  335.88  5087.8  337.08  5104.5  337.53  5110.1  339.62  5140.9  338.66
#Mann=4,-1,0
  4724.9    0.16       0  4998.2    0.07       0  5004.2    0.16       0
  5073.3    0.05       0
Bank Sta=4998.2,5004.2
Exp/Cntr=0.3,0.1

Type RM Length L Ch R = 1,1385,716,716,716
BEGIN DESCRIPTION:
UNT040 IN BECR 2.0
END DESCRIPTION:
XS GIS Cut Line= 2
      3808630.81     10474235.81      3808811.07     10473403.81
#Sta/Elev= 30
  4678.6  347.90  4698.1  346.25  4778.3  345.84  4796.9  343.61  4835.5  341.70
  4868.5  341.19  4884.7  339.73  4919.7  340.10  4933.9  339.00  4940.2  336.73
  4946.0  332.90  4950.4  330.00  4970.8  324.42  4991.3  323.50  4998.5  317.70
  5001.3  317.20  5004.5  317.70  5011.8  318.69  5022.0  322.41  5032.2  322.32
  5042.5  325.03  5114.1  324.62  5206.2  322.12  5277.8  322.13  5288.0  324.68
  5306.9  331.88  5312.0  331.28  5363.3  334.35  5462.0  337.78  5529.9  338.64
#Mann=6,-1,0
  4678.6    0.16       0  4778.3    0.05       0  4946.0    0.16       0
  4998.5    0.07       0  5004.5    0.16       0  5363.3    0.05       0
Bank Sta=4998.5,5004.5
Exp/Cntr=0.3,0.1

Type RM Length L Ch R = 1,669,286,286,286
BEGIN DESCRIPTION:
Mapping XS 71cbf844
END DESCRIPTION:
XS GIS Cut Line= 3
      3808804.41     10474201.09      3809103.03     10473930.25
      3809234.80     10473451.71
#Sta/Elev= 30
  4431.2  343.27  4470.9  342.98  4504.6  341.01  4622.3  338.18  4640.7  337.49
  4647.9  335.20  4683.1  337.20  4817.5  333.93  4837.0  332.24  4839.9  326.58
  4845.1  325.34  4886.3  319.28  4913.9  319.23  4919.1  318.18  4979.6  318.69
  4987.9  317.56  4993.1  318.34  4997.4  310.77  5000.1  310.27  5003.4  310.77
  5021.1  319.78  5052.2  322.16  5083.3  322.65  5124.8  327.16  5141.0  331.40
  5146.2  331.20  5187.1  338.24  5215.0  340.05  5259.7  340.42  5330.7  339.41
#Mann=5,-1,0
  4431.2    0.05       0  4504.6     0.1       0  4622.3    0.16       0
  4997.4    0.07       0  5003.4    0.16       0
Bank Sta=4997.4,5003.4
Exp/Cntr=0.3,0.1

Type RM Length L Ch R = 1,383,0,0,0
BEGIN DESCRIPTION:
UNT040 IN BECR 1.0
END DESCRIPTION:
XS GIS Cut Line= 4
      3808790.51     10474277.48      3809325.25     10474027.47
      3809478.03     10473701.08      3809332.18     10473478.84
#Sta/Elev= 30
  4192.5  346.05  4203.0  346.74  4213.6  344.87  4243.7  343.77  4263.8  343.91
  4401.2  342.33  4459.8  338.99  4544.7  338.53  4652.4  333.68  4716.6  330.99
  4754.5  327.05  4851.8  320.92  4868.1  318.84  4978.5  315.74  4994.3  314.52
  4997.6  309.93  5000.4  309.43  5003.6  309.93  5011.7  314.05  5017.2  310.60
  5022.7  313.41  5040.0  315.50  5045.5  318.93  5055.8  319.97  5062.8  322.95
  5100.0  330.11  5114.0  331.42  5122.1  333.75  5207.1  338.06  5409.0  339.15
#Mann=6,-1,0
  4192.5    0.16       0  4243.7    0.05       0  4263.8     0.1       0
  4652.4    0.16       0  4997.6    0.07       0  5003.6    0.16       0
Bank Sta=4997.6,5003.6
Exp/Cntr=0.3,0.1

Chan Stop Cuts=-1