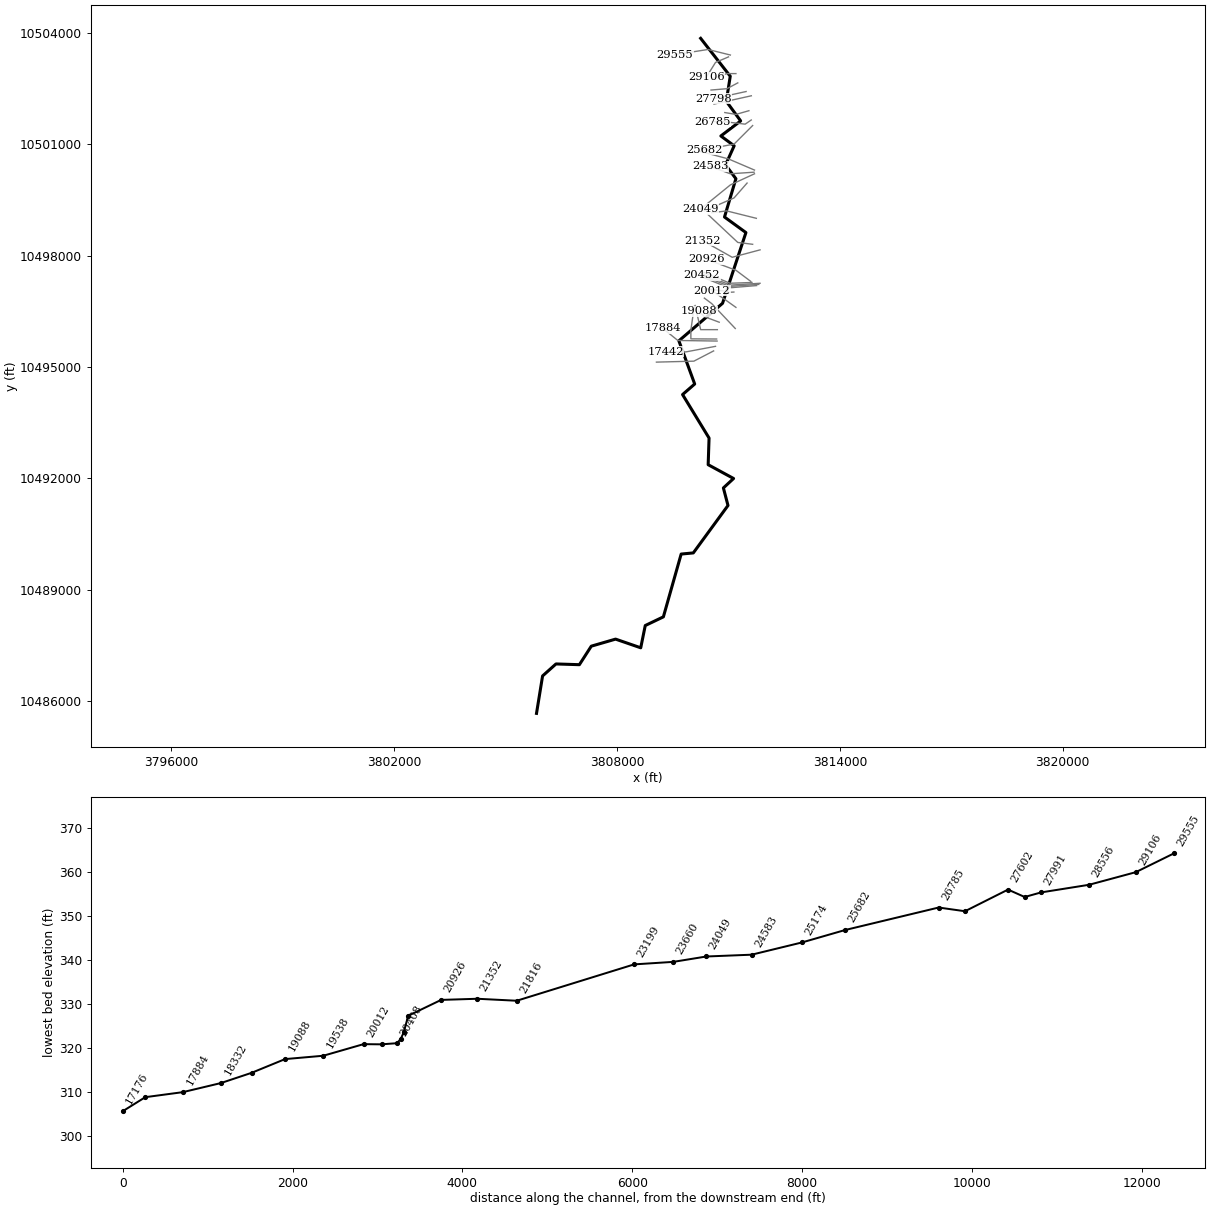
--- UNT043 IN BECR.prj (project) ---

Proj Title=UNT043 IN BECR Base Level Engineering
Current Plan=p01
Default Exp/Contr=0.3,0.1
English Units
Geom File=g01
Flow File=f01
Plan File=p01
Y Axis Title=Elevation
X Axis Title(PF)=Main Channel Distance
X Axis Title(XS)=Station
BEGIN DESCRIPTION:
UNT043 IN BECR
END DESCRIPTION:
DSS Export Rating Curves= 0
DSS Export Rating Curve Sorted= 0
DSS Export Volume Flow Curves= 0
DXF OffsetX= 0
DXF OffsetY= 0
DXF ScaleX= 1
DXF ScaleY= 10

--- UNT043 IN BECR.p01 (plan) ---

Plan Title=Multiple Run
Short Identifier=Multiple
Geom File=g01
Flow File=f01
Subcritical Flow
K Sum by GR= 0
Std Step Tol= 0.01
Critical Tol= 0.01
Num of Std Step Trials= 20
Max Error Tol= 0.3
Flow Tol Ratio= 0.001
Split Flow NTrial= 30
Split Flow Tol= 0.02
Split Flow Ratio= 0.02
Log Output Level= 0
Friction Slope Method= 1
Unsteady Friction Slope Method= 2
Unsteady Bridges Friction Slope Method= 1
Parabolic Critical Depth
Global Vel Dist=  1 , 1 , 1
Global Log Level= 0
CheckData=True
Encroach Param= -1, 0, 0, 0
BEGIN DESCRIPTION:
Multiple Run
END DESCRIPTION:

--- UNT043 IN BECR.f01 (steady flow) ---

Flow Title=Multiple
Program Version=4.10
Number of Profiles= 7
Profile Names=10-year,25-year,50-year,1pct_min,100-year,1pct_plu,500-year
River Rch & RM=UNT043 IN BECR,Reach-1         ,29555
     647     870    1053     936    1266    1713    1837
River Rch & RM=UNT043 IN BECR,Reach-1         ,24049
     784    1064    1295    1156    1564    2115    2289
River Rch & RM=UNT043 IN BECR,Reach-1         ,23199
     784    1064    1295    1156    1564    2115    2289
River Rch & RM=UNT043 IN BECR,Reach-1         ,17884
     960    1315    1611    1447    1957    2646    2899
River Rch & RM=UNT043 IN BECR,Reach-1         ,13658
    1114    1532    1881    1692    2288    3095    3401
Boundary for River Rch & Prof#=UNT043 IN BECR,Reach-1         , 1
Up Type= 0
Dn Type= 3
Dn Slope=0.003
Boundary for River Rch & Prof#=UNT043 IN BECR,Reach-1         , 2
Up Type= 0
Dn Type= 3
Dn Slope=0.003
Boundary for River Rch & Prof#=UNT043 IN BECR,Reach-1         , 3
Up Type= 0
Dn Type= 3
Dn Slope=0.003
Boundary for River Rch & Prof#=UNT043 IN BECR,Reach-1         , 4
Up Type= 0
Dn Type= 3
Dn Slope=0.003
Boundary for River Rch & Prof#=UNT043 IN BECR,Reach-1         , 5
Up Type= 0
Dn Type= 3
Dn Slope=0.003
Boundary for River Rch & Prof#=UNT043 IN BECR,Reach-1         , 6
Up Type= 0
Dn Type= 3
Dn Slope=0.003
Boundary for River Rch & Prof#=UNT043 IN BECR,Reach-1         , 7
Up Type= 0
Dn Type= 3
Dn Slope=0.003
DSS Import GetInterval= 0
DSS Import GetPeak= 0
DSS Import FillOption= 0

--- UNT043 IN BECR.g01 (geometry) ---

Geom Title=Existing Conditions
Program Version=4.10

River Reach=UNT043 IN BECR  ,Reach-1
Reach XY= 30
      3810249.61     10503860.19      3811046.25       10502839.
        3810940.       10502164.      3811327.25       10501635.
      3810793.75       10501229.        3811152.       10500964.
      3810920.75       10500450.      3811198.75       10500077.
      3810891.75       10499045.       3811468.5       10498626.
        3810839.       10496720.        3809663.       10495709.
        3810089.       10494545.      3809762.25       10494261.
        3810476.       10493089.        3810452.       10492371.
      3811136.25       10491999.      3810861.75       10491745.
      3810985.75       10491272.      3810051.75       10489994.
      3809724.75       10489963.        3809246.       10488271.
      3808757.75       10488037.        3808636.       10487437.
       3807958.5       10487671.       3807304.5       10487481.
        3806984.       10486982.        3806354.       10487002.
        3805993.       10486679.       3805829.5       10485670.

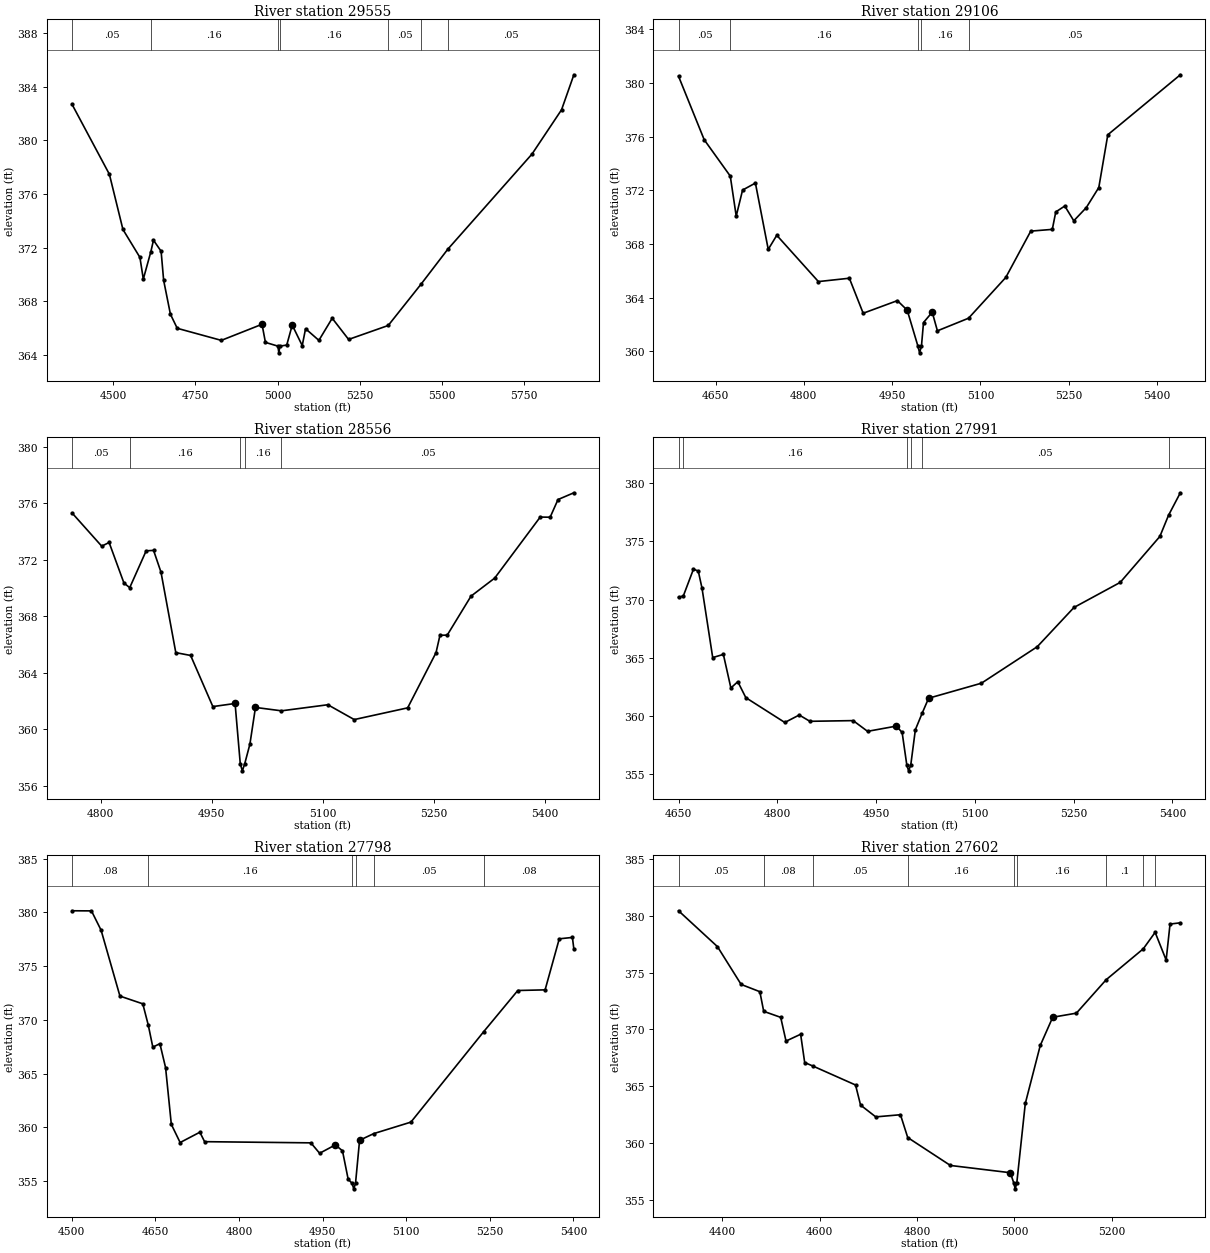
Type RM Length L Ch R = 1 ,29555   ,449,449,449
BEGIN DESCRIPTION:
UNT043 IN BECR 53.0
END DESCRIPTION:
XS GIS Cut Line= 3
      3811049.63     10503410.18      3810449.61     10503560.19
        3809554.     10503419.98
#Sta/Elev= 30
  4375.4  382.69  4488.8  377.48    4530  373.36  4581.6  371.28  4591.9  369.66
  4614.9  371.71  4622.8  372.56    4646  371.74  4653.7  369.57  4674.3  367.04
    4695  365.99    4829  365.09  4952.7  366.29    4963  364.94    5001  364.66
  5003.8  364.16    5007  364.66  5027.8  364.74  5044.5  366.23  5074.9   364.7
    5085  365.96  5125.5  365.09    5166  366.74  5215.8  365.16  5336.2   366.2
  5435.6  369.27  5517.3  371.89  5773.3  378.99    5863  382.29  5900.4   384.9
#Mann= 7 ,-1 , 0
  4375.4     .05       0  4614.9     .16       0    5001     .07       0
    5007     .16       0  5336.2     .05       0  5435.6     .08       0
  5517.3     .05       0
Bank Sta=4952.7,5044.5
XS Rating Curve= 0 ,0
Exp/Cntr=0.3,0.1

Type RM Length L Ch R = 1 ,29106   ,550,550,550
BEGIN DESCRIPTION:
UNT043 IN BECR 52.0
END DESCRIPTION:
XS GIS Cut Line= 3
      3810999.65     10503360.21      3810649.61     10503210.19
      3810399.63     10502810.22
#Sta/Elev= 30
  4587.2  380.51  4630.8  375.78  4675.1  373.07  4685.2  370.09    4696  372.03
  4717.8  372.55  4739.6  367.61  4754.1  368.66  4824.8  365.21  4877.4  365.46
  4900.9  362.85    4959  363.79  4975.7  363.08  4993.9   360.4  4996.7   359.9
  4999.9   360.4  5003.4  362.16  5018.2  362.93    5027  361.54  5079.9  362.48
  5143.2  365.52  5185.6  368.97  5222.2   369.1  5228.1   370.4  5243.4  370.84
  5258.7  369.74  5279.9  370.72  5301.2  372.22  5316.5  376.15  5439.7  380.62
#Mann= 5 ,-1 , 0
  4587.2     .05       0  4675.1     .16       0  4993.9     .07       0
  4999.9     .16       0  5079.9     .05       0
Bank Sta=4975.7,5018.2
XS Rating Curve= 0 ,0
Exp/Cntr=0.3,0.1

Type RM Length L Ch R = 1 ,28556   ,565,565,565
BEGIN DESCRIPTION:
UNT043 IN BECR 51.0
END DESCRIPTION:
XS GIS Cut Line= 3
      3811199.61     10502910.19      3810949.61     10502910.19
      3810549.61     10502760.19
#Sta/Elev= 30
  4761.4   375.3  4801.4  372.95  4811.4  373.21  4831.4  370.34  4839.2  370.01
  4861.4  372.62  4871.4  372.65  4881.4  371.11  4901.4  365.41  4921.4  365.21
  4951.4  361.59  4981.4  361.81  4988.4  357.54  4991.2  357.04  4994.4  357.54
  5001.4  358.93  5008.9  361.53    5044  361.29  5106.6  361.72  5142.2  360.67
  5214.3   361.5  5252.6  365.41  5257.9  366.64  5267.7  366.65  5299.8  369.41
  5331.8  370.69  5393.2  375.01  5406.6     375  5417.2  376.25  5438.6  376.73
#Mann= 5 ,-1 , 0
  4761.4     .05       0  4839.2     .16       0  4988.4     .07       0
  4994.4     .16       0    5044     .05       0
Bank Sta=4981.4,5008.9
XS Rating Curve= 0 ,0
Exp/Cntr=0.3,0.1

Type RM Length L Ch R = 1 ,27991   ,193,193,193
BEGIN DESCRIPTION:
UNT043 IN BECR 50.0
END DESCRIPTION:
XS GIS Cut Line= 3
      3811249.59     10502660.18      3810958.34     10502503.22
      3810528.64     10502466.76
#Sta/Elev= 30
  4649.9  370.19  4657.2  370.32  4672.6  372.62  4679.9  372.45  4685.6  370.97
  4701.8  365.03    4718   365.3  4729.4  362.42  4739.9  362.96  4752.1  361.59
  4811.3  359.46  4833.2   360.1  4849.4  359.56  4915.1  359.62    4937   358.7
  4980.8  359.15  4989.5   358.6  4996.6  355.81  4999.3  355.31  5002.6  355.81
  5009.6  358.84  5019.8  360.24  5029.7  361.54  5109.9  362.83  5194.7  365.96
  5250.5  369.33  5320.7  371.48  5380.9  375.42  5394.1  377.24    5412  379.17
#Mann= 6 ,-1 , 0
  4649.9     .05       0  4657.2     .16       0  4996.6     .07       0
  5002.6     .16       0  5019.8     .05       0  5394.1     .08       0
Bank Sta=4980.8,5029.7
XS Rating Curve= 0 ,0
Exp/Cntr=0.3,0.1

Type RM Length L Ch R = 1 ,27798   ,196,196,196
BEGIN DESCRIPTION:
UNT043 IN BECR 49.0
END DESCRIPTION:
XS GIS Cut Line= 2
      3811473.56     10502426.77      3810593.99      10502234.2
#Sta/Elev= 30
  4500.5  380.15  4535.3  380.14  4552.6  378.34  4586.4  372.21  4627.4  371.49
  4637.2  369.52  4645.4  367.46  4658.1  367.78  4668.3  365.55  4678.6  360.27
  4694.4  358.58  4729.8  359.54  4738.3  358.66    4929  358.55  4944.7  357.58
  4972.9  358.36  4985.7  357.81  4995.9  355.17  5003.1  354.77  5005.9  354.27
  5009.1  354.77  5016.4  358.79  5041.8  359.41  5108.5  360.48  5239.3  368.91
  5300.3  372.73  5349.3  372.79  5374.7  377.54  5398.3  377.67  5400.9  376.59
#Mann= 6 ,-1 , 0
  4500.5     .08       0  4637.2     .16       0  5003.1     .07       0
  5009.1     .16       0  5041.8     .05       0  5239.3     .08       0
Bank Sta=4972.9,5016.4
XS Rating Curve= 0 ,0
Exp/Cntr=0.3,0.1

Type RM Length L Ch R = 1 ,27602   ,507,507,507
BEGIN DESCRIPTION:
Mapping XS c6db0d68
END DESCRIPTION:
XS GIS Cut Line= 2
      3811614.24      10502312.2      3810608.99     10502088.23
#Sta/Elev= 30
  4310.5  380.45  4390.4  377.29    4439  373.96  4477.4  373.32  4485.3  371.59
  4520.2  371.06  4531.1  368.97  4561.1  369.57  4569.4  367.08  4585.7  366.78
  4673.8   365.1  4684.1  363.33  4715.3  362.29    4766  362.48  4780.9  360.47
  4868.5  358.01  4991.5  357.37  4998.7  356.45  5001.4  355.95  5004.7  356.45
  5022.2  363.47  5052.9  368.58  5078.5  371.07  5127.1  371.43  5188.3  374.38
  5264.4   377.1  5288.7  378.55  5311.3  376.11  5319.3  379.28  5340.4  379.39
#Mann= 9 ,-1 , 0
  4310.5     .05       0  4485.3     .08       0  4585.7     .05       0
  4780.9     .16       0  4998.7     .07       0  5004.7     .16       0
  5188.3      .1       0  5264.4     .05       0  5288.7     .08       0
Bank Sta=4991.5,5078.5
XS Rating Curve= 0 ,0
Exp/Cntr=0.3,0.1

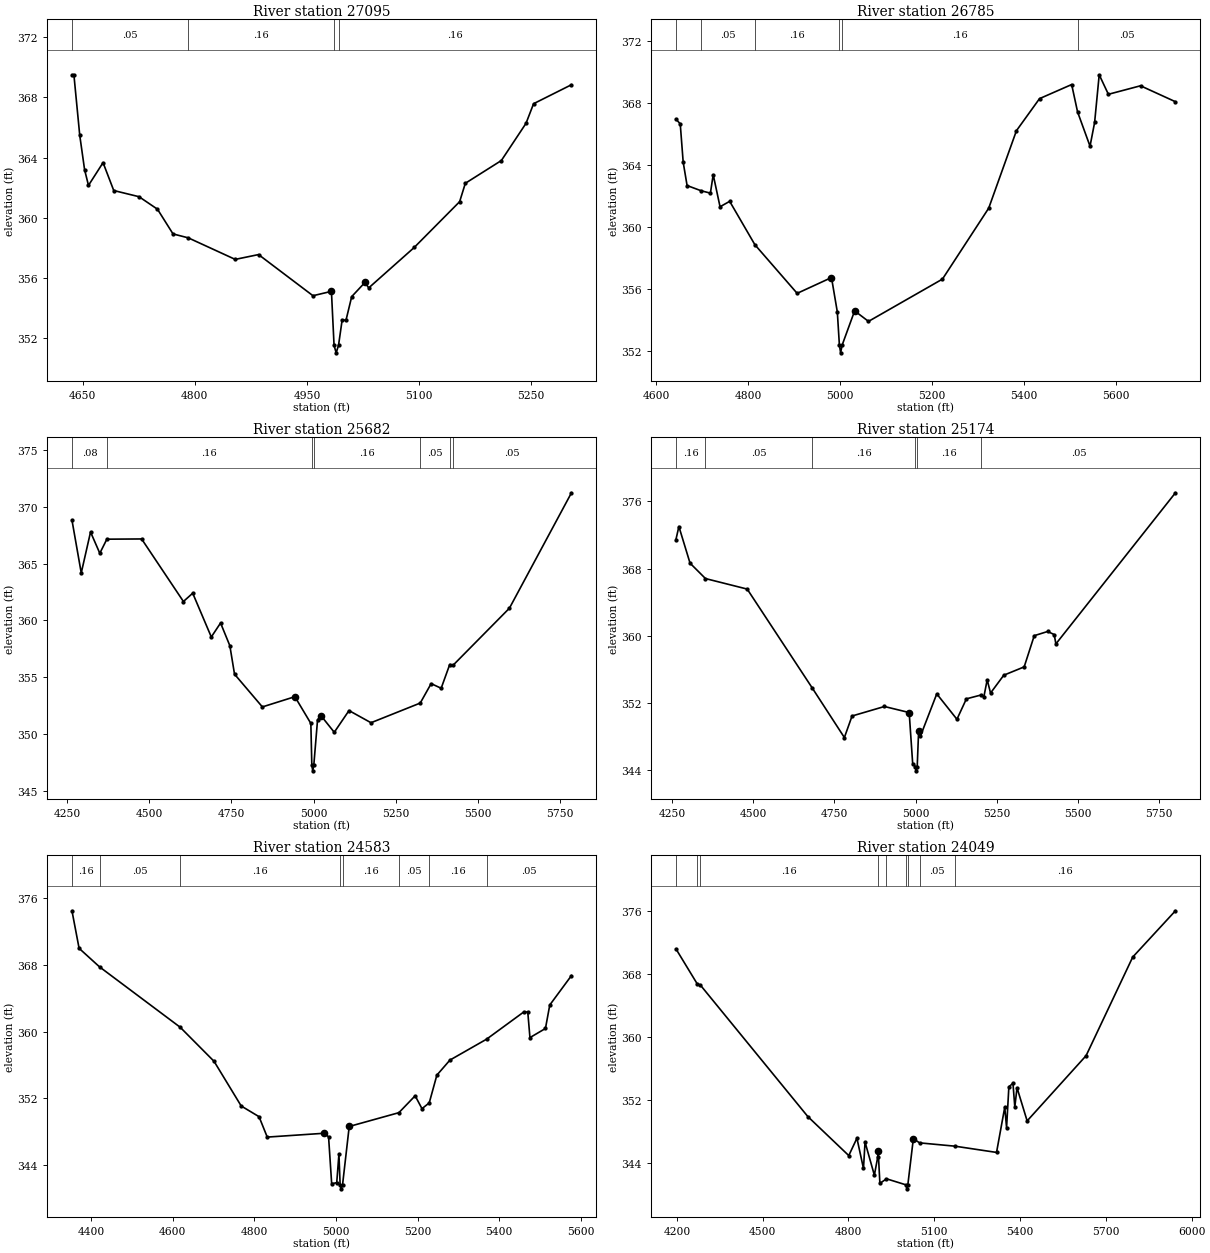
Type RM Length L Ch R = 1 ,27095   ,310,310,310
BEGIN DESCRIPTION:
UNT043 IN BECR 48.0
END DESCRIPTION:
XS GIS Cut Line= 3
      3811549.64      10501910.2      3811199.61     10501810.19
      3810899.59     10501860.19
#Sta/Elev= 30
  4635.6  369.49  4638.2  369.49    4646  365.48  4652.5  363.19  4657.7  362.15
  4677.2  363.66  4691.5  361.81  4725.3   361.4    4750  360.57  4770.8  358.93
  4791.2  358.67    4854  357.24  4885.2  357.56    4958  354.83  4982.7  355.12
  4986.2  351.54    4989  351.04  4992.2  351.54    4997  353.21  5002.2  353.21
  5009.8  354.77  5027.5  355.71  5032.6  355.35  5093.4  358.03  5154.2  361.07
  5161.8  362.29    5210   363.8    5243  366.27  5253.1  367.57  5303.8  368.83
#Mann= 4 ,-1 , 0
  4635.6     .05       0  4791.2     .16       0  4986.2     .07       0
  4992.2     .16       0
Bank Sta=4982.7,5027.5
XS Rating Curve= 0 ,0
Exp/Cntr=0.3,0.1

Type RM Length L Ch R = 1 ,26785   ,1103,1103,1103
BEGIN DESCRIPTION:
Mapping XS e8eb8547
END DESCRIPTION:
XS GIS Cut Line= 4
      3811612.66     10501660.31      3811447.76     10501547.49
      3810866.17     10501616.93       3810563.5     10501616.93
#Sta/Elev= 30
  4642.4  366.97  4651.8  366.66  4658.2  364.19  4666.7  362.68  4697.6  362.34
  4717.5  362.19  4723.6  363.38  4738.5  361.31  4759.5  361.66  4814.4  358.86
  4906.5  355.72  4981.3  356.74    4994  354.52  4998.5  352.38  5001.2  351.88
  5004.5  352.38  5031.7  354.59  5061.9  353.91    5223  356.64  5323.8  361.22
  5384.2  366.22  5434.5  368.29  5504.5   369.2  5517.4  367.43  5544.5  365.22
  5554.5  366.75  5564.5  369.83  5584.5  368.57  5654.5  369.12  5730.6  368.09
#Mann= 6 ,-1 , 0
  4642.4     .08       0  4697.6     .05       0  4814.4     .16       0
  4998.5     .07       0  5004.5     .16       0  5517.4     .05       0
Bank Sta=4981.3,5031.7
XS Rating Curve= 0 ,0
Exp/Cntr=0.3,0.1

Type RM Length L Ch R = 1 ,25682   ,508,508,508
BEGIN DESCRIPTION:
UNT043 IN BECR 47.0
END DESCRIPTION:
XS GIS Cut Line= 3
       3811649.6     10501510.18      3811149.61     10501010.19
      3810349.65      10500860.2
#Sta/Elev= 30
  4264.3  368.82  4292.6  364.17  4320.9  367.77  4349.1   365.9  4370.6  367.14
  4476.4  367.16  4603.7  361.66    4632  362.39  4688.6  358.54  4716.8  359.77
  4745.1  357.77  4759.3  355.27  4844.1  352.39  4943.1  353.29  4991.7  350.94
  4994.7  347.27  4997.4  346.77  5000.7  347.27  5012.1  351.25  5022.3  351.63
    5063  350.16  5107.9  352.07  5174.9     351  5324.8  352.73    5358  354.44
  5388.5  354.03  5414.6  356.12  5424.6  356.05  5596.3  361.07  5785.3  371.22
#Mann= 7 ,-1 , 0
  4264.3     .08       0  4370.6     .16       0  4994.7     .07       0
  5000.7     .16       0  5324.8     .05       0  5414.6     .08       0
  5424.6     .05       0
Bank Sta=4943.1,5022.3
XS Rating Curve= 0 ,0
Exp/Cntr=0.3,0.1

Type RM Length L Ch R = 1 ,25174   ,591,591,591
BEGIN DESCRIPTION:
UNT043 IN BECR 46.0
END DESCRIPTION:
XS GIS Cut Line= 3
       3811699.6     10500310.19      3810999.61     10500610.19
      3810249.59     10500810.19
#Sta/Elev= 30
  4262.1  371.44  4271.2     373  4305.6  368.64  4353.1  366.81  4481.5  365.56
  4681.1  353.84  4780.7  347.91  4804.3  350.47    4904   351.6  4980.2  350.88
    4991  344.78  4998.9  344.45  5001.7  343.95  5004.9  344.45  5009.2  348.65
  5014.6  348.06  5065.1   353.1  5127.2  350.08  5156.3  352.51  5202.7  352.98
    5210  352.73  5220.3  354.77  5230.7   353.2  5271.4  355.32  5334.2  356.31
  5365.2  360.02  5406.6  360.52  5426.7  360.15  5431.8  359.04  5799.9  377.01
#Mann= 6 ,-1 , 0
  4262.1     .16       0  4353.1     .05       0  4681.1     .16       0
  4998.9     .07       0  5004.9     .16       0  5202.7     .05       0
Bank Sta=4980.2,5009.2
XS Rating Curve= 0 ,0
Exp/Cntr=0.3,0.1

Type RM Length L Ch R = 1 ,24583   ,534,534,534
BEGIN DESCRIPTION:
UNT043 IN BECR 45.0
END DESCRIPTION:
XS GIS Cut Line= 3
      3811687.12     10500253.22      3811049.61     10500210.19
       3810499.6     10500410.19
#Sta/Elev= 30
    4353  374.44  4370.5  369.95  4420.6  367.73  4618.2  360.51  4701.3  356.43
  4767.8  351.09  4811.5  349.81  4831.6  347.37  4971.9  347.83  4981.9   347.4
  4989.5  341.79  5001.9  341.92  5007.3  345.33  5010.2  341.68    5013  341.18
  5016.2  341.68  5032.5  348.64  5154.2  350.29  5194.1  352.31  5210.8  350.77
  5228.6  351.46  5247.3  354.78  5279.3  356.58  5369.1  359.08  5460.1  362.33
  5470.1  362.33  5475.4  359.27  5513.4  360.36    5524  363.17  5577.2  366.69
#Mann= 8 ,-1 , 0
    4353     .16       0  4420.6     .05       0  4618.2     .16       0
  5010.2     .07       0  5016.2     .16       0  5154.2     .05       0
  5228.6     .16       0  5369.1     .05       0
Bank Sta=4971.9,5032.5
XS Rating Curve= 0 ,0
Exp/Cntr=0.3,0.1

Type RM Length L Ch R = 1 ,24049   ,389,389,389
BEGIN DESCRIPTION:
UNT043 IN BECR 44.0
END DESCRIPTION:
XS GIS Cut Line= 3
      3811699.64      10500210.2      3811049.61     10499910.19
      3810249.61     10499260.19
#Sta/Elev= 30
  4196.7  371.15  4272.1  366.66  4281.6  366.59  4657.9  349.92  4801.1  344.98
  4829.6  347.18  4852.5  343.35    4858  346.69  4890.6   342.5  4902.2  344.77
  4903.9   345.6  4909.9  341.46    4933  342.04  5001.6  341.27  5004.3  340.77
  5007.6  341.27  5026.9  347.12  5048.8  346.59  5172.4  346.17  5317.8  345.38
  5346.5   351.1  5352.9  348.52  5360.9  353.68  5375.2  354.14  5381.7  351.12
  5389.4  353.57  5424.8  349.37    5631  357.63    5794  370.11  5943.4  375.97
#Mann= 9 ,-1 , 0
  4196.7     .16       0  4272.1     .05       0  4281.6     .16       0
  4902.2     .12       0    4933     .16       0  5001.6     .07       0
  5007.6     .16       0  5048.8     .05       0  5172.4     .16       0
Bank Sta=4903.9,5026.9
XS Rating Curve= 0 ,0
Exp/Cntr=0.3,0.1

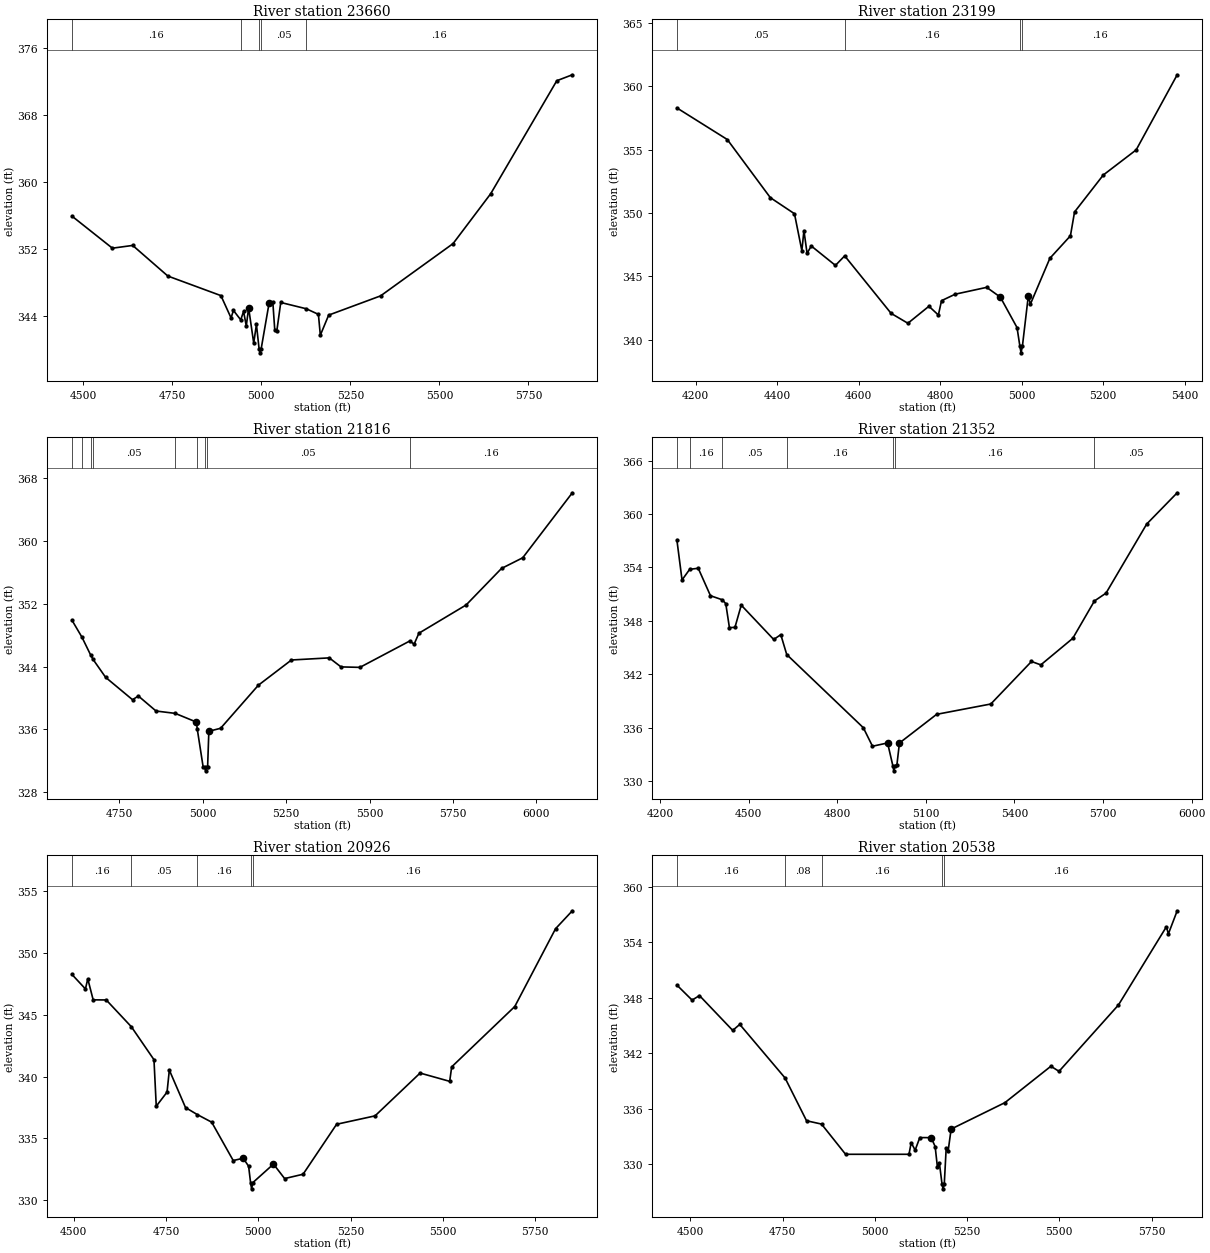
Type RM Length L Ch R = 1 ,23660   ,461,461,461
BEGIN DESCRIPTION:
UNT043 IN BECR 43.0
END DESCRIPTION:
XS GIS Cut Line= 3
      3811499.63     10499960.21      3811149.61     10499560.19
      3810349.65     10499210.21
#Sta/Elev= 30
  4468.4  355.89  4581.8  352.06  4638.8  352.39  4737.5  348.73  4886.5  346.39
    4915  343.72  4921.6  344.62  4942.2  343.49  4950.1  344.51  4957.7  342.76
  4964.3  344.92  4978.6  340.71  4986.2  342.95  4993.6  340.05  4996.4  339.55
  4999.6  340.05  5021.8  345.51  5032.3  345.58  5037.7  342.26  5043.6  342.22
  5054.5  345.57  5126.1  344.82  5160.2  344.15  5165.6  341.66    5189  344.06
  5334.8  346.36  5538.3  352.61  5643.9  358.57  5829.5  372.08  5873.1  372.79
#Mann= 5 ,-1 , 0
  4468.4     .16       0  4942.2     .05       0  4993.6     .04       0
  4999.6     .05       0  5126.1     .16       0
Bank Sta=4964.3,5021.8
XS Rating Curve= 0 ,0
Exp/Cntr=0.3,0.1

Type RM Length L Ch R = 1 ,23199   ,1383,1383,1383
BEGIN DESCRIPTION:
UNT043 IN BECR 42.0
END DESCRIPTION:
XS GIS Cut Line= 3
      3811749.61     10499010.19      3810949.61     10499210.19
      3810549.64     10499160.19
#Sta/Elev= 30
  4154.2  358.28  4277.9  355.79  4383.5  351.21  4442.8  349.94  4460.9  347.03
    4466  348.61  4473.7  346.82    4484   347.4  4543.3  345.87    4566  346.62
  4679.9  342.09  4721.1  341.31  4772.7  342.65  4795.9  341.96  4803.6  343.09
  4837.1   343.6  4914.4  344.14  4947.9  343.37  4988.9  340.97    4996  339.48
  4998.7  338.98    5002  339.48  5016.6  343.48  5021.6  342.81  5069.5  346.43
  5119.9   348.2    5130  350.08  5200.5  352.99  5281.2  354.97  5381.9  360.89
#Mann= 4 ,-1 , 0
  4154.2     .05       0    4566     .16       0    4996     .07       0
    5002     .16       0
Bank Sta=4947.9,5016.6
XS Rating Curve= 0 ,0
Exp/Cntr=0.3,0.1

Type RM Length L Ch R = 1 ,21816   ,464,464,464
BEGIN DESCRIPTION:
UNT043 IN BECR 41.0
END DESCRIPTION:
XS GIS Cut Line= 3
      3811649.59     10498310.19      3811249.61     10498360.19
       3810449.6      10499110.2
#Sta/Elev= 30
  4608.2  349.91  4638.1  347.75  4663.7  345.52  4671.4  344.92    4709  342.64
  4789.6  339.79  4807.2  340.26  4860.1  338.35  4917.6  338.05  4981.1  336.94
  4983.8  336.02  5001.2  331.25  5005.8  331.23  5008.5  330.73  5011.8  331.23
  5014.7  331.23  5018.4  335.77  5053.6  336.15  5166.9  341.64    5266  344.85
  5379.3  345.12  5414.5  343.97  5471.2  343.91  5620.2  347.26  5633.8  346.88
    5648  348.26  5789.6  351.86  5895.6  356.51  5959.2  357.87  6107.9  366.15
#Mann= 9 ,-1 , 0
  4608.2     .08       0  4638.1     .05       0  4663.7     .08       0
  4671.4     .05       0  4917.6     .16       0  4983.8     .05       0
  5005.8     .03       0  5011.8     .05       0  5620.2     .16       0
Bank Sta=4981.1,5018.4
XS Rating Curve= 0 ,0
Exp/Cntr=0.3,0.1

Type RM Length L Ch R = 1 ,21352   ,426,426,426
BEGIN DESCRIPTION:
UNT043 IN BECR 40.0
END DESCRIPTION:
XS GIS Cut Line= 3
       3811849.6     10498160.19      3811099.61     10497960.19
      3810299.59      10498410.2
#Sta/Elev= 30
    4257  357.11  4274.5   352.6  4300.4  353.79  4329.4  353.91  4370.8  350.83
    4411  350.37  4422.6  349.94  4434.9  347.26  4453.6  347.27    4475  349.77
  4584.9  345.92  4608.9  346.46    4629  344.23  4888.3  336.02  4919.4  333.94
  4970.5  334.31  4988.8  331.68  4991.6  331.18  4994.8  331.68  5002.2  331.89
  5010.6   334.3  5136.5  337.52    5320  338.68  5457.7  343.45  5489.3  343.07
  5597.6  346.05  5670.8  350.24  5710.1  351.12  5847.8  358.87  5951.1  362.38
#Mann= 7 ,-1 , 0
    4257     .08       0  4300.4     .16       0    4411     .05       0
    4629     .16       0  4988.8     .07       0  4994.8     .16       0
  5670.8     .05       0
Bank Sta=4970.5,5010.6
XS Rating Curve= 0 ,0
Exp/Cntr=0.3,0.1

Type RM Length L Ch R = 1 ,20926   ,388,388,388
BEGIN DESCRIPTION:
UNT043 IN BECR 39.0
END DESCRIPTION:
XS GIS Cut Line= 3
      3811599.59      10497310.2      3811199.61     10497610.19
      3810399.59     10497910.19
#Sta/Elev= 30
  4495.7  348.25  4532.1  347.08  4538.4   347.9    4553   346.2  4588.4  346.19
  4656.5  344.02  4717.6  341.36  4723.8   337.6    4753  338.74  4759.2  340.52
    4803  337.49  4834.5  336.93  4873.8  336.31  4932.1  333.21  4959.2  333.39
  4973.8  332.75  4979.1  331.42  4981.9  330.92  4985.1  331.42  5041.1  332.92
  5071.3  331.75  5121.2   332.1    5212  336.14  5316.1  336.82    5438  340.28
  5518.1  339.61  5523.5  340.78  5694.3  345.66  5804.7  351.95  5850.1   353.4
#Mann= 5 ,-1 , 0
  4495.7     .16       0  4656.5     .05       0  4834.5     .16       0
  4979.1     .07       0  4985.1     .16       0
Bank Sta=4959.2,5041.1
XS Rating Curve= 0 ,0
Exp/Cntr=0.3,0.1

Type RM Length L Ch R = 1 ,20538   ,52,52,52
BEGIN DESCRIPTION:
Mapping XS 4bcc19ff
END DESCRIPTION:
XS GIS Cut Line= 3
      3811630.91     10497281.35      3811040.63     10497260.51
      3810333.96     10497554.96
#Sta/Elev= 30
  4463.2  349.38  4504.5  347.75  4524.5  348.24  4614.6  344.47  4633.7  345.12
  4756.5  339.32  4814.7  334.69  4855.3  334.33  4920.5  331.06  5092.4  331.06
  5098.3  332.32  5109.1  331.51  5121.7  332.87  5152.5  332.86  5163.3   331.9
  5169.4  329.69  5174.8  330.11    5182  327.82  5184.7  327.32    5188  327.82
  5193.2   331.7  5198.6  331.44  5206.6  333.79  5352.4  336.65    5477  340.59
  5499.1  340.04  5660.1  347.22  5790.1  355.69  5795.5  354.92  5819.4  357.42
#Mann= 5 ,-1 , 0
  4463.2     .16       0  4756.5     .08       0  4855.3     .16       0
    5182     .07       0    5188     .16       0
Bank Sta=5152.5,5206.6
XS Rating Curve= 0 ,0
Exp/Cntr=0.3,0.1

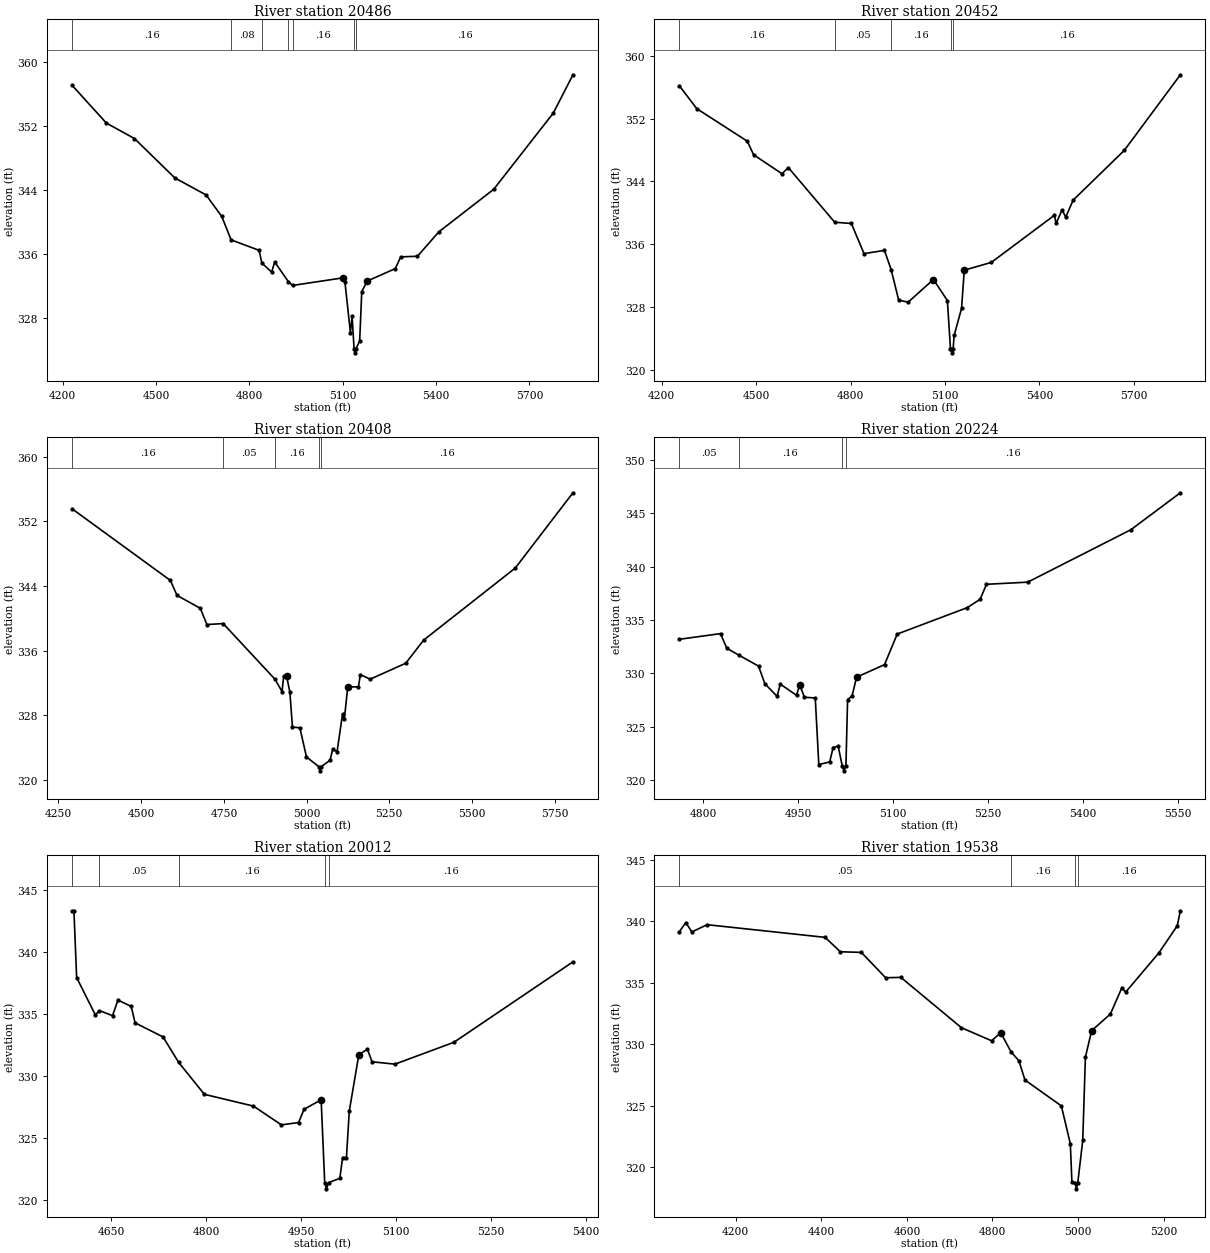
Type RM Length L Ch R = 1 ,20486   ,34,34,34
BEGIN DESCRIPTION:
UNT043 IN BECR 38.0
END DESCRIPTION:
XS GIS Cut Line= 3
      3811849.59     10497260.19      3811049.61     10497210.19
      3810299.62     10497510.18
#Sta/Elev= 30
  4230.6  357.14  4340.8   352.4    4431  350.46  4561.2  345.51  4661.4  343.38
  4711.5   340.7  4741.7  337.75  4831.7  336.44  4840.5  334.85  4871.8  333.71
  4881.8  334.98  4925.5  332.52  4939.4  332.04  5100.8  332.99  5107.5  332.44
    5125  326.12  5130.4  328.17  5136.8  324.09  5139.6  323.59  5142.8  324.09
  5154.7  325.08  5161.4  331.26  5178.9  332.59  5269.1  334.15  5286.6  335.62
  5340.4   335.7  5409.1  338.76  5585.5   344.1  5776.6  353.64  5839.9  358.45
#Mann= 7 ,-1 , 0
  4230.6     .16       0  4741.7     .08       0  4840.5     .16       0
  4925.5     .05       0  4939.4     .16       0  5136.8     .07       0
  5142.8     .16       0
Bank Sta=5100.8,5178.9
XS Rating Curve= 0 ,0
Exp/Cntr=0.3,0.1

Type RM Length L Ch R = 1 ,20452   ,44,44,44
BEGIN DESCRIPTION:
Mapping XS 3544c104
END DESCRIPTION:
XS GIS Cut Line= 3
      3811814.86     10497229.24      3811030.31     10497176.06
      3810280.55     10497471.19
#Sta/Elev= 30
  4256.2  356.16  4311.3  353.26  4471.9  349.11    4492  347.38  4582.2  344.96
  4602.2  345.75  4749.7  338.78  4802.7  338.62  4842.8  334.78  4907.8  335.19
  4929.2  332.72    4953  328.85  4983.1  328.59  5063.4  331.48  5107.8   328.8
  5117.6  322.63    5120  322.63  5122.7  322.13    5126  322.63  5129.3  324.35
  5152.8  327.79  5161.5  332.67  5247.5  333.66    5448  339.67  5453.4  338.63
  5472.4  340.36  5483.9  339.43  5507.5   341.6    5670  347.94  5848.3  357.58
#Mann= 5 ,-1 , 0
  4256.2     .16       0  4749.7     .05       0  4929.2     .16       0
    5120     .07       0    5126     .16       0
Bank Sta=5063.4,5161.5
XS Rating Curve= 0 ,0
Exp/Cntr=0.3,0.1

Type RM Length L Ch R = 1 ,20408   ,184,184,184
BEGIN DESCRIPTION:
Mapping XS b0feee9a
END DESCRIPTION:
XS GIS Cut Line= 4
      3811755.94     10497198.02      3811089.24     10497142.46
      3810992.02     10497145.93      3810297.61      10497423.7
#Sta/Elev= 30
  4290.9  353.56  4588.3  344.68  4608.3  342.83  4678.6  341.23  4698.6  339.22
  4747.8  339.34  4904.1  332.46  4925.7  330.92  4930.7  332.81  4939.5  332.85
  4949.5  330.82  4957.2  326.52  4979.6  326.43  4999.6  322.82  5037.5   321.6
  5040.3   321.1  5043.5   321.6  5070.6   322.4    5079  323.77  5092.1  323.46
  5108.7  328.16    5114  327.48  5124.4   331.5  5156.7   331.5  5162.5  333.02
  5192.1  332.45  5299.8  334.43  5353.7  337.29  5630.6  346.21  5805.1  355.54
#Mann= 5 ,-1 , 0
  4290.9     .16       0  4747.8     .05       0  4904.1     .16       0
  5037.5     .07       0  5043.5     .16       0
Bank Sta=4939.5,5124.4
XS Rating Curve= 0 ,0
Exp/Cntr=0.3,0.1

Type RM Length L Ch R = 1 ,20224   ,212,212,212
BEGIN DESCRIPTION:
Mapping XS 87122ea3
END DESCRIPTION:
XS GIS Cut Line= 4
      3811144.43     10497023.34      3810954.52     10497013.58
      3810872.05     10497052.64      3810365.32     10497114.49
#Sta/Elev= 30
    4762  333.19  4826.9  333.72  4836.9  332.34  4855.7  331.71    4887  330.67
    4897  329.02  4916.4  327.83  4921.4  328.98  4947.1  327.93  4952.1  328.93
  4959.5  327.75  4976.7  327.68  4982.3  321.43  4999.5  321.68    5005  323.03
  5012.9  323.17  5019.2  321.34    5022  320.84  5025.2  321.34  5027.8  327.52
    5035  327.89    5042  329.63  5086.2  330.81  5106.3  333.68  5217.1  336.16
  5237.3  336.94  5247.4  338.35  5312.5  338.55  5475.6  343.47  5553.9  346.94
#Mann= 4 ,-1 , 0
    4762     .05       0  4855.7     .16       0  5019.2     .07       0
  5025.2     .16       0
Bank Sta=4952.1,5042
XS Rating Curve= 0 ,0
Exp/Cntr=0.3,0.1

Type RM Length L Ch R = 1 ,20012   ,474,474,474
BEGIN DESCRIPTION:
UNT043 IN BECR 37.0
END DESCRIPTION:
XS GIS Cut Line= 3
      3811199.58     10496610.21      3810849.61     10496860.19
      3810549.64     10497060.17
#Sta/Elev= 30
  4588.5  343.36  4591.5  343.36  4595.8  337.96  4625.3  334.94  4631.8  335.29
  4652.4  334.88    4661  336.14  4681.9  335.63    4688   334.3  4732.2  333.16
  4756.7  331.11  4797.4  328.52  4874.8  327.57    4919  326.05  4946.1  326.24
  4954.7  327.31  4981.7  328.08  4987.3  321.38  4990.1  320.88  4993.3  321.38
  5011.2  321.73  5015.5  323.41  5021.6  323.41  5026.1  327.17  5041.1  331.71
  5054.6  332.18  5062.1  331.15  5098.2  330.96  5191.3  332.73  5379.1  339.23
#Mann= 5 ,-1 , 0
  4588.5      .1       0  4631.8     .05       0  4756.7     .16       0
  4987.3     .07       0  4993.3     .16       0
Bank Sta=4981.7,5041.1
XS Rating Curve= 0 ,0
Exp/Cntr=0.3,0.1

Type RM Length L Ch R = 1 ,19538   ,450,450,450
BEGIN DESCRIPTION:
UNT043 IN BECR 36.0
END DESCRIPTION:
XS GIS Cut Line= 3
      3811181.92     10496041.37      3810549.61     10496710.19
      3810349.61     10496860.19
#Sta/Elev= 30
  4068.6  339.15  4083.4  339.88  4097.6  339.12  4133.2  339.71  4409.1  338.68
  4444.3  337.51  4493.6  337.46  4550.3   335.4  4585.9  335.43  4727.5  331.34
  4797.9  330.28  4819.3  330.93  4843.4  329.38  4861.8  328.65  4875.9  327.09
  4960.9  324.99  4981.9  321.91  4985.6  318.79  4993.3  318.75    4996  318.25
  4999.3  318.75  5010.9  322.18  5017.1  328.95  5031.7   331.1  5075.5  332.45
  5102.5   334.6  5110.9  334.22    5189  337.43  5231.7  339.62    5239  340.84
#Mann= 4 ,-1 , 0
  4068.6     .05       0  4843.4     .16       0  4993.3     .07       0
  4999.3     .16       0
Bank Sta=4819.3,5031.7
XS Rating Curve= 0 ,0
Exp/Cntr=0.3,0.1

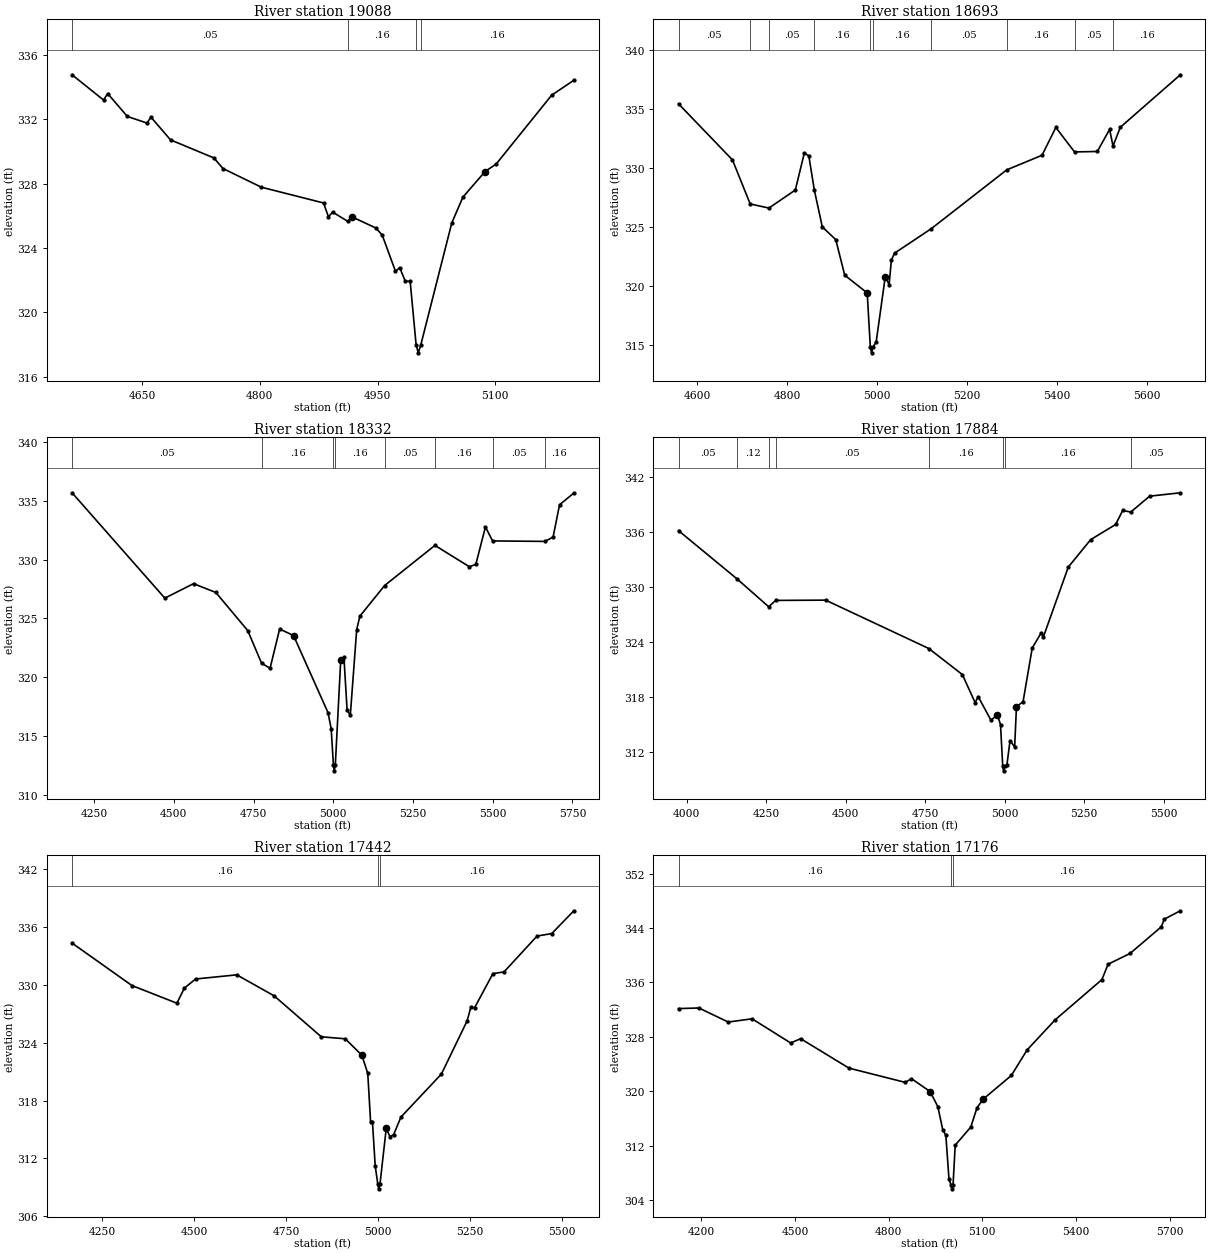
Type RM Length L Ch R = 1 ,19088   ,395,395,395
BEGIN DESCRIPTION:
UNT043 IN BECR 35.0
END DESCRIPTION:
XS GIS Cut Line= 3
      3810749.65     10496210.17      3810349.61     10496360.19
      3810199.59     10496510.21
#Sta/Elev= 30
  4560.8  334.78  4600.9  333.21  4606.2  333.61  4631.2  332.19  4656.1  331.78
  4661.4  332.14  4686.3  330.73  4741.5  329.61  4753.1  328.95    4802  327.79
  4881.2  326.81  4887.5  325.95  4892.8  326.24    4912  325.67  4917.7  325.94
    4948  325.25    4956  324.81  4972.9  322.56  4978.3  322.79  4985.4  321.94
  4991.6  321.94  4999.2  317.99  5001.9  317.49  5005.2  317.99  5044.6  325.56
  5058.8  327.17    5087  328.76  5101.2  329.23  5171.9  333.51  5200.2  334.44
#Mann= 4 ,-1 , 0
  4560.8     .05       0    4912     .16       0  4999.2     .07       0
  5005.2     .16       0
Bank Sta=4917.7,5087
XS Rating Curve= 0 ,0
Exp/Cntr=0.3,0.1

Type RM Length L Ch R = 1 ,18693   ,361,361,361
BEGIN DESCRIPTION:
UNT043 IN BECR 34.0
END DESCRIPTION:
XS GIS Cut Line= 3
      3810699.59     10496010.19      3810249.61     10496010.19
       3810099.6     10496660.22
#Sta/Elev= 30
  4558.1  335.44  4678.1   330.7  4717.6  326.97  4759.3  326.62  4818.1  328.15
  4838.1  331.27  4848.1  331.05  4860.3  328.17  4878.1  325.03  4908.1  323.95
  4928.1  320.94  4978.1  319.44  4985.1  314.87  4987.8  314.37  4991.1  314.87
  4998.1  315.29  5018.3  320.81  5026.9  320.15    5032  322.23  5038.9   322.8
  5120.9  324.88  5288.6  329.85  5367.3  331.09  5398.1  333.44  5439.7  331.37
  5490.4  331.41  5517.8  333.28  5525.3  331.87  5541.7  333.46  5675.2   337.9
#Mann= 10 ,-1 , 0
  4558.1     .05       0  4717.6     .16       0  4759.3     .05       0
  4860.3     .16       0  4985.1     .07       0  4991.1     .16       0
  5120.9     .05       0  5288.6     .16       0  5439.7     .05       0
  5525.3     .16       0
Bank Sta=4978.1,5018.3
XS Rating Curve= 0 ,0
Exp/Cntr=0.3,0.1

Type RM Length L Ch R = 1 ,18332   ,448,448,448
BEGIN DESCRIPTION:
Mapping XS 79e60a7a
END DESCRIPTION:
XS GIS Cut Line= 4
      3810680.35     10495757.91      3809985.94     10495762.25
      3809985.94     10495996.62      3810077.09     10496634.65
#Sta/Elev= 30
  4181.1  335.67  4471.9  326.72  4561.9  327.95  4631.9   327.2  4731.9  323.96
  4775.3  321.19  4801.9  320.76  4831.9   324.1  4875.5  323.54  4983.5     317
  4993.5  315.63  5000.5  312.55  5003.2  312.05  5006.5  312.55  5023.5  321.49
  5033.5  321.69  5043.5  317.18  5053.5  316.78  5073.5  324.05  5083.5  325.19
    5161  327.79  5318.8   331.2  5426.6  329.39  5446.9  329.58  5477.2  332.77
  5499.5  331.58  5663.8  331.54  5689.3  331.91  5709.5  334.65  5754.4  335.65
#Mann= 8 ,-1 , 0
  4181.1     .05       0  4775.3     .16       0  5000.5     .07       0
  5006.5     .16       0    5161     .05       0  5318.8     .16       0
  5499.5     .05       0  5663.8     .16       0
Bank Sta=4875.5,5023.5
XS Rating Curve= 0 ,0
Exp/Cntr=0.3,0.1

Type RM Length L Ch R = 1 ,17884   ,442,442,442
BEGIN DESCRIPTION:
UNT043 IN BECR 33.0
END DESCRIPTION:
XS GIS Cut Line= 3
       3810692.4     10495702.82      3809635.06     10495718.44
      3809229.64      10496045.9
#Sta/Elev= 30
    3974  336.19  4158.6  330.91  4257.5  327.89  4279.7  328.58  4436.8  328.61
  4761.5  323.33  4866.9  320.49  4906.9  317.44  4916.9  318.07  4956.9  315.51
  4976.9  316.11  4986.9  315.04  4993.9  310.49  4996.6  309.99  4999.9  310.49
  5006.9   310.6  5016.9  313.29  5031.4   312.6  5037.1  316.98  5057.9  317.54
  5086.7  323.39  5115.5  325.07  5121.9  324.61  5200.2  332.22  5270.6  335.21
    5349  336.86  5371.3  338.39  5396.8  338.22  5456.1  339.95  5552.6  340.32
#Mann= 8 ,-1 , 0
    3974     .05       0  4158.6     .12       0  4257.5     .16       0
  4279.7     .05       0  4761.5     .16       0  4993.9     .07       0
  4999.9     .16       0  5396.8     .05       0
Bank Sta=4976.9,5037.1
XS Rating Curve= 0 ,0
Exp/Cntr=0.3,0.1

Type RM Length L Ch R = 1 ,17442   ,266,266,266
BEGIN DESCRIPTION:
UNT043 IN BECR 32.0
END DESCRIPTION:
XS GIS Cut Line= 3
      3810649.62     10495560.19      3809849.61     10495410.19
      3809299.56     10495410.19
#Sta/Elev= 30
  4168.6  334.32  4331.4  329.92  4453.5  328.09  4473.8  329.65  4504.4   330.6
  4616.3  331.03    4718  328.85    4846  324.61  4911.3   324.4  4956.3   322.7
  4972.4  320.81    4980  315.82  4985.1  315.82  4992.6  311.24  4999.6  309.35
  5002.3  308.85  5005.6  309.35  5022.6  315.11  5032.6  314.27  5042.6  314.46
  5062.6  316.29  5172.6  320.75  5242.6  326.27  5252.6  327.69  5262.6  327.61
  5312.6  331.16  5342.6  331.33  5432.6  335.05  5472.6  335.31  5532.6  337.67
#Mann= 3 ,-1 , 0
  4168.6     .16       0  4999.6     .07       0  5005.6     .16       0
Bank Sta=4956.3,5022.6
XS Rating Curve= 0 ,0
Exp/Cntr=0.3,0.1

Type RM Length L Ch R = 1 ,17176   ,738,738,738
BEGIN DESCRIPTION:
UNT043 IN BECR 31.0
END DESCRIPTION:
XS GIS Cut Line= 3
      3810598.64     10495437.21      3810067.35     10495161.15
      3809058.42     10495135.15
#Sta/Elev= 30
  4126.5  332.16  4191.7  332.25  4285.8  330.18  4362.1  330.66    4486   327.1
  4517.7  327.74  4672.5  323.41    4853  321.31    4873  321.86    4933  319.95
  4957.4  317.74  4973.1  314.37  4983.1  313.53  4993.1  307.12  5000.1  306.16
  5002.8  305.66  5006.1  306.16  5013.1  312.08  5063.1  314.75  5083.1  317.59
  5103.1  318.86  5193.1  322.33  5243.1  326.06  5333.2   330.5  5483.2  336.42
  5503.2  338.69  5573.3  340.26  5673.3  344.17  5683.3  345.31  5734.5  346.54
#Mann= 3 ,-1 , 0
  4126.5     .16       0  5000.1     .07       0  5006.1     .16       0
Bank Sta=4933,5103.1
XS Rating Curve= 0 ,0
Exp/Cntr=0.3,0.1