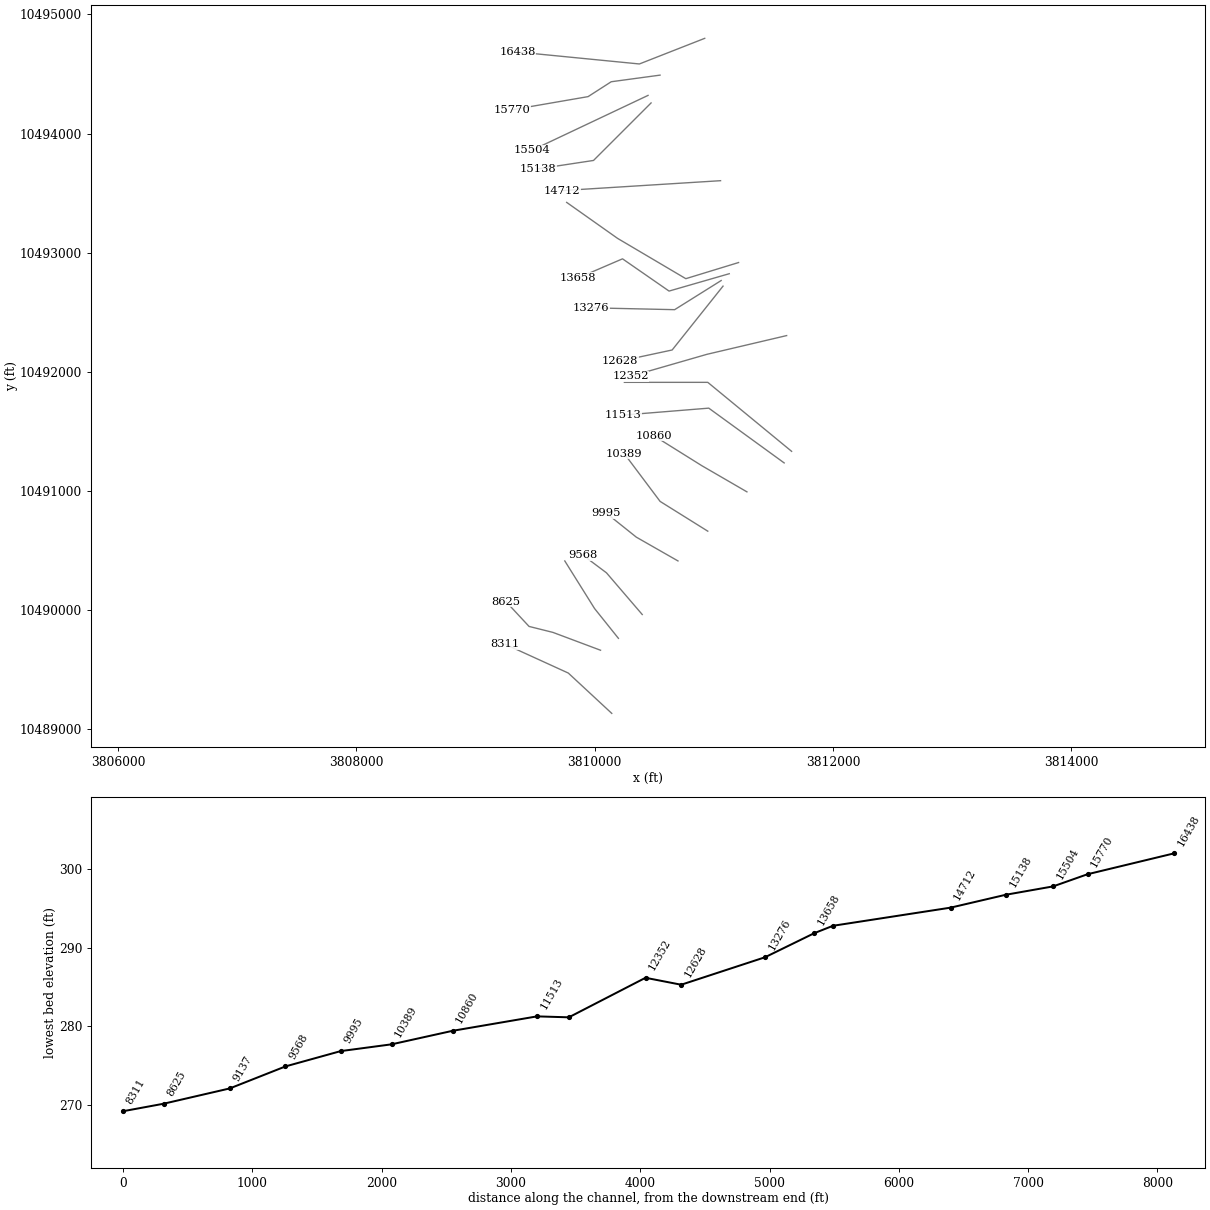
HEC-RAS study UNT043 IN BECR.prj: UNT043 IN BECR Base Level Engineering

--- UNT043 IN BECR.g01 (geometry) --- (continued)

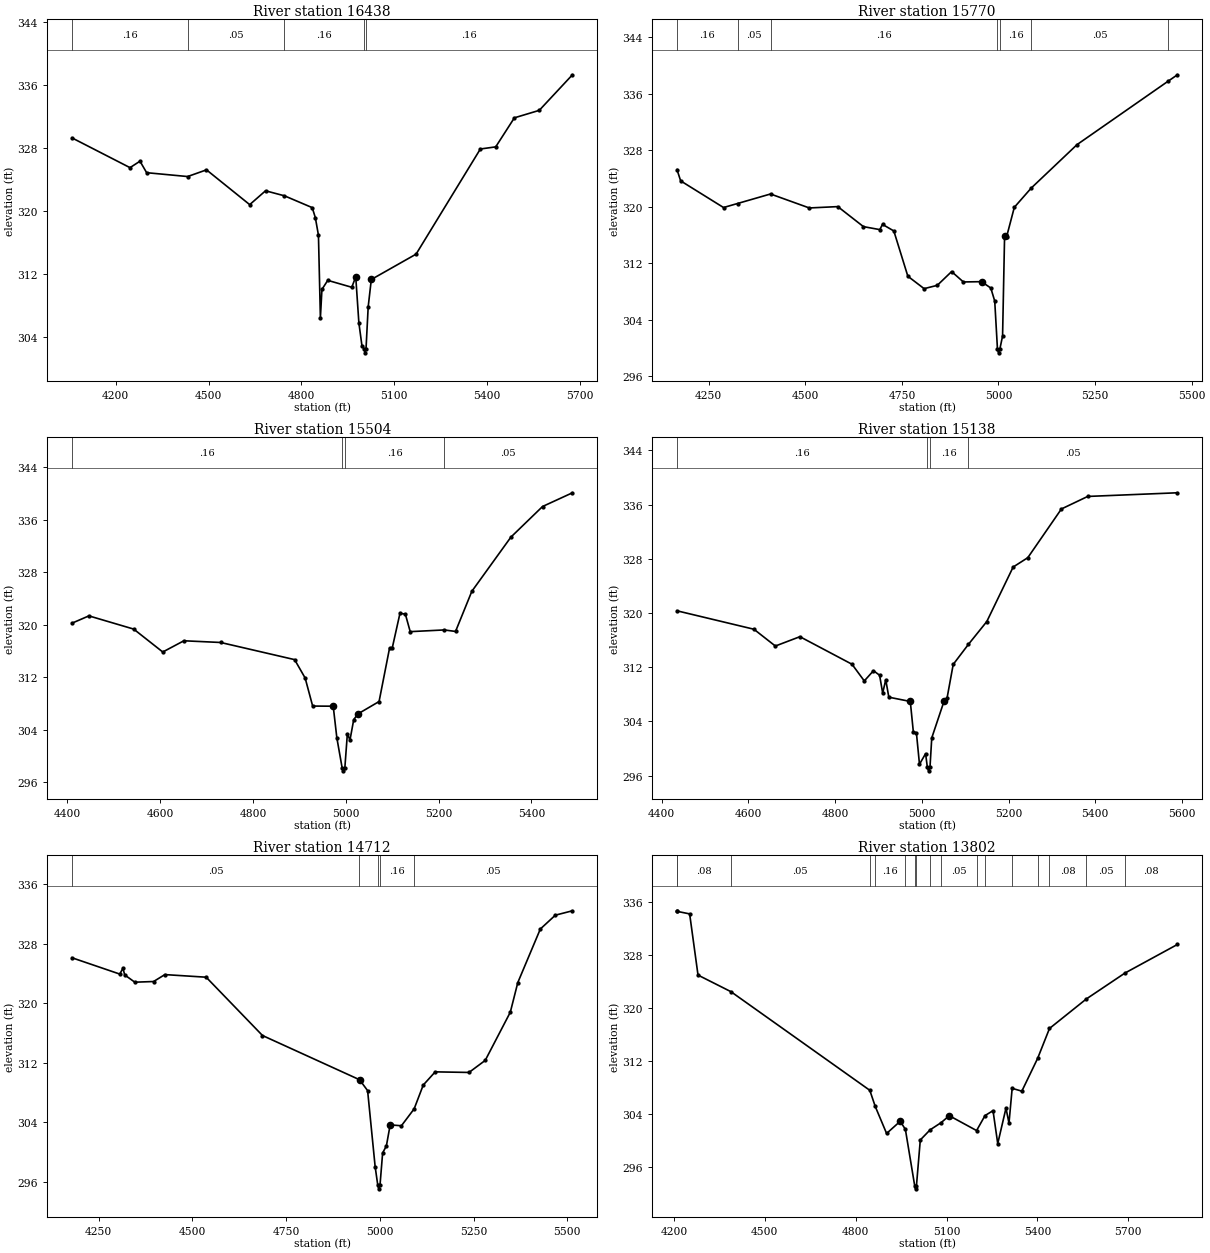
Type RM Length L Ch R = 1 ,16438   ,668,668,668
BEGIN DESCRIPTION:
UNT043 IN BECR 30.0
END DESCRIPTION:
XS GIS Cut Line= 3
      3810924.05     10494799.47      3810375.46      10494584.2
       3809352.9     10494684.72
#Sta/Elev= 30
  4058.9  329.24  4246.3  325.46  4278.5  326.28    4300  324.82  4432.4  324.33
  4493.4  325.18    4633  320.76  4684.2  322.52  4745.4  321.88    4835  320.38
    4845  319.12  4855.1  316.88  4861.4  306.38  4866.4  309.99  4885.2  311.14
  4962.8  310.26  4975.6  311.59  4985.7  305.75  4995.7  302.81  5002.8  302.43
  5005.5  301.93  5008.8  302.43  5015.8  307.77  5025.9  311.25  5170.5  314.47
  5378.2  327.83  5427.8   328.1  5488.1  331.79  5568.5  332.74  5675.7  337.26
#Mann= 5 ,-1 , 0
  4058.9     .16       0  4432.4     .05       0  4745.4     .16       0
  5002.8     .07       0  5008.8     .16       0
Bank Sta=4975.6,5025.9
XS Rating Curve= 0 ,0
Exp/Cntr=0.3,0.1

Type RM Length L Ch R = 1 ,15770   ,266,266,266
BEGIN DESCRIPTION:
UNT043 IN BECR 29.0
END DESCRIPTION:
XS GIS Cut Line= 4
      3810549.04     10494490.44      3810139.35     10494434.89
      3809944.91     10494309.89      3809303.62     10494198.97
#Sta/Elev= 30
  4167.8  325.27  4177.3  323.67  4288.3  319.89  4324.5  320.46  4409.9  321.81
  4510.3  319.83  4584.1  320.02  4650.5  317.18  4692.8  316.76  4699.8   317.5
  4729.1  316.57  4765.4  310.15  4807.5  308.39  4841.6  308.86  4878.7  310.81
  4909.1  309.34  4956.1  309.38  4980.1  308.48  4990.3  306.63  4997.4  299.79
  5000.2  299.29  5003.4  299.79  5010.6  301.67  5015.8  315.83  5020.9  315.72
    5041  319.92  5084.6  322.64  5203.4  328.81  5438.6  337.78  5463.2  338.71
#Mann= 7 ,-1 , 0
  4167.8     .16       0  4324.5     .05       0  4409.9     .16       0
  4997.4     .07       0  5003.4     .16       0  5084.6     .05       0
  5438.6     .16       0
Bank Sta=4956.1,5015.8
XS Rating Curve= 0 ,0
Exp/Cntr=0.3,0.1

Type RM Length L Ch R = 1 ,15504   ,366,366,366
BEGIN DESCRIPTION:
UNT043 IN BECR 28.0
END DESCRIPTION:
XS GIS Cut Line= 2
      3810448.38     10494320.31      3809473.65     10493858.96
#Sta/Elev= 30
  4409.9  320.23  4446.3  321.34  4542.8  319.33  4605.5  315.84    4651  317.55
  4730.3  317.29  4889.6  314.68  4912.3  311.88  4928.5  307.61  4972.8  307.59
  4980.6  302.78  4991.9  298.25  4994.7  297.75  4997.9  298.25  5003.3   303.4
  5008.9  302.44    5017  305.55  5026.1  306.42  5071.6   308.3  5094.3  316.47
  5099.9  316.42  5116.6  321.72  5128.2  321.62  5138.7  318.94  5212.1   319.2
  5236.4  318.97  5271.5  325.08  5355.7  333.33  5423.9  337.99  5488.3  340.08
#Mann= 4 ,-1 , 0
  4409.9     .16       0  4991.9     .07       0  4997.9     .16       0
  5212.1     .05       0
Bank Sta=4972.8,5026.1
XS Rating Curve= 0 ,0
Exp/Cntr=0.3,0.1

Type RM Length L Ch R = 1 ,15138   ,426,426,426
BEGIN DESCRIPTION:
UNT043 IN BECR 27.0
END DESCRIPTION:
XS GIS Cut Line= 3
       3810473.8     10494256.93      3809990.73     10493773.86
      3809525.04     10493703.13
#Sta/Elev= 30
  4435.3  320.31  4612.7  317.59  4662.2  315.11  4718.8  316.49    4839  312.42
  4867.3  309.96  4888.5  311.47  4902.6   310.8  4909.7  308.17  4916.8  310.13
  4923.9  307.56  4973.4  306.93  4980.4  302.46  4987.5   302.3  4994.6  297.66
  5008.7  299.23  5012.8  297.19  5015.5  296.69  5018.8  297.19  5022.9  301.55
  5051.1  306.94  5058.2  307.43  5072.4   312.4  5107.5  315.36  5149.9  318.73
  5210.6  326.77  5244.4  328.15  5321.9  335.34  5382.6  337.19  5589.5  337.73
#Mann= 4 ,-1 , 0
  4435.3     .16       0  5012.8     .07       0  5018.8     .16       0
  5107.5     .05       0
Bank Sta=4973.4,5051.1
XS Rating Curve= 0 ,0
Exp/Cntr=0.3,0.1

Type RM Length L Ch R = 1 ,14712   ,910,910,910
BEGIN DESCRIPTION:
UNT043 IN BECR 26.0
END DESCRIPTION:
XS GIS Cut Line= 2
      3811056.91     10493603.86      3809724.11     10493520.56
#Sta/Elev= 30
  4178.6  326.09  4306.1   323.9  4314.4  324.68  4319.4  323.78  4346.2  322.81
  4396.3   322.9  4426.4  323.83  4536.6  323.48  4686.9  315.65  4943.8  309.76
  4947.4  309.61  4967.4  308.25  4987.5  298.05  4994.5  295.56  4997.2  295.06
  5000.5  295.56  5007.5  299.88  5017.5  300.82  5027.6  303.65  5057.6  303.53
  5091.6   305.8  5115.9     309  5147.8  310.77    5238  310.69  5281.3  312.31
  5348.2  318.78  5368.2  322.76  5428.3  329.95  5468.4  331.81    5514   332.4
#Mann= 5 ,-1 , 0
  4178.6     .05       0  4943.8     .16       0  4994.5     .07       0
  5000.5     .16       0  5091.6     .05       0
Bank Sta=4947.4,5027.6
XS Rating Curve= 0 ,0
Exp/Cntr=0.3,0.1

Type RM Length L Ch R = 1 ,13802   ,144,144,144
BEGIN DESCRIPTION:
UNT043 IN BECR 25.0
END DESCRIPTION:
XS GIS Cut Line= 4
      3811208.01     10492916.37      3810765.27     10492780.94
      3810192.35     10493119.48      3809765.25     10493421.59
#Sta/Elev= 30
  4210.4   334.7  4211.1  334.61  4252.2  334.23  4279.8     325  4388.4   322.5
  4846.8  307.62  4864.7  305.19  4902.2  301.11  4947.1  302.95  4964.2  301.73
  4994.8  293.26  4997.6  292.76  5000.8  293.26  5013.4  300.13  5045.8  301.66
  5081.7  302.73  5109.1  303.79  5199.2  301.55    5227  303.81  5253.4  304.55
    5269  299.58  5296.2  304.93  5306.1  302.67  5316.6  307.92  5348.5  307.49
  5400.5  312.42  5439.8  316.95  5561.7  321.41  5688.6   325.3    5862  329.62
#Mann= 17 ,-1 , 0
  4210.4      .1       0  4211.1     .08       0  4388.4     .05       0
  4846.8     .08       0  4864.7     .16       0  4964.2     .08       0
  4994.8     .07       0  5000.8     .08       0  5045.8     .16       0
  5081.7     .05       0  5199.2     .08       0    5227     .16       0
  5316.6     .08       0  5400.5     .12       0  5439.8     .08       0
  5561.7     .05       0  5688.6     .08       0
Bank Sta=4947.1,5109.1
XS Rating Curve= 0 ,0
Exp/Cntr=0.3,0.1

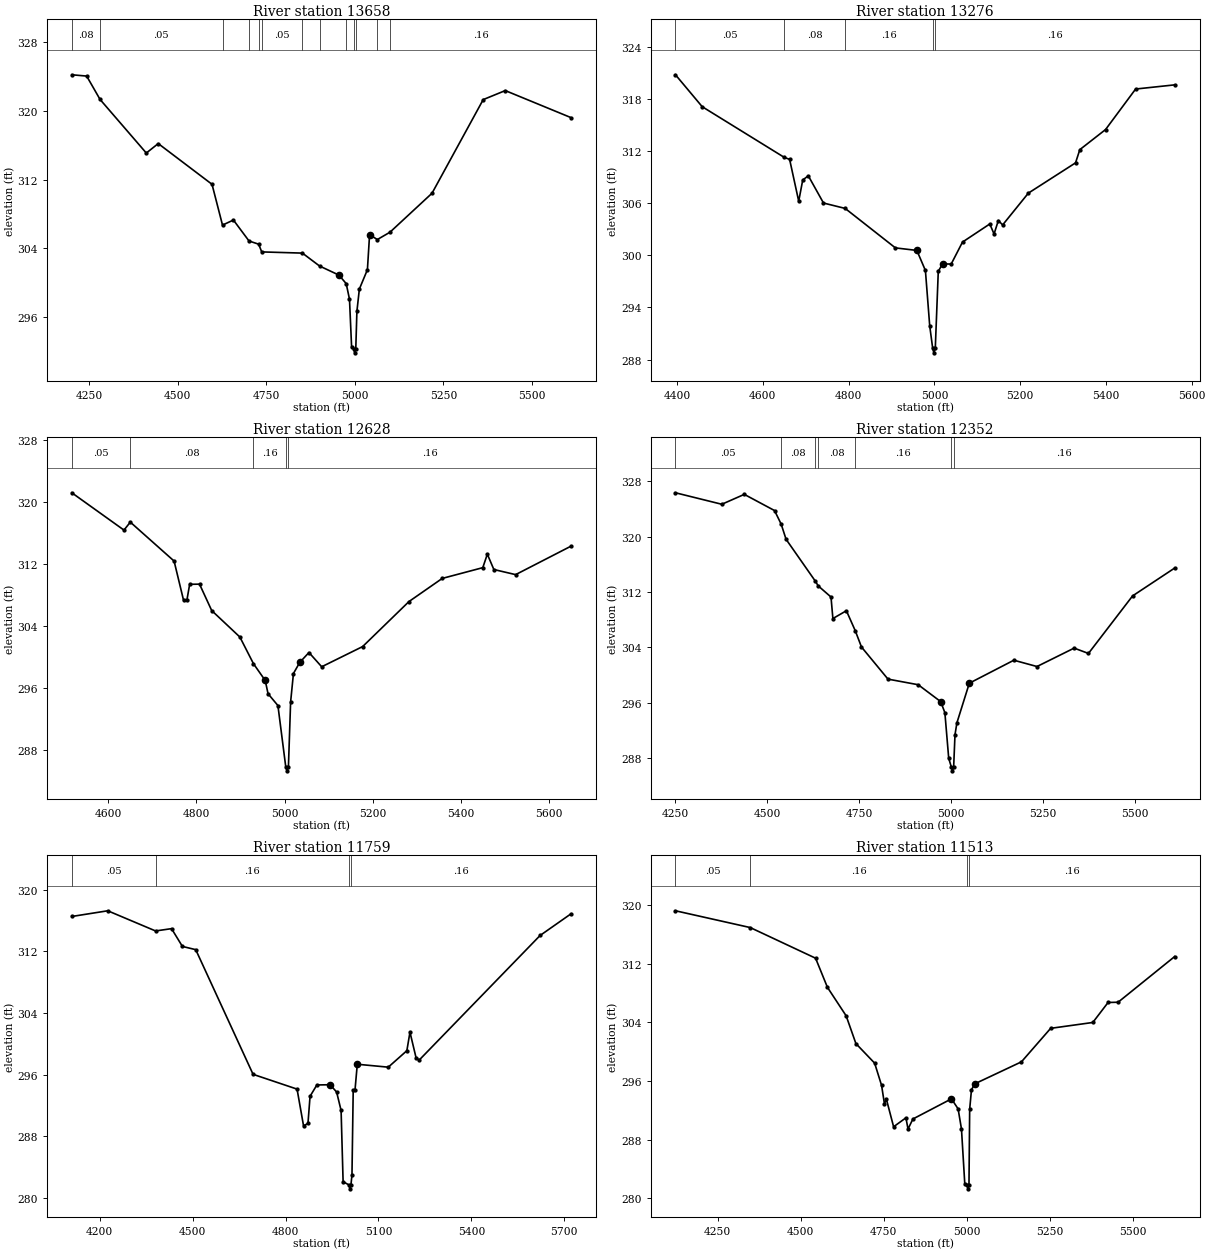
Type RM Length L Ch R = 1 ,13658   ,382,382,382
BEGIN DESCRIPTION:
UNT043 IN BECR 24.0
END DESCRIPTION:
XS GIS Cut Line= 4
      3811129.85     10492822.61      3810624.65     10492676.78
      3810234.02     10492947.61      3809859.06     10492786.17
#Sta/Elev= 30
  4201.1   324.2    4243  324.05  4280.8  321.33  4411.4  315.09  4445.1  316.19
  4596.9  311.45  4626.5   306.7  4657.3  307.29  4701.4  304.85  4728.6  304.48
  4737.2  303.58  4852.1  303.44  4900.4  301.94  4955.2  300.88  4975.7  299.89
    4985  298.08    4991  292.47  4996.8  292.33  4999.6  291.83  5002.8  292.33
  5005.9  296.65  5012.9  299.26  5035.6  301.51  5041.7  305.59  5063.6  305.02
  5099.2  305.87    5218  310.41  5362.5  321.31  5424.8  322.36  5610.5  319.21
#Mann= 13 ,-1 , 0
  4201.1     .08       0  4280.8     .05       0  4626.5     .08       0
  4701.4     .05       0  4728.6     .16       0  4737.2     .05       0
  4852.1     .16       0  4900.4     .05       0  4975.7     .16       0
  4996.8     .07       0  5002.8     .16       0  5063.6     .05       0
  5099.2     .16       0
Bank Sta=4955.2,5041.7
XS Rating Curve= 0 ,0
Exp/Cntr=0.3,0.1

Type RM Length L Ch R = 1 ,13276   ,648,648,648
BEGIN DESCRIPTION:
UNT043 IN BECR 23.0
END DESCRIPTION:
XS GIS Cut Line= 3
      3811062.15     10492765.32      3810671.52     10492520.53
      3809968.39     10492536.15
#Sta/Elev= 30
  4396.2  320.75  4458.5  317.08  4649.9  311.25  4662.4  311.02  4683.6  306.21
    4693  308.65    4706  309.13  4741.4     306  4791.9  305.38  4909.1  300.84
  4959.1  300.55  4979.1  298.24  4989.1  291.88  4996.1  289.27  4998.9  288.77
  5002.1  289.27  5009.1  298.15  5019.1     299  5039.2  298.98  5065.6  301.51
  5129.2  303.59  5139.2  302.44  5149.2  303.99  5159.2  303.48  5219.2  307.14
  5329.2  310.62  5339.2  312.14  5399.2  314.45  5469.3  319.11  5560.5  319.59
#Mann= 5 ,-1 , 0
  4396.2     .05       0  4649.9     .08       0  4791.9     .16       0
  4996.1     .07       0  5002.1     .16       0
Bank Sta=4959.1,5019.1
XS Rating Curve= 0 ,0
Exp/Cntr=0.3,0.1

Type RM Length L Ch R = 1 ,12628   ,276,276,276
BEGIN DESCRIPTION:
UNT043 IN BECR 22.0
END DESCRIPTION:
XS GIS Cut Line= 3
      3811077.77     10492718.44      3810650.69     10492181.98
       3810213.9     10492088.39
#Sta/Elev= 30
  4517.4   321.2  4635.7  316.38  4650.1  317.41  4749.4  312.38  4770.8  307.33
  4778.3  307.29  4784.7  309.38  4807.1   309.4  4834.7  305.99  4898.6  302.57
  4929.5  299.12  4956.1  296.96  4962.5  295.25  4984.9  293.72  5002.7  285.79
  5005.5  285.29  5008.7  285.79  5013.7  294.19  5020.1  297.86  5034.5   299.3
  5055.3  300.57  5084.2  298.73  5177.1  301.34  5282.1  307.15  5357.6  310.14
  5449.6  311.53  5459.9  313.27  5474.7  311.29  5524.1  310.63  5649.8  314.31
#Mann= 5 ,-1 , 0
  4517.4     .05       0  4650.1     .08       0  4929.5     .16       0
  5002.7     .07       0  5008.7     .16       0
Bank Sta=4956.1,5034.5
XS Rating Curve= 0 ,0
Exp/Cntr=0.3,0.1

Type RM Length L Ch R = 1 ,12352   ,593,593,593
BEGIN DESCRIPTION:
UNT043 IN BECR 21.0
END DESCRIPTION:
XS GIS Cut Line= 3
      3811611.62     10492302.96      3810942.35     10492145.53
      3810299.58     10491960.18
#Sta/Elev= 30
  4250.8  326.34  4376.7  324.68  4437.8  326.11    4520  323.77    4538  321.81
  4551.3  319.62  4631.1  313.55  4638.6  312.89  4673.4  311.28  4678.5  308.17
  4715.2   309.3  4739.3  306.41  4756.2  304.06  4828.2  299.42  4910.3  298.61
  4971.4  296.17  4982.8  294.57  4993.2  287.99  5000.6  286.67  5003.4  286.17
  5006.6  286.67  5010.3  291.39  5015.5  293.11  5049.2  298.83  5170.2  302.15
  5233.1  301.24    5334   303.9  5372.9  303.13  5492.8  311.44  5607.3  315.47
#Mann= 7 ,-1 , 0
  4250.8     .05       0    4538     .08       0  4631.1     .05       0
  4638.6     .08       0  4739.3     .16       0  5000.6     .07       0
  5006.6     .16       0
Bank Sta=4971.4,5049.2
XS Rating Curve= 0 ,0
Exp/Cntr=0.3,0.1

Type RM Length L Ch R = 1 ,11759   ,246,246,246
BEGIN DESCRIPTION:
UNT043 IN BECR 20.0
END DESCRIPTION:
XS GIS Cut Line= 3
      3811653.24     10491330.73      3810949.61     10491910.19
      3810249.63     10491910.19
#Sta/Elev= 30
  4110.2  316.53  4226.2  317.27  4380.6  314.65  4432.1  314.95  4467.2  312.64
  4510.2  312.22  4695.3  296.03  4837.3  294.11  4858.2  289.34  4872.5  289.66
  4879.2  293.18  4901.2  294.65    4944  294.68    4965  293.73  4979.4  291.34
  4985.9  282.09  5005.1  281.66  5007.8  281.16  5011.1  281.66  5014.5  282.93
  5018.5  293.94  5024.2  293.94  5031.7  297.34  5131.7  296.96  5191.7   299.1
  5201.7  301.51  5221.7  298.13  5231.7  297.89  5621.7  314.06  5721.7  316.88
#Mann= 4 ,-1 , 0
  4110.2     .05       0  4380.6     .16       0  5005.1     .07       0
  5011.1     .16       0
Bank Sta=4944,5031.7
XS Rating Curve= 0 ,0
Exp/Cntr=0.3,0.1

Type RM Length L Ch R = 1 ,11513   ,653,653,653
BEGIN DESCRIPTION:
UNT043 IN BECR 19.0
END DESCRIPTION:
XS GIS Cut Line= 3
      3811590.78     10491233.48      3810957.94     10491693.52
      3810239.69     10491635.15
#Sta/Elev= 30
  4122.9  319.22    4348  316.93  4544.7  312.75  4580.3  308.78  4636.7  304.89
  4666.1   301.1  4722.5  298.43  4743.4  295.39  4751.9  292.91  4758.1  293.47
  4779.6  289.75  4816.7  290.97    4823  289.44  4837.7  290.81  4953.8  293.56
  4973.8  292.19  4983.9  289.45  4993.9  281.96  5000.5  281.78  5003.3  281.28
  5006.5  281.78  5008.6  292.13    5014  294.79    5024  295.61  5164.5  298.61
  5252.4  303.18  5379.3  303.98  5425.3  306.71  5455.4  306.74  5625.9  312.98
#Mann= 4 ,-1 , 0
  4122.9     .05       0    4348     .16       0  5000.5     .07       0
  5006.5     .16       0
Bank Sta=4953.8,5024
XS Rating Curve= 0 ,0
Exp/Cntr=0.3,0.1

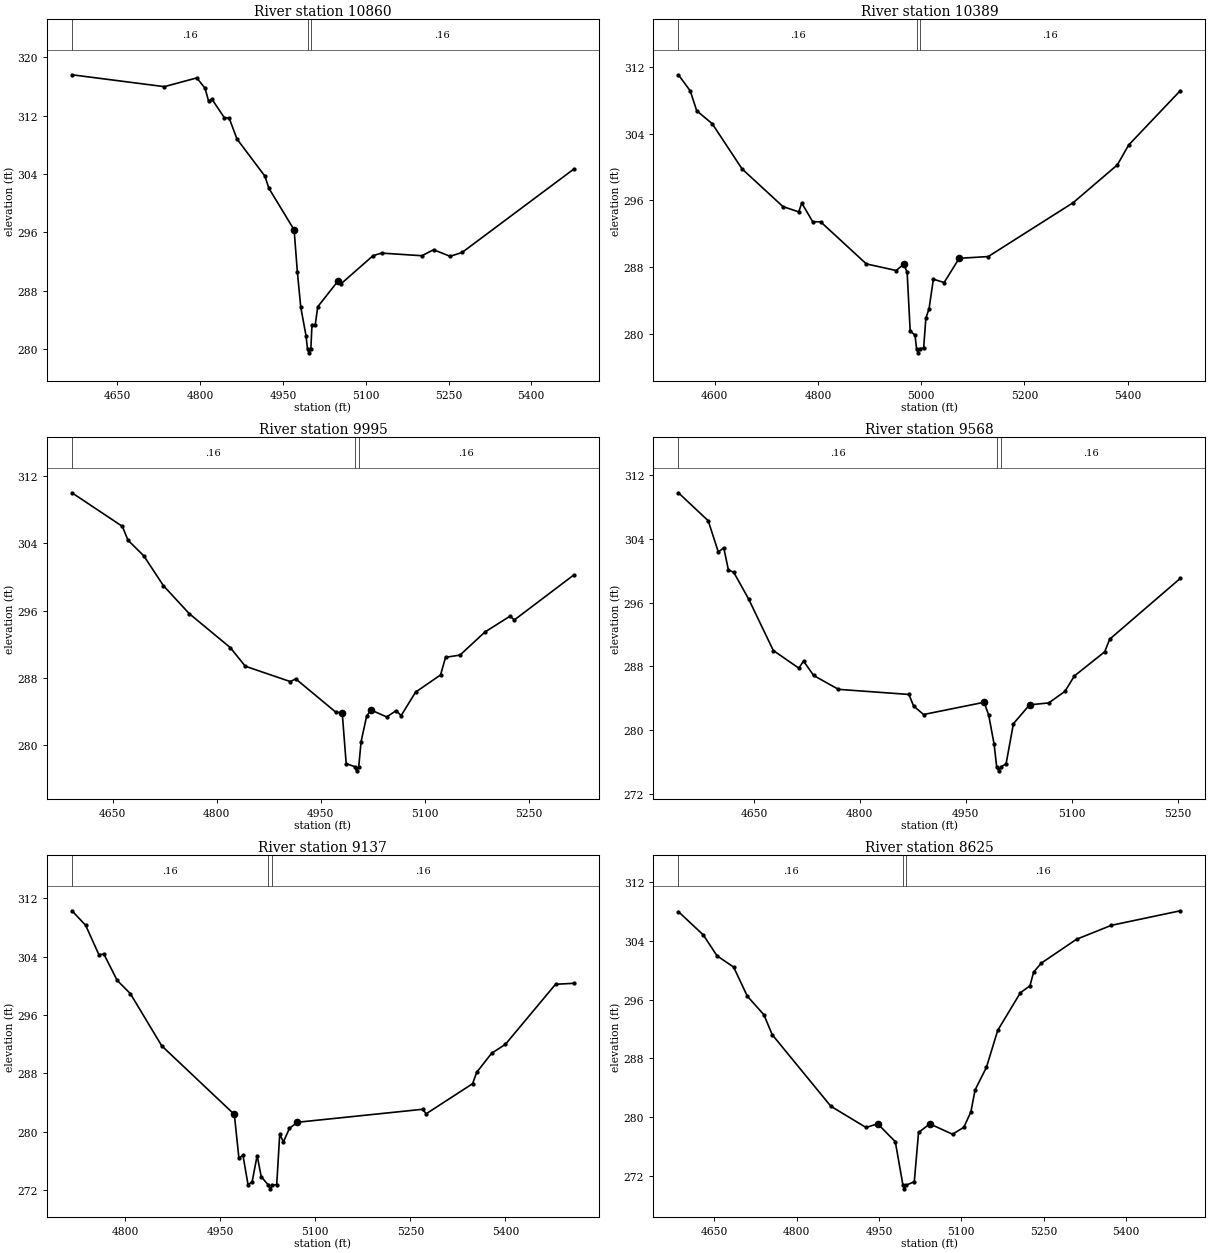
Type RM Length L Ch R = 1 ,10860   ,471,471,471
BEGIN DESCRIPTION:
UNT043 IN BECR 18.0
END DESCRIPTION:
XS GIS Cut Line= 3
      3811278.23     10490990.46      3810899.61     10491210.19
      3810499.58     10491460.21
#Sta/Elev= 30
  4567.6  317.59    4735  315.96  4793.8  317.16  4808.8  315.74  4815.3  313.94
  4821.1  314.26  4843.5  311.73  4852.6  311.63  4866.6  308.79  4917.2  303.69
  4924.4  302.03  4970.2  296.32    4976   290.6  4982.2  285.72  4991.7  281.82
  4994.5  279.95  4997.2  279.45  5000.5  279.95  5002.5   283.2  5008.3   283.2
    5013  285.77  5049.6  289.29  5055.5  288.94  5113.3  292.78  5128.6  293.13
  5201.7  292.77  5222.9  293.59    5253  292.69  5274.8  293.23  5477.1  304.66
#Mann= 3 ,-1 , 0
  4567.6     .16       0  4994.5     .07       0  5000.5     .16       0
Bank Sta=4970.2,5049.6
XS Rating Curve= 0 ,0
Exp/Cntr=0.3,0.1

Type RM Length L Ch R = 1 ,10389   ,394,394,394
BEGIN DESCRIPTION:
UNT043 IN BECR 17.0
END DESCRIPTION:
XS GIS Cut Line= 3
      3810949.62     10490660.18      3810549.61     10490910.19
      3810249.62     10491310.18
#Sta/Elev= 30
    4530  311.04    4553   309.1  4565.4  306.73  4595.5  305.18  4653.2  299.77
  4732.3  295.26  4762.9  294.62  4768.8  295.68    4790  293.44  4805.4  293.43
  4893.8  288.39  4951.6   287.6  4966.3  288.35  4972.8  287.39  4978.7  280.37
  4988.1  279.85    4991  278.24  4993.8  277.74    4997  278.24  5004.8  278.31
    5009  281.87  5015.3  283.04  5023.6  286.56  5044.4  286.16  5073.6  289.06
  5129.8  289.27  5294.4  295.73  5379.8  300.25  5401.7  302.63  5501.7  309.14
#Mann= 3 ,-1 , 0
    4530     .16       0    4991     .07       0    4997     .16       0
Bank Sta=4966.3,5073.6
XS Rating Curve= 0 ,0
Exp/Cntr=0.3,0.1

Type RM Length L Ch R = 1 ,9995    ,427,427,427
BEGIN DESCRIPTION:
UNT043 IN BECR 16.0
END DESCRIPTION:
XS GIS Cut Line= 3
      3810699.63     10490410.17      3810349.61     10490610.19
      3810099.61     10490810.19
#Sta/Elev= 30
  4591.5  310.05  4664.2  306.04  4672.2   304.4  4695.2  302.51  4723.3  298.97
  4760.7  295.62  4819.7  291.58  4841.3  289.36  4906.1  287.53    4914  287.85
  4971.6  283.89    4981  283.78  4986.7  277.75  4998.8  277.38  5001.6  276.88
  5004.8  277.38  5008.2  280.37  5016.3  283.44  5022.7  284.13  5045.1  283.31
  5058.7  284.06  5065.9  283.47  5086.7  286.27  5122.7  288.32  5129.9  290.42
  5150.7  290.69  5186.7  293.44  5222.8  295.33  5229.2  294.89  5314.8  300.25
#Mann= 3 ,-1 , 0
  4591.5     .16       0  4998.8     .07       0  5004.8     .16       0
Bank Sta=4981,5022.7
XS Rating Curve= 0 ,0
Exp/Cntr=0.3,0.1

Type RM Length L Ch R = 1 ,9568    ,431,431,431
BEGIN DESCRIPTION:
UNT043 IN BECR 15.0
END DESCRIPTION:
XS GIS Cut Line= 3
      3810399.59     10489960.21      3810099.61     10490310.19
      3809899.65     10490460.16
#Sta/Elev= 30
    4543  309.74  4585.2  306.24  4599.5  302.33  4607.2  302.85  4613.8  300.09
  4621.4  299.78  4642.3  296.47  4677.4     290  4713.6  287.79  4720.2  288.68
  4734.5  286.88  4769.6  285.14  4869.5   284.5  4876.1  283.05  4890.3  281.99
    4976  283.52  4982.5  281.91  4990.2  278.25  4993.8  275.44  4996.6  274.94
  4999.8  275.44  5007.1  275.81  5017.5  280.84  5040.4   283.2  5067.5  283.44
  5090.4  284.88  5103.9  286.82  5146.7  289.83  5153.9  291.42  5253.9  299.03
#Mann= 3 ,-1 , 0
    4543     .16       0  4993.8     .07       0  4999.8     .16       0
Bank Sta=4976,5040.4
XS Rating Curve= 0 ,0
Exp/Cntr=0.3,0.1

Type RM Length L Ch R = 1 ,9137    ,512,512,512
BEGIN DESCRIPTION:
UNT043 IN BECR 14.0
END DESCRIPTION:
XS GIS Cut Line= 3
      3810199.63     10489760.17      3809999.61     10490010.19
       3809749.6      10490410.2
#Sta/Elev= 30
    4716  310.29  4737.6   308.3  4758.4  304.29  4766.5  304.33  4787.3  300.75
  4808.1  298.93  4857.7  291.76  4972.2  282.36  4979.4  276.38  4985.8  276.75
  4993.8  272.74  5000.2  273.07  5008.2  276.72  5014.6  273.83    5026  272.65
  5028.7  272.15    5032  272.65  5039.1  272.74  5043.8  279.62  5049.7   278.6
  5059.2  280.45  5071.6  281.28  5269.1  283.06    5275  282.45  5348.1  286.57
  5354.6  288.13  5378.2  290.75    5400  291.98    5479  300.21  5507.9  300.34
#Mann= 3 ,-1 , 0
    4716     .16       0    5026     .07       0    5032     .16       0
Bank Sta=4972.2,5071.6
XS Rating Curve= 0 ,0
Exp/Cntr=0.3,0.1

Type RM Length L Ch R = 1 ,8625    ,314,314,314
BEGIN DESCRIPTION:
UNT043 IN BECR 13.0
END DESCRIPTION:
XS GIS Cut Line= 4
      3810049.62     10489660.18      3809649.61     10489810.19
      3809449.61     10489860.19      3809258.14     10490066.05
#Sta/Elev= 30
  4584.5  308.02  4629.9  304.84  4654.8     302  4685.1  300.46    4710   296.5
  4740.3  293.95  4755.4  291.24  4862.2  281.48  4926.3  278.58  4947.6  279.08
  4979.7  276.64  4993.6  270.71  4996.3  270.21  4999.6  270.71  5014.3  271.19
    5022   277.9  5042.6  279.07  5083.9  277.66  5104.5   278.6  5117.4  280.71
  5125.1  283.71  5145.7  286.78  5166.3  291.83  5207.6  296.96    5225   297.9
  5231.8  299.79  5245.9  301.01    5310  304.26  5373.5  306.16    5499  308.14
#Mann= 3 ,-1 , 0
  4584.5     .16       0  4993.6     .07       0  4999.6     .16       0
Bank Sta=4947.6,5042.6
XS Rating Curve= 0 ,0
Exp/Cntr=0.3,0.1

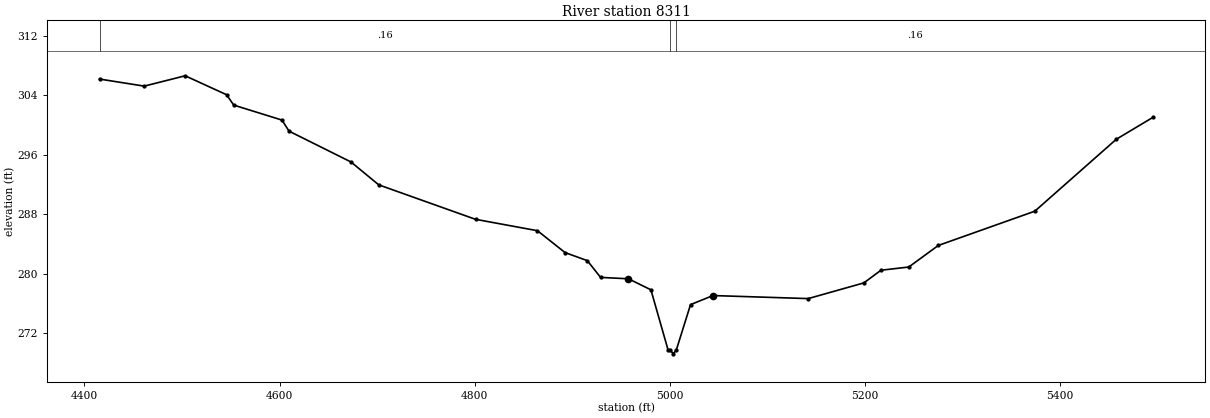
Type RM Length L Ch R = 1 ,8311    ,652,652,652
BEGIN DESCRIPTION:
UNT043 IN BECR 12.0
END DESCRIPTION:
XS GIS Cut Line= 3
      3810143.73     10489129.92      3809779.16     10489468.44
      3809249.63     10489710.18
#Sta/Elev= 30
  4415.4  306.17  4461.2  305.22  4503.2  306.61  4545.7  304.06    4553  302.67
  4602.4  300.66  4609.7  299.17  4673.2  295.03  4701.6  291.96  4800.8  287.33
  4864.3   285.8  4892.6  282.86  4915.4  281.78    4929  279.53  4957.6  279.34
  4980.6  277.86  4998.1  269.82  5000.6  269.76  5003.4  269.26  5006.6  269.76
  5021.2  275.87  5044.2  277.09  5141.8  276.68  5198.9  278.79  5216.4  280.49
  5244.9  280.92  5275.2  283.82  5374.1  288.42  5457.7  298.09    5495  301.01
#Mann= 3 ,-1 , 0
  4415.4     .16       0  5000.6     .07       0  5006.6     .16       0
Bank Sta=4957.6,5044.2
XS Rating Curve= 0 ,0
Exp/Cntr=0.3,0.1