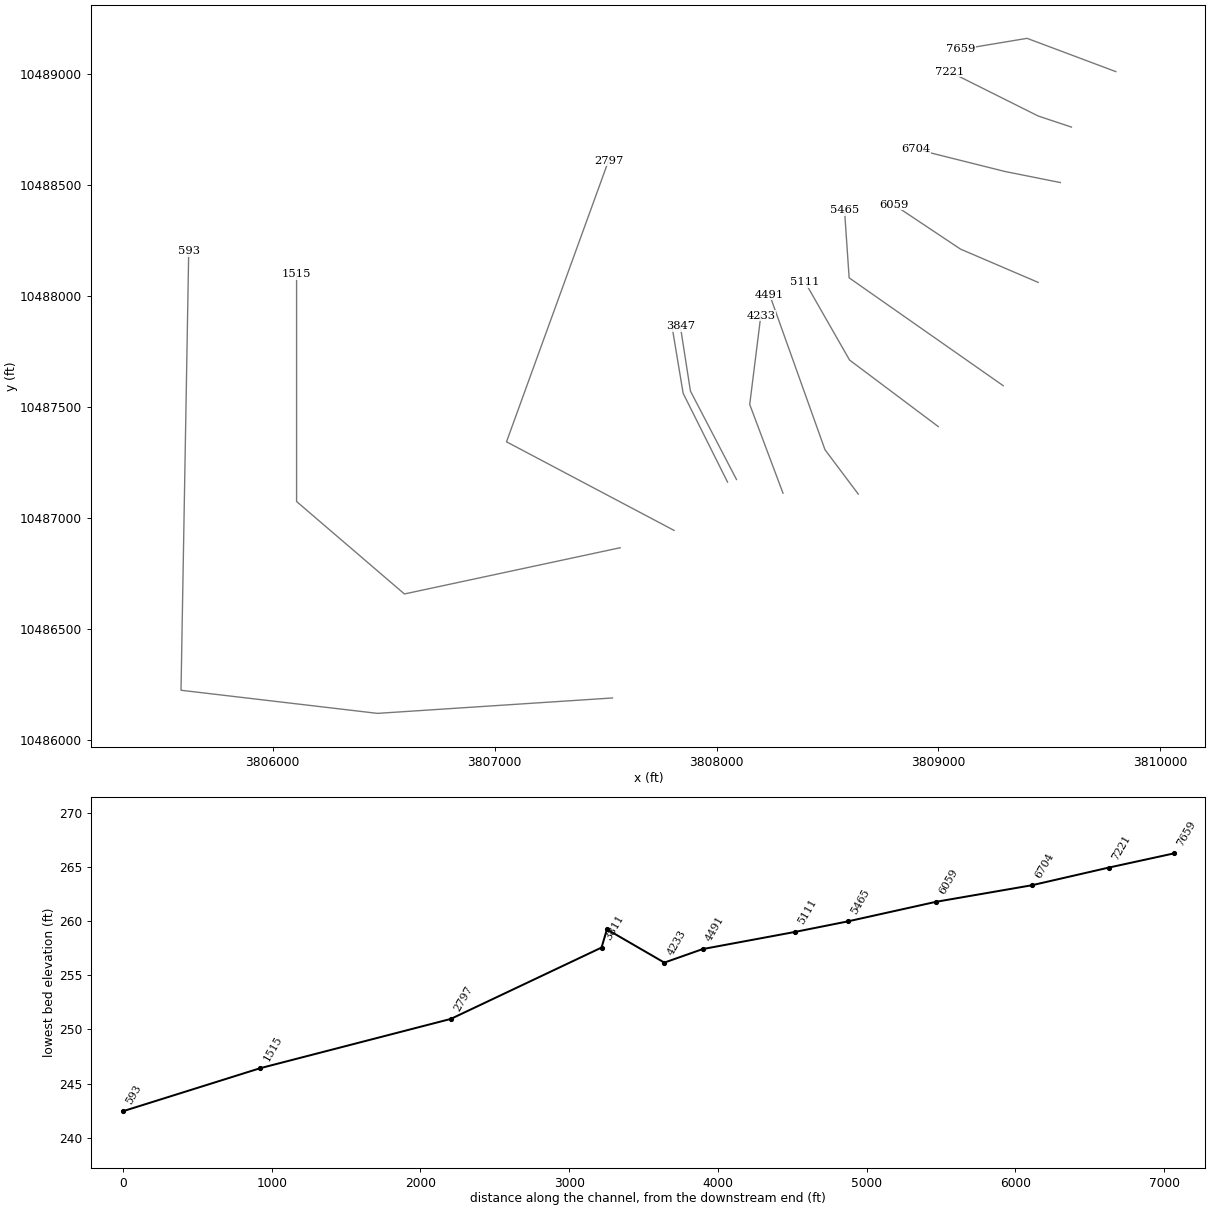
HEC-RAS study UNT043 IN BECR.prj: UNT043 IN BECR Base Level Engineering

--- UNT043 IN BECR.g01 (geometry) --- (continued)

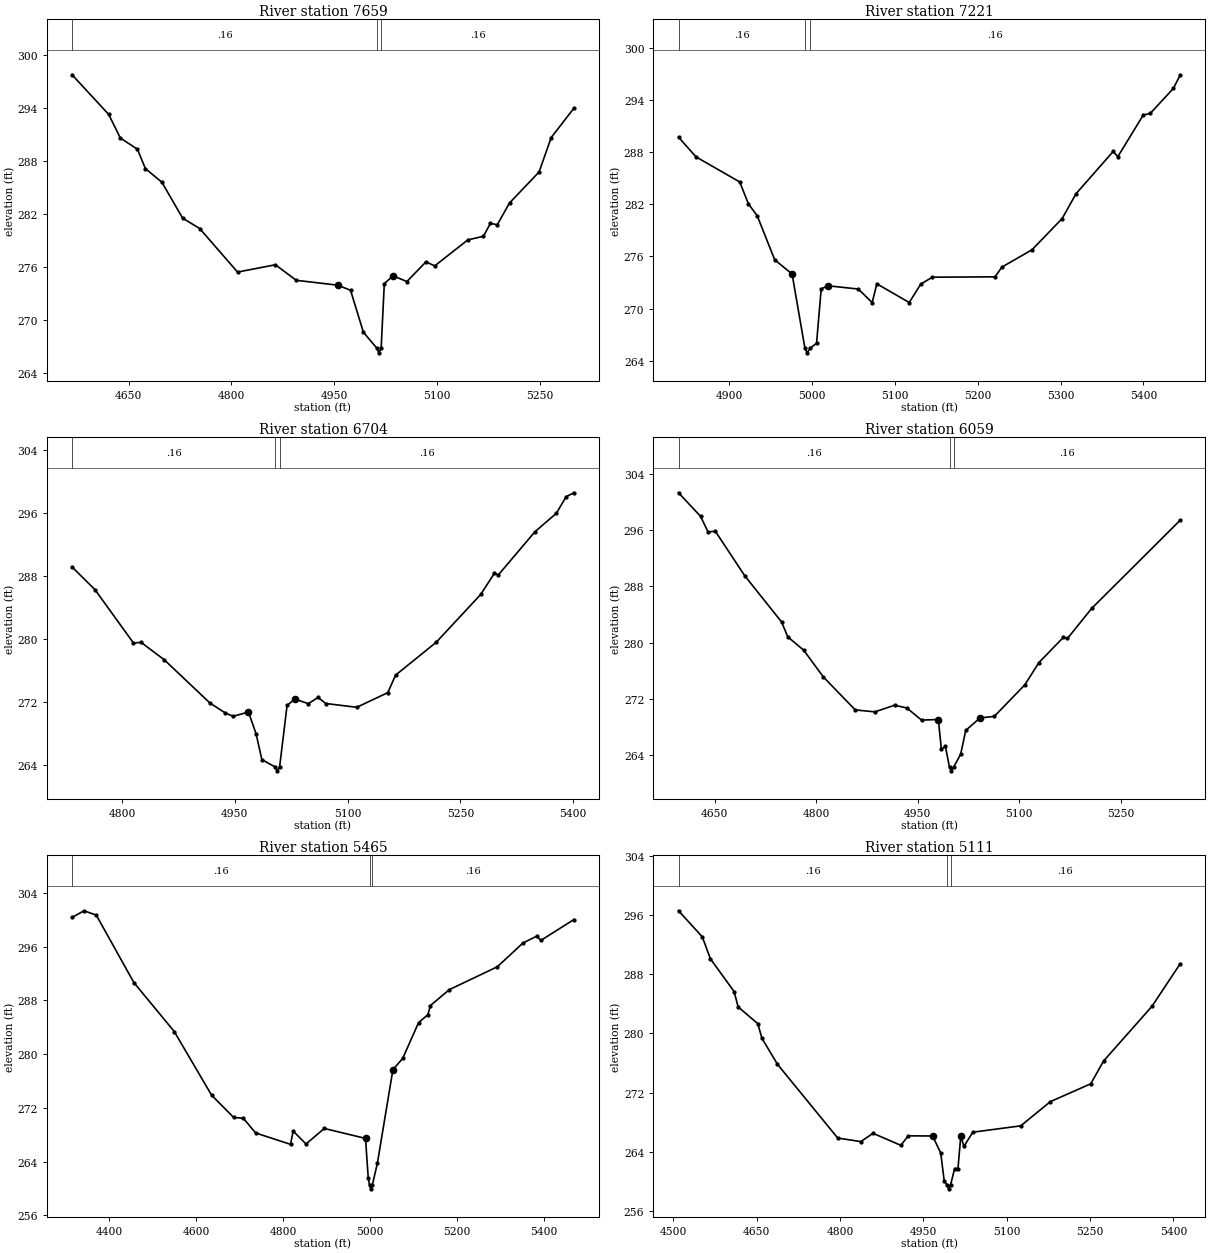
Type RM Length L Ch R = 1 ,7659    ,438,438,438
BEGIN DESCRIPTION:
UNT043 IN BECR 11.0
END DESCRIPTION:
XS GIS Cut Line= 3
      3809799.63     10489010.18      3809399.61     10489160.19
      3809099.57     10489110.18
#Sta/Elev= 30
  4567.7  297.71  4621.1  293.22    4638  290.56    4663  289.28  4674.5   287.1
  4698.6  285.55  4728.8  281.49  4753.7  280.31  4808.9  275.38  4864.1  276.21
  4894.4  274.45  4954.9   273.9  4973.6  273.32  4992.3  268.58  5012.2  266.74
  5014.9  266.24  5018.2  266.74  5022.8  274.07  5035.5  274.96  5055.7  274.31
  5083.6  276.54  5096.3  276.08  5144.5  279.02  5167.3  279.43  5177.4  280.89
  5187.5  280.74  5205.3   283.2  5248.4  286.71  5266.1  290.61  5299.1  293.92
#Mann= 3 ,-1 , 0
  4567.7     .16       0  5012.2     .07       0  5018.2     .16       0
Bank Sta=4954.9,5035.5
XS Rating Curve= 0 ,0
Exp/Cntr=0.3,0.1

Type RM Length L Ch R = 1 ,7221    ,517,517,517
BEGIN DESCRIPTION:
UNT043 IN BECR 10.0
END DESCRIPTION:
XS GIS Cut Line= 3
      3809599.61     10488760.19      3809449.61     10488810.19
      3809049.63     10489010.18
#Sta/Elev= 30
  4839.2   289.7  4860.3  287.44    4913  284.56  4923.5  282.04  4934.1  280.68
  4955.2  275.62  4976.2  273.98  4991.7  265.43  4994.4  264.93  4997.7  265.43
  5005.7  266.04  5011.3  272.28  5019.7  272.63    5056  272.26  5072.8   270.7
  5078.4  272.86  5117.5  270.71  5131.5  272.84  5145.5  273.62  5220.9  273.66
  5229.3  274.78  5265.6  276.77    5302  280.36  5318.7  283.21  5363.5  288.06
  5369.1  287.46  5399.8  292.25  5408.2  292.43  5436.1   295.3  5444.5  296.87
#Mann= 3 ,-1 , 0
  4839.2     .16       0  4991.7     .07       0  4997.7     .16       0
Bank Sta=4976.2,5019.7
XS Rating Curve= 0 ,0
Exp/Cntr=0.3,0.1

Type RM Length L Ch R = 1 ,6704    ,645,645,645
BEGIN DESCRIPTION:
UNT043 IN BECR 9.0
END DESCRIPTION:
XS GIS Cut Line= 3
      3809549.61     10488510.19      3809299.61     10488560.19
      3808899.57      10488660.2
#Sta/Elev= 30
  4733.6  289.19  4764.2  286.29  4815.2  279.54  4825.4  279.61    4856  277.42
  4917.2  271.89  4937.6  270.64  4947.8  270.23  4968.2  270.77  4978.4  267.97
    4986  264.72  5003.6   263.8  5006.3   263.3  5009.6   263.8  5019.5   271.6
  5029.8  272.42  5047.8  271.83  5060.7  272.62    5071  271.85  5112.2  271.37
  5153.5  273.23  5163.8  275.45  5217.9  279.63  5277.2  285.72  5295.2  288.39
  5300.4  288.17  5349.3  293.68  5377.7  296.01  5390.6  298.11  5400.9  298.61
#Mann= 3 ,-1 , 0
  4733.6     .16       0  5003.6     .07       0  5009.6     .16       0
Bank Sta=4968.2,5029.8
XS Rating Curve= 0 ,0
Exp/Cntr=0.3,0.1

Type RM Length L Ch R = 1 ,6059    ,594,594,594
BEGIN DESCRIPTION:
UNT043 IN BECR 8.0
END DESCRIPTION:
XS GIS Cut Line= 3
      3809449.59      10488060.2      3809099.61     10488210.19
      3808799.63     10488410.17
#Sta/Elev= 30
  4596.5  301.27  4629.1  297.92    4640  295.72  4650.9   295.8  4694.4  289.47
  4748.8  282.91  4757.9   280.8  4781.4  278.91  4810.4  275.11  4857.6  270.42
  4886.6  270.15  4915.6  271.09  4933.8   270.7  4955.5  268.98  4980.3  269.06
  4984.8  264.84  4990.8  265.23  4996.8  262.27  4999.6  261.77  5002.8  262.27
  5013.3  264.14  5020.8  267.51  5041.9  269.29  5062.9   269.5    5108  273.98
    5129  277.16  5165.1  280.74  5171.1  280.58  5207.1  284.87  5337.8  297.39
#Mann= 3 ,-1 , 0
  4596.5     .16       0  4996.8     .07       0  5002.8     .16       0
Bank Sta=4980.3,5041.9
XS Rating Curve= 0 ,0
Exp/Cntr=0.3,0.1

Type RM Length L Ch R = 1 ,5465    ,354,354,354
BEGIN DESCRIPTION:
UNT043 IN BECR 7.0
END DESCRIPTION:
XS GIS Cut Line= 3
      3809292.15      10487594.6      3808597.69     10488080.73
      3808576.89     10488385.72
#Sta/Elev= 30
  4314.8  300.33  4342.3  301.32  4370.5  300.67  4456.8  290.65  4549.8  283.35
  4635.5  273.89  4686.1  270.58  4708.5  270.46  4736.7  268.27  4816.9  266.58
    4823  268.55  4852.6  266.63  4894.5  268.94  4989.3  267.46  4995.6  261.54
  4998.7  260.46  5001.5  259.96  5004.7  260.46  5016.6  263.77  5052.3   277.7
  5074.7  279.35  5111.3  284.69  5132.5  285.85  5138.6  287.23    5182  289.59
  5292.3  292.99  5351.1  296.52  5382.5  297.54  5392.5  296.92  5468.2  300.01
#Mann= 3 ,-1 , 0
  4314.8     .16       0  4998.7     .07       0  5004.7     .16       0
Bank Sta=4989.3,5052.3
XS Rating Curve= 0 ,0
Exp/Cntr=0.3,0.1

Type RM Length L Ch R = 1 ,5111    ,620,620,620
BEGIN DESCRIPTION:
UNT043 IN BECR 6.0
END DESCRIPTION:
XS GIS Cut Line= 3
      3808999.61     10487410.19      3808599.61     10487710.19
      3808399.61     10488060.18
#Sta/Elev= 30
  4509.3  296.55    4552  293.04  4566.6  290.07  4609.3  285.64  4616.6  283.56
    4652   281.3  4659.3  279.34  4687.4  275.81  4795.8  265.85  4837.4  265.37
  4859.3  266.49  4909.3  264.87  4922.8  266.15  4966.6  266.13  4981.2  263.82
  4987.4  260.09  4992.8  259.49  4995.5  258.99  4998.8  259.49  5006.2  261.73
  5012.2  261.73  5017.2  266.07    5023  264.73  5038.8  266.64  5125.2   267.5
  5178.5  270.77  5251.2  273.18  5274.2  276.25  5361.3  283.64  5412.4  289.42
#Mann= 3 ,-1 , 0
  4509.3     .16       0  4992.8     .07       0  4998.8     .16       0
Bank Sta=4966.6,5017.2
XS Rating Curve= 0 ,0
Exp/Cntr=0.3,0.1

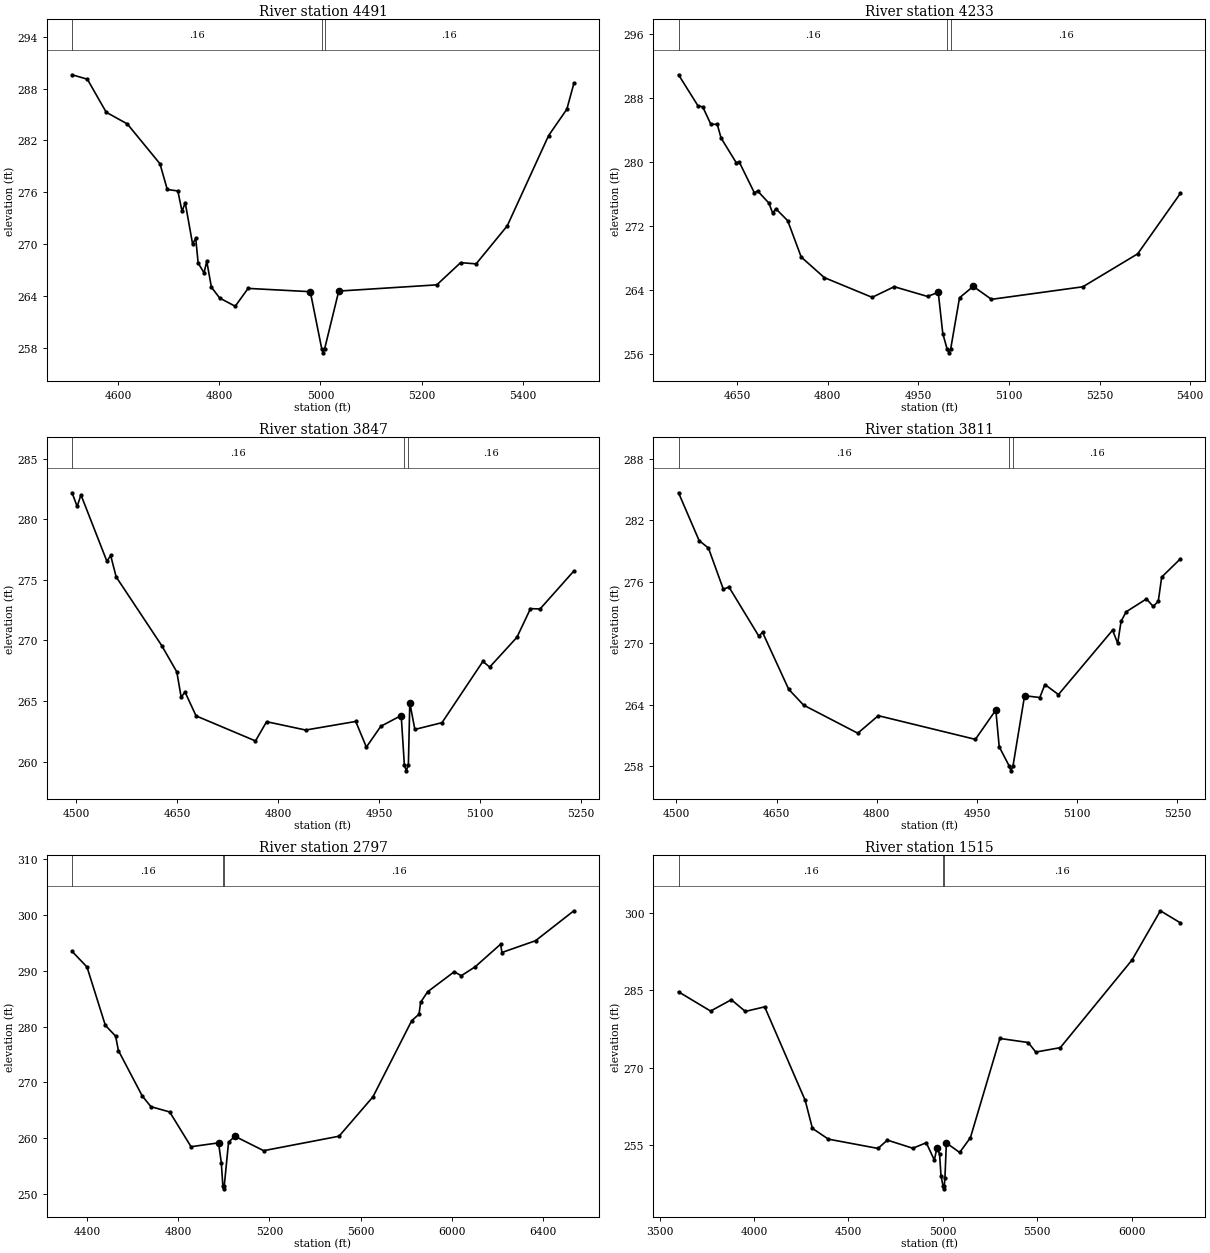
Type RM Length L Ch R = 1 ,4491    ,258,258,258
BEGIN DESCRIPTION:
UNT043 IN BECR 5.0
END DESCRIPTION:
XS GIS Cut Line= 3
      3808638.85     10487106.01      3808488.85     10487306.02
      3808238.99     10488005.63
#Sta/Elev= 30
  4508.5   289.6  4538.7  289.09  4576.1  285.26  4617.8  283.91  4682.4   279.3
  4696.9  276.32  4717.8  276.15  4726.1  273.79  4732.4  274.79  4746.9  270.03
  4753.2  270.66    4758   267.8  4769.7  266.67    4775  268.02  4784.2  265.01
  4800.5  263.76  4831.3   262.8  4856.8  264.87  4979.9  264.49  5002.4  257.91
  5005.2  257.41  5008.4  257.91  5036.2  264.56  5230.2  265.28  5277.3  267.85
    5308  267.71  5369.6  272.11  5451.4  282.56  5487.5  285.61  5501.4   288.6
#Mann= 3 ,-1 , 0
  4508.5     .16       0  5002.4     .07       0  5008.4     .16       0
Bank Sta=4979.9,5036.2
XS Rating Curve= 0 ,0
Exp/Cntr=0.3,0.1

Type RM Length L Ch R = 1 ,4233    ,386,386,386
BEGIN DESCRIPTION:
UNT043 IN BECR 4.0
END DESCRIPTION:
XS GIS Cut Line= 3
      3808299.63     10487110.14      3808149.61     10487510.19
      3808199.61     10487910.23
#Sta/Elev= 30
  4553.1  290.93  4585.2  287.06  4593.2  286.91  4606.5  284.75  4617.2  284.73
  4623.5  283.02  4648.4  279.96  4653.7     280  4678.6  276.17    4684   276.4
  4702.7  274.88  4708.9  273.63  4714.2  274.18  4733.8  272.68  4756.1  268.14
  4794.3  265.57  4873.5   263.1    4910  264.43  4965.2  263.21  4982.9  263.73
  4990.4  258.57  4997.5  256.66  5000.3  256.16  5003.5  256.66  5018.1  263.05
  5040.8  264.47    5071  262.85  5222.2  264.42  5312.9  268.54  5383.5  276.09
#Mann= 3 ,-1 , 0
  4553.1     .16       0  4997.5     .07       0  5003.5     .16       0
Bank Sta=4982.9,5040.8
XS Rating Curve= 0 ,0
Exp/Cntr=0.3,0.1

Type RM Length L Ch R = 1 ,3847    ,36,36,36
BEGIN DESCRIPTION:
Mapping XS db5af26a
END DESCRIPTION:
XS GIS Cut Line= 3
      3808089.96     10487171.96      3807882.37     10487570.53
      3807836.71     10487863.91
#Sta/Elev= 30
  4493.5   282.2  4501.1  281.07  4506.7  282.03  4545.3  276.54  4550.9  277.02
  4559.1  275.25  4626.8  269.58  4649.3   267.4  4655.8   265.3  4661.4  265.75
  4677.9  263.77  4766.3   261.7  4782.8  263.29    4841   262.6  4915.4  263.31
  4931.2  261.19  4952.7  262.91    4983   263.8  4987.7  259.73  4990.5  259.23
  4993.7  259.73  4995.8  264.86  5003.3  262.65  5043.7  263.21  5104.5  268.27
  5114.6   267.8  5155.1  270.26  5175.3  272.63  5189.5   272.6  5239.8  275.74
#Mann= 3 ,-1 , 0
  4493.5     .16       0  4987.7     .07       0  4993.7     .16       0
Bank Sta=4983,4995.8
XS Rating Curve= 0 ,0
Exp/Cntr=0.3,0.1

Type RM Length L Ch R = 1 ,3811    ,1014,1014,1014
BEGIN DESCRIPTION:
UNT043 IN BECR 3.0
END DESCRIPTION:
XS GIS Cut Line= 3
      3808049.63     10487160.15      3807849.61     10487560.19
      3807799.61     10487860.19
#Sta/Elev= 30
  4503.1  284.67  4533.9  280.01  4547.9  279.28  4570.2  275.26  4578.6  275.48
  4623.3  270.69  4628.9  271.06  4668.1   265.5  4690.4  263.96  4771.5  261.22
  4802.2  262.93  4947.6  260.62  4978.2  263.48  4983.3   259.9    4998  258.05
  5000.8  257.55    5004  258.05  5021.3  264.88  5044.1   264.7  5051.7  265.97
    5072  264.99  5153.1  271.27  5160.7  269.99  5165.8  272.14  5173.4  273.06
  5203.8  274.32  5213.9  273.58  5221.5   274.1  5226.6  276.45  5254.5  278.22
#Mann= 3 ,-1 , 0
  4503.1     .16       0    4998     .07       0    5004     .16       0
Bank Sta=4978.2,5021.3
XS Rating Curve= 0 ,0
Exp/Cntr=0.3,0.1

Type RM Length L Ch R = 1 ,2797    ,1282,1282,1282
BEGIN DESCRIPTION:
UNT043 IN BECR 2.0
END DESCRIPTION:
XS GIS Cut Line= 3
      3807808.65     10486942.41      3807053.47     10487341.71
      3807513.52     10488609.04
#Sta/Elev= 30
  4333.8  293.47  4399.4  290.66  4479.8  280.23    4525  278.29  4537.1  275.72
  4641.5  267.61  4679.9  265.67  4762.3  264.72    4856   258.5  4976.7  259.19
  4988.8  255.66  4995.7  251.46  4998.5  250.96  5001.7  251.46  5020.7  259.31
  5048.4  260.37  5174.8  257.79  5505.6  260.38  5654.5  267.43  5824.7  281.06
  5856.7  282.22  5863.7  284.34  5894.3  286.23  6011.4  289.82  6042.1   289.1
  6103.3  290.71  6215.1  294.76  6220.4  293.26  6368.1  295.37  6536.3  300.73
#Mann= 3 ,-1 , 0
  4333.8     .16       0  4995.7     .07       0  5001.7     .16       0
Bank Sta=4976.7,5048.4
XS Rating Curve= 0 ,0
Exp/Cntr=0.3,0.1

Type RM Length L Ch R = 1 ,1515    ,922,922,922
BEGIN DESCRIPTION:
Mapping XS e9586362
END DESCRIPTION:
XS GIS Cut Line= 4
      3807565.66     10486864.29       3806593.4     10486655.94
      3806107.28     10487072.61      3806107.28     10488096.03
#Sta/Elev= 30
  3600.6  284.74  3770.4     281  3880.2   283.2  3954.5  280.93  4056.8  281.82
  4271.5  263.62  4309.8  258.17  4394.3  256.08  4657.2  254.27  4706.6  255.89
  4841.6  254.31  4912.9  255.38  4955.5  252.01  4968.9  254.26  4983.2  253.24
  4990.9  248.95  5002.1  246.91  5004.9  246.41  5008.1  246.91  5011.7  248.52
  5019.4  255.34  5089.7  253.49  5146.7  256.36  5302.8  275.67  5452.8  274.88
  5492.8  273.02  5622.8  273.88  6002.8  290.94  6152.8  300.51  6258.6  298.17
#Mann= 3 ,-1 , 0
  3600.6     .16       0  5002.1     .07       0  5008.1     .16       0
Bank Sta=4968.9,5019.4
XS Rating Curve= 0 ,0
Exp/Cntr=0.3,0.1

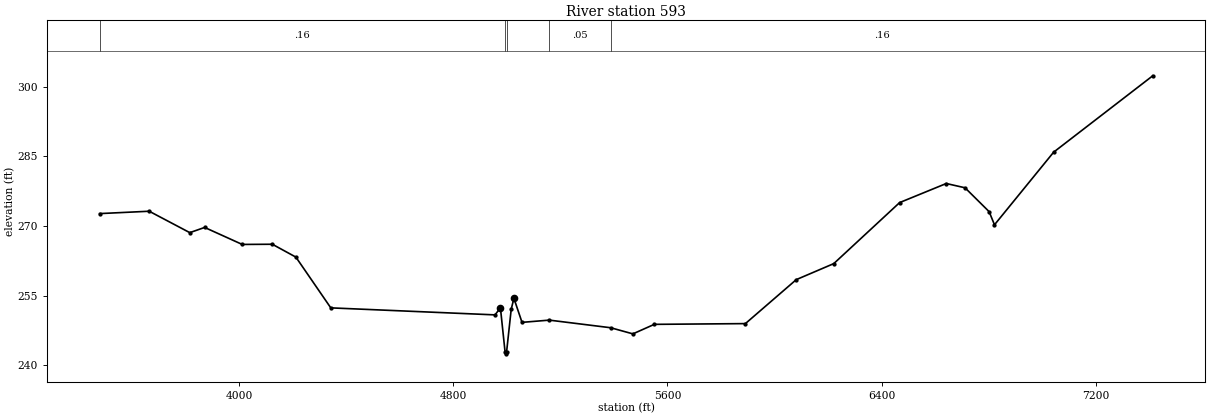
Type RM Length L Ch R = 1 ,593     ,0,0,0
BEGIN DESCRIPTION:
UNT043 IN BECR 1.0
END DESCRIPTION:
XS GIS Cut Line= 4
      3807530.88     10486187.19      3806471.87     10486117.75
      3805586.45     10486221.92      3805621.17      10488201.1
#Sta/Elev= 30
  3479.7  272.64  3664.8  273.15  3816.3  268.54  3871.8  269.66  4012.1     266
  4124.5  266.04  4212.5  263.27  4342.8  252.34  4956.1  250.83  4976.2  252.35
  4993.4  242.94  4996.1  242.44  4999.4  242.94  5016.5  252.04  5026.6   254.4
  5056.8  249.22  5158.8   249.7    5388  248.06  5470.8  246.74  5550.8  248.79
  5890.9  248.95  6080.9  258.42  6220.9  261.87  6466.8  275.01    6641  279.12
    6711   278.2    6801  273.06    6821  270.23  7041.9  285.87    7412  302.32
#Mann= 5 ,-1 , 0
  3479.7     .16       0  4993.4     .07       0  4999.4     .16       0
  5158.8     .05       0    5388     .16       0
Bank Sta=4976.2,5026.6
XS Rating Curve= 0 ,0
Exp/Cntr=0.3,0.1

Chan Stop Cuts=-1
Use User Specified Reach Order=0
Composite Channel Slope=5