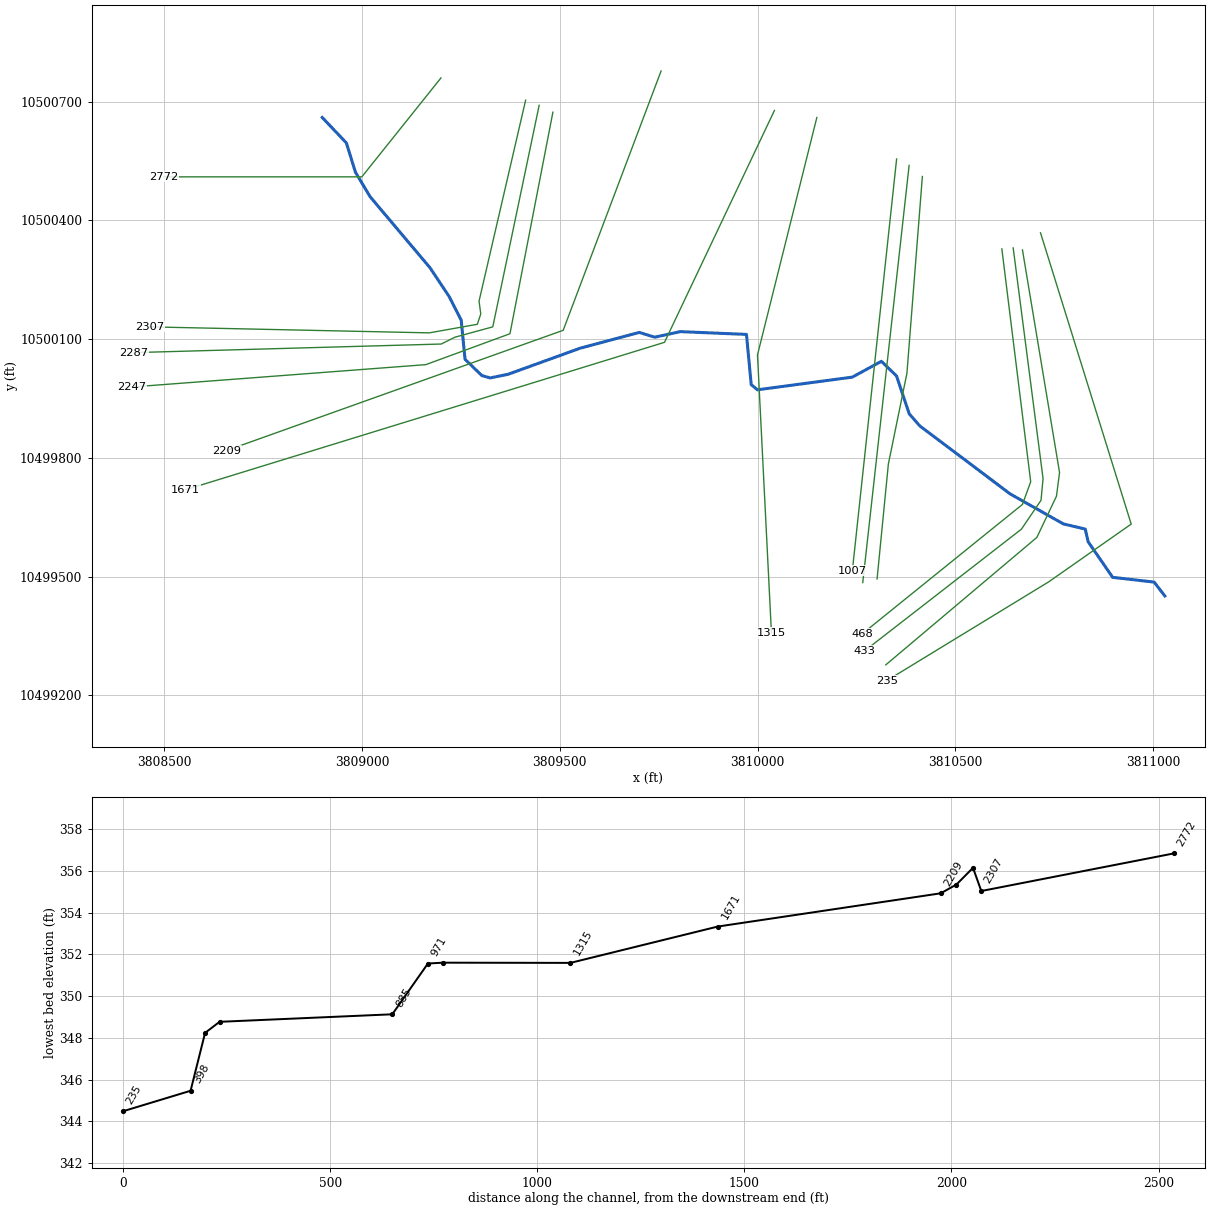
--- UNT044 IN BECR.prj (project) ---

Proj Title=UNT044 IN BECR Base Level Engineering
Current Plan=p01
Default Exp/Contr=0.3,0.1
English Units
Geom File=g01
Flow File=f01
Plan File=p01
BEGIN DESCRIPTION:
UNT044 IN BECR
END DESCRIPTION:

--- UNT044 IN BECR.p01 (plan) ---

Plan Title=Multiple Run
Short Identifier=Multiple
Geom File=g01
Flow File=f01
Subcritical Flow
K Sum by GR= 0
Std Step Tol= 0.01
Critical Tol= 0.01
Num of Std Step Trials= 20
Max Error Tol= 0.3
Flow Tol Ratio= 0.001
Split Flow NTrial= 30
Split Flow Tol= 0.02
Split Flow Ratio= 0.02
Log Output Level= 0
Friction Slope Method= 1
Unsteady Friction Slope Method= 2
Unsteady Bridges Friction Slope Method= 1
Parabolic Critical Depth
Global Vel Dist=  1 , 1 , 1
Global Log Level= 0
CheckData=True
Encroach Param= -1, 0, 0, 0
BEGIN DESCRIPTION:
Multiple Run
END DESCRIPTION:

--- UNT044 IN BECR.f01 (steady flow) ---

Flow Title=Multiple
Number of Profiles=7
Profile Names=10-year,25-year,50-year,1pct_min,100-year,1pct_plu,500-year
River Rch & RM= UNT044 IN BECR,Reach-1,2772
     159     195     222     187     253     342     327
Boundary for River Rch & Prof#=UNT044 IN BECR,Reach-1,1
Up Type=0
Dn Type=3
Dn Slope=0.005
Boundary for River Rch & Prof#=UNT044 IN BECR,Reach-1,2
Up Type=0
Dn Type=3
Dn Slope=0.005
Boundary for River Rch & Prof#=UNT044 IN BECR,Reach-1,3
Up Type=0
Dn Type=3
Dn Slope=0.005
Boundary for River Rch & Prof#=UNT044 IN BECR,Reach-1,4
Up Type=0
Dn Type=3
Dn Slope=0.005
Boundary for River Rch & Prof#=UNT044 IN BECR,Reach-1,5
Up Type=0
Dn Type=3
Dn Slope=0.005
Boundary for River Rch & Prof#=UNT044 IN BECR,Reach-1,6
Up Type=0
Dn Type=3
Dn Slope=0.005
Boundary for River Rch & Prof#=UNT044 IN BECR,Reach-1,7
Up Type=0
Dn Type=3
Dn Slope=0.005

--- UNT044 IN BECR.g01 (geometry) ---

Geom Title=Existing Conditions

River Reach=UNT044 IN BECR,Reach-1
Reach XY= 30
      3808899.61     10500660.19      3808960.50     10500596.00
      3808983.50     10500522.00      3809020.50     10500460.00
      3809171.50     10500281.00      3809220.75     10500207.00
      3809250.75     10500148.00      3809260.50     10500049.00
      3809303.00     10500008.00      3809324.00     10500002.00
      3809369.21     10500011.17      3809551.00     10500077.00
      3809700.75     10500117.00      3809740.00     10500105.00
      3809804.50     10500119.00      3809971.75     10500112.00
      3809983.75     10499985.00      3809999.50     10499972.00
      3810239.25     10500004.00      3810312.75     10500044.00
      3810351.00     10500007.00      3810383.25     10499911.00
      3810409.50     10499881.00      3810638.00     10499709.00
      3810772.75     10499633.00      3810828.00     10499620.00
      3810835.25     10499588.00      3810897.25     10499498.00
      3811002.25     10499486.00      3811029.00     10499451.00

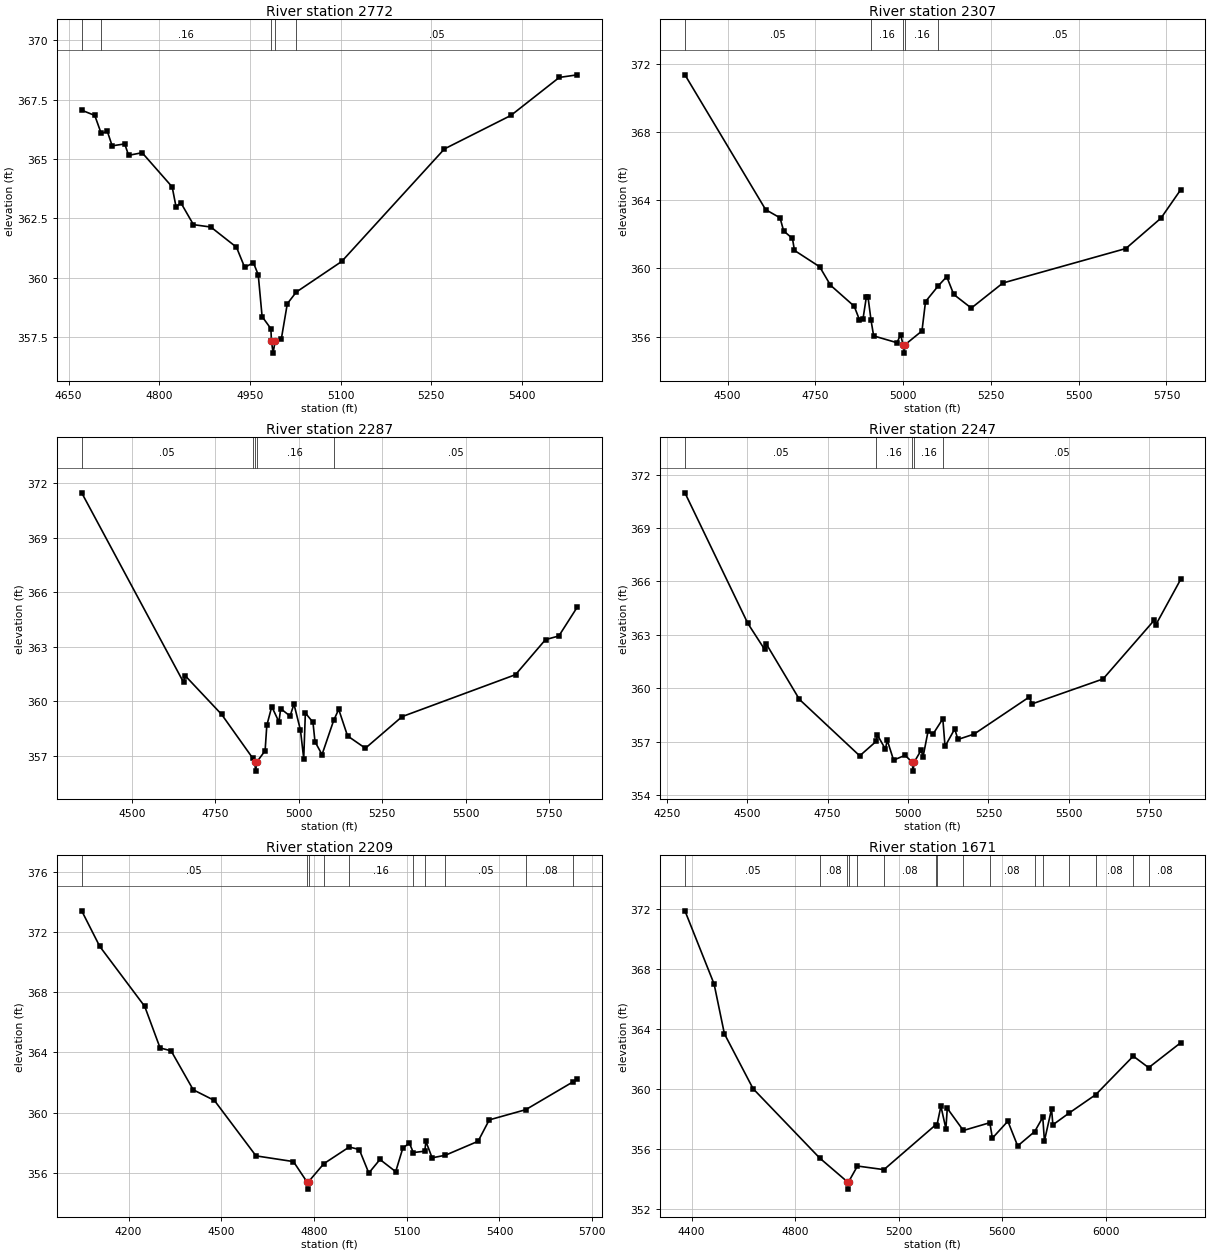
Type RM Length L Ch R = 1,2772,465,465,465
BEGIN DESCRIPTION:
UNT044 IN BECR 5.0
END DESCRIPTION:
XS GIS Cut Line= 3
      3809199.61     10500760.19      3808999.61     10500510.19
      3808499.56     10500510.19
#Sta/Elev= 30
  4671.7  367.06  4693.3  366.84  4704.0  366.08  4714.1  366.17  4722.1  365.56
  4742.9  365.64  4749.3  365.16  4771.7  365.27  4821.4  363.83  4827.8  362.99
  4835.8  363.16  4856.6  362.24  4885.4  362.14  4927.8  361.29  4941.4  360.44
  4955.8  360.64  4963.8  360.13  4970.2  358.37  4984.7  357.86  4985.7  357.33
  4988.4  356.83  4991.7  357.33  5001.9  357.41  5011.9  358.91  5026.7  359.40
  5101.9  360.69  5271.9  365.43  5381.9  366.84  5461.9  368.44  5491.9  368.55
#Mann=5,-1,0
  4671.7    0.05       0  4704.0    0.16       0  4985.7    0.07       0
  4991.7    0.16       0  5026.7    0.05       0
Bank Sta=4985.7,4991.7
Exp/Cntr=0.3,0.1

Type RM Length L Ch R = 1,2307,20,20,20
BEGIN DESCRIPTION:
UNT044 IN BECR 4.0
END DESCRIPTION:
XS GIS Cut Line= 6
      3809413.63     10500704.01      3809295.89     10500196.18
      3809300.23     10500163.63      3809291.55     10500137.58
      3809170.02     10500115.88      3808463.63     10500131.05
#Sta/Elev= 30
  4378.7  371.34  4608.5  363.44  4649.5  362.96  4659.8  362.19  4684.9  361.75
  4690.6  361.05  4762.4  360.09  4793.2  359.01  4860.7  357.78  4875.4  357.00
  4885.6  357.01  4895.4  358.33  4900.0  358.33  4908.7  356.95  4916.1  356.04
  4982.6  355.64  4992.7  356.11  4999.9  355.53  5002.6  355.03  5005.9  355.53
  5053.7  356.33  5063.8  358.05  5100.4  358.98  5124.2  359.51  5144.2  358.47
  5194.2  357.67  5284.2  359.14  5634.3  361.16  5734.3  362.94  5790.3  364.60
#Mann=5,-1,0
  4378.7    0.05       0  4908.7    0.16       0  4999.9    0.07       0
  5005.9    0.16       0  5100.4    0.05       0
Bank Sta=4999.9,5005.9
Exp/Cntr=0.3,0.1

Type RM Length L Ch R = 1,2287,40,40,40
BEGIN DESCRIPTION:
Mapping XS 4fcaa447
END DESCRIPTION:
XS GIS Cut Line= 5
      3809447.81     10500691.01      3809330.61     10500131.07
      3809235.13     10500105.03      3809200.41     10500087.67
      3808424.07     10500065.99
#Sta/Elev= 30
  4349.0  371.46  4654.4  361.03  4659.5  361.39  4768.7  359.26  4861.6  356.86
  4867.9  356.64  4870.6  356.14  4873.9  356.64  4899.0  357.26  4904.1  358.66
  4919.0  359.69  4940.5  358.85  4945.7  359.58  4973.9  359.17  4985.5  359.83
  5005.0  358.40  5014.8  356.83  5019.7  359.34  5042.5  358.83  5048.6  357.76
  5069.7  357.05  5104.8  358.94  5119.7  359.54  5146.2  358.08  5199.7  357.40
  5309.8  359.14  5649.9  361.45  5739.9  363.38  5779.9  363.58  5835.5  365.18
#Mann=5,-1,0
  4349.0    0.05       0  4861.6    0.16       0  4867.9    0.07       0
  4873.9    0.16       0  5104.8    0.05       0
Bank Sta=4867.9,4873.9
Exp/Cntr=0.3,0.1

Type RM Length L Ch R = 1,2247,38,38,38
BEGIN DESCRIPTION:
Mapping XS 42280b9c
END DESCRIPTION:
XS GIS Cut Line= 4
      3809482.53     10500673.63      3809374.02     10500113.71
      3809161.34     10500035.59      3808419.19     10499979.17
#Sta/Elev= 30
  4306.4  370.98  4502.0  363.64  4553.8  362.19  4558.9  362.50  4662.4  359.37
  4849.8  356.20  4900.8  357.01  4904.8  357.37  4929.9  356.57  4935.2  357.09
  4955.1  355.96  4990.9  356.23  5013.0  355.84  5015.8  355.34  5019.0  355.84
  5041.2  356.53  5046.5  356.12  5062.5  357.60  5077.0  357.40  5108.2  358.28
  5115.1  356.73  5145.2  357.71  5155.2  357.12  5205.3  357.42  5376.6  359.50
  5385.9  359.12  5606.5  360.52  5765.0  363.81  5770.1  363.55  5847.6  366.11
#Mann=5,-1,0
  4306.4    0.05       0  4900.8    0.16       0  5013.0    0.07       0
  5019.0    0.16       0  5108.2    0.05       0
Bank Sta=5013,5019
Exp/Cntr=0.3,0.1

Type RM Length L Ch R = 1,2209,538,538,538
BEGIN DESCRIPTION:
UNT044 IN BECR 3.0
END DESCRIPTION:
XS GIS Cut Line= 3
      3809755.95     10500777.76      3809508.57     10500122.39
      3808657.89     10499818.58
#Sta/Elev= 30
  4048.3  373.41  4106.6  371.05  4252.2  367.06  4301.9  364.30  4337.5  364.11
  4409.1  361.52  4477.7  360.81  4612.2  357.13  4733.4  356.75  4776.5  355.42
  4779.3  354.92  4782.5  355.42  4831.7  356.61  4914.0  357.72  4946.4  357.55
  4977.2  355.99  5013.3  356.89  5064.2  356.08  5087.5  357.66  5108.7  357.97
  5121.2  357.35  5158.4  357.44  5161.9  358.09  5182.1  357.00  5224.7  357.17
  5330.8  358.10  5366.9  359.52  5485.1  360.20  5639.0  362.06  5652.1  362.23
#Mann=10,-1,0
  4048.3    0.05       0  4776.5    0.07       0  4782.5    0.05       0
  4831.7    0.08       0  4914.0    0.16       0  5121.2    0.05       0
  5158.4    0.08       0  5224.7    0.05       0  5485.1    0.08       0
  5639.0    0.05       0
Bank Sta=4776.5,4782.5
Exp/Cntr=0.3,0.1

Type RM Length L Ch R = 1,1671,356,356,356
BEGIN DESCRIPTION:
Mapping XS 4920bcf2
END DESCRIPTION:
XS GIS Cut Line= 3
      3810042.41     10500677.93      3809764.64     10500092.01
      3808554.80     10499719.54
#Sta/Elev= 30
  4374.2  371.89  4486.8  367.01  4526.6  363.69  4637.3  360.03  4894.8  355.40
  5000.7  353.83  5003.4  353.33  5006.7  353.83  5040.4  354.87  5142.7  354.63
  5344.1  357.64  5347.1  357.57  5362.7  358.86  5382.0  357.36  5387.3  358.72
  5449.4  357.24  5551.6  357.76  5561.5  356.73  5621.3  357.86  5659.2  356.21
  5724.9  357.17  5756.1  358.12  5762.5  356.55  5790.0  358.67  5795.2  357.62
  5858.3  358.41  5960.6  359.63  6105.6  362.20  6165.0  361.43  6288.5  363.09
#Mann=16,-1,0
  4374.2    0.05       0  4894.8    0.08       0  5000.7    0.07       0
  5006.7    0.08       0  5040.4    0.05       0  5142.7    0.08       0
  5344.1    0.16       0  5347.1     0.1       0  5449.4    0.05       0
  5551.6    0.08       0  5724.9    0.16       0  5756.1     0.1       0
  5858.3    0.05       0  5960.6    0.08       0  6105.6    0.05       0
  6165.0    0.08       0
Bank Sta=5000.7,5006.7
Exp/Cntr=0.3,0.1

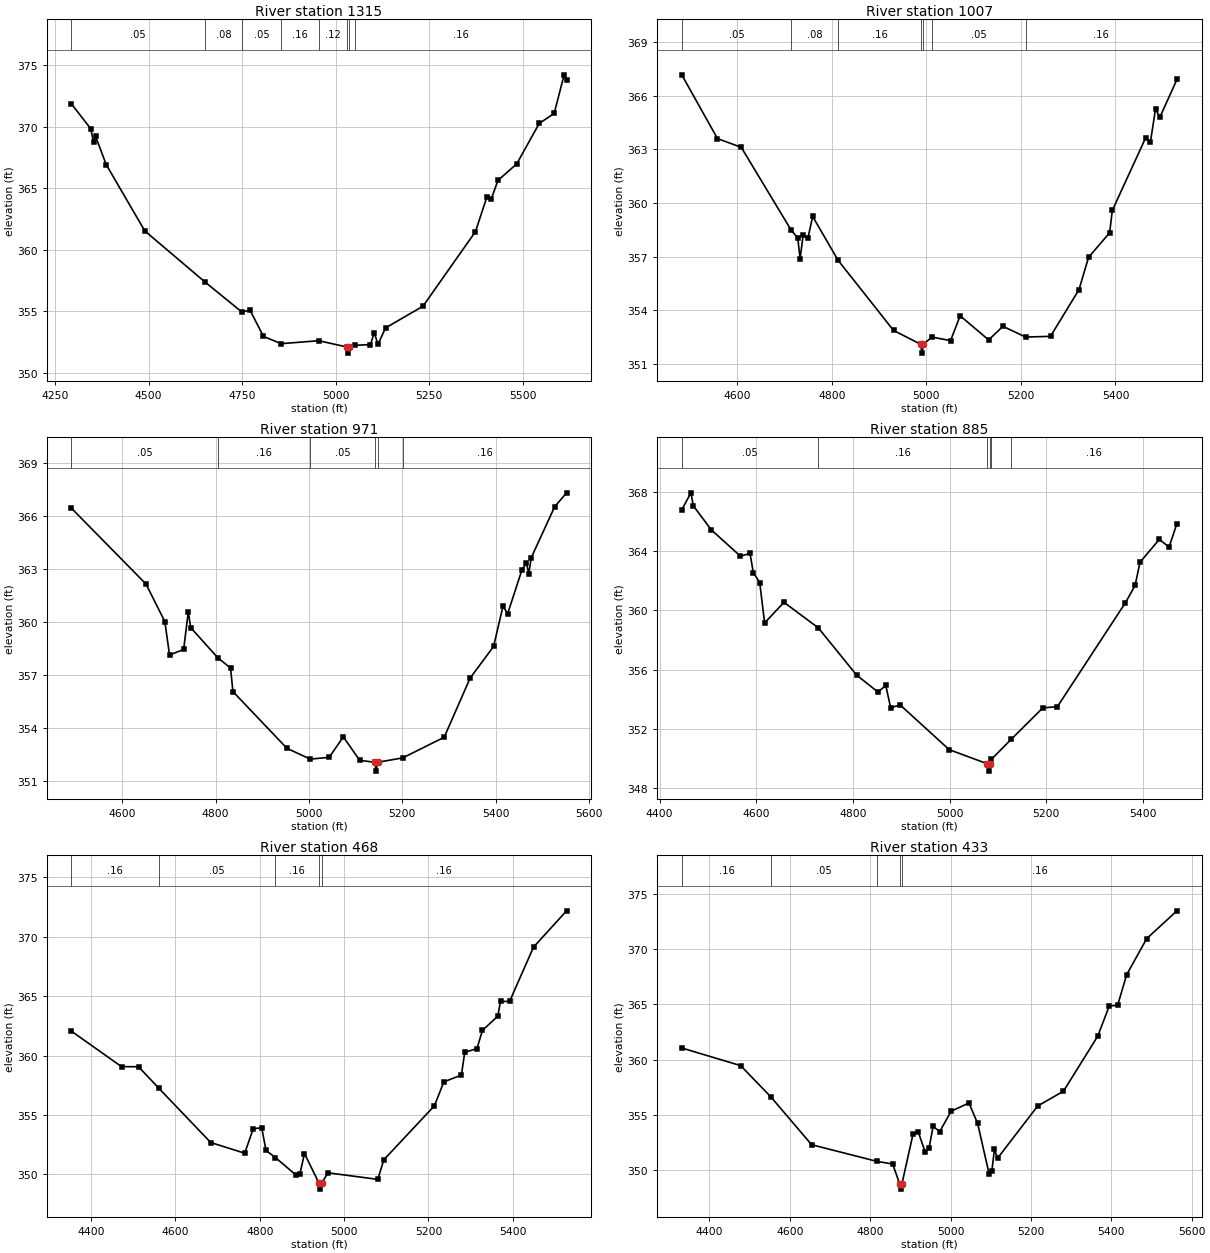
Type RM Length L Ch R = 1,1315,308,308,308
BEGIN DESCRIPTION:
UNT044 IN BECR 2.0
END DESCRIPTION:
XS GIS Cut Line= 3
      3810149.62     10500660.22      3809999.61     10500060.19
      3810034.87     10499357.17
#Sta/Elev= 30
  4294.1  371.88  4345.7  369.85  4353.4  368.74  4358.6  369.24  4386.9  366.94
  4490.0  361.54  4650.0  357.40  4749.5  354.93  4770.9  355.10  4806.9  352.95
  4854.3  352.36  4954.6  352.60  5029.8  352.09  5032.5  351.59  5035.8  352.09
  5052.7  352.23  5092.8  352.28  5102.8  353.26  5112.9  352.30  5132.9  353.64
  5233.0  355.41  5373.2  361.48  5403.2  364.26  5415.0  364.11  5433.3  365.65
  5483.3  366.99  5543.4  370.28  5583.4  371.10  5609.9  374.24  5616.5  373.82
#Mann=8,-1,0
  4294.1    0.05       0  4650.0    0.08       0  4749.5    0.05       0
  4854.3    0.16       0  4954.6    0.12       0  5029.8    0.07       0
  5035.8    0.12       0  5052.7    0.16       0
Bank Sta=5029.8,5035.8
Exp/Cntr=0.3,0.1

Type RM Length L Ch R = 1,1007,36,36,36
BEGIN DESCRIPTION:
Mapping XS 1ae49f9e
END DESCRIPTION:
XS GIS Cut Line= 2
      3810351.22     10500555.28      3810239.32     10499514.38
#Sta/Elev= 30
  4483.0  367.18  4558.5  363.61  4608.8  363.12  4714.6  358.47  4728.2  358.05
  4733.2  356.89  4739.6  358.20  4749.6  358.02  4759.7  359.25  4813.7  356.79
  4930.7  352.87  4988.0  352.10  4990.8  351.60  4994.0  352.10  5011.9  352.50
  5051.3  352.30  5071.5  353.69  5131.8  352.34  5162.0  353.10  5210.1  352.50
  5262.6  352.54  5322.9  355.16  5343.0  356.96  5387.6  358.34  5393.3  359.59
  5463.7  363.65  5473.8  363.41  5484.6  365.26  5493.9  364.81  5529.9  366.92
#Mann=7,-1,0
  4483.0    0.05       0  4714.6    0.08       0  4813.7    0.16       0
  4988.0    0.07       0  4994.0    0.16       0  5011.9    0.05       0
  5210.1    0.16       0
Bank Sta=4988,4994
Exp/Cntr=0.3,0.1

Type RM Length L Ch R = 1,971,86,86,86
BEGIN DESCRIPTION:
Mapping XS 09de1dc5
END DESCRIPTION:
XS GIS Cut Line= 2
      3810382.81     10500539.08      3810265.66     10499484.77
#Sta/Elev= 30
  4491.0  366.43  4650.8  362.14  4691.1  360.02  4701.2  358.13  4731.4  358.44
  4741.4  360.57  4746.4  359.68  4804.3  357.98  4831.9  357.39  4837.0  356.06
  4952.7  352.85  5002.6  352.24  5043.3  352.34  5073.5  353.50  5108.6  352.17
  5140.9  352.06  5143.6  351.56  5146.9  352.06  5200.9  352.31  5289.7  353.48
  5345.1  356.82  5395.4  358.61  5415.5  360.88  5425.6  360.47  5455.8  362.91
  5465.8  363.34  5470.8  362.72  5475.9  363.62  5526.2  366.51  5551.8  367.30
#Mann=6,-1,0
  4491.0    0.05       0  4804.3    0.16       0  5002.6    0.05       0
  5140.9    0.07       0  5146.9    0.05       0  5200.9    0.16       0
Bank Sta=5140.9,5146.9
Exp/Cntr=0.3,0.1

Type RM Length L Ch R = 1,885,417,417,417
BEGIN DESCRIPTION:
Mapping XS 55fc8a62
END DESCRIPTION:
XS GIS Cut Line= 4
      3810416.33     10500511.04      3810377.26     10500013.64
      3810330.39     10499784.47      3810301.86     10499494.01
#Sta/Elev= 30
  4445.9  366.81  4464.8  367.96  4469.8  367.08  4506.9  365.46  4567.1  363.68
  4587.2  363.86  4593.9  362.56  4607.2  361.89  4617.3  359.16  4657.4  360.55
  4728.3  358.83  4807.9  355.62  4852.0  354.48  4868.0  354.93  4878.1  353.43
  4898.1  353.60  4999.4  350.58  5078.0  349.63  5080.8  349.13  5084.0  349.63
  5086.7  349.93  5127.2  351.27  5193.1  353.41  5223.2  353.49  5363.9  360.52
  5384.0  361.69  5394.1  363.26  5434.2  364.81  5454.3  364.29  5470.6  365.88
#Mann=6,-1,0
  4445.9    0.05       0  4728.3    0.16       0  5078.0    0.07       0
  5084.0    0.16       0  5086.7    0.05       0  5127.2    0.16       0
Bank Sta=5078,5084
Exp/Cntr=0.3,0.1

Type RM Length L Ch R = 1,468,35,35,35
BEGIN DESCRIPTION:
Mapping XS 2c08738d
END DESCRIPTION:
XS GIS Cut Line= 4
      3810617.18     10500328.12      3810690.10     10499739.58
      3810669.26     10499682.29      3810264.42     10499355.30
#Sta/Elev= 30
  4353.2  362.05  4472.0  359.07  4512.3  359.06  4560.6  357.25  4683.6  352.69
  4764.2  351.79  4784.4  353.85  4804.6  353.93  4814.6  352.02  4837.2  351.42
  4885.2  349.97  4895.2  350.07  4906.0  351.76  4940.4  349.27  4943.2  348.77
  4946.4  349.27  4961.9  350.14  5079.8  349.59  5094.2  351.24  5214.2  355.78
  5236.5  357.79  5278.1  358.36  5286.1  360.28  5314.9  360.58  5328.1  362.12
  5364.4  363.31  5370.9  364.56  5392.4  364.55  5449.2  369.12  5527.6  372.17
#Mann=5,-1,0
  4353.2    0.16       0  4560.6    0.05       0  4837.2    0.16       0
  4940.4    0.07       0  4946.4    0.16       0
Bank Sta=4940.4,4946.4
Exp/Cntr=0.3,0.1

Type RM Length L Ch R = 1,433,35,35,35
BEGIN DESCRIPTION:
Mapping XS d4bdfc80
END DESCRIPTION:
XS GIS Cut Line= 5
      3810645.83     10500330.69      3810721.35     10499747.39
      3810716.14     10499692.71      3810666.66     10499619.79
      3810270.85     10499312.52
#Sta/Elev= 30
  4331.1  361.05  4477.6  359.45  4553.1  356.60  4654.3  352.27  4816.8  350.76
  4855.9  350.52  4873.1  348.74  4875.9  348.24  4879.1  348.74  4906.4  353.20
  4919.3  353.46  4936.5  351.65  4946.6  351.98  4956.6  353.94  4973.0  353.46
  5001.4  355.31  5045.9  356.06  5067.4  354.20  5096.3  349.57  5102.7  349.85
  5109.2  351.85  5117.1  351.05  5216.7  355.78  5281.0  357.13  5366.1  362.11
  5395.0  364.86  5415.8  364.93  5438.4  367.71  5488.2  370.98  5563.4  373.50
#Mann=5,-1,0
  4331.1    0.16       0  4553.1    0.05       0  4816.8    0.16       0
  4873.1    0.07       0  4879.1    0.16       0
Bank Sta=4873.1,4879.1
Exp/Cntr=0.3,0.1

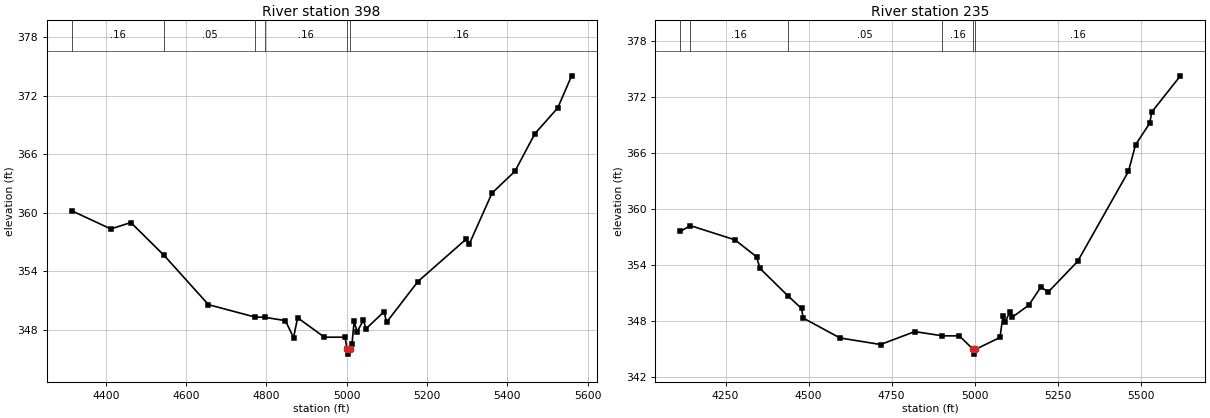
Type RM Length L Ch R = 1,398,163,163,163
BEGIN DESCRIPTION:
Mapping XS 95a42c96
END DESCRIPTION:
XS GIS Cut Line= 5
      3810669.26     10500325.55      3810763.01     10499763.02
      3810755.20     10499703.12      3810705.72     10499598.96
      3810323.78     10499276.77
#Sta/Elev= 30
  4314.6  360.20  4412.2  358.33  4462.0  358.99  4545.0  355.61  4655.5  350.55
  4770.5  349.29  4796.2  349.25  4847.2  348.91  4867.5  347.16  4877.6  349.21
  4944.3  347.21  4995.8  347.21  5000.9  345.97  5003.6  345.47  5006.9  345.97
  5013.0  346.49  5018.5  348.84  5026.0  347.76  5041.3  348.95  5048.2  348.08
  5092.9  349.83  5099.4  348.75  5177.4  352.93  5298.3  357.31  5304.9  356.74
  5362.1  362.02  5419.2  364.26  5468.7  368.11  5525.9  370.77  5560.3  374.06
#Mann=6,-1,0
  4314.6    0.16       0  4545.0    0.05       0  4770.5    0.08       0
  4796.2    0.16       0  5000.9    0.07       0  5006.9    0.16       0
Bank Sta=5000.9,5006.9
Exp/Cntr=0.3,0.1

Type RM Length L Ch R = 1,235,0,0,0
BEGIN DESCRIPTION:
UNT044 IN BECR 1.0
END DESCRIPTION:
XS GIS Cut Line= 4
      3810714.92     10500368.72      3810944.10     10499632.56
      3810735.77     10499486.73      3810326.03     10499236.72
#Sta/Elev= 30
  4114.3  357.63  4144.2  358.24  4278.3  356.72  4343.2  354.91  4353.8  353.66
  4438.1  350.72  4478.7  349.38  4483.9  348.35  4594.5  346.22  4716.9  345.52
  4819.7  346.90  4902.8  346.45  4954.2  346.44  4995.7  344.99  4998.4  344.49
  5001.7  344.99  5076.3  346.27  5085.0  348.52  5091.1  347.93  5105.9  348.96
  5112.0  348.41  5163.1  349.73  5199.8  351.69  5221.2  351.12  5310.2  354.42
  5463.1  364.04  5484.4  366.89  5527.0  369.19  5533.4  370.40  5619.6  374.27
#Mann=6,-1,0
  4114.3    0.05       0  4144.2    0.16       0  4438.1    0.05       0
  4902.8    0.16       0  4995.7    0.07       0  5001.7    0.16       0
Bank Sta=4995.7,5001.7
Exp/Cntr=0.3,0.1

Chan Stop Cuts=-1