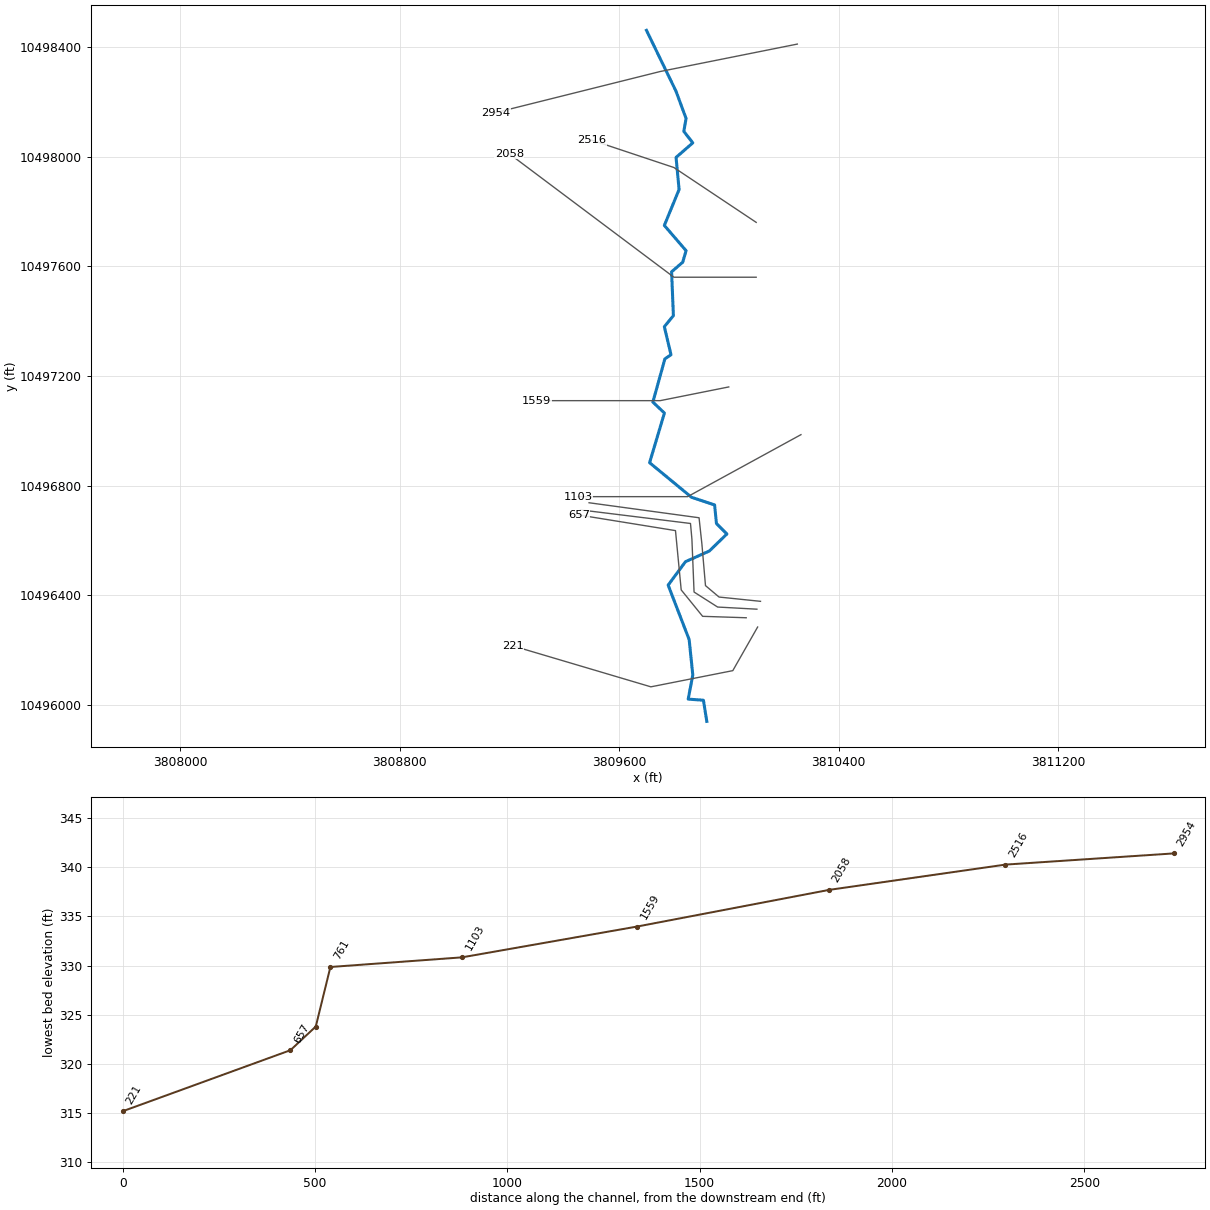
--- UNT045 IN BECR.prj (project) ---

Proj Title=UNT045 IN BECR Base Level Engineering
Current Plan=p01
Default Exp/Contr=0.3,0.1
English Units
Geom File=g01
Flow File=f01
Plan File=p01
BEGIN DESCRIPTION:
UNT045 IN BECR
END DESCRIPTION:

--- UNT045 IN BECR.p01 (plan) ---

Plan Title=Multiple Run
Short Identifier=Multiple
Geom File=g01
Flow File=f01
Subcritical Flow
K Sum by GR= 0
Std Step Tol= 0.01
Critical Tol= 0.01
Num of Std Step Trials= 20
Max Error Tol= 0.3
Flow Tol Ratio= 0.001
Split Flow NTrial= 30
Split Flow Tol= 0.02
Split Flow Ratio= 0.02
Log Output Level= 0
Friction Slope Method= 1
Unsteady Friction Slope Method= 2
Unsteady Bridges Friction Slope Method= 1
Parabolic Critical Depth
Global Vel Dist=  1 , 1 , 1
Global Log Level= 0
CheckData=True
Encroach Param= -1, 0, 0, 0
BEGIN DESCRIPTION:
Multiple Run
END DESCRIPTION:

--- UNT045 IN BECR.f01 (steady flow) ---

Flow Title=Multiple
Number of Profiles=7
Profile Names=10-year,25-year,50-year,1pct_min,100-year,1pct_plu,500-year
River Rch & RM= UNT045 IN BECR,Reach-1,2954
     170     210     241     204     275     372     360
Boundary for River Rch & Prof#=UNT045 IN BECR,Reach-1,1
Up Type=0
Dn Type=3
Dn Slope=0.005
Boundary for River Rch & Prof#=UNT045 IN BECR,Reach-1,2
Up Type=0
Dn Type=3
Dn Slope=0.005
Boundary for River Rch & Prof#=UNT045 IN BECR,Reach-1,3
Up Type=0
Dn Type=3
Dn Slope=0.005
Boundary for River Rch & Prof#=UNT045 IN BECR,Reach-1,4
Up Type=0
Dn Type=3
Dn Slope=0.005
Boundary for River Rch & Prof#=UNT045 IN BECR,Reach-1,5
Up Type=0
Dn Type=3
Dn Slope=0.005
Boundary for River Rch & Prof#=UNT045 IN BECR,Reach-1,6
Up Type=0
Dn Type=3
Dn Slope=0.005
Boundary for River Rch & Prof#=UNT045 IN BECR,Reach-1,7
Up Type=0
Dn Type=3
Dn Slope=0.005

--- UNT045 IN BECR.g01 (geometry) ---

Geom Title=Existing Conditions

River Reach=UNT045 IN BECR,Reach-1
Reach XY= 30
      3809699.61     10498460.19      3809807.00     10498239.00
      3809844.00     10498139.00      3809835.75     10498092.00
      3809868.50     10498050.00      3809807.50     10497997.00
      3809818.50     10497880.00      3809764.75     10497749.00
      3809844.00     10497657.00      3809831.75     10497615.00
      3809791.25     10497580.00      3809797.75     10497420.00
      3809764.75     10497380.00      3809789.03     10497277.67
      3809766.68     10497262.26      3809723.00     10497105.00
      3809765.00     10497065.00      3809711.00     10496884.00
      3809863.75     10496758.00      3809948.00     10496730.00
      3809954.75     10496662.00      3809992.75     10496624.00
      3809928.75     10496562.00      3809841.75     10496523.00
      3809778.68     10496437.61      3809855.25     10496239.00
      3809868.50     10496110.00      3809851.75     10496022.00
      3809907.25     10496018.00      3809919.50     10495941.00

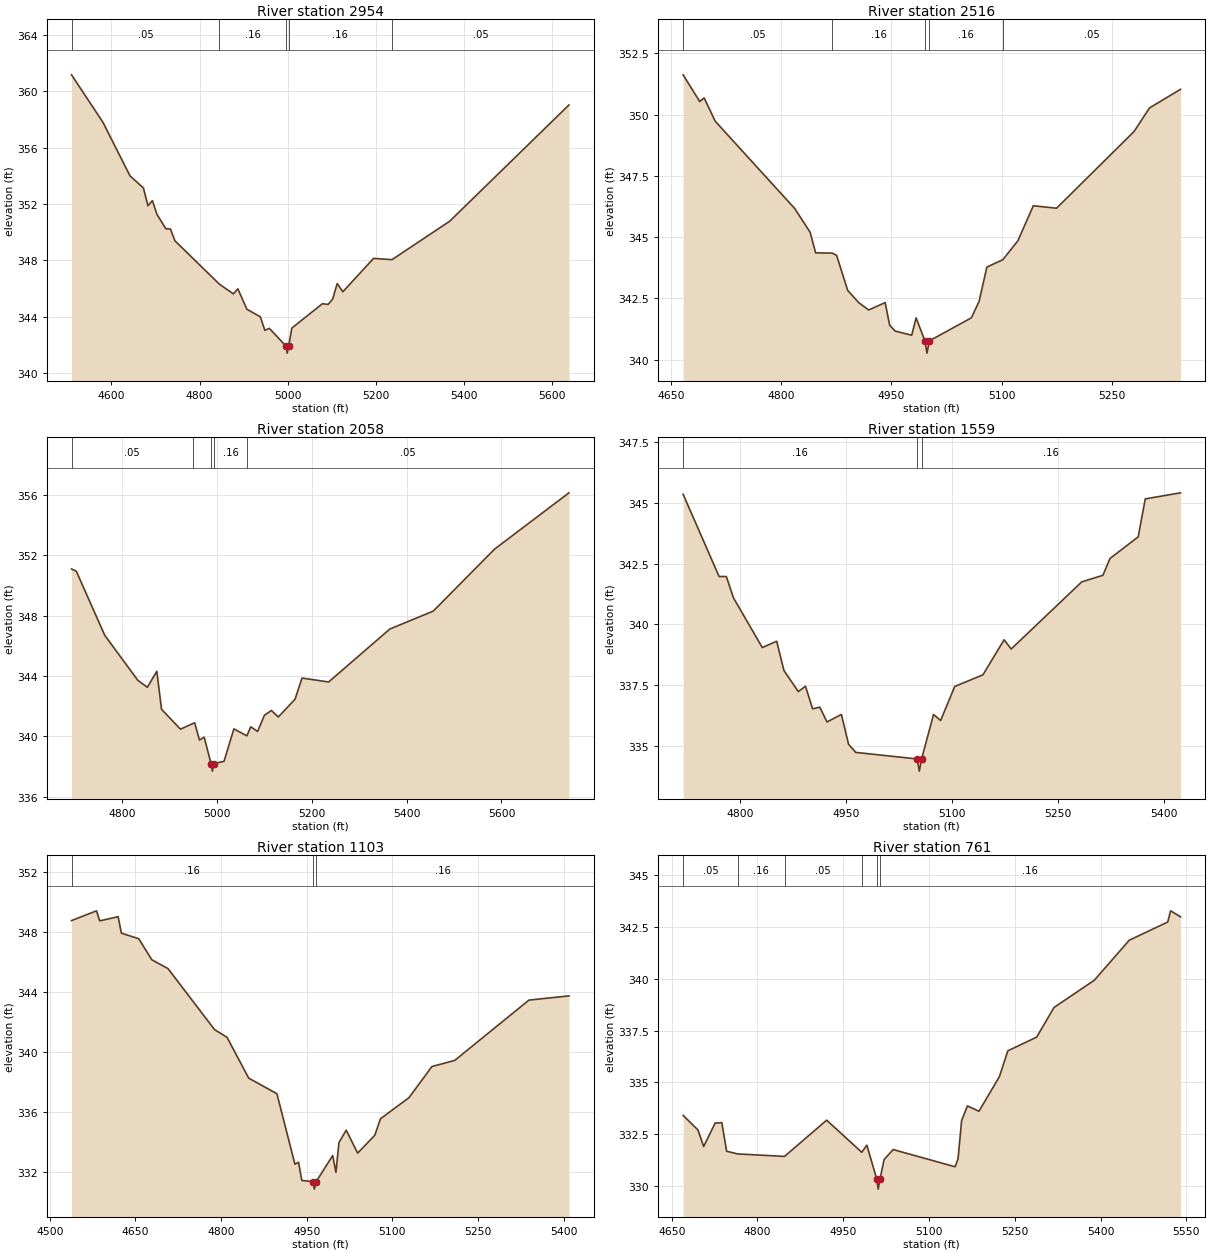
Type RM Length L Ch R = 1,2954,438,438,438
BEGIN DESCRIPTION:
UNT045 IN BECR 6.0
END DESCRIPTION:
XS GIS Cut Line= 3
      3810249.57     10498410.18      3809749.61     10498310.19
      3809149.64     10498160.20
#Sta/Elev= 30
  4509.5  361.18  4580.9  357.80  4642.0  354.01  4672.6  353.14  4682.8  351.88
  4693.0  352.24  4703.2  351.27  4723.6  350.24  4733.8  350.23  4744.0  349.39
  4844.9  346.31  4876.6  345.62  4886.8  345.98  4907.2  344.53  4937.8  343.99
  4948.0  343.03  4958.2  343.17  4996.0  341.91  4998.7  341.41  5002.0  341.91
  5009.2  343.19  5078.6  344.92  5091.5  344.87  5101.8  345.25  5112.1  346.35
  5125.0  345.77  5194.6  348.14  5236.5  348.05  5367.3  350.78  5637.8  359.04
#Mann=5,-1,0
  4509.5    0.05       0  4844.9    0.16       0  4996.0    0.07       0
  5002.0    0.16       0  5236.5    0.05       0
Bank Sta=4996,5002
Exp/Cntr=0.3,0.1

Type RM Length L Ch R = 1,2516,458,458,458
BEGIN DESCRIPTION:
UNT045 IN BECR 5.0
END DESCRIPTION:
XS GIS Cut Line= 3
      3810099.63     10497760.18      3809799.61     10497960.19
      3809499.61     10498060.19
#Sta/Elev= 30
  4666.6  351.62  4689.2  350.53  4695.2  350.68  4710.2  349.73  4818.4  346.17
  4839.4  345.20  4846.9  344.36  4869.4  344.35  4875.4  344.26  4890.5  342.83
  4905.5  342.33  4919.0  342.03  4941.5  342.33  4947.6  341.41  4955.1  341.17
  4977.6  341.00  4983.6  341.71  4995.6  340.77  4998.4  340.27  5001.6  340.77
  5058.8  341.71  5069.3  342.38  5079.9  343.78  5101.6  344.08  5122.0  344.85
  5143.1  346.28  5174.7  346.18  5280.2  349.31  5301.2  350.27  5343.4  351.03
#Mann=5,-1,0
  4666.6    0.05       0  4869.4    0.16       0  4995.6    0.07       0
  5001.6    0.16       0  5101.6    0.05       0
Bank Sta=4995.6,5001.6
Exp/Cntr=0.3,0.1

Type RM Length L Ch R = 1,2058,499,499,499
BEGIN DESCRIPTION:
UNT045 IN BECR 4.0
END DESCRIPTION:
XS GIS Cut Line= 3
      3810099.64     10497560.19      3809799.61     10497560.19
      3809199.63     10498010.17
#Sta/Elev= 30
  4692.5  351.10  4702.5  350.96  4762.5  346.71  4832.5  343.72  4852.5  343.26
  4872.5  344.32  4882.5  341.80  4922.5  340.48  4948.2  340.85  4952.5  340.90
  4962.5  339.76  4972.5  339.95  4987.0  338.20  4989.8  337.70  4993.0  338.20
  5014.4  338.35  5035.2  340.50  5062.7  340.04  5070.7  340.64  5085.2  340.33
  5099.8  341.41  5114.4  341.72  5129.0  341.29  5164.4  342.47  5179.0  343.87
  5235.2  343.61  5364.4  347.12  5456.1  348.31  5585.2  352.41  5742.5  356.15
#Mann=5,-1,0
  4692.5    0.05       0  4948.2    0.16       0  4987.0    0.07       0
  4993.0    0.16       0  5062.7    0.05       0
Bank Sta=4987,4993
Exp/Cntr=0.3,0.1

Type RM Length L Ch R = 1,1559,456,456,456
BEGIN DESCRIPTION:
UNT045 IN BECR 3.0
END DESCRIPTION:
XS GIS Cut Line= 3
      3809999.59     10497160.19      3809749.61     10497110.19
      3809299.64     10497110.19
#Sta/Elev= 30
  4718.9  345.35  4769.9  341.97  4780.1  341.97  4790.3  341.09  4831.1  339.05
  4851.5  339.31  4861.7  338.11  4882.1  337.24  4892.3  337.46  4902.4  336.53
  4912.6  336.60  4922.8  335.99  4943.2  336.30  4953.4  335.07  4963.6  334.74
  5050.8  334.47  5053.6  333.97  5056.8  334.47  5073.8  336.30  5083.8  336.05
  5103.8  337.45  5143.8  337.93  5173.8  339.37  5183.8  338.99  5283.8  341.75
  5313.8  342.02  5323.8  342.71  5363.8  343.60  5373.8  345.16  5423.8  345.41
#Mann=3,-1,0
  4718.9    0.16       0  5050.8    0.07       0  5056.8    0.16       0
Bank Sta=5050.8,5056.8
Exp/Cntr=0.3,0.1

Type RM Length L Ch R = 1,1103,342,342,342
BEGIN DESCRIPTION:
UNT045 IN BECR 2.0
END DESCRIPTION:
XS GIS Cut Line= 3
      3810262.85     10496986.21      3809849.61     10496760.19
      3809449.62     10496760.19
#Sta/Elev= 30
  4538.2  348.73  4581.9  349.38  4587.6  348.71  4619.8  348.99  4625.5  347.89
  4655.9  347.52  4678.7  346.12  4707.1  345.53  4788.7  341.46  4810.5  340.95
  4848.4  338.23  4897.8  337.19  4929.4  332.49  4935.7  332.62  4941.4  331.41
  4960.6  331.33  4963.4  330.83  4966.6  331.33  4995.5  333.07  5001.2  331.95
  5006.4  333.93  5019.2  334.76  5039.2  333.23  5069.2  334.42  5079.2  335.52
  5129.2  336.93  5169.2  339.00  5209.2  339.41  5339.2  343.43  5409.2  343.71
#Mann=3,-1,0
  4538.2    0.16       0  4960.6    0.07       0  4966.6    0.16       0
Bank Sta=4960.6,4966.6
Exp/Cntr=0.3,0.1

Type RM Length L Ch R = 1,761,38,38,38
BEGIN DESCRIPTION:
Mapping XS ecfaec96
END DESCRIPTION:
XS GIS Cut Line= 6
      3810115.33     10496378.56      3809964.24     10496394.19
      3809914.76     10496435.86      3809901.74     10496586.90
      3809891.33     10496683.26      3809490.33     10496737.94
#Sta/Elev= 30
  4670.0  333.41  4695.9  332.71  4705.9  331.91  4726.0  333.04  4737.7  333.06
  4746.1  331.68  4765.4  331.55  4847.3  331.43  4921.0  333.18  4982.4  331.63
  4991.3  331.97  5008.4  330.35  5011.1  329.85  5014.4  330.35  5021.4  331.28
  5037.3  331.76  5145.6  330.93  5150.7  331.31  5157.0  333.16  5167.1  333.87
  5187.3  333.61  5223.0  335.28  5237.8  336.53  5288.2  337.19  5318.5  338.62
  5389.1  339.94  5450.1  341.87  5517.4  342.75  5522.4  343.29  5539.8  343.00
#Mann=6,-1,0
  4670.0    0.05       0  4765.4    0.16       0  4847.3    0.05       0
  4982.4    0.16       0  5008.4    0.07       0  5014.4    0.16       0
Bank Sta=5008.4,5014.4
Exp/Cntr=0.3,0.1

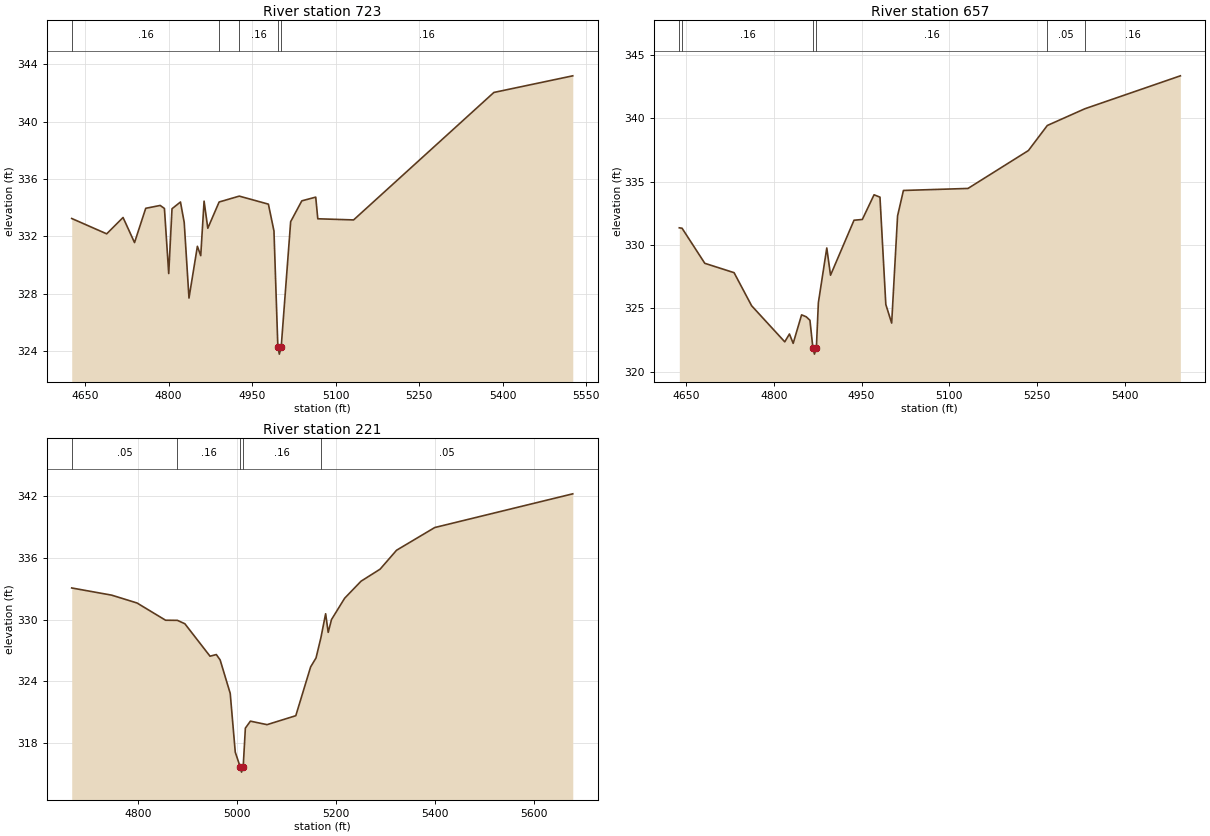
Type RM Length L Ch R = 1,723,66,66,66
BEGIN DESCRIPTION:
Mapping XS c52de4f3
END DESCRIPTION:
XS GIS Cut Line= 6
      3810102.27     10496349.92      3809959.03     10496357.74
      3809873.10     10496412.42      3809865.28     10496605.13
      3809860.08     10496662.42      3809459.02     10496711.90
#Sta/Elev= 30
  4625.9  333.25  4688.7  332.18  4718.1  333.32  4738.7  331.57  4758.8  333.96
  4784.8  334.16  4792.4  333.95  4800.1  329.41  4806.0  333.93  4821.2  334.40
  4827.9  332.98  4836.5  327.70  4851.6  331.31  4857.6  330.66  4863.6  334.46
  4870.3  332.57  4890.6  334.40  4926.8  334.81  4979.1  334.25  4989.1  332.38
  4996.1  324.29  4998.8  323.79  5002.1  324.29  5019.1  333.03  5039.1  334.48
  5064.1  334.74  5067.8  333.23  5132.1  333.15  5384.0  342.04  5525.7  343.20
#Mann=5,-1,0
  4625.9    0.16       0  4890.6    0.05       0  4926.8    0.16       0
  4996.1    0.07       0  5002.1    0.16       0
Bank Sta=4996.1,5002.1
Exp/Cntr=0.3,0.1

Type RM Length L Ch R = 1,657,436,436,436
BEGIN DESCRIPTION:
Mapping XS 16d8fcf7
END DESCRIPTION:
XS GIS Cut Line= 5
      3810063.23     10496318.67      3809904.35     10496323.88
      3809826.22     10496420.24      3809805.39     10496636.38
      3809452.94     10496693.40
#Sta/Elev= 30
  4638.3  331.35  4643.0  331.32  4681.9  328.55  4732.0  327.81  4762.0  325.20
  4818.7  322.35  4826.7  322.97  4833.1  322.23  4847.5  324.48  4855.4  324.33
  4861.8  324.05  4866.8  321.88  4869.5  321.38  4872.8  321.88  4876.2  325.44
  4890.6  329.76  4897.0  327.61  4937.2  331.95  4951.4  332.01  4971.5  333.96
  4981.6  333.77  4991.6  325.30  5001.6  323.83  5011.7  332.29  5021.7  334.30
  5132.2  334.46  5235.5  337.45  5267.9  339.43  5332.1  340.75  5495.5  343.35
#Mann=6,-1,0
  4638.3    0.05       0  4643.0    0.16       0  4866.8    0.07       0
  4872.8    0.16       0  5267.9    0.05       0  5332.1    0.16       0
Bank Sta=4866.8,4872.8
Exp/Cntr=0.3,0.1

Type RM Length L Ch R = 1,221,0,0,0
BEGIN DESCRIPTION:
UNT045 IN BECR 1.0
END DESCRIPTION:
XS GIS Cut Line= 4
      3810104.88     10496284.85      3810014.35     10496125.87
      3809715.74     10496066.84      3809212.26     10496216.15
#Sta/Elev= 30
  4665.2  333.09  4746.0  332.39  4797.1  331.63  4854.9  329.95  4878.7  329.94
  4893.8  329.61  4944.7  326.45  4957.4  326.61  4965.1  326.09  4985.5  322.83
  4995.7  317.11  5005.7  315.67  5008.4  315.17  5011.7  315.67  5016.1  319.45
  5026.3  320.13  5059.9  319.79  5118.0  320.66  5148.0  325.41  5158.9  326.28
  5168.8  328.26  5178.3  330.58  5183.5  328.77  5190.2  330.02  5216.7  332.09
  5249.9  333.75  5288.4  334.92  5321.6  336.76  5398.8  338.97  5677.7  342.25
#Mann=5,-1,0
  4665.2    0.05       0  4878.7    0.16       0  5005.7    0.07       0
  5011.7    0.16       0  5168.8    0.05       0
Bank Sta=5005.7,5011.7
Exp/Cntr=0.3,0.1

Chan Stop Cuts=-1