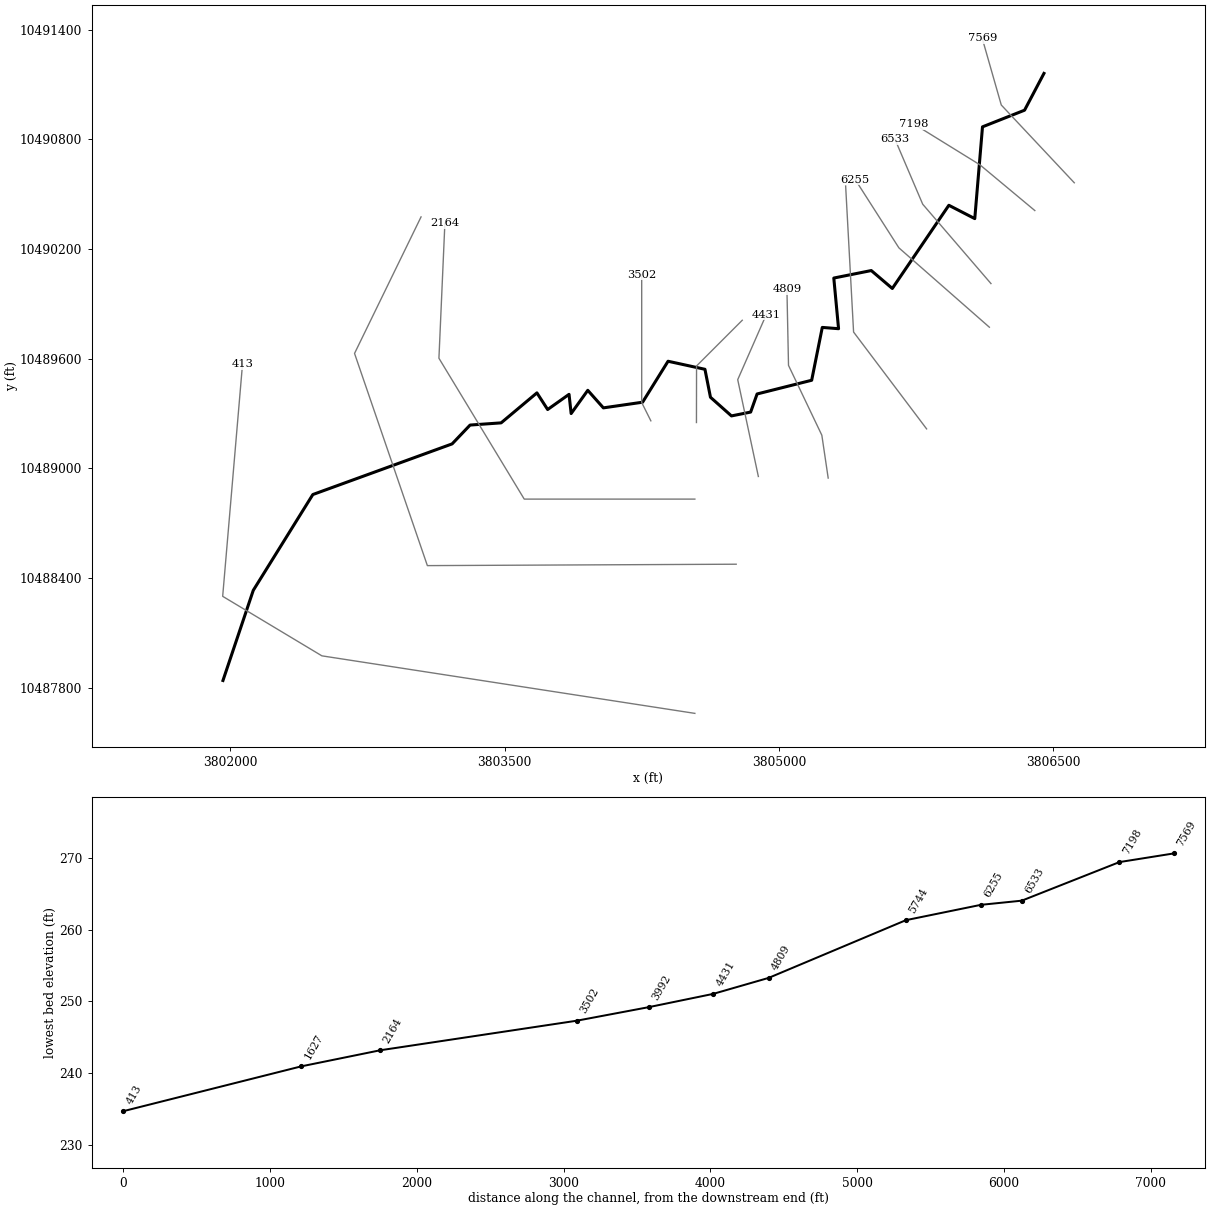
--- UNT046 IN BECR.prj (project) ---

Proj Title=UNT046 IN BECR Base Level Engineering
Current Plan=p01
Default Exp/Contr=0.3,0.1
English Units
Geom File=g01
Flow File=f01
Plan File=p01
BEGIN DESCRIPTION:
UNT046 IN BECR
END DESCRIPTION:

--- UNT046 IN BECR.p01 (plan) ---

Plan Title=Multiple Run
Short Identifier=Multiple
Geom File=g01
Flow File=f01
Subcritical Flow
K Sum by GR= 0
Std Step Tol= 0.01
Critical Tol= 0.01
Num of Std Step Trials= 20
Max Error Tol= 0.3
Flow Tol Ratio= 0.001
Split Flow NTrial= 30
Split Flow Tol= 0.02
Split Flow Ratio= 0.02
Log Output Level= 0
Friction Slope Method= 1
Unsteady Friction Slope Method= 2
Unsteady Bridges Friction Slope Method= 1
Parabolic Critical Depth
Global Vel Dist=  1 , 1 , 1
Global Log Level= 0
CheckData=True
Encroach Param= -1, 0, 0, 0
BEGIN DESCRIPTION:
Multiple Run
END DESCRIPTION:

--- UNT046 IN BECR.f01 (steady flow) ---

Flow Title=Multiple
Number of Profiles=7
Profile Names=10-year,25-year,50-year,1pct_min,100-year,1pct_plu,500-year
River Rch & RM= UNT046 IN BECR,Reach-1,7569
     513     684     823     728     985    1332    1414
River Rch & RM= UNT046 IN BECR,Reach-1,4809
     712     966    1175    1050    1420    1920    2080
Boundary for River Rch & Prof#=UNT046 IN BECR,Reach-1,1
Up Type=0
Dn Type=3
Dn Slope=0.005
Boundary for River Rch & Prof#=UNT046 IN BECR,Reach-1,2
Up Type=0
Dn Type=3
Dn Slope=0.005
Boundary for River Rch & Prof#=UNT046 IN BECR,Reach-1,3
Up Type=0
Dn Type=3
Dn Slope=0.005
Boundary for River Rch & Prof#=UNT046 IN BECR,Reach-1,4
Up Type=0
Dn Type=3
Dn Slope=0.005
Boundary for River Rch & Prof#=UNT046 IN BECR,Reach-1,5
Up Type=0
Dn Type=3
Dn Slope=0.005
Boundary for River Rch & Prof#=UNT046 IN BECR,Reach-1,6
Up Type=0
Dn Type=3
Dn Slope=0.005
Boundary for River Rch & Prof#=UNT046 IN BECR,Reach-1,7
Up Type=0
Dn Type=3
Dn Slope=0.005

--- UNT046 IN BECR.g01 (geometry) ---

Geom Title=Existing Conditions

River Reach=UNT046 IN BECR,Reach-1
Reach XY= 30
      3806449.61     10491160.19      3806343.50     10490959.00
      3806113.50     10490868.00      3806071.25     10490366.00
      3805929.50     10490439.00      3805620.25     10489984.00
      3805505.25     10490082.00      3805300.25     10490041.00
      3805326.25     10489764.00      3805237.25     10489771.00
      3805179.25     10489482.00      3804880.75     10489407.00
      3804845.50     10489308.00      3804740.50     10489287.00
      3804625.75     10489389.00      3804595.50     10489542.00
      3804393.75     10489586.00      3804254.50     10489362.00
      3804040.00     10489331.00      3803954.75     10489427.00
      3803863.75     10489300.00      3803852.25     10489405.00
      3803735.25     10489322.00      3803676.50     10489413.00
      3803480.75     10489249.00      3803311.00     10489237.00
      3803212.75     10489134.00      3802451.00     10488857.00
      3802125.25     10488333.00      3801959.50     10487840.00

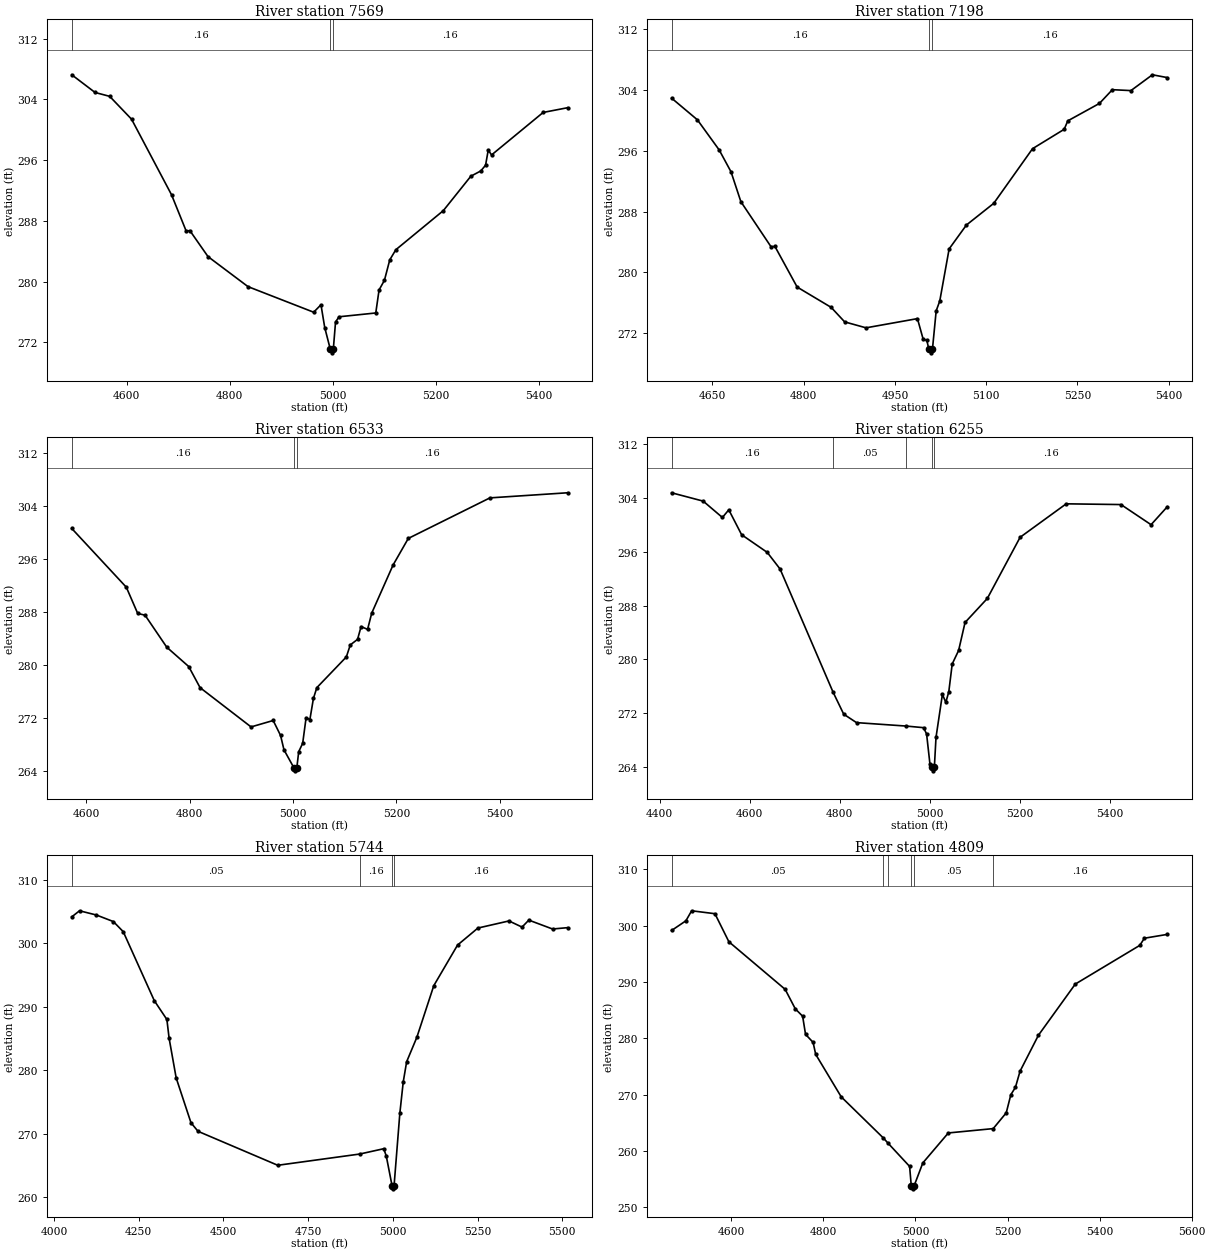
Type RM Length L Ch R = 1,7569,371,371,371
BEGIN DESCRIPTION:
UNT046 IN BECR 11.0
END DESCRIPTION:
XS GIS Cut Line= 3
      3806615.47     10490562.08      3806216.18     10490987.41
      3806112.00     10491352.03
#Sta/Elev= 30
  4493.4  307.25  4538.6  304.92  4567.0  304.41  4609.5  301.40  4687.1  291.45
  4715.5  286.68  4722.8  286.72  4758.0  283.30  4835.6  279.35  4963.1  275.98
  4977.3  276.96  4984.6  273.96  4995.3  271.13  4998.1  270.63  5001.3  271.13
  5005.6  274.70  5012.4  275.38  5083.7  275.88  5090.1  278.91  5100.5  280.18
  5110.9  282.88  5122.7  284.21  5214.9  289.36  5268.3  293.89  5287.7  294.59
  5296.9  295.34  5302.1  297.34  5308.5  296.69  5408.7  302.29  5456.0  302.91
#Mann=3,-1,0
  4493.4    0.16       0  4995.3    0.07       0  5001.3    0.16       0
Bank Sta=4995.3,5001.3
Exp/Cntr=0.3,0.1

Type RM Length L Ch R = 1,7198,665,665,665
BEGIN DESCRIPTION:
UNT046 IN BECR 10.0
END DESCRIPTION:
XS GIS Cut Line= 3
      3806399.65     10490410.16      3806099.61     10490660.19
      3805738.74     10490883.24
#Sta/Elev= 30
  4582.9  302.92  4625.3  300.07  4661.1  296.11  4680.6  293.23  4696.8  289.30
  4746.3  283.38  4752.8  283.41  4789.3  278.07  4845.2  275.40  4867.4  273.49
  4902.5  272.71  4987.0  273.92  4996.5  271.19  5002.4  271.07  5005.7  269.92
  5008.5  269.42  5011.7  269.92  5017.8  274.94  5023.7  276.24  5039.1  283.09
  5067.5  286.23  5112.4  289.08  5176.2  296.27  5228.2  298.82  5234.1  299.93
  5286.1  302.22  5307.4  304.03  5337.9  303.91  5373.2  305.99  5397.7  305.62
#Mann=3,-1,0
  4582.9    0.16       0  5005.7    0.07       0  5011.7    0.16       0
Bank Sta=5005.7,5011.7
Exp/Cntr=0.3,0.1

Type RM Length L Ch R = 1,6533,278,278,278
BEGIN DESCRIPTION:
UNT046 IN BECR 9.0
END DESCRIPTION:
XS GIS Cut Line= 3
      3806159.78     10490010.81      3805786.49     10490444.88
      3805634.61     10490800.71
#Sta/Elev= 30
  4571.7  300.63  4677.3  291.76  4699.3  287.80  4713.5  287.54  4755.5  282.71
  4798.0  279.79  4820.0  276.60  4918.7  270.67  4961.5  271.64  4975.8  269.38
  4982.4  267.21  5001.3  264.54  5004.0  264.04  5007.3  264.54  5010.9  266.93
  5018.6  268.20  5025.2  272.07  5032.5  271.77  5039.4  274.98  5046.0  276.60
  5103.1  281.24  5110.7  283.05  5124.8  283.89  5131.6  285.82  5144.2  285.40
  5152.2  287.85  5193.5  295.11  5223.0  299.13  5381.0  305.25  5531.1  306.02
#Mann=3,-1,0
  4571.7    0.16       0  5001.3    0.07       0  5007.3    0.16       0
Bank Sta=5001.3,5007.3
Exp/Cntr=0.3,0.1

Type RM Length L Ch R = 1,6255,511,511,511
BEGIN DESCRIPTION:
UNT046 IN BECR 8.0
END DESCRIPTION:
XS GIS Cut Line= 3
      3806151.05     10489772.15      3805656.28     10490206.16
      3805417.58     10490579.40
#Sta/Elev= 30
  4426.8  304.75  4497.0  303.51  4539.7  301.08  4553.9  302.22  4582.4  298.52
  4639.3  295.90  4667.8  293.43  4785.5  275.15  4809.2  271.87  4837.6  270.62
  4947.7  270.11  4986.6  269.87  4993.3  268.93  5000.7  264.48  5004.5  263.96
  5007.3  263.46  5010.5  263.96  5014.2  268.43  5028.4  274.81  5036.0  273.63
  5042.6  275.20  5050.2  279.33  5064.4  281.33  5078.7  285.49  5128.2  289.06
  5201.0  298.14  5303.4  303.11  5425.1  303.00  5491.9  300.01  5528.0  302.68
#Mann=5,-1,0
  4426.8    0.16       0  4785.5    0.05       0  4947.7    0.16       0
  5004.5    0.07       0  5010.5    0.16       0
Bank Sta=5004.5,5010.5
Exp/Cntr=0.3,0.1

Type RM Length L Ch R = 1,5744,935,935,935
BEGIN DESCRIPTION:
UNT046 IN BECR 7.0
END DESCRIPTION:
XS GIS Cut Line= 3
      3805807.78     10489216.11      3805408.45     10489745.66
      3805365.05     10490544.23
#Sta/Elev= 30
  4052.6  304.15  4075.5  305.11  4125.5  304.44  4175.4  303.41  4204.5  301.82
  4296.2  290.95  4333.3  287.99  4339.9  285.03  4360.7  278.79  4404.4  271.73
  4425.2  270.38  4660.5  265.03  4902.4  266.80  4973.3  267.64  4980.8  266.48
  4997.8  261.82  5000.5  261.32  5003.8  261.82  5020.8  273.22  5030.8  278.15
  5040.9  281.34  5070.9  285.17  5121.0  293.32  5191.1  299.71  5251.2  302.39
  5342.9  303.51  5381.4  302.54  5401.4  303.64  5471.5  302.24  5515.6  302.45
#Mann=4,-1,0
  4052.6    0.05       0  4902.4    0.16       0  4997.8    0.07       0
  5003.8    0.16       0
Bank Sta=4997.8,5003.8
Exp/Cntr=0.3,0.1

Type RM Length L Ch R = 1,4809,378,378,378
BEGIN DESCRIPTION:
UNT046 IN BECR 6.0
END DESCRIPTION:
XS GIS Cut Line= 4
      3805269.56     10488947.04      3805234.84     10489181.42
      3805052.55     10489563.37      3805043.87     10489980.02
#Sta/Elev= 30
  4470.2  299.12  4501.3  300.84  4513.8  302.62  4564.4  302.10  4594.7  297.12
  4716.9  288.68  4739.0  285.21  4754.9  283.91  4761.2  280.69  4777.6  279.27
  4783.3  277.13  4838.7  269.60  4930.3  262.29  4939.9  261.42  4987.3  257.25
  4990.9  253.77  4993.6  253.27  4996.9  253.77  5016.0  257.87  5071.4  263.19
  5168.9  263.96  5197.2  266.76  5207.2  269.98  5217.2  271.29  5227.2  274.15
  5267.2  280.54  5347.2  289.61  5487.3  296.48  5497.3  297.75  5547.1  298.43
#Mann=6,-1,0
  4470.2    0.05       0  4930.3    0.16       0  4939.9    0.05       0
  4990.9    0.03       0  4996.9    0.05       0  5168.9    0.16       0
Bank Sta=4990.9,4996.9
Exp/Cntr=0.3,0.1

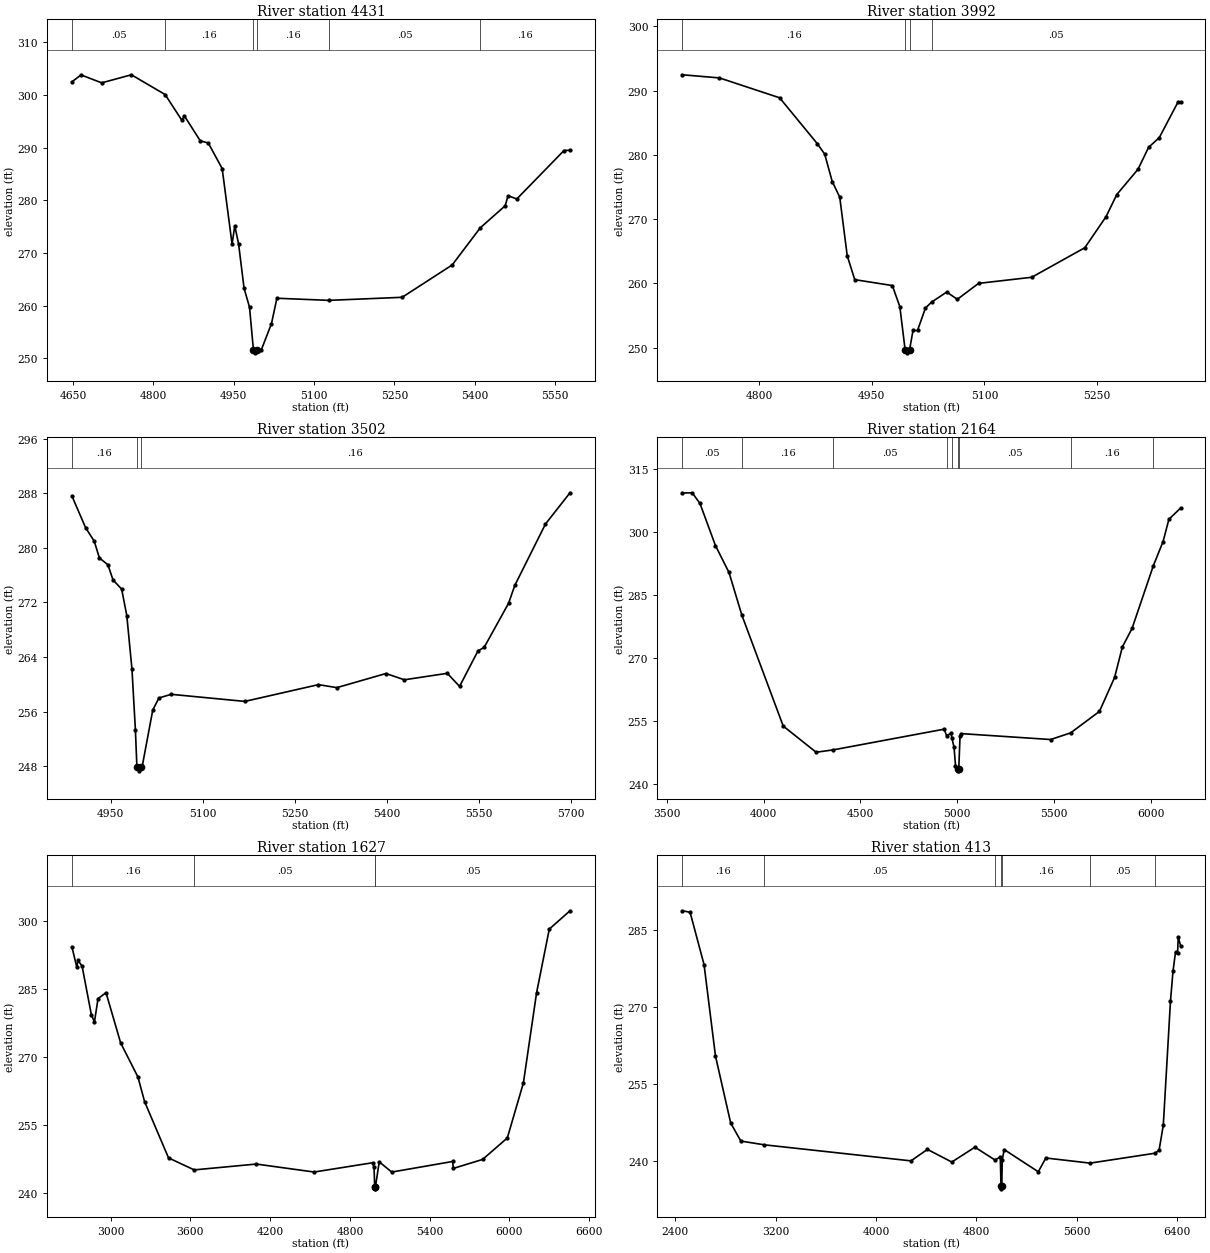
Type RM Length L Ch R = 1,4431,439,439,439
BEGIN DESCRIPTION:
UNT046 IN BECR 5.0
END DESCRIPTION:
XS GIS Cut Line= 3
      3804887.61     10488955.75      3804774.77     10489485.24
      3804931.03     10489841.17
#Sta/Elev= 30
  4647.9  302.47  4665.0  303.78  4703.6  302.28  4759.0  303.81  4822.0  300.06
  4853.0  295.21  4858.1  295.98  4887.6  291.28  4902.6  290.86  4928.5  286.01
  4947.0  271.67  4952.1  275.16  4959.2  271.67  4969.4  263.29  4979.6  259.69
  4986.9  251.54  4989.6  251.04  4992.9  251.54  5001.7  251.63  5020.5  256.56
  5030.7  261.40  5127.9  261.00  5264.6  261.58  5358.0  267.72  5410.3  274.75
  5456.8  278.94  5462.4  280.86  5478.6  280.24  5566.7  289.43  5578.0  289.50
#Mann=6,-1,0
  4647.9    0.05       0  4822.0    0.16       0  4986.9    0.07       0
  4992.9    0.16       0  5127.9    0.05       0  5410.3    0.16       0
Bank Sta=4986.9,4992.9
Exp/Cntr=0.3,0.1

Type RM Length L Ch R = 1,3992,490,490,490
BEGIN DESCRIPTION:
UNT046 IN BECR 4.0
END DESCRIPTION:
XS GIS Cut Line= 3
      3804549.07     10489250.83      3804549.61     10489560.19
      3804799.60     10489810.18
#Sta/Elev= 30
  4698.1  292.46  4747.5  291.97  4827.5  288.88  4877.5  281.76  4887.5  280.11
  4897.5  275.85  4907.5  273.42  4917.5  264.29  4927.5  260.58  4977.5  259.66
  4987.5  256.38  4994.5  249.69  4997.2  249.19  5000.5  249.69  5005.0  252.67
  5011.0  252.67  5021.6  256.17  5029.7  257.08  5049.9  258.65  5064.0  257.52
  5092.3  260.00  5163.0  260.95  5233.7  265.55  5262.0  270.40  5276.2  273.82
  5304.4  277.75  5318.6  281.18  5332.7  282.67  5357.5  288.18  5361.0  288.18
#Mann=4,-1,0
  4698.1    0.16       0  4994.5    0.07       0  5000.5    0.16       0
  5029.7    0.05       0
Bank Sta=4994.5,5000.5
Exp/Cntr=0.3,0.1

Type RM Length L Ch R = 1,3502,1338,1338,1338
BEGIN DESCRIPTION:
UNT046 IN BECR 3.0
END DESCRIPTION:
XS GIS Cut Line= 3
      3804299.63     10489260.15      3804249.61     10489360.19
      3804249.61     10490060.14
#Sta/Elev= 30
  4886.7  287.61  4909.1  282.94  4923.1  280.98  4931.5  278.52  4945.4  277.51
  4953.8  275.28  4967.8  273.95  4976.2  270.06  4984.6  262.22  4990.2  253.32
  4992.7  247.80  4995.5  247.30  4998.7  247.80  5001.0  247.80  5018.5  256.21
  5028.5  257.98  5048.5  258.52  5168.5  257.48  5288.5  259.94  5318.5  259.50
  5398.5  261.57  5428.5  260.65  5498.5  261.60  5518.5  259.68  5548.5  264.89
  5558.5  265.39  5598.5  271.89  5608.5  274.49  5658.5  283.49  5698.5  288.07
#Mann=3,-1,0
  4886.7    0.16       0  4992.7    0.07       0  4998.7    0.16       0
Bank Sta=4992.7,4998.7
Exp/Cntr=0.3,0.1

Type RM Length L Ch R = 1,2164,537,537,537
BEGIN DESCRIPTION:
UNT046 IN BECR 2.0
END DESCRIPTION:
XS GIS Cut Line= 4
      3804540.43     10488832.03      3803607.23     10488832.03
      3803140.65     10489602.43      3803173.21     10490340.25
#Sta/Elev= 30
  3580.3  309.36  3631.1  309.42  3671.1  306.88  3751.1  296.85  3821.1  290.43
  3887.3  280.29  4101.1  253.84  4271.1  247.61  4360.3  248.18  4932.2  253.11
  4945.1  251.51  4967.8  252.20  4972.0  251.05  4983.3  248.78  4990.7  244.45
  5001.7  243.68  5004.4  243.18  5007.7  243.68  5014.1  251.42  5020.2  252.05
  5482.0  250.64  5585.2  252.22  5734.0  257.33  5812.3  265.42  5852.4  272.69
  5902.4  277.09  6012.7  292.08  6062.6  297.79  6092.6  303.09  6152.7  305.76
#Mann=9,-1,0
  3580.3    0.05       0  3887.3    0.16       0  4360.3    0.05       0
  4945.1    0.16       0  4972.0    0.05       0  5001.7    0.03       0
  5007.7    0.05       0  5585.2    0.16       0  6012.7    0.05       0
Bank Sta=5001.7,5007.7
Exp/Cntr=0.3,0.1

Type RM Length L Ch R = 1,1627,1214,1214,1214
BEGIN DESCRIPTION:
Mapping XS 18b4332e
END DESCRIPTION:
XS GIS Cut Line= 4
      3804766.41     10488475.95      3803077.42     10488468.29
      3802679.11     10489628.76      3803042.87     10490375.43
#Sta/Elev= 30
  2709.1  294.35  2745.9  289.89  2755.9  291.35  2785.9  290.08  2855.9  279.32
  2878.8  277.80  2905.9  282.94  2965.9  284.23  3075.9  273.14  3205.9  265.62
  3255.9  260.19  3435.9  247.77  3628.9  245.12  4095.9  246.41  4531.1  244.65
  4971.0  246.70  4981.6  245.72  4986.5  241.44  4989.2  240.94  4992.5  241.44
  5020.7  246.90  5114.5  244.64  5572.8  246.98  5578.1  245.45  5798.2  247.43
  5984.1  252.17  6104.9  264.31  6203.9  284.17  6299.7  298.27  6455.6  302.31
#Mann=4,-1,0
  2709.1    0.16       0  3628.9    0.05       0  4986.5    0.03       0
  4992.5    0.05       0
Bank Sta=4986.5,4992.5
Exp/Cntr=0.3,0.1

Type RM Length L Ch R = 1,413,0,0,0
BEGIN DESCRIPTION:
UNT046 IN BECR 1.0
END DESCRIPTION:
XS GIS Cut Line= 4
      3804540.44     10487660.15      3802500.46     10487974.82
      3801957.93     10488300.34      3802066.44     10489569.92
#Sta/Elev= 30
  2456.9  288.76  2518.4  288.47  2629.7  278.29  2720.8  260.51  2842.2  247.46
  2923.2  243.97  3110.4  243.24  4279.0  240.12  4410.6  242.35  4604.5  239.89
  4789.1  242.78  4947.7  240.31  4991.2  240.85  4997.1  235.18  4999.9  234.68
  5003.1  235.18  5006.8  240.30  5022.3  242.32  5294.1  238.00  5354.4  240.68
  5707.1  239.68  6227.8  241.62  6257.6  242.25  6290.8  247.09  6347.9  271.20
  6368.0  276.99  6388.0  280.71  6404.7  280.56  6409.8  283.67  6427.9  282.00
#Mann=7,-1,0
  2456.9    0.16       0  3110.4    0.05       0  4947.7    0.16       0
  4997.1    0.07       0  5003.1    0.16       0  5707.1    0.05       0
  6227.8    0.16       0
Bank Sta=4997.1,5003.1
Exp/Cntr=0.3,0.1

Chan Stop Cuts=-1