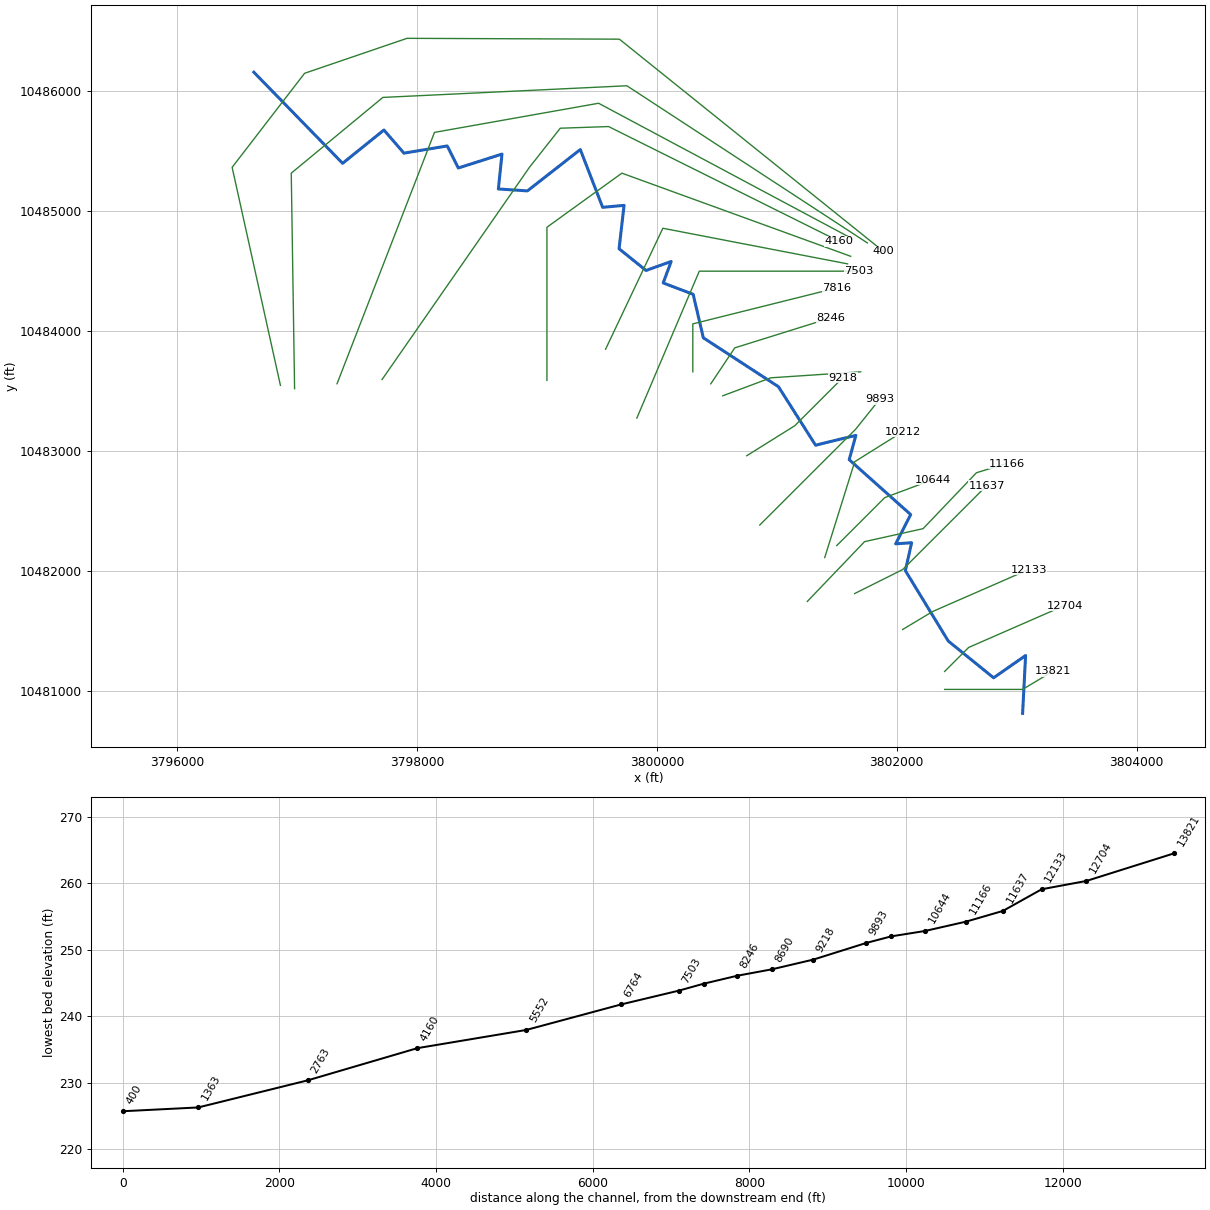
--- UNT047 IN BECR.prj (project) ---

Proj Title=UNT047 IN BECR Base Level Engineering
Current Plan=p01
Default Exp/Contr=0.3,0.1
English Units
Geom File=g01
Flow File=f01
Plan File=p01
Y Axis Title=Elevation
X Axis Title(PF)=Main Channel Distance
X Axis Title(XS)=Station
BEGIN DESCRIPTION:
UNT047 IN BECR
END DESCRIPTION:
DSS Export Rating Curves= 0
DSS Export Rating Curve Sorted= 0
DSS Export Volume Flow Curves= 0
DXF OffsetX= 0
DXF OffsetY= 0
DXF ScaleX= 1
DXF ScaleY= 10

--- UNT047 IN BECR.p01 (plan) ---

Plan Title=Multiple Run
Short Identifier=Multiple
Geom File=g01
Flow File=f01
Subcritical Flow
K Sum by GR= 0
Std Step Tol= 0.01
Critical Tol= 0.01
Num of Std Step Trials= 20
Max Error Tol= 0.3
Flow Tol Ratio= 0.001
Split Flow NTrial= 30
Split Flow Tol= 0.02
Split Flow Ratio= 0.02
Log Output Level= 0
Friction Slope Method= 1
Unsteady Friction Slope Method= 2
Unsteady Bridges Friction Slope Method= 1
Parabolic Critical Depth
Global Vel Dist=  1 , 1 , 1
Global Log Level= 0
CheckData=True
Encroach Param= -1, 0, 0, 0
BEGIN DESCRIPTION:
Multiple Run
END DESCRIPTION:

--- UNT047 IN BECR.f01 (steady flow) ---

Flow Title=Multiple
Number of Profiles=7
Profile Names=10-year,25-year,50-year,1pct_min,100-year,1pct_plu,500-year
River Rch & RM= UNT047 IN BECR,Reach-1,13821
     972    1333    1634    1469    1986    2686    2946
River Rch & RM= UNT047 IN BECR,Reach-1,2763
    1088    1499    1842    1660    2244    3035    3345
Boundary for River Rch & Prof#=UNT047 IN BECR,Reach-1,1
Up Type=0
Dn Type=3
Dn Slope=0.005
Boundary for River Rch & Prof#=UNT047 IN BECR,Reach-1,2
Up Type=0
Dn Type=3
Dn Slope=0.005
Boundary for River Rch & Prof#=UNT047 IN BECR,Reach-1,3
Up Type=0
Dn Type=3
Dn Slope=0.005
Boundary for River Rch & Prof#=UNT047 IN BECR,Reach-1,4
Up Type=0
Dn Type=3
Dn Slope=0.005
Boundary for River Rch & Prof#=UNT047 IN BECR,Reach-1,5
Up Type=0
Dn Type=3
Dn Slope=0.005
Boundary for River Rch & Prof#=UNT047 IN BECR,Reach-1,6
Up Type=0
Dn Type=3
Dn Slope=0.005
Boundary for River Rch & Prof#=UNT047 IN BECR,Reach-1,7
Up Type=0
Dn Type=3
Dn Slope=0.005

--- UNT047 IN BECR.g01 (geometry) ---

Geom Title=Existing Conditions
Program Version=4.10

River Reach=UNT047 IN BECR  ,Reach-1
Reach XY= 30
      3803049.61     10480810.19       3803074.5       10481293.
      3802807.75       10481107.       3802429.5       10481414.
        3802072.       10482001.        3802124.       10482234.
      3801991.25       10482225.       3802116.5       10482469.
      3801603.75       10482927.      3801659.25       10483130.
      3801323.25       10483048.      3801013.75       10483536.
       3800387.5       10483944.       3800302.5       10484307.
       3800052.5       10484402.      3800119.25       10484581.
      3799909.75       10484506.      3799684.75       10484687.
      3799726.25       10485049.      3799547.75       10485033.
       3799361.5       10485515.       3798920.5       10485170.
      3798678.25       10485186.       3798708.5       10485477.
        3798344.       10485361.      3798251.75       10485545.
      3797890.75       10485485.        3797724.       10485678.
       3797379.5       10485400.       3796639.5       10486160.

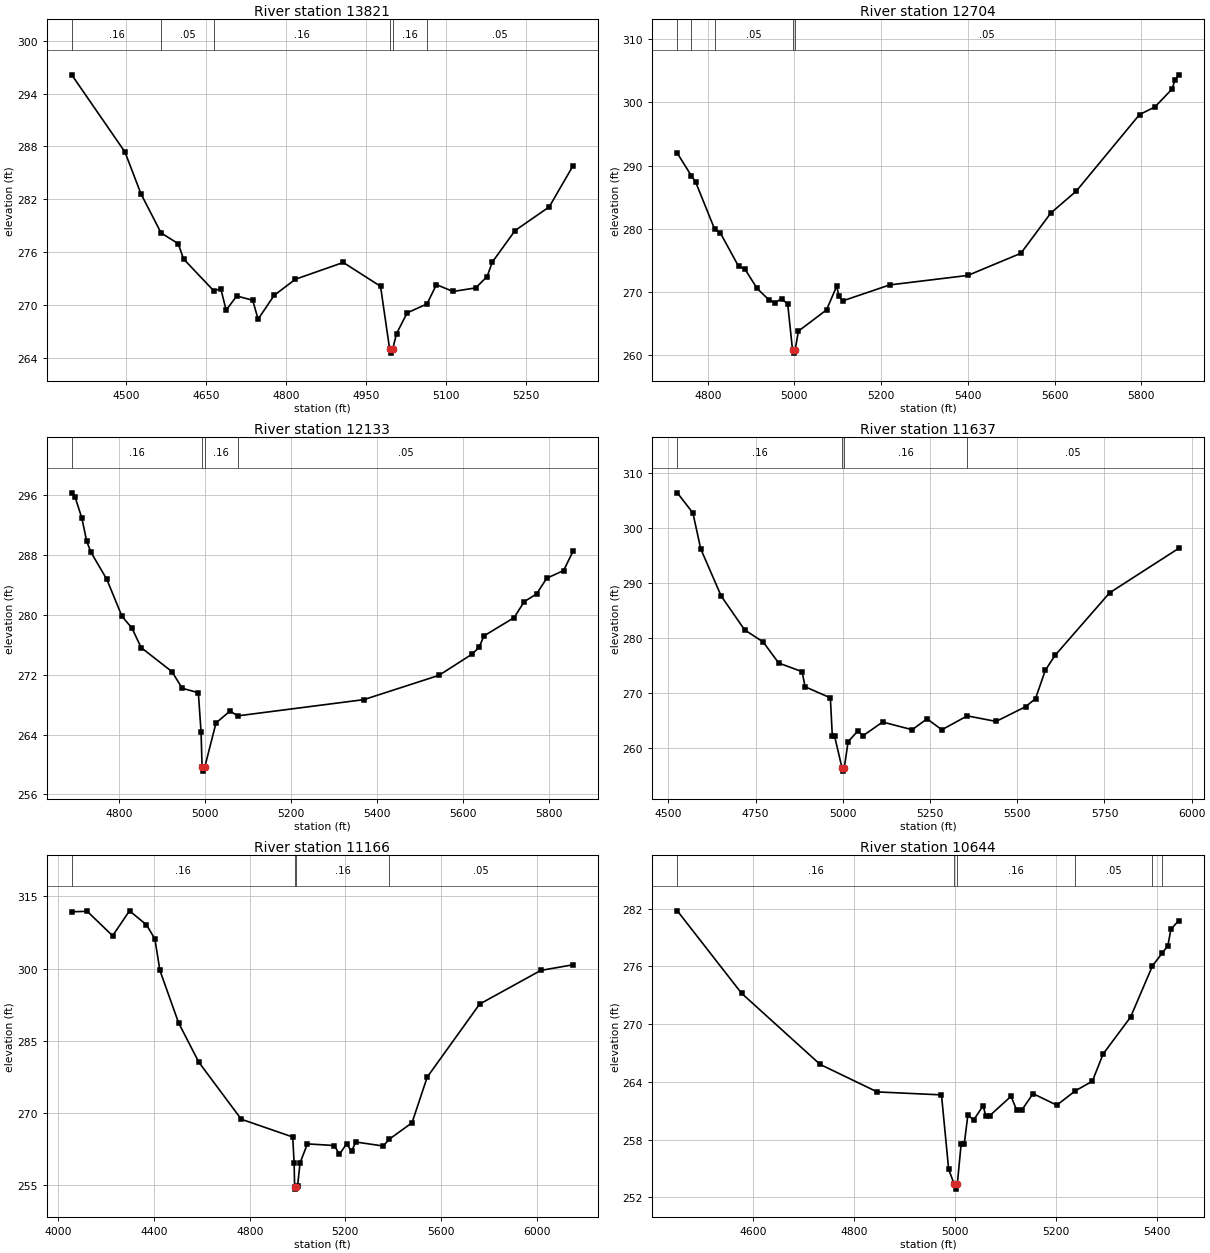
Type RM Length L Ch R = 1 ,13821   ,1117,1117,1117
BEGIN DESCRIPTION:
UNT047 IN BECR 15.0
END DESCRIPTION:
XS GIS Cut Line= 3
      3802399.62     10481010.19      3803049.61     10481010.19
      3803299.57     10481160.17
#Sta/Elev= 30
  4397.7  296.15  4497.7  287.37  4527.7  282.62  4565.5  278.17  4597.7  276.95
  4607.7  275.21  4664.4  271.59  4677.7  271.82  4687.7  269.39  4707.7     271
  4737.7  270.51  4747.7  268.35  4777.7  271.06  4817.7   272.9  4907.7  274.81
  4977.7   272.1  4994.7     265  4997.4   264.5  5000.7     265  5007.7  266.71
  5027.7  269.08  5064.9  270.09  5082.7  272.29  5113.8  271.51  5156.5  271.92
  5177.9  273.21  5187.6  274.85  5230.4  278.44  5294.5  281.13  5339.2   285.8
#Mann= 6 ,-1 , 0
  4397.7     .16       0  4565.5     .05       0  4664.4     .16       0
  4994.7     .07       0  5000.7     .16       0  5064.9     .05       0
Bank Sta=4994.7,5000.7
XS Rating Curve= 0 ,0
Exp/Cntr=0.3,0.1

Type RM Length L Ch R = 1 ,12704   ,571,571,571
BEGIN DESCRIPTION:
UNT047 IN BECR 14.0
END DESCRIPTION:
XS GIS Cut Line= 3
       3802399.6     10481160.18      3802599.61     10481360.19
      3803399.63      10481710.2
#Sta/Elev= 30
  4729.9  291.95  4762.1  288.41  4772.3  287.37  4816.1  279.93  4828.9  279.38
  4871.3  274.06  4885.5  273.68  4913.8  270.59  4942.1  268.72  4956.2  268.36
  4970.3  268.98  4984.5   268.1  4995.6  260.86  4998.4  260.36  5001.6  260.86
  5009.2  263.84    5074  267.19  5097.4  270.92  5102.8  269.39    5111  268.61
  5219.8  271.14  5399.9  272.64  5522.3  276.14  5591.3   282.5  5650.1  285.97
  5795.9  298.06  5831.4  299.26  5871.5  302.14    5877  303.46    5886  304.34
#Mann= 5 ,-1 , 0
  4729.9     .05       0  4762.1     .16       0  4816.1     .05       0
  4995.6     .03       0  5001.6     .05       0
Bank Sta=4995.6,5001.6
XS Rating Curve= 0 ,0
Exp/Cntr=0.3,0.1

Type RM Length L Ch R = 1 ,12133   ,496,496,496
BEGIN DESCRIPTION:
UNT047 IN BECR 13.0
END DESCRIPTION:
XS GIS Cut Line= 3
      3802049.64     10481510.21      3802299.61     10481660.19
      3803099.59     10482010.18
#Sta/Elev= 30
  4690.5  296.33  4698.2  295.77  4713.8     293  4725.4  289.83  4735.2  288.38
  4772.1  284.75  4807.1  279.83  4830.4  278.24  4851.8  275.63  4923.7   272.4
    4947   270.2  4984.7  269.59    4991  264.32  4993.4  259.61  4996.2  259.11
  4999.4  259.61  5025.7  265.55  5058.4  267.15    5076   266.5  5369.1  268.67
  5543.8  271.92  5619.4  274.71  5636.9  275.65  5648.2  277.19  5718.4  279.64
  5741.8  281.77  5770.6  282.81    5794   284.9  5833.4  285.94  5855.2  288.51
#Mann= 4 ,-1 , 0
  4690.5     .16       0  4993.4     .07       0  4999.4     .16       0
    5076     .05       0
Bank Sta=4993.4,4999.4
XS Rating Curve= 0 ,0
Exp/Cntr=0.3,0.1

Type RM Length L Ch R = 1 ,11637   ,471,471,471
BEGIN DESCRIPTION:
UNT047 IN BECR 12.0
END DESCRIPTION:
XS GIS Cut Line= 3
       3801649.6     10481810.19      3802049.61     10482010.19
      3802749.63     10482710.21
#Sta/Elev= 30
  4525.4  306.47  4570.1   302.8  4592.5  296.28  4651.2   287.7  4718.3  281.54
  4771.4  279.35  4816.1  275.51  4883.2  273.94  4891.6   271.2  4964.2  269.18
  4969.8  262.24  4976.2  262.24  4997.9  256.35  5000.7  255.85  5003.9  256.35
    5015  261.18  5043.3  263.19  5057.5  262.27    5114  264.78  5198.9  263.38
  5241.3  265.37  5283.7  263.37  5356.7   265.9  5439.3  264.89  5524.2  267.58
  5552.4  269.04  5580.7  274.23    5609  276.95  5764.6  288.27  5962.6  296.36
#Mann= 4 ,-1 , 0
  4525.4     .16       0  4997.9     .07       0  5003.9     .16       0
  5356.7     .05       0
Bank Sta=4997.9,5003.9
XS Rating Curve= 0 ,0
Exp/Cntr=0.3,0.1

Type RM Length L Ch R = 1 ,11166   ,522,522,522
BEGIN DESCRIPTION:
UNT047 IN BECR 11.0
END DESCRIPTION:
XS GIS Cut Line= 5
      3801254.23     10481743.95      3801731.68     10482243.11
      3802219.97     10482351.61      3802664.84     10482818.19
      3802914.43     10482894.15
#Sta/Elev= 30
  4055.7  311.81  4120.4  311.91  4226.7  306.83  4297.4  312.01  4368.2  309.11
  4403.4  306.18  4424.5  299.64  4502.5  288.77  4587.4  280.57  4764.8  268.75
  4979.9  265.06  4985.8  259.71  4987.9  254.74  4990.7  254.24  4993.9  254.74
  5000.4  254.97  5010.7   259.7  5041.4  263.63  5154.1  263.29  5175.3  261.44
  5205.3  263.66  5225.8   262.1  5243.9  264.02  5358.5  263.19    5384  264.62
  5478.9  268.01  5542.5   277.5  5761.7  292.65  6017.4  299.64  6152.2  300.81
#Mann= 4 ,-1 , 0
  4055.7     .16       0  4987.9     .07       0  4993.9     .16       0
    5384     .05       0
Bank Sta=4987.9,4993.9
XS Rating Curve= 0 ,0
Exp/Cntr=0.3,0.1

Type RM Length L Ch R = 1 ,10644   ,432,432,432
BEGIN DESCRIPTION:
UNT047 IN BECR 10.0
END DESCRIPTION:
XS GIS Cut Line= 3
      3801499.64     10482210.22      3801899.61     10482610.19
      3802299.57     10482760.18
#Sta/Elev= 30
  4450.2  281.78  4577.4  273.21    4733  265.81  4846.1  262.95  4973.4  262.64
  4987.6   254.9  4998.7  253.34  5001.4  252.84  5004.7  253.34  5012.3  257.52
  5018.5  257.52  5025.6  260.53  5037.2  260.03  5055.9  261.52  5061.2  260.44
  5069.2  260.49  5111.1  262.49  5122.6  261.03  5133.3  261.12  5154.7  262.77
  5201.8  261.57  5238.4  263.06  5272.2  264.06  5293.5  266.89  5347.8  270.72
  5391.3  276.06  5410.1  277.35  5421.7  278.15  5427.9  279.87    5443  280.75
#Mann= 6 ,-1 , 0
  4450.2     .16       0  4998.7     .07       0  5004.7     .16       0
  5238.4     .05       0  5391.3     .16       0  5410.1     .05       0
Bank Sta=4998.7,5004.7
XS Rating Curve= 0 ,0
Exp/Cntr=0.3,0.1

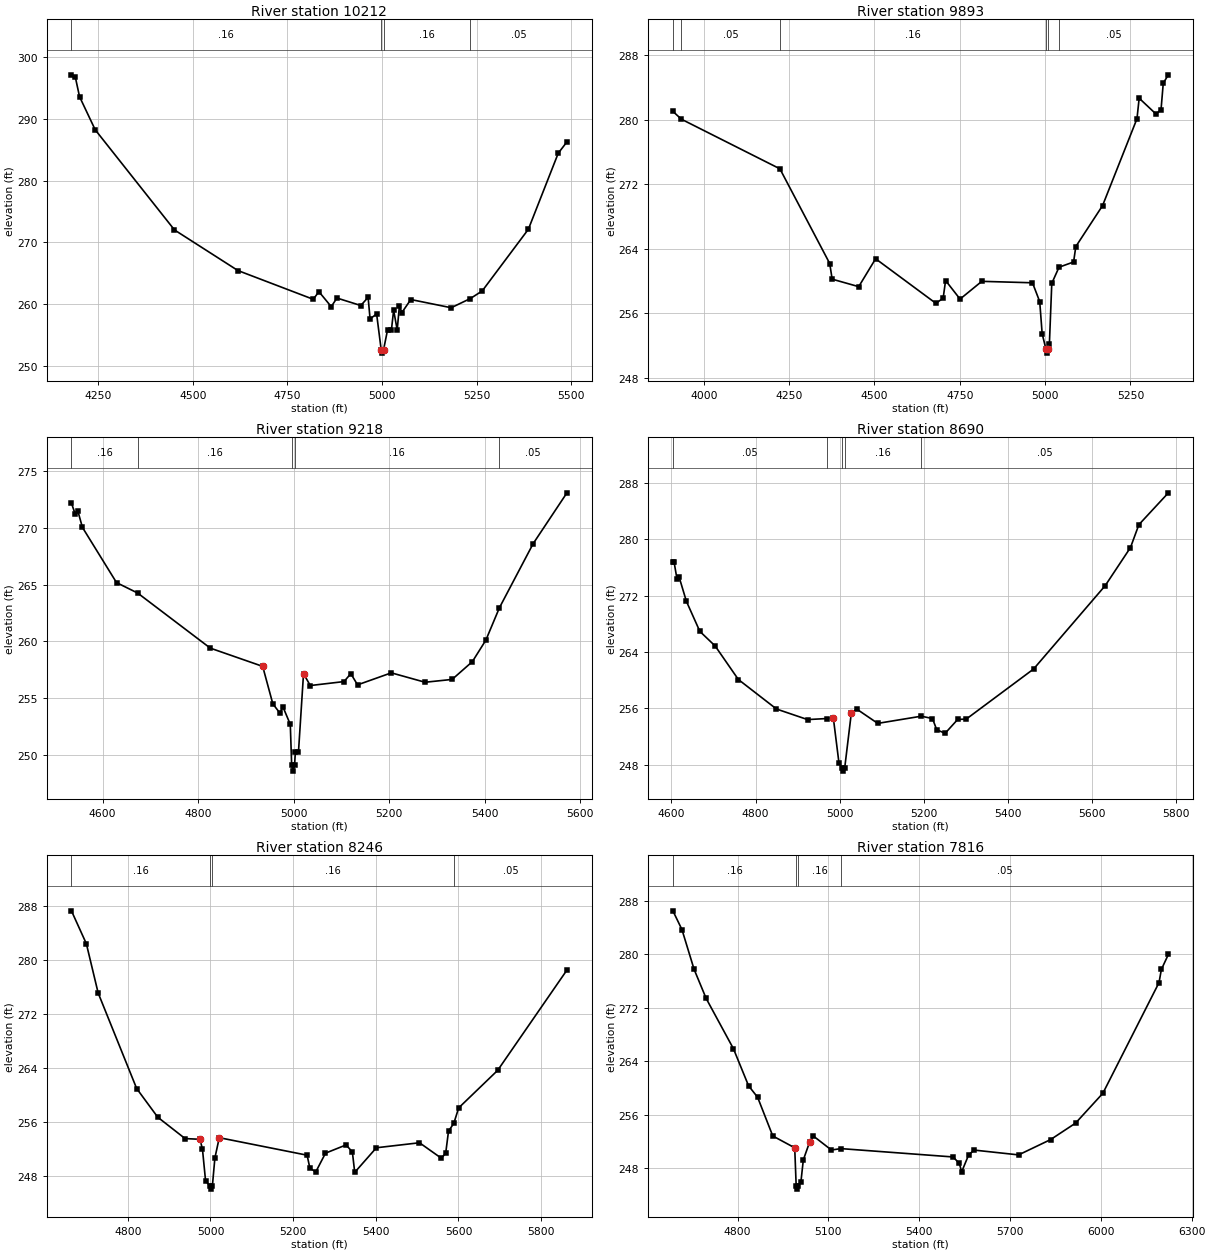
Type RM Length L Ch R = 1 ,10212   ,319,319,319
BEGIN DESCRIPTION:
UNT047 IN BECR 9.0
END DESCRIPTION:
XS GIS Cut Line= 3
      3801399.62     10482110.23      3801649.61     10482910.19
       3802049.6     10483160.18
#Sta/Elev= 30
    4179  297.15  4189.4  296.74  4200.4  293.61  4241.8  288.24  4451.4     272
    4619  265.42  4818.1  260.76  4833.2  261.99  4865.7  259.57  4880.9  260.96
  4943.8  259.75  4963.2  261.07  4968.4  257.58  4985.7  258.38  4997.9  252.53
  5000.6  252.03  5003.9  252.53  5014.5  255.77  5024.8  255.78  5030.7  258.99
  5040.1  255.79    5046  259.71  5052.5  258.61  5076.1  260.72  5182.8  259.39
  5233.5  260.88  5264.8  262.11  5386.8  272.11  5465.8  284.44  5488.8  286.28
#Mann= 4 ,-1 , 0
    4179     .16       0  4997.9     .07       0  5003.9     .16       0
  5233.5     .05       0
Bank Sta=4997.9,5003.9
XS Rating Curve= 0 ,0
Exp/Cntr=0.3,0.1

Type RM Length L Ch R = 1 ,9893    ,675,675,675
BEGIN DESCRIPTION:
UNT047 IN BECR 8.0
END DESCRIPTION:
XS GIS Cut Line= 3
       3800858.1     10482381.87      3801658.12     10483181.89
      3801858.14     10483431.92
#Sta/Elev= 30
  3909.7  281.01  3934.6  280.04  4223.2  273.89  4369.2  262.15  4376.3  260.21
  4454.1  259.28  4503.6  262.74  4680.3  257.21  4701.5  257.86  4708.6  260.04
    4751  257.74  4814.7  259.94  4963.2  259.76  4984.4  257.42  4991.5  253.45
  5002.6  251.54  5005.3  251.04  5008.6  251.54  5012.7  252.17  5019.7  259.69
  5040.9  261.69  5083.6  262.34  5090.1  264.25  5168.5  269.33  5269.3   280.1
  5275.7  282.64  5325.3  280.67  5339.8  281.24  5346.3  284.51  5361.3  285.54
#Mann= 6 ,-1 , 0
  3909.7     .16       0  3934.6     .05       0  4223.2     .16       0
  5002.6     .07       0  5008.6     .16       0  5040.9     .05       0
Bank Sta=5002.6,5008.6
XS Rating Curve= 0 ,0
Exp/Cntr=0.3,0.1

Type RM Length L Ch R = 1 ,9218    ,528,528,528
BEGIN DESCRIPTION:
UNT047 IN BECR 7.0
END DESCRIPTION:
XS GIS Cut Line= 3
      3800749.57     10482960.16      3801149.61     10483210.19
      3801549.59     10483610.16
#Sta/Elev= 30
  4534.7  272.19  4542.4  271.23  4548.3  271.46  4557.7  270.04  4629.1  265.17
  4673.3  264.25  4825.4  259.39  4935.1  257.78  4956.3  254.48  4971.1  253.66
  4977.6   254.2  4992.9  252.66  4995.8  249.04  4998.5  248.54  5001.8  249.04
  5003.5  250.21    5010  250.21  5020.6  257.14  5034.7  256.09  5105.4  256.44
  5119.6  257.14  5133.7  256.15  5204.4  257.21  5275.1  256.38  5331.7  256.63
  5374.1   258.2  5402.4   260.1  5430.7  262.95  5501.4  268.61  5572.1  273.09
#Mann= 5 ,-1 , 0
  4534.7     .16       0  4673.3     .16       0  4995.8     .07       0
  5001.8     .16       0  5430.7     .05       0
Bank Sta=4935.1,5020.6
XS Rating Curve= 0 ,0
Exp/Cntr=0.3,0.1

Type RM Length L Ch R = 1 ,8690    ,444,444,444
BEGIN DESCRIPTION:
UNT047 IN BECR 6.0
END DESCRIPTION:
XS GIS Cut Line= 3
      3800549.59     10483460.18      3800949.61     10483610.19
      3801699.63     10483660.19
#Sta/Elev= 30
  4603.4  276.82  4606.1  276.82  4613.2  274.35  4618.5  274.59  4635.5   271.2
  4667.5  266.93    4704  264.85  4759.2  260.09  4849.9   255.9  4923.8   254.4
  4970.4  254.55  4985.2  254.61  4998.6  248.21  5006.3  247.58    5009  247.08
  5012.3  247.58  5027.9   255.3  5040.6   255.9  5090.8  253.86  5194.4  254.88
    5221  254.55  5231.1  252.96  5251.1  252.45  5281.2  254.43  5301.2  254.46
  5461.6  261.58    5632  273.42  5692.1  278.83  5712.1  282.08  5782.3   286.6
#Mann= 5 ,-1 , 0
  4603.4     .05       0  4970.4     .16       0  5006.3     .07       0
  5012.3     .16       0  5194.4     .05       0
Bank Sta=4985.2,5027.9
XS Rating Curve= 0 ,0
Exp/Cntr=0.3,0.1

Type RM Length L Ch R = 1 ,8246    ,430,430,430
BEGIN DESCRIPTION:
UNT047 IN BECR 5.0
END DESCRIPTION:
XS GIS Cut Line= 3
       3800449.6     10483560.18      3800649.61     10483860.19
      3801449.59     10484110.18
#Sta/Elev= 30
  4663.7  287.28  4699.8  282.41  4728.3  275.13  4821.5  260.99  4872.5  256.75
  4938.6  253.59  4974.7  253.48  4980.7     252  4988.2  247.32  4998.7  246.61
  5001.5  246.11  5004.7  246.61  5010.7  250.71  5021.3  253.72  5233.8  251.13
  5240.6  249.19  5254.8  248.66  5278.3  251.43  5328.1  252.65  5343.3  251.61
    5349  248.59  5401.4  252.23  5505.7  252.97  5558.6  250.68  5569.1  251.43
  5575.9  254.69  5588.7  255.84  5600.5  258.13  5694.8  263.68  5862.4  278.52
#Mann= 4 ,-1 , 0
  4663.7     .16       0  4998.7     .07       0  5004.7     .16       0
  5588.7     .05       0
Bank Sta=4974.7,5021.3
XS Rating Curve= 0 ,0
Exp/Cntr=0.3,0.1

Type RM Length L Ch R = 1 ,7816    ,313,313,313
BEGIN DESCRIPTION:
UNT047 IN BECR 4.0
END DESCRIPTION:
XS GIS Cut Line= 3
      3800299.61     10483660.23      3800299.61     10484060.19
      3801499.62     10484360.19
#Sta/Elev= 30
  4586.2  286.53  4616.2  283.72  4656.2  277.79  4696.2  273.42  4786.2  265.91
  4836.2  260.37  4866.2  258.64  4916.2  252.86  4988.7  251.09  4993.5  245.41
  4996.2  244.91  4999.5  245.41  5009.3  246.05  5017.1  249.28  5037.7  251.92
  5050.6  252.84  5109.9  250.76  5141.3  250.97  5511.9  249.72  5532.5  248.75
  5540.2   247.5  5563.4  250.04  5581.4  250.75  5728.3  250.03    5834  252.32
  5916.4  254.78  6006.6  259.24  6192.2   275.8  6199.9  277.76  6223.1  280.01
#Mann= 4 ,-1 , 0
  4586.2     .16       0  4993.5     .07       0  4999.5     .16       0
  5141.3     .05       0
Bank Sta=4988.7,5037.7
XS Rating Curve= 0 ,0
Exp/Cntr=0.3,0.1

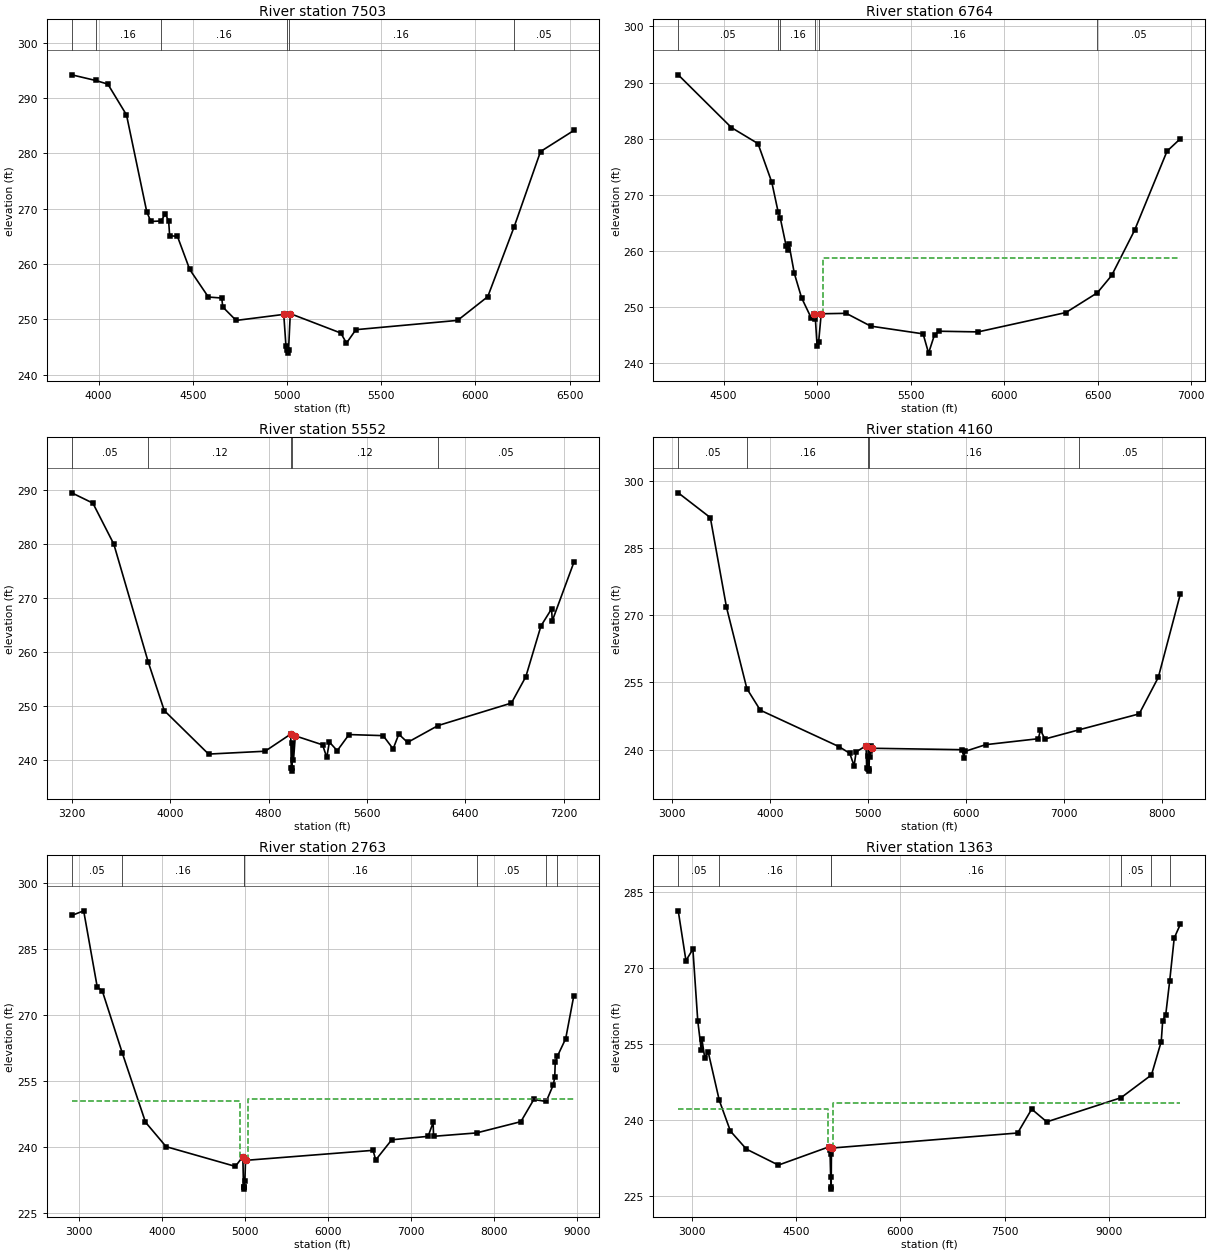
Type RM Length L Ch R = 1 ,7503    ,739,739,739
BEGIN DESCRIPTION:
UNT047 IN BECR 3.0
END DESCRIPTION:
XS GIS Cut Line= 3
      3799832.81     10483273.91      3800353.65     10484500.05
      3801686.47     10484500.05
#Sta/Elev= 30
  3857.4  294.19  3984.1  293.17  4048.9  292.51  4147.8  286.95  4255.4  269.44
  4277.1  267.68  4331.4  267.77  4353.3  269.02  4371.5  267.83  4376.9  265.11
  4418.3  264.99  4483.5     259  4582.5  254.02  4653.4  253.84  4658.9  252.22
  4729.8  249.79  4982.6  250.88  4994.2  245.22    5002  244.38  5004.8  243.88
    5008  244.38  5017.2  251.02  5285.5  247.51  5315.5  245.69  5365.5  248.12
  5905.5   249.8  6065.5  254.09  6205.5  266.71  6345.5  280.32  6522.4  284.13
#Mann= 6 ,-1 , 0
  3857.4     .05       0  3984.1     .16       0  4331.4     .16       0
    5002     .07       0    5008     .16       0  6205.5     .05       0
Bank Sta=4982.6,5017.2
XS Rating Curve= 0 ,0
Exp/Cntr=0.3,0.1

Type RM Length L Ch R = 1 ,6764    ,1212,1212,1212
BEGIN DESCRIPTION:
UNT047 IN BECR 2.0
END DESCRIPTION:
XS GIS Cut Line= 3
      3799572.39     10483849.01      3800049.83     10484858.12
      3801590.16     10484560.97
#Sta/Elev= 30
  4257.5  291.37  4542.1  281.97  4684.1  279.12  4757.9  272.23  4791.5     267
  4803.4  265.83  4834.1  260.97  4843.4   260.2    4849  261.32  4878.3  256.01
  4917.2  251.65  4968.3  248.08  4985.5  248.84    4991  247.88    5000  243.14
  5008.2  243.73  5022.1  248.81  5155.8  248.89  5286.8  246.61  5567.1  245.23
  5596.3   241.8  5628.2  245.09  5653.5   245.7  5860.9  245.58    6331  249.03
  6498.5  252.54  6575.4  255.63  6697.6  263.65  6871.7  277.78  6942.6  279.98
#Mann= 6 ,-1 , 0
  4257.5     .05       0  4791.5     .12       0  4803.4     .16       0
    4991     .05       0  5008.2     .16       0  6498.5     .05       0
#XS Ineff= 2 , 0
                         5031.25          258.78
Permanent Ineff=
       F       F
Bank Sta=4985.5,5022.1
XS Rating Curve= 0 ,0
Exp/Cntr=0.3,0.1

Type RM Length L Ch R = 1 ,5552    ,1392,1392,1392
BEGIN DESCRIPTION:
Mapping XS 1f197c6e
END DESCRIPTION:
XS GIS Cut Line= 4
      3799083.18     10483588.78      3799083.18     10484866.53
      3799708.18     10485317.92      3801616.23     10484624.08
#Sta/Elev= 30
  3201.5  289.56  3372.9  287.65  3542.9  280.06  3822.9  258.17  3952.9  249.19
  4312.9  241.12  4772.2  241.65  4980.6  244.83  4985.1  238.46  4987.8  237.96
  4991.1  238.46  4994.2  243.21  5002.8  239.96  5017.5   244.5  5239.5  242.83
    5273  240.49  5294.3  243.35  5358.1  241.75  5453.9  244.74  5731.1  244.54
  5812.3  242.08  5858.3  244.82  5929.3  243.28  6177.5  246.41  6773.3  250.58
  6890.4  255.47  7013.3  264.88  7099.8  268.05  7105.1  265.81  7280.5  276.66
#Mann= 5 ,-1 , 0
  3201.5     .05       0  3822.9     .12       0  4985.1     .07       0
  4991.1     .12       0  6177.5     .05       0
Bank Sta=4980.6,5017.5
XS Rating Curve= 0 ,0
Exp/Cntr=0.3,0.1

Type RM Length L Ch R = 1 ,4160    ,1397,1397,1397
BEGIN DESCRIPTION:
Mapping XS d2c7c66e
END DESCRIPTION:
XS GIS Cut Line= 5
      3797708.19     10483595.71      3798937.35     10485366.53
      3799194.29     10485692.92      3799597.07     10485706.81
      3801520.66     10484748.49
#Sta/Elev= 30
  3065.8  297.29  3393.3  291.76  3558.2  271.77  3766.1  253.62  3903.2  248.81
  4708.3  240.66  4815.7  239.19  4860.2  236.41  4881.2  239.51  4982.4  240.88
  4988.6  235.91  5003.4  238.67  5006.5  235.72  5009.2  235.22  5012.5  235.72
  5018.3  239.82  5024.4  238.41  5031.1  240.73  5039.2  240.32  5962.3     240
  5982.3  238.08  5990.1  239.61  6202.5  241.12  6739.8  242.45  6762.2  244.38
  6806.9  242.38  7159.5  244.46  7769.5  247.99  7964.3  256.13  8188.9   274.7
#Mann= 5 ,-1 , 0
  3065.8     .05       0  3766.1     .16       0  5006.5     .07       0
  5012.5     .16       0  7159.5     .05       0
Bank Sta=4982.4,5039.2
XS Rating Curve= 0 ,0
Exp/Cntr=0.3,0.1

Type RM Length L Ch R = 1 ,2763    ,1400,1400,1400
BEGIN DESCRIPTION:
Mapping XS f21bfebd
END DESCRIPTION:
XS GIS Cut Line= 4
      3797333.17     10483560.95      3798145.68      10485658.2
      3799513.74     10485901.25      3801631.82     10484769.29
#Sta/Elev= 30
  2917.3  292.62  3060.5  293.67  3223.9  276.32  3283.8   275.5  3526.3  261.27
  3804.2  245.61    4052  240.05  4885.5  235.56  4975.5  237.78  4983.3  230.89
    4986  230.39  4989.3  230.89  4999.9  232.24  5007.7  236.93  6541.6  239.21
  6574.2  237.03  6766.7  241.61  7204.2  242.39  7264.4  245.54  7270.1   242.4
  7787.1  243.17    8320  245.73  8475.7  250.77  8625.5  250.32  8711.4  254.16
  8727.7   255.9  8733.4  259.21  8760.1  260.63  8859.4   264.6  8957.5  274.41
#Mann= 7 ,-1 , 0
  2917.3     .05       0  3526.3     .16       0  4983.3     .07       0
  4989.3     .16       0  7787.1     .05       0  8625.5     .16       0
  8760.1     .05       0
#XS Ineff= 2 , 0
         4947.16  250.32 5038.64          250.85
Permanent Ineff=
       F       F
Bank Sta=4975.5,5007.7
XS Rating Curve= 0 ,0
Exp/Cntr=0.3,0.1

Type RM Length L Ch R = 1 ,1363    ,963,963,963
BEGIN DESCRIPTION:
Mapping XS 84d0ec4b
END DESCRIPTION:
XS GIS Cut Line= 5
      3796979.01      10483519.3      3796951.24     10485317.92
      3797715.12     10485949.86      3799749.85     10486047.09
       3801755.2     10484735.62
#Sta/Elev= 30
  2803.3   281.3  2914.2  271.47  3014.2  273.72  3083.9  259.62  3134.2  253.84
  3144.2  255.88  3184.2  252.29  3234.2  253.42  3394.3  243.83  3554.3  237.77
  3784.3  234.21  4244.4  231.06  4978.6   234.7  4986.5  234.04  5000.6  226.31
  5003.8  226.81  5004.8  228.63  5007.3  233.17  5015.1  234.43  7686.5   237.4
  7888.5  242.12  8105.7   239.6  9173.2  244.37    9612  248.88  9752.3  255.47
  9773.4  259.62  9816.9  260.78    9873  267.34  9939.2  275.93 10026.7  278.63
#Mann= 7 ,-1 , 0
  2803.3     .05       0  3394.3     .16       0  5003.8     .12       0
  5004.8     .16       0  9173.2     .05       0    9612     .16       0
    9873     .05       0
#XS Ineff= 2 , 0
         4955.68  242.09 5027.27          243.33
Permanent Ineff=
       F       F
Bank Sta=4978.6,5015.1
XS Rating Curve= 0 ,0
Exp/Cntr=0.3,0.1

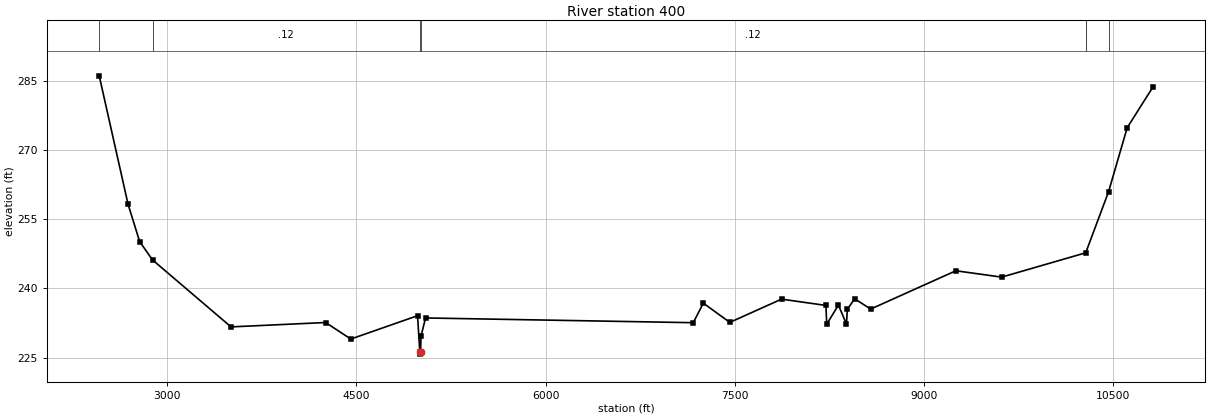
Type RM Length L Ch R = 1 ,400     ,0,0,0
BEGIN DESCRIPTION:
UNT047 IN BECR 1.0
END DESCRIPTION:
XS GIS Cut Line= 6
      3796860.95     10483547.13      3796458.18     10485366.53
      3797062.35     10486151.25      3797916.51     10486442.92
      3799687.35     10486435.97      3801888.67     10484665.19
#Sta/Elev= 30
  2460.3  286.13  2688.8  258.28  2780.9  250.16  2883.4  246.17  3505.2  231.65
  4255.8   232.6    4455  229.01  4984.1  234.08    5002  226.24  5004.7  225.74
    5008  226.24  5011.3  229.64  5047.7  233.59  7169.8  232.56  7249.8   236.8
  7459.8  232.63  7869.8  237.67  8221.5  236.31    8228  232.24  8320.8  236.38
  8384.8  232.24  8391.2  235.43  8448.8  237.75  8576.7  235.52  9251.9  243.83
    9615  242.45 10281.5  247.73 10462.5  260.98 10610.1  274.87 10812.7  283.64
#Mann= 7 ,-1 , 0
  2460.3     .05       0  2883.4     .12       0    5002     .07       0
    5008     .12       0 10281.5     .05       0 10281.5     .16       0
 10462.5     .05       0
Bank Sta=5002,5008
XS Rating Curve= 0 ,0
Exp/Cntr=0.3,0.1

Chan Stop Cuts=-1
Use User Specified Reach Order=0
Composite Channel Slope=5