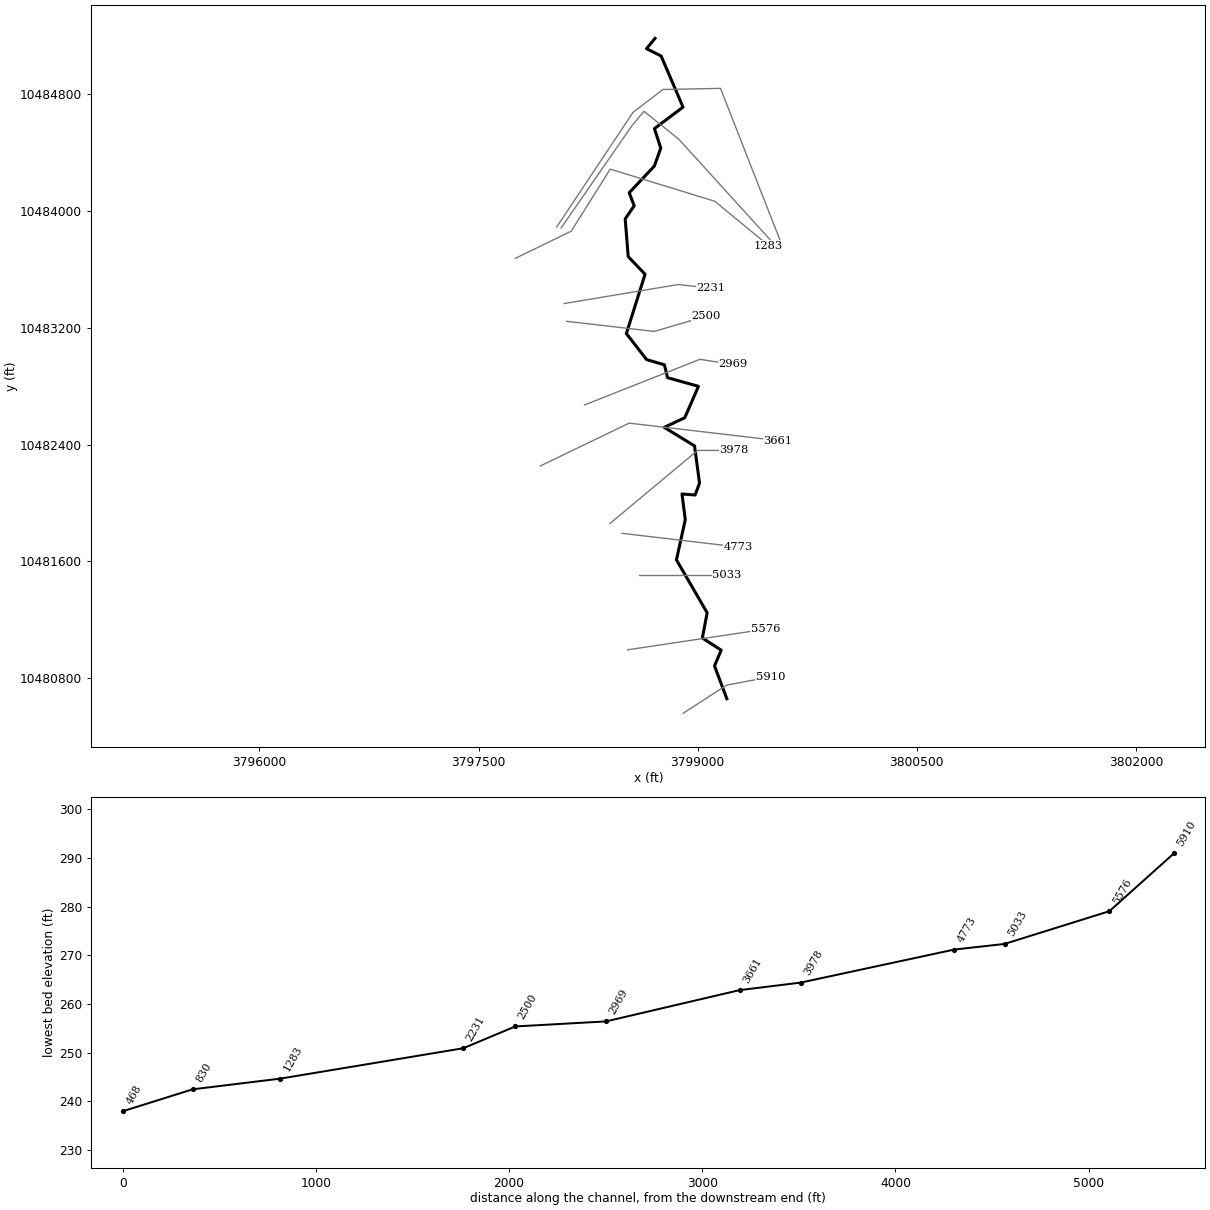
--- UNT048 IN BECR.prj (project) ---

Proj Title=UNT048 IN BECR Base Level Engineering
Current Plan=p01
Default Exp/Contr=0.3,0.1
English Units
Geom File=g01
Flow File=f01
Plan File=p01
Y Axis Title=Elevation
X Axis Title(PF)=Main Channel Distance
X Axis Title(XS)=Station
BEGIN DESCRIPTION:
UNT048 IN BECR
END DESCRIPTION:
DSS Export Rating Curves= 0
DSS Export Rating Curve Sorted= 0
DSS Export Volume Flow Curves= 0
DXF OffsetX= 0
DXF OffsetY= 0
DXF ScaleX= 1
DXF ScaleY= 10

--- UNT048 IN BECR.p01 (plan) ---

Plan Title=Multiple Run
Short Identifier=Multiple
Geom File=g01
Flow File=f01
Subcritical Flow
K Sum by GR= 0
Std Step Tol= 0.01
Critical Tol= 0.01
Num of Std Step Trials= 20
Max Error Tol= 0.3
Flow Tol Ratio= 0.001
Split Flow NTrial= 30
Split Flow Tol= 0.02
Split Flow Ratio= 0.02
Log Output Level= 0
Friction Slope Method= 1
Unsteady Friction Slope Method= 2
Unsteady Bridges Friction Slope Method= 1
Parabolic Critical Depth
Global Vel Dist=  1 , 1 , 1
Global Log Level= 0
CheckData=True
Encroach Param= -1, 0, 0, 0
BEGIN DESCRIPTION:
Multiple Run
END DESCRIPTION:

--- UNT048 IN BECR.f01 (steady flow) ---

Flow Title=Multiple
Program Version=4.10
Number of Profiles= 7
Profile Names=10-year,25-year,50-year,1pct_min,100-year,1pct_plu,500-year
River Rch & RM=UNT048 IN BECR,Reach-1         ,5910
     280     360     424     367     496     671     682
Boundary for River Rch & Prof#=UNT048 IN BECR,Reach-1         , 1
Up Type= 0
Dn Type= 3
Dn Slope=0.005
Boundary for River Rch & Prof#=UNT048 IN BECR,Reach-1         , 2
Up Type= 0
Dn Type= 3
Dn Slope=0.005
Boundary for River Rch & Prof#=UNT048 IN BECR,Reach-1         , 3
Up Type= 0
Dn Type= 3
Dn Slope=0.005
Boundary for River Rch & Prof#=UNT048 IN BECR,Reach-1         , 4
Up Type= 0
Dn Type= 3
Dn Slope=0.005
Boundary for River Rch & Prof#=UNT048 IN BECR,Reach-1         , 5
Up Type= 0
Dn Type= 3
Dn Slope=0.005
Boundary for River Rch & Prof#=UNT048 IN BECR,Reach-1         , 6
Up Type= 0
Dn Type= 3
Dn Slope=0.005
Boundary for River Rch & Prof#=UNT048 IN BECR,Reach-1         , 7
Up Type= 0
Dn Type= 3
Dn Slope=0.005
DSS Import GetInterval= 0
DSS Import GetPeak= 0
DSS Import FillOption= 0

--- UNT048 IN BECR.g01 (geometry) ---

Geom Title=Existing Conditions
Program Version=4.10

River Reach=UNT048 IN BECR  ,Reach-1
Reach XY= 30
      3799199.61     10480660.19        3799115.       10480885.
        3799161.       10480993.        3799032.       10481076.
      3799064.75       10481249.       3798854.5       10481611.
        3798915.       10481886.       3798892.5       10482062.
      3798982.25       10482055.       3799012.5       10482136.
       3798978.5       10482391.        3798771.       10482518.
       3798911.5       10482584.      3799005.25       10482799.
       3798793.5       10482858.      3798772.25       10482946.
      3798650.25       10482982.      3798511.75       10483160.
      3798639.75       10483566.      3798524.25       10483687.
      3798503.75       10483945.      3798565.25       10484035.
      3798531.25       10484124.       3798703.5       10484307.
      3798747.25       10484430.      3798703.75       10484563.
      3798899.61     10484710.19      3798749.61     10485060.19
      3798649.61     10485110.19        3798708.       10485181.

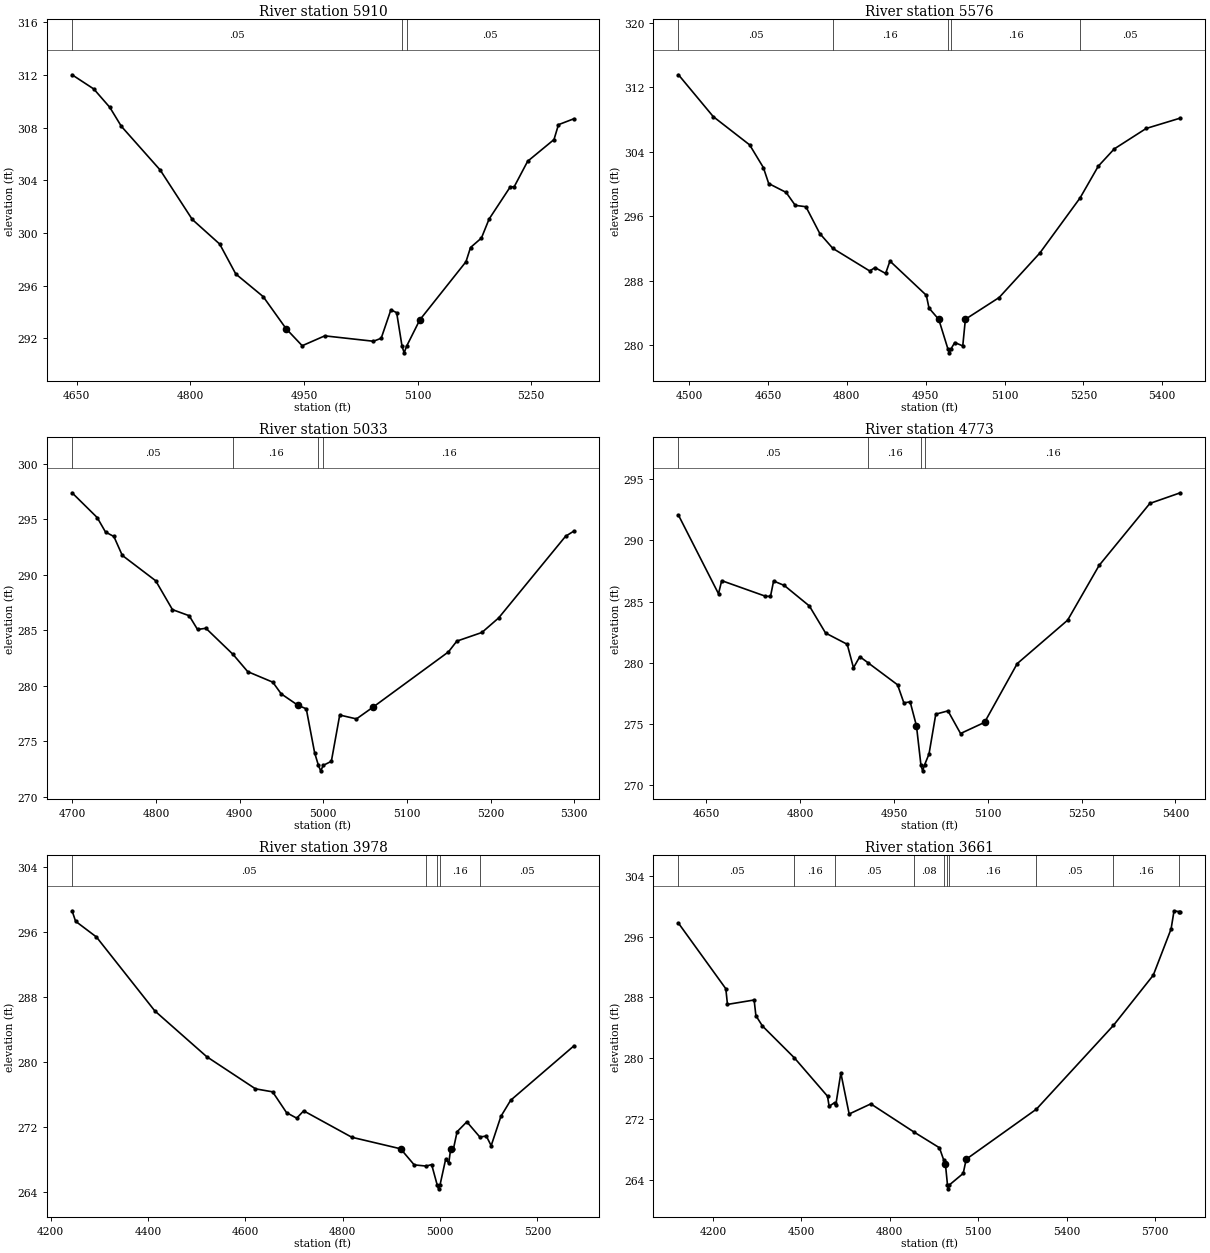
Type RM Length L Ch R = 1 ,5910    ,334,334,334
BEGIN DESCRIPTION:
UNT048 IN BECR 10.0
END DESCRIPTION:
XS GIS Cut Line= 3
      3798899.57     10480560.16       3799198.6     10480753.72
      3799499.64      10480810.2
#Sta/Elev= 30
  4643.8  312.02  4672.5  310.94  4693.7  309.54  4708.8  308.11  4760.2  304.78
  4802.5  301.03  4838.7  299.16  4859.9  296.89  4896.1  295.17  4926.4  292.73
  4947.6  291.44  4977.4  292.19  5041.7  291.78  5051.9  292.01  5064.7  294.17
  5072.3  293.95  5079.4   291.4  5082.2   290.9  5085.4   291.4  5102.8   293.4
  5163.8  297.82  5169.8   298.9  5184.2  299.62  5194.3  301.06  5222.3  303.51
  5227.4  303.51  5245.2  305.45    5280   307.1  5285.9  308.23  5306.3  308.68
#Mann= 3 ,-1 , 0
  4643.8     .05       0  5079.4     .03       0  5085.4     .05       0
Bank Sta=4926.4,5102.8
XS Rating Curve= 0 ,0
Exp/Cntr=0.3,0.1

Type RM Length L Ch R = 1 ,5576    ,543,543,543
BEGIN DESCRIPTION:
UNT048 IN BECR 9.0
END DESCRIPTION:
XS GIS Cut Line= 2
      3798519.91     10480995.28      3799463.93     10481136.34
#Sta/Elev= 30
  4479.8  313.58    4546  308.38  4615.2  304.87  4641.3  302.05  4651.4  300.07
  4684.5  298.97  4701.9  297.36  4722.2  297.19  4748.6  293.86  4773.3  292.02
  4843.5  289.21  4853.6  289.63  4873.8   288.9    4882  290.44  4951.2  286.19
  4956.3   284.6  4974.9  283.19  4992.2  279.54  4994.9  279.04  4998.2  279.54
  5005.3  280.32  5020.5   279.9  5025.5  283.21  5089.7  285.91    5167  291.43
  5243.6  298.28  5278.3  302.23  5308.6  304.37  5369.3  306.91  5434.3   308.2
#Mann= 5 ,-1 , 0
  4479.8     .05       0  4773.3     .16       0  4992.2     .07       0
  4998.2     .16       0  5243.6     .05       0
Bank Sta=4974.9,5025.5
XS Rating Curve= 0 ,0
Exp/Cntr=0.3,0.1

Type RM Length L Ch R = 1 ,5033    ,260,260,260
BEGIN DESCRIPTION:
UNT048 IN BECR 8.0
END DESCRIPTION:
XS GIS Cut Line= 3
      3798599.63     10481510.19      3798899.61     10481510.19
      3799199.63     10481510.19
#Sta/Elev= 30
  4699.6  297.38  4729.6  295.15  4739.6  293.84  4749.6  293.44  4759.6  291.74
  4799.6  289.45  4819.6  286.85  4839.6   286.3  4849.6  285.06  4859.6  285.17
  4892.1  282.81  4909.6  281.26  4939.6  280.31  4949.6  279.26  4969.6  278.23
  4979.6  277.91  4989.6  273.95  4994.1  272.82  4996.8  272.32  5000.1  272.82
  5009.6  273.18  5019.6  277.35  5039.6     277  5059.6  278.07  5149.6  283.04
  5159.6  284.01  5189.6  284.79  5209.6   286.1  5289.6  293.46  5299.6  293.93
#Mann= 4 ,-1 , 0
  4699.6     .05       0  4892.1     .16       0  4994.1     .07       0
  5000.1     .16       0
Bank Sta=4969.6,5059.6
XS Rating Curve= 0 ,0
Exp/Cntr=0.3,0.1

Type RM Length L Ch R = 1 ,4773    ,795,795,795
BEGIN DESCRIPTION:
UNT048 IN BECR 7.0
END DESCRIPTION:
XS GIS Cut Line= 2
      3798481.71     10481792.75      3799278.61     10481698.99
#Sta/Elev= 30
  4605.6  292.06  4669.6  285.64  4674.7  286.71  4744.5  285.44  4752.7  285.42
  4757.7  286.68  4774.7  286.32  4814.9  284.64  4840.8  282.43  4875.4  281.51
  4885.4  279.59  4895.5   280.5  4908.7     280  4955.9   278.2    4966  276.72
    4976  276.81  4986.1  274.85  4993.2  271.67  4995.9  271.17  4999.2  271.67
  5006.2  272.55    5017   275.8  5036.5  276.07  5056.6  274.22    5095  275.13
  5147.2  279.93  5227.8  283.48  5278.1  287.95  5359.3  293.02    5408  293.89
#Mann= 4 ,-1 , 0
  4605.6     .05       0  4908.7     .16       0  4993.2     .07       0
  4999.2     .16       0
Bank Sta=4986.1,5095
XS Rating Curve= 0 ,0
Exp/Cntr=0.3,0.1

Type RM Length L Ch R = 1 ,3978    ,317,317,317
BEGIN DESCRIPTION:
UNT048 IN BECR 6.0
END DESCRIPTION:
XS GIS Cut Line= 3
      3798399.61     10481860.19      3798999.61     10482360.19
      3799249.58     10482360.19
#Sta/Elev= 30
  4244.2  298.62  4251.4  297.33  4294.3  295.39  4414.1   286.3  4520.8  280.66
    4621   276.7  4656.2  276.33  4684.8  273.77  4705.7  273.09    4720  273.99
  4818.9  270.74  4919.1  269.32  4947.1  267.34    4972  267.19  4982.9  267.38
  4994.2  264.89    4997  264.39  5000.2  264.89  5011.6  268.01  5018.1  267.57
    5022  269.31  5027.7  269.31  5035.2  271.42  5055.2  272.64  5081.9  270.77
  5095.2  270.89  5105.2   269.7  5125.2  273.31  5145.2  275.29  5275.2  281.99
#Mann= 5 ,-1 , 0
  4244.2     .05       0    4972     .16       0  4994.2     .07       0
  5000.2     .16       0  5081.9     .05       0
Bank Sta=4919.1,5022
XS Rating Curve= 0 ,0
Exp/Cntr=0.3,0.1

Type RM Length L Ch R = 1 ,3661    ,692,692,692
BEGIN DESCRIPTION:
UNT048 IN BECR 5.0
END DESCRIPTION:
XS GIS Cut Line= 3
      3797923.12     10482253.97      3798530.73     10482546.93
      3799550.73     10482427.57
#Sta/Elev= 30
  4083.4  297.77  4243.9  289.15  4249.5  287.09  4339.9  287.67  4345.9  285.61
  4368.1  284.25  4476.4  280.06  4588.7  275.02  4594.2  273.69  4612.4  274.17
  4616.9   273.9  4633.9  278.07  4662.1  272.68  4735.5  274.01  4882.3   270.3
  4968.2  268.24  4982.3  266.67  4988.4   266.1  4995.5  263.34  4998.2  262.84
  5001.5  263.34  5048.8  264.87  5058.9  266.73  5296.8  273.31  5557.9  284.32
  5693.2  290.93  5753.6  297.01  5763.6   299.4    5782  299.27  5784.9  299.27
#Mann= 10 ,-1 , 0
  4083.4     .05       0  4476.4     .16       0  4612.4     .05       0
  4882.3     .08       0  4982.3     .16       0  4995.5     .07       0
  5001.5     .16       0  5296.8     .05       0  5557.9     .16       0
    5782     .05       0
Bank Sta=4988.4,5058.9
XS Rating Curve= 0 ,0
Exp/Cntr=0.3,0.1

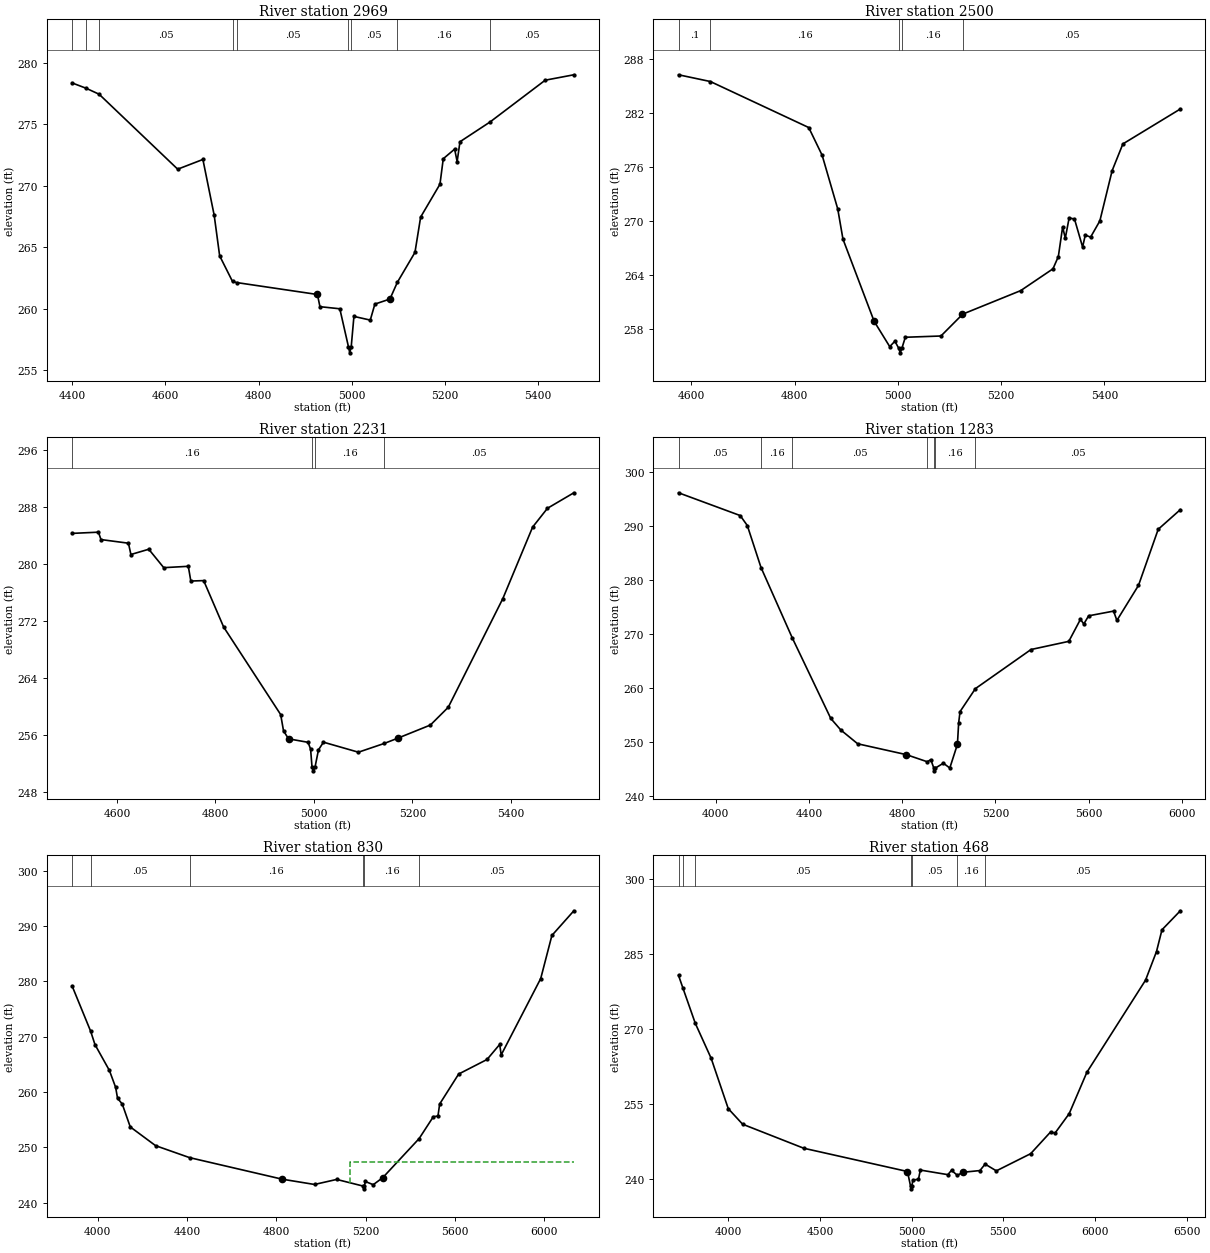
Type RM Length L Ch R = 1 ,2969    ,469,469,469
BEGIN DESCRIPTION:
UNT048 IN BECR 4.0
END DESCRIPTION:
XS GIS Cut Line= 3
       3798224.8     10482671.23       3799014.7     10482983.72
      3799240.38       10482949.
#Sta/Elev= 30
  4399.5  278.35    4430  277.91  4457.6  277.43  4626.4  271.34  4680.5  272.13
  4704.8  267.59  4716.5   264.3  4744.1  262.22  4752.9  262.13  4926.5  261.16
  4931.9  260.17  4974.6     260  4993.1  256.92  4995.9  256.42  4999.1  256.92
  5004.9  259.38    5040  259.08  5049.9  260.38  5082.2  260.79  5098.2  262.15
    5136  264.58  5148.2  267.45  5189.7  270.12  5196.8  272.19  5221.2  272.97
  5226.6  271.96  5232.7  273.57  5297.1  275.17  5415.8  278.57  5477.3  279.01
#Mann= 9 ,-1 , 0
  4399.5     .05       0    4430      .1       0  4457.6     .05       0
  4744.1     .08       0  4752.9     .05       0  4993.1     .03       0
  4999.1     .05       0  5098.2     .16       0  5297.1     .05       0
Bank Sta=4926.5,5082.2
XS Rating Curve= 0 ,0
Exp/Cntr=0.3,0.1

Type RM Length L Ch R = 1 ,2500    ,269,269,269
BEGIN DESCRIPTION:
UNT048 IN BECR 3.0
END DESCRIPTION:
XS GIS Cut Line= 3
      3798103.25     10483244.13       3798702.2     10483174.69
      3799056.38     10483278.36
#Sta/Elev= 30
  4574.9  286.27  4636.6  285.52  4827.1  280.41  4853.1  277.33  4883.3  271.37
  4893.4  268.02  4953.8  258.89    4984  256.08    4994  256.68  5001.5  255.89
  5004.3  255.39  5007.5  255.89  5014.2  257.12  5083.2  257.26  5124.9  259.66
  5126.7  259.72  5237.7   262.3  5300.2  264.72  5310.6  266.08  5318.9  269.36
  5324.1  268.13  5331.5  270.37  5341.9  270.25  5357.6  267.14  5362.8  268.47
  5373.1  268.24    5391  270.04  5414.8  275.62  5435.6  278.59  5546.9  282.47
#Mann= 5 ,-1 , 0
  4574.9      .1       0  4636.6     .16       0  5001.5     .07       0
  5007.5     .16       0  5126.7     .05       0
Bank Sta=4953.8,5124.9
XS Rating Curve= 0 ,0
Exp/Cntr=0.3,0.1

Type RM Length L Ch R = 1 ,2231    ,948,948,948
BEGIN DESCRIPTION:
UNT048 IN BECR 2.0
END DESCRIPTION:
XS GIS Cut Line= 3
      3798085.92     10483365.67      3798867.13     10483495.87
      3799092.85     10483469.83
#Sta/Elev= 30
  4508.7  284.31  4562.3  284.48  4567.4  283.44  4623.2  282.93  4628.2  281.34
  4664.5  282.08  4694.9  279.49  4744.8  279.68  4749.9  277.61    4776  277.67
  4816.6  271.14  4932.4  258.83  4938.2  256.54  4948.4  255.42  4988.1  254.93
  4993.2  253.96  4996.1  251.42  4998.8  250.92  5002.1  251.42  5009.2  253.87
  5019.3  254.95  5090.3  253.54  5142.7  254.77  5170.6  255.52  5236.5  257.36
  5272.8  259.86  5383.7  275.15  5444.1  285.19  5474.3  287.84  5527.9  290.02
#Mann= 4 ,-1 , 0
  4508.7     .16       0  4996.1     .07       0  5002.1     .16       0
  5142.7     .05       0
Bank Sta=4948.4,5170.6
XS Rating Curve= 0 ,0
Exp/Cntr=0.3,0.1

Type RM Length L Ch R = 1 ,1283    ,453,453,453
BEGIN DESCRIPTION:
UNT048 IN BECR 1.0
END DESCRIPTION:
XS GIS Cut Line= 5
      3797751.78     10483674.99       3798134.4     10483861.02
      3798401.09     10484285.58      3799116.67     10484066.02
      3799485.09     10483762.61
#Sta/Elev= 30
  3840.7  296.07  4105.2  291.86  4135.7  290.02  4194.5  282.26  4328.2  269.29
  4493.8  254.36  4536.8  252.23  4609.2  249.68  4818.3  247.67  4907.6  246.36
  4922.9  246.75  4935.9  245.18  4938.7  244.68  4941.9  245.18  4976.9  246.09
  5004.4   245.2  5037.1  249.58  5042.4  253.56  5048.4  255.63  5114.1  259.87
  5352.7   267.1  5514.9  268.61  5564.9  272.68  5579.2  271.82    5600  273.33
  5706.9   274.2  5721.2  272.48  5813.8  278.95  5898.4  289.32  5993.3  292.95
#Mann= 7 ,-1 , 0
  3840.7     .05       0  4194.5     .16       0  4328.2     .05       0
  4907.6     .16       0  4935.9     .07       0  4941.9     .16       0
  5114.1     .05       0
Bank Sta=4818.3,5037.1
XS Rating Curve= 0 ,0
Exp/Cntr=0.3,0.1

Type RM Length L Ch R = 1 ,830     ,362,362,362
BEGIN DESCRIPTION:
Mapping XS 71c8df96
END DESCRIPTION:
XS GIS Cut Line= 5
      3798064.97     10483882.74       3798548.9     10484581.51
      3798631.94     10484681.48      3798870.66     10484490.51
      3799517.38     10483778.68
#Sta/Elev= 30
    3885  279.16  3968.3  270.96  3987.5  268.56  4052.2  263.88  4080.1  260.83
  4088.7  258.85  4109.8  257.81  4145.6  253.68  4259.1  250.29  4411.2  248.13
  4826.5  244.23  4970.9  243.28  5070.2  244.19  5188.4  242.99  5191.1  242.49
  5194.4  242.99  5198.1  243.82  5233.9  243.24  5276.5  244.51  5439.4  251.57
  5502.9  255.52  5523.8  255.65  5531.3  257.81  5616.4  263.23  5743.5  265.86
  5800.2  268.58    5807  266.69    5984  280.49    6034  288.27  6132.4  292.73
#Mann= 6 ,-1 , 0
    3885     .16       0  3968.3     .05       0  4411.2     .16       0
  5188.4     .03       0  5194.4     .16       0  5439.4     .05       0
#XS Ineff= 2 , 0
                         5127.84           247.3
Permanent Ineff=
       F       F
Bank Sta=4826.5,5276.5
XS Rating Curve= 0 ,0
Exp/Cntr=0.3,0.1

Type RM Length L Ch R = 1 ,468     ,0,0,0
BEGIN DESCRIPTION:
Mapping XS 84ed52b5
END DESCRIPTION:
XS GIS Cut Line= 5
      3798034.59     10483889.26      3798557.15     10484673.96
      3798762.12      10484830.9      3799156.05     10484838.39
      3799572.71      10483775.9
#Sta/Elev= 30
  3728.9  280.73  3751.8   278.3  3820.3  271.13  3906.8  264.13    4000  254.05
  4078.4  250.93  4411.7  246.12  4977.3  241.46  4994.3  238.49  4997.1  237.99
  5000.3  238.49  5007.3  239.76  5037.3   239.9  5047.3  241.75  5197.4  240.83
  5217.4   241.7  5249.8  240.68  5277.4   241.3  5372.4  241.65  5400.6  242.94
  5461.9  241.59    5649  245.03  5757.5  249.37    5782  249.16    5859  253.04
  5955.6  261.33  6275.5  279.78  6335.2  285.51    6365  289.86  6465.1  293.67
#Mann= 7 ,-1 , 0
  3728.9     .05       0  3751.8     .16       0  3820.3     .05       0
  4994.3     .03       0  5000.3     .05       0  5249.8     .16       0
  5400.6     .05       0
Bank Sta=4977.3,5277.4
XS Rating Curve= 0 ,0
Exp/Cntr=0.3,0.1

Chan Stop Cuts=-1
Use User Specified Reach Order=0
Composite Channel Slope=5