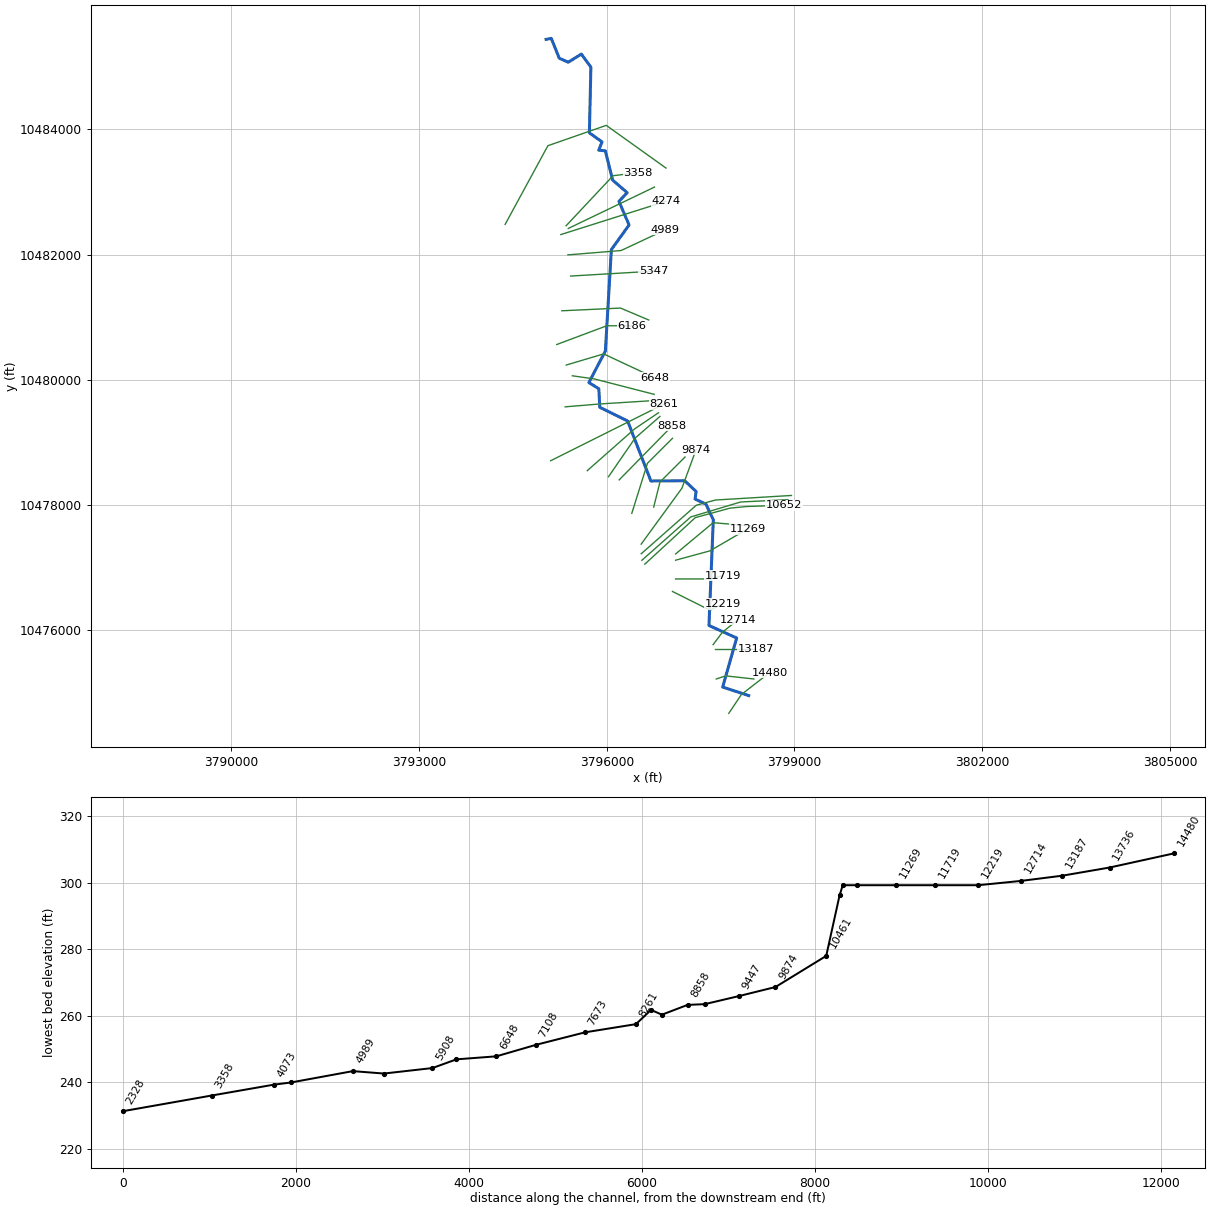
--- UNT049 IN BECR.prj (project) ---

Proj Title=UNT049 IN BECR Base Level Engineering
Current Plan=p01
Default Exp/Contr=0.3,0.1
English Units
Geom File=g01
Flow File=f01
Plan File=p01
Y Axis Title=Elevation
X Axis Title(PF)=Main Channel Distance
X Axis Title(XS)=Station
BEGIN DESCRIPTION:
UNT049 IN BECR
END DESCRIPTION:
DSS Export Rating Curves= 0
DSS Export Rating Curve Sorted= 0
DSS Export Volume Flow Curves= 0
DXF OffsetX= 0
DXF OffsetY= 0
DXF ScaleX= 1
DXF ScaleY= 10

--- UNT049 IN BECR.p01 (plan) ---

Plan Title=Multiple Run
Short Identifier=Multiple
Geom File=g01
Flow File=f01
Subcritical Flow
K Sum by GR= 0
Std Step Tol= 0.01
Critical Tol= 0.01
Num of Std Step Trials= 20
Max Error Tol= 0.3
Flow Tol Ratio= 0.001
Split Flow NTrial= 30
Split Flow Tol= 0.02
Split Flow Ratio= 0.02
Log Output Level= 0
Friction Slope Method= 1
Unsteady Friction Slope Method= 2
Unsteady Bridges Friction Slope Method= 1
Parabolic Critical Depth
Global Vel Dist=  1 , 1 , 1
Global Log Level= 0
CheckData=True
Encroach Param= -1, 0, 0, 0
BEGIN DESCRIPTION:
Multiple Run
END DESCRIPTION:

--- UNT049 IN BECR.f01 (steady flow) ---

Flow Title=Multiple
Number of Profiles=7
Profile Names=10-year,25-year,50-year,1pct_min,100-year,1pct_plu,500-year
River Rch & RM= UNT049 IN BECR,Reach-1,14480
     401     528     631     556     752    1016    1067
River Rch & RM= UNT049 IN BECR,Reach-1,10811
     564     761     925     826    1117    1511    1636
River Rch & RM= UNT049 IN BECR,Reach-1,9874
     817    1120    1372    1235    1670    2259    2483
Boundary for River Rch & Prof#=UNT049 IN BECR,Reach-1,1
Up Type=0
Dn Type=3
Dn Slope=0.005
Boundary for River Rch & Prof#=UNT049 IN BECR,Reach-1,2
Up Type=0
Dn Type=3
Dn Slope=0.005
Boundary for River Rch & Prof#=UNT049 IN BECR,Reach-1,3
Up Type=0
Dn Type=3
Dn Slope=0.005
Boundary for River Rch & Prof#=UNT049 IN BECR,Reach-1,4
Up Type=0
Dn Type=3
Dn Slope=0.005
Boundary for River Rch & Prof#=UNT049 IN BECR,Reach-1,5
Up Type=0
Dn Type=3
Dn Slope=0.005
Boundary for River Rch & Prof#=UNT049 IN BECR,Reach-1,6
Up Type=0
Dn Type=3
Dn Slope=0.005
Boundary for River Rch & Prof#=UNT049 IN BECR,Reach-1,7
Up Type=0
Dn Type=3
Dn Slope=0.005

--- UNT049 IN BECR.g01 (geometry) ---

Geom Title=Existing Conditions
Program Version=4.10

River Reach=UNT049 IN BECR  ,Reach-1
Reach XY= 30
      3798267.46       10474945.        3797852.       10475081.
       3798075.5       10475866.      3797632.75       10476066.
       3797702.5       10477757.        3797584.       10478008.
      3797410.25       10478088.      3797428.25       10478209.
      3797244.75       10478381.       3796704.5       10478377.
      3796332.75       10479337.        3795888.       10479556.
      3795872.25       10479853.       3795713.5       10479952.
        3795977.       10480456.        3796073.       10482079.
        3796356.       10482472.      3796193.75       10482851.
      3796325.75       10482989.        3796093.       10483191.
        3795976.       10483659.       3795870.5       10483669.
      3795923.25       10483802.      3795721.75       10483946.
       3795745.5       10484997.      3795593.25       10485206.
      3795383.75       10485076.       3795239.5       10485140.
        3795112.       10485458.       3795029.5       10485441.

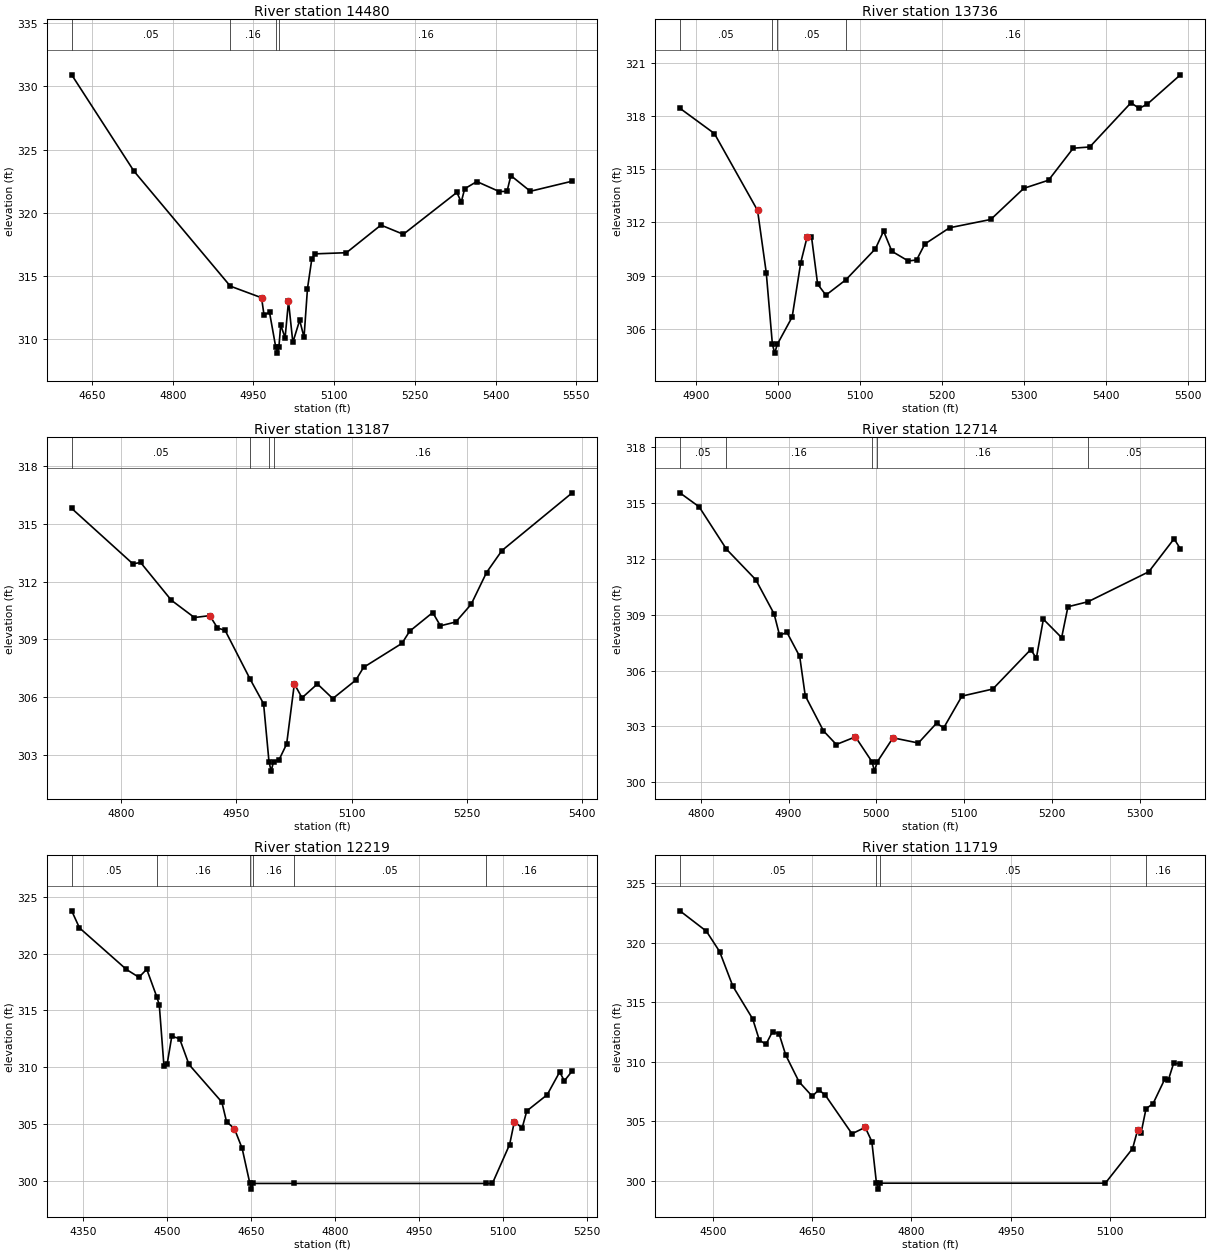
Type RM Length L Ch R = 1 ,14480   ,744,744,744
BEGIN DESCRIPTION:
UNT049 IN BECR 25.0
END DESCRIPTION:
XS GIS Cut Line= 3
      3797949.61     10474660.19      3798149.61     10474960.19
      3798599.57     10475310.16
#Sta/Elev= 30
    4612  330.92  4727.7  323.29  4906.9  314.17    4965  313.25  4969.6  311.88
  4979.8   312.1  4991.3  309.36    4994  308.86  4997.3  309.36  5000.6  311.09
  5008.8  310.08  5015.1  312.97  5023.2  309.71  5035.9  311.47    5044  310.11
  5050.4  313.98  5058.5  316.33  5064.9  316.73  5122.8  316.82    5187  319.01
  5228.6  318.28  5328.2   321.6  5336.3  320.83  5342.7  321.89  5365.3  322.46
  5406.9  321.67  5421.4  321.68  5428.6  322.93  5464.8  321.69  5542.6  322.49
#Mann= 4 ,-1 , 0
    4612     .05       0  4906.9     .16       0  4991.3     .07       0
  4997.3     .16       0
Bank Sta=4965,5015.1
XS Rating Curve= 0 ,0
Exp/Cntr=0.3,0.1

Type RM Length L Ch R = 1 ,13736   ,549,549,549
BEGIN DESCRIPTION:
UNT049 IN BECR 24.0
END DESCRIPTION:
XS GIS Cut Line= 3
      3797749.65      10475210.2      3797899.61     10475260.19
      3798349.57     10475210.19
#Sta/Elev= 30
  4879.9  318.46    4922  317.03  4974.7  312.68  4985.3  309.16  4992.8  305.11
  4995.6  304.61  4998.8  305.11  5016.9  306.65  5027.4  309.73  5035.3   311.2
  5040.5   311.2    5048  308.51  5058.1  307.89  5082.5  308.76  5118.5  310.51
  5128.5  311.51  5138.6  310.37  5158.7  309.82  5168.8  309.88  5178.8  310.78
    5209   311.7  5259.3  312.17  5299.6  313.93  5329.8  314.39  5359.9   316.2
  5380.1  316.27  5430.4  318.77  5440.4  318.45  5450.5   318.7  5490.7  320.35
#Mann= 4 ,-1 , 0
  4879.9     .05       0  4992.8     .03       0  4998.8     .05       0
  5082.5     .16       0
Bank Sta=4974.7,5035.3
XS Rating Curve= 0 ,0
Exp/Cntr=0.3,0.1

Type RM Length L Ch R = 1 ,13187   ,473,473,473
BEGIN DESCRIPTION:
UNT049 IN BECR 23.0
END DESCRIPTION:
XS GIS Cut Line= 2
        3797730.     10475683.37        3798381.     10475683.37
#Sta/Elev= 30
    4736   315.8  4815.6  312.92  4825.6  312.99  4865.6  311.03  4895.6  310.13
  4915.6  310.23  4925.6  309.59  4935.6  309.46  4968.2  306.92  4985.6  305.65
  4992.6  302.65  4995.4  302.15  4998.6  302.65  5005.6  302.73  5015.6  303.56
  5025.6  306.68  5035.6  305.96  5055.6  306.68  5075.6  305.92  5105.6  306.88
  5115.6  307.54  5165.6  308.79  5175.6  309.42  5205.6  310.39  5215.6   309.7
  5235.6   309.9  5255.6  310.82  5275.6  312.47  5295.6  313.61    5387  316.61
#Mann= 4 ,-1 , 0
    4736     .05       0  4968.2     .16       0  4992.6     .07       0
  4998.6     .16       0
Bank Sta=4915.6,5025.6
XS Rating Curve= 0 ,0
Exp/Cntr=0.3,0.1

Type RM Length L Ch R = 1 ,12714   ,495,495,495
BEGIN DESCRIPTION:
UNT049 IN BECR 22.0
END DESCRIPTION:
XS GIS Cut Line= 3
      3797699.58     10475760.15      3797849.61     10475960.19
      3798099.61     10476160.19
#Sta/Elev= 30
  4776.2  315.55  4798.1   314.8  4829.3  312.52  4862.7  310.88  4883.5  309.05
  4889.8  307.89  4898.1  308.06  4912.7  306.76    4919  304.65  4939.8  302.76
  4954.4  302.03  4976.2  302.44  4995.1   301.1  4997.9   300.6  5001.1   301.1
    5019  302.39  5047.9  302.11  5068.7  303.18  5076.7  302.92  5097.5  304.63
  5132.7  305.01  5175.9  307.13  5182.3  306.67  5190.3  308.76  5211.1  307.77
  5218.3  309.43  5241.2   309.7  5310.4  311.31  5339.2  313.08  5346.4  312.54
#Mann= 5 ,-1 , 0
  4776.2     .05       0  4829.3     .16       0  4995.1     .07       0
  5001.1     .16       0  5241.2     .05       0
Bank Sta=4976.2,5019
XS Rating Curve= 0 ,0
Exp/Cntr=0.3,0.1

Type RM Length L Ch R = 1 ,12219   ,500,500,500
BEGIN DESCRIPTION:
UNT049 IN BECR 21.0
END DESCRIPTION:
XS GIS Cut Line= 3
      3797049.64     10476610.17      3797649.61     10476310.19
      3797849.61     10476410.19
#Sta/Elev= 30
  4329.2  323.75  4343.1  322.25    4427   318.6  4449.4  317.91  4463.3  318.62
  4481.3  316.19  4485.7  315.49  4494.1  310.09  4499.7  310.27  4508.1  312.73
    4522  312.52  4538.8  310.25  4597.5  306.95  4605.9  305.22  4619.9  304.62
  4633.8  302.88  4647.6   299.8  4650.4   299.3  4653.6   299.8  4726.1   299.8
  5070.2   299.8    5081   299.8  5111.8  303.22  5120.2  305.22  5134.2  304.68
  5142.5  306.17  5178.9  307.59  5201.2  309.59  5209.6  308.81  5223.6  309.68
#Mann= 6 ,-1 , 0
  4329.2     .05       0  4481.3     .16       0  4647.6    .033       0
  4653.6     .16       0  4726.1     .05       0  5070.2     .16       0
Bank Sta=4619.9,5120.2
XS Rating Curve= 0 ,0
Exp/Cntr=0.3,0.1

Type RM Length L Ch R = 1 ,11719   ,450,450,450
BEGIN DESCRIPTION:
UNT049 IN BECR 20.0
END DESCRIPTION:
XS GIS Cut Line= 3
       3797099.6     10476810.19      3797649.61     10476810.19
      3797849.64      10476860.2
#Sta/Elev= 30
  4450.1  322.68  4490.1  320.97  4510.1  319.26  4530.1  316.35  4560.1   313.6
  4570.1  311.83  4580.1  311.46  4590.1  312.54  4600.1  312.32  4610.1  310.55
  4630.1  308.32  4650.1   307.1  4660.1  307.65  4670.1  307.17  4710.1  303.95
  4730.1  304.49  4740.1   303.3  4747.1   299.8  4749.9   299.3  4753.1   299.8
  5092.9   299.8  5134.1  302.71  5141.8  304.29    5147  304.05  5154.4  306.06
    5165  306.48  5183.1  308.59  5188.2  308.49    5196  309.86  5206.3  309.84
#Mann= 4 ,-1 , 0
  4450.1     .05       0  4747.1    .033       0  4753.1     .05       0
  5154.4     .16       0
Bank Sta=4730.1,5141.8
XS Rating Curve= 0 ,0
Exp/Cntr=0.3,0.1

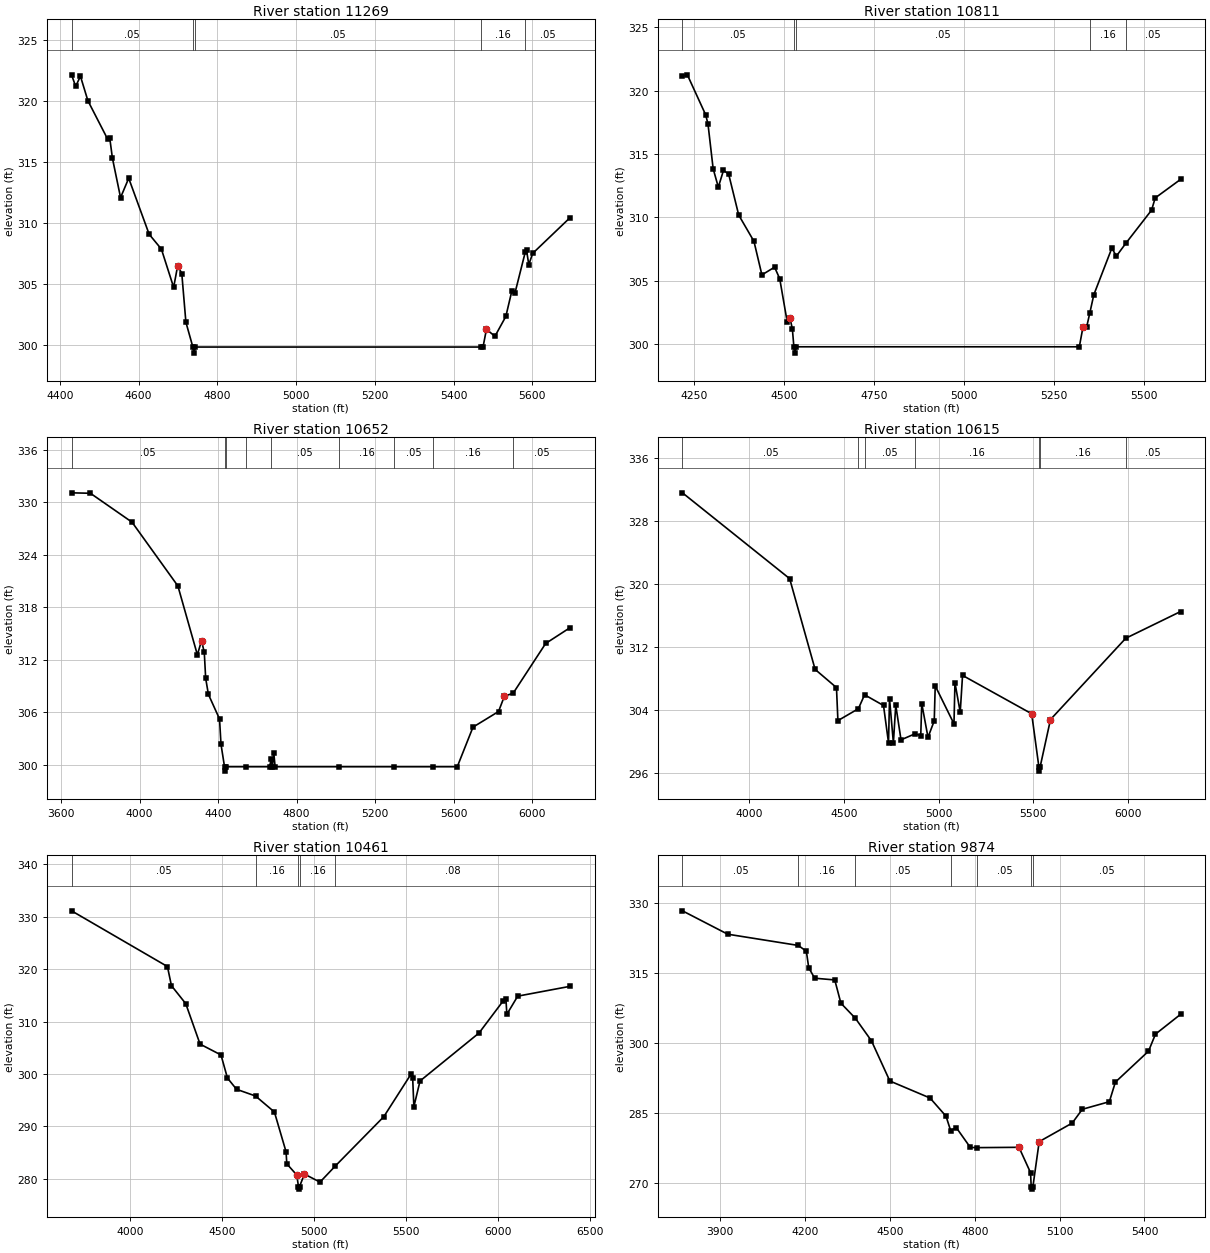
Type RM Length L Ch R = 1 ,11269   ,458,458,458
BEGIN DESCRIPTION:
UNT049 IN BECR 19.0
END DESCRIPTION:
XS GIS Cut Line= 3
      3797099.58     10477110.18      3797649.61     10477260.19
      3798249.58     10477610.17
#Sta/Elev= 30
    4430  322.15  4440.4   321.2  4452.5  322.04  4471.5  320.02  4521.6  316.87
  4526.8     317  4533.7  315.31  4554.4  312.07  4575.1  313.66    4627  309.06
  4658.1  307.84  4689.2   304.7  4699.5  306.49  4709.9  305.83  4720.3  301.84
    4738   299.8  4740.7   299.3    4744   299.8  5470.4   299.8  5474.8   299.8
  5483.5  301.26    5505  300.68  5532.7  302.31    5548  304.41  5555.8  304.22
  5582.4  307.64  5585.2  307.78    5591  306.56  5600.9  307.49  5694.7  310.39
#Mann= 5 ,-1 , 0
    4430     .05       0    4738    .033       0    4744     .05       0
  5470.4     .16       0  5582.4     .05       0
Bank Sta=4699.5,5483.5
XS Rating Curve= 0 ,0
Exp/Cntr=0.3,0.1

Type RM Length L Ch R = 1 ,10811   ,159,159,159
BEGIN DESCRIPTION:
UNT049 IN BECR 18.0
END DESCRIPTION:
XS GIS Cut Line= 3
      3797099.62      10477210.2      3797699.61     10477710.19
      3798299.62     10477660.19
#Sta/Elev= 30
  4217.5  321.18  4231.1  321.25  4281.9   318.1  4288.4  317.37  4302.7  313.85
  4317.1  312.39  4331.4  313.71  4345.7  313.43  4373.7  310.19    4416  308.12
  4438.1  305.47  4473.3  306.08  4487.6  305.17  4508.4  301.76  4516.2  302.05
  4522.7  301.21  4526.9   299.8  4529.6   299.3  4532.9   299.8  5319.6   299.8
  5329.6  301.33  5339.7  301.33  5348.9  302.49  5359.8   303.9  5409.9  307.58
  5422.5  306.95  5448.4  307.95  5520.3  310.58  5530.3  311.54  5600.6     313
#Mann= 5 ,-1 , 0
  4217.5     .05       0  4526.9    .033       0  4532.9     .05       0
  5348.9     .16       0  5448.4     .05       0
Bank Sta=4516.2,5329.6
XS Rating Curve= 0 ,0
Exp/Cntr=0.3,0.1

Type RM Length L Ch R = 1 ,10652   ,37,37,37
BEGIN DESCRIPTION:
Mapping XS 4810b373
END DESCRIPTION:
XS GIS Cut Line= 5
      3796607.57     10477046.94      3797414.84     10477791.72
      3797966.93     10477942.76      3798232.55      10477968.8
      3798831.56     10477989.64
#Sta/Elev= 30
  3653.8  331.06  3749.7  331.01  3961.8  327.71  4195.4  320.43  4294.7  312.57
  4315.7  314.19  4329.8  312.86  4336.9  309.89  4350.8  308.06  4407.5  305.25
  4414.9  302.37  4432.9   299.8  4435.6   299.3  4438.9   299.8  4541.7   299.8
  4662.7   299.8  4670.5  300.71  4676.9   299.8  4683.7   301.4  4690.6   299.8
  5014.3   299.8  5296.9   299.8  5495.5   299.8  5618.5   299.8  5698.6  304.32
  5828.6   306.1  5858.6  307.85  5903.2  308.19  6068.8  313.87  6190.8  315.64
#Mann= 9 ,-1 , 0
  3653.8     .05       0  4432.9    .033       0  4438.9     .05       0
  4541.7     .16       0  4670.5     .05       0  5014.3     .16       0
  5296.9     .05       0  5495.5     .16       0  5903.2     .05       0
Bank Sta=4315.7,5858.6
XS Rating Curve= 0 ,0
Exp/Cntr=0.3,0.1

Type RM Length L Ch R = 1 ,10615   ,154,154,154
BEGIN DESCRIPTION:
UNT049 IN BECR 17.0
END DESCRIPTION:
XS GIS Cut Line= 4
      3796560.69     10477109.43      3797341.93     10477802.14
       3798138.8     10478041.72        3798894.     10478078.18
#Sta/Elev= 30
  3646.6  331.53  4213.1  320.64  4347.7  309.12  4460.6  306.81  4468.2  302.62
  4576.3  304.13  4609.1   305.9  4709.2  304.54  4735.7   299.8  4740.9  305.42
  4761.4   299.8  4773.9  304.58  4801.7  300.18    4875  300.94    4906  300.72
  4911.3  304.79  4944.3   300.5  4977.3  302.59  4982.5  307.03  5081.6  302.21
  5086.8  307.44  5114.6  303.68  5126.9  308.36  5492.3  303.49  5530.6  296.71
  5533.4  296.21  5536.6  296.71  5591.7  302.76  5989.4  313.07  6278.9  316.46
#Mann= 7 ,-1 , 0
  3646.6     .05       0  4576.3     .16       0  4609.1     .05       0
    4875     .16       0  5530.6     .07       0  5536.6     .16       0
  5989.4     .05       0
Bank Sta=5492.3,5591.7
XS Rating Curve= 0 ,0
Exp/Cntr=0.3,0.1

Type RM Length L Ch R = 1 ,10461   ,587,587,587
BEGIN DESCRIPTION:
Mapping XS af21fe3d
END DESCRIPTION:
XS GIS Cut Line= 4
       3796550.3     10477213.63      3797430.47     10477989.64
      3797737.76     10478072.97      3798951.27     10478145.88
#Sta/Elev= 30
  3683.8  331.15  4204.9  320.52  4226.7  316.87  4304.5  313.44  4382.3  305.72
  4496.1  303.65  4531.2  299.24  4580.5   297.1  4683.7  295.82  4786.4  292.77
  4849.9  285.16  4853.8  282.88  4908.1  280.74  4917.2  278.55  4919.9  278.05
  4923.2  278.55  4949.6  280.92  5034.4  279.39  5117.2  282.45  5381.1  291.87
  5528.1  299.94  5538.1  299.26  5544.6  293.79  5578.2  298.69  5898.8  307.84
    6029  313.91  6045.1  314.26  6050.1  311.41  6109.1  314.87  6391.3  316.73
#Mann= 5 ,-1 , 0
  3683.8     .05       0  4683.7     .16       0  4917.2     .07       0
  4923.2     .16       0  5117.2     .08       0
Bank Sta=4908.1,4949.6
XS Rating Curve= 0 ,0
Exp/Cntr=0.3,0.1

Type RM Length L Ch R = 1 ,9874    ,427,427,427
BEGIN DESCRIPTION:
UNT049 IN BECR 16.0
END DESCRIPTION:
XS GIS Cut Line= 3
      3796549.44     10477367.43      3797200.46      10478261.5
      3797425.67     10478876.49
#Sta/Elev= 30
  3766.6  328.25  3926.5  323.25  4176.3  320.84  4204.6   319.6  4213.1  316.06
    4234  313.83  4305.1  313.46  4326.7  308.49  4378.1  305.24  4434.9  300.42
  4499.8  291.83  4641.9  288.19  4698.4   284.3  4714.7  281.23  4734.9  281.84
  4784.4  277.61  4809.5  277.57  4956.4  277.64  4997.3  272.21  4999.6  269.19
  5002.4  268.69  5005.6  269.19  5027.8  278.85  5144.6  282.83  5180.4  285.78
  5275.9   287.4  5297.2  291.59  5414.3  298.21    5439  301.86  5527.5  306.09
#Mann= 7 ,-1 , 0
  3766.6     .05       0  4176.3     .16       0  4378.1     .05       0
  4714.7     .08       0  4809.5     .05       0  4999.6     .03       0
  5005.6     .05       0
Bank Sta=4956.4,5027.8
XS Rating Curve= 0 ,0
Exp/Cntr=0.3,0.1

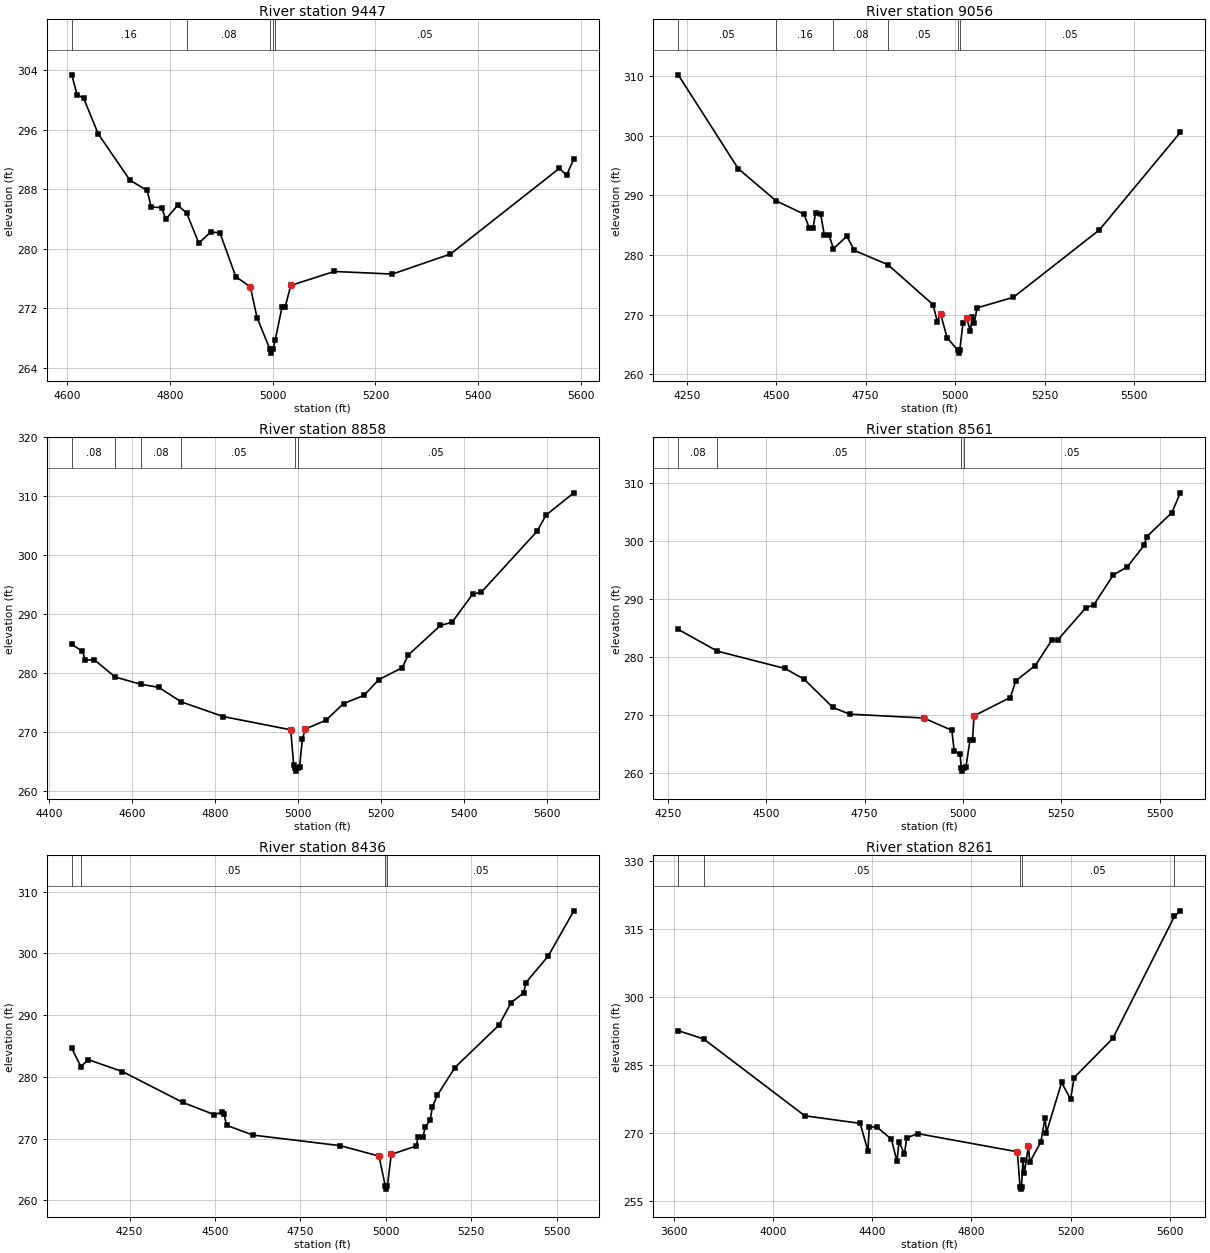
Type RM Length L Ch R = 1 ,9447    ,391,391,391
BEGIN DESCRIPTION:
UNT049 IN BECR 15.0
END DESCRIPTION:
XS GIS Cut Line= 3
      3796749.61     10477960.18      3796849.61     10478360.19
      3797249.61     10478760.19
#Sta/Elev= 30
  4608.6  303.36  4618.9  300.69  4631.8  300.21  4660.1  295.42    4722  289.18
  4755.5  287.81  4763.2  285.59  4783.8   285.5  4791.6  283.94  4814.8  285.82
  4832.4  284.78    4856  280.73  4879.2  282.22  4897.2  282.12  4928.1  276.22
  4956.5  274.84  4969.4  270.73  4994.7  266.44  4997.5  265.94  5000.7  266.44
  5004.9  267.71  5018.3  272.17  5024.5  272.17  5035.1  275.04  5119.9  276.92
    5233  276.57  5346.2  279.26  5558.3  290.78  5572.5  289.86  5586.6  292.06
#Mann= 5 ,-1 , 0
  4608.6     .16       0  4832.4     .08       0  4994.7     .07       0
  5000.7     .08       0  5004.9     .05       0
Bank Sta=4956.5,5035.1
XS Rating Curve= 0 ,0
Exp/Cntr=0.3,0.1

Type RM Length L Ch R = 1 ,9056    ,198,198,198
BEGIN DESCRIPTION:
UNT049 IN BECR 14.0
END DESCRIPTION:
XS GIS Cut Line= 3
      3796399.62     10477860.22      3796649.61     10478660.19
       3797049.6     10479060.18
#Sta/Elev= 30
  4225.9   310.2  4393.5  294.48  4499.2  289.08  4577.4  286.85  4592.6   284.5
    4603  284.53  4609.8  287.06    4624  286.86  4634.5  283.32  4647.6  283.31
  4659.9  281.05  4697.3  283.14  4718.3  280.76  4812.3  278.36  4938.3  271.67
  4950.3   268.8  4959.3  270.12  4977.6  266.14  5007.1  264.04  5009.8  263.54
  5013.1  264.04  5022.1  268.59  5032.6   269.4  5042.5   267.2  5047.8  269.64
  5053.5  268.51  5061.4  271.13    5163   272.9  5403.4   284.2  5629.7  300.55
#Mann= 6 ,-1 , 0
  4225.9     .05       0  4499.2     .16       0  4659.9     .08       0
  4812.3     .05       0  5007.1     .03       0  5013.1     .05       0
Bank Sta=4959.3,5032.6
XS Rating Curve= 0 ,0
Exp/Cntr=0.3,0.1

Type RM Length L Ch R = 1 ,8858    ,297,297,297
BEGIN DESCRIPTION:
Mapping XS d9661867
END DESCRIPTION:
XS GIS Cut Line= 2
      3796198.02     10478395.43      3797045.59     10479259.26
#Sta/Elev= 30
  4454.4  284.84  4480.1  283.68  4487.2  282.16  4508.4  282.26  4559.1   279.3
  4620.7  278.08    4664  277.55  4718.4  275.08  4819.5  272.59  4982.1  270.34
  4989.3  264.37  4993.3  263.82    4996  263.32  4999.3  263.82  5003.4  264.04
  5010.4  268.85  5017.6  270.48    5067  271.96  5109.4  274.79    5159   276.2
  5194.3  278.85  5250.9  280.89    5265     283  5342.9  288.06  5371.2  288.62
  5420.6  293.36  5441.7  293.72  5576.2  304.07  5597.3  306.79  5664.6  310.59
#Mann= 6 ,-1 , 0
  4454.4     .08       0  4559.1     .05       0  4620.7     .08       0
  4718.4     .05       0  4993.3     .03       0  4999.3     .05       0
Bank Sta=4982.1,5017.6
XS Rating Curve= 0 ,0
Exp/Cntr=0.3,0.1

Type RM Length L Ch R = 1 ,8561    ,125,125,125
BEGIN DESCRIPTION:
UNT049 IN BECR 13.0
END DESCRIPTION:
XS GIS Cut Line= 3
      3796027.54     10478446.27      3796449.61     10479060.19
       3796849.6     10479410.18
#Sta/Elev= 30
  4276.1  284.75  4375.6  281.01  4547.6  278.03  4596.4  276.17  4669.2  271.33
  4711.9  270.17  4899.8  269.51  4971.7   267.4  4977.8  263.79  4992.7  263.29
  4995.8  260.87  4998.5  260.37  5001.8  260.87  5007.6  261.13  5018.1  265.81
  5024.4  265.81  5028.2  269.89  5120.3  273.03  5134.5  275.92  5183.9  278.54
  5226.6  282.98  5240.8  282.93    5312  288.43  5332.9  288.99  5382.2  294.12
  5418.3  295.54  5460.1  299.19  5467.7  300.73  5531.3  304.86  5552.6  308.25
#Mann= 4 ,-1 , 0
  4276.1     .08       0  4375.6     .05       0  4995.8     .03       0
  5001.8     .05       0
Bank Sta=4899.8,5028.2
XS Rating Curve= 0 ,0
Exp/Cntr=0.3,0.1

Type RM Length L Ch R = 1 ,8436    ,175,175,175
BEGIN DESCRIPTION:
Mapping XS b7ffd58b
END DESCRIPTION:
XS GIS Cut Line= 3
      3795688.17      10478542.7      3796444.05     10479210.33
      3796825.61     10479468.32
#Sta/Elev= 30
    4081  284.64  4107.6  281.67  4129.8  282.78  4229.4  280.86  4405.9  275.86
  4497.9  273.89  4519.7  274.26  4526.4  274.03  4533.9  272.15  4611.7  270.57
  4866.9  268.86  4979.8  267.17  4998.5  262.32  5001.3  261.82  5004.5  262.32
  5015.8  267.44  5089.5  268.82  5094.2  270.33  5108.3  270.22  5115.2  271.85
  5130.1  273.06  5136.2  275.19  5151.1  277.06  5202.1  281.52  5330.9  288.38
  5366.9  292.05  5402.9  293.58  5410.1  295.29  5474.8  299.55  5550.1   306.9
#Mann= 4 ,-1 , 0
    4081     .08       0  4107.6     .05       0  4998.5     .03       0
  5004.5     .05       0
Bank Sta=4979.8,5015.8
XS Rating Curve= 0 ,0
Exp/Cntr=0.3,0.1

Type RM Length L Ch R = 1 ,8261    ,588,588,588
BEGIN DESCRIPTION:
UNT049 IN BECR 12.0
END DESCRIPTION:
XS GIS Cut Line= 2
      3795102.55     10478700.98      3796915.78     10479608.37
#Sta/Elev= 30
  3615.7  292.49  3718.1  290.67  4126.8  273.71  4350.4  272.04  4381.6  265.98
  4387.2  271.26  4417.5  271.25  4476.6  268.54    4499  263.65    4507  267.98
  4529.4  265.27  4538.1  268.82  4582.8  269.78  4985.2  265.77    4996  258.03
  4998.8  257.53    5002  258.03  5007.6  263.94  5013.1  261.02  5029.9  266.96
  5035.5   263.5  5080.2  267.95    5097   273.3  5102.6     270    5164  281.06
  5200.3  277.35  5214.3  282.12  5370.8  290.79  5619.3  317.68  5643.3  318.93
#Mann= 5 ,-1 , 0
  3615.7     .08       0  3718.1     .05       0    4996     .03       0
    5002     .05       0  5619.3     .08       0
Bank Sta=4985.2,5029.9
XS Rating Curve= 0 ,0
Exp/Cntr=0.3,0.1

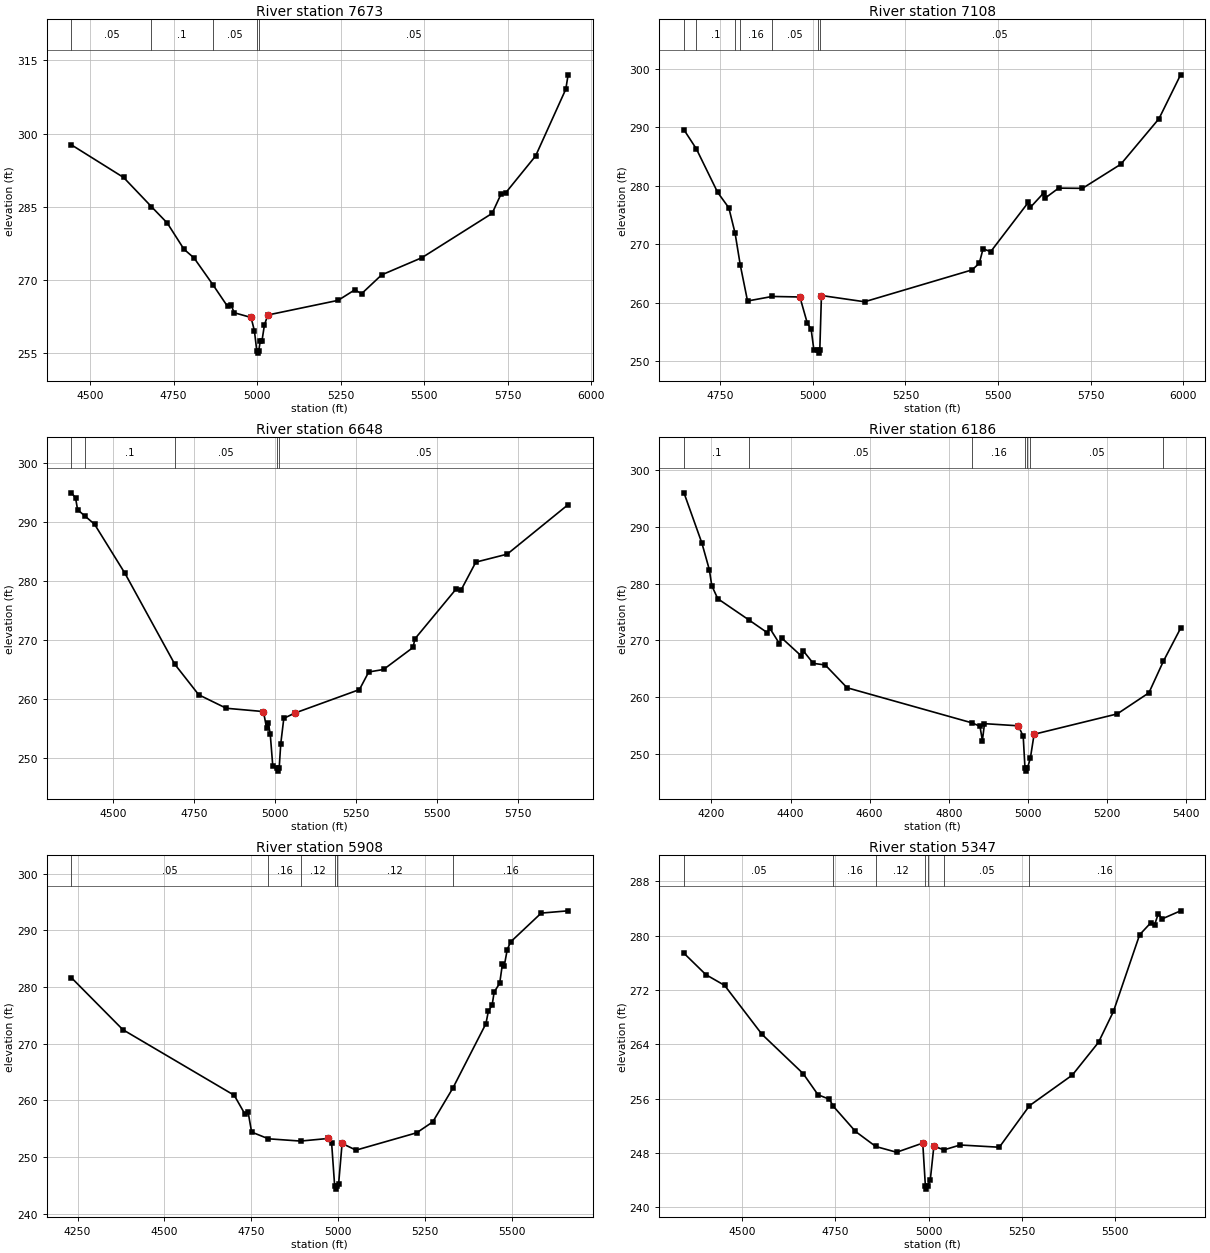
Type RM Length L Ch R = 1 ,7673    ,565,565,565
BEGIN DESCRIPTION:
UNT049 IN BECR 11.0
END DESCRIPTION:
XS GIS Cut Line= 3
       3795334.1     10479563.58      3795899.61     10479610.19
      3796816.59     10479667.63
#Sta/Elev= 30
  4444.7  297.68  4600.7  291.01  4683.8  285.05  4731.2   281.7  4781.3  276.33
  4811.4  274.55  4868.1  269.05  4911.8  264.62  4921.8  264.93  4931.9  263.33
    4982  262.37  4992.1  259.65  4999.1  255.57  5001.8  255.07  5005.1  255.57
  5009.6  257.52  5014.6  257.52  5022.1  260.84  5032.2  262.87  5242.6  265.87
  5292.7  268.03  5312.7  267.22  5372.8  271.08  5493.1  274.59  5703.5  283.67
  5730.2  287.62  5743.6  287.83  5833.7  295.43  5923.9  309.07  5930.9  312.02
#Mann= 5 ,-1 , 0
  4444.7     .05       0  4683.8      .1       0  4868.1     .05       0
  4999.1     .03       0  5005.1     .05       0
Bank Sta=4982,5032.2
XS Rating Curve= 0 ,0
Exp/Cntr=0.3,0.1

Type RM Length L Ch R = 1 ,7108    ,460,460,460
BEGIN DESCRIPTION:
UNT049 IN BECR 10.0
END DESCRIPTION:
XS GIS Cut Line= 3
      3795449.62     10480060.19      3795799.61     10480010.19
      3796756.21     10479763.63
#Sta/Elev= 30
  4651.9  289.59  4685.4  286.32  4742.8  278.88  4773.1  276.22    4790  271.86
  4803.8  266.49  4823.6  260.26  4890.4  261.04    4965  260.95  4985.2  256.43
  4995.3  255.46  5002.9  251.84  5012.8  251.83  5015.5  251.33  5018.8  251.83
  5023.2   261.2  5139.7  260.13  5430.1  265.59  5449.5  266.72  5459.8   269.2
  5480.5  268.72  5582.5   277.2  5587.7  276.31  5623.2  278.75  5628.3  277.93
  5663.9   279.6  5728.3  279.56  5831.8  283.69  5934.9  291.49  5993.3  299.01
#Mann= 7 ,-1 , 0
  4651.9     .05       0  4685.4      .1       0    4790     .05       0
  4803.8     .16       0  4890.4     .05       0  5012.8     .03       0
  5018.8     .05       0
Bank Sta=4965,5023.2
XS Rating Curve= 0 ,0
Exp/Cntr=0.3,0.1

Type RM Length L Ch R = 1 ,6648    ,462,462,462
BEGIN DESCRIPTION:
UNT049 IN BECR 9.0
END DESCRIPTION:
XS GIS Cut Line= 3
      3795351.48     10480231.98      3795949.61     10480410.19
      3796773.19     10480024.55
#Sta/Elev= 30
  4372.2  294.96  4384.7  294.09  4391.1  292.09  4415.1  290.97  4443.3  289.65
  4537.2  281.34  4691.4  265.93  4765.1  260.78  4850.2   258.5    4965  257.94
  4974.5  255.17  4979.7  256.05  4985.9  254.15  4993.7  248.74  5007.5  248.36
  5010.2  247.86  5013.5  248.36  5018.4  252.51  5027.8   256.8  5062.6   257.7
  5261.3  261.66    5290  264.64  5335.7  265.06  5426.9  268.79  5432.5  270.24
  5559.4  278.65    5575  278.49  5620.7  283.23  5717.6  284.58  5905.7  292.96
#Mann= 5 ,-1 , 0
  4372.2     .05       0  4415.1      .1       0  4691.4     .05       0
  5007.5     .03       0  5013.5     .05       0
Bank Sta=4965,5062.6
XS Rating Curve= 0 ,0
Exp/Cntr=0.3,0.1

Type RM Length L Ch R = 1 ,6186    ,278,278,278
BEGIN DESCRIPTION:
UNT049 IN BECR 8.0
END DESCRIPTION:
XS GIS Cut Line= 3
      3795199.66     10480560.21      3795999.61     10480860.19
      3796399.66     10480860.19
#Sta/Elev= 30
  4130.9  296.02  4176.2  287.15  4194.9  282.49  4201.2  279.64  4216.3  277.35
  4295.7  273.57  4341.8  271.34  4347.1  272.21    4372  269.44  4377.4  270.45
  4427.2  267.26  4432.6  268.13  4457.5  265.95  4487.7  265.67  4542.9  261.65
  4858.4  255.46  4878.5  254.86  4884.7  252.35    4890  255.32  4975.5  254.94
  4987.8  253.08  4992.3  247.45    4995  246.95  4998.3  247.45  5005.8  249.21
  5015.3  253.45  5225.3  257.04  5305.3  260.76  5341.8  266.32  5385.3  272.14
#Mann= 7 ,-1 , 0
  4130.9      .1       0  4295.7     .05       0  4858.4     .16       0
  4992.3     .07       0  4998.3     .16       0  5005.8     .05       0
  5341.8     .16       0
Bank Sta=4975.5,5015.3
XS Rating Curve= 0 ,0
Exp/Cntr=0.3,0.1

Type RM Length L Ch R = 1 ,5908    ,561,561,561
BEGIN DESCRIPTION:
UNT049 IN BECR 7.0
END DESCRIPTION:
XS GIS Cut Line= 3
      3795282.04     10481100.04      3796219.56     10481143.44
       3796670.9     10480952.49
#Sta/Elev= 30
  4232.7  281.62  4380.4  272.47  4700.8  260.89  4730.8  257.66  4740.8  257.91
  4750.8   254.4  4799.3  253.21  4891.5  252.81  4971.1  253.27  4981.1  252.39
  4989.8  244.83  4992.5  244.33  4995.8  244.83  5001.1  245.23  5011.1  252.39
  5051.1  251.21  5225.6  254.27  5271.9  256.19  5329.8  262.16  5424.9  273.53
  5431.9  275.74  5442.7  276.79  5448.6  279.13  5464.4  280.63  5472.3  284.03
  5477.7  283.76  5486.2   286.6    5496  287.96  5583.9  293.04  5661.3  293.44
#Mann= 6 ,-1 , 0
  4232.7     .05       0  4799.3     .16       0  4891.5     .12       0
  4989.8     .03       0  4995.8     .12       0  5329.8     .16       0
Bank Sta=4971.1,5011.1
XS Rating Curve= 0 ,0
Exp/Cntr=0.3,0.1

Type RM Length L Ch R = 1 ,5347    ,358,358,358
BEGIN DESCRIPTION:
UNT049 IN BECR 6.0
END DESCRIPTION:
XS GIS Cut Line= 2
      3795420.99      10481655.6       3796749.1     10481733.72
#Sta/Elev= 30
  4344.8  277.42  4403.5  274.27  4453.6  272.69  4553.8  265.48    4664   259.7
    4704  256.57  4734.1  255.93  4744.8  254.89  4804.2  251.18  4858.6  248.96
  4914.4  248.11  4984.5  249.46  4991.5  243.18  4994.3  242.68  4997.5  243.18
  5004.6     244  5014.3  249.01  5041.2  248.46  5084.7  249.18  5189.6  248.85
  5270.4  254.97  5385.2  259.48  5455.3   264.3  5495.4  268.86  5565.5  280.15
  5595.6  281.92  5605.6  281.62  5615.6  283.26  5625.6  282.48  5675.2  283.67
#Mann= 7 ,-1 , 0
  4344.8     .05       0  4744.8     .16       0  4858.6     .12       0
  4991.5     .07       0  4997.5     .12       0  5041.2     .05       0
  5270.4     .16       0
Bank Sta=4984.5,5014.3
XS Rating Curve= 0 ,0
Exp/Cntr=0.3,0.1

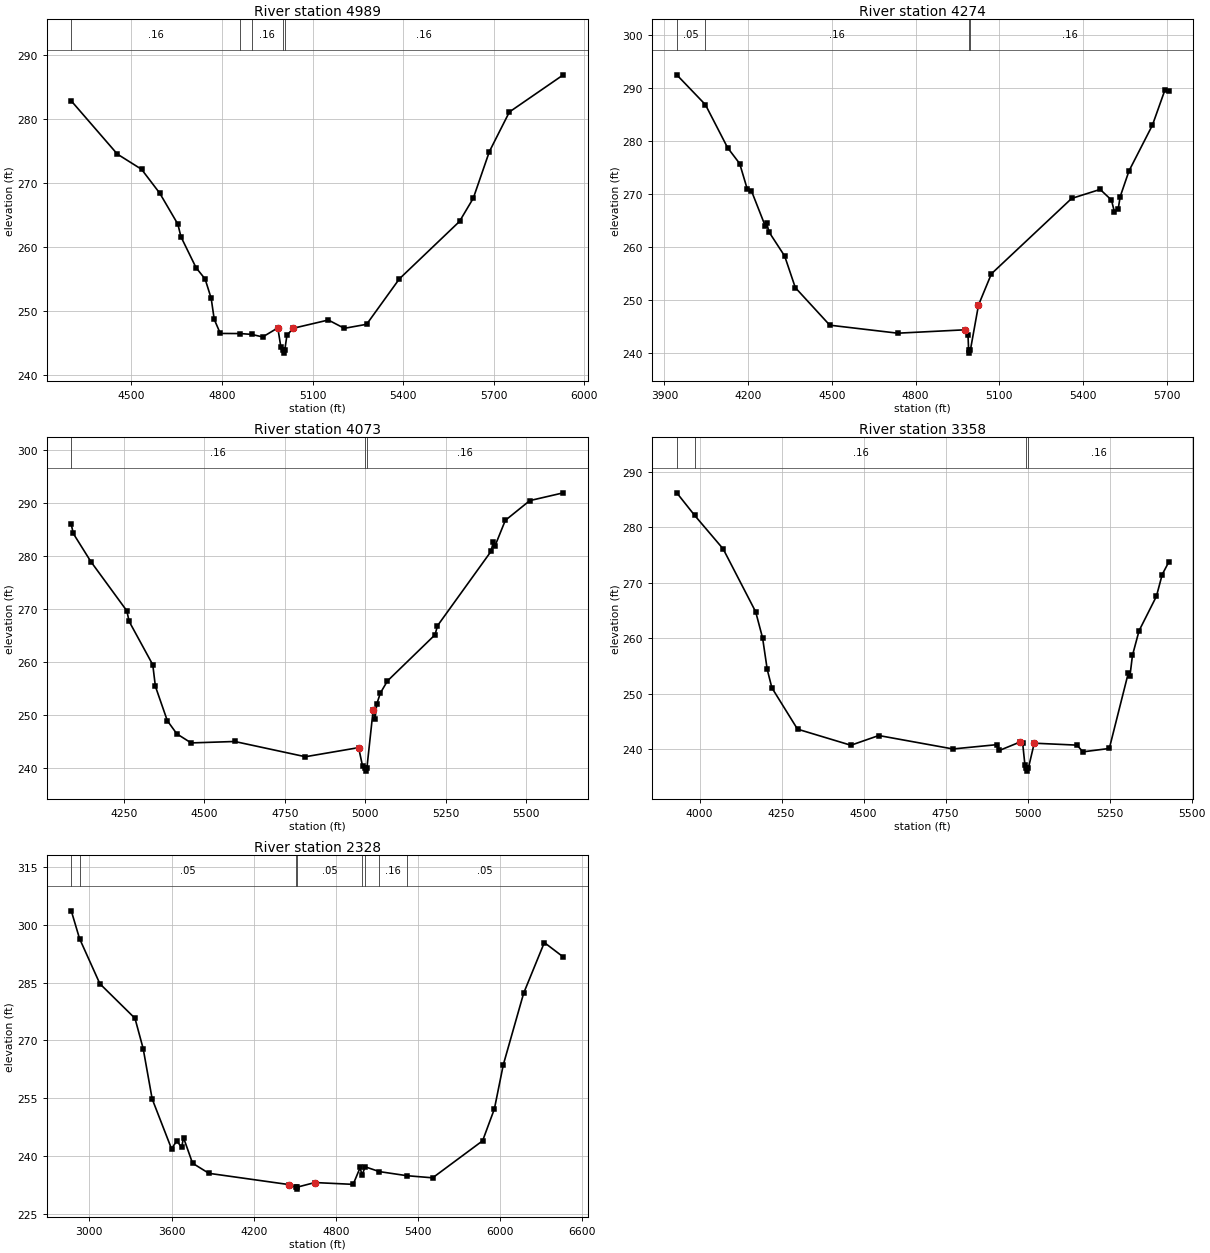
Type RM Length L Ch R = 1 ,4989    ,715,715,715
BEGIN DESCRIPTION:
UNT049 IN BECR 5.0
END DESCRIPTION:
XS GIS Cut Line= 3
      3795377.56     10481994.14      3796228.24     10482063.58
       3796931.4     10482393.46
#Sta/Elev= 30
  4300.6  282.87  4453.2  274.55  4533.4  272.17  4593.6  268.44  4653.8  263.58
  4663.9  261.62    4714  256.78  4744.1     255  4764.2  251.96  4774.2   248.7
  4794.3  246.49  4860.6  246.47  4898.3  246.34  4934.8  245.94  4984.9  247.36
    4995  244.35    5002  243.91  5004.7  243.41    5008  243.91    5015  246.17
  5035.1  247.29  5152.3  248.59  5205.2  247.29  5279.1  247.92  5387.6  255.03
  5586.8  264.01  5632.5  267.65  5685.8  274.95  5752.1  281.14  5930.8  286.95
#Mann= 5 ,-1 , 0
  4300.6     .16       0  4860.6     .12       0  4898.3     .16       0
    5002     .07       0    5008     .16       0
Bank Sta=4984.9,5035.1
XS Rating Curve= 0 ,0
Exp/Cntr=0.3,0.1

Type RM Length L Ch R = 1 ,4274    ,201,201,201
BEGIN DESCRIPTION:
UNT049 IN BECR 4.0
END DESCRIPTION:
XS GIS Cut Line= 2
      3795264.69     10482319.07       3796945.6     10482850.45
#Sta/Elev= 30
  3944.3  292.48  4046.9  286.85  4126.5  278.73  4169.7  275.74  4196.4  271.02
  4211.7  270.62    4261  264.01  4266.3  264.59  4274.6  262.86  4330.9   258.3
    4369  252.35  4492.5  245.27    4736  243.76  4977.3   244.4  4987.7  243.38
    4990   240.5  4992.8     240    4996   240.5  5025.3  249.06  5071.6  254.96
    5359  269.17  5461.2  270.87  5501.6  268.87  5512.1  266.67  5525.9  267.24
  5533.1  269.53  5564.6  274.37  5648.5     283  5692.7  289.54  5707.2  289.41
#Mann= 4 ,-1 , 0
  3944.3     .05       0  4046.9     .16       0    4990     .07       0
    4996     .16       0
Bank Sta=4977.3,5025.3
XS Rating Curve= 0 ,0
Exp/Cntr=0.3,0.1

Type RM Length L Ch R = 1 ,4073    ,715,715,715
BEGIN DESCRIPTION:
UNT049 IN BECR 3.0
END DESCRIPTION:
XS GIS Cut Line= 2
      3795384.04     10482416.72      3796762.03     10483078.59
#Sta/Elev= 30
  4086.2  285.97  4092.4  284.24  4147.1  278.92  4258.8  269.62  4265.9  267.63
  4339.4  259.43  4347.5  255.36  4384.6  248.86  4414.1  246.38  4458.5  244.66
    4594  244.93  4813.5  242.05  4978.9  243.77    4991  240.32  4998.5  239.83
  5001.3  239.33  5004.5  239.83  5024.2  250.95  5029.7  249.17  5035.3     252
  5046.4  254.08  5068.6  256.38  5216.4   265.1  5223.9   266.8  5390.3  280.86
  5397.5  282.72  5403.1  281.96  5434.7  286.72  5510.7  290.45  5614.9  291.92
#Mann= 3 ,-1 , 0
  4086.2     .16       0  4998.5     .07       0  5004.5     .16       0
Bank Sta=4978.9,5024.2
XS Rating Curve= 0 ,0
Exp/Cntr=0.3,0.1

Type RM Length L Ch R = 1 ,3358    ,1030,1030,1030
BEGIN DESCRIPTION:
UNT049 IN BECR 2.0
END DESCRIPTION:
XS GIS Cut Line= 3
      3795349.62      10482460.2      3796099.61     10483260.19
      3796499.63     10483310.19
#Sta/Elev= 30
  3930.7  286.19  3985.2  282.13  4072.1  276.09  4171.2  264.77  4192.3  260.05
  4206.4  254.39  4220.6  251.08  4298.7  243.64  4461.4  240.74  4546.4  242.49
  4772.5  240.07  4906.9  240.85  4914.2  239.81  4977.7  241.34    4985  241.07
  4991.9  237.12  4996.2  236.58  4998.9  236.08  5002.2  236.58  5020.2  241.11
  5150.7  240.76  5168.4  239.55    5249  240.16  5306.9  253.75    5312  253.24
  5319.5  256.91  5339.7  261.36  5392.6  267.56  5410.2  271.48  5430.4  273.75
#Mann= 4 ,-1 , 0
  3930.7     .05       0  3985.2     .16       0  4996.2     .07       0
  5002.2     .16       0
Bank Sta=4977.7,5020.2
XS Rating Curve= 0 ,0
Exp/Cntr=0.3,0.1

Type RM Length L Ch R = 1 ,2328    ,0,0,0
BEGIN DESCRIPTION:
UNT049 IN BECR 1.0
END DESCRIPTION:
XS GIS Cut Line= 4
      3794374.92     10482481.84      3795058.51      10483740.5
      3795991.67     10484066.02      3796945.59      10483383.1
#Sta/Elev= 30
  2867.9  303.72  2928.2  296.51  3076.7  284.76  3333.2  275.77  3393.1  267.88
  3458.7  254.81  3600.3  241.82  3638.3   243.9    3674   242.2  3687.7  244.74
  3753.6  238.09    3873  235.46  4460.2  232.52  4510.2  231.85  4512.9  231.35
  4516.2  231.85    4647  233.06  4926.6  232.59  4978.1  236.98  4991.1  234.91
  5014.1  237.16  5117.4  235.91  5319.8  234.84  5507.2  234.29  5872.1  243.92
  5958.1   252.2  6023.2  263.68  6171.8  282.29  6322.9  295.47  6461.7  291.71
#Mann= 8 ,-1 , 0
  2867.9     .16       0  2928.2     .05       0  4510.2     .07       0
  4516.2     .05       0  4991.1     .16       0  5014.1     .12       0
  5117.4     .16       0  5319.8     .05       0
Bank Sta=4460.2,4647
XS Rating Curve= 0 ,0
Exp/Cntr=0.3,0.1

Chan Stop Cuts=-1
Use User Specified Reach Order=0
Composite Channel Slope=5