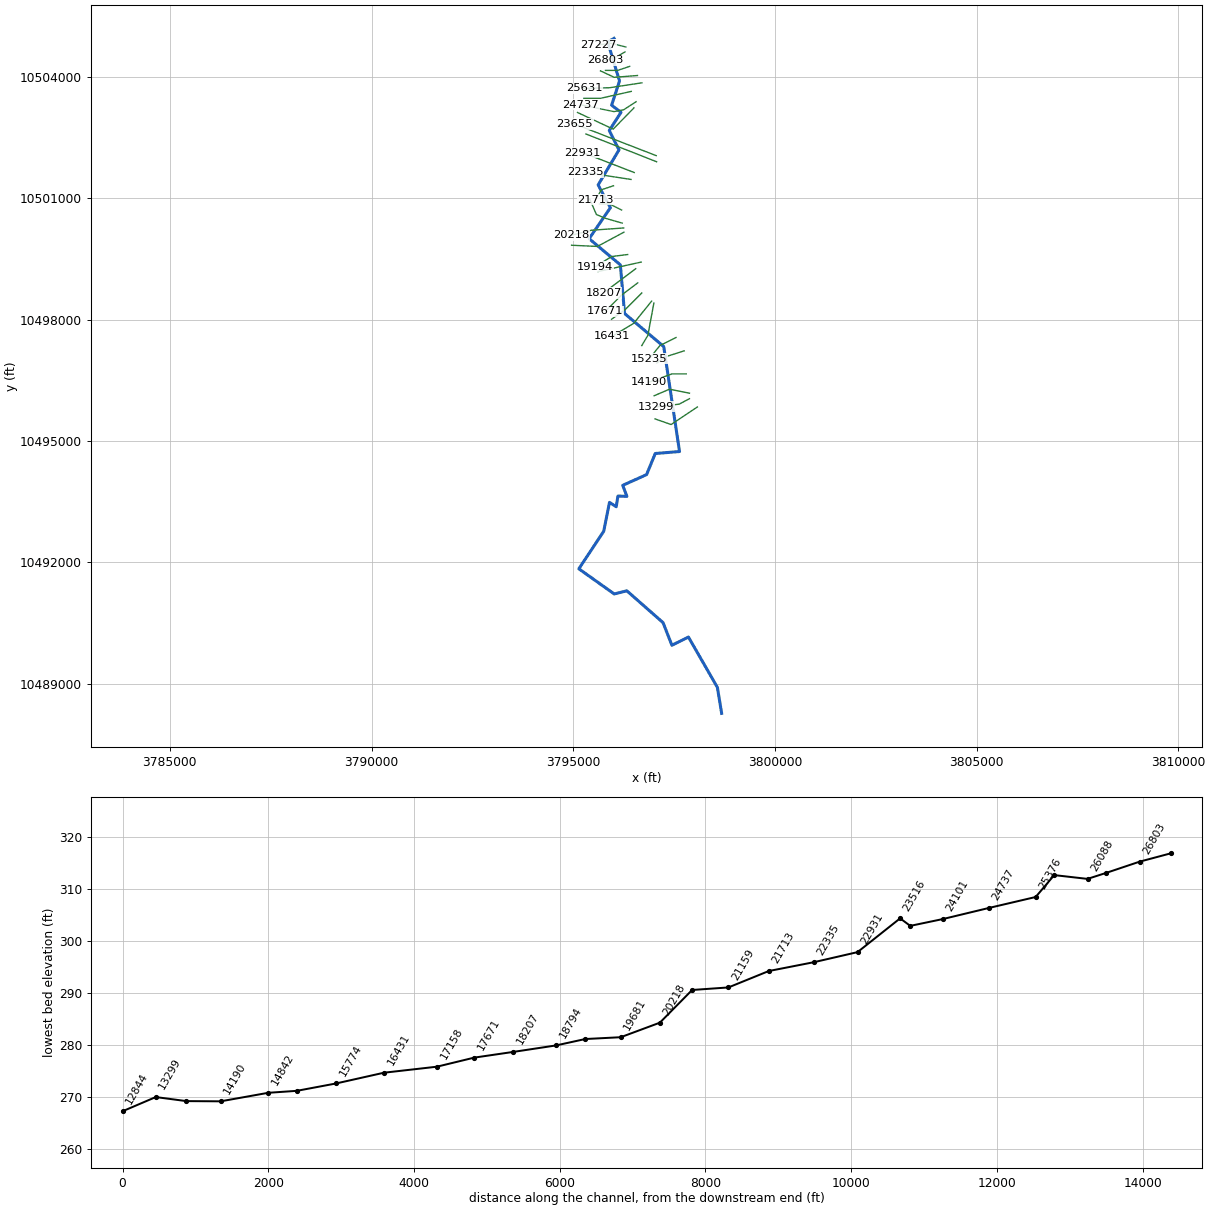
--- UNT050 IN BECR.prj (project) ---

Proj Title=UNT050 IN BECR Base Level Engineering
Current Plan=p01
Default Exp/Contr=0.3,0.1
English Units
Geom File=g01
Flow File=f01
Plan File=p01
Y Axis Title=Elevation
X Axis Title(PF)=Main Channel Distance
X Axis Title(XS)=Station
BEGIN DESCRIPTION:
UNT050 IN BECR
END DESCRIPTION:
DSS Export Rating Curves= 0
DSS Export Rating Curve Sorted= 0
DSS Export Volume Flow Curves= 0
DXF OffsetX= 0
DXF OffsetY= 0
DXF ScaleX= 1
DXF ScaleY= 10

--- UNT050 IN BECR.p01 (plan) ---

Plan Title=Multiple Run
Short Identifier=Multiple
Geom File=g01
Flow File=f01
Subcritical Flow
K Sum by GR= 0
Std Step Tol= 0.01
Critical Tol= 0.01
Num of Std Step Trials= 20
Max Error Tol= 0.3
Flow Tol Ratio= 0.001
Split Flow NTrial= 30
Split Flow Tol= 0.02
Split Flow Ratio= 0.02
Log Output Level= 0
Friction Slope Method= 1
Unsteady Friction Slope Method= 2
Unsteady Bridges Friction Slope Method= 1
Parabolic Critical Depth
Global Vel Dist=  1 , 1 , 1
Global Log Level= 0
CheckData=True
Encroach Param= -1, 0, 0, 0
BEGIN DESCRIPTION:
Multiple Run
END DESCRIPTION:

--- UNT050 IN BECR.f01 (steady flow) ---

Flow Title=Multiple
Number of Profiles=7
Profile Names=10-year,25-year,50-year,1pct_min,100-year,1pct_plu,500-year
River Rch & RM= UNT050 IN BECR,Reach-1,27227
     701     959    1176    1059    1433    1937    2134
River Rch & RM= UNT050 IN BECR,Reach-1,19681
     896    1235    1519    1371    1855    2508    2776
River Rch & RM= UNT050 IN BECR,Reach-1,12346
    1455    2039    2536    2310    3124    4225    4761
River Rch & RM= UNT050 IN BECR,Reach-1,5414
    1486    2083    2590    2359    3190    4314    4861
River Rch & RM= UNT050 IN BECR,Reach-1,3602
    1504    2106    2618    2383    3223    4359    4906
Boundary for River Rch & Prof#=UNT050 IN BECR,Reach-1,1
Up Type=0
Dn Type=3
Dn Slope=0.005
Boundary for River Rch & Prof#=UNT050 IN BECR,Reach-1,2
Up Type=0
Dn Type=3
Dn Slope=0.005
Boundary for River Rch & Prof#=UNT050 IN BECR,Reach-1,3
Up Type=0
Dn Type=3
Dn Slope=0.005
Boundary for River Rch & Prof#=UNT050 IN BECR,Reach-1,4
Up Type=0
Dn Type=3
Dn Slope=0.005
Boundary for River Rch & Prof#=UNT050 IN BECR,Reach-1,5
Up Type=0
Dn Type=3
Dn Slope=0.005
Boundary for River Rch & Prof#=UNT050 IN BECR,Reach-1,6
Up Type=0
Dn Type=3
Dn Slope=0.005
Boundary for River Rch & Prof#=UNT050 IN BECR,Reach-1,7
Up Type=0
Dn Type=3
Dn Slope=0.005

--- UNT050 IN BECR.g01 (geometry) ---

Geom Title=Existing Conditions
Program Version=4.10

River Reach=UNT050 IN BECR  ,Reach-1
Reach XY= 30
        3796012.       10504953.      3795854.75       10504862.
       3796147.5       10503899.      3795951.75       10503300.
      3796185.25       10503125.      3795893.75       10502675.
      3796135.25       10502197.       3795617.5       10501330.
       3795921.5       10500767.       3795394.5       10500002.
      3796168.25       10499355.        3796273.       10498153.
       3797243.5       10497337.      3797635.25       10494742.
      3797033.25       10494693.      3796818.75       10494172.
      3796227.25       10493906.      3796331.25       10493634.
        3796109.       10493641.       3796065.5       10493378.
      3795899.25       10493485.        3795756.       10492772.
        3795140.       10491844.        3796016.       10491222.
        3796329.       10491300.      3797226.25       10490514.
       3797446.5       10489955.       3797856.5       10490157.
        3798574.       10488913.      3798679.75       10488271.

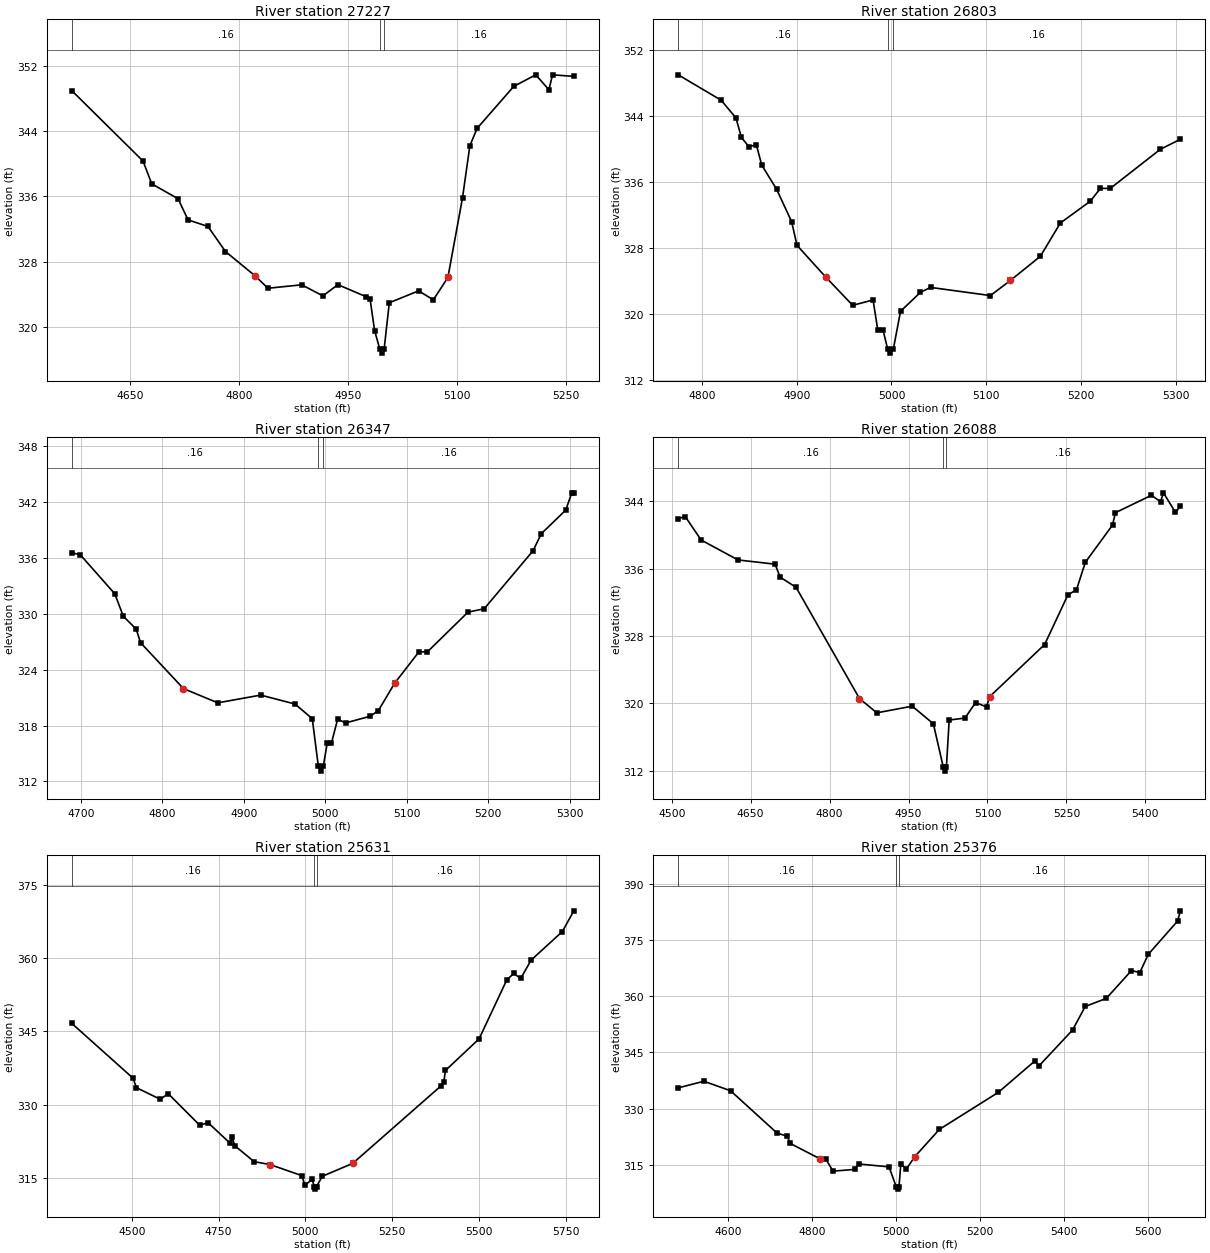
Type RM Length L Ch R = 1 ,27227   ,424,424,424
BEGIN DESCRIPTION:
UNT050 IN BECR 51.0
END DESCRIPTION:
XS GIS Cut Line= 3
      3796304.71     10504739.35       3795943.6     10504829.63
      3795627.62     10504791.43
#Sta/Elev= 30
  4570.3  348.94  4668.3  340.33  4680.3  337.54  4716.4  335.73  4730.2  333.14
  4757.6  332.33  4781.7  329.27  4822.9  326.26  4840.1  324.78  4886.5   325.2
  4915.7  323.85  4936.3  325.22  4975.6  323.73  4980.6  323.42  4986.8  319.59
  4993.9  317.35  4996.7  316.85  4999.9  317.35    5007  323.01  5047.3  324.46
  5067.6  323.37  5087.6   326.1  5107.7  335.85  5117.8  342.21  5127.8  344.33
  5178.2  349.46  5208.4  350.87  5226.5  349.05  5231.5  350.87  5260.8  350.68
#Mann= 3 ,-1 , 0
  4570.3     .16       0  4993.9     .07       0  4999.9     .16       0
Bank Sta=4822.9,5087.6
XS Rating Curve= 0 ,0
Exp/Cntr=0.3,0.1

Type RM Length L Ch R = 1 ,26803   ,456,456,456
BEGIN DESCRIPTION:
UNT050 IN BECR 50.0
END DESCRIPTION:
XS GIS Cut Line= 3
      3796283.86     10504617.81      3796099.61     10504510.19
      3795799.62     10504410.19
#Sta/Elev= 30
  4775.1  348.96  4820.3  345.89    4836  343.74  4841.7  341.38  4849.5  340.28
  4857.5  340.47  4863.2  338.03  4878.9  335.09  4894.7  331.18  4900.4  328.31
  4930.6  324.48  4959.1  321.05  4980.6   321.7  4985.6  318.06  4991.1  318.06
    4996  315.76  4998.8  315.26    5002  315.76  5009.6  320.33  5030.6  322.62
  5041.2  323.22  5104.4  322.23  5125.5  324.06  5157.1  326.99  5178.2  331.02
  5209.8  333.66  5220.4  335.21  5230.9  335.21  5283.6  339.94  5304.7  341.15
#Mann= 3 ,-1 , 0
  4775.1     .16       0    4996     .07       0    5002     .16       0
Bank Sta=4930.6,5125.5
XS Rating Curve= 0 ,0
Exp/Cntr=0.3,0.1

Type RM Length L Ch R = 1 ,26347   ,259,259,259
BEGIN DESCRIPTION:
UNT050 IN BECR 49.0
END DESCRIPTION:
XS GIS Cut Line= 3
      3796399.65      10504260.2      3796099.61     10504160.19
      3795799.58     10504160.19
#Sta/Elev= 30
  4688.7  336.55  4699.3  336.32  4741.5  332.14    4752  329.73  4767.8  328.35
  4773.1   326.9  4825.8  321.97  4867.9  320.44  4920.6  321.27  4962.8  320.31
  4983.9  318.74  4991.4  313.61  4994.2  313.11  4997.4  313.61  5002.3  316.13
  5007.5  316.13    5015  318.67    5025  318.29    5055     319    5065   319.6
    5085  322.54    5115  325.93    5125  325.89    5175  330.17    5195  330.54
    5255  336.77    5265  338.59    5295  341.12  5302.5  342.98    5305  342.98
#Mann= 3 ,-1 , 0
  4688.7     .16       0  4991.4     .07       0  4997.4     .16       0
Bank Sta=4825.8,5085
XS Rating Curve= 0 ,0
Exp/Cntr=0.3,0.1

Type RM Length L Ch R = 1 ,26088   ,457,457,457
BEGIN DESCRIPTION:
UNT050 IN BECR 48.0
END DESCRIPTION:
XS GIS Cut Line= 3
      3796592.93     10504034.49      3796016.51     10503989.35
      3795676.22     10504149.08
#Sta/Elev= 30
  4512.4  341.96  4525.8  342.19  4555.9  339.41  4626.1  337.04  4696.3  336.54
  4706.3  334.99  4736.4  333.78  4856.8  320.57  4889.8  318.87  4957.1  319.66
  4997.2  317.57    5016  312.44  5018.8  311.94    5022  312.44  5027.3  318.01
  5057.4  318.25  5077.4  320.09  5098.2  319.58    5104  320.78  5208.7  326.99
  5252.9  332.89  5269.2   333.5    5286  336.76  5337.7  341.19  5343.2  342.66
  5411.7  344.73  5428.9  343.96  5434.5  345.02  5457.3  342.69  5466.5  343.41
#Mann= 3 ,-1 , 0
  4512.4     .16       0    5016     .07       0    5022     .16       0
Bank Sta=4856.8,5104
XS Rating Curve= 0 ,0
Exp/Cntr=0.3,0.1

Type RM Length L Ch R = 1 ,25631   ,255,255,255
BEGIN DESCRIPTION:
Mapping XS c472e84f
END DESCRIPTION:
XS GIS Cut Line= 3
        3796704.     10503853.93      3795901.93      10503732.4
      3795266.49     10503715.04
#Sta/Elev= 30
  4327.1  346.66  4503.5  335.43  4513.6  333.47  4582.5  331.08  4604.6  332.27
  4695.7  325.79  4720.1  326.29  4783.8  322.05  4788.9  323.39  4796.8  321.59
  4852.6   318.3  4897.9  317.72  4990.1  315.44  4999.1  313.45  5019.3  314.67
  5026.4  313.17  5029.2  312.67  5032.4  313.17  5048.8  315.29    5137  317.96
  5390.7  333.81  5399.1  334.59  5404.1  337.01  5500.8  343.47  5580.8  355.58
  5600.8  356.89  5620.8  355.87  5650.8  359.63  5740.9  365.49    5774  369.74
#Mann= 3 ,-1 , 0
  4327.1     .16       0  5026.4     .07       0  5032.4     .16       0
Bank Sta=4897.9,5137
XS Rating Curve= 0 ,0
Exp/Cntr=0.3,0.1

Type RM Length L Ch R = 1 ,25376   ,639,639,639
BEGIN DESCRIPTION:
UNT050 IN BECR 47.0
END DESCRIPTION:
XS GIS Cut Line= 3
      3796439.12     10503641.79      3795673.46      10503469.9
      3795263.27      10503469.9
#Sta/Elev= 30
  4482.1  335.52  4543.1  337.29  4606.6  334.75  4717.3  323.43  4741.7  322.59
  4748.1   320.7  4819.8  316.53  4833.5  316.44  4850.6  313.26  4901.8  313.72
    4912  315.17  4983.8   314.4  5001.3  308.95    5004  308.45  5007.3  308.95
  5011.9  315.17  5024.8   313.8  5045.3  317.16  5103.7  324.43  5243.9  334.32
  5330.7   342.7  5340.7   341.4  5420.7     351  5450.7  357.28  5500.7  359.43
  5560.7  366.87  5580.7  366.36  5600.7  371.21  5670.7  380.14    5677  382.85
#Mann= 3 ,-1 , 0
  4482.1     .16       0  5001.3     .07       0  5007.3     .16       0
Bank Sta=4819.8,5045.3
XS Rating Curve= 0 ,0
Exp/Cntr=0.3,0.1

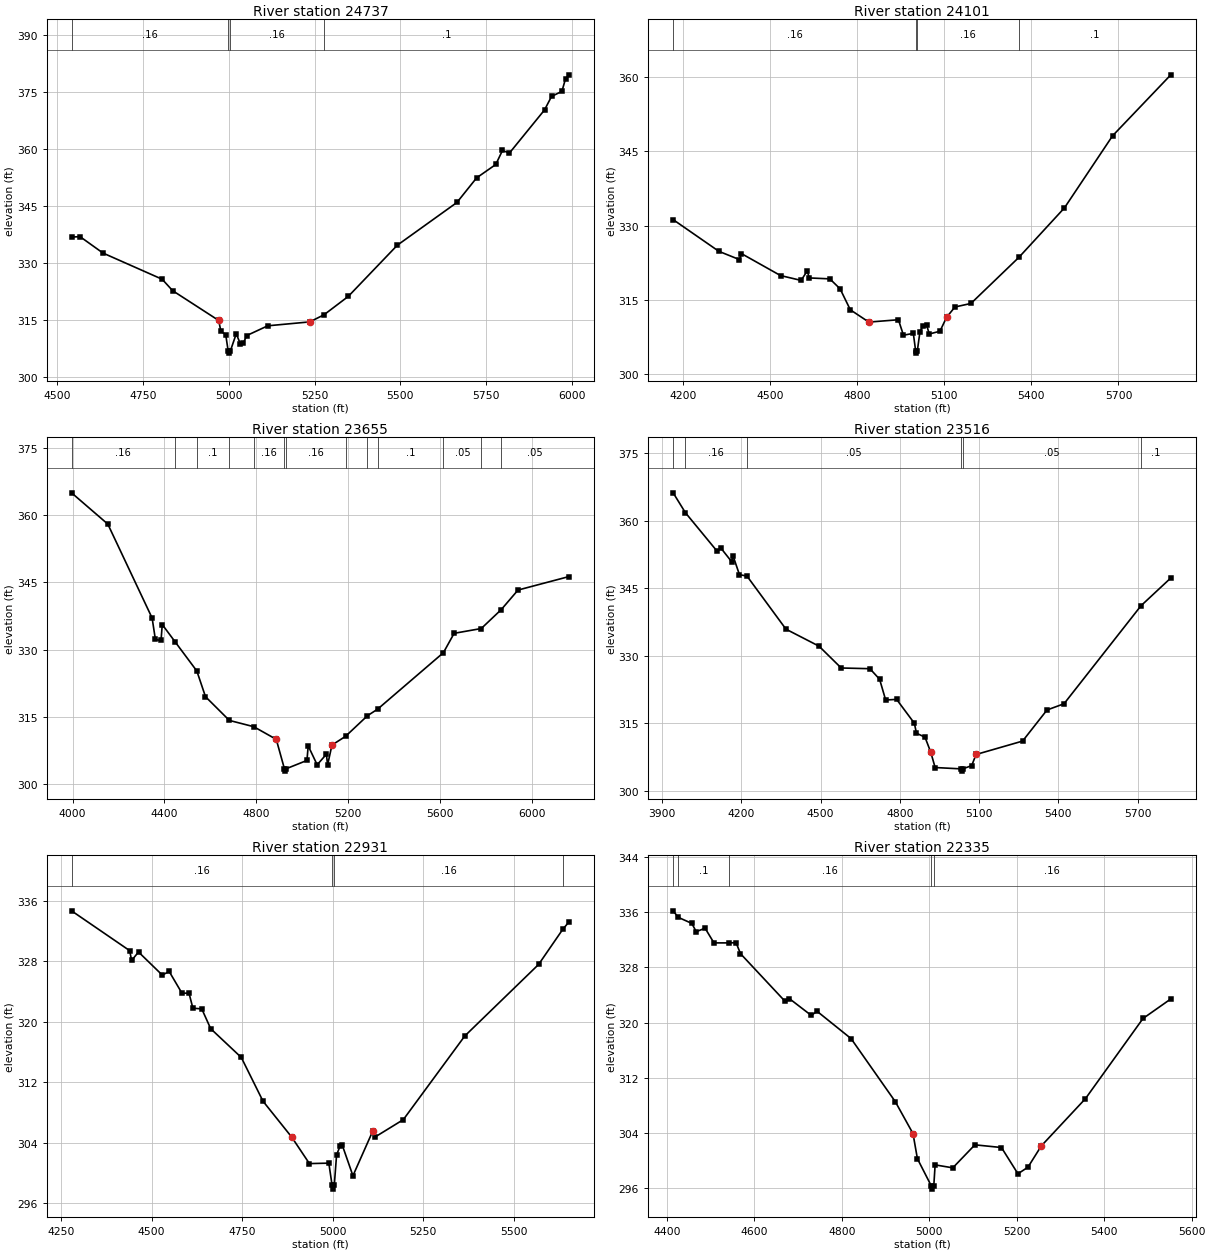
Type RM Length L Ch R = 1 ,24737   ,636,636,636
BEGIN DESCRIPTION:
UNT050 IN BECR 46.0
END DESCRIPTION:
XS GIS Cut Line= 4
      3796558.84     10503386.55      3796251.58     10503188.65
        3796012.     10503141.78      3795189.11     10503308.44
#Sta/Elev= 30
  4542.4   336.9  4567.3  336.99    4634  332.68  4806.3  325.79  4836.7  322.79
    4971  314.94  4977.1  312.15  4991.4  311.19  4998.6  306.85  5001.3  306.35
  5004.6  306.85    5022  311.44  5033.7  308.85  5042.3  308.92  5052.5  310.97
  5113.7  313.54  5236.1  314.57  5277.6  316.44  5348.3  321.28  5491.1  334.75
  5664.6  345.99    5722  352.47  5777.8  355.99  5797.2  359.67  5817.6     359
  5919.7  370.34  5940.1  373.88  5970.4  375.25  5980.9  378.54  5991.6  379.58
#Mann= 4 ,-1 , 0
  4542.4     .16       0  4998.6     .07       0  5004.6     .16       0
  5277.6      .1       0
Bank Sta=4971,5236.1
XS Rating Curve= 0 ,0
Exp/Cntr=0.3,0.1

Type RM Length L Ch R = 1 ,24101   ,446,446,446
BEGIN DESCRIPTION:
UNT050 IN BECR 45.0
END DESCRIPTION:
XS GIS Cut Line= 3
      3796506.81     10503235.55      3795991.17     10502709.49
      3795105.74     10503120.95
#Sta/Elev= 30
  4167.2   331.2  4324.6  324.79  4395.3  323.12  4402.3  324.33  4536.8  319.89
  4607.5  318.91  4628.6   320.8  4635.8  319.41  4706.5  319.22  4741.8  317.21
  4777.1  312.96  4840.8  310.48  4942.6  310.95    4960  307.82  4993.9   308.2
  5001.8   304.7  5004.5   304.2  5007.8   304.7  5016.8  308.55  5026.8  309.66
  5039.7  309.84  5048.9  308.07  5085.5  308.63  5108.4  311.44  5137.1  313.53
  5192.3  314.25  5357.6  323.59  5514.1  333.58  5679.8  348.16  5880.2  360.49
#Mann= 4 ,-1 , 0
  4167.2     .16       0  5001.8     .07       0  5007.8     .16       0
  5357.6      .1       0
Bank Sta=4840.8,5108.4
XS Rating Curve= 0 ,0
Exp/Cntr=0.3,0.1

Type RM Length L Ch R = 1 ,23655   ,139,139,139
BEGIN DESCRIPTION:
UNT050 IN BECR 44.0
END DESCRIPTION:
XS GIS Cut Line= 2
      3797056.76     10502054.31      3795036.38     10502835.38
#Sta/Elev= 30
  3995.7  364.95  4153.5  357.98  4346.4  337.03  4360.6  332.25  4385.2  332.03
  4390.5  335.58  4446.5  331.72    4541  325.22  4578.7  319.49  4682.5   314.2
  4788.6   312.8  4886.7  309.98  4922.4  303.39  4925.1  302.89  4928.4  303.39
  5020.4  305.28  5025.7  308.52  5064.8   304.3  5104.9  306.66  5110.2  304.27
  5129.1   308.7  5188.3  310.65  5283.8  315.25  5327.9  316.71  5614.2   329.3
  5660.9  333.62    5779  334.69  5865.8   338.9    5939  343.27  6161.8  346.29
#Mann= 13 ,-1 , 0
  3995.7     .16       0  4446.5     .05       0    4541      .1       0
  4682.5     .05       0  4788.6     .16       0  4922.4     .07       0
  4928.4     .16       0  5188.3     .05       0  5283.8     .16       0
  5327.9      .1       0  5614.2     .05       0    5779     .16       0
  5865.8     .05       0
Bank Sta=4886.7,5129.1
XS Rating Curve= 0 ,0
Exp/Cntr=0.3,0.1

Type RM Length L Ch R = 1 ,23516   ,585,585,585
BEGIN DESCRIPTION:
UNT050 IN BECR 43.0
END DESCRIPTION:
XS GIS Cut Line= 2
      3797067.18     10501903.27      3795313.32     10502590.24
#Sta/Elev= 30
  3942.2  366.21  3988.6  361.79    4109   353.2  4122.2  353.98  4163.3  350.92
  4168.7  352.23  4193.1  348.02  4221.7   347.7  4369.2   335.9  4494.3  332.12
  4578.3  327.27  4686.9  327.11  4723.6  324.77  4746.5  320.15    4788  320.29
  4855.1  314.99  4863.2  312.76  4895.4  311.89  4916.9   308.6  4933.8  305.14
    5032  304.84  5034.8  304.34    5038  304.84  5072.1  305.56  5088.7  308.04
  5264.8  311.02  5357.2  317.93  5421.7  319.32  5713.2  341.12  5825.8  347.28
#Mann= 6 ,-1 , 0
  3942.2     .05       0  3988.6     .16       0  4221.7     .05       0
    5032     .04       0    5038     .05       0  5713.2      .1       0
Bank Sta=4916.9,5088.7
XS Rating Curve= 0 ,0
Exp/Cntr=0.3,0.1

Type RM Length L Ch R = 1 ,22931   ,596,596,596
BEGIN DESCRIPTION:
UNT050 IN BECR 42.0
END DESCRIPTION:
XS GIS Cut Line= 2
      3796512.03     10501636.56      3795230.75     10502131.36
#Sta/Elev= 30
  4279.3  334.67  4439.7   329.4  4445.1   328.1  4464.1  329.22  4529.6  326.17
  4548.8  326.64  4584.1  323.76  4603.4  323.78  4614.2  321.78  4638.7  321.69
  4663.3  319.07  4747.8  315.26  4807.7  309.47  4886.9  304.72  4935.8  301.21
  4989.4  301.27  4998.4  298.33  5001.1  297.83  5004.4  298.33  5010.8  302.37
  5020.6  303.54    5026  303.72  5055.9   299.6  5110.5   305.5    5118  304.76
    5195  307.03  5364.6   318.1  5568.3  327.57  5635.2  332.23  5652.8  333.24
#Mann= 4 ,-1 , 0
  4279.3     .16       0  4998.4     .07       0  5004.4     .16       0
  5635.2      .1       0
Bank Sta=4886.9,5110.5
XS Rating Curve= 0 ,0
Exp/Cntr=0.3,0.1

Type RM Length L Ch R = 1 ,22335   ,622,622,622
BEGIN DESCRIPTION:
UNT050 IN BECR 41.0
END DESCRIPTION:
XS GIS Cut Line= 2
      3796431.81     10501465.76      3795306.77     10501637.64
#Sta/Elev= 30
  4414.2  336.17  4425.8  335.23  4456.9  334.35    4467  333.15  4487.2  333.66
  4507.5  331.53  4541.7  331.53  4558.1  331.56  4568.2  329.97  4669.3  323.13
  4679.9  323.47    4730  321.04  4743.4  321.63  4821.1  317.68  4922.2  308.56
  4962.7  303.94  4972.8   300.3  5004.3   296.4    5007   295.9  5010.3   296.4
  5013.3  299.41  5053.7  298.98  5104.3  302.31    5165  301.92  5202.7  298.12
  5225.7  299.08  5256.1  302.15  5357.2     309  5488.7  320.59  5552.3  323.42
#Mann= 5 ,-1 , 0
  4414.2     .16       0  4425.8      .1       0  4541.7     .16       0
  5004.3     .07       0  5010.3     .16       0
Bank Sta=4962.7,5256.1
XS Rating Curve= 0 ,0
Exp/Cntr=0.3,0.1

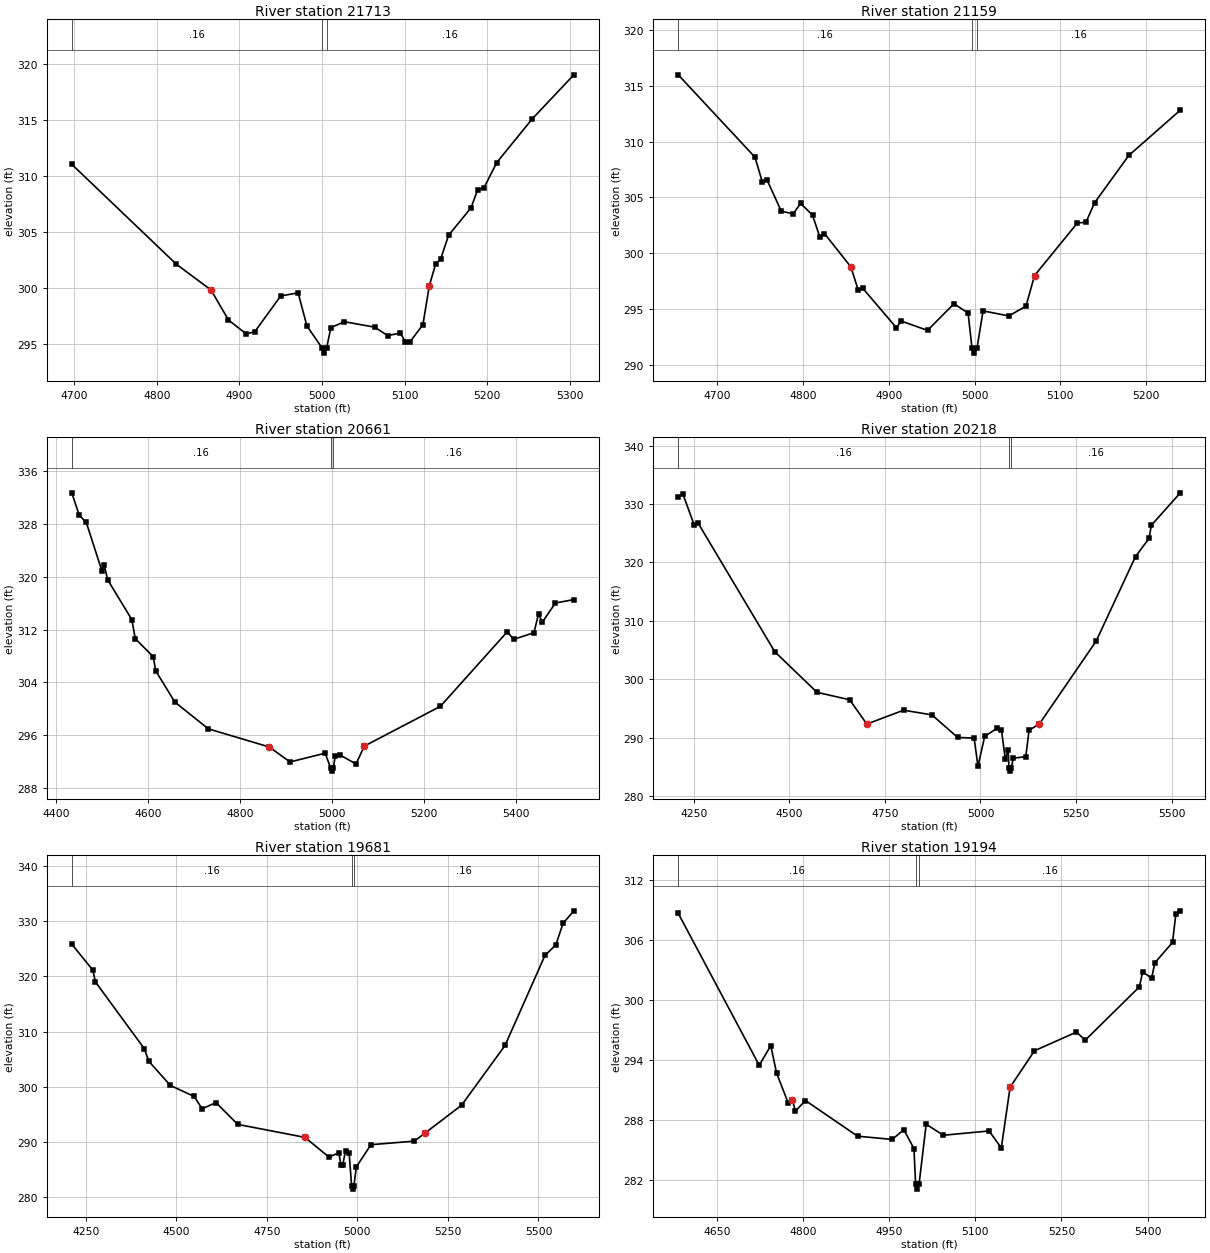
Type RM Length L Ch R = 1 ,21713   ,554,554,554
BEGIN DESCRIPTION:
UNT050 IN BECR 40.0
END DESCRIPTION:
XS GIS Cut Line= 3
      3795999.57     10501310.18      3795699.61     10501210.19
      3795549.63     10500960.22
#Sta/Elev= 30
    4697  311.07  4823.4  302.15  4865.6  299.83  4886.7  297.15  4907.8  295.93
  4918.3  296.08  4949.9   299.3    4971  299.58  4981.6  296.62  4999.6  294.69
  5002.4  294.19  5005.6  294.69  5010.6  296.47  5026.8     297  5063.7  296.51
  5079.3  295.76  5094.8  295.98  5100.7   295.2  5106.5  295.21    5122  296.73
  5129.8  300.23  5137.6   302.2  5143.4  302.58  5153.1  304.73  5180.3  307.18
  5188.1  308.76  5195.9  308.97  5211.4  311.23  5254.2  315.12  5304.7  319.07
#Mann= 3 ,-1 , 0
    4697     .16       0  4999.6     .07       0  5005.6     .16       0
Bank Sta=4865.6,5129.8
XS Rating Curve= 0 ,0
Exp/Cntr=0.3,0.1

Type RM Length L Ch R = 1 ,21159   ,498,498,498
BEGIN DESCRIPTION:
UNT050 IN BECR 39.0
END DESCRIPTION:
XS GIS Cut Line= 3
      3796199.65     10500710.17      3795899.61     10500860.19
      3795649.57     10500860.19
#Sta/Elev= 30
  4654.4     316  4743.9  308.61  4752.3  306.42  4757.9  306.58  4774.6  303.76
  4788.6  303.53    4797  304.47    4811  303.41  4819.4  301.47  4824.9  301.76
  4855.7  298.77  4864.1  296.73  4869.7  296.84  4908.8  293.31  4914.4  293.91
  4945.1  293.07  4975.9  295.46  4992.4  294.63  4996.9  291.53  4999.6  291.03
  5002.9  291.53  5009.9  294.82  5039.9  294.37  5059.9  295.24  5069.9  297.99
  5119.9  302.71  5129.9  302.77  5139.9  304.52  5179.9  308.77  5239.9  312.83
#Mann= 3 ,-1 , 0
  4654.4     .16       0  4996.9     .07       0  5002.9     .16       0
Bank Sta=4855.7,5069.9
XS Rating Curve= 0 ,0
Exp/Cntr=0.3,0.1

Type RM Length L Ch R = 1 ,20661   ,443,443,443
BEGIN DESCRIPTION:
UNT050 IN BECR 38.0
END DESCRIPTION:
XS GIS Cut Line= 4
      3796215.12     10500386.57      3795777.62     10500511.57
       3795574.5     10500600.11      3795407.84     10500980.31
#Sta/Elev= 30
  4434.8  332.72  4450.9  329.36  4466.3  328.24  4500.1  320.94  4505.3  321.72
  4513.3  319.48  4565.3  313.52  4572.9  310.62  4611.9  307.88  4617.3  305.74
  4658.9  301.01  4731.7  296.95  4864.2   294.2  4909.4  291.93  4985.8  293.26
  4997.6  291.04  5000.3  290.54  5003.6  291.04  5007.6   292.8  5018.5  292.97
  5052.9  291.62  5070.8  294.33  5236.3  300.36    5382  311.68  5395.3   310.5
  5439.7  311.52  5449.9  314.41  5457.6  313.08  5486.4  316.02  5526.5  316.54
#Mann= 3 ,-1 , 0
  4434.8     .16       0  4997.6     .07       0  5003.6     .16       0
Bank Sta=4864.2,5070.8
XS Rating Curve= 0 ,0
Exp/Cntr=0.3,0.1

Type RM Length L Ch R = 1 ,20218   ,537,537,537
BEGIN DESCRIPTION:
UNT050 IN BECR 37.0
END DESCRIPTION:
XS GIS Cut Line= 3
      3796251.57     10500266.78      3795449.61     10500210.19
      3794956.14     10500084.85
#Sta/Elev= 30
  4209.5  331.22  4221.5  331.75  4251.6  326.32  4261.6  326.71  4462.1  304.68
  4572.4  297.74  4657.9  296.46  4702.7   292.3  4799.1  294.68  4873.1  293.87
  4940.3  290.01  4983.4   289.9  4993.4  285.05    5011   290.2  5044.4  291.61
  5054.7  291.31    5065  286.24  5072.3  287.92  5074.5  284.74  5077.2  284.24
  5080.5  284.74  5085.7  286.47  5118.4   286.7    5127  291.24  5154.2  292.34
  5302.4   306.5  5405.5     321  5440.8   324.1  5446.8  326.35  5522.6  331.91
#Mann= 3 ,-1 , 0
  4209.5     .16       0  5074.5     .07       0  5080.5     .16       0
Bank Sta=4702.7,5154.2
XS Rating Curve= 0 ,0
Exp/Cntr=0.3,0.1

Type RM Length L Ch R = 1 ,19681   ,487,487,487
BEGIN DESCRIPTION:
UNT050 IN BECR 36.0
END DESCRIPTION:
XS GIS Cut Line= 3
      3796256.76      10500162.6      3795599.61     10499810.19
      3794959.87      10499839.7
#Sta/Elev= 30
  4211.5  325.83  4270.1  321.09  4276.4  319.02  4412.2  306.85  4423.9  304.63
  4483.7  300.23  4549.5  298.23  4571.4     296  4609.6  297.12  4669.7  293.17
  4855.1  290.82  4921.5  287.26  4949.1  288.02  4954.3  285.82  4959.7  285.82
  4967.2  288.43  4977.2     288  4984.2  281.94    4987  281.44  4990.2  281.94
  4997.2  285.47  5037.3  289.49  5157.4  290.14  5187.4  291.63  5287.6  296.64
  5407.7  307.48  5517.8  323.78  5547.8  325.69  5567.8   329.6  5597.6  331.87
#Mann= 3 ,-1 , 0
  4211.5     .16       0  4984.2     .07       0  4990.2     .16       0
Bank Sta=4855.1,5187.4
XS Rating Curve= 0 ,0
Exp/Cntr=0.3,0.1

Type RM Length L Ch R = 1 ,19194   ,400,400,400
BEGIN DESCRIPTION:
UNT050 IN BECR 35.0
END DESCRIPTION:
XS GIS Cut Line= 3
      3796349.58     10499610.18      3795949.61     10499560.19
      3795549.59     10499310.18
#Sta/Elev= 30
  4582.3  308.68  4723.4  293.48  4743.5  295.44  4753.6  292.72  4773.7  289.73
  4781.3  290.04  4786.3  288.89    4804  289.95  4894.7  286.39  4955.1  286.06
  4975.3  287.04    4993  285.15  4995.9  281.59  4998.7  281.09  5001.9  281.59
  5014.3  287.58  5044.3  286.48  5123.9  286.91  5145.2  285.21  5160.5  291.28
    5203  294.93  5276.1   296.8  5291.4  295.99  5385.7  301.32  5391.6  302.83
    5407  302.19  5412.9  303.74  5443.5  305.77  5449.4  308.64  5457.1  308.93
#Mann= 3 ,-1 , 0
  4582.3     .16       0  4995.9     .07       0  5001.9     .16       0
Bank Sta=4781.3,5160.5
XS Rating Curve= 0 ,0
Exp/Cntr=0.3,0.1

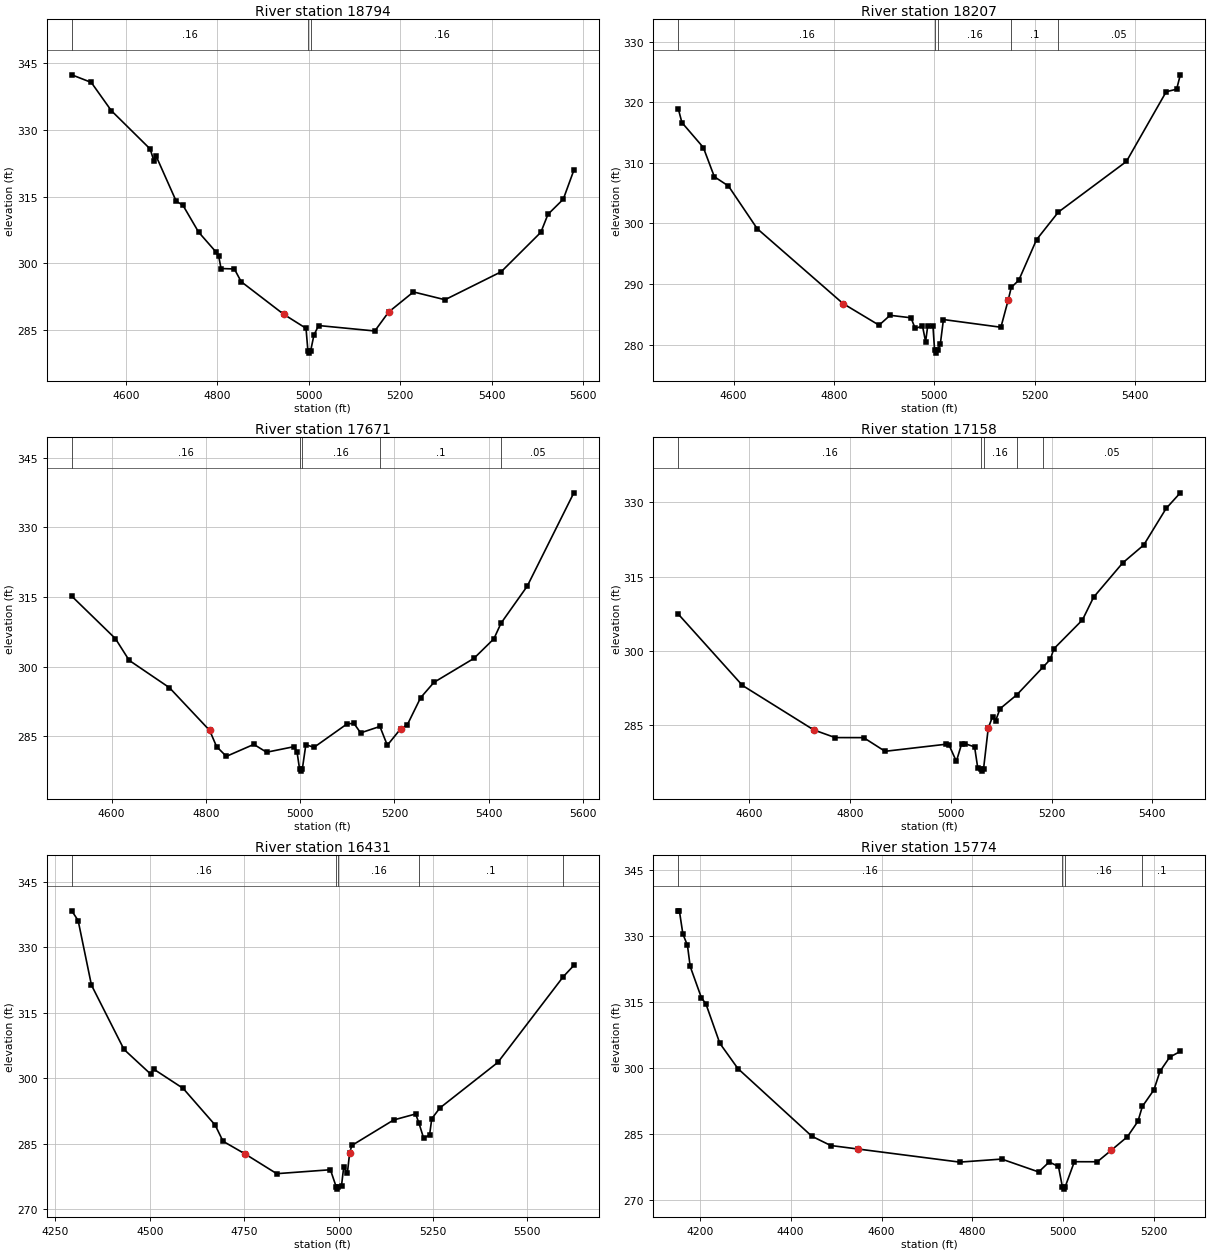
Type RM Length L Ch R = 1 ,18794   ,587,587,587
BEGIN DESCRIPTION:
UNT050 IN BECR 34.0
END DESCRIPTION:
XS GIS Cut Line= 2
      3796687.01      10499424.1      3795614.31     10499189.78
#Sta/Elev= 30
  4481.5  342.31  4524.1  340.61    4568  334.27  4652.9  325.67  4660.9  323.06
    4666  324.07  4709.9  313.95  4724.5  313.06  4758.9  307.01  4796.2  302.64
  4802.8   301.6    4808  298.84  4837.1  298.75  4851.9   295.9  4944.8  288.59
  4993.8  285.43  4997.9  280.36  5000.6  279.86  5003.9  280.36  5011.1  283.92
  5021.3  286.05  5144.2  284.83  5174.5  289.08  5228.7  293.59  5297.7  291.84
  5420.5  298.11  5507.4  306.98  5522.9  311.01  5556.4   314.4  5579.5   320.9
#Mann= 3 ,-1 , 0
  4481.5     .16       0  4997.9     .07       0  5003.9     .16       0
Bank Sta=4944.8,5174.5
XS Rating Curve= 0 ,0
Exp/Cntr=0.3,0.1

Type RM Length L Ch R = 1 ,18207   ,536,536,536
BEGIN DESCRIPTION:
UNT050 IN BECR 33.0
END DESCRIPTION:
XS GIS Cut Line= 3
      3796549.63      10499260.2      3796149.61     10498960.19
      3795749.63      10498660.2
#Sta/Elev= 30
  4489.8  318.95  4497.1  316.65  4539.8  312.53  4561.7  307.71  4589.8  306.18
  4647.1  299.14    4818  286.79  4889.8  283.22  4911.7  284.85  4953.4  284.44
  4961.7  282.68  4976.3  283.08  4982.5   280.5  4986.7  283.08  4997.1  283.11
  5000.4  279.11  5003.1  278.61  5006.4  279.11  5011.7  280.04    5018  284.15
  5132.5  282.88  5147.1   287.4  5153.1  289.46    5168  290.62  5203.4  297.32
  5246.8  301.87  5382.5  310.23  5461.7  321.73  5482.5  322.15  5489.8  324.52
#Mann= 5 ,-1 , 0
  4489.8     .16       0  5000.4     .07       0  5006.4     .16       0
  5153.1      .1       0  5246.8     .05       0
Bank Sta=4818,5147.1
XS Rating Curve= 0 ,0
Exp/Cntr=0.3,0.1

Type RM Length L Ch R = 1 ,17671   ,513,513,513
BEGIN DESCRIPTION:
UNT050 IN BECR 32.0
END DESCRIPTION:
XS GIS Cut Line= 3
      3796599.58     10498910.17      3796199.61     10498610.19
      3795799.64     10498210.22
#Sta/Elev= 30
  4515.3  315.19    4608  306.04  4637.1  301.37  4722.6  295.48    4808  286.27
  4822.6   282.8  4843.4  280.69  4901.7  283.27  4928.8  281.58  4987.1  282.78
  4993.4  281.64  4998.7  278.01  5001.5  277.51  5004.7  278.01  5012.1  283.21
  5029.4  282.63  5100.1  287.72  5114.3  287.77  5128.4  285.75  5169.3  287.13
    5185  283.08  5213.3  286.62  5227.4  287.48  5255.7  293.32    5284  296.63
  5368.8  301.79  5411.2  306.01  5426.4  309.38    5482  317.35  5580.9  337.45
#Mann= 5 ,-1 , 0
  4515.3     .16       0  4998.7     .07       0  5004.7     .16       0
  5169.3      .1       0  5426.4     .05       0
Bank Sta=4808,5213.3
XS Rating Curve= 0 ,0
Exp/Cntr=0.3,0.1

Type RM Length L Ch R = 1 ,17158   ,727,727,727
BEGIN DESCRIPTION:
UNT050 IN BECR 31.0
END DESCRIPTION:
XS GIS Cut Line= 3
      3796699.64     10498660.22      3796299.61     10498260.19
      3795949.64     10498010.21
#Sta/Elev= 30
  4459.5  307.46  4586.8  293.06  4728.2  284.08  4770.7  282.53  4827.2  282.52
  4869.7  279.76  4989.9  281.18  4996.9  280.97  5011.1  277.73  5021.7   281.3
  5028.3   281.3  5047.3  280.65  5053.5  276.43  5059.1  276.26  5061.8  275.76
  5065.1  276.26  5074.4  284.47    5083  286.77  5089.1  285.96  5097.7  288.35
  5131.1  291.17  5182.8  296.73  5197.3   298.3  5204.6  300.46  5261.2  306.28
  5283.3  310.86  5341.1  317.79  5382.8   321.4  5427.1  328.77  5455.3  331.93
#Mann= 5 ,-1 , 0
  4459.5     .16       0  5059.1     .07       0  5065.1     .16       0
  5131.1      .1       0  5182.8     .05       0
Bank Sta=4728.2,5074.4
XS Rating Curve= 0 ,0
Exp/Cntr=0.3,0.1

Type RM Length L Ch R = 1 ,16431   ,657,657,657
BEGIN DESCRIPTION:
UNT050 IN BECR 30.0
END DESCRIPTION:
XS GIS Cut Line= 3
      3796944.28     10498459.47      3796499.61     10497910.19
      3795965.14     10497589.71
#Sta/Elev= 30
  4293.3  338.36  4310.2  336.13  4345.4  321.35  4431.6  306.61    4502  300.98
    4510  302.11  4588.3  297.68  4673.1  289.28  4693.9  285.57  4751.4  282.71
  4836.2  278.14  4978.4  279.04  4993.8   275.1  4996.5   274.6  4999.8   275.1
  5007.8   275.4  5013.6  279.64  5023.3  278.24  5029.2  282.81    5035   284.6
  5145.8  290.44  5204.1  291.82  5212.9  289.72  5225.5  286.22  5241.1  287.06
  5246.9  290.74  5268.3  293.19  5421.8  303.63    5595  323.25  5623.2  325.86
#Mann= 5 ,-1 , 0
  4293.3     .16       0  4993.8     .07       0  4999.8     .16       0
  5212.9      .1       0    5595     .05       0
Bank Sta=4751.4,5029.2
XS Rating Curve= 0 ,0
Exp/Cntr=0.3,0.1

Type RM Length L Ch R = 1 ,15774   ,539,539,539
BEGIN DESCRIPTION:
UNT050 IN BECR 29.0
END DESCRIPTION:
XS GIS Cut Line= 3
      3796999.61     10498410.17      3796849.61     10497610.19
      3796699.59     10497360.16
#Sta/Elev= 30
  4152.4  335.69  4154.9  335.69  4162.6  330.45  4172.7  327.84  4178.7  323.08
  4203.3  315.99  4213.4  314.55    4244  305.62  4283.8  299.89  4446.6  284.53
  4488.1  282.43  4549.2  281.62  4772.2  278.66  4864.6  279.35    4946  276.43
  4969.2  278.69  4989.6  277.67  4998.3  273.03  5001.1  272.53  5004.3  273.03
  5024.6  278.75  5075.2  278.74  5106.3  281.39  5141.3  284.41  5164.6  287.92
  5174.3  291.29  5199.6  295.03  5213.2  299.27  5234.5  302.48  5257.9  303.79
#Mann= 4 ,-1 , 0
  4152.4     .16       0  4998.3     .07       0  5004.3     .16       0
  5174.3      .1       0
Bank Sta=4549.2,5106.3
XS Rating Curve= 0 ,0
Exp/Cntr=0.3,0.1

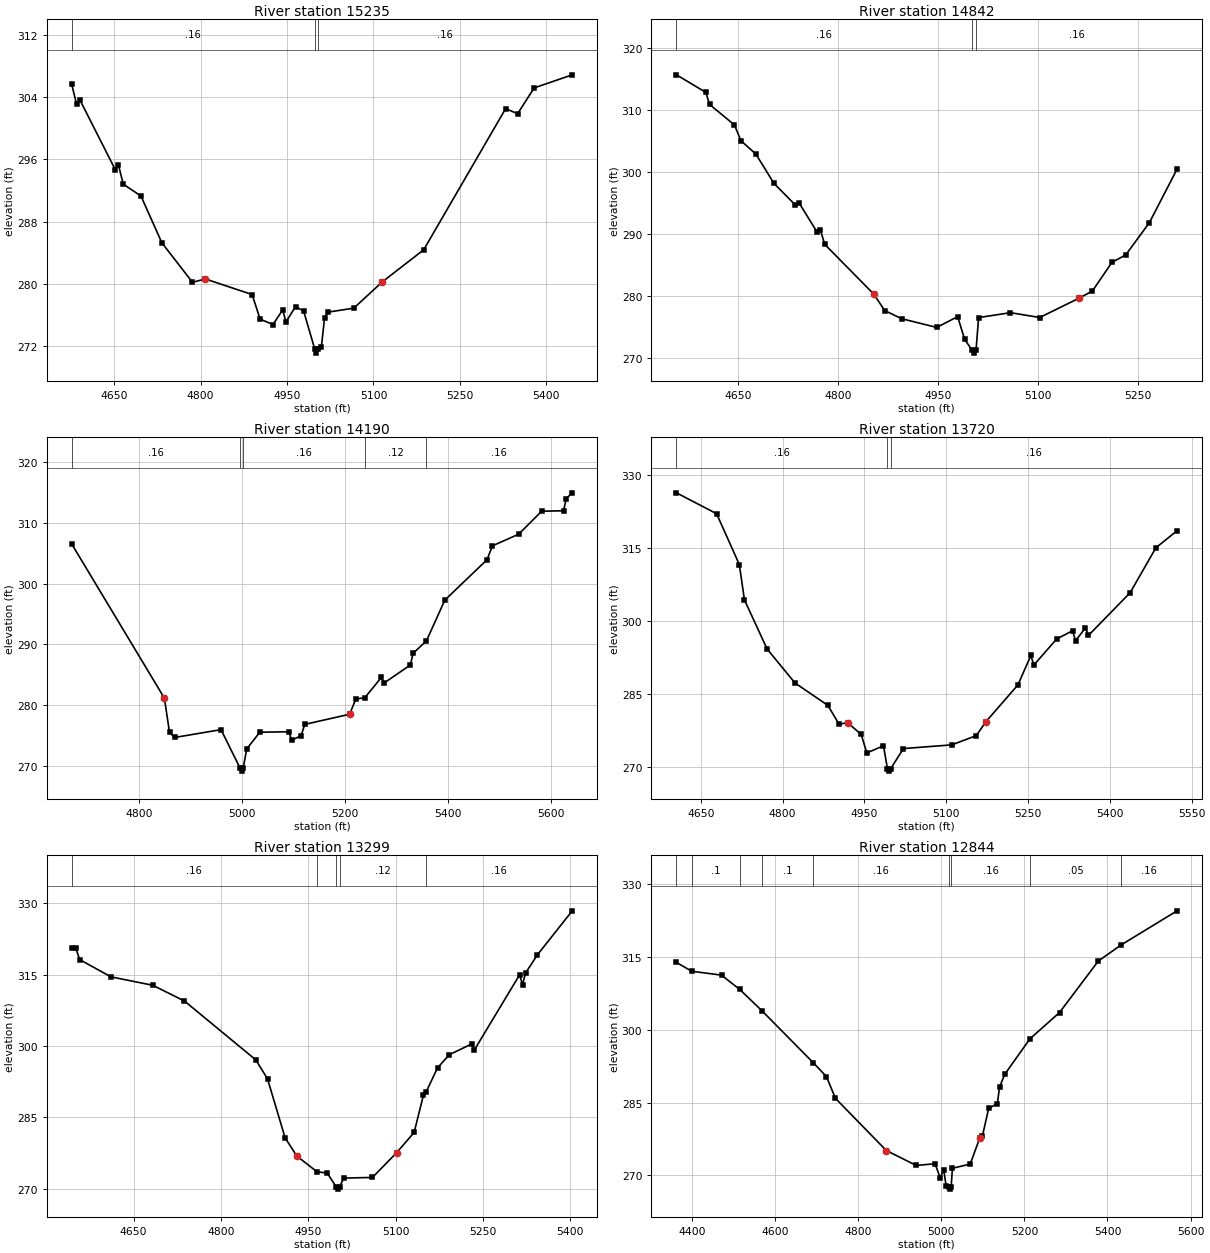
Type RM Length L Ch R = 1 ,15235   ,393,393,393
BEGIN DESCRIPTION:
UNT050 IN BECR 28.0
END DESCRIPTION:
XS GIS Cut Line= 3
      3797549.62      10497560.2      3797149.61     10497360.19
      3796882.94     10497033.81
#Sta/Elev= 30
  4576.3  305.62  4584.7  303.09  4590.3  303.65  4651.8  294.67  4657.4  295.28
  4665.8  292.79  4696.5  291.28  4732.8  285.27  4785.9   280.2  4808.3  280.63
  4889.4  278.63  4903.3  275.47  4925.7  274.78  4942.5  276.66  4948.1  275.12
  4964.8  277.07  4978.8  276.52  4998.2  271.61  5000.9  271.11  5004.2  271.61
  5009.6   271.9  5015.1  275.58  5020.7  276.37  5065.9  276.88  5115.4  280.26
  5187.2  284.37  5329.4  302.49  5350.2  301.84  5378.9  305.15    5445  306.83
#Mann= 3 ,-1 , 0
  4576.3     .16       0  4998.2     .07       0  5004.2     .16       0
Bank Sta=4808.3,5115.4
XS Rating Curve= 0 ,0
Exp/Cntr=0.3,0.1

Type RM Length L Ch R = 1 ,14842   ,652,652,652
BEGIN DESCRIPTION:
UNT050 IN BECR 27.0
END DESCRIPTION:
XS GIS Cut Line= 3
      3797751.61     10497230.33      3797273.57      10497077.9
       3797074.1     10496928.29
#Sta/Elev= 30
  4557.5  315.65  4601.6  312.81  4607.1  310.87  4644.5  307.56  4654.1  305.03
  4676.7  302.85  4703.7  298.14  4735.9  294.63  4741.1  295.04  4768.1  290.33
  4773.3  290.67    4780  288.28  4853.5  280.26    4870   277.6  4895.5  276.28
    4948  274.88  4979.4  276.62  4989.9  272.95    5001  271.23  5003.8  270.73
    5007  271.23  5010.9  276.47  5058.7  277.26  5102.5  276.48  5160.9  279.56
  5181.7  280.77  5210.9  285.38  5231.7  286.59  5267.1  291.79  5308.6  300.42
#Mann= 3 ,-1 , 0
  4557.5     .16       0    5001     .07       0    5007     .16       0
Bank Sta=4853.5,5160.9
XS Rating Curve= 0 ,0
Exp/Cntr=0.3,0.1

Type RM Length L Ch R = 1 ,14190   ,470,470,470
BEGIN DESCRIPTION:
UNT050 IN BECR 26.0
END DESCRIPTION:
XS GIS Cut Line= 3
      3797799.65     10496660.19      3797449.61     10496660.19
      3796863.66     10496451.33
#Sta/Elev= 30
  4669.1  306.56  4849.1  281.13  4859.1  275.47  4869.1  274.64  4959.1  275.93
  4996.1  269.59  4998.9  269.09  5002.1  269.59  5009.1  272.76  5034.5  275.51
  5090.9  275.58  5096.2  274.17  5114.7  274.95  5121.7   276.8  5208.8  278.47
  5220.9  280.99  5238.3  281.19  5270.5  284.54  5275.8  283.62  5326.8   286.6
  5332.1  288.52    5358  290.57  5393.7  297.29  5475.6  303.95  5486.3  306.25
  5537.2  308.17  5581.8  311.96  5624.3  312.03  5629.6  314.04  5641.2  314.99
#Mann= 5 ,-1 , 0
  4669.1     .16       0  4996.1     .07       0  5002.1     .16       0
  5238.3     .12       0    5358     .16       0
Bank Sta=4849.1,5208.8
XS Rating Curve= 0 ,0
Exp/Cntr=0.3,0.1

Type RM Length L Ch R = 1 ,13720   ,421,421,421
BEGIN DESCRIPTION:
UNT050 IN BECR 25.0
END DESCRIPTION:
XS GIS Cut Line= 3
      3797881.76     10496183.45        3797387.      10496282.4
      3797006.82     10496120.96
#Sta/Elev= 30
  4605.6  326.37  4679.2  322.07  4720.8  311.62  4730.2  304.36  4771.7  294.25
  4822.7  287.28  4883.1  282.65  4903.5  278.81  4919.6  279.07  4944.3  276.67
  4954.5  272.87  4985.1  274.34  4992.3  269.63  4995.1  269.13  4998.3  269.63
  5021.6  273.77  5110.2  274.53  5155.2  276.43  5172.5  279.25  5231.6  286.88
  5255.3  292.92  5260.7  290.95  5302.6  296.31  5331.7  298.01  5337.1  295.95
  5355.3  298.57  5360.8  297.04  5437.2  305.82  5484.5  315.07  5523.2  318.57
#Mann= 3 ,-1 , 0
  4605.6     .16       0  4992.3     .07       0  4998.3     .16       0
Bank Sta=4919.6,5172.5
XS Rating Curve= 0 ,0
Exp/Cntr=0.3,0.1

Type RM Length L Ch R = 1 ,13299   ,455,455,455
BEGIN DESCRIPTION:
UNT050 IN BECR 24.0
END DESCRIPTION:
XS GIS Cut Line= 3
      3797881.75     10496048.01      3797626.58     10495912.61
      3797060.06     10495845.04
#Sta/Elev= 30
  4543.8  320.55  4550.8  320.56  4557.5  318.16  4611.2  314.53  4682.8  312.77
  4737.4  309.45  4859.8  297.09    4880  293.09  4910.2   280.7  4930.3  276.86
  4964.7  273.59  4982.7  273.26  4997.8  270.41  5000.6  269.91  5003.8  270.41
  5010.9  272.23  5060.2  272.37  5101.5  277.54  5131.7  281.82  5147.8  289.71
  5151.9  290.24    5172  295.41  5192.2  298.17  5230.3  300.41  5235.3  299.19
  5312.8  314.96  5317.8   312.9  5323.1  315.34  5343.2  319.13  5403.2  328.41
#Mann= 5 ,-1 , 0
  4543.8     .16       0  4964.7     .12       0  4997.8     .07       0
  5003.8     .12       0  5151.9     .16       0
Bank Sta=4930.3,5101.5
XS Rating Curve= 0 ,0
Exp/Cntr=0.3,0.1

Type RM Length L Ch R = 1 ,12844   ,498,498,498
BEGIN DESCRIPTION:
UNT050 IN BECR 23.0
END DESCRIPTION:
XS GIS Cut Line= 3
      3798078.04     10495843.37        3797427.     10495409.34
      3797027.71     10495548.22
#Sta/Elev= 30
  4362.3  313.84  4398.8  312.03  4470.9  311.22  4514.6  308.28  4568.7  303.84
  4691.8  293.18  4723.3  290.36    4745  285.87  4867.5  275.13  4939.6  272.05
  4984.7  272.41  4997.4  269.53  5005.7  271.17  5011.7  267.79  5017.7  267.68
  5020.5  267.18  5023.7  267.68  5026.7  271.47  5069.5  272.34  5092.8  277.75
  5098.9  278.09  5113.9  283.79  5134.9   284.8  5140.2  288.17  5152.6   290.8
  5213.4  298.12  5284.6  303.53  5377.9  314.12  5432.6  317.42  5567.5  324.46
#Mann= 9 ,-1 , 0
  4362.3     .16       0  4398.8      .1       0  4514.6     .16       0
  4568.7      .1       0  4691.8     .16       0  5017.7     .07       0
  5023.7     .16       0  5213.4     .05       0  5432.6     .16       0
Bank Sta=4867.5,5092.8
XS Rating Curve= 0 ,0
Exp/Cntr=0.3,0.1