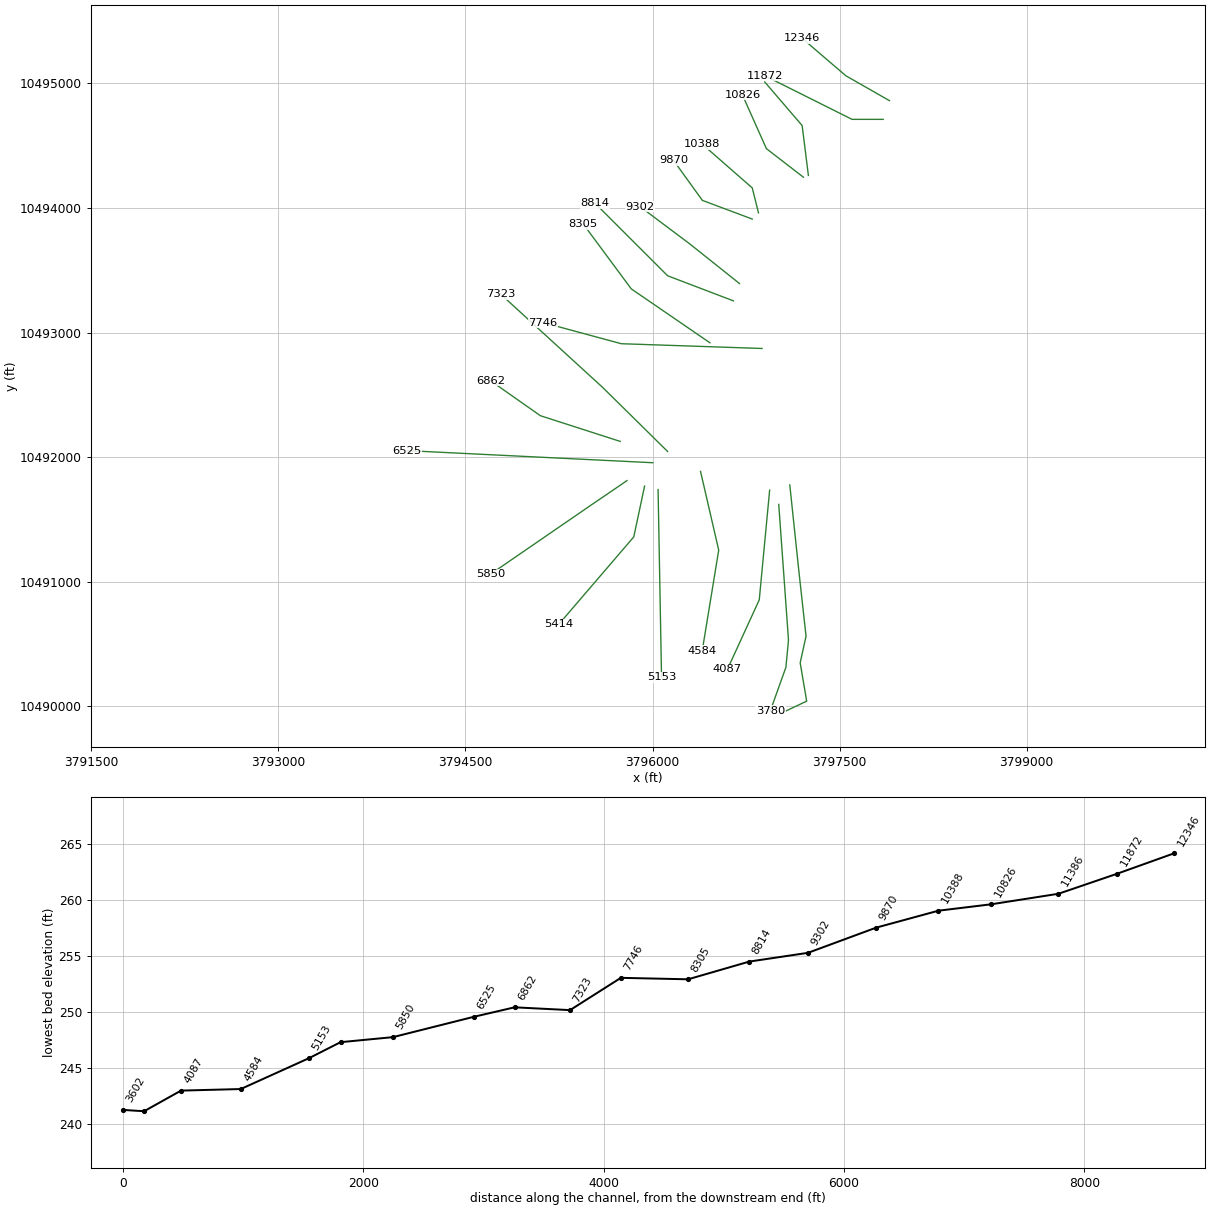
HEC-RAS study UNT050 IN BECR.prj: UNT050 IN BECR Base Level Engineering

--- UNT050 IN BECR.g01 (geometry) --- (continued)

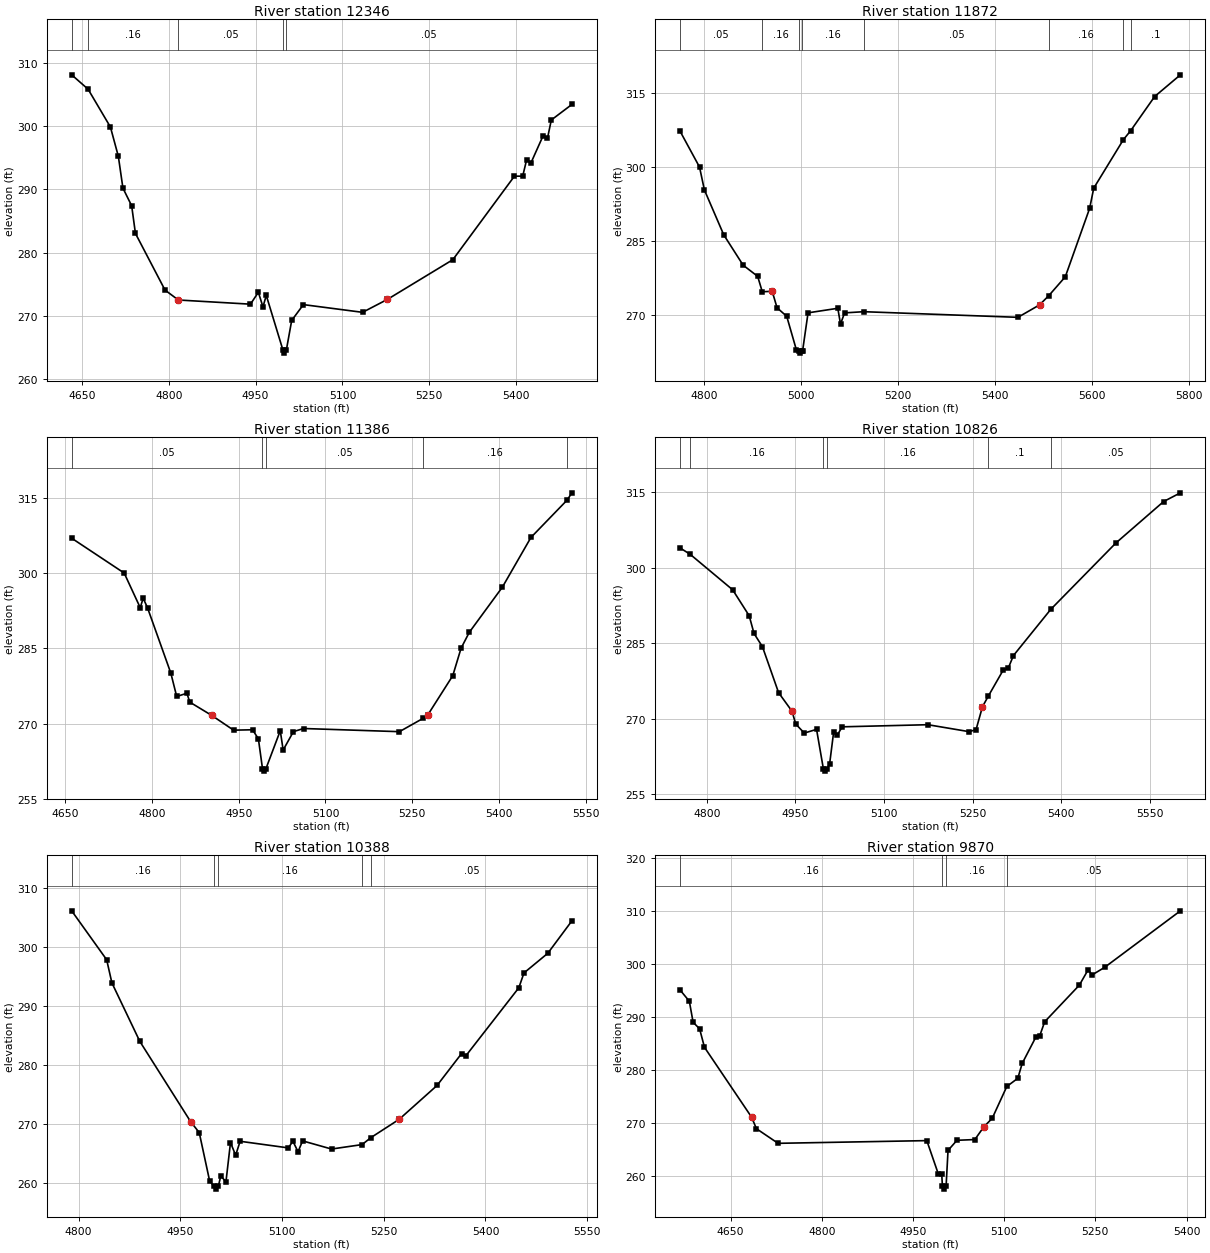
Type RM Length L Ch R = 1 ,12346   ,474,474,474
BEGIN DESCRIPTION:
UNT050 IN BECR 22.0
END DESCRIPTION:
XS GIS Cut Line= 3
      3797899.57     10494860.21      3797549.61     10495060.19
      3797199.64     10495360.16
#Sta/Elev= 30
  4632.3  308.12  4660.6  305.85  4699.2  299.87  4712.9  295.23  4720.8  290.21
  4735.9  287.42  4742.4  283.05  4793.5  274.09  4816.2  272.54  4816.5  272.52
  4941.1  271.86  4954.7  273.74  4962.7  271.43  4968.4  273.25  4997.1  264.62
  4999.8  264.12  5003.1  264.62  5012.3  269.29  5032.5  271.79  5134.7  270.57
  5177.5  272.61  5290.6  278.89    5397   292.1  5411.3   292.1  5417.9  294.63
  5425.6  294.21  5446.4  298.46  5454.1   298.1  5460.7  300.98  5496.3  303.44
#Mann= 5 ,-1 , 0
  4632.3     .05       0  4660.6     .16       0  4816.2     .05       0
  4997.1     .03       0  5003.1     .05       0
Bank Sta=4816.5,5177.5
XS Rating Curve= 0 ,0
Exp/Cntr=0.3,0.1

Type RM Length L Ch R = 1 ,11872   ,486,486,486
BEGIN DESCRIPTION:
UNT050 IN BECR 21.0
END DESCRIPTION:
XS GIS Cut Line= 3
      3797849.58     10494710.19      3797599.61     10494710.19
      3796899.61     10495060.19
#Sta/Elev= 30
  4750.4  307.21  4790.4  299.98  4800.4  295.36  4840.4  286.25  4880.4  280.11
  4910.4  277.85  4919.9  274.73  4940.4  274.82  4950.4  271.49  4970.4  269.75
  4990.4  262.93  4994.9   262.8  4997.6   262.3  5000.9   262.8  5003.2   262.8
  5014.4  270.46  5075.8  271.38  5081.4  268.19  5089.8  270.45  5129.5  270.69
  5447.6  269.55  5492.3  272.07  5511.4  273.95  5545.4  277.76  5595.7  291.64
  5604.1  295.71  5665.3  305.53  5680.6  307.38  5729.9  314.27    5783  318.66
#Mann= 8 ,-1 , 0
  4750.4     .05       0  4919.9     .16       0  4994.9     .07       0
  5000.9     .16       0  5129.5     .05       0  5511.4     .16       0
  5665.3     .05       0  5680.6      .1       0
Bank Sta=4940.4,5492.3
XS Rating Curve= 0 ,0
Exp/Cntr=0.3,0.1

Type RM Length L Ch R = 1 ,11386   ,560,560,560
BEGIN DESCRIPTION:
UNT050 IN BECR 20.0
END DESCRIPTION:
XS GIS Cut Line= 3
      3797249.61     10494260.18      3797199.61     10494660.19
      3796899.61     10495010.19
#Sta/Elev= 30
  4661.6  306.92  4752.3  299.98    4780  293.08  4785.1  294.97  4792.6  293.06
  4832.9  280.03    4843  275.39  4860.6  276.03  4865.7  274.26  4903.5  271.62
  4941.3  268.68    4974  268.76  4984.1  266.96  4991.2  261.02  4993.9  260.52
  4997.2  261.02  5021.9  268.57  5026.9  264.72  5044.6  268.39  5062.2  269.01
  5227.7  268.38  5268.7  271.04  5277.1  271.78  5319.9  279.54  5334.2     285
  5348.4  288.17  5405.5  297.16  5454.9  307.07  5517.2  314.49  5525.7  315.96
#Mann= 5 ,-1 , 0
  4661.6     .05       0  4991.2     .03       0  4997.2     .05       0
  5268.7     .16       0  5517.2      .1       0
Bank Sta=4903.5,5277.1
XS Rating Curve= 0 ,0
Exp/Cntr=0.3,0.1

Type RM Length L Ch R = 1 ,10826   ,438,438,438
BEGIN DESCRIPTION:
UNT050 IN BECR 19.0
END DESCRIPTION:
XS GIS Cut Line= 3
      3797209.94     10494245.92      3796913.04     10494475.11
      3796720.81     10494906.33
#Sta/Elev= 30
  4754.7  303.95  4771.6   302.7  4843.6  295.64  4871.6  290.48  4879.8  286.95
  4894.1  284.31  4921.4  275.18  4944.1   271.5  4950.4  268.95  4964.9  267.15
  4985.7  267.88  4997.2  260.08    5000  259.58  5003.2  260.08  5007.8  260.99
  5014.7   267.4    5021  266.79  5029.2  268.39  5174.3  268.81    5244  267.43
  5255.8  267.82  5266.7  272.39  5276.6   274.5  5301.4  279.59  5310.5   280.1
  5319.2  282.57  5382.3  291.74  5492.7  304.95  5573.4  313.18  5601.9  314.92
#Mann= 6 ,-1 , 0
  4754.7     .05       0  4771.6     .16       0  4997.2     .07       0
  5003.2     .16       0  5276.6      .1       0  5382.3     .05       0
Bank Sta=4944.1,5266.7
XS Rating Curve= 0 ,0
Exp/Cntr=0.3,0.1

Type RM Length L Ch R = 1 ,10388   ,518,518,518
BEGIN DESCRIPTION:
UNT050 IN BECR 18.0
END DESCRIPTION:
XS GIS Cut Line= 3
      3796849.61     10493960.17      3796799.61     10494160.19
       3796399.6      10494510.2
#Sta/Elev= 30
  4789.8  306.07  4841.4   297.8  4849.1  293.89  4890.3  283.99  4965.1  270.44
  4977.9  268.57  4993.4  260.31  5000.1  259.51  5002.8  259.01  5006.1  259.51
  5009.7  261.25  5017.3  260.24    5024  266.88  5031.6  264.74  5038.2   267.1
  5109.4  265.98    5116  267.12  5123.6  265.33  5130.3  267.17    5173  265.79
    5218  266.54  5231.3  267.74  5272.6   270.8  5328.6  276.54  5364.7  281.92
  5371.4   281.6  5449.2  293.06  5456.8  295.57  5491.9  298.89  5527.5  304.38
#Mann= 5 ,-1 , 0
  4789.8     .16       0  5000.1     .07       0  5006.1     .16       0
    5218      .1       0  5231.3     .05       0
Bank Sta=4965.1,5272.6
XS Rating Curve= 0 ,0
Exp/Cntr=0.3,0.1

Type RM Length L Ch R = 1 ,9870    ,568,568,568
BEGIN DESCRIPTION:
UNT050 IN BECR 17.0
END DESCRIPTION:
XS GIS Cut Line= 3
      3796799.58      10493910.2      3796399.61     10494060.19
      3796168.25     10494381.36
#Sta/Elev= 30
  4566.9  295.08    4582  292.98  4588.2  289.01  4598.9  287.77  4606.9  284.28
  4684.3  271.11  4692.4  268.91    4728  266.15  4972.7  266.66  4991.4  260.44
  4997.2  260.44  4998.4     258  5001.2   257.5  5004.4     258  5007.6  264.81
  5022.3  266.72  5051.7  266.86  5066.5  269.26  5080.3  270.87  5104.3  276.88
  5122.4  278.43  5129.6  281.23  5152.4  286.28  5158.5  286.46  5166.6   289.1
  5223.6  296.01  5238.3  298.96  5244.4  297.93  5265.3  299.38  5389.9  310.05
#Mann= 4 ,-1 , 0
  4566.9     .16       0  4998.4     .07       0  5004.4     .16       0
  5104.3     .05       0
Bank Sta=4684.3,5066.5
XS Rating Curve= 0 ,0
Exp/Cntr=0.3,0.1

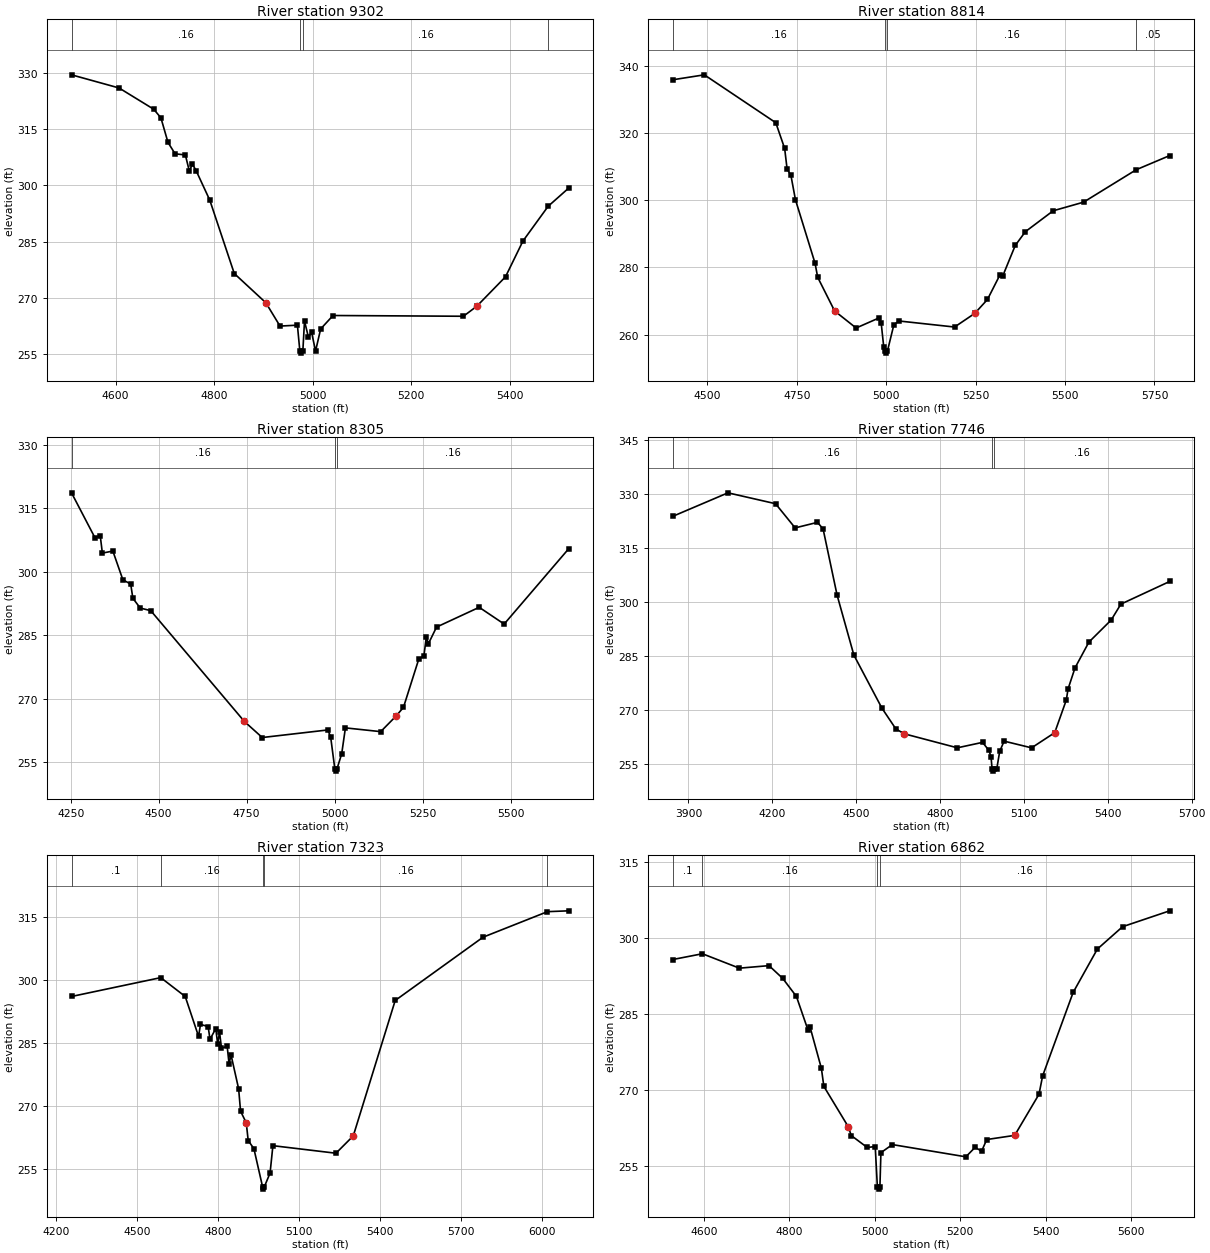
Type RM Length L Ch R = 1 ,9302    ,488,488,488
BEGIN DESCRIPTION:
UNT050 IN BECR 16.0
END DESCRIPTION:
XS GIS Cut Line= 3
      3796697.36     10493392.87      3796299.61     10493710.19
      3795899.62     10494010.18
#Sta/Elev= 30
  4510.6  329.52  4607.1  326.01  4677.5  320.33    4692  318.04  4706.4  311.47
  4720.8  308.44  4741.6  308.14  4749.6  303.87    4756  305.66  4763.6  303.91
  4791.2  296.07  4840.9  276.49  4904.9   268.7  4933.7  262.47    4969  262.71
    4974  255.75  4976.7  255.25    4980  255.75  4983.4  263.79  4991.4  259.49
  4997.8  260.81  5005.8  255.79  5016.2  261.71  5041.3  265.29  5305.9  265.09
    5333  267.76  5391.3  275.62  5426.7  285.17  5477.9  294.45  5519.4  299.28
#Mann= 4 ,-1 , 0
  4510.6     .16       0    4974     .07       0    4980     .16       0
  5477.9     .05       0
Bank Sta=4904.9,5333
XS Rating Curve= 0 ,0
Exp/Cntr=0.3,0.1

Type RM Length L Ch R = 1 ,8814    ,509,509,509
BEGIN DESCRIPTION:
UNT050 IN BECR 15.0
END DESCRIPTION:
XS GIS Cut Line= 3
      3796648.82     10493253.94      3796121.01     10493455.35
      3795537.67     10494038.68
#Sta/Elev= 30
  4402.5  335.75  4491.4  337.23  4691.2  322.99    4716  315.35  4722.8  309.24
  4733.5  307.34  4746.1  300.12  4800.9  281.23  4808.4  277.02  4855.7  267.01
  4915.8  261.94  4978.9  264.89    4986  263.32  4993.1  256.25  4997.1  254.97
  4999.9  254.47  5003.1  254.97  5021.3  262.88  5035.5  264.03  5191.1  262.23
  5247.6  266.29    5283  270.42  5318.3  277.81  5325.4  277.31  5360.8   286.5
    5389  290.58  5466.8   296.8  5551.7  299.36    5699  309.01  5792.4  313.21
#Mann= 4 ,-1 , 0
  4402.5     .16       0  4997.1     .07       0  5003.1     .16       0
    5699     .05       0
Bank Sta=4855.7,5247.6
XS Rating Curve= 0 ,0
Exp/Cntr=0.3,0.1

Type RM Length L Ch R = 1 ,8305    ,559,559,559
BEGIN DESCRIPTION:
UNT050 IN BECR 14.0
END DESCRIPTION:
XS GIS Cut Line= 3
      3796459.95      10492917.8      3795829.71     10493350.11
      3795444.46     10493870.71
#Sta/Elev= 30
  4252.5  318.65  4319.1  308.03    4334  308.54  4340.1  304.41  4369.9  304.89
  4398.4  298.09  4420.6   297.1  4426.7  293.74  4447.7  291.42  4477.5  290.81
  4743.5  264.62  4794.2  260.83  4980.5  262.62  4988.5  260.96  5000.4  253.39
  5003.1  252.89  5006.4  253.39  5019.9  257.01  5030.4  263.11  5130.6  262.22
  5174.5  265.92  5195.3  267.96  5239.2  279.48  5253.2  280.03  5260.1   284.5
  5266.3  283.03  5289.3  286.93  5410.4   291.6  5481.3  287.64  5664.4  305.42
#Mann= 3 ,-1 , 0
  4252.5     .16       0  5000.4     .07       0  5006.4     .16       0
Bank Sta=4743.5,5174.5
XS Rating Curve= 0 ,0
Exp/Cntr=0.3,0.1

Type RM Length L Ch R = 1 ,7746    ,423,423,423
BEGIN DESCRIPTION:
UNT050 IN BECR 13.0
END DESCRIPTION:
XS GIS Cut Line= 3
      3796877.93     10492872.01      3795749.61     10492910.19
      3795122.84     10493079.85
#Sta/Elev= 30
  3842.9  323.69  4041.3  330.24  4211.4  327.22  4281.5  320.51  4361.5  322.05
  4381.5  320.22  4431.6  301.85  4491.6  285.22  4591.7  270.53  4641.7  264.74
  4671.7  263.38  4861.8  259.49  4951.9     261  4974.5  258.79  4982.2  257.06
  4986.2  253.52    4989  253.02  4992.2  253.52  5002.9  253.71  5013.3   258.5
  5029.1  261.34  5127.3  259.48  5210.1  263.69  5251.6  272.76  5257.8  275.81
  5282.7  281.67  5332.4  288.82  5412.1  294.95  5446.8  299.36  5621.2  305.64
#Mann= 3 ,-1 , 0
  3842.9     .16       0  4986.2     .07       0  4992.2     .16       0
Bank Sta=4671.7,5210.1
XS Rating Curve= 0 ,0
Exp/Cntr=0.3,0.1

Type RM Length L Ch R = 1 ,7323    ,461,461,461
BEGIN DESCRIPTION:
UNT050 IN BECR 12.0
END DESCRIPTION:
XS GIS Cut Line= 3
        3796121.     10492045.63      3795599.61     10492560.19
      3794780.75      10493309.5
#Sta/Elev= 30
  4257.8  296.02  4588.6  300.51  4679.2  296.02  4728.7  286.52  4735.8  289.37
  4764.1  288.86  4771.1  285.83  4792.4  288.36  4799.4  284.79  4806.5  287.48
  4813.6  283.74  4834.8  284.11  4841.8  279.95    4849  282.11  4877.2  274.02
  4884.3  268.71  4905.5  265.92  4912.6  261.72  4933.8  259.77  4966.1  250.64
  4968.9  250.14  4972.1  250.64  4993.7  253.97  5004.2  260.49  5237.9  258.69
  5302.1  262.82  5457.5  295.07  5783.1  310.14  6021.8  316.22  6100.3  316.42
#Mann= 5 ,-1 , 0
  4257.8      .1       0  4588.6     .16       0  4966.1     .07       0
  4972.1     .16       0  6021.8      .1       0
Bank Sta=4905.5,5302.1
XS Rating Curve= 0 ,0
Exp/Cntr=0.3,0.1

Type RM Length L Ch R = 1 ,6862    ,337,337,337
BEGIN DESCRIPTION:
UNT050 IN BECR 11.0
END DESCRIPTION:
XS GIS Cut Line= 3
      3795741.12     10492126.49      3795100.97     10492332.64
      3794699.51     10492614.75
#Sta/Elev= 30
  4526.7  295.79  4596.6  296.94  4683.1  294.09  4752.5  294.59  4784.6  292.06
  4816.6   288.5  4843.4  281.92  4848.7  282.38    4875  274.28  4880.8  270.71
    4938  262.72  4944.9  260.99  4982.2  258.63    5001  258.81    5006  250.89
  5008.8  250.39    5012  250.89  5014.3   257.6  5041.1   259.2  5213.1  256.78
  5234.9  258.67  5249.8  257.88    5262   260.2  5327.3  261.02  5384.2  269.15
  5392.7  272.78  5464.1  289.29  5520.8  297.87  5579.8  302.29  5689.9  305.43
#Mann= 4 ,-1 , 0
  4526.7      .1       0  4596.6     .16       0    5006     .07       0
    5012     .16       0
Bank Sta=4938,5327.3
XS Rating Curve= 0 ,0
Exp/Cntr=0.3,0.1

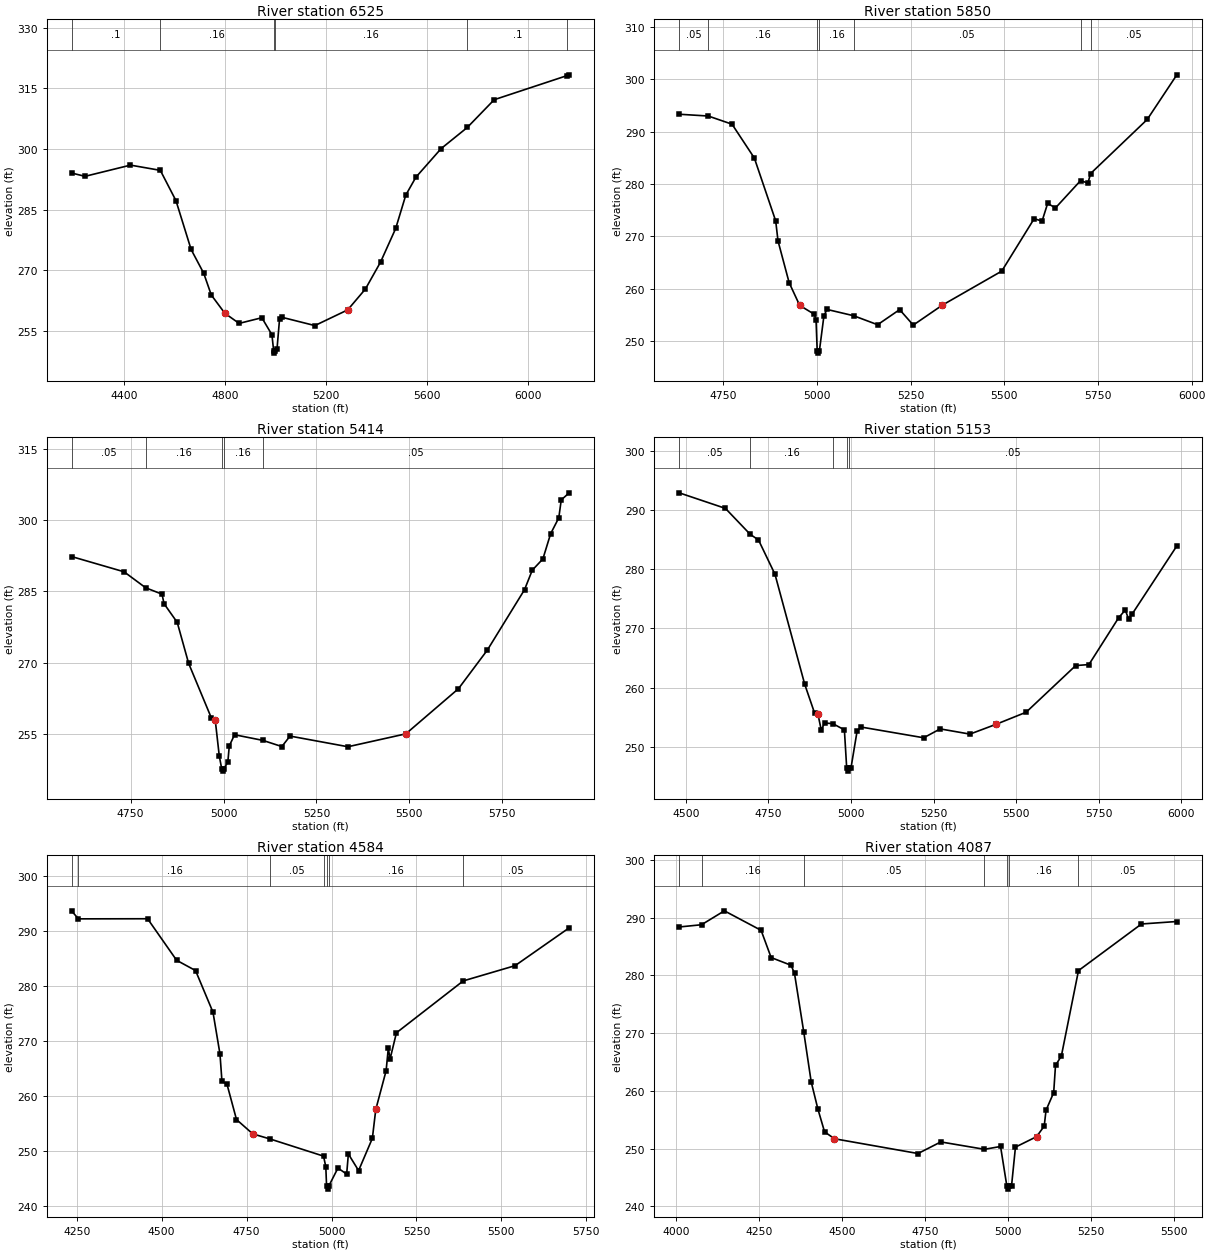
Type RM Length L Ch R = 1 ,6525    ,675,675,675
BEGIN DESCRIPTION:
UNT050 IN BECR 10.0
END DESCRIPTION:
XS GIS Cut Line= 2
      3796002.97     10491955.35      3794032.66     10492052.47
#Sta/Elev= 30
  4191.3  294.07  4244.7  293.25  4424.9  296.02  4543.2  294.73  4605.2  287.24
  4665.2  275.18  4715.3  269.28  4745.3  263.91  4798.9  259.41  4855.5   256.9
  4945.6   258.3  4985.6   254.1  4992.6  250.05  4995.3  249.55  4998.6  250.05
  5005.6  250.45  5015.7  257.87  5025.7   258.4  5155.8  256.36    5286  260.24
  5356.1  265.39  5416.1  272.04  5476.2  280.36  5516.3  288.62  5556.3  293.03
  5656.4  300.11  5760.1  305.33  5866.7  312.19  6156.7  318.17    6164  318.34
#Mann= 6 ,-1 , 0
  4191.3      .1       0  4543.2     .16       0  4992.6     .07       0
  4998.6     .16       0  5760.1      .1       0  6156.7     .16       0
Bank Sta=4798.9,5286
XS Rating Curve= 0 ,0
Exp/Cntr=0.3,0.1

Type RM Length L Ch R = 1 ,5850    ,436,436,436
BEGIN DESCRIPTION:
UNT050 IN BECR 9.0
END DESCRIPTION:
XS GIS Cut Line= 3
      3795795.43     10491811.82      3795499.61     10491610.19
      3794699.63      10491060.2
#Sta/Elev= 30
  4631.7  293.31  4709.3  292.97  4772.8  291.41  4832.4  284.95  4889.4  272.95
  4895.5  269.16  4925.3  261.17  4953.4  256.84  4992.7  255.13  4997.1  254.03
  5000.2  248.23    5003  247.73  5006.2  248.23  5018.1   254.8  5026.1  256.07
  5097.3  254.87  5161.5  253.15  5220.3  256.03  5256.7  253.08  5334.7   256.9
    5493  263.38  5579.6  273.39  5600.6  272.91  5615.5  276.29  5636.5  275.44
  5703.4  280.64  5723.1  280.18  5730.2  281.99  5881.4  292.31  5960.5  300.83
#Mann= 7 ,-1 , 0
  4631.7     .05       0  4709.3     .16       0  5000.2     .07       0
  5006.2     .16       0  5097.3     .05       0  5703.4     .16       0
  5730.2     .05       0
Bank Sta=4953.4,5334.7
XS Rating Curve= 0 ,0
Exp/Cntr=0.3,0.1

Type RM Length L Ch R = 1 ,5414    ,261,261,261
BEGIN DESCRIPTION:
UNT050 IN BECR 8.0
END DESCRIPTION:
XS GIS Cut Line= 3
      3795936.47     10491768.37      3795849.61     10491360.19
      3795249.59     10490660.17
#Sta/Elev= 30
    4591  292.34  4732.3  289.14  4790.5  285.78  4834.5  284.44  4839.9  282.44
  4875.4  278.52  4906.1  269.91  4967.4  258.42  4977.7  258.01  4988.6  250.44
  4995.1  247.78  4997.8  247.28  5001.1  247.78  5011.6  249.17  5015.5  252.57
  5029.7  254.92  5105.7  253.74    5157  252.44    5179  254.64  5334.8   252.4
  5490.7  255.11  5632.3  264.59  5710.2  272.72  5810.1  285.38  5830.9  289.47
  5859.5  291.84  5880.3  297.12  5902.3  300.47  5908.9  304.23  5930.3  305.72
#Mann= 5 ,-1 , 0
    4591     .05       0  4790.5     .16       0  4995.1     .07       0
  5001.1     .16       0  5105.7     .05       0
Bank Sta=4977.7,5490.7
XS Rating Curve= 0 ,0
Exp/Cntr=0.3,0.1

Type RM Length L Ch R = 1 ,5153    ,569,569,569
BEGIN DESCRIPTION:
UNT050 IN BECR 7.0
END DESCRIPTION:
XS GIS Cut Line= 2
      3796044.62     10491740.08      3796072.38     10490234.14
#Sta/Elev= 30
  4479.7  292.92  4619.6  290.29  4694.8  285.89  4719.6  284.96  4769.6  279.15
  4859.7  260.53  4889.7  255.64  4899.7  255.47  4909.7   252.8  4919.7     254
  4944.6  253.89  4979.7  252.84  4986.7  246.36  4989.4  245.86  4992.7  246.36
  4999.7  246.42  5018.2  252.64  5029.7  253.32  5219.7   251.5  5269.7     253
  5359.7  252.12  5439.8   253.8  5529.8  255.82  5679.8  263.71  5719.8  263.88
  5809.8   271.8  5829.8   273.1  5839.8   271.6  5849.8  272.35  5985.9  283.94
#Mann= 5 ,-1 , 0
  4479.7     .05       0  4694.8     .16       0  4944.6     .05       0
  4986.7     .03       0  4992.7     .05       0
Bank Sta=4899.7,5439.8
XS Rating Curve= 0 ,0
Exp/Cntr=0.3,0.1

Type RM Length L Ch R = 1 ,4584    ,497,497,497
BEGIN DESCRIPTION:
UNT050 IN BECR 6.0
END DESCRIPTION:
XS GIS Cut Line= 3
       3796384.9     10491885.87      3796530.73     10491253.96
      3796398.79     10490448.41
#Sta/Elev= 30
  4234.7  293.69  4254.9  292.23  4458.5  292.25    4544   284.7  4599.7  282.83
    4651  275.26  4671.6  267.67  4677.4   262.7  4692.1   262.2  4720.2  255.75
  4768.1  253.14  4819.9   252.2  4976.4   249.1  4983.1  247.17  4985.4   243.6
  4988.1   243.1  4991.4   243.6  5018.8  246.93  5044.5  245.83  5049.5  249.49
  5079.6  246.47  5120.1  252.33  5130.2  257.58  5160.6  264.62  5167.1  268.74
  5172.2  266.74    5191  271.52  5387.6  280.95  5540.2  283.72  5699.5   290.6
#Mann= 7 ,-1 , 0
  4234.7      .1       0  4254.9     .16       0  4819.9     .05       0
  4976.4     .16       0  4985.4     .07       0  4991.4     .16       0
  5387.6     .05       0
Bank Sta=4768.1,5130.2
XS Rating Curve= 0 ,0
Exp/Cntr=0.3,0.1

Type RM Length L Ch R = 1 ,4087    ,307,307,307
BEGIN DESCRIPTION:
UNT050 IN BECR 5.0
END DESCRIPTION:
XS GIS Cut Line= 3
      3796939.08     10491735.51      3796855.75     10490855.32
      3796600.53     10490298.01
#Sta/Elev= 30
  4010.2  288.39  4077.4  288.78  4146.1  291.19  4256.6  287.81  4286.8  283.09
    4347  281.75  4357.1  280.33  4384.8  270.24  4407.3  261.55  4427.4  256.85
  4447.5  252.89  4477.3  251.69  4728.7  249.13  4797.2  251.14  4928.5  249.86
    4977  250.35    4996  243.46  4998.7  242.96    5002  243.46    5010  243.51
  5021.8  250.24  5085.3  252.05  5108.3  253.88  5113.8  256.63  5136.8  259.68
  5142.3   264.4  5159.9  266.03  5211.4  280.83  5400.9  288.91  5507.3  289.34
#Mann= 7 ,-1 , 0
  4010.2     .05       0  4077.4     .16       0  4384.8     .05       0
  4928.5     .16       0    4996     .07       0    5002     .16       0
  5211.4     .05       0
Bank Sta=4477.3,5085.3
XS Rating Curve= 0 ,0
Exp/Cntr=0.3,0.1

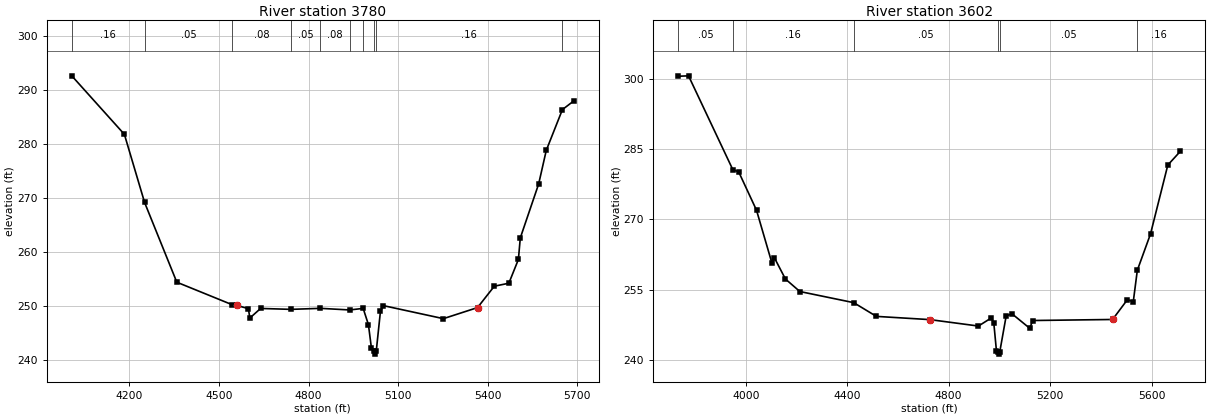
Type RM Length L Ch R = 1 ,3780    ,178,178,178
BEGIN DESCRIPTION:
UNT050 IN BECR 4.0
END DESCRIPTION:
XS GIS Cut Line= 4
        3797012.     10491620.99      3797090.12      10490532.4
      3797069.29     10490313.65      3796944.53     10489965.35
#Sta/Elev= 30
  4007.1  292.66  4183.3  281.82  4250.9  269.21  4358.8  254.44  4545.1  250.25
  4559.3  250.15  4598.4  249.54  4603.4  247.81  4639.5  249.58  4741.3  249.41
  4839.4   249.6  4937.5   249.3  4982.8  249.59  5000.4  246.58  5010.5   242.2
  5020.5  241.62  5023.2  241.12  5026.5  241.62  5040.6  249.03  5050.6   250.1
  5251.4  247.69  5365.7  249.74  5421.9   253.7  5470.6  254.25  5502.5  258.65
  5508.9  262.64  5570.4  272.64  5595.9  278.86  5649.9  286.41  5688.2  288.02
#Mann= 10 ,-1 , 0
  4007.1     .16       0  4250.9     .05       0  4545.1     .08       0
  4741.3     .05       0  4839.4     .08       0  4937.5     .05       0
  4982.8     .16       0  5020.5     .07       0  5026.5     .16       0
  5649.9     .05       0
Bank Sta=4559.3,5365.7
XS Rating Curve= 0 ,0
Exp/Cntr=0.3,0.1

Type RM Length L Ch R = 1 ,3602    ,1759,1759,1759
BEGIN DESCRIPTION:
UNT050 IN BECR 3.0
END DESCRIPTION:
XS GIS Cut Line= 6
      3797100.54     10491777.22      3797173.46     10491084.49
      3797230.75     10490563.65      3797183.87     10490350.11
      3797235.96     10490042.82      3797029.05     10489944.54
#Sta/Elev= 30
  3733.5  300.51  3774.1   300.6  3948.7  280.59  3971.8  280.13  4042.2  271.93
  4102.6  260.73  4112.6   261.8  4156.2  257.26  4213.2  254.59  4425.5  252.22
  4514.9  249.29  4726.1   248.6  4917.3  247.23  4967.8  248.95  4977.8  247.95
  4988.3  241.96  4995.5  241.74  4998.3  241.24  5001.5  241.74  5026.7  249.39
  5049.7  249.84  5119.4  246.76  5131.6  248.41  5446.4  248.63    5505  252.88
  5527.8  252.38  5543.9  259.13  5595.9  266.88  5664.1  281.57  5713.4  284.49
#Mann= 6 ,-1 , 0
  3733.5     .05       0  3948.7     .16       0  4425.5     .05       0
  4995.5     .04       0  5001.5     .05       0  5543.9     .16       0
Bank Sta=4726.1,5446.4
XS Rating Curve= 0 ,0
Exp/Cntr=0.3,0.1