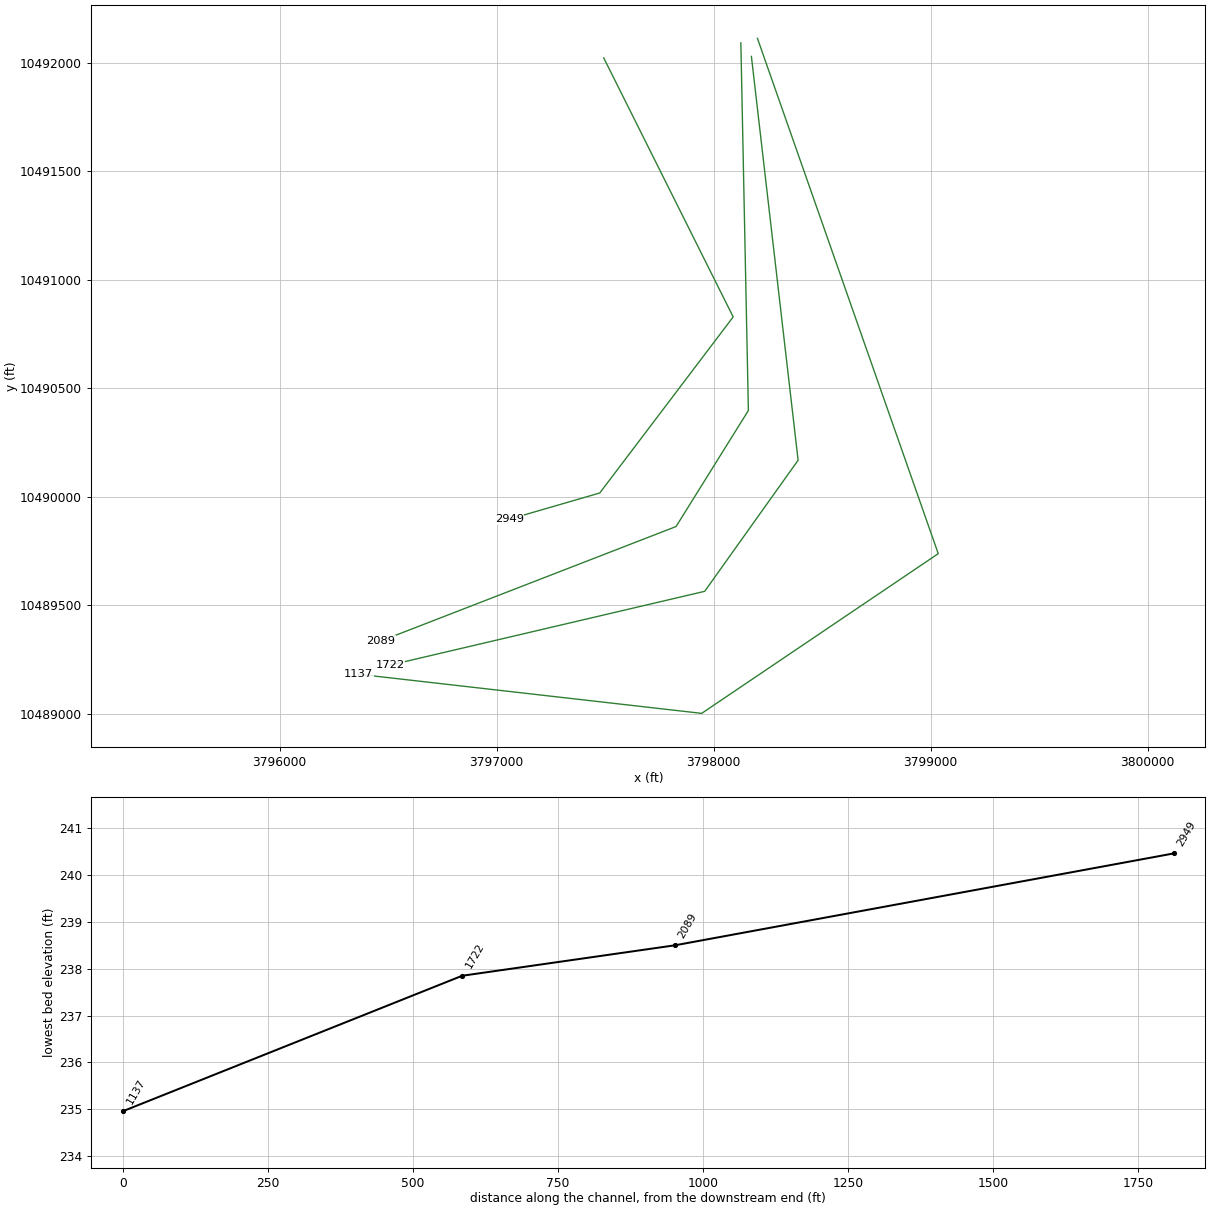
HEC-RAS study UNT050 IN BECR.prj: UNT050 IN BECR Base Level Engineering

--- UNT050 IN BECR.g01 (geometry) --- (continued)

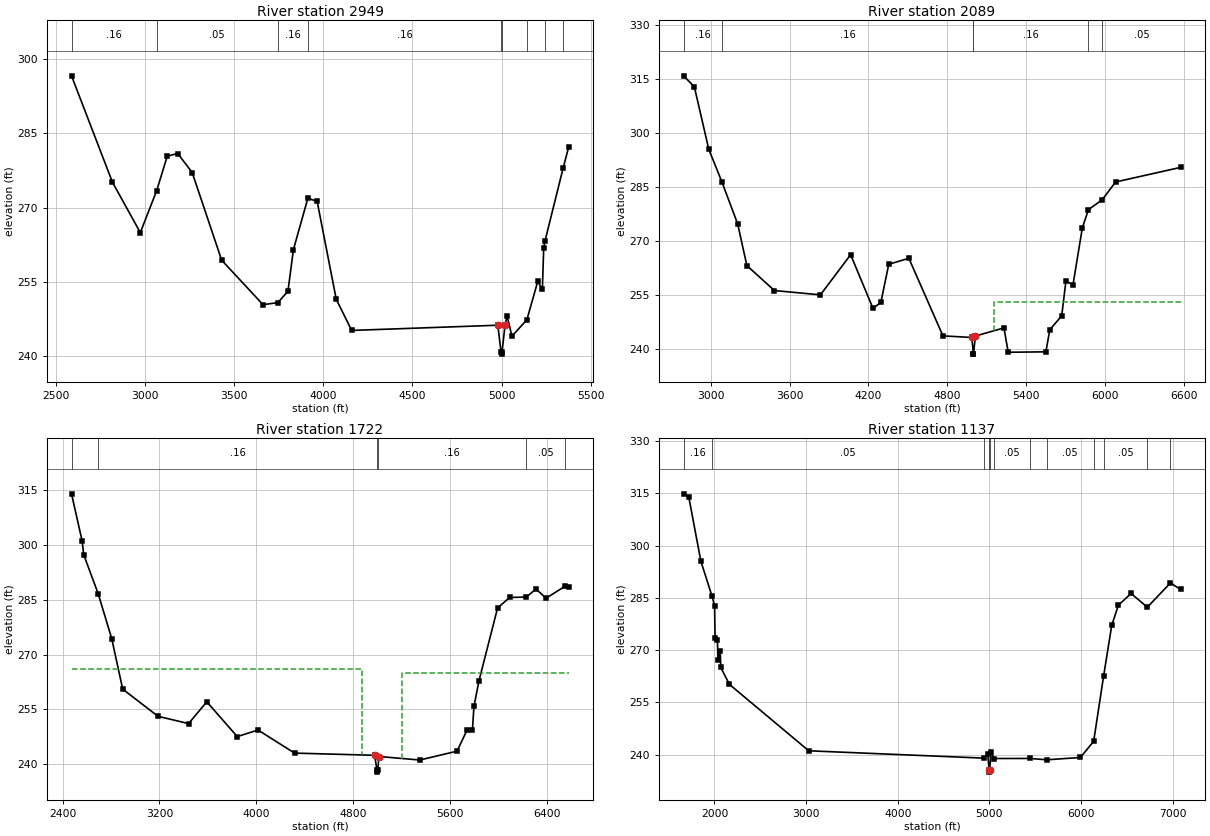
Type RM Length L Ch R = 1 ,2949    ,860,860,860
BEGIN DESCRIPTION:
UNT050 IN BECR 2.0
END DESCRIPTION:
XS GIS Cut Line= 4
      3797493.51     10492022.96      3798090.12     10490829.28
      3797475.17     10490017.85      3797058.86     10489896.98
#Sta/Elev= 30
  2589.3  296.59  2818.5  275.15    2975  264.97  3066.8  273.45    3126  280.39
  3184.9  280.92  3265.8  277.08  3430.9  259.41  3662.7  250.44  3745.9  250.84
  3802.5  253.14  3833.3  261.55  3914.3  271.92  3966.3  271.25  4073.2  251.54
  4159.7  245.24  4978.9  246.29    4997  240.96  4999.8  240.46    5003  240.96
  5019.3  246.27    5031  248.15    5058  244.07  5141.9  247.39  5202.7  255.11
  5228.8  253.56  5236.2   261.8  5243.7  263.32  5345.5  278.03  5375.4  282.14
#Mann= 9 ,-1 , 0
  2589.3     .16       0  3066.8     .05       0  3745.9     .16       0
  3914.3     .16       0    4997     .07       0    5003     .16       0
  5141.9     .05       0  5243.7     .16       0  5345.5     .05       0
Bank Sta=4978.9,5019.3
XS Rating Curve= 0 ,0
Exp/Cntr=0.3,0.1

Type RM Length L Ch R = 1 ,2089    ,367,367,367
BEGIN DESCRIPTION:
Mapping XS ea390830
END DESCRIPTION:
XS GIS Cut Line= 4
      3798125.46     10492092.35      3798160.18     10490397.95
      3797826.85     10489863.22      3796465.76     10489335.46
#Sta/Elev= 30
  2792.5  315.82  2874.7  312.77  2984.7   295.4  3084.7  286.34  3204.7  274.67
  3274.8  263.09  3484.8  256.16  3834.9  254.97  4064.9  266.13    4235  251.21
    4295  252.87    4355  263.46  4508.2  265.13  4767.9  243.57  4987.4  243.13
  4999.8   238.5  5000.3   238.5  5014.9  243.53  5232.4  245.79  5264.6  239.02
  5551.6  239.14  5581.6  245.29  5672.1  249.14  5704.3  258.83  5757.9  257.72
  5829.4  273.62  5875.9  278.64  5980.2  281.38  6082.6  286.33  6577.2  290.38
#Mann= 6 ,-1 , 0
  2792.5     .16       0  3084.7     .16       0  4999.8     .08       0
  5000.3     .16       0  5875.9     .16       0  5980.2     .05       0
#XS Ineff= 2 , 0
                         5156.25          253.08
Permanent Ineff=
       F       F
Bank Sta=4987.4,5014.9
XS Rating Curve= 0 ,0
Exp/Cntr=0.3,0.1

Type RM Length L Ch R = 1 ,1722    ,585,585,585
BEGIN DESCRIPTION:
Mapping XS abc5b2f5
END DESCRIPTION:
XS GIS Cut Line= 4
      3798174.08     10492029.88      3798389.35     10490168.78
       3797958.8     10489564.61       3796509.2     10489224.75
#Sta/Elev= 30
  2474.2  313.93  2562.7  300.92  2574.6  297.31  2694.4  286.62  2806.1  274.37
  2896.7  260.54  3188.6  253.11  3440.7  251.12  3591.3  257.08    3843  247.56
  4014.1  249.37  4316.1  243.05  4977.3  242.45    4997  238.35  4999.8  237.85
    5003  238.35  5012.9  242.12  5350.3  241.16  5657.7  243.58  5742.6   249.5
    5785  249.49  5797.5  255.82  5838.6  262.76  5992.6  282.73  6092.4   285.6
  6230.1  285.71  6309.8  287.91  6393.2  285.39  6550.9   288.7  6578.5  288.36
#Mann= 6 ,-1 , 0
  2474.2     .16       0  2694.4     .16       0    4997     .07       0
    5003     .16       0  6230.1     .05       0  6550.9     .16       0
#XS Ineff= 2 , 0
         4869.32  266.01 5204.55          264.87
Permanent Ineff=
       F       F
Bank Sta=4977.3,5012.9
XS Rating Curve= 0 ,0
Exp/Cntr=0.3,0.1

Type RM Length L Ch R = 1 ,1137    ,0,0,0
BEGIN DESCRIPTION:
UNT050 IN BECR 1.0
END DESCRIPTION:
XS GIS Cut Line= 4
      3798201.86     10492113.21      3799035.18     10489738.22
      3797944.91     10489002.11      3796363.11     10489182.49
#Sta/Elev= 30
  1662.4  314.89  1718.6  314.09  1851.5  295.54  1973.9  285.43  2001.2   282.7
  2006.5  273.46  2032.2  272.87  2037.5  267.07  2063.2  269.62  2068.5  265.02
  2163.7  260.15  3028.6  241.09  4939.9  238.98  4982.4  240.27    4997  235.46
  4999.8  234.96    5003  235.46  5018.6  240.77  5052.5  238.87  5438.2  238.89
  5627.2   238.5  5993.4  239.17  6138.4   243.8  6246.8  262.52  6335.6   277.1
  6407.8  282.88  6546.9  286.27  6724.1  282.32  6976.7  289.31  7086.9  287.42
#Mann= 12 ,-1 , 0
  1662.4     .16       0  1973.9     .05       0  4939.9     .16       0
    4997     .07       0    5003     .16       0  5052.5     .05       0
  5438.2     .08       0  5627.2     .05       0  6138.4     .16       0
  6246.8     .05       0  6724.1     .16       0  6976.7     .05       0
Bank Sta=4997,5003
XS Rating Curve= 0 ,0
Exp/Cntr=0.3,0.1

Chan Stop Cuts=-1
Use User Specified Reach Order=0
Composite Channel Slope=5