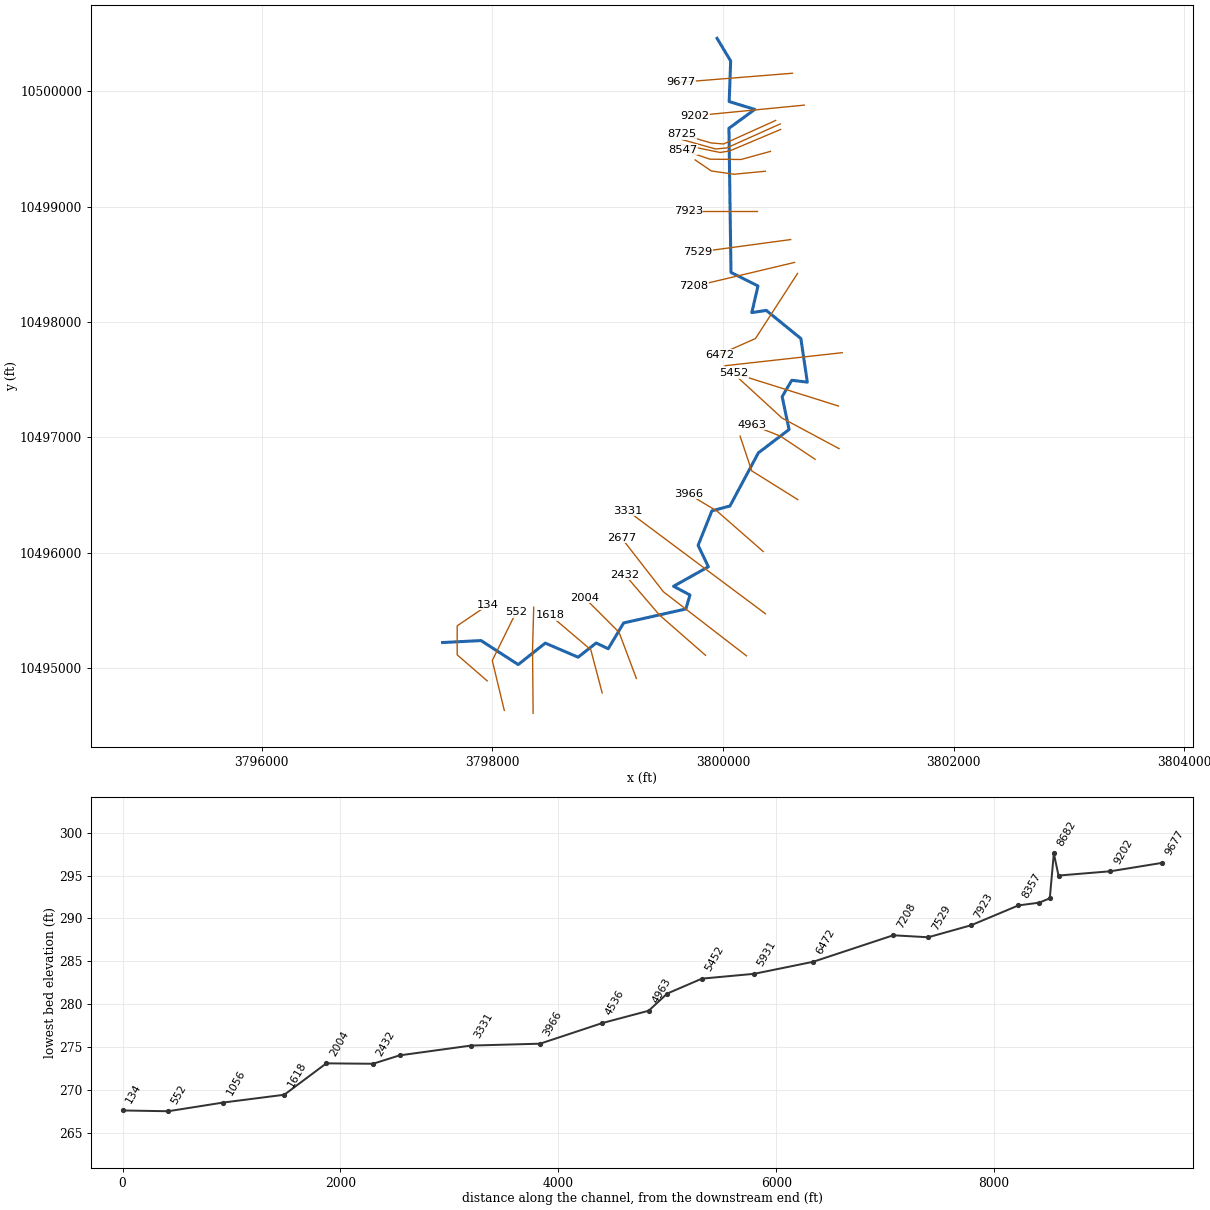
--- UNT052 IN BECR.prj (project) ---

Proj Title=UNT052 IN BECR Base Level Engineering
Current Plan=p01
Default Exp/Contr=0.3,0.1
English Units
Geom File=g01
Flow File=f01
Plan File=p01
Y Axis Title=Elevation
X Axis Title(PF)=Main Channel Distance
X Axis Title(XS)=Station
BEGIN DESCRIPTION:
UNT052 IN BECR
END DESCRIPTION:
DSS Export Rating Curves= 0
DSS Export Rating Curve Sorted= 0
DSS Export Volume Flow Curves= 0
DXF OffsetX= 0
DXF OffsetY= 0
DXF ScaleX= 1
DXF ScaleY= 10

--- UNT052 IN BECR.p01 (plan) ---

Plan Title=Multiple Run
Short Identifier=Multiple
Geom File=g01
Flow File=f01
Subcritical Flow
K Sum by GR= 0
Std Step Tol= 0.01
Critical Tol= 0.01
Num of Std Step Trials= 20
Max Error Tol= 0.3
Flow Tol Ratio= 0.001
Split Flow NTrial= 30
Split Flow Tol= 0.02
Split Flow Ratio= 0.02
Log Output Level= 0
Friction Slope Method= 1
Unsteady Friction Slope Method= 2
Unsteady Bridges Friction Slope Method= 1
Parabolic Critical Depth
Global Vel Dist=  1 , 1 , 1
Global Log Level= 0
CheckData=True
Encroach Param= -1, 0, 0, 0
BEGIN DESCRIPTION:
Multiple Run
END DESCRIPTION:

--- UNT052 IN BECR.f01 (steady flow) ---

Flow Title=Multiple
Program Version=4.10
Number of Profiles= 7
Profile Names=10-year,25-year,50-year,1pct_min,100-year,1pct_plu,500-year
River Rch & RM=UNT052 IN BECR,Reach-1         ,9677
     565     760     920     819    1107    1498    1609
River Rch & RM=UNT052 IN BECR,Reach-1         ,7923
     702     950    1155    1031    1394    1886    2038
Boundary for River Rch & Prof#=UNT052 IN BECR,Reach-1         , 1
Up Type= 0
Dn Type= 3
Dn Slope=0.003
Boundary for River Rch & Prof#=UNT052 IN BECR,Reach-1         , 2
Up Type= 0
Dn Type= 3
Dn Slope=0.003
Boundary for River Rch & Prof#=UNT052 IN BECR,Reach-1         , 3
Up Type= 0
Dn Type= 3
Dn Slope=0.003
Boundary for River Rch & Prof#=UNT052 IN BECR,Reach-1         , 4
Up Type= 0
Dn Type= 3
Dn Slope=0.003
Boundary for River Rch & Prof#=UNT052 IN BECR,Reach-1         , 5
Up Type= 0
Dn Type= 3
Dn Slope=0.003
Boundary for River Rch & Prof#=UNT052 IN BECR,Reach-1         , 6
Up Type= 0
Dn Type= 3
Dn Slope=0.003
Boundary for River Rch & Prof#=UNT052 IN BECR,Reach-1         , 7
Up Type= 0
Dn Type= 3
Dn Slope=0.003
DSS Import GetInterval= 0
DSS Import GetPeak= 0
DSS Import FillOption= 0

--- UNT052 IN BECR.g01 (geometry) ---

Geom Title=Existing Conditions
Program Version=4.10

River Reach=UNT052 IN BECR  ,Reach-1
Reach XY= 30
      3799949.61     10500460.19       3800067.5       10500264.
      3800054.75       10499912.      3800276.75       10499844.
       3800052.5       10499680.       3800070.5       10498430.
       3800304.5       10498313.      3800250.75       10498082.
      3800376.75       10498101.      3800676.25       10497857.
      3800732.25       10497479.      3800597.25       10497495.
        3800514.       10497353.        3800574.       10497068.
      3800307.75       10496866.      3800061.25       10496405.
        3799905.       10496363.      3799785.25       10496064.
      3799874.25       10495878.      3799572.25       10495709.
      3799714.75       10495633.        3799679.       10495512.
       3799139.5       10495391.      3799005.75       10495167.
      3798901.25       10495217.       3798744.5       10495094.
      3798460.25       10495216.      3798225.25       10495030.
        3797903.       10495238.       3797569.5       10495221.

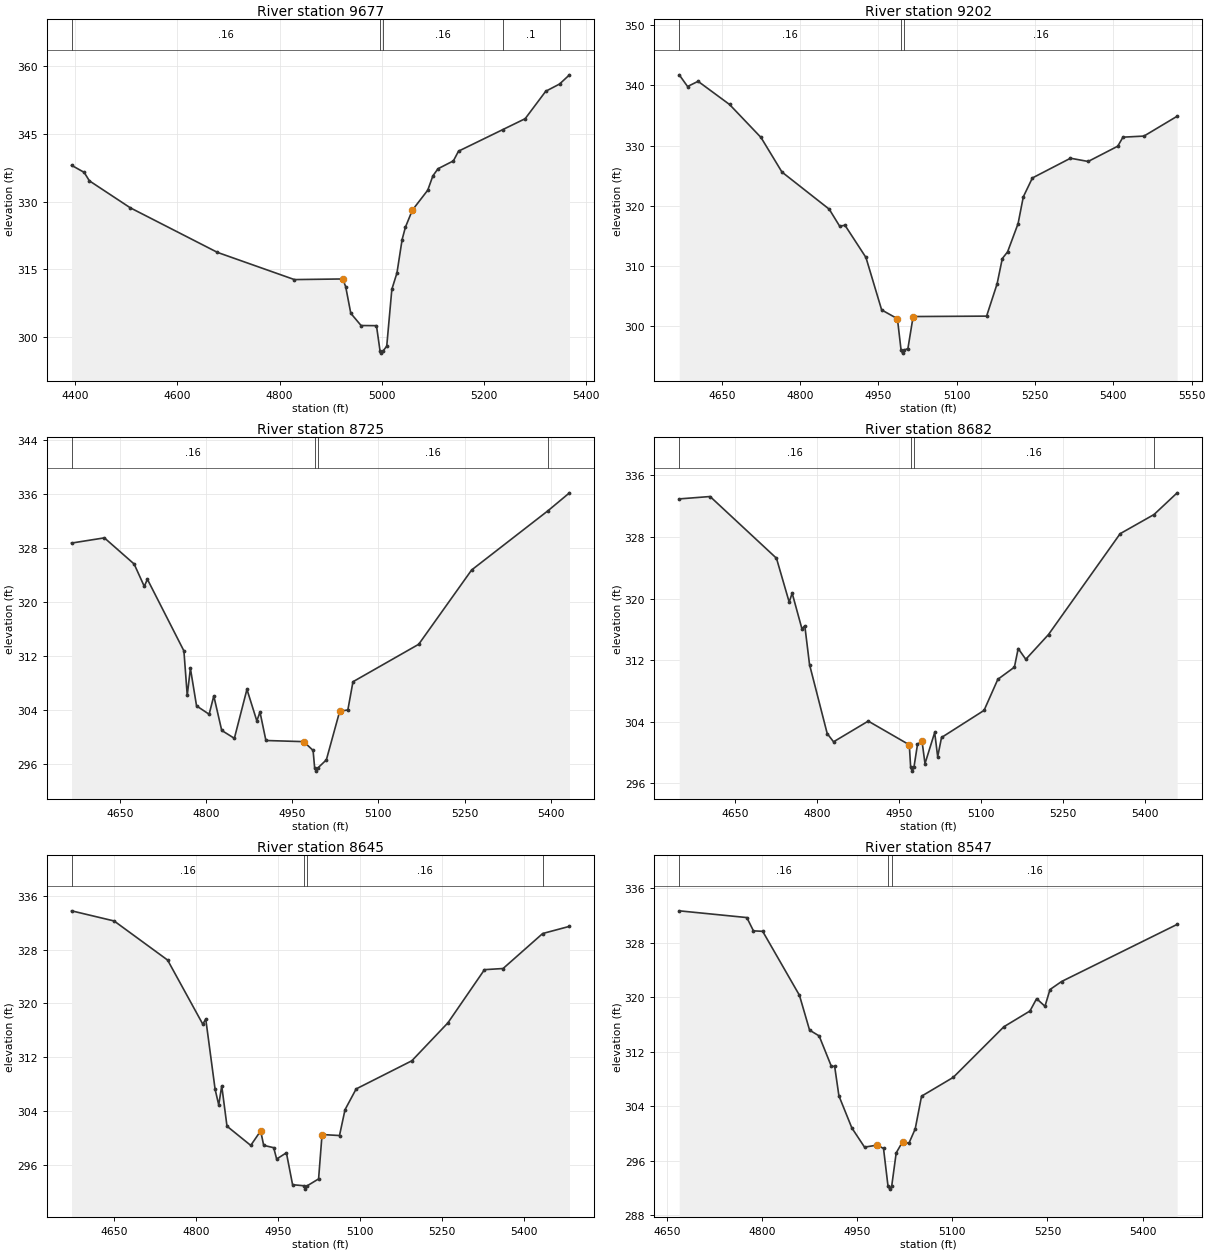
Type RM Length L Ch R = 1 ,9677    ,475,475,475
BEGIN DESCRIPTION:
UNT052 IN BECR 19.0
END DESCRIPTION:
XS GIS Cut Line= 2
       3800604.1     10500157.61      3799633.22     10500079.59
#Sta/Elev= 30
    4393  338.06  4417.6   336.5  4427.9  334.62  4507.9  328.65  4678.4  318.78
  4828.9  312.76  4923.4   312.9  4929.2  311.19  4939.2   305.3  4959.3  302.59
  4989.4  302.56  4996.4  296.98  4999.2  296.48  5002.4  296.98  5009.5  298.01
  5019.5  310.61  5029.5  314.23  5039.6  321.62    5046  324.35  5059.6  328.13
  5089.7  332.55  5099.8  335.73  5109.8   337.3  5139.9  339.04  5149.9  341.19
  5236.8  345.98  5280.3  348.38  5320.5  354.45  5347.5  356.05    5367  358.09
#Mann= 5 ,-1 , 0
    4393     .16       0  4996.4     .07       0  5002.4     .16       0
  5236.8      .1       0  5347.5     .16       0
Bank Sta=4923.4,5059.6
XS Rating Curve= 0 ,0
Exp/Cntr=0.3,0.1

Type RM Length L Ch R = 1 ,9202    ,477,477,477
BEGIN DESCRIPTION:
Mapping XS 101a4b10
END DESCRIPTION:
XS GIS Cut Line= 2
      3800705.51     10499880.98      3799756.31     10499788.53
#Sta/Elev= 30
  4568.6  341.75  4584.6  339.81  4604.7  340.67    4665  336.82  4725.2  331.34
  4765.4  325.59  4855.9  319.42    4876  316.58    4886  316.76  4926.2   311.4
  4956.3  302.68  4986.5  301.22  4993.5     296  4996.3   295.5  4999.5     296
  5006.6  296.26  5016.6  301.58  5157.3  301.65  5177.4  307.01  5187.4  311.22
  5197.5  312.33  5217.6  317.02  5227.6  321.47    5245  324.61    5318  327.89
  5351.8  327.35  5408.5  329.89  5418.5  331.39  5458.7  331.57  5522.3  334.87
#Mann= 3 ,-1 , 0
  4568.6     .16       0  4993.5     .07       0  4999.5     .16       0
Bank Sta=4986.5,5016.6
XS Rating Curve= 0 ,0
Exp/Cntr=0.3,0.1

Type RM Length L Ch R = 1 ,8725    ,43,43,43
BEGIN DESCRIPTION:
UNT052 IN BECR 18.0
END DESCRIPTION:
XS GIS Cut Line= 4
      3800457.77     10499748.23      3800006.42     10499544.25
      3799897.92     10499552.93      3799646.16     10499626.72
#Sta/Elev= 30
  4566.2  328.73  4623.3   329.5  4675.1  325.63  4692.7  322.33  4698.2  323.37
  4761.7  312.78  4767.5   306.2    4773   310.2  4783.7  304.65  4805.6  303.41
  4813.7  306.12  4827.5  301.02  4849.5  299.85  4871.4   307.1  4888.6  302.43
  4894.1  303.74  4904.4  299.53  4970.2  299.36  4986.5  298.06  4989.2   295.5
  4991.9     295  4995.2   295.5  5009.6  296.67  5032.8  303.85    5047  304.05
  5055.9  308.22  5170.3  313.76  5262.4  324.75  5395.1   333.5  5432.7  336.16
#Mann= 4 ,-1 , 0
  4566.2     .16       0  4989.2     .07       0  4995.2     .16       0
  5395.1      .1       0
Bank Sta=4970.2,5032.8
XS Rating Curve= 0 ,0
Exp/Cntr=0.3,0.1

Type RM Length L Ch R = 1 ,8682    ,37,37,37
BEGIN DESCRIPTION:
Mapping XS fe58cfb6
END DESCRIPTION:
XS GIS Cut Line= 4
      3800496.89     10499717.87      3800032.46     10499509.53
      3799936.98     10499500.85      3799643.22     10499582.93
#Sta/Elev= 30
  4548.4  332.95  4604.8  333.26  4726.1  325.24  4749.3  319.55  4754.8   320.7
  4772.5   316.1  4777.9  316.45  4786.5  311.43  4818.8  302.46  4830.4  301.39
  4893.8  304.08  4968.8     301  4971.3  298.08  4974.1  297.58  4977.3  298.08
  4983.8  301.05    4992  301.52  4997.5  298.55  5015.2   302.6  5020.7  299.45
  5027.7  301.95  5105.4  305.47  5130.6  309.51  5160.9  311.09  5167.8  313.51
  5181.7  312.11  5223.2  315.33  5354.1  328.43    5416  330.92  5458.3  333.74
#Mann= 4 ,-1 , 0
  4548.4     .16       0  4971.3     .07       0  4977.3     .16       0
    5416      .1       0
Bank Sta=4968.8,4992
XS Rating Curve= 0 ,0
Exp/Cntr=0.3,0.1

Type RM Length L Ch R = 1 ,8645    ,98,98,98
BEGIN DESCRIPTION:
Mapping XS 24b685da
END DESCRIPTION:
XS GIS Cut Line= 4
      3800501.19     10499670.11      3800058.51     10499483.49
      3799976.04     10499470.47      3799637.49     10499539.91
#Sta/Elev= 30
    4573  333.79  4650.7  332.28  4748.4  326.46  4812.7  316.91  4818.1  317.68
  4835.2  307.21  4841.8  304.89  4847.3  307.73  4856.9  301.72  4900.3  298.86
  4918.4  301.02  4923.9  298.87  4942.2  298.52  4947.6  296.83  4965.4  297.76
  4976.7  293.01  4997.5  292.85  5000.2  292.35  5003.5  292.85  5024.2  293.87
  5030.5  300.48  5062.4  300.33  5072.5  304.18  5092.8  307.27  5194.5  311.46
  5260.4  317.11  5327.2  325.03  5361.2   325.2  5433.5  330.41  5482.5  331.48
#Mann= 4 ,-1 , 0
    4573     .16       0  4997.5     .07       0  5003.5     .16       0
  5433.5      .1       0
Bank Sta=4918.4,5030.5
XS Rating Curve= 0 ,0
Exp/Cntr=0.3,0.1

Type RM Length L Ch R = 1 ,8547    ,190,190,190
BEGIN DESCRIPTION:
Mapping XS 2153e1f4
END DESCRIPTION:
XS GIS Cut Line= 4
      3800412.52     10499479.93      3800157.35     10499409.63
      3799887.82     10499412.23      3799649.55     10499492.96
#Sta/Elev= 30
  4668.9  332.71  4775.6  331.72    4786  329.77  4800.6   329.7  4858.6  320.31
  4874.6  315.19  4889.7  314.34    4909  309.87  4914.2  309.86  4920.9  305.54
  4941.3  300.83  4961.3  298.01  4981.3   298.3  4991.3  297.81  4998.3  292.34
  5001.1  291.84  5004.3  292.34  5011.3  297.16  5021.3  298.79  5031.3  298.56
  5041.3  300.68  5051.3  305.49  5101.3  308.25  5181.3  315.69  5222.4     318
  5232.9  319.81  5246.1  318.69    5254  321.15  5272.3  322.33  5454.7  330.72
#Mann= 3 ,-1 , 0
  4668.9     .16       0  4998.3     .07       0  5004.3     .16       0
Bank Sta=4981.3,5021.3
XS Rating Curve= 0 ,0
Exp/Cntr=0.3,0.1

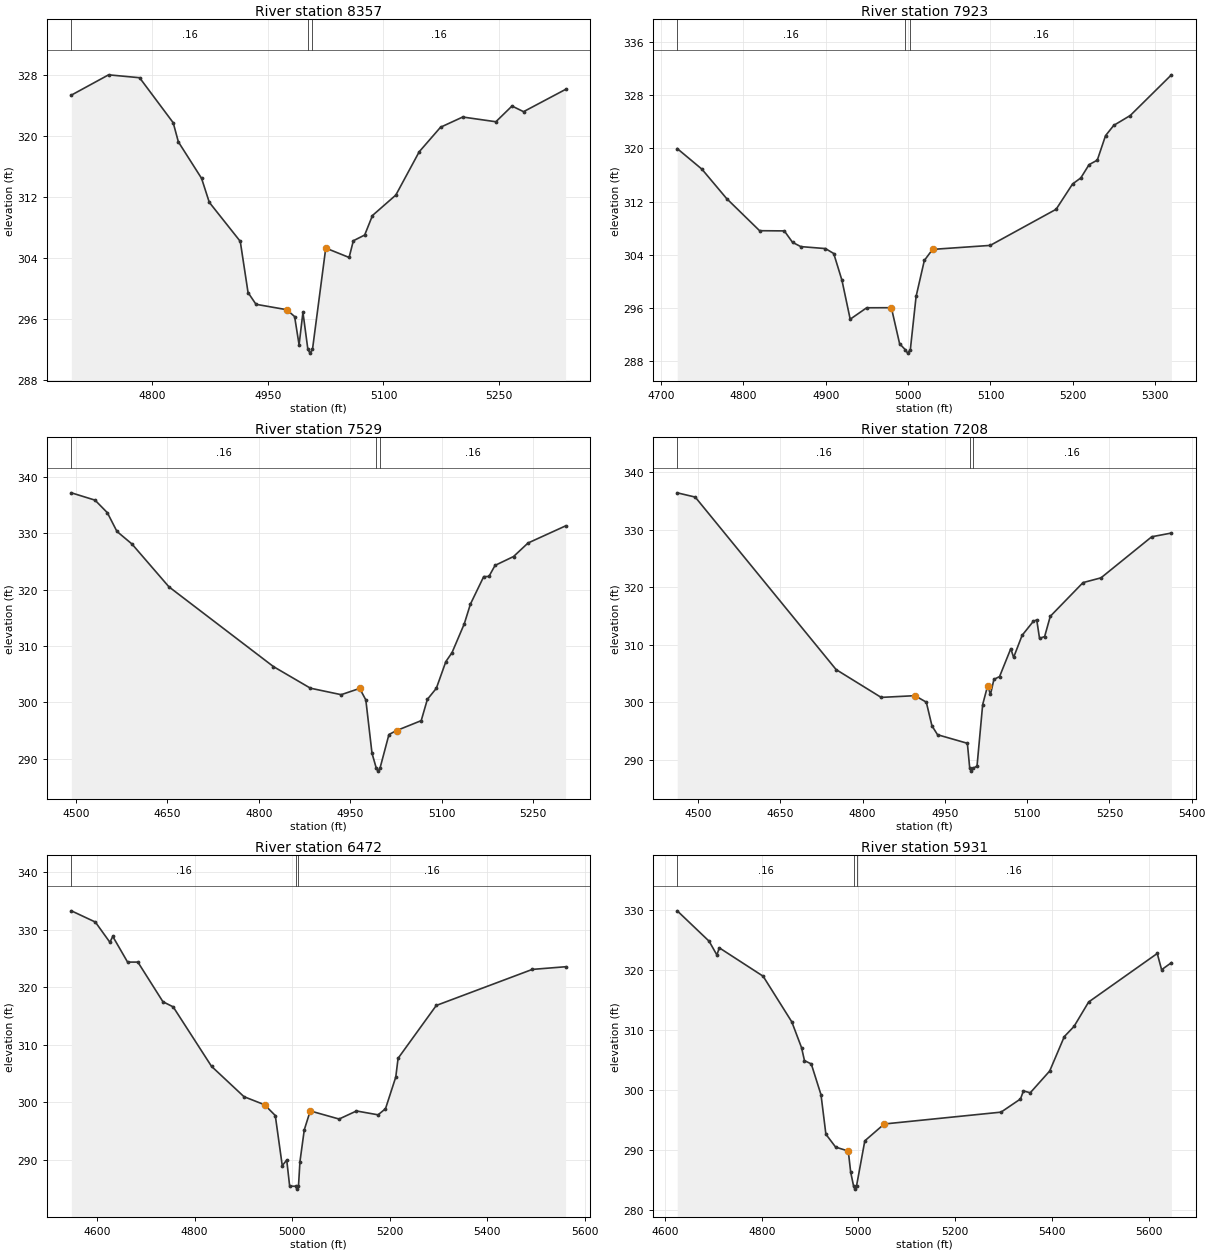
Type RM Length L Ch R = 1 ,8357    ,434,434,434
BEGIN DESCRIPTION:
UNT052 IN BECR 17.0
END DESCRIPTION:
XS GIS Cut Line= 4
      3800367.73      10499307.7      3800097.57     10499281.67
      3799899.61     10499310.19      3799759.49      10499405.9
#Sta/Elev= 30
  4695.1  325.34  4743.4     328  4783.6  327.62  4827.2  321.72  4833.9  319.21
    4864  314.43    4874  311.29  4914.2  306.17  4924.3  299.46  4934.6  297.92
  4974.6  297.21  4984.7  296.31  4990.5  292.61  4995.5  296.87  5001.9  292.02
  5004.6  291.52  5007.9  292.02  5025.1  305.29  5055.4  304.06  5060.9  306.25
  5075.6     307  5085.7  309.56    5116  312.24  5146.3  317.91    5174  321.13
  5202.8  322.47  5245.8  321.85  5266.7  323.91  5281.7  323.17  5336.2  326.09
#Mann= 3 ,-1 , 0
  4695.1     .16       0  5001.9     .07       0  5007.9     .16       0
Bank Sta=4974.6,5025.1
XS Rating Curve= 0 ,0
Exp/Cntr=0.3,0.1

Type RM Length L Ch R = 1 ,7923    ,394,394,394
BEGIN DESCRIPTION:
UNT052 IN BECR 16.0
END DESCRIPTION:
XS GIS Cut Line= 3
      3800299.59     10498960.19      3800049.61     10498960.19
      3799699.59     10498960.19
#Sta/Elev= 30
  4719.7  319.97  4749.7  316.87  4779.7  312.45  4819.7  307.62  4849.7  307.59
  4859.7  305.87  4869.7  305.23  4899.7  304.93  4909.7  304.19  4919.7  300.16
  4929.7  294.31  4949.7  296.03  4979.7  296.04  4989.7  290.62  4996.7  289.71
  4999.4  289.21  5002.7  289.71  5009.7  297.73  5019.7  303.14  5029.7  304.81
  5099.7  305.41  5179.7  310.84  5199.7  314.65  5209.7  315.56  5219.7  317.55
  5229.7  318.23  5239.7  321.91  5249.7  323.46  5269.7  324.94  5319.7  331.06
#Mann= 3 ,-1 , 0
  4719.7     .16       0  4996.7     .07       0  5002.7     .16       0
Bank Sta=4979.7,5029.7
XS Rating Curve= 0 ,0
Exp/Cntr=0.3,0.1

Type RM Length L Ch R = 1 ,7529    ,321,321,321
BEGIN DESCRIPTION:
UNT052 IN BECR 15.0
END DESCRIPTION:
XS GIS Cut Line= 2
      3800588.05     10498715.26      3799785.05     10498606.75
#Sta/Elev= 30
  4492.7  337.21  4531.5  335.91  4551.7  333.68  4567.4  330.36    4592  328.13
  4652.6  320.53  4824.1  306.36  4884.7  302.53  4935.1  301.38  4965.4  302.49
  4975.5  300.45  4985.6     291  4992.7  288.31  4995.4  287.81  4998.7  288.31
  5013.4  294.31  5025.9  295.01  5066.3  296.77  5076.4  300.55  5091.1  302.51
  5106.7  307.25  5116.8  308.84  5136.9  313.95    5147  317.46  5168.8  322.34
  5177.3  322.36  5187.4  324.33  5217.7   325.9  5241.4   328.3    5303  331.34
#Mann= 3 ,-1 , 0
  4492.7     .16       0  4992.7     .07       0  4998.7     .16       0
Bank Sta=4965.4,5025.9
XS Rating Curve= 0 ,0
Exp/Cntr=0.3,0.1

Type RM Length L Ch R = 1 ,7208    ,736,736,736
BEGIN DESCRIPTION:
UNT052 IN BECR 14.0
END DESCRIPTION:
XS GIS Cut Line= 2
      3800621.48     10498516.99      3799744.69     10498308.64
#Sta/Elev= 30
  4461.9  336.43  4494.7  335.69  4751.6   305.7  4833.8  300.86  4895.5  301.16
  4916.1  300.03  4926.4  295.92  4936.6  294.37    4991  292.88  4995.3  288.54
    4998  288.04  5001.3  288.54  5008.6  288.91  5018.9  299.61    5028   302.9
  5033.1  301.37  5039.4  303.99  5049.7  304.48  5070.2  309.34  5075.3  307.81
  5090.8  311.65  5111.4   314.1  5117.5  314.33  5122.6  311.12  5131.9  311.44
  5142.2  314.96  5201.9  320.82  5234.7  321.65  5327.2  328.79  5363.1  329.44
#Mann= 3 ,-1 , 0
  4461.9     .16       0  4995.3     .07       0  5001.3     .16       0
Bank Sta=4895.5,5028
XS Rating Curve= 0 ,0
Exp/Cntr=0.3,0.1

Type RM Length L Ch R = 1 ,6472    ,541,541,541
BEGIN DESCRIPTION:
UNT052 IN BECR 13.0
END DESCRIPTION:
XS GIS Cut Line= 3
      3800647.49      10498421.5       3800282.9     10497857.26
      3799970.36     10497718.35
#Sta/Elev= 30
  4547.2  333.27  4596.4  331.32  4626.2  327.81  4632.1  328.83  4662.5  324.37
  4683.6  324.37    4735  317.49  4756.1  316.59  4834.7  306.27  4901.3     301
  4943.5   299.6  4965.5  297.73  4979.8  289.03    4989  289.99    4995  285.46
  5007.1  285.45  5009.9  284.95  5013.1  285.45  5016.1  289.72    5025  295.25
  5037.2  298.53  5096.4  297.12  5132.1  298.52  5176.4  297.85  5191.6  298.91
  5212.7  304.42  5217.4  307.66  5295.8  316.84  5492.8   323.1    5561  323.56
#Mann= 3 ,-1 , 0
  4547.2     .16       0  5007.1     .07       0  5013.1     .16       0
Bank Sta=4943.5,5037.2
XS Rating Curve= 0 ,0
Exp/Cntr=0.3,0.1

Type RM Length L Ch R = 1 ,5931    ,479,479,479
BEGIN DESCRIPTION:
UNT052 IN BECR 12.0
END DESCRIPTION:
XS GIS Cut Line= 2
       3801035.1     10497734.36      3800019.45     10497621.51
#Sta/Elev= 30
  4625.3  329.82  4691.2  324.77  4707.3  322.48  4712.3  323.67  4802.9  318.95
  4862.2  311.36  4882.4  307.06  4888.4  304.92  4902.5  304.36  4922.6  299.24
  4932.7  292.68  4952.8  290.54    4979  289.88    4984  286.36    4990  284.05
  4992.8  283.55    4996  284.05  5013.2  291.58  5053.4  294.38  5294.9  296.35
  5335.1  298.54  5341.2  299.88  5355.3  299.57  5395.5  303.19  5425.7  308.91
  5445.8   310.6    5476  314.66  5617.9  322.73  5626.9  320.03  5647.2   321.2
#Mann= 3 ,-1 , 0
  4625.3     .16       0    4990     .07       0    4996     .16       0
Bank Sta=4979,5053.4
XS Rating Curve= 0 ,0
Exp/Cntr=0.3,0.1

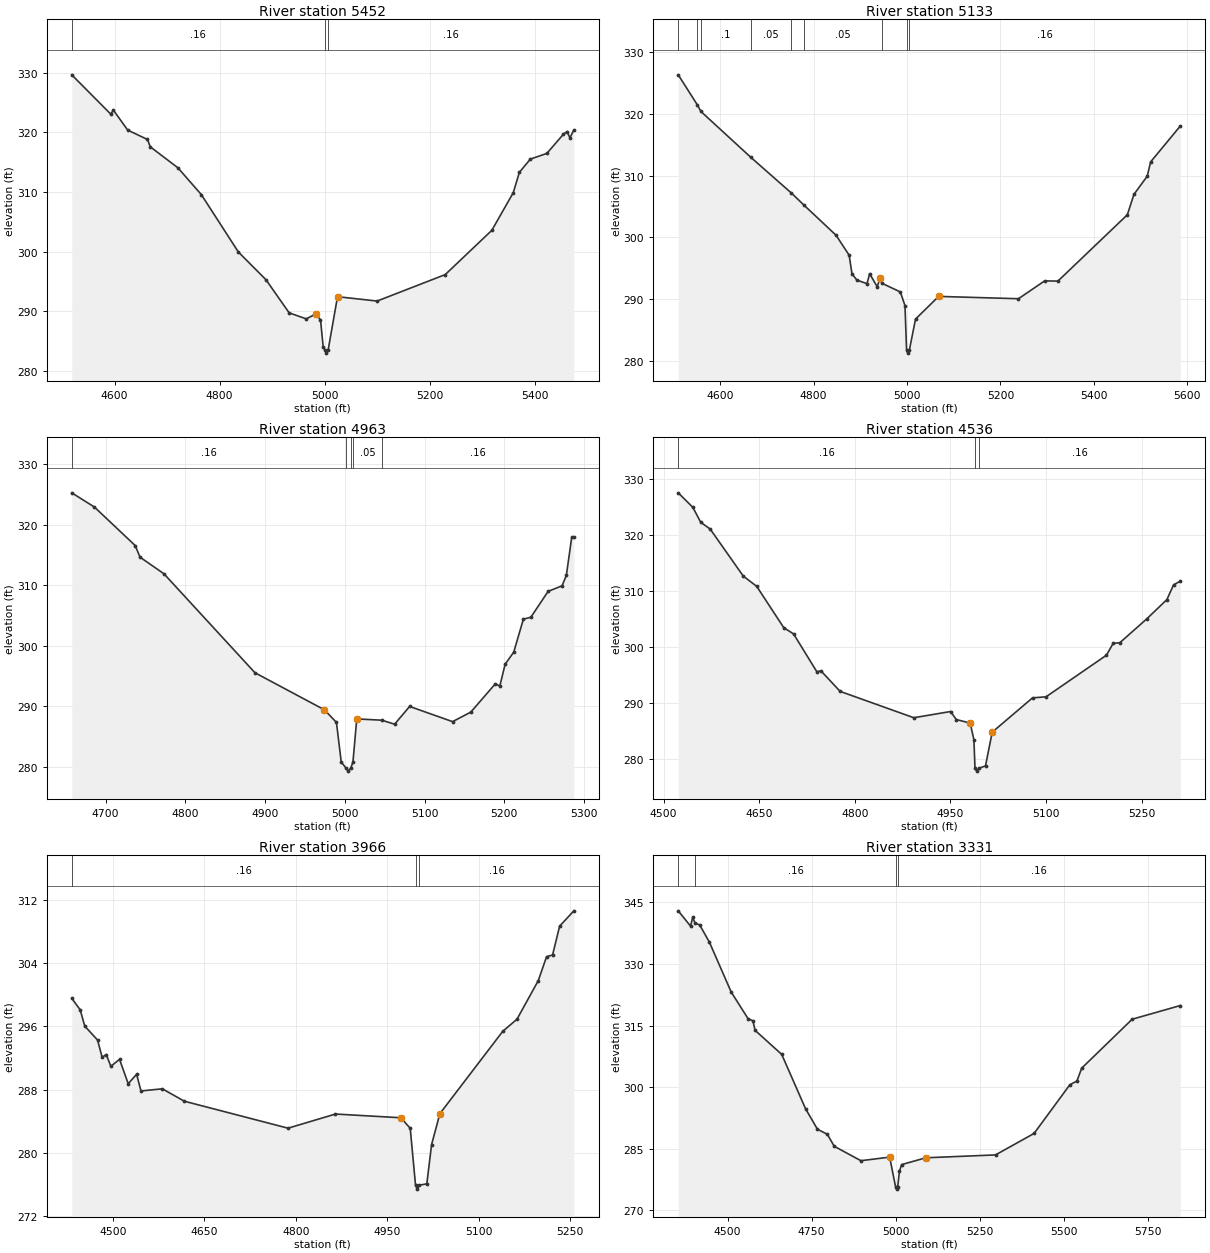
Type RM Length L Ch R = 1 ,5452    ,319,319,319
BEGIN DESCRIPTION:
UNT052 IN BECR 11.0
END DESCRIPTION:
XS GIS Cut Line= 2
      3801002.11     10497272.02      3800090.67     10497558.47
#Sta/Elev= 30
  4518.6  329.64  4592.6  323.07  4597.9  323.71    4625  320.38  4662.7   318.8
    4668  317.57  4720.4  314.07  4765.1  309.57  4835.7  299.93  4888.1   295.3
  4932.3  289.74  4964.7  288.74  4982.4  289.51  4991.9  288.59  4997.1  284.01
  5000.4  283.49  5003.2  282.99  5006.4  283.49  5024.3  292.45  5099.6  291.72
  5229.2  296.15  5317.9  303.57  5358.8   309.9  5370.3  313.29  5391.2  315.51
  5422.7  316.47  5454.1  319.68  5461.2  320.14  5466.5  319.06    5474  320.39
#Mann= 3 ,-1 , 0
  4518.6     .16       0  5000.4     .07       0  5006.4     .16       0
Bank Sta=4982.4,5024.3
XS Rating Curve= 0 ,0
Exp/Cntr=0.3,0.1

Type RM Length L Ch R = 1 ,5133    ,170,170,170
BEGIN DESCRIPTION:
Mapping XS f3ba65ee
END DESCRIPTION:
XS GIS Cut Line= 3
      3801007.25     10496902.26       3800512.5     10497167.86
      3800134.36     10497514.92
#Sta/Elev= 30
  4510.2  326.33  4550.9  321.49  4558.8  320.39  4665.4  312.98  4752.5  307.18
    4780  305.18    4848  300.35  4876.1  297.11  4882.1  294.13  4892.4  293.09
  4914.3   292.5  4919.9  294.12  4936.2  291.99  4941.9  293.36  4946.1  292.57
  4985.7  291.16  4995.6  288.95    4999  281.75  5001.7  281.25    5005  281.75
  5018.2  286.77  5067.7  290.44  5238.5  290.06  5294.6  292.95    5323  292.92
  5471.6  303.66  5485.8  306.97  5514.1   309.9  5521.5  312.23    5585  318.04
#Mann= 9 ,-1 , 0
  4510.2      .1       0  4550.9     .08       0  4558.8      .1       0
  4665.4     .05       0  4752.5     .16       0    4780     .05       0
  4946.1     .16       0    4999     .07       0    5005     .16       0
Bank Sta=4941.9,5067.7
XS Rating Curve= 0 ,0
Exp/Cntr=0.3,0.1

Type RM Length L Ch R = 1 ,4963    ,427,427,427
BEGIN DESCRIPTION:
UNT052 IN BECR 10.0
END DESCRIPTION:
XS GIS Cut Line= 3
      3800799.59      10496810.2      3800499.61     10497010.19
       3800249.6     10497110.19
#Sta/Elev= 30
  4657.5  325.25    4686  322.89  4737.1  316.53  4743.1  314.62  4773.2  311.86
  4887.3  295.51  4974.5  289.38  4989.5   287.3  4995.5  280.78  5001.5  279.75
  5004.3  279.25  5007.5  279.75  5010.2  280.75    5015  287.88  5046.3  287.67
  5062.5  287.01  5081.3  289.94  5135.2  287.43  5158.1  289.01    5189  293.71
  5194.4  293.29  5201.1  296.92  5211.9  298.92    5224  304.37  5233.4  304.69
    5255  308.96  5272.5  309.88  5277.9   311.6  5284.6  317.87  5287.3  317.87
#Mann= 5 ,-1 , 0
  4657.5     .16       0  5001.5     .07       0  5007.5     .16       0
  5010.2     .05       0  5046.3     .16       0
Bank Sta=4974.5,5015
XS Rating Curve= 0 ,0
Exp/Cntr=0.3,0.1

Type RM Length L Ch R = 1 ,4536    ,570,570,570
BEGIN DESCRIPTION:
UNT052 IN BECR 9.0
END DESCRIPTION:
XS GIS Cut Line= 3
      3800649.57     10496460.21      3800249.61     10496710.19
       3800149.6      10497010.2
#Sta/Elev= 30
    4523  327.48    4546  324.88  4558.3  322.22  4573.1  321.02    4625  312.63
  4646.2  310.78  4688.6  303.41    4704   302.3  4740.5  295.55    4747   295.7
  4777.1  292.04  4892.7  287.34  4950.4  288.45  4959.3  287.02  4981.1  286.39
    4987  283.42  4988.7  278.31  4991.5  277.81  4994.7  278.31  5005.2  278.75
  5015.7  284.76    5079  290.89  5100.1  291.07  5194.9  298.49  5205.5  300.61
    5216  300.73  5258.2  304.98  5289.8  308.42  5300.3  311.05  5310.9  311.72
#Mann= 3 ,-1 , 0
    4523     .16       0  4988.7     .07       0  4994.7     .16       0
Bank Sta=4981.1,5015.7
XS Rating Curve= 0 ,0
Exp/Cntr=0.3,0.1

Type RM Length L Ch R = 1 ,3966    ,635,635,635
BEGIN DESCRIPTION:
UNT052 IN BECR 8.0
END DESCRIPTION:
XS GIS Cut Line= 3
       3800349.6     10496010.19      3799949.61     10496360.19
      3799699.65     10496510.16
#Sta/Elev= 30
  4432.9  299.55  4446.7   298.1  4454.2  296.03  4475.1  294.28  4482.7  292.09
  4489.4  292.44    4497  290.95  4511.2  291.83  4525.4  288.75  4539.2  289.94
  4546.3  287.83  4581.4   288.1  4617.5  286.53  4787.4  283.12  4865.2  284.91
  4972.2  284.44  4987.7  283.11  4996.4  275.91  4999.1  275.41  5002.4  275.91
  5014.9  276.08  5022.7  281.04  5036.3  284.96  5139.3  295.37  5162.7  296.91
  5197.6  301.79  5211.2  304.82    5221  305.03  5232.6  308.68  5255.9  310.62
#Mann= 3 ,-1 , 0
  4432.9     .16       0  4996.4     .07       0  5002.4     .16       0
Bank Sta=4972.2,5036.3
XS Rating Curve= 0 ,0
Exp/Cntr=0.3,0.1

Type RM Length L Ch R = 1 ,3331    ,654,654,654
BEGIN DESCRIPTION:
UNT052 IN BECR 7.0
END DESCRIPTION:
XS GIS Cut Line= 2
      3800369.72     10495470.09      3799173.16     10496363.18
#Sta/Elev= 30
  4353.3  342.95  4389.9  339.23  4396.2  341.33  4403.6  339.93    4417  339.53
  4446.2  335.28  4510.9  323.16  4560.9   316.7  4575.5  316.17  4581.7  313.86
    4661     308  4731.8  294.78  4767.3  289.77  4796.5  288.56  4817.3  285.62
  4896.5  282.11    4982  282.98  4999.8  275.69  5002.6  275.19  5005.8  275.69
  5011.2  279.55  5017.4  281.16  5089.7  282.82  5296.8  283.52  5411.5  288.75
  5517.8  300.59  5538.9  301.51  5553.2  304.65  5703.3  316.56  5846.4  319.89
#Mann= 4 ,-1 , 0
  4353.3     .05       0  4403.6     .16       0  4999.8     .07       0
  5005.8     .16       0
Bank Sta=4982,5089.7
XS Rating Curve= 0 ,0
Exp/Cntr=0.3,0.1

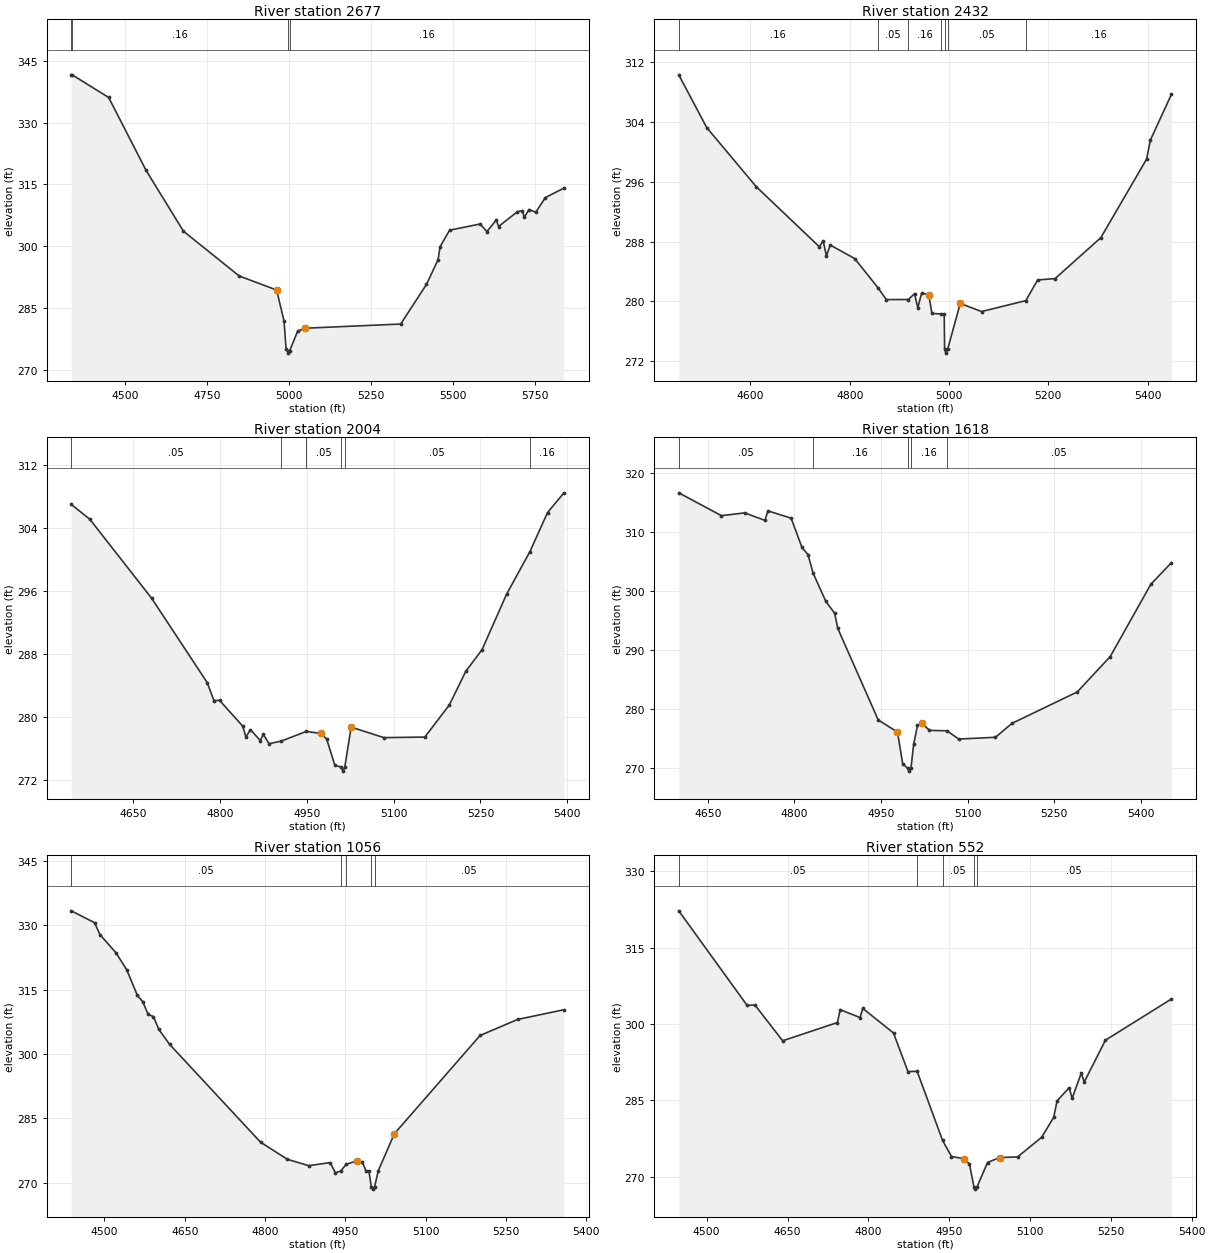
Type RM Length L Ch R = 1 ,2677    ,245,245,245
BEGIN DESCRIPTION:
UNT052 IN BECR 6.0
END DESCRIPTION:
XS GIS Cut Line= 3
      3800204.78     10495105.51      3799484.29     10495661.08
      3799119.68     10496129.86
#Sta/Elev= 30
    4335   341.5  4337.6  341.61    4449  336.12  4563.1  318.43  4677.3  303.65
  4847.5  292.78  4961.7  289.37  4984.4  281.85  4990.7  274.95  4995.2  274.55
  4997.9  274.05  5001.2  274.55    5026   279.4  5048.7   280.1  5340.4  281.11
  5419.1  290.73  5454.4   296.7  5460.7  299.88  5489.7   303.9  5582.9   305.4
  5603.7  303.56  5632.6   306.4    5639  304.78  5696.9  308.39  5711.4  308.62
  5717.7  307.03  5732.2  308.91    5753  308.27    5782  311.81  5838.7  314.11
#Mann= 4 ,-1 , 0
    4335     .05       0  4337.6     .16       0  4995.2     .07       0
  5001.2     .16       0
Bank Sta=4961.7,5048.7
XS Rating Curve= 0 ,0
Exp/Cntr=0.3,0.1

Type RM Length L Ch R = 1 ,2432    ,428,428,428
BEGIN DESCRIPTION:
UNT052 IN BECR 5.0
END DESCRIPTION:
XS GIS Cut Line= 3
      3799849.59     10495110.21      3799449.61     10495460.19
      3799149.58     10495810.22
#Sta/Elev= 30
  4455.6  310.34    4512  303.27  4611.7  295.36  4738.9  287.31  4746.5  288.12
  4753.1  286.07  4760.7  287.55  4810.1  285.73  4856.8  281.84  4873.7  280.24
    4918  280.25  4930.6  281.03  4937.2  279.14  4944.8   281.1  4959.1  280.92
  4965.7  278.38  4983.6  278.32  4990.4  278.33  4991.2  273.57    4994  273.07
  4997.2  273.57  5022.7  279.73  5065.6  278.64  5154.8   280.1  5178.6  282.87
  5213.7  283.05  5305.9  288.53  5398.1  299.05  5405.8  301.61  5448.1  307.71
#Mann= 7 ,-1 , 0
  4455.6     .16       0  4856.8     .05       0    4918     .16       0
  4983.6     .05       0  4991.2     .03       0  4997.2     .05       0
  5154.8     .16       0
Bank Sta=4959.1,5022.7
XS Rating Curve= 0 ,0
Exp/Cntr=0.3,0.1

Type RM Length L Ch R = 1 ,2004    ,386,386,386
BEGIN DESCRIPTION:
UNT052 IN BECR 4.0
END DESCRIPTION:
XS GIS Cut Line= 3
       3799249.6     10494910.22      3799099.61     10495310.19
      3798799.63     10495610.17
#Sta/Elev= 30
  4542.8  306.95  4574.8  305.07  4681.6  295.05  4777.7  284.35  4789.3  282.07
  4799.1  282.09  4839.1  278.83  4844.5  277.44  4852.5  278.38  4869.4     277
  4874.7  277.78  4884.5   276.6  4905.3  276.92  4948.8  278.15  4973.5  277.91
  4984.1  277.21  4998.2  273.88  5009.4  273.62  5012.1  273.12  5015.4  273.62
  5026.5   278.7  5083.1  277.37  5153.8  277.44  5196.2  281.52  5224.5  285.77
  5252.8  288.54  5295.2  295.58  5335.2  300.93  5365.9  305.92  5394.2  308.42
#Mann= 6 ,-1 , 0
  4542.8     .05       0  4905.3     .16       0  4948.8     .05       0
  5009.4     .03       0  5015.4     .05       0  5335.2     .16       0
Bank Sta=4973.5,5026.5
XS Rating Curve= 0 ,0
Exp/Cntr=0.3,0.1

Type RM Length L Ch R = 1 ,1618    ,562,562,562
BEGIN DESCRIPTION:
UNT052 IN BECR 3.0
END DESCRIPTION:
XS GIS Cut Line= 3
      3798953.48     10494783.79      3798854.51     10495158.84
      3798499.58     10495460.21
#Sta/Elev= 30
  4599.6  316.66  4673.5  312.79  4713.8  313.26  4748.9  311.99  4754.1   313.6
  4794.3  312.36  4813.1  307.39  4823.4   306.2  4832.3  303.05  4854.4  298.25
  4869.7  296.23  4875.1  293.66  4945.1  278.15  4978.5  276.08  4987.5  270.75
  4995.9  269.96  4998.6  269.46  5001.9  269.96  5006.6  274.01  5013.2  277.21
  5020.2  277.62    5034  276.37  5064.3   276.3  5084.6   274.9  5148.3   275.2
  5176.9  277.56    5290  282.89  5347.1  288.89  5417.4  301.14  5453.1  304.82
#Mann= 5 ,-1 , 0
  4599.6     .05       0  4832.3     .16       0  4995.9     .07       0
  5001.9     .16       0  5064.3     .05       0
Bank Sta=4978.5,5020.2
XS Rating Curve= 0 ,0
Exp/Cntr=0.3,0.1

Type RM Length L Ch R = 1 ,1056    ,504,504,504
BEGIN DESCRIPTION:
UNT052 IN BECR 2.0
END DESCRIPTION:
XS GIS Cut Line= 3
      3798354.51     10494606.72      3798349.61     10495160.19
      3798359.67     10495526.86
#Sta/Elev= 30
  4438.1  333.33  4481.6  330.56  4491.6   327.8  4521.6  323.56  4541.6  319.61
  4561.6  313.64  4571.6  312.18  4581.6  309.22  4591.6  308.71  4601.6  305.72
  4621.6  302.27  4791.6  279.48  4841.6   275.5  4881.6  274.01  4921.6  274.73
  4931.6  272.33  4941.5  272.78  4951.5   274.3  4971.6  275.15  4981.6  274.84
  4989.1  272.71  4994.1  272.71  4998.6  269.05  5001.3  268.55  5004.6  269.05
  5011.6  272.84  5041.6  281.44  5201.7  304.31  5271.7  308.04  5358.4  310.31
#Mann= 5 ,-1 , 0
  4438.1     .05       0  4941.5     .16       0  4951.5     .05       0
  4998.6     .03       0  5004.6     .05       0
Bank Sta=4971.6,5041.6
XS Rating Curve= 0 ,0
Exp/Cntr=0.3,0.1

Type RM Length L Ch R = 1 ,552     ,418,418,418
BEGIN DESCRIPTION:
Mapping XS 32e4c6d0
END DESCRIPTION:
XS GIS Cut Line= 3
      3798104.51     10494632.79      3798000.35     10495065.09
      3798208.25     10495486.08
#Sta/Elev= 30
  4448.2  322.23    4575  303.65  4589.5  303.73    4641  296.69  4742.6  300.28
  4747.8  302.81  4784.6  301.25  4789.7  303.06  4846.7  298.22  4873.5  290.65
  4890.6  290.68  4937.8   277.1  4954.3  273.95  4976.6  273.54  4987.5  272.51
  4995.9  268.04  4998.7  267.54  5001.9  268.04  5021.2  272.77  5043.6  273.75
    5077  273.87  5121.6  277.73  5143.9  281.63  5150.2  284.87  5172.7  287.48
  5178.2  285.38  5195.1  290.32  5200.7   288.6    5240  296.81  5362.4   304.9
#Mann= 5 ,-1 , 0
  4448.2     .05       0  4890.6     .16       0  4937.8     .05       0
  4995.9     .03       0  5001.9     .05       0
Bank Sta=4976.6,5043.6
XS Rating Curve= 0 ,0
Exp/Cntr=0.3,0.1

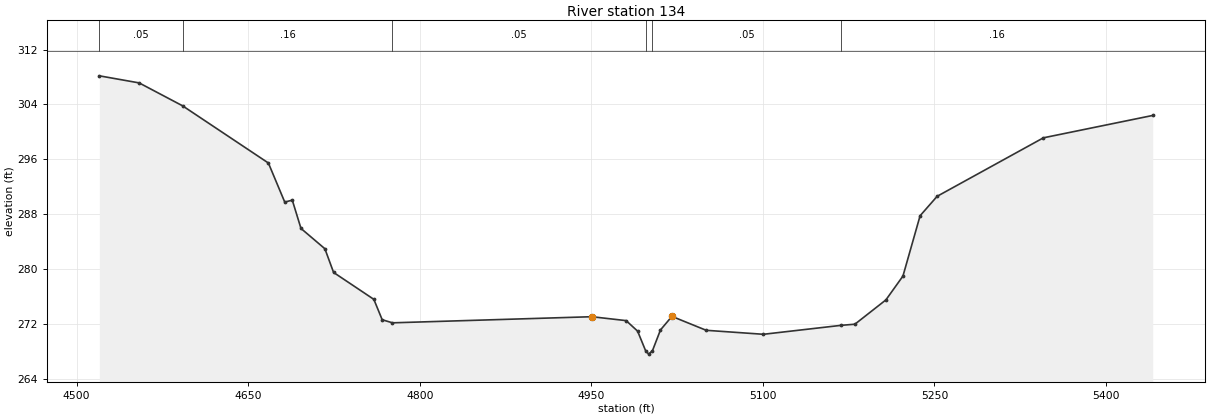
Type RM Length L Ch R = 1 ,134     ,0,0,0
BEGIN DESCRIPTION:
UNT052 IN BECR 1.0
END DESCRIPTION:
XS GIS Cut Line= 4
       3797956.5     10494888.52      3797696.09      10495114.2
      3797696.09     10495365.94      3797964.89     10495548.03
#Sta/Elev= 30
  4519.9  308.17  4554.7  307.14  4592.7   303.8  4667.7  295.47    4682  289.78
  4688.6  290.06  4696.2  285.94  4717.1  282.98  4724.7  279.53  4759.9  275.61
  4767.2  272.64  4776.2  272.19  4950.5  273.08  4980.5  272.51  4990.5  270.98
  4997.5  268.13  5000.2  267.63  5003.5  268.13  5010.5  271.15  5020.5  273.13
  5050.5   271.1  5100.5  270.52  5168.3  271.82  5180.5  271.99  5207.6  275.53
  5222.5     279  5237.5  287.79  5252.4  290.62  5345.3  299.14  5440.9   302.4
#Mann= 6 ,-1 , 0
  4519.9     .05       0  4592.7     .16       0  4776.2     .05       0
  4997.5     .03       0  5003.5     .05       0  5168.3     .16       0
Bank Sta=4950.5,5020.5
XS Rating Curve= 0 ,0
Exp/Cntr=0.3,0.1

Chan Stop Cuts=-1
Use User Specified Reach Order=0
Composite Channel Slope=5