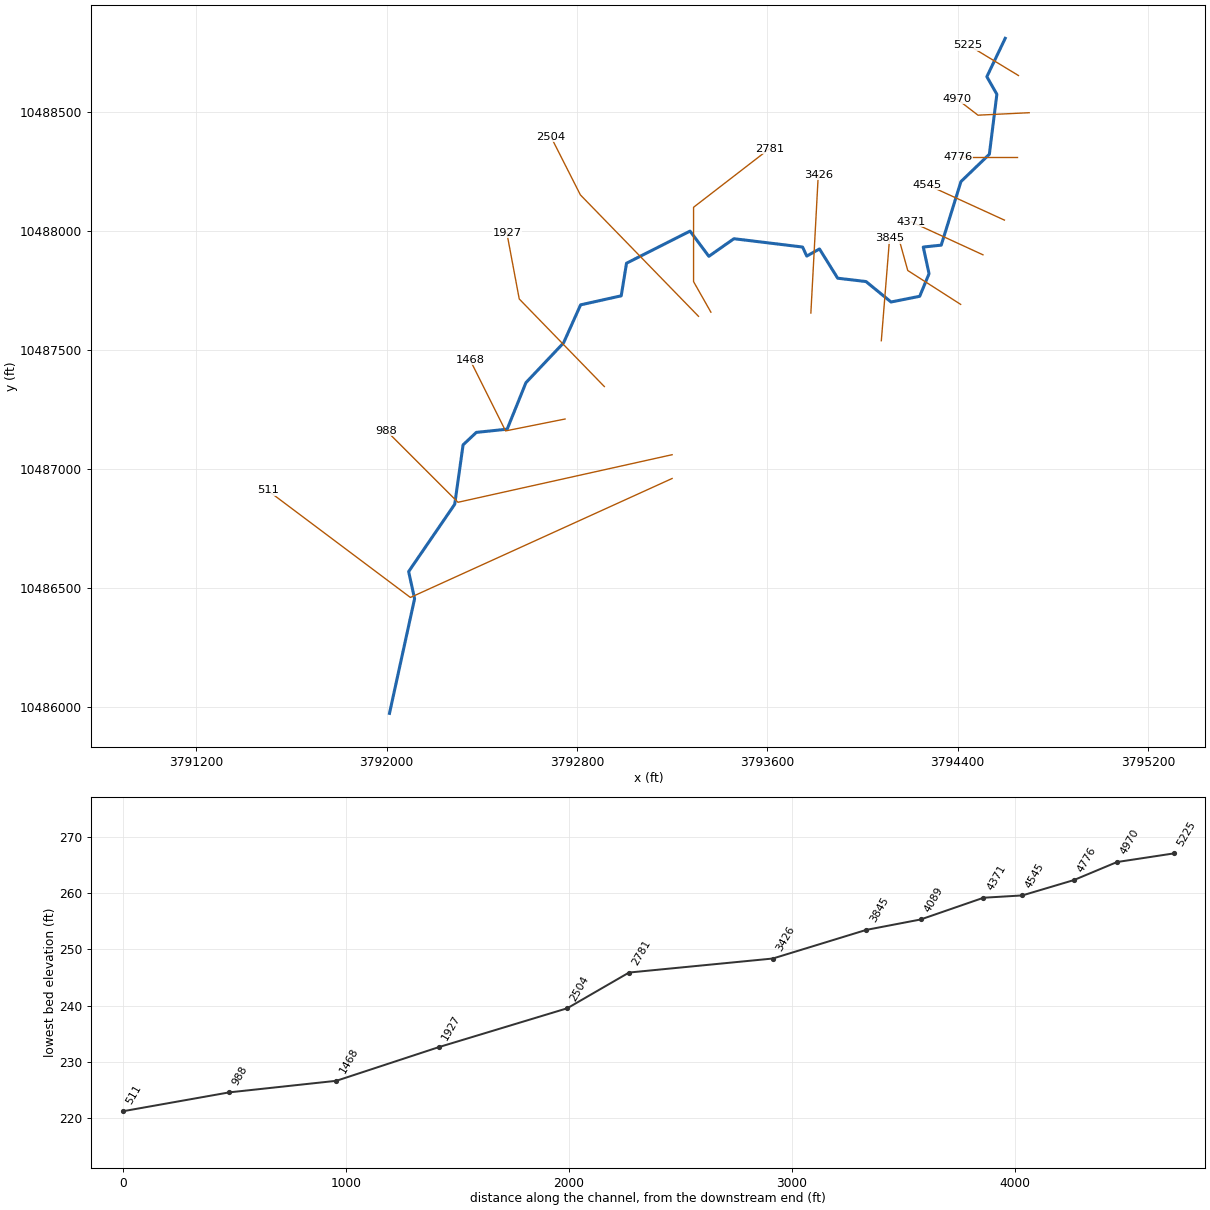
--- UNT055 IN BECR.prj (project) ---

Proj Title=UNT055 IN BECR Base Level Engineering
Current Plan=p01
Default Exp/Contr=0.3,0.1
English Units
Geom File=g01
Flow File=f01
Plan File=p01
Y Axis Title=Elevation
X Axis Title(PF)=Main Channel Distance
X Axis Title(XS)=Station
BEGIN DESCRIPTION:
UNT055 IN BECR
END DESCRIPTION:
DSS Export Rating Curves= 0
DSS Export Rating Curve Sorted= 0
DSS Export Volume Flow Curves= 0
DXF OffsetX= 0
DXF OffsetY= 0
DXF ScaleX= 1
DXF ScaleY= 10

--- UNT055 IN BECR.p01 (plan) ---

Plan Title=Multiple Run
Short Identifier=Multiple
Geom File=g01
Flow File=f01
Subcritical Flow
K Sum by GR= 0
Std Step Tol= 0.01
Critical Tol= 0.01
Num of Std Step Trials= 20
Max Error Tol= 0.3
Flow Tol Ratio= 0.001
Split Flow NTrial= 30
Split Flow Tol= 0.02
Split Flow Ratio= 0.02
Log Output Level= 0
Friction Slope Method= 1
Unsteady Friction Slope Method= 2
Unsteady Bridges Friction Slope Method= 1
Parabolic Critical Depth
Global Vel Dist=  1 , 1 , 1
Global Log Level= 0
CheckData=True
Encroach Param= -1, 0, 0, 0
BEGIN DESCRIPTION:
Multiple Run
END DESCRIPTION:

--- UNT055 IN BECR.f01 (steady flow) ---

Flow Title=Multiple
Number of Profiles=7
Profile Names=10-year,25-year,50-year,1pct_min,100-year,1pct_plu,500-year
River Rch & RM= UNT055 IN BECR,Reach-1,5225
     142     173     196     164     222     301     286
River Rch & RM= UNT055 IN BECR,Reach-1,2504
     269     344     403     348     470     636     642
Boundary for River Rch & Prof#=UNT055 IN BECR,Reach-1,1
Up Type=0
Dn Type=3
Dn Slope=0.005
Boundary for River Rch & Prof#=UNT055 IN BECR,Reach-1,2
Up Type=0
Dn Type=3
Dn Slope=0.005
Boundary for River Rch & Prof#=UNT055 IN BECR,Reach-1,3
Up Type=0
Dn Type=3
Dn Slope=0.005
Boundary for River Rch & Prof#=UNT055 IN BECR,Reach-1,4
Up Type=0
Dn Type=3
Dn Slope=0.005
Boundary for River Rch & Prof#=UNT055 IN BECR,Reach-1,5
Up Type=0
Dn Type=3
Dn Slope=0.005
Boundary for River Rch & Prof#=UNT055 IN BECR,Reach-1,6
Up Type=0
Dn Type=3
Dn Slope=0.005
Boundary for River Rch & Prof#=UNT055 IN BECR,Reach-1,7
Up Type=0
Dn Type=3
Dn Slope=0.005

--- UNT055 IN BECR.g01 (geometry) ---

Geom Title=Existing Conditions
Program Version=4.10

River Reach=UNT055 IN BECR  ,Reach-1
Reach XY= 30
      3794599.61     10488810.19       3794522.5       10488649.
       3794564.5       10488575.        3794533.       10488323.
       3794413.5       10488208.      3794330.75       10487941.
      3794255.25       10487933.       3794279.5       10487821.
      3794240.25       10487726.      3794119.75       10487702.
       3794014.5       10487788.       3793895.5       10487802.
        3793819.       10487925.       3793765.5       10487895.
        3793748.       10487933.       3793459.5       10487968.
        3793354.       10487894.        3793275.       10488000.
        3793008.       10487865.      3792985.75       10487728.
        3792815.       10487690.      3792743.25       10487530.
      3792585.25       10487363.      3792506.32     10487167.43
      3792376.75       10487154.      3792321.07      10487101.5
        3792286.       10486852.      3792092.25       10486569.
      3792117.25       10486455.      3792011.75       10485973.

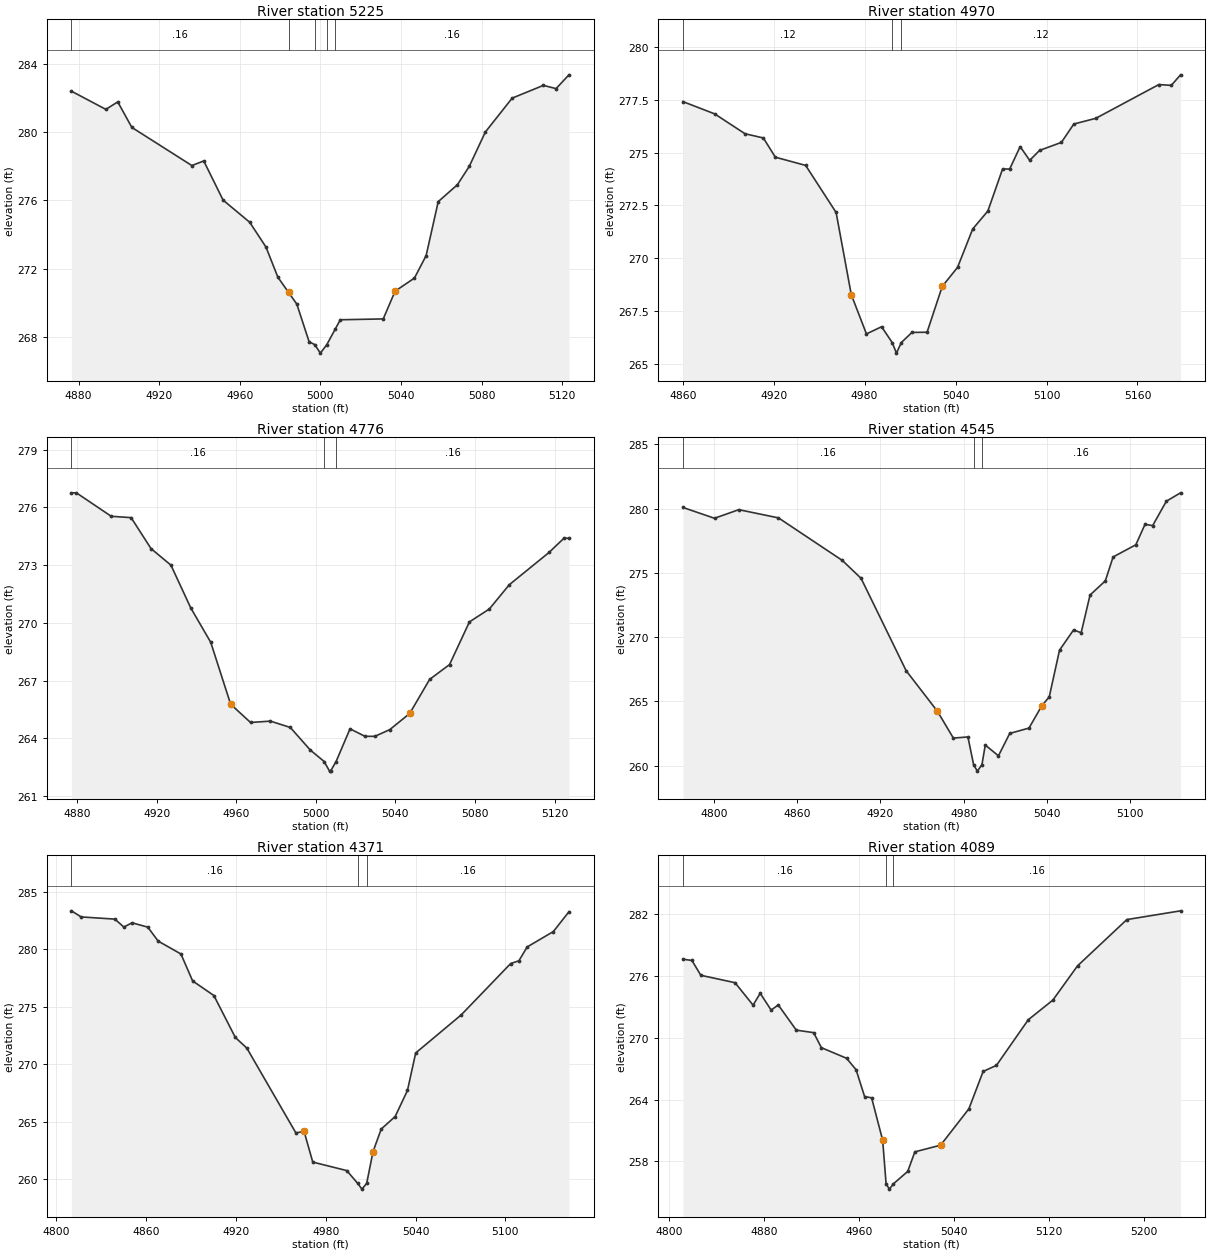
Type RM Length L Ch R = 1 ,5225    ,255,255,255
BEGIN DESCRIPTION:
UNT055 IN BECR 11.0
END DESCRIPTION:
XS GIS Cut Line= 2
      3794655.29     10488653.88       3794444.1     10488781.98
#Sta/Elev= 30
  4876.4  282.42  4893.5  281.35  4899.4  281.79  4906.4  280.29  4936.2  278.05
  4942.1  278.32  4951.7  276.02  4964.9  274.72    4973  273.26  4978.9  271.49
  4984.2   270.6  4988.3  269.91  4994.4   267.7  4997.2  267.53    5000  267.03
  5003.2  267.53  5007.5  268.47  5009.9  268.99  5031.2  269.04  5037.1  270.67
  5046.7  271.44  5052.5  272.76  5058.5  275.93    5068  276.92  5073.9     278
  5081.9  280.02  5095.2  282.01  5110.7  282.76    5117  282.57  5123.4  283.38
#Mann= 5 ,-1 , 0
  4876.4     .16       0  4984.2     .12       0  4997.2     .07       0
  5003.2     .12       0  5007.5     .16       0
Bank Sta=4984.2,5037.1
XS Rating Curve= 0 ,0
Exp/Cntr=0.3,0.1

Type RM Length L Ch R = 1 ,4970    ,194,194,194
BEGIN DESCRIPTION:
Mapping XS 0c835217
END DESCRIPTION:
XS GIS Cut Line= 3
      3794700.45     10488497.61      3794485.18     10488487.19
      3794395.87     10488555.89
#Sta/Elev= 30
  4860.2  277.41  4881.1  276.83  4901.1  275.89  4913.2  275.69  4921.1  274.78
  4941.1  274.39  4961.2  272.16  4971.2  268.27  4981.2  266.41  4991.2  266.75
  4998.2     266    5001   265.5  5004.2     266  5011.2  266.48  5021.2  266.49
  5031.2  268.66  5041.3  269.56  5051.3  271.38  5061.3  272.23    5071  274.22
  5075.7  274.22  5082.6  275.28  5088.9  274.63  5095.4   275.1  5109.8  275.48
    5118  276.35  5132.5  276.62  5174.1  278.22  5182.3  278.18  5188.4  278.68
#Mann= 3 ,-1 , 0
  4860.2     .12       0  4998.2     .07       0  5004.2     .12       0
Bank Sta=4971.2,5031.2
XS Rating Curve= 0 ,0
Exp/Cntr=0.3,0.1

Type RM Length L Ch R = 1 ,4776    ,231,231,231
BEGIN DESCRIPTION:
UNT055 IN BECR 10.0
END DESCRIPTION:
XS GIS Cut Line= 3
      3794649.59     10488310.19      3794499.61     10488310.19
      3794399.59     10488310.19
#Sta/Elev= 30
  4877.2  276.76  4879.7  276.76  4897.2  275.54  4907.2  275.47  4917.2  273.86
  4927.2     273  4937.2  270.77  4947.2  268.99  4957.2  265.77  4967.2  264.82
  4977.2  264.89  4987.2  264.56  4997.2  263.39  5004.2  262.79  5006.9  262.29
  5007.4  262.29  5010.2  262.79  5017.2  264.49  5024.7   264.1  5029.7   264.1
  5037.2  264.45  5047.2  265.29  5057.2  267.06  5067.2  267.83  5077.2  270.05
  5087.2  270.72  5097.2  271.98  5117.2  273.66  5124.7   274.4  5127.2   274.4
#Mann= 3 ,-1 , 0
  4877.2     .16       0  5004.2     .07       0  5010.2     .16       0
Bank Sta=4957.2,5047.2
XS Rating Curve= 0 ,0
Exp/Cntr=0.3,0.1

Type RM Length L Ch R = 1 ,4545    ,174,174,174
BEGIN DESCRIPTION:
Mapping XS e2848862
END DESCRIPTION:
XS GIS Cut Line= 2
      3794596.31     10488046.21       3794270.3     10488195.34
#Sta/Elev= 30
  4777.8  280.08  4800.5  279.24    4818  279.91  4846.6  279.27  4892.6  275.96
  4906.1  274.57  4938.6  267.38  4961.1  264.23  4972.6  262.14  4983.1  262.23
  4987.2  260.07  4989.9  259.57  4993.2  260.07  4995.6   261.6  5005.1  260.76
  5013.2   262.5  5027.1  262.92  5036.2  264.63  5041.7  265.35  5049.1  268.98
  5059.2  270.55  5064.7  270.34  5071.1  273.27  5082.1  274.37  5087.7  276.23
  5104.1  277.18  5110.7  278.77  5116.2  278.67  5126.1  280.57  5136.3  281.22
#Mann= 3 ,-1 , 0
  4777.8     .16       0  4987.2     .07       0  4993.2     .16       0
Bank Sta=4961.1,5036.2
XS Rating Curve= 0 ,0
Exp/Cntr=0.3,0.1

Type RM Length L Ch R = 1 ,4371    ,282,282,282
BEGIN DESCRIPTION:
UNT055 IN BECR 9.0
END DESCRIPTION:
XS GIS Cut Line= 2
      3794505.98      10487900.4      3794204.25     10488039.13
#Sta/Elev= 30
  4810.3  283.34  4816.8  282.81  4839.3  282.62  4845.3  281.93  4850.8   282.3
  4861.3  281.92  4868.2  280.71  4883.4  279.59  4891.2  277.25  4905.4  275.98
  4919.7  272.34  4927.4  271.41  4960.1  264.05  4965.6  264.17  4971.4  261.51
  4994.1  260.77  5001.4  259.66  5004.2  259.16  5007.4  259.66  5011.6  262.41
  5017.1  264.38  5026.4  265.47  5034.6  267.73  5040.1  270.99  5070.5   274.3
  5103.5  278.76    5109     279  5114.5   280.2    5132  281.54  5142.4  283.26
#Mann= 3 ,-1 , 0
  4810.3     .16       0  5001.4     .07       0  5007.4     .16       0
Bank Sta=4965.6,5011.6
XS Rating Curve= 0 ,0
Exp/Cntr=0.3,0.1

Type RM Length L Ch R = 1 ,4089    ,244,244,244
BEGIN DESCRIPTION:
Mapping XS 71105238
END DESCRIPTION:
XS GIS Cut Line= 3
      3794412.27     10487692.05      3794190.04     10487834.41
      3794148.38      10487983.7
#Sta/Elev= 30
  4811.7  277.63  4819.2  277.51  4826.7  276.07  4855.5  275.35  4870.7  273.17
  4876.7  274.32  4885.9  272.69  4891.9  273.19  4907.1  270.74  4921.7   270.5
  4928.2  269.04  4949.4  268.01  4957.4   266.9  4964.6  264.29  4970.5  264.17
  4979.8  260.05  4982.7   255.8  4985.5   255.3  4988.7   255.8  5000.9  257.02
  5006.9  258.92  5028.6  259.57  5052.4   263.1  5064.4  266.73  5075.6  267.32
  5102.4  271.75  5123.1  273.66  5143.9  276.99  5185.4  281.48  5230.6  282.33
#Mann= 3 ,-1 , 0
  4811.7     .16       0  4982.7     .07       0  4988.7     .16       0
Bank Sta=4979.8,5028.6
XS Rating Curve= 0 ,0
Exp/Cntr=0.3,0.1

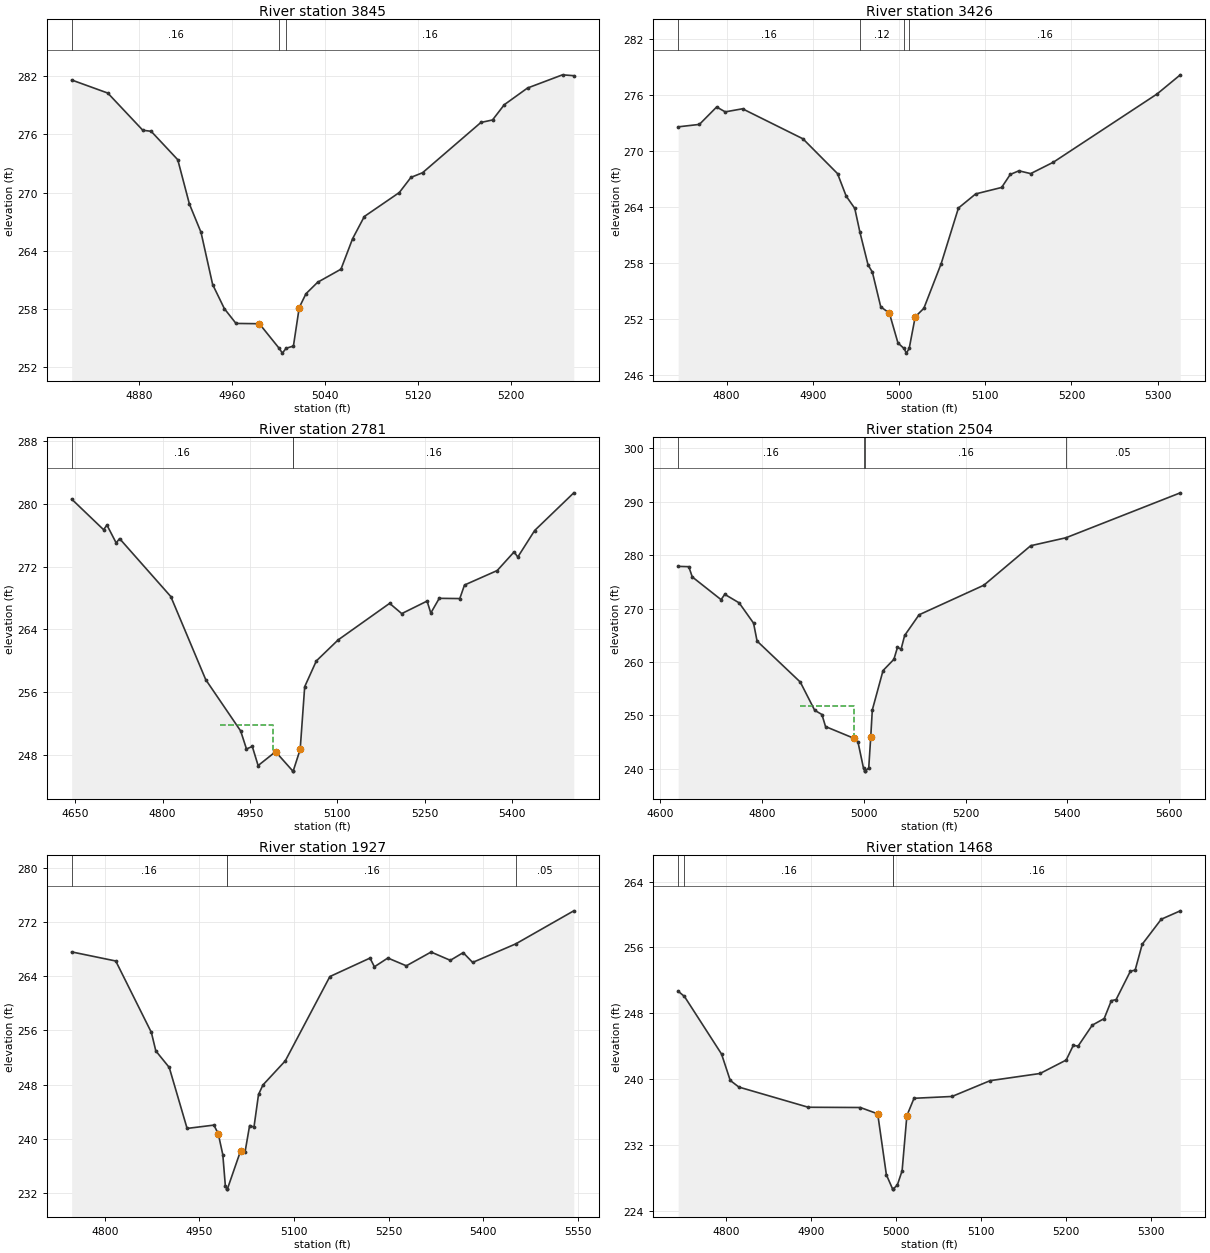
Type RM Length L Ch R = 1 ,3845    ,419,419,419
BEGIN DESCRIPTION:
UNT055 IN BECR 8.0
END DESCRIPTION:
XS GIS Cut Line= 2
      3794078.93     10487539.23      3794113.66     10487969.83
#Sta/Elev= 30
  4822.3   281.6  4853.4  280.25  4883.5  276.42  4890.7  276.31  4913.6  273.38
  4923.6  268.82  4933.6   265.9  4943.6  260.52  4953.7  258.03  4963.7  256.51
  4983.8  256.48  5000.8  253.95  5003.6  253.45  5006.8  253.95  5013.1  254.18
  5018.1  258.15  5023.9  259.57  5033.9  260.75    5054   262.1    5064  265.24
  5074.1  267.53  5104.2     270  5114.2  271.56  5124.2  272.04  5174.4  277.22
  5184.4  277.48  5194.5  279.05  5214.5  280.77  5244.6  282.13  5254.3  282.04
#Mann= 3 ,-1 , 0
  4822.3     .16       0  5000.8     .07       0  5006.8     .16       0
Bank Sta=4983.8,5018.1
XS Rating Curve= 0 ,0
Exp/Cntr=0.3,0.1

Type RM Length L Ch R = 1 ,3426    ,645,645,645
BEGIN DESCRIPTION:
UNT055 IN BECR 7.0
END DESCRIPTION:
XS GIS Cut Line= 2
      3793782.81     10487655.67      3793813.96     10488237.14
#Sta/Elev= 30
  4743.9  272.56  4768.5  272.82  4788.5  274.68  4798.5  274.16  4818.5  274.49
  4888.6  271.28  4928.7  267.56  4938.7  265.16  4948.7  263.84  4954.7  261.28
  4964.1   257.8  4969.1  257.03  4978.8  253.32  4988.8  252.65  4998.8  249.45
  5005.8  248.87  5008.5  248.37  5011.8  248.87  5018.8  252.25  5028.8  253.16
  5048.9  257.94  5068.9  263.88  5088.9  265.39    5119  266.08    5129  267.47
    5139  267.86  5152.7  267.56    5179  268.78  5299.2  276.07  5326.2  278.12
#Mann= 4 ,-1 , 0
  4743.9     .16       0  4954.7     .12       0  5005.8     .07       0
  5011.8     .16       0
Bank Sta=4988.8,5018.8
XS Rating Curve= 0 ,0
Exp/Cntr=0.3,0.1

Type RM Length L Ch R = 1 ,2781    ,277,277,277
BEGIN DESCRIPTION:
UNT055 IN BECR 6.0
END DESCRIPTION:
XS GIS Cut Line= 4
      3793362.67     10487659.17      3793289.76     10487787.64
      3793289.76     10488100.14      3793608.23     10488345.91
#Sta/Elev= 30
  4643.9  280.61  4698.8   276.7  4704.5   277.3  4720.4  275.01  4726.2  275.57
  4814.2  268.17  4874.2  257.56  4934.2  251.01  4944.2  248.71  4954.2  249.03
  4964.2  246.59  4994.2  248.36  5023.9  245.88  5024.4  245.88 5036.44  248.65
  5044.2  256.66  5064.2  259.95  5101.6  262.63  5190.1   267.3  5210.9  265.99
  5254.4  267.59  5260.8  266.06  5275.3  267.94  5310.6  267.91  5318.7  269.64
  5374.9  271.49  5403.9  273.87  5410.2  273.21  5439.2   276.6  5506.4  281.41
#Mann= 3 ,-1 , 0
  4643.9     .16       0  5023.9     .07       0  5024.4     .16       0
#XS Ineff= 1 ,-1
 4898.82 4989.25   251.8
Permanent Ineff=
       F
Bank Sta=4994.2,5036.44
XS Rating Curve= 0 ,0
Exp/Cntr=0.3,0.1

Type RM Length L Ch R = 1 ,2504    ,577,577,577
BEGIN DESCRIPTION:
UNT055 IN BECR 5.0
END DESCRIPTION:
XS GIS Cut Line= 3
      3793310.56     10487641.83      3792814.06     10488152.22
      3792689.95     10488397.01
#Sta/Elev= 30
  4635.3  277.91  4656.1  277.85    4663  275.93  4719.6  271.67  4726.8  272.67
  4755.1  271.07  4783.4  267.27  4790.3  263.91  4875.2  256.23  4903.5  250.94
  4917.7  250.15  4924.8  247.89  4981.4  245.66  4988.4  245.06  4999.5  240.04
  5002.3  239.54  5002.8  239.54  5009.7  240.16 5013.63  245.98  5016.7     251
  5037.8  258.39  5059.1  260.49  5066.1  262.72  5073.3  262.41  5080.2  264.96
  5108.5  268.83  5235.9  274.38  5327.9  281.78  5397.1  283.27  5621.8  291.69
#Mann= 4 ,-1 , 0
  4635.3     .16       0  4999.5     .07       0  5002.8     .16       0
  5397.1     .05       0
#XS Ineff= 1 ,-1
 4873.66 4979.82  251.83
Permanent Ineff=
       F
Bank Sta=4981.4,5013.63
XS Rating Curve= 0 ,0
Exp/Cntr=0.3,0.1

Type RM Length L Ch R = 1 ,1927    ,459,459,459
BEGIN DESCRIPTION:
UNT055 IN BECR 4.0
END DESCRIPTION:
XS GIS Cut Line= 3
      3792914.79     10487346.63      3792557.12     10487714.72
      3792505.03     10487992.53
#Sta/Elev= 30
  4747.6  267.57  4817.5  266.23    4874   255.7    4881  252.99  4902.3  250.55
  4930.6  241.57  4973.1  242.06    4980  240.78  4987.2   237.7  4991.2  233.13
  4993.9  232.63  4994.4  232.63  5015.5   238.3  5022.5  238.13  5029.7     242
  5036.6  241.76  5043.8  246.57  5050.8  247.97  5086.2  251.52  5156.9  263.94
  5220.5  266.66  5227.5  265.38  5248.8  266.67  5278.1  265.52  5317.3  267.55
  5347.8  266.33  5368.2  267.46  5383.2  266.02  5451.5  268.75  5543.5  273.62
#Mann= 4 ,-1 , 0
  4747.6     .16       0  4993.9     .07       0  4994.4     .16       0
  5451.5     .05       0
Bank Sta=4980,5015.5
XS Rating Curve= 0 ,0
Exp/Cntr=0.3,0.1

Type RM Length L Ch R = 1 ,1468    ,480,480,480
BEGIN DESCRIPTION:
UNT055 IN BECR 3.0
END DESCRIPTION:
XS GIS Cut Line= 3
      3792749.61     10487210.19      3792499.61     10487160.19
      3792349.59     10487460.22
#Sta/Elev= 30
    4744  250.69  4751.4  250.05    4795  243.06  4805.2  239.86  4815.4  239.05
    4897   236.6  4958.2  236.57  4978.6   235.8  4988.8   228.4  4996.2  226.66
  4996.7  226.66  5001.7  227.16  5007.3  228.89  5012.9  235.58  5021.3  237.69
    5066  237.91  5110.8  239.83  5169.5   240.7  5200.2  242.33  5208.6  244.12
  5214.2  244.02  5230.9  246.57  5244.9  247.37  5253.3  249.54  5258.9  249.67
  5275.7  253.12  5281.3  253.25  5289.6  256.39    5312  259.43  5334.4  260.45
#Mann= 4 ,-1 , 0
    4744     .16       0  4751.4     .16       0  4996.2     .07       0
  4996.7     .16       0
Bank Sta=4978.6,5012.9
XS Rating Curve= 0 ,0
Exp/Cntr=0.3,0.1

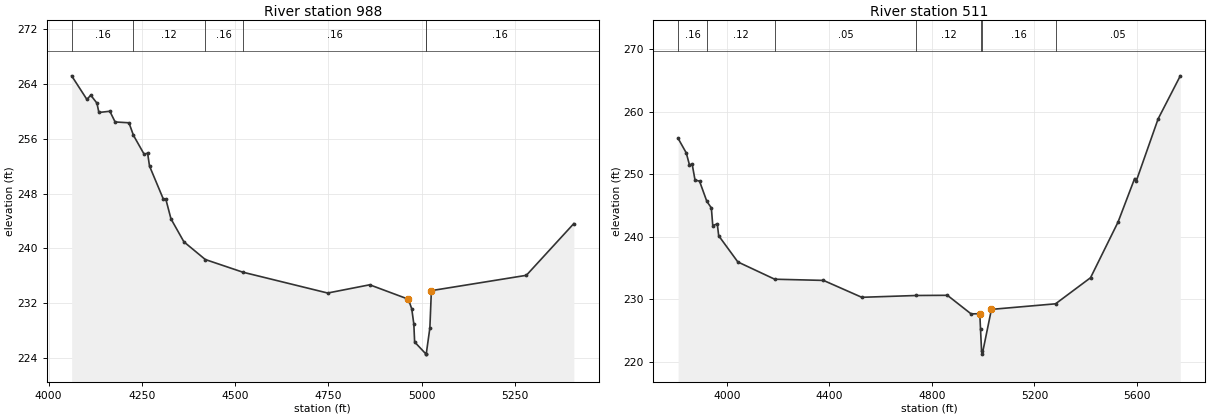
Type RM Length L Ch R = 1 ,988     ,477,477,477
BEGIN DESCRIPTION:
UNT055 IN BECR 2.0
END DESCRIPTION:
XS GIS Cut Line= 3
      3793199.58     10487060.18      3792299.61     10486860.19
       3791999.6      10487160.2
#Sta/Elev= 30
    4062  265.15  4102.9  261.71  4113.2  262.33  4129.8  261.17    4135  259.81
  4164.4  259.99  4178.5  258.43  4215.6  258.31  4227.6  256.49  4256.6   253.7
  4265.6   253.9  4270.7  252.01  4307.8  247.19  4314.2  247.23  4328.3  244.31
  4362.9  240.97  4420.3  238.39  4520.7  236.55  4748.3  233.51    4861  234.71
  4964.7  232.61  4973.7   231.2 4979.29  228.98  4981.4  226.38    5012  224.61
  5012.5  224.61 5022.28  228.43  5026.3  233.86  5280.9  236.09  5408.2  243.63
#Mann= 6 ,-1 , 0
    4062     .16       0  4227.6     .12       0  4420.3     .16       0
  4520.7     .16       0    5012     .07       0  5012.5     .16       0
Bank Sta=4964.7,5026.3
XS Rating Curve= 0 ,0
Exp/Cntr=0.3,0.1

Type RM Length L Ch R = 1 ,511     ,0,0,0
BEGIN DESCRIPTION:
UNT055 IN BECR 1.0
END DESCRIPTION:
XS GIS Cut Line= 3
       3793199.6     10486960.18      3792099.61     10486460.19
      3791499.61     10486910.19
#Sta/Elev= 30
  3810.4  255.73  3842.2  253.41  3854.3  251.55  3865.3  251.59  3876.3  249.08
  3893.9   248.9  3922.4  245.67    3940  244.62  3945.5  241.81  3963.1  242.07
  3968.6  240.18  4043.3  235.99  4187.1  233.23  4377.2  233.04  4526.6  230.34
  4739.7  230.63  4860.5  230.66  4952.8  227.69  4986.8  227.72  4989.6   225.3
  4993.7  221.76  4996.5  221.26  5032.2  228.41  5282.2   229.3  5418.7  233.47
    5526  242.37  5590.6  249.32  5596.8   248.9  5682.2  258.85  5768.7  265.73
#Mann= 7 ,-1 , 0
  3810.4     .16       0  3922.4     .12       0  4187.1     .05       0
  4739.7     .12       0  4989.6     .05       0  4993.7     .16       0
  5282.2     .05       0
Bank Sta=4986.8,5032.2
XS Rating Curve= 0 ,0
Exp/Cntr=0.3,0.1

Chan Stop Cuts=-1
Use User Specified Reach Order=0
Composite Channel Slope=5