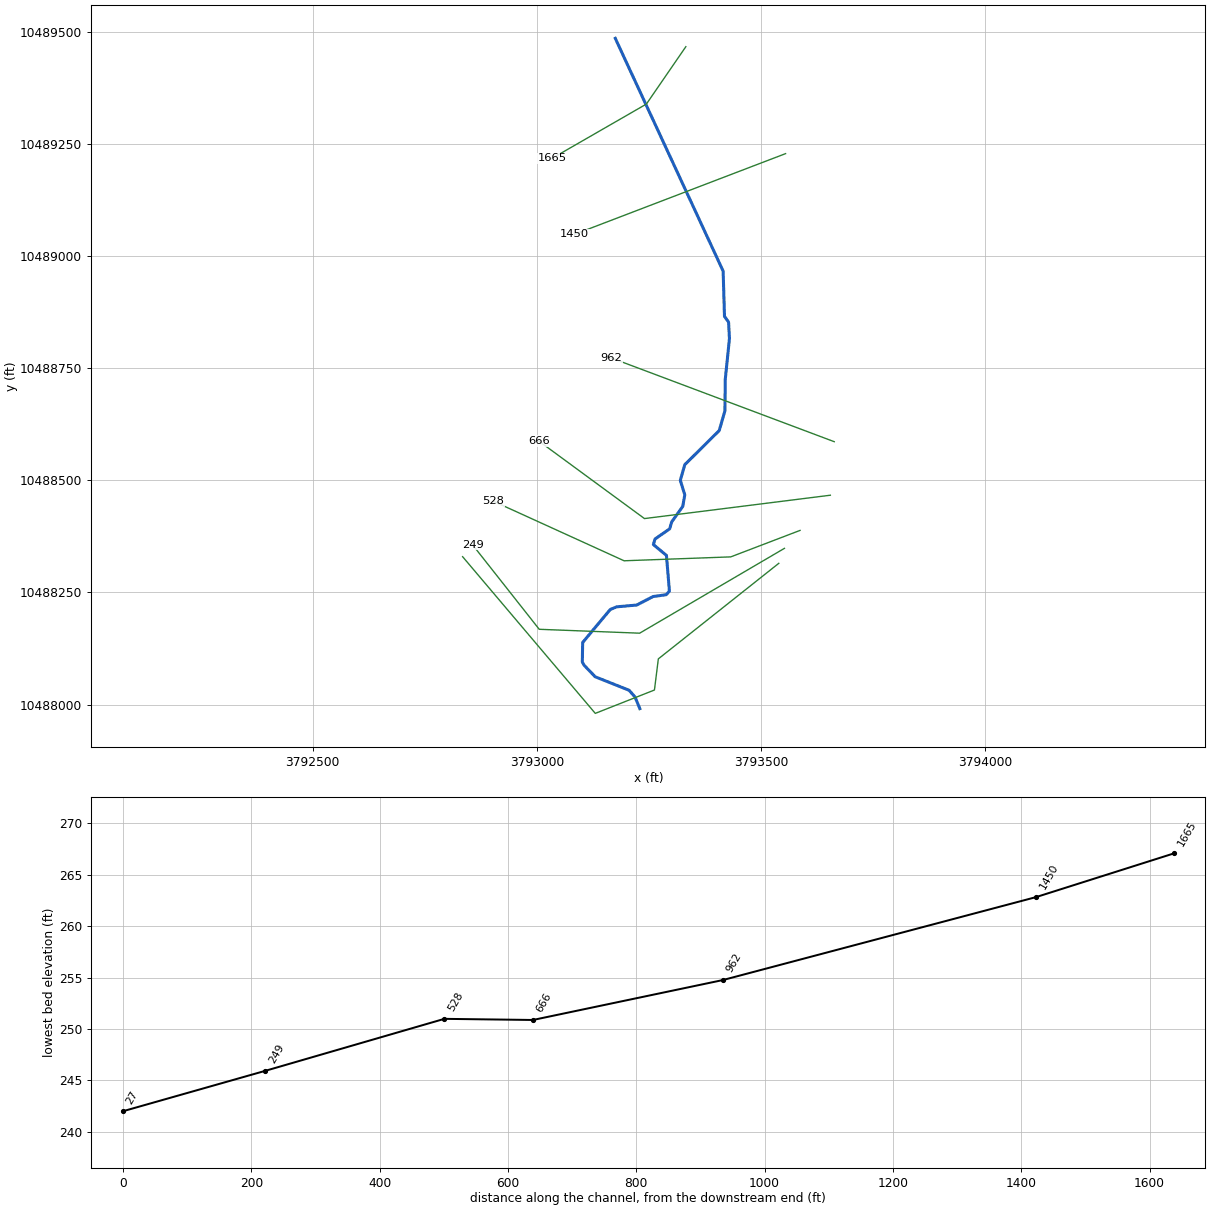
--- UNT056 IN BECR.prj (project) ---

Proj Title=UNT056 IN BECR Base Level Engineering
Current Plan=p01
Default Exp/Contr=0.3,0.1
English Units
Geom File=g01
Flow File=f01
Plan File=p01
Y Axis Title=Elevation
X Axis Title(PF)=Main Channel Distance
X Axis Title(XS)=Station
BEGIN DESCRIPTION:
UNT056 IN BECR
END DESCRIPTION:
DSS Export Rating Curves= 0
DSS Export Rating Curve Sorted= 0
DSS Export Volume Flow Curves= 0
DXF OffsetX= 0
DXF OffsetY= 0
DXF ScaleX= 1
DXF ScaleY= 10

--- UNT056 IN BECR.p01 (plan) ---

Plan Title=Multiple Run
Short Identifier=Multiple
Geom File=g01
Flow File=f01
Subcritical Flow
K Sum by GR= 0
Std Step Tol= 0.01
Critical Tol= 0.01
Num of Std Step Trials= 20
Max Error Tol= 0.3
Flow Tol Ratio= 0.001
Split Flow NTrial= 30
Split Flow Tol= 0.02
Split Flow Ratio= 0.02
Log Output Level= 0
Friction Slope Method= 1
Unsteady Friction Slope Method= 2
Unsteady Bridges Friction Slope Method= 1
Parabolic Critical Depth
Global Vel Dist=  1 , 1 , 1
Global Log Level= 0
CheckData=True
Encroach Param= -1, 0, 0, 0
BEGIN DESCRIPTION:
Multiple Run
END DESCRIPTION:

--- UNT056 IN BECR.f01 (steady flow) ---

Flow Title=Multiple
Program Version=4.10
Number of Profiles= 7
Profile Names=10-year,25-year,50-year,1pct_min,100-year,1pct_plu,500-year
River Rch & RM=UNT056 IN BECR,Reach-1         ,1665
     128     156     177     149     201     272     260
River Rch & RM=UNT056 IN BECR,Reach-1         ,27
     128     156     177     149     201     272     260
Boundary for River Rch & Prof#=UNT056 IN BECR,Reach-1         , 1
Up Type= 0
Dn Type= 3
Dn Slope=0.005
Boundary for River Rch & Prof#=UNT056 IN BECR,Reach-1         , 2
Up Type= 0
Dn Type= 3
Dn Slope=0.005
Boundary for River Rch & Prof#=UNT056 IN BECR,Reach-1         , 3
Up Type= 0
Dn Type= 3
Dn Slope=0.005
Boundary for River Rch & Prof#=UNT056 IN BECR,Reach-1         , 4
Up Type= 0
Dn Type= 3
Dn Slope=0.005
Boundary for River Rch & Prof#=UNT056 IN BECR,Reach-1         , 5
Up Type= 0
Dn Type= 3
Dn Slope=0.005
Boundary for River Rch & Prof#=UNT056 IN BECR,Reach-1         , 6
Up Type= 0
Dn Type= 3
Dn Slope=0.005
Boundary for River Rch & Prof#=UNT056 IN BECR,Reach-1         , 7
Up Type= 0
Dn Type= 3
Dn Slope=0.005
DSS Import GetInterval= 0
DSS Import GetPeak= 0
DSS Import FillOption= 0

--- UNT056 IN BECR.g01 (geometry) ---

Geom Title=Existing Conditions
Program Version=4.10

River Reach=UNT056 IN BECR  ,Reach-1
Reach XY= 30
      3793174.75      10489485.7      3793415.27     10488966.68
      3793418.29     10488865.76       3793427.4     10488852.74
      3793429.35     10488816.28        3793420.       10488725.
      3793419.25       10488655.       3793406.5       10488611.
      3793329.75       10488535.      3793319.75       10488500.
      3793329.75     10488467.75      3793325.25       10488442.
      3793300.46     10488407.26      3793296.13     10488391.99
      3793263.32     10488369.16      3793259.67     10488356.92
      3793288.84     10488332.71       3793295.5       10488253.
      3793288.25       10488245.      3793259.25       10488241.
       3793222.5       10488222.      3793177.75       10488218.
       3793163.5       10488212.      3793102.03     10488138.52
      3793101.25       10488095.       3793105.5      10488087.5
        3793130.       10488062.       3793205.5       10488032.
      3793218.75       10488017.       3793229.5       10487991.

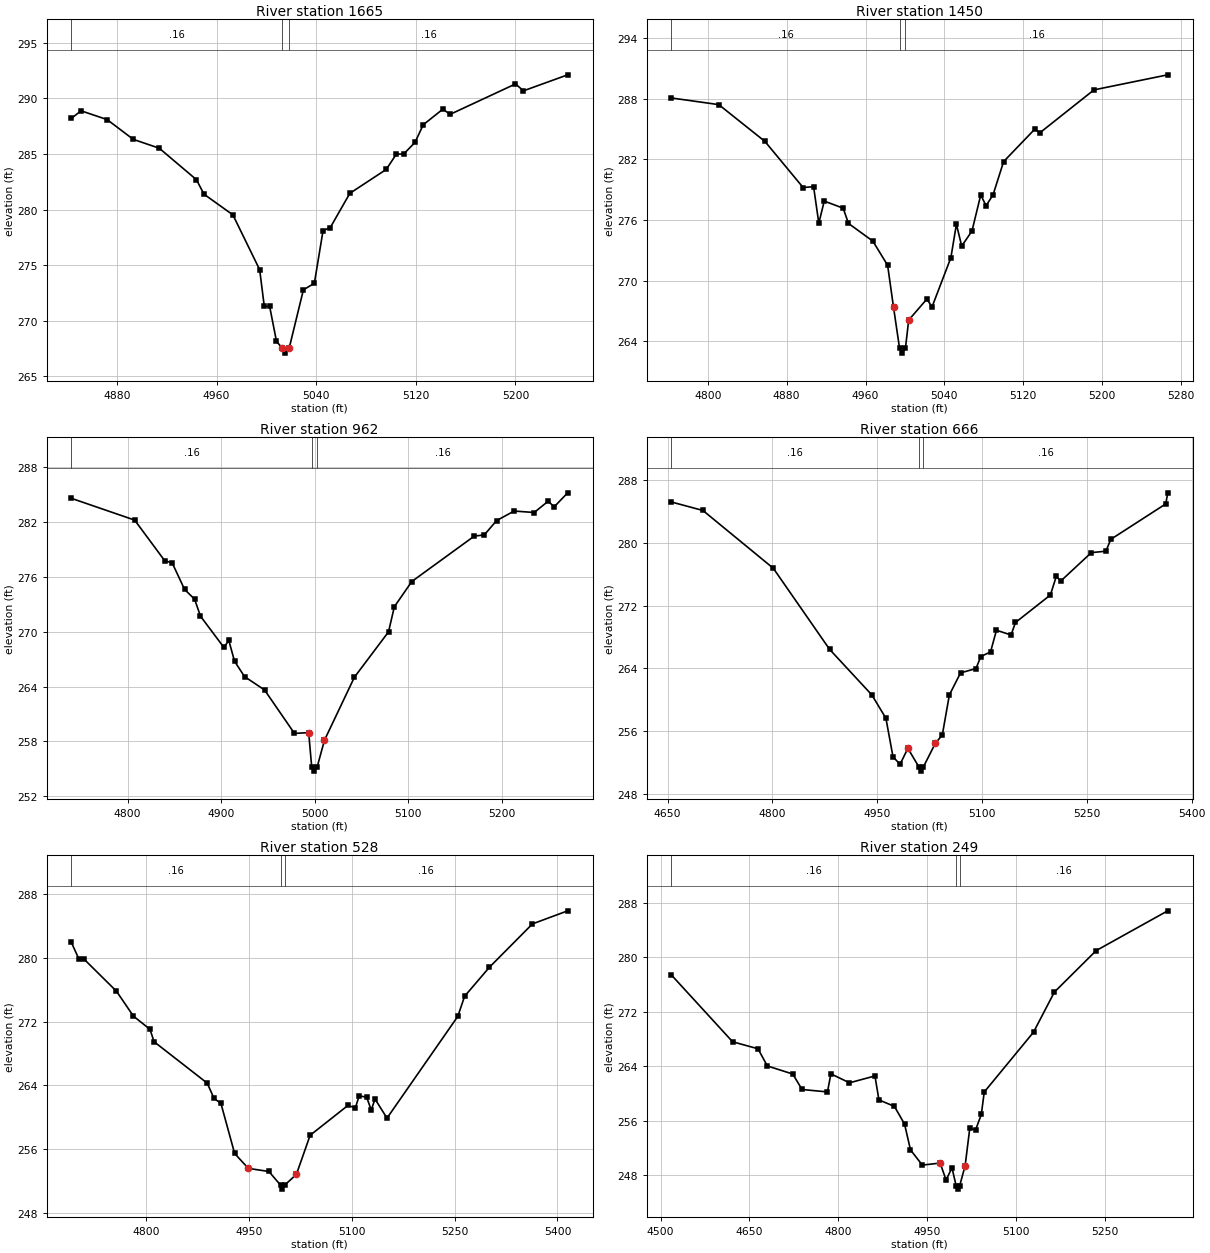
Type RM Length L Ch R = 1 ,1665    ,215,215,215
BEGIN DESCRIPTION:
UNT056 IN BECR 4.0
END DESCRIPTION:
XS GIS Cut Line= 3
       3793332.1     10489467.08      3793244.11     10489339.11
      3793033.34     10489217.77
#Sta/Elev= 30
  4843.4  288.21  4851.2  288.89  4872.1   288.1  4893.1  286.32    4914  285.52
  4943.8  282.69  4949.9  281.38  4973.1  279.52  4994.6  274.58  4998.3  271.28
  5002.6  271.28  5008.1  268.13  5012.4  267.57  5015.2  267.07  5018.4  267.57
  5029.7  272.77  5038.5  273.36  5045.5  278.11  5051.2  278.36    5067  281.46
  5096.2  283.61  5104.4     285  5110.1  284.99  5119.3  286.04  5125.9  287.63
  5141.7  289.04  5147.5  288.57    5200  291.31  5206.4  290.69  5241.9  292.13
#Mann= 3 ,-1 , 0
  4843.4     .16       0  5012.4     .07       0  5018.4     .16       0
Bank Sta=5012.4,5018.4
XS Rating Curve= 0 ,0
Exp/Cntr=0.3,0.1

Type RM Length L Ch R = 1 ,1450    ,488,488,488
BEGIN DESCRIPTION:
UNT056 IN BECR 3.0
END DESCRIPTION:
XS GIS Cut Line= 2
      3793554.49      10489228.6      3793084.12     10489048.69
#Sta/Elev= 30
    4763  288.08  4811.1  287.42  4857.9  283.78  4896.7  279.21  4907.3   279.3
  4912.6  275.68  4918.1  277.87  4937.3  277.17  4942.7  275.66  4967.4  273.91
  4982.4  271.52 4988.41  267.36  4994.5  263.32  4997.2  262.82  5000.5  263.32
  5003.8  266.09  5022.2  268.17  5027.5   267.4  5046.6  272.27  5052.2  275.57
  5057.6  273.42    5068  274.91  5076.9  278.48  5082.3  277.41  5089.4  278.49
  5100.1  281.78  5131.7  284.99    5137  284.64  5191.8  288.88  5266.6  290.37
#Mann= 3 ,-1 , 0
    4763     .16       0  4994.5     .07       0  5000.5     .16       0
Bank Sta=4988.41,5003.8
XS Rating Curve= 0 ,0
Exp/Cntr=0.3,0.1

Type RM Length L Ch R = 1 ,962     ,296,296,296
BEGIN DESCRIPTION:
UNT056 IN BECR 2.0
END DESCRIPTION:
XS GIS Cut Line= 2
      3793662.99     10488586.26      3793166.07     10488772.88
#Sta/Elev= 30
  4739.9  284.57  4807.6  282.19  4839.6  277.77  4847.8   277.5    4861  274.61
  4871.7  273.55    4878  271.69    4903  268.28  4908.3  269.04  4914.4  266.77
  4925.1  265.09  4946.5  263.63  4978.5  258.88  4993.7  258.97  4996.9  255.26
  4999.6  254.76  5002.9  255.26  5010.6  258.14  5042.6  265.02  5079.1  269.98
  5085.3  272.72    5104  275.48  5170.8  280.44  5181.5  280.57  5194.7  282.14
  5213.5  283.18  5234.9  283.02  5249.9  284.26  5256.2  283.63  5270.7  285.17
#Mann= 3 ,-1 , 0
  4739.9     .16       0  4996.9     .07       0  5002.9     .16       0
Bank Sta=4993.7,5010.6
XS Rating Curve= 0 ,0
Exp/Cntr=0.3,0.1

Type RM Length L Ch R = 1 ,666     ,138,138,138
BEGIN DESCRIPTION:
Mapping XS 4df69ab9
END DESCRIPTION:
XS GIS Cut Line= 3
      3793654.36     10488466.89      3793239.84     10488414.81
      3793003.94     10488587.95
#Sta/Elev= 30
  4655.3  285.23  4700.4  284.15  4801.2  276.77  4881.8  266.42  4942.3   260.6
  4962.4  257.62  4972.5  252.71  4982.6  251.75  4993.8  253.79  5009.8  251.38
  5012.6  250.88  5015.8  251.38    5033  254.41  5043.1   255.5  5053.2  260.61
  5069.2  263.42  5091.3  263.97  5098.2  265.51  5112.1  266.09  5120.6  268.86
  5141.5  268.26  5147.8  269.85  5197.8  273.36  5206.3  275.76  5212.5  275.13
  5256.4  278.77  5277.3  278.95  5284.2  280.46    5363  284.99  5365.7   286.4
#Mann= 3 ,-1 , 0
  4655.3     .16       0  5009.8     .07       0  5015.8     .16       0
Bank Sta=4993.8,5033
XS Rating Curve= 0 ,0
Exp/Cntr=0.3,0.1

Type RM Length L Ch R = 1 ,528     ,279,279,279
BEGIN DESCRIPTION:
Mapping XS 9e44ee7d
END DESCRIPTION:
XS GIS Cut Line= 4
      3793586.76     10488388.41      3793432.24     10488329.38
      3793194.39      10488320.7      3792902.84     10488453.53
#Sta/Elev= 30
  4691.1  281.92  4702.1  279.84  4709.5  279.83  4756.9   275.8  4781.6  272.68
  4805.8  271.02  4811.7  269.47  4889.2  264.28  4899.2  262.36  4909.2  261.74
  4929.2  255.46  4949.2  253.59  4979.2   253.2  4996.2  251.49    4999  250.99
  5002.2  251.49  5019.3  252.84  5039.3  257.74  5094.4  261.48  5105.3  261.18
  5110.8  262.69  5121.8  262.51  5128.4   260.9  5133.9  262.29  5151.4  259.89
  5254.6  272.64  5264.6  275.17  5300.7   278.8  5363.5  284.24  5414.9  285.88
#Mann= 3 ,-1 , 0
  4691.1     .16       0  4996.2     .07       0  5002.2     .16       0
Bank Sta=4949.2,5019.3
XS Rating Curve= 0 ,0
Exp/Cntr=0.3,0.1

Type RM Length L Ch R = 1 ,249     ,222,222,222
BEGIN DESCRIPTION:
Mapping XS b2dd6605
END DESCRIPTION:
XS GIS Cut Line= 4
      3793552.05     10488348.48      3793229.11     10488159.24
      3793005.16     10488167.92      3792856.64     10488356.16
#Sta/Elev= 30
  4518.1  277.41  4621.5  267.59  4664.4  266.56  4680.1  264.04  4723.1  262.85
  4738.8  260.58  4781.7  260.22  4787.5  262.88  4818.9  261.56  4861.9  262.57
  4868.6  259.05  4894.7   258.1  4911.9   255.5  4921.9  251.71  4941.9  249.47
    4972  249.77    4982  247.29    4992  249.07    4999  246.44  5001.7  245.94
    5005  246.44  5014.2  249.38    5022  254.85    5032  254.67  5041.5  256.91
  5046.5  260.21  5129.7     269  5164.9  274.89  5235.4  280.98  5356.3  286.83
#Mann= 3 ,-1 , 0
  4518.1     .16       0    4999     .07       0    5005     .16       0
Bank Sta=4972,5014.2
XS Rating Curve= 0 ,0
Exp/Cntr=0.3,0.1

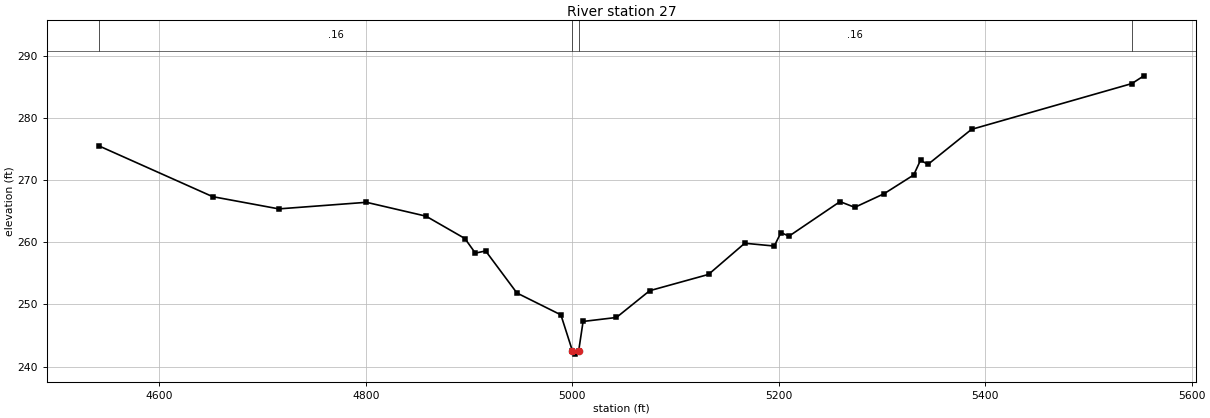
Type RM Length L Ch R = 1 ,27      ,0,0,0
BEGIN DESCRIPTION:
UNT056 IN BECR 1.0
END DESCRIPTION:
XS GIS Cut Line= 5
      3793539.36     10488315.01      3793270.78     10488101.95
       3793262.1      10488032.5      3793130.16     10487980.42
      3792834.31     10488329.84
#Sta/Elev= 30
  4541.2  275.54  4651.5  267.36  4715.6  265.39  4800.5  266.45  4858.2  264.22
  4895.9  260.62    4906  258.27    4916  258.62  4946.3  251.85  4988.9  248.33
  5000.1  242.51  5002.9  242.01  5006.1  242.51  5010.4  247.27  5042.7  247.91
  5074.9  252.22  5131.9  254.84    5167  259.86  5195.6  259.41  5202.1  261.57
  5209.9     261  5259.3  266.56  5273.6  265.64  5302.1  267.84  5330.7  270.85
  5337.3  273.23  5344.5  272.55  5386.7  278.19    5542  285.56  5553.7  286.81
#Mann= 4 ,-1 , 0
  4541.2     .16       0  5000.1     .07       0  5006.1     .16       0
    5542     .05       0
Bank Sta=5000.1,5006.1
XS Rating Curve= 0 ,0
Exp/Cntr=0.3,0.1

Chan Stop Cuts=-1
Use User Specified Reach Order=0
Composite Channel Slope=5