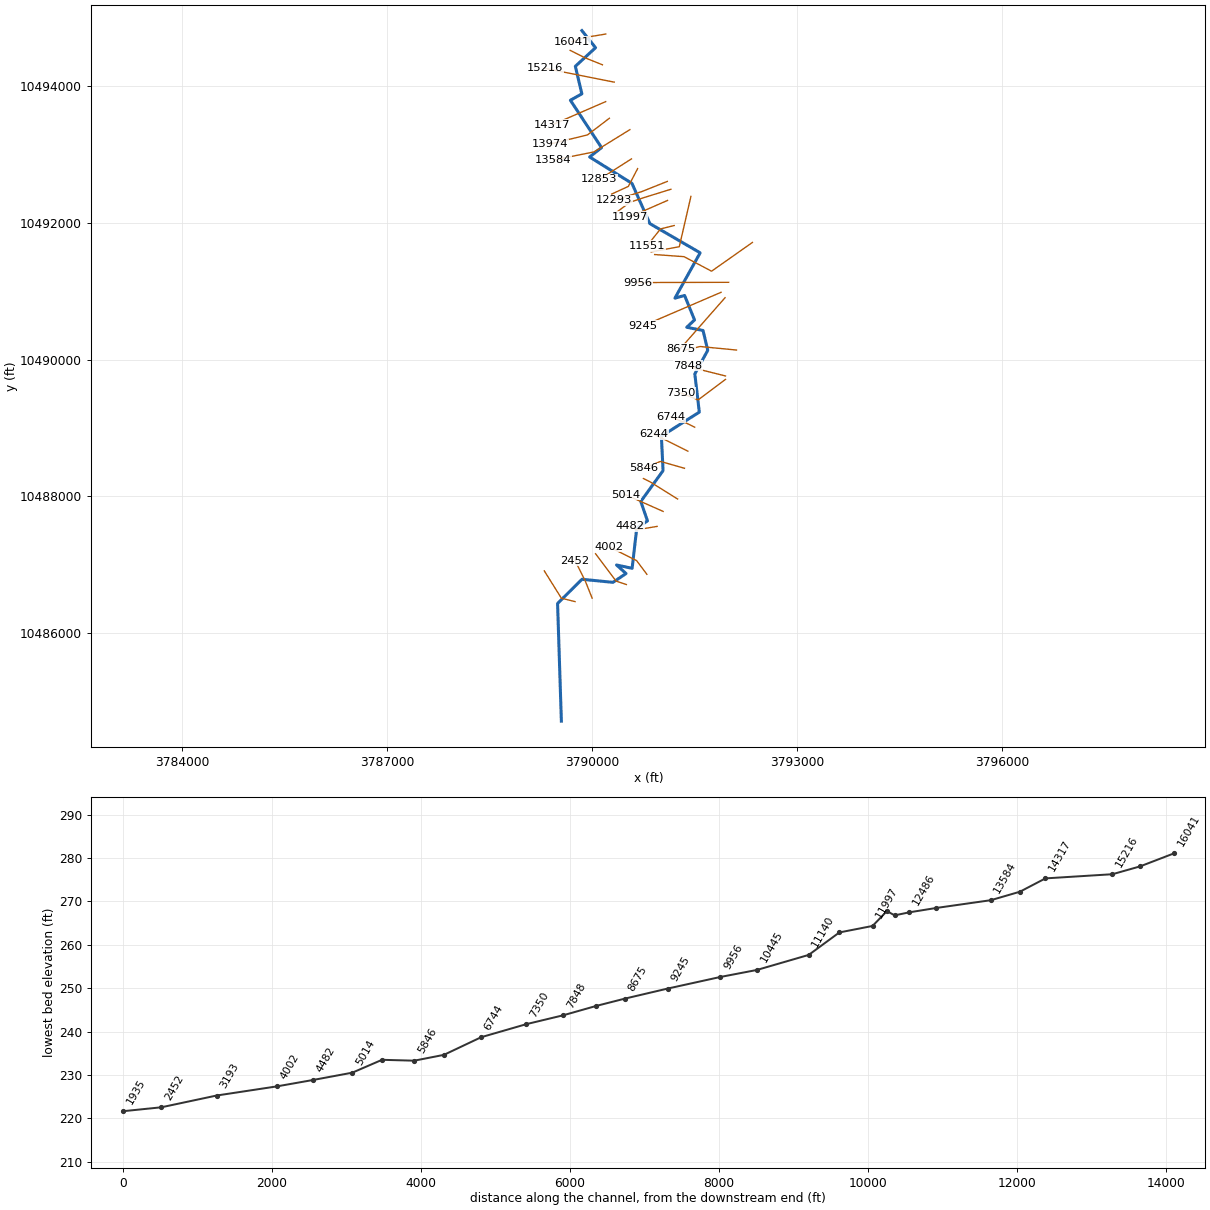
--- UNT057 IN BECR.prj (project) ---

Proj Title=UNT057 IN BECR Base Level Engineering
Current Plan=p01
Default Exp/Contr=0.3,0.1
English Units
Geom File=g01
Flow File=f01
Plan File=p01
Y Axis Title=Elevation
X Axis Title(PF)=Main Channel Distance
X Axis Title(XS)=Station
BEGIN DESCRIPTION:
UNT057 IN BECR
END DESCRIPTION:
DSS Export Rating Curves= 0
DSS Export Rating Curve Sorted= 0
DSS Export Volume Flow Curves= 0
DXF OffsetX= 0
DXF OffsetY= 0
DXF ScaleX= 1
DXF ScaleY= 10

--- UNT057 IN BECR.p01 (plan) ---

Plan Title=Multiple Run
Short Identifier=Multiple
Geom File=g01
Flow File=f01
Subcritical Flow
K Sum by GR= 0
Std Step Tol= 0.01
Critical Tol= 0.01
Num of Std Step Trials= 20
Max Error Tol= 0.3
Flow Tol Ratio= 0.001
Split Flow NTrial= 30
Split Flow Tol= 0.02
Split Flow Ratio= 0.02
Log Output Level= 0
Friction Slope Method= 1
Unsteady Friction Slope Method= 2
Unsteady Bridges Friction Slope Method= 1
Parabolic Critical Depth
Global Vel Dist=  1 , 1 , 1
Global Log Level= 0
CheckData=True
Encroach Param= -1, 0, 0, 0
BEGIN DESCRIPTION:
Multiple Run
END DESCRIPTION:

--- UNT057 IN BECR.f01 (steady flow) ---

Flow Title=Multiple
Program Version=4.10
Number of Profiles= 7
Profile Names=10-year,25-year,50-year,1pct_min,100-year,1pct_plu,500-year
River Rch & RM=UNT057 IN BECR,Reach-1         ,16041
     586     790     958     854    1155    1562    1684
River Rch & RM=UNT057 IN BECR,Reach-1         ,12190
     803    1097    1341    1204    1629    2203    2410
River Rch & RM=UNT057 IN BECR,Reach-1         ,313
     803    1097    1341    1204    1629    2203    2410
Boundary for River Rch & Prof#=UNT057 IN BECR,Reach-1         , 1
Up Type= 0
Dn Type= 3
Dn Slope=0.0035
Boundary for River Rch & Prof#=UNT057 IN BECR,Reach-1         , 2
Up Type= 0
Dn Type= 3
Dn Slope=0.0035
Boundary for River Rch & Prof#=UNT057 IN BECR,Reach-1         , 3
Up Type= 0
Dn Type= 3
Dn Slope=0.0035
Boundary for River Rch & Prof#=UNT057 IN BECR,Reach-1         , 4
Up Type= 0
Dn Type= 3
Dn Slope=0.0035
Boundary for River Rch & Prof#=UNT057 IN BECR,Reach-1         , 5
Up Type= 0
Dn Type= 3
Dn Slope=0.0035
Boundary for River Rch & Prof#=UNT057 IN BECR,Reach-1         , 6
Up Type= 0
Dn Type= 3
Dn Slope=0.0035
Boundary for River Rch & Prof#=UNT057 IN BECR,Reach-1         , 7
Up Type= 0
Dn Type= 3
Dn Slope=0.0035
DSS Import GetInterval= 0
DSS Import GetPeak= 0
DSS Import FillOption= 0

--- UNT057 IN BECR.g01 (geometry) ---

Geom Title=Existing Conditions
Program Version=4.10

River Reach=UNT057 IN BECR  ,Reach-1
Reach XY= 30
      3789849.61     10494810.19      3790049.61     10494560.19
      3789753.75       10494288.      3789849.25       10493885.
      3789681.75       10493792.      3790136.75       10493099.
        3789963.       10492962.        3790582.       10492576.
       3790843.5       10491988.        3791579.       10491561.
        3791210.       10490898.       3791351.5       10490937.
        3791497.       10490579.      3791383.25       10490472.
      3791621.25       10490425.      3791690.25       10490135.
        3791501.       10489790.       3791566.5       10489231.
        3791012.       10488879.       3791036.5       10488376.
      3790711.25       10487925.      3790808.75       10487641.
      3790651.75       10487534.        3790584.       10486947.
      3790356.25       10486996.      3790495.25       10486871.
      3790303.75       10486742.      3789851.25       10486787.
        3789494.       10486433.       3789549.5       10484713.

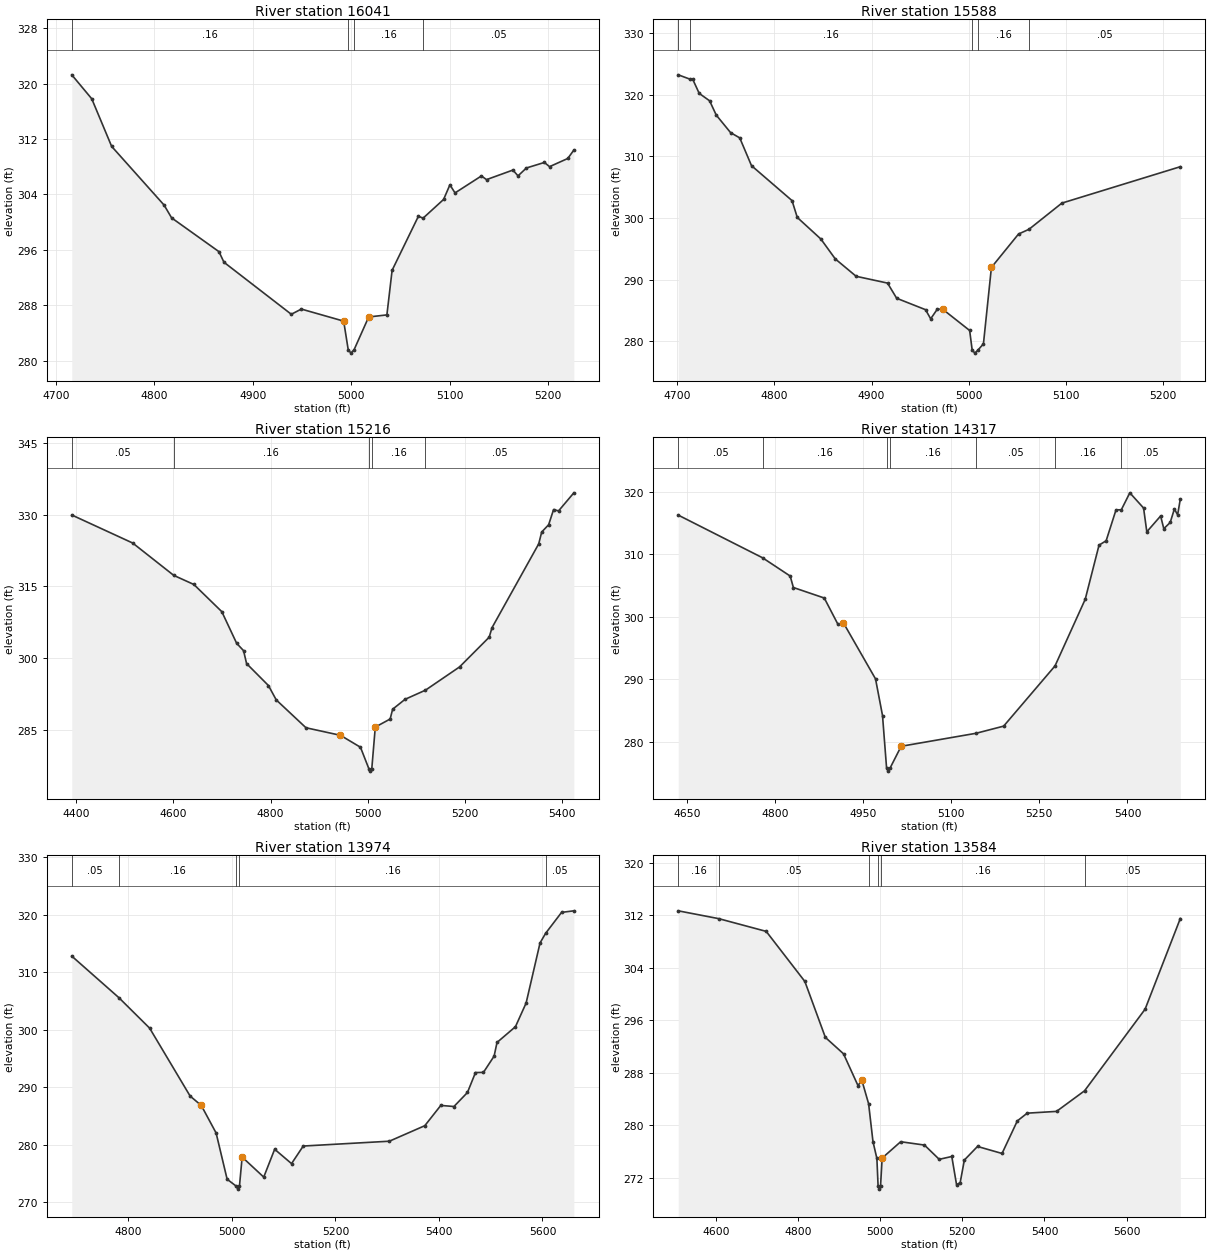
Type RM Length L Ch R = 1 ,16041   ,453,453,453
BEGIN DESCRIPTION:
UNT057 IN BECR 30.0
END DESCRIPTION:
XS GIS Cut Line= 3
      3790199.59     10494760.19      3789899.61     10494710.19
      3789703.76     10494646.72
#Sta/Elev= 30
    4716  321.27  4736.3  317.81  4756.5  310.94  4809.8  302.46  4817.4  300.62
  4865.5  295.74  4870.6  294.21    4939   286.7  4949.2  287.45  4992.2  285.71
  4996.8  281.59  4999.6  281.09  5002.8  281.59  5017.6  286.31  5036.1  286.61
  5041.4  293.05  5068.1  300.85  5072.9  300.58  5093.7  303.28  5100.1  305.39
  5105.3  304.22  5132.1  306.67  5137.3  306.14  5164.1  307.52  5169.3  306.68
  5177.8  307.82  5196.1  308.62  5201.3  308.01  5219.8  309.19    5226   310.4
#Mann= 4 ,-1 , 0
    4716     .16       0  4996.8     .07       0  5002.8     .16       0
  5072.9     .05       0
Bank Sta=4992.2,5017.6
XS Rating Curve= 0 ,0
Exp/Cntr=0.3,0.1

Type RM Length L Ch R = 1 ,15588   ,372,372,372
BEGIN DESCRIPTION:
UNT057 IN BECR 29.0
END DESCRIPTION:
XS GIS Cut Line= 3
      3790149.62     10494310.18      3789899.61     10494410.19
       3789678.6     10494521.44
#Sta/Elev= 30
  4701.1   323.2  4713.3  322.49  4715.9  322.51  4722.7  320.19  4733.4  318.99
  4740.2  316.68    4755  313.83  4764.4  312.98  4776.5  308.48  4818.2  302.82
  4823.6  300.09  4847.9  296.59  4862.7  293.37  4884.2  290.55  4916.5  289.45
  4925.9  286.99  4955.6  285.14  4960.9  283.66  4967.7  285.22  4973.2  285.22
    5001  281.77  5003.6   278.6  5006.4   278.1  5009.6   278.6  5015.2  279.61
  5023.4  291.99  5051.3   297.4  5062.1  298.17  5095.9  302.41  5217.8  308.31
#Mann= 5 ,-1 , 0
  4701.1     .05       0  4713.3     .16       0  5003.6     .07       0
  5009.6     .16       0  5062.1     .05       0
Bank Sta=4973.2,5023.4
XS Rating Curve= 0 ,0
Exp/Cntr=0.3,0.1

Type RM Length L Ch R = 1 ,15216   ,899,899,899
BEGIN DESCRIPTION:
UNT057 IN BECR 28.0
END DESCRIPTION:
XS GIS Cut Line= 2
      3790322.58     10494056.48      3789308.68     10494257.87
#Sta/Elev= 30
  4390.8  329.92  4516.2  324.05  4600.7  317.28  4642.2  315.37  4699.7  309.68
  4730.3  303.05  4744.5  301.51  4750.7  298.81  4795.7  294.21  4811.8   291.2
    4873  285.37    4944  283.79  4985.2  281.29  5002.5  276.79  5005.3  276.29
  5008.5  276.79  5015.7  285.51  5046.3   287.2  5051.4  289.25  5076.9  291.32
    5119  293.24  5189.1   298.1  5250.2  304.33    5256  306.32  5352.2  323.88
  5358.3  326.35  5372.6  327.88  5382.8  331.06    5393  330.77  5424.5  334.56
#Mann= 5 ,-1 , 0
  4390.8     .05       0  4600.7     .16       0  5002.5     .07       0
  5008.5     .16       0    5119     .05       0
Bank Sta=4944,5015.7
XS Rating Curve= 0 ,0
Exp/Cntr=0.3,0.1

Type RM Length L Ch R = 1 ,14317   ,343,343,343
BEGIN DESCRIPTION:
UNT057 IN BECR 27.0
END DESCRIPTION:
XS GIS Cut Line= 2
      3790197.57     10493771.74      3789413.78     10493431.87
#Sta/Elev= 30
  4635.6  316.24  4779.1  309.42  4826.1   306.5  4831.5  304.67  4884.1  302.99
  4907.4  298.78  4916.8     299  4971.3  290.07  4983.2  284.21  4990.1  275.83
  4992.8  275.33  4996.1  275.83  5014.9   279.3  5142.5  281.38  5189.3  282.52
  5276.7  292.14  5328.1  302.79  5351.6  311.44  5363.7  312.14  5380.5  317.08
  5389.5  317.09    5404   319.8  5427.4  317.37  5432.9  313.57  5456.4   316.1
  5461.8  314.07  5472.7  315.06  5479.8  317.22  5485.3  316.29  5489.9   318.8
#Mann= 7 ,-1 , 0
  4635.6     .05       0  4779.1     .16       0  4990.1     .07       0
  4996.1     .16       0  5142.5     .05       0  5276.7     .16       0
  5389.5     .05       0
Bank Sta=4916.8,5014.9
XS Rating Curve= 0 ,0
Exp/Cntr=0.3,0.1

Type RM Length L Ch R = 1 ,13974   ,390,390,390
BEGIN DESCRIPTION:
UNT057 IN BECR 26.0
END DESCRIPTION:
XS GIS Cut Line= 3
      3790251.51     10493528.38      3789932.07     10493285.33
      3789380.02     10493149.92
#Sta/Elev= 30
  4690.8  312.81  4781.6  305.59  4841.2  300.27  4919.4  288.45    4941  286.81
  4969.6  282.02  4990.9  273.97  5008.7  272.75  5011.5  272.25  5014.7  272.75
  5019.9  277.83  5061.6  274.34  5082.7  279.19  5115.3  276.69  5137.9  279.75
  5304.2  280.59  5372.7  283.29  5403.6  286.82    5429  286.63  5455.1  289.07
  5470.6  292.54    5486  292.57  5506.6   295.4  5512.2  297.78  5547.8  300.52
  5568.4  304.64  5595.3   315.1  5606.1  316.78  5636.9  320.42  5660.6  320.69
#Mann= 5 ,-1 , 0
  4690.8     .05       0  4781.6     .16       0  5008.7     .07       0
  5014.7     .16       0  5606.1     .05       0
Bank Sta=4941,5019.9
XS Rating Curve= 0 ,0
Exp/Cntr=0.3,0.1

Type RM Length L Ch R = 1 ,13584   ,731,731,731
BEGIN DESCRIPTION:
UNT057 IN BECR 25.0
END DESCRIPTION:
XS GIS Cut Line= 3
      3790551.73     10493362.01      3790023.99     10493035.64
      3789434.18     10492917.68
#Sta/Elev= 30
  4508.6  312.69  4607.1   311.5  4722.7  309.56  4816.8  301.93  4866.7  293.41
  4910.9  290.91  4946.1  286.07  4955.4   286.9  4971.9  283.32  4982.6  277.53
  4992.1  274.97    4995   270.8  4997.7   270.3    5001   270.8  5004.9  275.03
    5050  277.52  5107.9  277.01  5143.8  274.84  5174.4  275.27    5186  270.98
  5194.8  271.29    5205  274.73    5237   276.8  5296.7  275.73  5333.9  280.69
  5357.9  281.87  5429.3  282.14  5497.6  285.28  5644.9  297.71  5730.6  311.52
#Mann= 6 ,-1 , 0
  4508.6     .16       0  4607.1     .05       0  4971.9     .16       0
    4995     .07       0    5001     .16       0  5497.6     .05       0
Bank Sta=4955.4,5004.9
XS Rating Curve= 0 ,0
Exp/Cntr=0.3,0.1

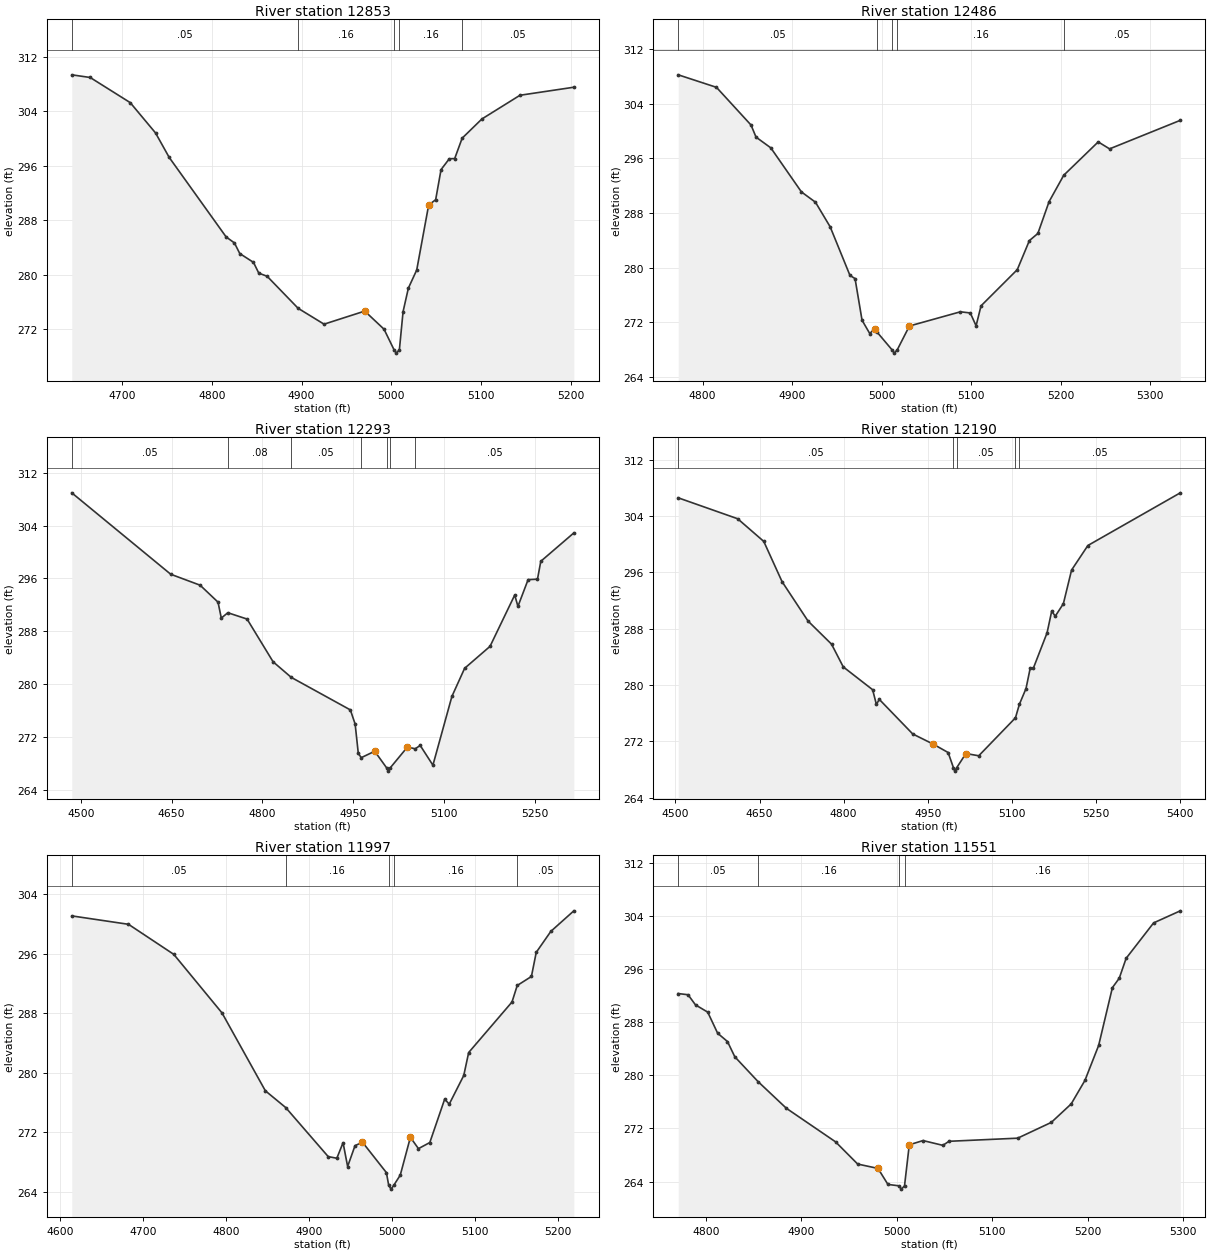
Type RM Length L Ch R = 1 ,12853   ,367,367,367
BEGIN DESCRIPTION:
UNT057 IN BECR 24.0
END DESCRIPTION:
XS GIS Cut Line= 2
      3790574.44     10492934.64      3790103.38      10492633.3
#Sta/Elev= 30
  4644.1  309.36  4664.6  308.97  4709.2  305.28  4737.4  300.83  4752.6  297.24
    4816  285.57  4825.3  284.68  4831.2  283.13  4846.5  281.83  4852.4  280.25
  4861.7  279.79  4896.2  275.09  4925.1  272.76  4970.4  274.68  4991.9  272.02
    5003  269.01  5005.7  268.51    5009  269.01  5013.1   274.6    5019  278.05
  5028.3  280.71  5041.6  290.25  5049.4  291.03  5055.4  295.45  5064.6  297.04
  5070.6  297.07  5078.9  300.06  5100.9  302.88  5143.3  306.36  5203.3  307.54
#Mann= 5 ,-1 , 0
  4644.1     .05       0  4896.2     .16       0    5003     .07       0
    5009     .16       0  5078.9     .05       0
Bank Sta=4970.4,5041.6
XS Rating Curve= 0 ,0
Exp/Cntr=0.3,0.1

Type RM Length L Ch R = 1 ,12486   ,193,193,193
BEGIN DESCRIPTION:
UNT057 IN BECR 23.0
END DESCRIPTION:
XS GIS Cut Line= 3
      3790664.72      10492792.3       3790529.3     10492531.86
      3790286.24     10492420.75
#Sta/Elev= 30
  4772.8  308.23  4815.5   306.4  4854.1  300.88  4859.7  299.11  4876.2  297.54
  4910.4  291.09  4926.1  289.58  4942.5  285.98  4964.6  278.87  4970.3   278.4
  4978.1  272.31  4986.7  270.36  4992.4  271.09  4994.6  270.61  5011.5  267.99
  5014.2  267.49  5017.5  267.99    5031  271.46    5088  273.54    5099  273.37
  5105.5  271.49    5111  274.41  5151.5  279.71    5165  283.96  5174.5  285.01
    5187  289.66  5203.4  293.53  5241.9  298.41  5254.6  297.39  5333.6  301.57
#Mann= 5 ,-1 , 0
  4772.8     .05       0  4994.6     .16       0  5011.5     .07       0
  5017.5     .16       0  5203.4     .05       0
Bank Sta=4992.4,5031
XS Rating Curve= 0 ,0
Exp/Cntr=0.3,0.1

Type RM Length L Ch R = 1 ,12293   ,103,103,103
BEGIN DESCRIPTION:
Mapping XS 9ea000a7
END DESCRIPTION:
XS GIS Cut Line= 3
      3791098.75     10492604.78      3790723.74     10492455.47
      3790317.51     10492327.01
#Sta/Elev= 30
  4485.1  308.95  4648.6  296.62  4697.2  294.96  4726.8  292.39  4732.2  289.98
    4743  290.79  4774.8  289.83  4817.8  283.36  4847.8     281  4945.5  276.07
  4953.4  273.92  4958.6  269.48  4963.5  268.84  4985.7  269.81  5005.4   267.3
  5008.2   266.8  5011.4   267.3  5039.9  270.46  5052.6  270.18  5060.9  270.69
  5081.9   267.7  5113.3  278.12  5134.3  282.37  5176.3   285.7  5217.1  293.47
  5222.4  291.75  5239.2   295.8  5254.7  295.87  5260.2  298.58  5314.8  302.88
#Mann= 7 ,-1 , 0
  4485.1     .05       0    4743     .08       0  4847.8     .05       0
  4963.5     .16       0  5005.4     .07       0  5011.4     .16       0
  5052.6     .05       0
Bank Sta=4985.7,5039.9
XS Rating Curve= 0 ,0
Exp/Cntr=0.3,0.1

Type RM Length L Ch R = 1 ,12190   ,193,193,193
BEGIN DESCRIPTION:
Mapping XS 3220ce87
END DESCRIPTION:
XS GIS Cut Line= 4
      3791150.85      10492490.2      3790758.46     10492368.67
      3790550.13     10492299.22      3790338.29     10492139.47
#Sta/Elev= 30
    4505   306.6    4611  303.63  4657.6  300.41  4690.2   294.7  4736.6   289.1
  4778.5  285.82  4799.4  282.59  4851.8  279.35  4858.5  277.26  4863.7  277.98
  4923.3  273.07  4960.2  271.61  4986.5  270.43  4995.9  268.29  4998.6  267.79
  5001.9  268.29  5018.2  270.29  5041.1  269.97  5106.6  275.36  5113.7   277.3
  5125.4  279.51    5133  282.44  5138.7  282.44    5163  287.43  5171.3  290.52
  5177.6  289.79  5192.1  291.57  5206.7  296.34  5235.8  299.83  5400.7  307.31
#Mann= 5 ,-1 , 0
    4505     .05       0  4995.9     .04       0  5001.9     .05       0
  5106.6     .16       0  5113.7     .05       0
Bank Sta=4960.2,5018.2
XS Rating Curve= 0 ,0
Exp/Cntr=0.3,0.1

Type RM Length L Ch R = 1 ,11997   ,446,446,446
BEGIN DESCRIPTION:
UNT057 IN BECR 22.0
END DESCRIPTION:
XS GIS Cut Line= 2
      3791102.18     10492326.98      3790548.09     10492084.57
#Sta/Elev= 30
  4614.2  301.07  4682.5  299.94  4737.1   295.9  4795.2  288.03  4847.4  277.57
  4871.9  275.32  4923.1  268.73  4933.5  268.51    4941   270.6  4946.5   267.4
  4955.4   270.2  4964.4  270.66  4993.2  266.58    4996  264.86  4998.8  264.36
    5002  264.86  5009.9  266.24  5022.1  271.32  5031.8   269.8  5045.5  270.62
  5063.4  276.45  5068.9  275.78  5086.4  279.63  5092.3  282.71  5144.5   289.5
  5150.8  291.72  5167.9  292.93  5173.7  296.17  5191.3  298.99    5219  301.75
#Mann= 5 ,-1 , 0
  4614.2     .05       0  4871.9     .16       0    4996     .07       0
    5002     .16       0  5150.8     .05       0
Bank Sta=4964.4,5022.1
XS Rating Curve= 0 ,0
Exp/Cntr=0.3,0.1

Type RM Length L Ch R = 1 ,11551   ,411,411,411
BEGIN DESCRIPTION:
UNT057 IN BECR 21.0
END DESCRIPTION:
XS GIS Cut Line= 3
      3791199.63     10491960.19      3790999.61     10491910.19
      3790799.63     10491660.21
#Sta/Elev= 30
  4770.9  292.34  4781.2  292.16    4789  290.63  4801.8  289.54  4812.2  286.36
  4822.5  285.11  4830.2  282.81  4854.7  279.05  4884.3  275.04  4935.8  269.99
    4959  266.64  4980.3  265.98  4990.7  263.57  5002.1  263.36  5004.8  262.86
  5008.1  263.36  5013.1  269.54  5027.5  270.18  5048.3  269.46  5054.7  270.07
  5126.7  270.54    5162  272.92  5182.8   275.7  5197.2  279.24  5211.6  284.52
    5226  293.23  5233.2  294.65  5240.4  297.65  5269.2  302.99  5297.2  304.81
#Mann= 4 ,-1 , 0
  4770.9     .05       0  4854.7     .16       0  5002.1     .07       0
  5008.1     .16       0
Bank Sta=4980.3,5013.1
XS Rating Curve= 0 ,0
Exp/Cntr=0.3,0.1

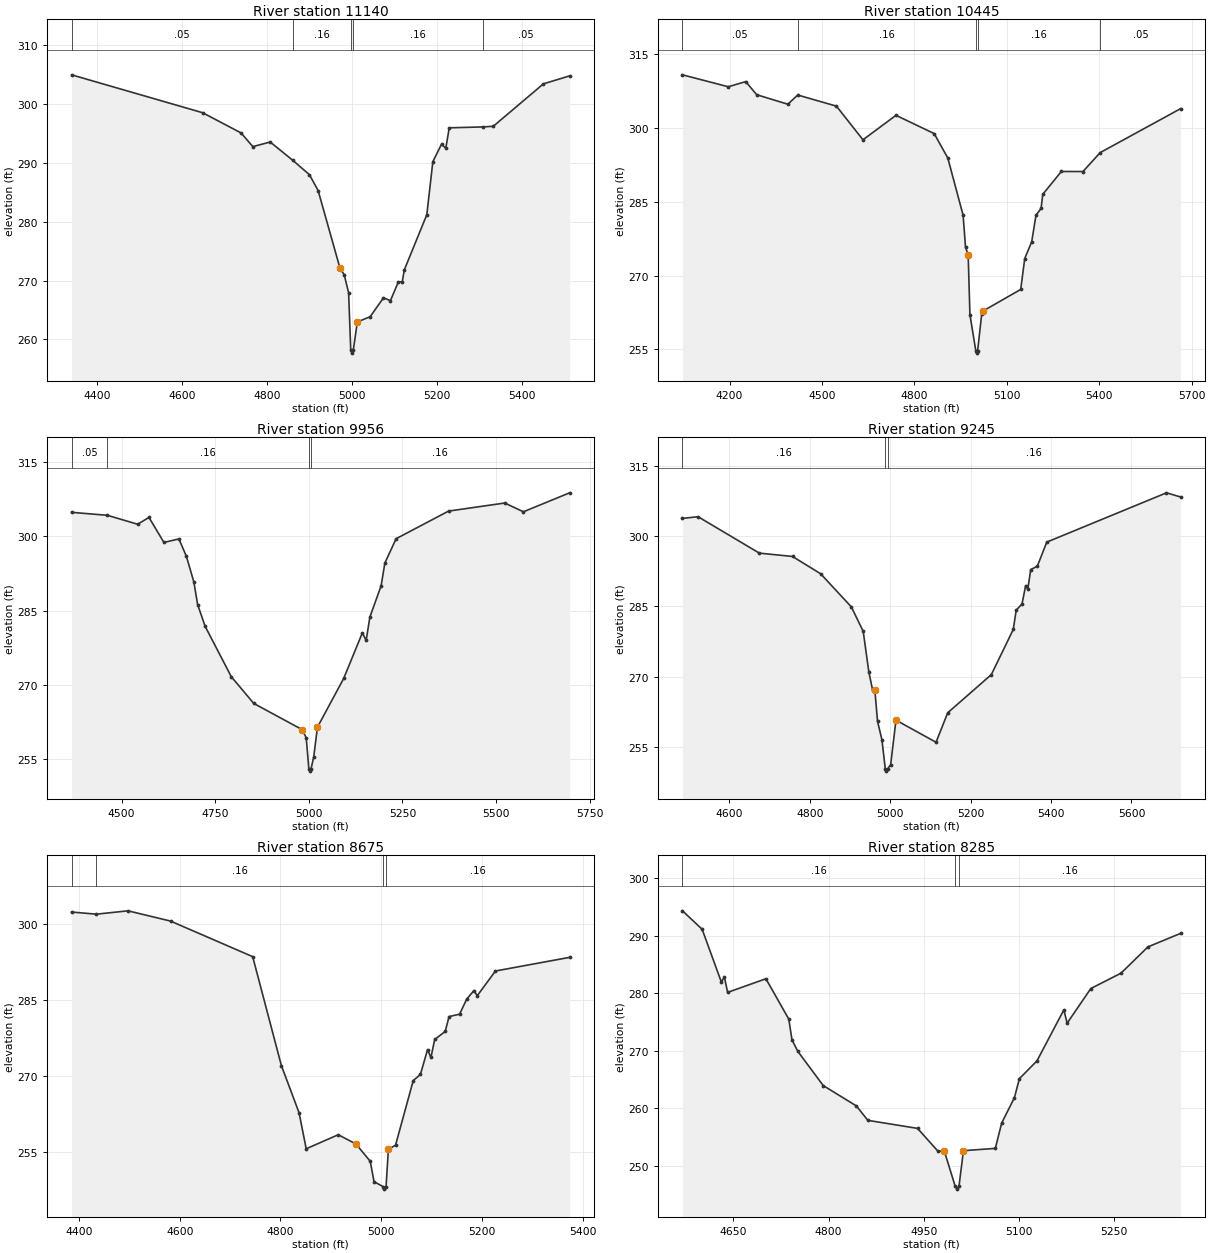
Type RM Length L Ch R = 1 ,11140   ,695,695,695
BEGIN DESCRIPTION:
UNT057 IN BECR 20.0
END DESCRIPTION:
XS GIS Cut Line= 3
      3791444.14     10492386.37      3791273.99     10491650.23
      3790862.71     10491574.19
#Sta/Elev= 30
  4338.9   304.9  4647.8  298.47  4738.4  295.04  4766.1  292.72  4807.1   293.5
  4860.5  290.38  4899.5  287.96    4920  285.27  4971.3  272.15  4981.6  270.96
  4991.9  267.91  4996.9  258.18  4999.7  257.68  5002.9  258.18  5012.4  262.98
  5042.7  263.86    5074  267.06  5090.5  266.59  5109.1  269.78  5118.2  269.75
  5123.2  271.81  5176.2  281.17  5190.4  290.17  5210.8  293.12  5220.9  292.45
  5229.1  295.91  5308.2  296.06  5332.8  296.17    5451  303.37  5512.7  304.72
#Mann= 5 ,-1 , 0
  4338.9     .05       0  4860.5     .16       0  4996.9     .07       0
  5002.9     .16       0  5308.2     .05       0
Bank Sta=4971.3,5012.4
XS Rating Curve= 0 ,0
Exp/Cntr=0.3,0.1

Type RM Length L Ch R = 1 ,10445   ,489,489,489
BEGIN DESCRIPTION:
UNT057 IN BECR 19.0
END DESCRIPTION:
XS GIS Cut Line= 4
      3792343.42     10491712.72       3791746.1     10491292.02
      3791343.43     10491504.39       3790913.7     10491535.58
#Sta/Elev= 30
  4047.3  310.84    4196  308.41  4252.6  309.46  4288.3  306.79  4389.3  304.86
  4421.4  306.73    4547  304.47  4633.2  297.62  4740.4   302.6  4864.4  298.88
  4908.6  293.91  4958.3  282.25  4966.1  275.74  4974.7  274.23  4980.4  262.03
  4999.4  254.71  5002.1  254.21  5005.4  254.71  5018.7  262.19  5024.4  262.83
  5145.2  267.17  5158.3  273.45  5180.9  276.87  5194.9  282.28  5211.3  283.65
    5217  286.53  5277.1  291.17  5347.3  291.16  5403.2  295.01    5664  303.95
#Mann= 5 ,-1 , 0
  4047.3     .05       0  4421.4     .16       0  4999.4     .07       0
  5005.4     .16       0  5403.2     .05       0
Bank Sta=4974.7,5024.4
XS Rating Curve= 0 ,0
Exp/Cntr=0.3,0.1

Type RM Length L Ch R = 1 ,9956    ,711,711,711
BEGIN DESCRIPTION:
UNT057 IN BECR 18.0
END DESCRIPTION:
XS GIS Cut Line= 2
       3791996.2     10491129.39       3790666.3     10491125.92
#Sta/Elev= 30
  4366.6  304.87  4462.3  304.27  4543.2  302.46  4573.2  303.85  4613.2  298.79
  4653.2   299.5  4673.2  295.99  4693.2  290.79  4703.2  286.25  4723.2  281.86
  4793.2  271.66  4853.2  266.27  4983.2  260.95  4993.2  259.31  5000.2   253.1
  5002.9   252.6  5006.2   253.1  5013.2  255.45  5023.2  261.48  5093.2  271.31
  5143.2  280.54  5153.2  278.99  5163.2  283.72  5193.2  290.03  5203.2  294.63
  5233.2  299.54  5373.2  305.12  5523.2  306.75  5573.2  304.98  5696.5  308.81
#Mann= 4 ,-1 , 0
  4366.6     .05       0  4462.3     .16       0  5000.2     .07       0
  5006.2     .16       0
Bank Sta=4983.2,5023.2
XS Rating Curve= 0 ,0
Exp/Cntr=0.3,0.1

Type RM Length L Ch R = 1 ,9245    ,570,570,570
BEGIN DESCRIPTION:
UNT057 IN BECR 17.0
END DESCRIPTION:
XS GIS Cut Line= 2
      3791885.13     10490983.57      3790747.58     10490494.57
#Sta/Elev= 30
  4483.7  303.76  4522.4  304.12  4674.8  296.36  4757.3  295.65  4827.1  291.97
  4903.3  284.93    4933  279.71  4946.9  271.11  4956.5  267.12    4962  267.15
  4968.6  260.53  4979.5  256.62  4987.9  250.41  4990.7  249.91  4993.9  250.41
  5001.3  251.32  5014.5  260.77  5114.1  256.06  5143.1  262.34  5251.6  270.48
  5306.1   280.1  5313.4  284.22  5327.8  285.51  5336.9  289.44  5342.3  288.75
  5349.6  292.86  5365.9  293.57  5389.4  298.71    5687  309.21  5721.9  308.33
#Mann= 3 ,-1 , 0
  4483.7     .16       0  4987.9     .07       0  4993.9     .16       0
Bank Sta=4962,5014.5
XS Rating Curve= 0 ,0
Exp/Cntr=0.3,0.1

Type RM Length L Ch R = 1 ,8675    ,390,390,390
BEGIN DESCRIPTION:
UNT057 IN BECR 16.0
END DESCRIPTION:
XS GIS Cut Line= 2
      3791942.96     10490904.38      3791290.16      10490161.3
#Sta/Elev= 30
  4385.2  302.27  4434.4  301.85  4497.3  302.51  4581.7  300.49  4744.9  293.47
  4801.9  271.98    4837  262.68  4851.2  255.57  4914.8  258.34  4949.9  256.52
  4978.4   253.1  4985.9  249.08  5003.8  248.11  5006.6  247.61  5009.8  248.11
  5014.4  255.46  5028.6  256.28  5063.8  269.03    5078  270.23  5092.2  275.14
  5098.9  273.58  5106.4  277.13  5127.3  278.72  5134.9  281.65  5155.8  282.12
    5170   285.1  5184.3  286.78  5190.9  285.76    5227  290.64  5374.3  293.33
#Mann= 4 ,-1 , 0
  4385.2     .05       0  4434.4     .16       0  5003.8     .07       0
  5009.8     .16       0
Bank Sta=4949.9,5014.4
XS Rating Curve= 0 ,0
Exp/Cntr=0.3,0.1

Type RM Length L Ch R = 1 ,8285    ,437,437,437
BEGIN DESCRIPTION:
UNT057 IN BECR 15.0
END DESCRIPTION:
XS GIS Cut Line= 3
      3792110.44     10490138.74      3791579.22     10490190.82
       3791334.5     10490133.55
#Sta/Elev= 30
  4569.6  294.33  4600.6  291.12  4630.7  281.99  4635.7  282.76  4640.8  280.14
  4701.1  282.51  4737.2  275.48  4742.2  271.88  4751.3  269.89  4791.5  263.92
  4843.7  260.38  4861.8  257.87  4940.2  256.47  4972.4  252.49  4982.4  252.51
  4999.5   246.4  5002.2   245.9  5005.5   246.4  5012.5  252.59  5062.8  252.99
  5072.8  257.41  5092.9  261.82  5100.7  265.12  5128.4  268.22  5170.8  277.09
    5176  274.78  5213.3  280.81  5260.9  283.48  5303.4  288.06  5354.7   290.4
#Mann= 3 ,-1 , 0
  4569.6     .16       0  4999.5     .07       0  5005.5     .16       0
Bank Sta=4982.4,5012.5
XS Rating Curve= 0 ,0
Exp/Cntr=0.3,0.1

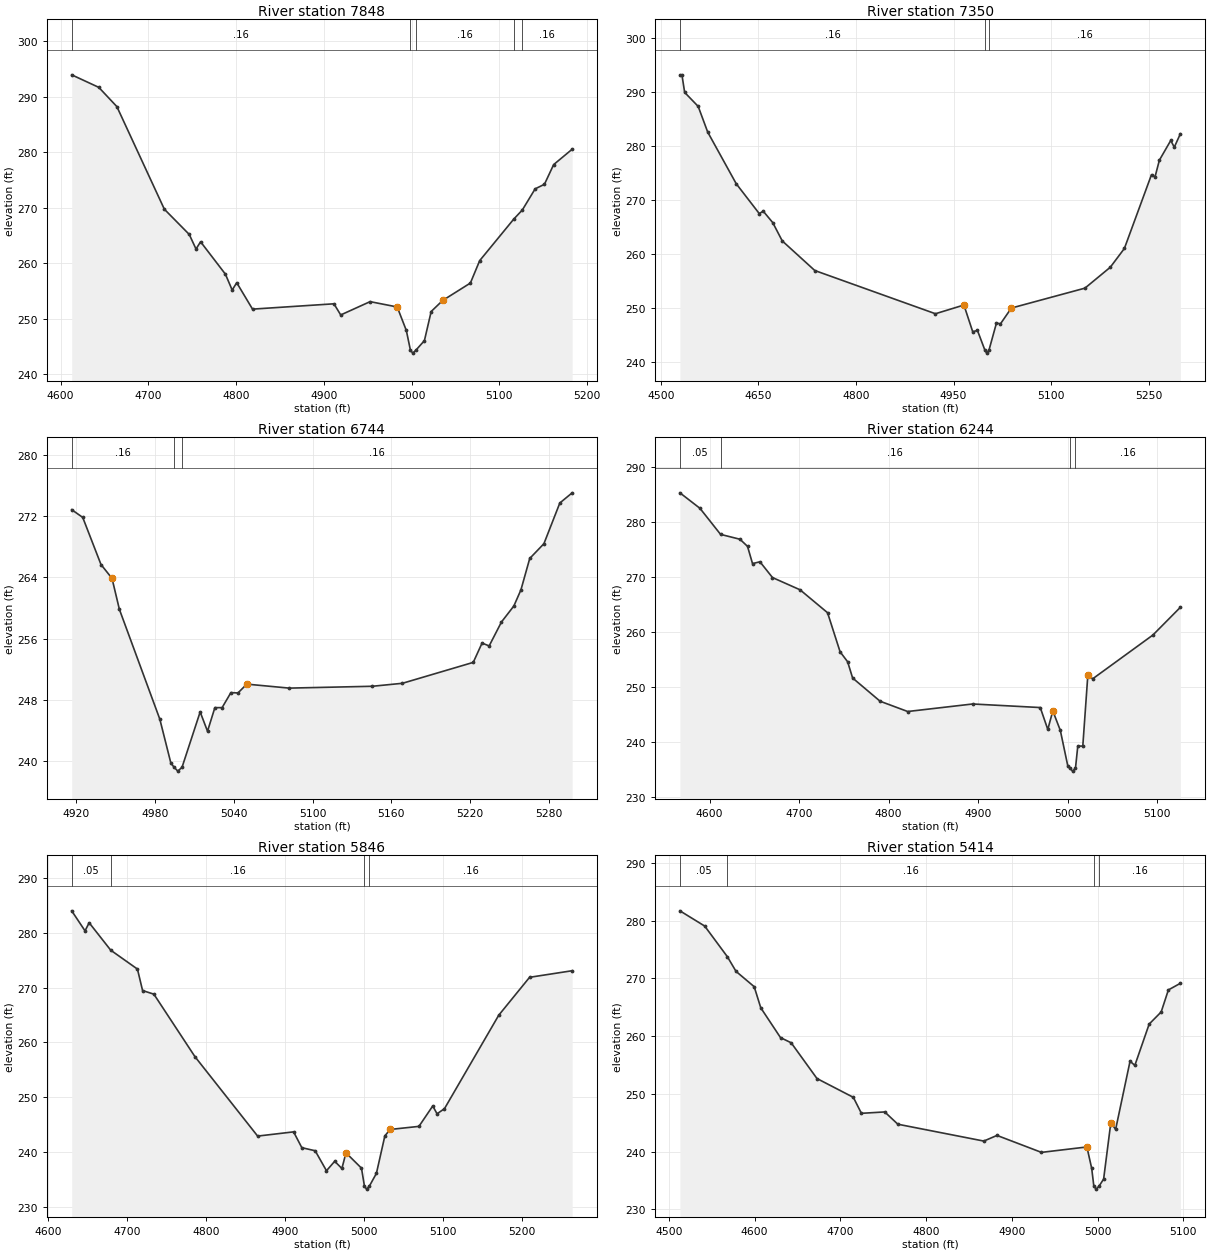
Type RM Length L Ch R = 1 ,7848    ,498,498,498
BEGIN DESCRIPTION:
UNT057 IN BECR 14.0
END DESCRIPTION:
XS GIS Cut Line= 3
      3791949.58      10489760.2      3791549.61     10489860.19
       3791399.6     10489910.19
#Sta/Elev= 30
  4612.7  293.93  4643.6  291.67  4664.2   288.2  4718.3  269.71  4746.7  265.16
  4754.4  262.53  4759.6  263.84  4787.9     258  4795.6  255.14  4800.8  256.46
  4818.8   251.7  4911.6  252.66  4919.3  250.65  4952.8  253.05  4983.7  252.09
  4994.1  247.85  4998.8  244.27  5001.5  243.77  5004.8  244.27  5014.7  246.02
  5022.4  251.27  5035.5  253.26  5067.1   256.4  5077.7  260.44  5116.6  267.94
  5126.3  269.57  5140.9  273.38  5151.5   274.2    5162  277.75  5183.1  280.52
#Mann= 5 ,-1 , 0
  4612.7     .16       0  4998.8     .07       0  5004.8     .16       0
  5116.6      .1       0  5126.3     .16       0
Bank Sta=4983.7,5035.5
XS Rating Curve= 0 ,0
Exp/Cntr=0.3,0.1

Type RM Length L Ch R = 1 ,7350    ,606,606,606
BEGIN DESCRIPTION:
UNT057 IN BECR 13.0
END DESCRIPTION:
XS GIS Cut Line= 3
       3791949.6     10489710.18      3791549.61     10489410.19
      3791299.66     10489510.17
#Sta/Elev= 30
  4529.5  293.15  4532.6  293.15  4536.8   289.9  4557.6  287.31  4572.2  282.57
    4616  273.03  4651.4  267.51  4657.6  267.94  4672.2  265.83  4686.8  262.45
  4736.8  256.98  4922.2  248.99    4966   250.6  4979.5  245.67  4986.8   245.9
  4998.4  242.21  5001.1  241.71  5004.4  242.21    5016  247.27  5022.2  247.13
  5038.9  250.04    5152  253.72    5191  257.59  5212.6  261.05  5254.3   274.7
  5259.7  274.27  5266.4  277.37  5283.9  281.02  5289.3  279.77  5298.7  282.26
#Mann= 3 ,-1 , 0
  4529.5     .16       0  4998.4     .07       0  5004.4     .16       0
Bank Sta=4966,5038.9
XS Rating Curve= 0 ,0
Exp/Cntr=0.3,0.1

Type RM Length L Ch R = 1 ,6744    ,500,500,500
BEGIN DESCRIPTION:
UNT057 IN BECR 12.0
END DESCRIPTION:
XS GIS Cut Line= 3
       3791499.6      10489010.2      3791399.61     10489060.19
      3791149.65     10489160.17
#Sta/Elev= 30
  4916.6  272.84    4925  271.83  4938.9  265.68  4947.3  263.87  4952.9  259.83
  4983.7  245.48  4992.1  239.75  4994.6   239.2  4997.4   238.7  5000.6   239.2
  5014.4  246.43    5020  243.91  5025.6  246.99  5031.1  246.99  5037.8  248.95
  5043.2  248.91  5049.9  250.06  5082.2  249.54  5145.5  249.78  5168.4  250.17
  5222.3   252.9    5229  255.42  5234.4  255.05  5243.8  258.18  5253.2  260.26
  5258.6  262.37  5265.3  266.47  5276.1   268.4  5288.2  273.71  5297.6  275.04
#Mann= 3 ,-1 , 0
  4916.6     .16       0  4994.6     .07       0  5000.6     .16       0
Bank Sta=4947.3,5049.9
XS Rating Curve= 0 ,0
Exp/Cntr=0.3,0.1

Type RM Length L Ch R = 1 ,6244    ,398,398,398
BEGIN DESCRIPTION:
UNT057 IN BECR 11.0
END DESCRIPTION:
XS GIS Cut Line= 3
      3791399.61     10488660.19      3790999.61     10488860.19
      3790899.62     10488910.18
#Sta/Elev= 30
  4566.9  285.28  4589.3  282.46  4612.3  277.72    4634  276.83  4642.4  275.54
    4648   272.4  4656.3  272.73  4670.3  269.86  4701.1  267.63  4731.8  263.46
  4745.8  256.35  4754.2  254.54  4759.8  251.58  4790.5  247.35  4821.3  245.48
  4893.9  246.85  4969.4   246.2  4977.8  242.21  4983.4  245.59  4991.8  242.04
  5000.1  235.61  5002.7  235.13  5005.5  234.63  5008.7  235.13  5011.3  239.19
  5016.9  239.19  5022.5  252.06  5028.1  251.45  5095.2   259.4  5125.9  264.45
#Mann= 4 ,-1 , 0
  4566.9     .05       0  4612.3     .16       0  5002.7     .07       0
  5008.7     .16       0
Bank Sta=4983.4,5022.5
XS Rating Curve= 0 ,0
Exp/Cntr=0.3,0.1

Type RM Length L Ch R = 1 ,5846    ,432,432,432
BEGIN DESCRIPTION:
UNT057 IN BECR 10.0
END DESCRIPTION:
XS GIS Cut Line= 3
      3791349.63     10488410.18      3790999.61     10488510.19
       3790749.6     10488410.19
#Sta/Elev= 30
  4630.3  283.98  4647.2  280.33  4652.4  281.81  4679.7  276.81  4713.5  273.37
    4720  269.46  4734.3   268.8  4786.3  257.41  4865.6  242.95  4911.1  243.72
  4921.5  240.84  4938.4  240.28  4952.7  236.64  4963.1  238.36  4972.2  237.05
  4977.4   239.9    4997  237.11  5000.8  233.79  5003.5  233.29  5006.8  233.79
  5015.9  236.16  5026.6     243  5033.4  244.16  5069.7  244.72  5087.2  248.44
  5092.6  247.01    5102  247.94  5170.7  264.97  5209.7  271.87  5263.6  273.07
#Mann= 4 ,-1 , 0
  4630.3     .05       0  4679.7     .16       0  5000.8     .07       0
  5006.8     .16       0
Bank Sta=4977.4,5033.4
XS Rating Curve= 0 ,0
Exp/Cntr=0.3,0.1

Type RM Length L Ch R = 1 ,5414    ,400,400,400
BEGIN DESCRIPTION:
UNT057 IN BECR 9.0
END DESCRIPTION:
XS GIS Cut Line= 3
      3791249.58     10487960.21      3790849.61     10488210.19
      3790749.58      10488260.2
#Sta/Elev= 30
    4513  281.73  4541.9  279.09  4568.4  273.76  4578.4  271.24  4599.6  268.58
  4607.3  264.91  4630.3  259.75  4642.7  258.86  4672.8  252.66  4715.2   249.4
  4724.6  246.63  4751.8  246.87  4767.1  244.74  4867.3  241.82  4882.7   242.8
  4934.5  239.86  4987.5   240.8  4993.1  237.08  4995.6  233.99  4998.4  233.49
  5001.6  233.99    5007  235.23  5015.4  245.02    5021  243.84  5037.8  255.66
  5043.4  254.94  5060.1   262.1  5074.1   264.2  5082.5  268.02  5096.5  269.17
#Mann= 4 ,-1 , 0
    4513     .05       0  4568.4     .16       0  4995.6     .07       0
  5001.6     .16       0
Bank Sta=4987.5,5015.4
XS Rating Curve= 0 ,0
Exp/Cntr=0.3,0.1

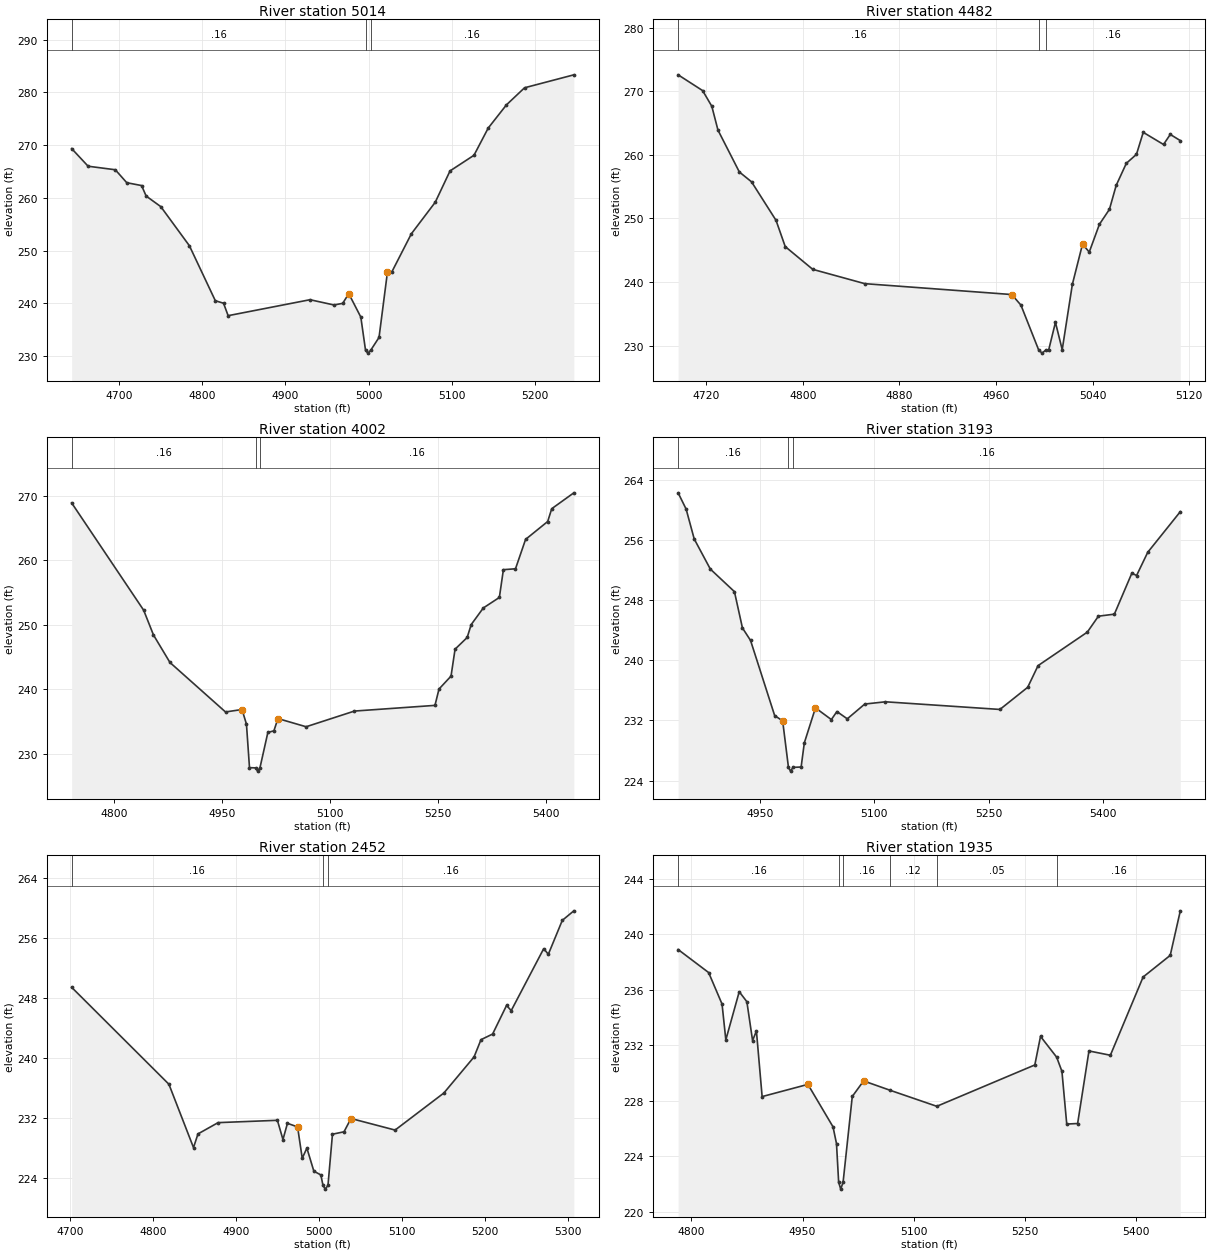
Type RM Length L Ch R = 1 ,5014    ,532,532,532
BEGIN DESCRIPTION:
UNT057 IN BECR 8.0
END DESCRIPTION:
XS GIS Cut Line= 2
      3791037.59     10487779.35      3790485.43     10488024.18
#Sta/Elev= 30
  4642.9  269.35  4662.7     266  4695.4  265.33  4709.2  262.87    4727  262.33
  4732.5  260.34  4750.1  258.33  4784.5  250.91  4815.7  240.47  4825.6  239.99
  4831.1  237.63  4929.6  240.66  4958.4  239.66  4968.9  239.97  4976.2  241.81
  4990.7  237.36  4996.4  231.02  4999.2  230.52  5002.4  231.02  5012.6   233.5
  5022.7  245.88  5028.2     246  5051.5  253.18  5080.2  259.16    5098  265.11
  5126.8  268.08  5143.9  273.24  5165.8  277.64  5187.6  280.89  5246.9  283.35
#Mann= 3 ,-1 , 0
  4642.9     .16       0  4996.4     .07       0  5002.4     .16       0
Bank Sta=4976.2,5022.7
XS Rating Curve= 0 ,0
Exp/Cntr=0.3,0.1

Type RM Length L Ch R = 1 ,4482    ,480,480,480
BEGIN DESCRIPTION:
UNT057 IN BECR 7.0
END DESCRIPTION:
XS GIS Cut Line= 3
      3790949.61     10487560.19      3790649.61     10487510.19
      3790549.65     10487560.17
#Sta/Elev= 30
  4696.8  272.57  4717.1  270.09  4724.7  267.63  4729.8  263.88  4747.5   257.3
  4757.6  255.75  4777.9  249.69  4785.5  245.57  4808.3  241.99  4851.4  239.74
  4973.1  238.03  4980.7  236.37  4995.4  229.32  4998.2  228.82  5001.4  229.32
  5003.7  229.32  5009.3  233.66  5014.9  229.36  5023.3  239.63  5031.7  245.94
  5037.3  244.71  5045.7  249.07    5054  251.42  5059.6  255.19    5068  258.66
  5076.4  260.07    5082  263.53  5098.8  261.62  5104.4   263.2  5112.7  262.23
#Mann= 3 ,-1 , 0
  4696.8     .16       0  4995.4     .07       0  5001.4     .16       0
Bank Sta=4973.1,5031.7
XS Rating Curve= 0 ,0
Exp/Cntr=0.3,0.1

Type RM Length L Ch R = 1 ,4002    ,809,809,809
BEGIN DESCRIPTION:
UNT057 IN BECR 6.0
END DESCRIPTION:
XS GIS Cut Line= 3
      3790799.62     10486860.17      3790649.61     10487060.19
      3790249.64     10487260.17
#Sta/Elev= 30
  4741.3  268.89  4841.3  252.27  4854.9  248.44  4877.8  244.18  4954.9  236.52
  4977.8   236.9    4984  234.63  4988.2   227.9  4996.7  227.86  4999.5  227.36
  5002.7  227.86  5013.7  233.35  5022.1   233.6  5027.7   235.5  5066.8  234.23
  5133.9  236.66  5245.7  237.54  5251.3  240.07    5268  242.07  5273.6  246.24
  5290.4  248.05    5296  250.05  5312.8  252.62  5335.1  254.25  5340.7  258.55
  5357.5  258.69  5371.5  263.24  5402.2  266.01  5407.8  267.99  5438.5  270.45
#Mann= 3 ,-1 , 0
  4741.3     .16       0  4996.7     .07       0  5002.7     .16       0
Bank Sta=4977.8,5027.7
XS Rating Curve= 0 ,0
Exp/Cntr=0.3,0.1

Type RM Length L Ch R = 1 ,3193    ,741,741,741
BEGIN DESCRIPTION:
UNT057 IN BECR 5.0
END DESCRIPTION:
XS GIS Cut Line= 3
      3790499.61     10486710.19      3790349.61     10486760.19
      3790049.62     10487160.17
#Sta/Elev= 30
    4843  262.34  4853.5  260.17  4864.1  256.19  4885.2  252.18  4916.8  249.17
  4927.3  244.33  4937.9  242.67  4969.5  232.66    4980  231.94  4987.6  225.75
  4990.3  225.25  4993.6  225.75  5004.2   225.8  5008.4  229.02    5023  233.68
  5043.8  232.12  5051.1  233.19  5064.7  232.22  5087.6  234.19  5114.7  234.49
  5264.7  233.47  5301.1  236.42  5314.7  239.31  5379.2  243.77  5393.8   245.9
  5414.7  246.17  5437.6  251.63  5443.8  251.32  5458.4  254.41  5501.1  259.83
#Mann= 3 ,-1 , 0
    4843     .16       0  4987.6     .07       0  4993.6     .16       0
Bank Sta=4980,5023
XS Rating Curve= 0 ,0
Exp/Cntr=0.3,0.1

Type RM Length L Ch R = 1 ,2452    ,517,517,517
BEGIN DESCRIPTION:
UNT057 IN BECR 4.0
END DESCRIPTION:
XS GIS Cut Line= 3
       3789999.6     10486510.22      3789899.61     10486760.19
      3789749.63     10487060.15
#Sta/Elev= 30
  4702.3   249.4  4819.4   236.5    4849  228.07  4854.4  229.89  4878.6  231.39
    4950   231.7  4956.7  229.14  4962.1   231.3  4974.3  230.82  4979.9  226.65
  4985.5     228  4993.9  224.93  5002.3  224.43  5004.9  223.04  5007.6  222.54
  5010.9  223.04  5016.3  229.85  5030.2  230.17  5038.6  231.94  5091.7   230.4
  5150.4  235.33  5186.8  240.14  5195.1  242.43  5209.1  243.18  5225.9  246.99
  5231.5   246.3  5270.6  254.54  5276.2   253.8    5293  258.31  5306.9  259.58
#Mann= 3 ,-1 , 0
  4702.3     .16       0  5004.9     .07       0  5010.9     .16       0
Bank Sta=4974.3,5038.6
XS Rating Curve= 0 ,0
Exp/Cntr=0.3,0.1

Type RM Length L Ch R = 1 ,1935    ,475,475,475
BEGIN DESCRIPTION:
UNT057 IN BECR 3.0
END DESCRIPTION:
XS GIS Cut Line= 3
      3789749.62     10486460.19      3789549.61     10486510.19
      3789299.59     10486910.22
#Sta/Elev= 30
    4782   238.9  4823.2  237.24  4841.3  234.97  4846.4  232.39  4864.5  235.86
  4874.8  235.14  4882.5  232.34  4887.7  233.03  4895.4   228.3  4957.2  229.18
  4991.1  226.12  4995.8  224.91  4998.7  222.13  5001.5  221.63  5004.7  222.13
  5017.1  228.31  5032.4  229.43  5067.9  228.76  5131.2   227.6  5263.5  230.58
  5271.2  232.64    5293  231.14  5300.1  230.12  5306.6  226.32  5321.3  226.36
  5336.6  231.59  5365.5  231.28  5409.7  236.92  5446.3  238.48  5459.9  241.69
#Mann= 6 ,-1 , 0
    4782     .16       0  4998.7     .07       0  5004.7     .16       0
  5067.9     .12       0  5131.2     .05       0    5293     .16       0
Bank Sta=4957.2,5032.4
XS Rating Curve= 0 ,0
Exp/Cntr=0.3,0.1