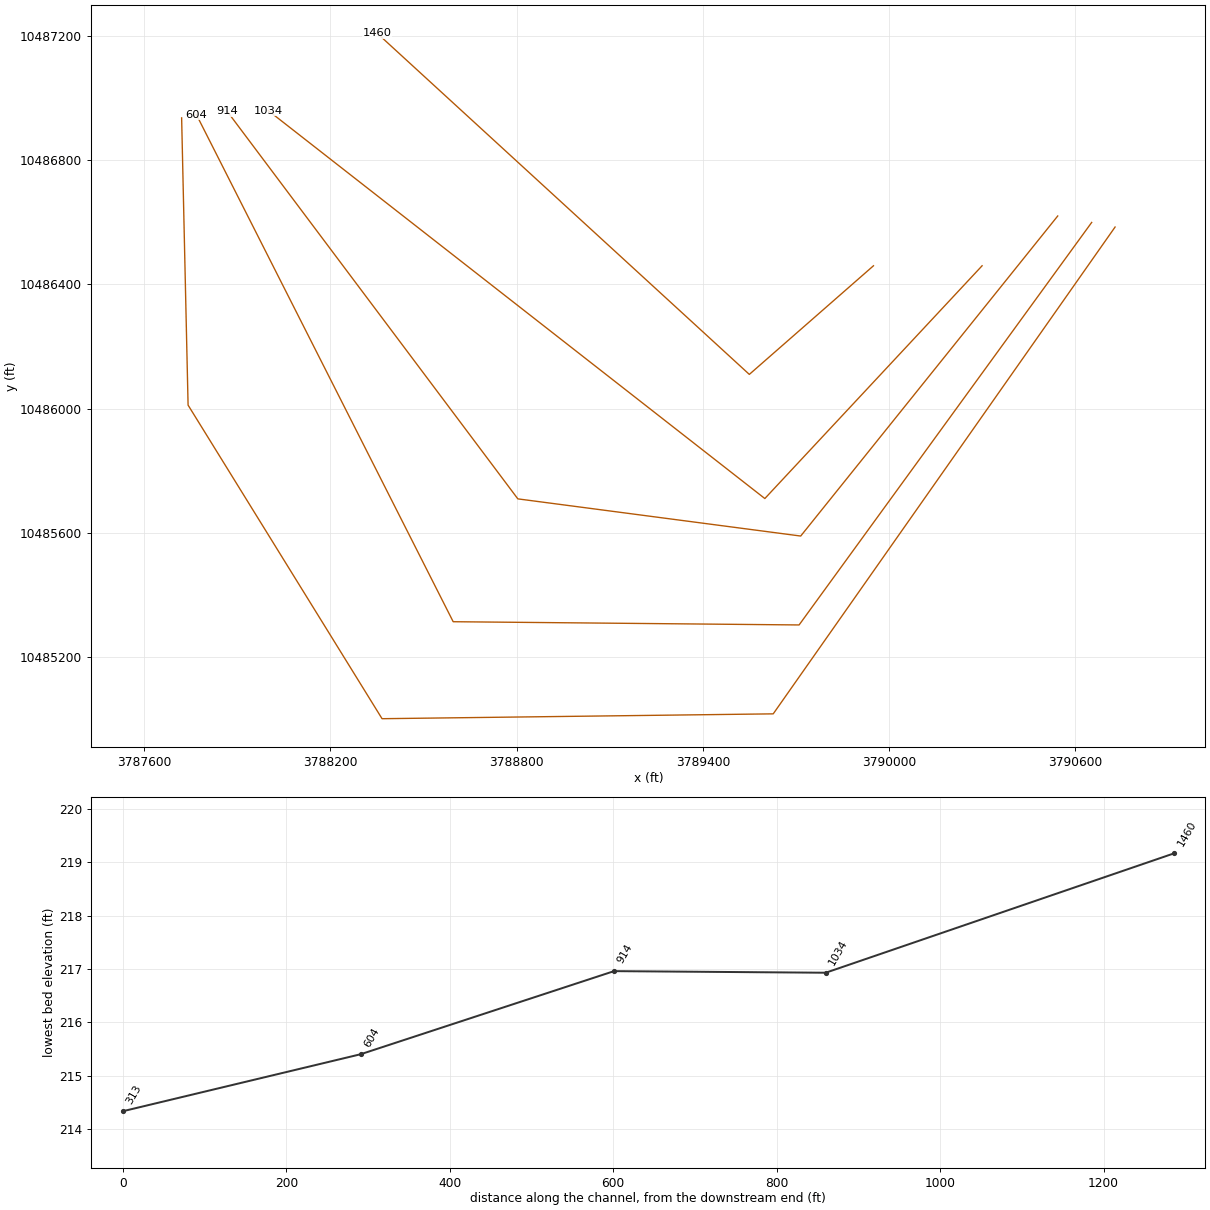
HEC-RAS study UNT057 IN BECR.prj: UNT057 IN BECR Base Level Engineering

--- UNT057 IN BECR.g01 (geometry) --- (continued)

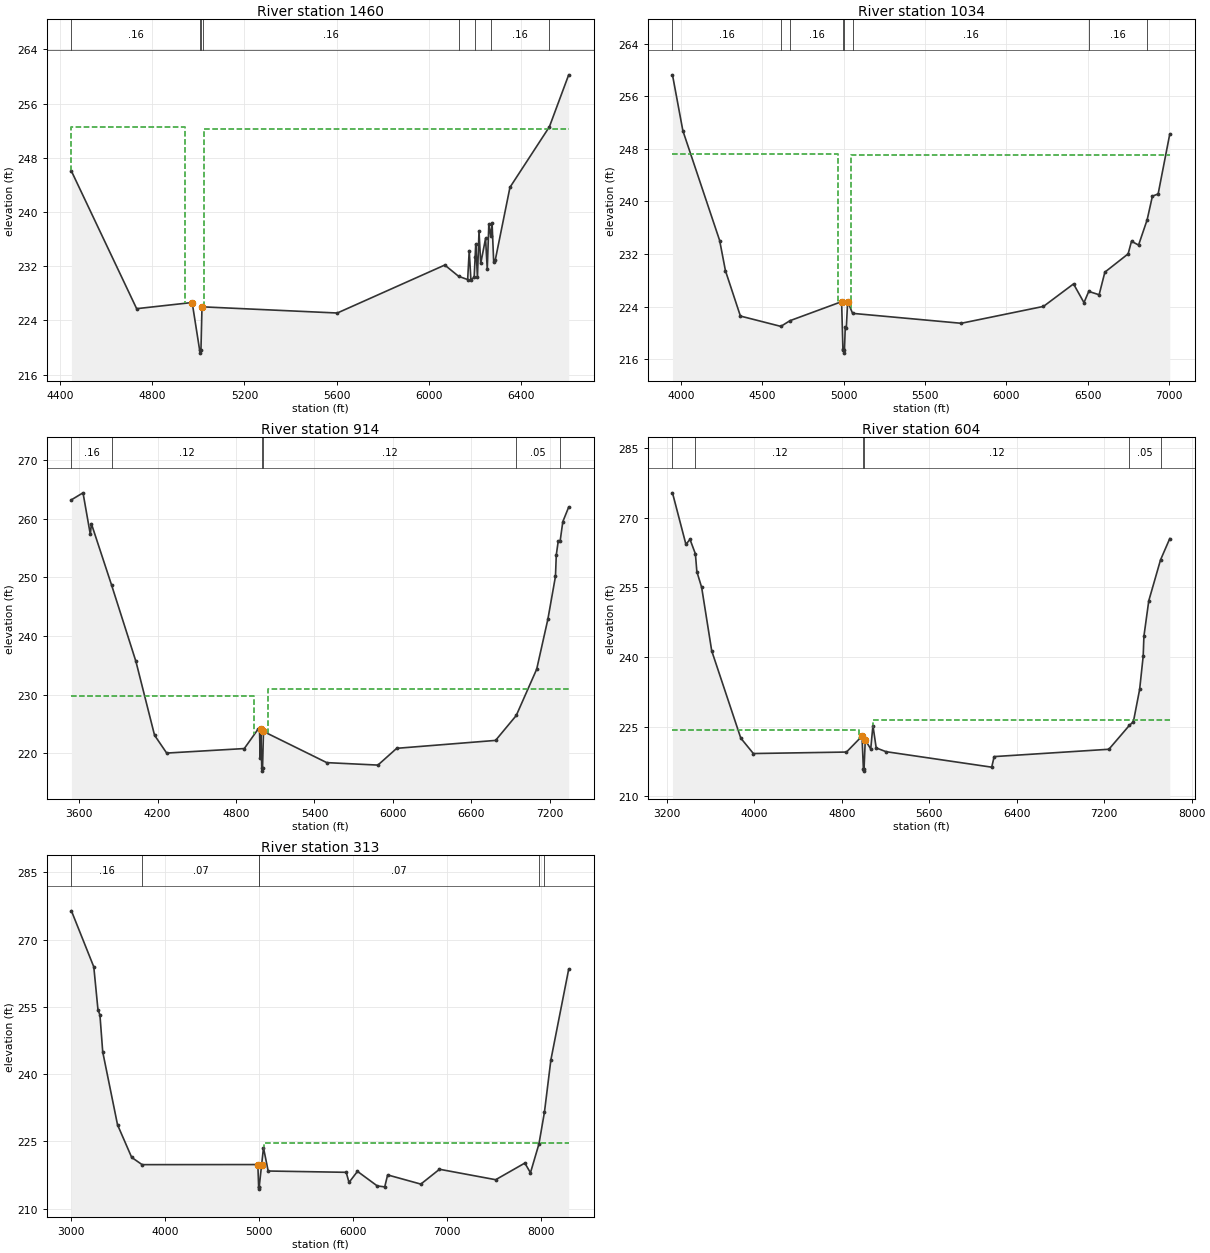
Type RM Length L Ch R = 1 ,1460    ,426,426,426
BEGIN DESCRIPTION:
UNT057 IN BECR 2.0
END DESCRIPTION:
XS GIS Cut Line= 3
      3789949.62      10486460.2      3789549.61     10486110.19
      3788349.61     10487210.18
#Sta/Elev= 30
  4448.6  246.04  4731.9  225.73    4973  226.64  5005.2  219.67  5007.9  219.17
  5011.2  219.67  5015.6  225.93  5018.6     226  5603.2  225.09    6070  232.17
  6130.3   230.5  6169.3  230.03  6176.1   234.3  6183.5  229.92  6197.6   230.4
  6201.8  233.39  6204.4  235.24  6211.8  230.39  6218.6  237.19    6226   232.4
    6247  236.09  6254.4  231.54  6261.2  238.16  6269.3  236.43  6275.3  238.34
  6282.4  232.57  6289.5  232.96    6353  243.64  6524.2  252.57    6608  260.24
#Mann= 8 ,-1 , 0
  4448.6     .16       0  5005.2     .07       0  5011.2     .16       0
  5018.6     .16       0  6130.3     .16       0  6201.8     .05       0
  6269.3     .16       0  6524.2     .12       0
#XS Ineff= 2 , 0
         4943.64  252.61 5026.21          252.24
Permanent Ineff=
       F       F
Bank Sta=4973,5015.6
XS Rating Curve= 0 ,0
Exp/Cntr=0.3,0.1

Type RM Length L Ch R = 1 ,1034    ,259,259,259
BEGIN DESCRIPTION:
UNT057 IN BECR 1.0
END DESCRIPTION:
XS GIS Cut Line= 3
      3790299.63     10486460.21      3789599.61     10485710.19
      3787999.63     10486960.17
#Sta/Elev= 30
  3947.9  259.27  4011.7  250.77  4237.9  234.06  4273.5  229.46  4365.4  222.57
  4613.8     221  4670.5  221.87  4987.4  224.76  4995.5  217.55  4998.9  217.43
  5001.6  216.93  5004.9  217.43    5010  220.93  5016.3  220.78  5024.5  224.77
    5055  222.98  5722.5  221.47  6228.2  224.04  6412.8  227.46    6477  224.61
  6506.3  226.32  6570.1  225.81  6605.4  229.25  6748.3  232.03  6769.1  233.95
  6812.5  233.37  6865.2  237.21  6897.5  240.81  6932.8  241.15  7004.2  250.25
#Mann= 8 ,-1 , 0
  3947.9     .16       0  4613.8     .16       0  4670.5     .16       0
  4998.9     .07       0  5004.9     .16       0    5055     .16       0
  6506.3     .16       0  6865.2     .05       0
#XS Ineff= 2 , 0
         4965.27  247.24 5043.91          247.01
Permanent Ineff=
       F       F
Bank Sta=4987.4,5024.5
XS Rating Curve= 0 ,0
Exp/Cntr=0.3,0.1

Type RM Length L Ch R = 1 ,914     ,310,310,310
BEGIN DESCRIPTION:
Mapping XS cdef5972
END DESCRIPTION:
XS GIS Cut Line= 4
       3790543.3      10486620.6      3789715.16     10485589.33
       3788803.7     10485709.12      3787866.22      10486959.1
#Sta/Elev= 30
  3540.7  263.24  3629.5  264.43  3685.5  257.33  3693.5  259.17    3849  248.63
  4034.4  235.66  4176.8  223.08  4269.6  220.04  4863.3  220.81  4969.8  224.15
  4979.9  223.93    4985  219.12    4990   224.1    4997  217.46  4999.8  216.96
    5003  217.46  5010.1  223.73  5494.3  218.41  5885.7  217.99  6029.4  220.85
  6785.7   222.2    6944  226.45  7100.2  234.34  7185.7  242.85    7244  250.18
  7250.2  253.83  7264.8  256.14  7280.2  256.29  7300.2  259.51  7345.1     262
#Mann= 6 ,-1 , 0
  3540.7     .16       0    3849     .12       0    4997     .07       0
    5003     .12       0    6944     .05       0  7280.2     .08       0
#XS Ineff= 2 , 0
         4940.34  229.77 5042.61          230.99
Permanent Ineff=
       F       F
Bank Sta=4990,5010.1
XS Rating Curve= 0 ,0
Exp/Cntr=0.3,0.1

Type RM Length L Ch R = 1 ,604     ,291,291,291
BEGIN DESCRIPTION:
Mapping XS c99634d2
END DESCRIPTION:
XS GIS Cut Line= 4
      3790652.69     10486599.78      3789709.95     10485302.87
      3788595.37     10485313.29      3787768.16      10486946.9
#Sta/Elev= 30
  3250.5  275.36  3373.6  264.25  3410.7  265.34  3460.2  262.21  3473.5  258.39
  3517.6  254.97  3609.5  241.31  3875.4  222.51  3990.6  219.19  4842.3  219.51
  4984.2  222.94    4997   215.9  4999.8   215.4    5003   215.9  5014.2  222.11
  5064.2  220.17  5084.2  225.22  5114.2   220.4  5204.2  219.59  6170.9  216.25
  6193.2  218.53  7242.8  220.11  7429.5  225.24    7467  226.05  7524.2  233.02
  7556.7  240.21  7563.1  244.44  7607.7  252.11  7715.3  260.92  7799.6   265.5
#Mann= 6 ,-1 , 0
  3250.5     .16       0  3460.2     .12       0    4997     .07       0
    5003     .12       0  7429.5     .05       0  7715.3     .16       0
#XS Ineff= 2 , 0
         4960.23  224.28 5088.07           226.5
Permanent Ineff=
       F       F
Bank Sta=4984.2,5014.2
XS Rating Curve= 0 ,0
Exp/Cntr=0.3,0.1

Type RM Length L Ch R = 1 ,313     ,0,0,0
BEGIN DESCRIPTION:
UNT057 IN BECR 31.0
END DESCRIPTION:
XS GIS Cut Line= 5
      3790728.12     10486585.01      3789626.62     10485016.41
       3788366.2     10485000.79       3787741.2      10486011.2
       3787720.4     10486936.74
#Sta/Elev= 30
  3004.7   276.4  3242.9   263.9  3287.4  254.33  3308.3  253.17  3337.9  244.94
  3495.6  228.67    3646  221.41    3757  219.79  4988.4  219.81    4997  214.83
  4999.8  214.33    5003  214.83  5028.4  219.71  5048.4  223.56  5098.4  218.37
  5928.5  218.08  5958.5  215.82  6048.5  218.29  6259.3  215.04  6338.5  214.83
  6369.3   217.5  6722.6  215.45  6921.2  218.76  7519.1  216.43  7829.1  220.14
  7889.1  217.98  7979.2   224.4  8037.7  231.47  8106.4  243.16  8295.8  263.38
#Mann= 6 ,-1 , 0
  3004.7     .16       0    3757     .07       0    4997     .05       0
    5003     .07       0  7979.2     .05       0  8037.7     .16       0
#XS Ineff= 2 , 0
                         5052.27          224.64
Permanent Ineff=
       F       F
Bank Sta=4988.4,5028.4
XS Rating Curve= 0 ,0
Exp/Cntr=0.3,0.1

Chan Stop Cuts=-1
Use User Specified Reach Order=0
Composite Channel Slope=5