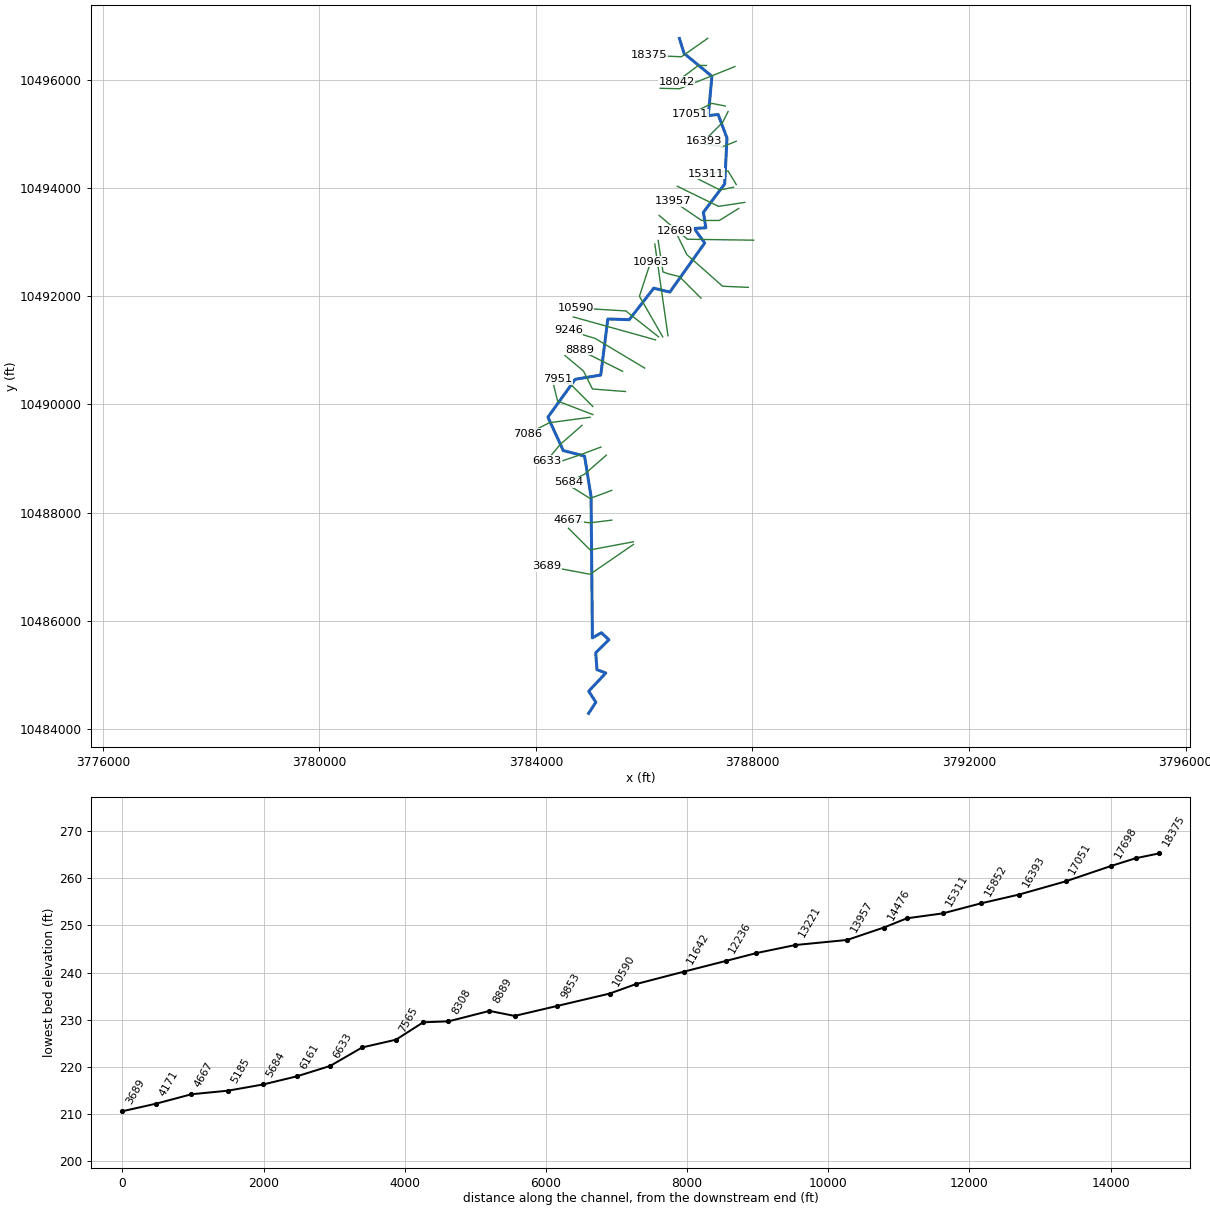
--- UNT058 IN BECR.prj (project) ---

Proj Title=UNT058 IN BECR Base Level Engineering
Current Plan=p01
Default Exp/Contr=0.3,0.1
English Units
Geom File=g01
Flow File=f01
Plan File=p01
Y Axis Title=Elevation
X Axis Title(PF)=Main Channel Distance
X Axis Title(XS)=Station
BEGIN DESCRIPTION:
UNT058 IN BECR
END DESCRIPTION:
DSS Export Rating Curves= 0
DSS Export Rating Curve Sorted= 0
DSS Export Volume Flow Curves= 0
DXF OffsetX= 0
DXF OffsetY= 0
DXF ScaleX= 1
DXF ScaleY= 10

--- UNT058 IN BECR.p01 (plan) ---

Plan Title=Multiple Run
Short Identifier=Multiple
Geom File=g01
Flow File=f01
Subcritical Flow
K Sum by GR= 0
Std Step Tol= 0.01
Critical Tol= 0.01
Num of Std Step Trials= 20
Max Error Tol= 0.3
Flow Tol Ratio= 0.001
Split Flow NTrial= 30
Split Flow Tol= 0.02
Split Flow Ratio= 0.02
Log Output Level= 0
Friction Slope Method= 1
Unsteady Friction Slope Method= 2
Unsteady Bridges Friction Slope Method= 1
Parabolic Critical Depth
Global Vel Dist=  1 , 1 , 1
Global Log Level= 0
CheckData=True
Encroach Param= -1, 0, 0, 0
BEGIN DESCRIPTION:
Multiple Run
END DESCRIPTION:

--- UNT058 IN BECR.f01 (steady flow) ---

Flow Title=Multiple
Program Version=4.10
Number of Profiles= 7
Profile Names=10-year,25-year,50-year,1pct_min,100-year,1pct_plu,500-year
River Rch & RM=UNT058 IN BECR,Reach-1         ,18375
     640     874    1070     963    1302    1761    1936
River Rch & RM=UNT058 IN BECR,Reach-1         ,18042
     778    1068    1311    1182    1599    2162    2386
River Rch & RM=UNT058 IN BECR,Reach-1         ,10590
     956    1324    1635    1482    2004    2710    3022
River Rch & RM=UNT058 IN BECR,Reach-1         ,9853
     956    1324    1635    1482    2004    2710    3022
River Rch & RM=UNT058 IN BECR,Reach-1         ,7086
    1456    2053    2564    2347    3175    4293    4886
Boundary for River Rch & Prof#=UNT058 IN BECR,Reach-1         , 1
Up Type= 0
Dn Type= 3
Dn Slope=0.002
Boundary for River Rch & Prof#=UNT058 IN BECR,Reach-1         , 2
Up Type= 0
Dn Type= 3
Dn Slope=0.002
Boundary for River Rch & Prof#=UNT058 IN BECR,Reach-1         , 3
Up Type= 0
Dn Type= 3
Dn Slope=0.002
Boundary for River Rch & Prof#=UNT058 IN BECR,Reach-1         , 4
Up Type= 0
Dn Type= 3
Dn Slope=0.002
Boundary for River Rch & Prof#=UNT058 IN BECR,Reach-1         , 5
Up Type= 0
Dn Type= 3
Dn Slope=0.002
Boundary for River Rch & Prof#=UNT058 IN BECR,Reach-1         , 6
Up Type= 0
Dn Type= 3
Dn Slope=0.002
Boundary for River Rch & Prof#=UNT058 IN BECR,Reach-1         , 7
Up Type= 0
Dn Type= 3
Dn Slope=0.002
DSS Import GetInterval= 0
DSS Import GetPeak= 0
DSS Import FillOption= 0

--- UNT058 IN BECR.g01 (geometry) ---

Geom Title=Existing Conditions
Program Version=4.10

River Reach=UNT058 IN BECR  ,Reach-1
Reach XY= 30
      3786649.61     10496760.19      3786736.25       10496483.
      3787250.25       10496060.      3787183.75       10495334.
      3787365.75       10495354.      3787528.75       10494920.
      3787486.25       10494072.       3787093.5       10493548.
      3787137.75       10493261.      3786922.75       10493249.
      3787117.25       10492980.      3786472.75       10492073.
      3786176.75       10492146.       3785722.5       10491563.
      3785327.25       10491577.       3785196.5       10490541.
        3784725.       10490462.        3784221.       10489763.
       3784504.5       10489145.       3784897.5       10489044.
      3785017.75       10488295.      3785042.25       10485685.
      3785208.75       10485780.      3785347.25       10485650.
       3785103.5       10485410.        3785127.       10485096.
      3785289.75       10485036.      3784974.25       10484700.
       3785106.5       10484496.        3784972.       10484290.

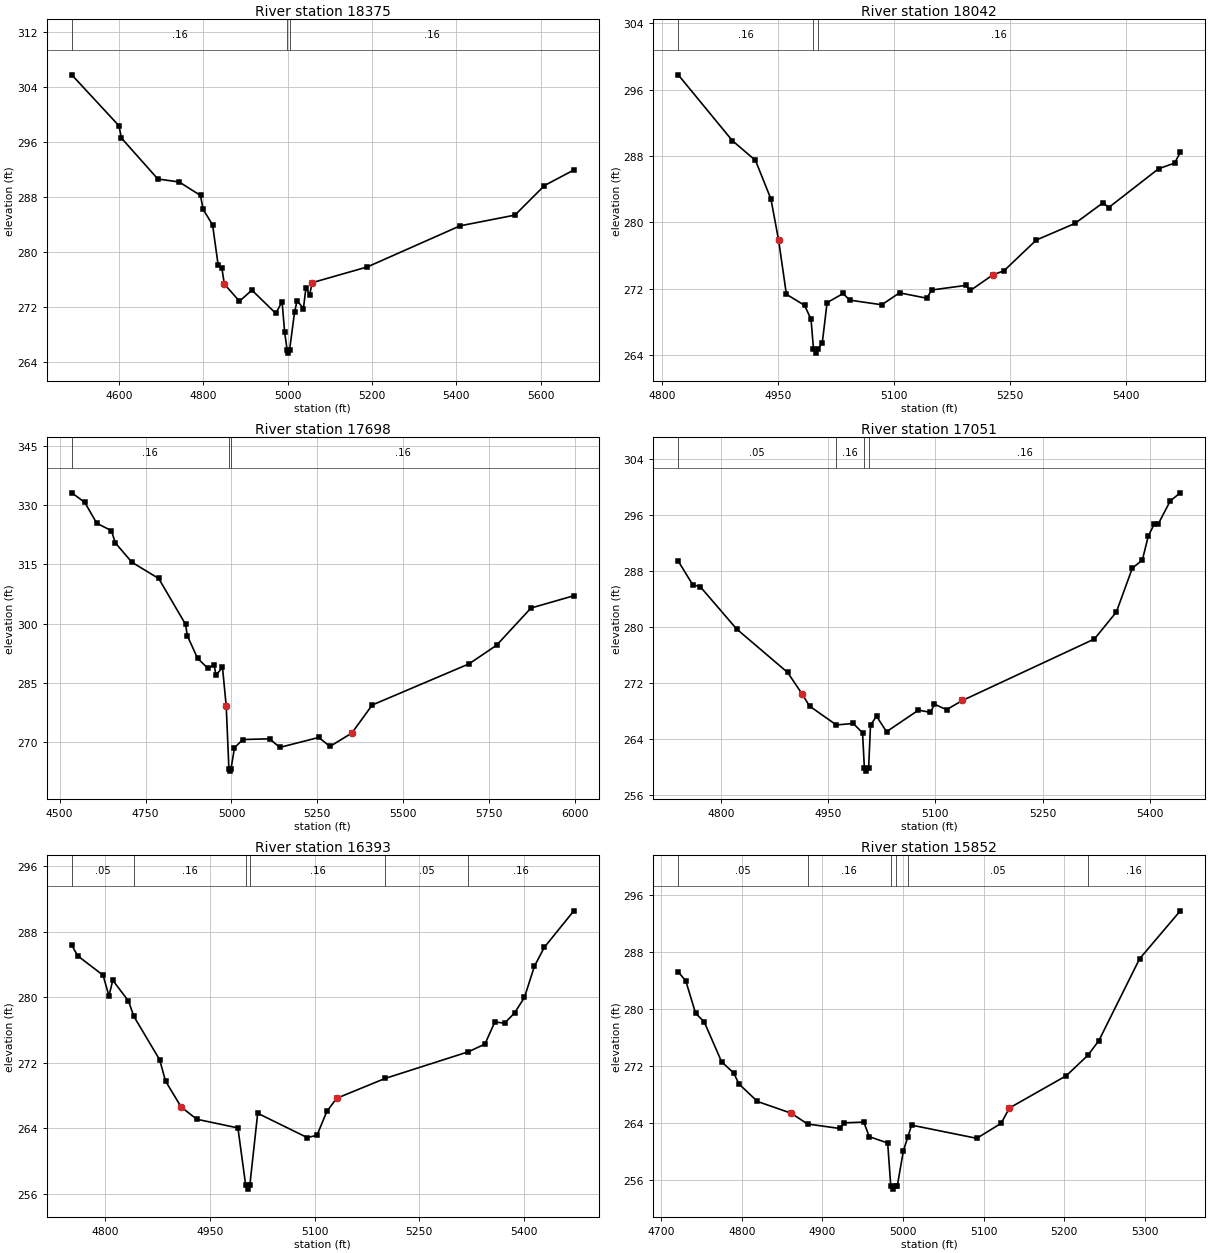
Type RM Length L Ch R = 1 ,18375   ,333,333,333
BEGIN DESCRIPTION:
UNT058 IN BECR 32.0
END DESCRIPTION:
XS GIS Cut Line= 3
       3787173.3     10496761.34      3786687.18     10496421.06
      3786089.96     10496445.36
#Sta/Elev= 30
  4487.9  305.75  4599.7  298.35  4605.8  296.55  4692.1   290.6  4742.7  290.17
  4793.3  288.21  4799.4   286.2    4822  283.92  4835.1  278.11  4843.8  277.71
  4849.9  275.32  4885.7  272.83  4915.3  274.44    4972  271.05  4986.8  272.78
  4992.9  268.33  4998.7  265.78  5001.4  265.28  5004.7  265.78  5016.5  271.27
  5022.6  272.93  5037.4  271.74  5043.5   274.8  5052.2  273.75  5058.3  275.53
  5188.9  277.81  5409.1  283.79  5539.2  285.35  5609.3  289.65    5679  291.91
#Mann= 3 ,-1 , 0
  4487.9     .16       0  4998.7     .07       0  5004.7     .16       0
Bank Sta=4849.9,5058.3
XS Rating Curve= 0 ,0
Exp/Cntr=0.3,0.1

Type RM Length L Ch R = 1 ,18042   ,344,344,344
BEGIN DESCRIPTION:
UNT058 IN BECR 31.0
END DESCRIPTION:
XS GIS Cut Line= 3
      3787149.61     10496260.19      3786999.61     10496260.19
      3786599.61     10495960.19
#Sta/Elev= 30
  4820.7   297.8  4890.7  289.87  4920.7  287.48  4940.7  282.83  4950.7  277.83
  4960.7  271.35  4984.2  270.01  4992.6  268.35  4995.8  264.75  4998.6  264.25
  5001.8  264.75  5007.2  265.51  5013.4  270.33  5034.2  271.44  5042.6  270.64
  5084.2  270.08  5107.2  271.52  5142.6  270.87  5148.8  271.86  5192.6  272.41
  5198.8   271.8    5228  273.68  5242.6  274.19  5284.2  277.88  5334.2  279.88
  5370.7  282.38    5378   281.8  5442.6  286.48  5463.4  287.16  5470.7  288.47
#Mann= 3 ,-1 , 0
  4820.7     .16       0  4995.8     .07       0  5001.8     .16       0
Bank Sta=4950.7,5228
XS Rating Curve= 0 ,0
Exp/Cntr=0.3,0.1

Type RM Length L Ch R = 1 ,17698   ,647,647,647
BEGIN DESCRIPTION:
UNT058 IN BECR 30.0
END DESCRIPTION:
XS GIS Cut Line= 3
      3787676.75      10496240.5      3786655.93     10495830.78
      3786294.87     10495837.72
#Sta/Elev= 30
  4535.3  333.16  4573.2  330.73  4608.1  325.44  4650.7  323.57  4661.9  320.49
  4710.3  315.56  4788.3  311.45  4866.3  299.84  4871.7  296.93  4901.3  291.23
  4930.9  288.73  4949.7  289.45  4955.1  286.95  4973.9  288.94  4984.8  279.07
  4992.6  263.13  4995.3  262.63  4998.6  263.13  5008.8  268.57    5033  270.64
    5111  270.81  5140.6  268.64  5254.2  271.17  5286.5  268.88  5350.4  272.28
  5409.5  279.38  5691.6  289.82  5771.6  294.54  5871.6  303.96  5996.4  307.08
#Mann= 3 ,-1 , 0
  4535.3     .16       0  4992.6     .07       0  4998.6     .16       0
Bank Sta=4984.8,5350.4
XS Rating Curve= 0 ,0
Exp/Cntr=0.3,0.1

Type RM Length L Ch R = 1 ,17051   ,658,658,658
BEGIN DESCRIPTION:
UNT058 IN BECR 29.0
END DESCRIPTION:
XS GIS Cut Line= 3
      3787499.62     10495510.19      3787249.61     10495560.19
      3786849.59     10495360.18
#Sta/Elev= 30
  4740.4  289.41  4760.8     286    4771  285.77    4822   279.7  4893.4  273.47
  4913.8  270.37    4924  268.66  4961.5  265.96  4985.2  266.17  4998.2  264.83
  5000.7  259.85  5003.5  259.35  5006.7  259.85  5009.3  265.91  5017.7  267.22
  5031.7  264.99  5076.4  268.08  5093.2  267.76  5098.8  268.93  5115.6  268.15
  5137.9  269.46  5322.4  278.26  5353.1  282.11  5375.5   288.4  5389.5  289.56
  5397.9  293.02  5406.2  294.71  5411.8  294.74  5428.6  298.03  5442.6  299.18
#Mann= 4 ,-1 , 0
  4740.4     .05       0  4961.5     .16       0  5000.7     .07       0
  5006.7     .16       0
Bank Sta=4913.8,5137.9
XS Rating Curve= 0 ,0
Exp/Cntr=0.3,0.1

Type RM Length L Ch R = 1 ,16393   ,541,541,541
BEGIN DESCRIPTION:
UNT058 IN BECR 28.0
END DESCRIPTION:
XS GIS Cut Line= 3
      3787549.63     10495410.23      3787449.61     10495210.19
      3787099.63     10494860.21
#Sta/Elev= 30
  4752.5  286.34  4760.9  285.04  4797.3  282.67  4805.7  280.15  4811.2  282.05
  4833.6  279.53  4841.4  277.64  4878.3  272.35  4886.7  269.75  4909.1  266.58
  4931.4  265.09  4990.3  264.03  5001.4  257.06  5004.2  256.56  5007.4  257.06
  5018.6  265.82  5089.3  262.86  5103.4  263.12  5117.6  266.05  5131.7  267.65
  5200.9  270.07    5320  273.32  5343.8  274.26    5358  276.96  5372.1  276.82
  5386.3  278.07  5400.4  279.96  5414.6  283.75  5428.7  286.06  5471.1  290.53
#Mann= 6 ,-1 , 0
  4752.5     .05       0  4841.4     .16       0  5001.4     .07       0
  5007.4     .16       0  5200.9     .05       0    5320     .16       0
Bank Sta=4909.1,5131.7
XS Rating Curve= 0 ,0
Exp/Cntr=0.3,0.1

Type RM Length L Ch R = 1 ,15852   ,541,541,541
BEGIN DESCRIPTION:
UNT058 IN BECR 27.0
END DESCRIPTION:
XS GIS Cut Line= 3
       3787699.6     10494860.18      3787449.61     10494760.19
      3787099.61     10494810.19
#Sta/Elev= 30
  4721.2  285.19  4730.6   283.9  4742.7  279.39  4753.5  278.14    4775  272.56
  4789.9     271  4796.6  269.44  4819.5  266.99  4861.2  265.35  4881.6  263.83
  4921.8   263.2  4927.2  263.99  4951.4   264.1  4958.1  262.06    4981  261.16
  4984.8  255.19  4987.5  254.69  4990.8  255.19    4993  255.19  5000.5  260.08
  5005.9  261.98  5010.7  263.67  5091.5  261.82  5121.8  263.93  5131.9  266.07
  5202.6  270.61  5229.4  273.48    5243  275.54  5293.5  287.02    5344  293.75
#Mann= 6 ,-1 , 0
  4721.2     .05       0  4881.6     .16       0  4984.8     .07       0
  4990.8     .16       0  5005.9     .05       0  5229.4     .16       0
Bank Sta=4861.2,5131.9
XS Rating Curve= 0 ,0
Exp/Cntr=0.3,0.1

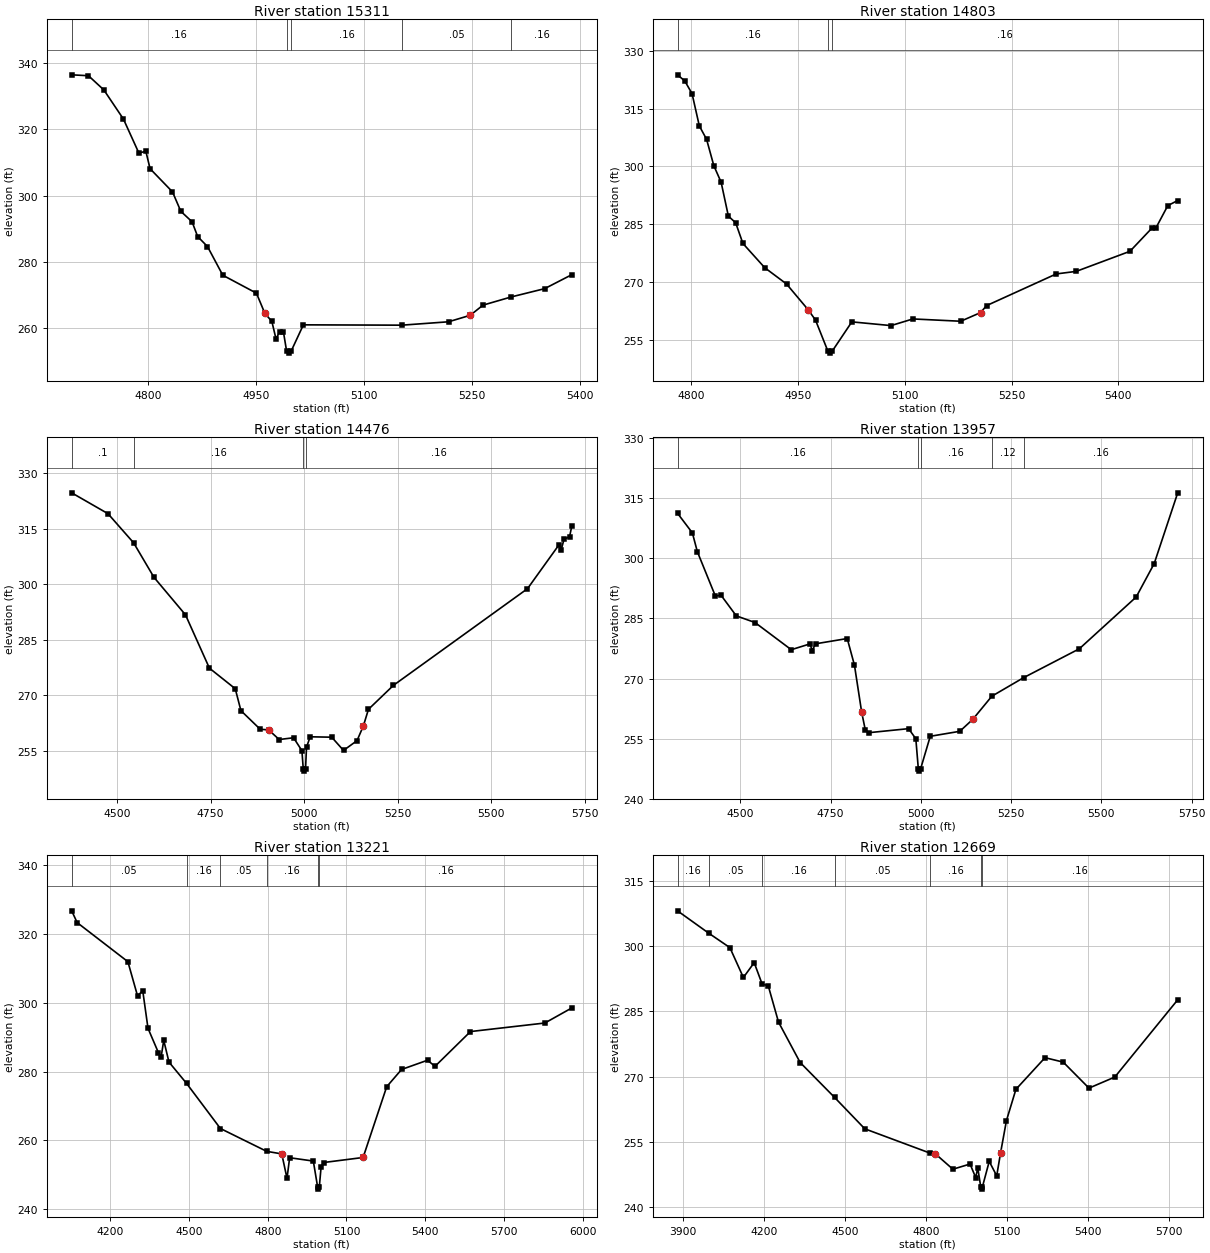
Type RM Length L Ch R = 1 ,15311   ,508,508,508
BEGIN DESCRIPTION:
UNT058 IN BECR 26.0
END DESCRIPTION:
XS GIS Cut Line= 3
      3787699.62     10494060.17      3787549.61     10494310.19
      3787149.59     10494260.19
#Sta/Elev= 30
  4693.9  336.38  4717.2  336.11  4738.6  331.83  4765.8  323.05  4787.2  312.83
  4796.9  313.35  4802.8   308.1  4833.9  301.13  4845.5  295.27  4861.1  292.12
  4868.9  287.66  4882.5  284.67  4903.8  276.02  4950.5  270.62  4962.1  264.58
  4971.9  262.11  4977.7  256.83  4982.6  258.94    4988  258.94  4992.5  253.06
  4995.3  252.56  4998.5  253.06  5015.7  261.08  5152.4  260.98  5217.3     262
  5247.5  263.96  5265.1  267.01  5304.5  269.49  5350.8  271.98  5388.6   276.2
#Mann= 5 ,-1 , 0
  4693.9     .16       0  4992.5     .07       0  4998.5     .16       0
  5152.4     .05       0  5304.5     .16       0
Bank Sta=4962.1,5247.5
XS Rating Curve= 0 ,0
Exp/Cntr=0.3,0.1

Type RM Length L Ch R = 1 ,14803   ,327,327,327
BEGIN DESCRIPTION:
UNT058 IN BECR 25.0
END DESCRIPTION:
XS GIS Cut Line= 3
      3787649.59     10494010.18      3787399.61     10493960.19
      3786999.65     10494160.17
#Sta/Elev= 30
  4781.2   323.8  4791.4  322.21  4801.6  318.91  4811.8  310.54    4822  307.05
  4832.2  300.18  4842.4  295.91  4852.6   287.1  4862.8  285.38    4873     280
  4903.6  273.71  4934.2  269.48  4964.7  262.76  4974.9   260.1  4992.3  252.02
  4995.1  251.52  4998.3  252.02  5025.9  259.64  5080.9  258.67  5111.6   260.4
  5178.7   259.8  5206.6  262.05    5215  263.86  5312.8  272.09  5340.8  272.75
  5416.3  277.97    5447  283.97  5452.6     284  5469.4  289.83  5483.3  291.16
#Mann= 3 ,-1 , 0
  4781.2     .16       0  4992.3     .07       0  4998.3     .16       0
Bank Sta=4964.7,5206.6
XS Rating Curve= 0 ,0
Exp/Cntr=0.3,0.1

Type RM Length L Ch R = 1 ,14476   ,519,519,519
BEGIN DESCRIPTION:
UNT058 IN BECR 24.0
END DESCRIPTION:
XS GIS Cut Line= 3
      3787857.32     10493730.09      3787371.21     10493657.17
      3786610.77     10494028.71
#Sta/Elev= 30
  4378.3   324.7  4475.4  319.07    4544   311.2  4598.4  301.89  4682.7  291.76
  4746.7  277.36  4815.8  271.81    4831  265.89  4882.7  260.85    4905  260.71
  4933.3  258.09  4971.8  258.57  4994.1  255.09  4997.8  250.06  5000.6  249.56
  5003.8  250.06  5006.4  256.04  5016.3  258.83  5073.9  258.72  5105.4  255.15
  5141.5  257.79  5158.5  261.76  5172.1  266.25  5238.9  272.72  5597.5  298.82
    5682   310.7  5687.5  309.29  5695.2  312.15  5710.1  312.89  5716.2  315.83
#Mann= 4 ,-1 , 0
  4378.3      .1       0    4544     .16       0  4997.8     .07       0
  5003.8     .16       0
Bank Sta=4905,5158.5
XS Rating Curve= 0 ,0
Exp/Cntr=0.3,0.1

Type RM Length L Ch R = 1 ,13957   ,736,736,736
BEGIN DESCRIPTION:
UNT058 IN BECR 23.0
END DESCRIPTION:
XS GIS Cut Line= 4
      3787746.24     10493618.99      3787388.57     10493396.75
      3787058.71     10493396.75       3786534.5     10493754.32
#Sta/Elev= 30
    4326  311.17  4367.2  306.27  4380.9  301.61  4430.9  290.53  4446.3  290.78
  4488.8  285.61  4540.7  283.95  4641.1  277.18  4693.1  278.63  4698.9  276.94
  4708.4  278.65  4796.1  279.96  4816.1  273.33  4836.1  261.61  4846.1   257.2
  4856.1  256.51  4966.1  257.51  4986.1  254.99  4993.1  247.43  4995.8  246.93
  4999.1  247.43  5026.1  255.61  5107.9  256.85  5143.8  259.82  5196.6  265.59
  5284.4   270.2    5439  277.41  5596.4   290.3  5646.4  298.64  5711.5  316.26
#Mann= 5 ,-1 , 0
    4326     .16       0  4993.1     .07       0  4999.1     .16       0
  5196.6     .12       0  5284.4     .16       0
Bank Sta=4836.1,5143.8
XS Rating Curve= 0 ,0
Exp/Cntr=0.3,0.1

Type RM Length L Ch R = 1 ,13221   ,552,552,552
BEGIN DESCRIPTION:
UNT058 IN BECR 22.0
END DESCRIPTION:
XS GIS Cut Line= 3
      3788020.55     10493032.17      3786798.29     10493049.53
      3786274.27     10493490.26
#Sta/Elev= 30
  4052.2  326.67  4073.1  323.25  4266.5   311.9  4303.2     302  4323.2  303.45
  4343.2  292.55  4383.2  285.43  4393.2  284.21  4403.2  289.05  4423.2  282.74
  4490.2  276.56  4619.3  263.45  4795.8  256.82  4853.2  256.08  4873.2  248.97
  4883.2  254.97  4973.5     254  4990.2  246.35    4993  245.85  4996.2  246.35
  5003.2  252.32  5013.2  253.58  5163.3  255.04  5253.3  275.59    5310   280.6
  5408.9  283.28  5437.5  281.51  5572.7  291.61  5856.3  294.09  5959.3  298.48
#Mann= 6 ,-1 , 0
  4052.2     .05       0  4490.2     .16       0  4619.3     .05       0
  4795.8     .16       0  4990.2     .07       0  4996.2     .16       0
Bank Sta=4853.2,5163.3
XS Rating Curve= 0 ,0
Exp/Cntr=0.3,0.1

Type RM Length L Ch R = 1 ,12669   ,433,433,433
BEGIN DESCRIPTION:
UNT058 IN BECR 21.0
END DESCRIPTION:
XS GIS Cut Line= 4
      3787923.28     10492160.64       3787447.6     10492181.48
      3786787.88     10492764.81      3786569.14     10493209.23
#Sta/Elev= 30
    3881  308.14  3996.5     303  4074.9  299.68  4124.9  292.81  4164.9  296.22
  4194.7  291.24  4216.7  290.96    4255  282.55  4335.1  273.26  4462.7  265.22
  4574.4  258.01  4816.2  252.42  4836.2  252.23  4900.6  248.72  4964.2  249.91
  4985.1   246.8  4992.7  249.03  5003.9  244.64  5006.6  244.14  5009.9  244.64
  5035.2  250.52  5062.9  247.19  5077.1  252.45  5098.9  259.89    5134  267.09
  5241.7  274.37  5309.1  273.35  5404.5  267.37  5500.1  269.91  5733.1  287.68
#Mann= 7 ,-1 , 0
    3881     .16       0  3996.5     .05       0  4194.7     .16       0
  4462.7     .05       0  4816.2     .16       0  5003.9     .07       0
  5009.9     .16       0
Bank Sta=4836.2,5077.1
XS Rating Curve= 0 ,0
Exp/Cntr=0.3,0.1

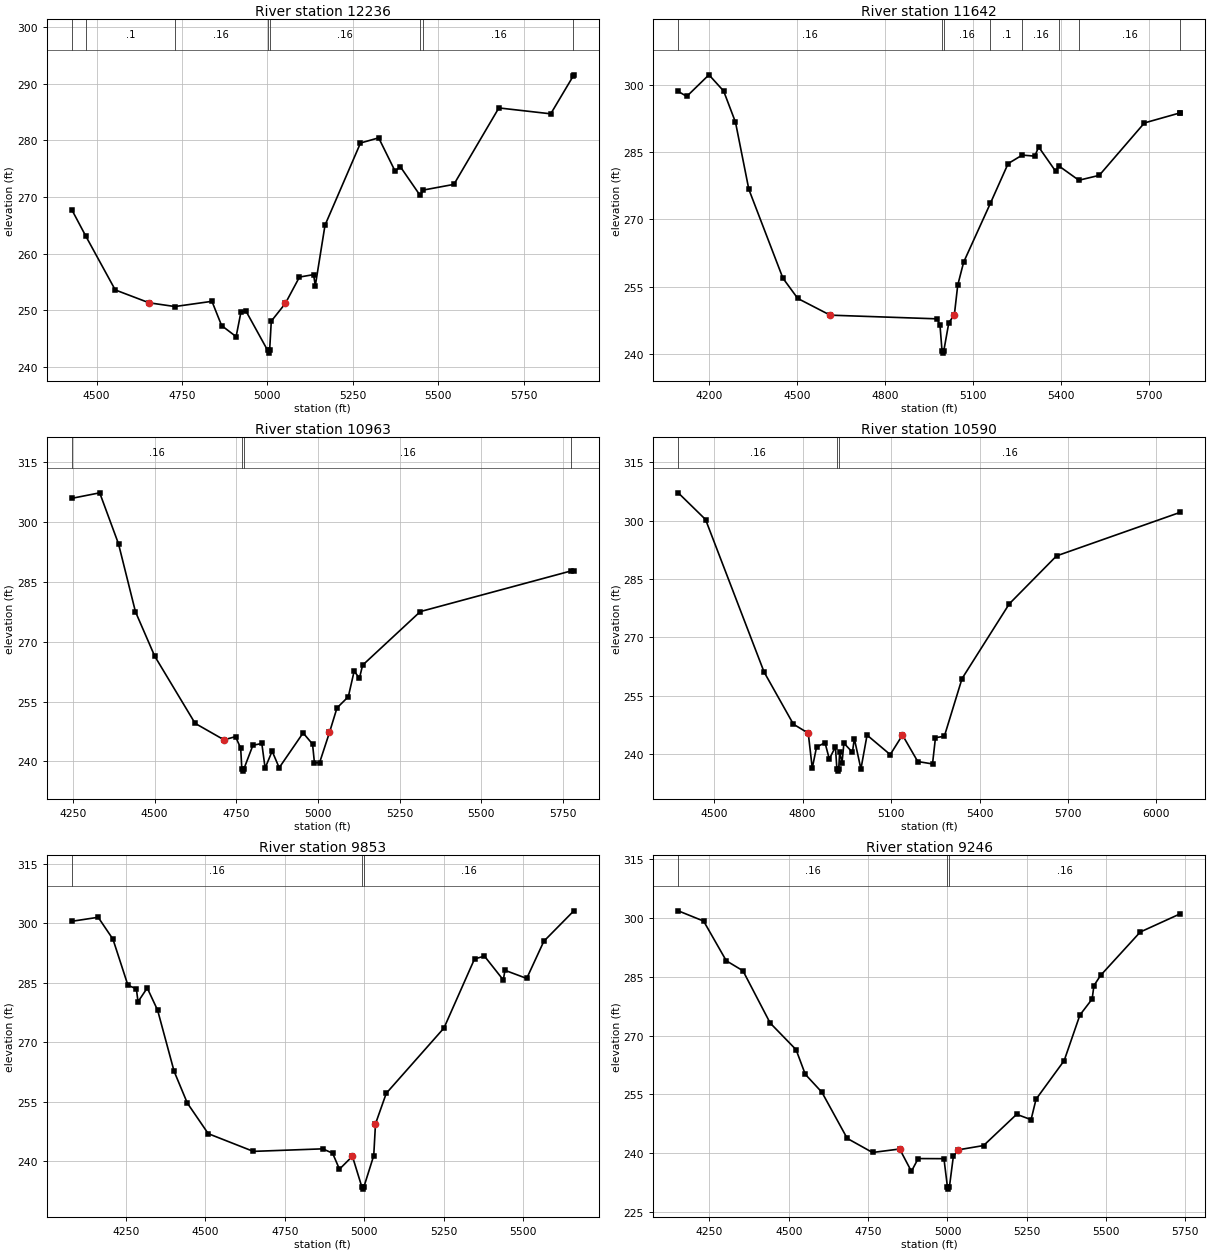
Type RM Length L Ch R = 1 ,12236   ,594,594,594
BEGIN DESCRIPTION:
UNT058 IN BECR 20.0
END DESCRIPTION:
XS GIS Cut Line= 5
      3787049.58     10491960.22      3786649.61     10492360.19
      3786449.61     10492410.19       3786346.9     10492445.36
      3786256.89     10493026.98
#Sta/Elev= 30
  4427.6  267.78  4468.4  263.14  4554.8  253.62  4653.8  251.35  4729.3  250.69
  4837.7  251.61    4866  247.33  4908.4  245.38  4922.5  249.69  4936.7  249.95
  5000.5  242.97  5003.3  242.47  5006.5  242.97  5011.3  248.11  5052.5  251.24
  5093.7  255.89    5135  256.32  5140.1  254.36  5168.5  265.04  5272.3  279.54
  5325.5  280.45  5373.6  274.57  5388.5  275.39  5446.8  270.29    5456  271.24
  5545.6  272.24  5677.1  285.73  5828.9  284.69  5895.4  291.43  5896.5  291.57
#Mann= 8 ,-1 , 0
  4427.6     .16       0  4468.4      .1       0  4729.3     .16       0
  5000.5     .07       0  5006.5     .16       0  5446.8      .1       0
    5456     .16       0  5895.4     .05       0
Bank Sta=4653.8,5052.5
XS Rating Curve= 0 ,0
Exp/Cntr=0.3,0.1

Type RM Length L Ch R = 1 ,11642   ,679,679,679
BEGIN DESCRIPTION:
UNT058 IN BECR 19.0
END DESCRIPTION:
XS GIS Cut Line= 2
       3786438.8     10491266.92      3786195.74     10492961.38
#Sta/Elev= 30
  4094.1  298.52  4123.1   297.4  4198.8  302.21  4248.9   298.6  4289.3  291.65
  4334.8   276.7    4451   256.9  4501.5  252.39  4612.1  248.66  4976.3  247.84
  4986.4  246.52  4993.5   240.7  4996.3   240.2  4999.5   240.7  5016.7     247
  5035.5  248.72    5047  255.33  5067.2  260.47  5158.4  273.59  5218.8  282.43
    5267  284.33  5309.7  284.09  5322.9  286.14  5380.4  280.76  5392.2  281.89
    5460  278.72  5529.5  279.81  5683.5  291.49  5805.5  293.74  5805.9  293.74
#Mann= 8 ,-1 , 0
  4094.1     .16       0  4993.5     .07       0  4999.5     .16       0
  5158.4      .1       0    5267     .16       0  5392.2      .1       0
    5460     .16       0  5805.5     .05       0
Bank Sta=4612.1,5035.5
XS Rating Curve= 0 ,0
Exp/Cntr=0.3,0.1

Type RM Length L Ch R = 1 ,10963   ,373,373,373
BEGIN DESCRIPTION:
UNT058 IN BECR 18.0
END DESCRIPTION:
XS GIS Cut Line= 3
      3786341.58     10491246.06      3785911.02     10491996.06
      3786119.36     10492634.95
#Sta/Elev= 30
  4246.6  305.89  4332.1  307.27  4389.7  294.48  4441.5  277.49  4500.4  266.37
  4624.1  249.53  4712.6   245.4  4747.8   246.2  4763.6  243.32  4767.2  238.06
    4770  237.56  4773.2  238.06    4801  244.03  4828.3  244.49  4838.4  238.32
  4859.9  242.56  4881.5  238.41  4954.7  247.13  4983.6  244.33  4989.4  239.63
  5005.2  239.69  5035.4  247.24  5058.4  253.39  5093.1   256.2  5110.9  262.59
  5127.2  260.86  5136.8   264.1  5313.4  277.52  5776.1  287.73  5783.4   287.7
#Mann= 4 ,-1 , 0
  4246.6     .16       0  4767.2     .07       0  4773.2     .16       0
  5776.1      .1       0
Bank Sta=4712.6,5035.4
XS Rating Curve= 0 ,0
Exp/Cntr=0.3,0.1

Type RM Length L Ch R = 1 ,10590   ,737,737,737
BEGIN DESCRIPTION:
UNT058 IN BECR 17.0
END DESCRIPTION:
XS GIS Cut Line= 3
      3786265.22     10491246.04      3785661.02     10491725.23
      3784730.43     10491780.78
#Sta/Elev= 30
  4377.8  307.16  4470.5  300.29  4669.1  261.04  4768.5  247.63  4818.9  245.32
  4832.5   236.3    4847  241.74  4875.8  242.86  4890.3  238.67  4911.1  241.78
  4916.1  236.05  4918.9  235.55  4922.1  236.05  4925.5  240.36  4933.5  237.75
  4939.9  242.75  4968.8  240.39  4975.2  243.93  4997.6  236.09  5018.4  244.82
    5097   239.8  5138.6  244.83  5190.4  238.02  5240.5   237.4  5250.5  244.16
  5280.6  244.51  5340.7  259.37    5501   278.6  5661.3  290.93  6081.2  302.15
#Mann= 3 ,-1 , 0
  4377.8     .16       0  4916.1     .07       0  4922.1     .16       0
Bank Sta=4818.9,5138.6
XS Rating Curve= 0 ,0
Exp/Cntr=0.3,0.1

Type RM Length L Ch R = 1 ,9853    ,607,607,607
BEGIN DESCRIPTION:
UNT058 IN BECR 16.0
END DESCRIPTION:
XS GIS Cut Line= 2
      3786209.61     10491190.51       3784688.8     10491614.11
#Sta/Elev= 30
  4080.1   300.5  4163.1  301.51  4209.6  295.99  4256.6  284.38  4283.2  283.46
  4288.4  280.21  4317.4  283.68    4350  278.08  4401.9  262.66  4443.4  254.66
  4509.2  246.94    4651  242.47    4869  243.11  4900.2  242.02  4921.8  237.98
  4962.5  241.24  4992.4  233.45  4995.1  232.95  4998.4  233.45  5029.6  241.41
  5035.1  249.41    5069  257.12  5250.4  273.58  5346.5     291  5377.7  291.72
    5437   285.7  5442.2  288.14  5510.6  286.09  5564.5  295.47  5658.8  303.14
#Mann= 3 ,-1 , 0
  4080.1     .16       0  4992.4     .07       0  4998.4     .16       0
Bank Sta=4962.5,5035.1
XS Rating Curve= 0 ,0
Exp/Cntr=0.3,0.1

Type RM Length L Ch R = 1 ,9246    ,357,357,357
BEGIN DESCRIPTION:
UNT058 IN BECR 15.0
END DESCRIPTION:
XS GIS Cut Line= 3
      3786008.28     10490669.65      3785091.58     10491218.28
      3784598.53     10491364.11
#Sta/Elev= 30
  4151.5  301.84  4231.5  299.22  4302.9   289.1  4355.5  286.54  4441.3   273.2
  4522.9  266.41  4551.9  260.13  4604.4  255.53  4684.1  243.77  4763.9  240.17
  4849.4  241.06  4886.4  235.36  4907.8  238.62    4989  238.59  5000.1  231.32
  5002.8  230.82  5006.1  231.32  5018.6  239.16  5034.2  240.85  5113.9  241.94
  5218.1  249.91  5263.6  248.55  5279.3  253.77  5367.9  263.61  5417.6  275.26
  5456.1  279.33  5461.7  282.75  5482.6  285.35  5607.7  296.43    5734  301.09
#Mann= 3 ,-1 , 0
  4151.5     .16       0  5000.1     .07       0  5006.1     .16       0
Bank Sta=4849.4,5034.2
XS Rating Curve= 0 ,0
Exp/Cntr=0.3,0.1

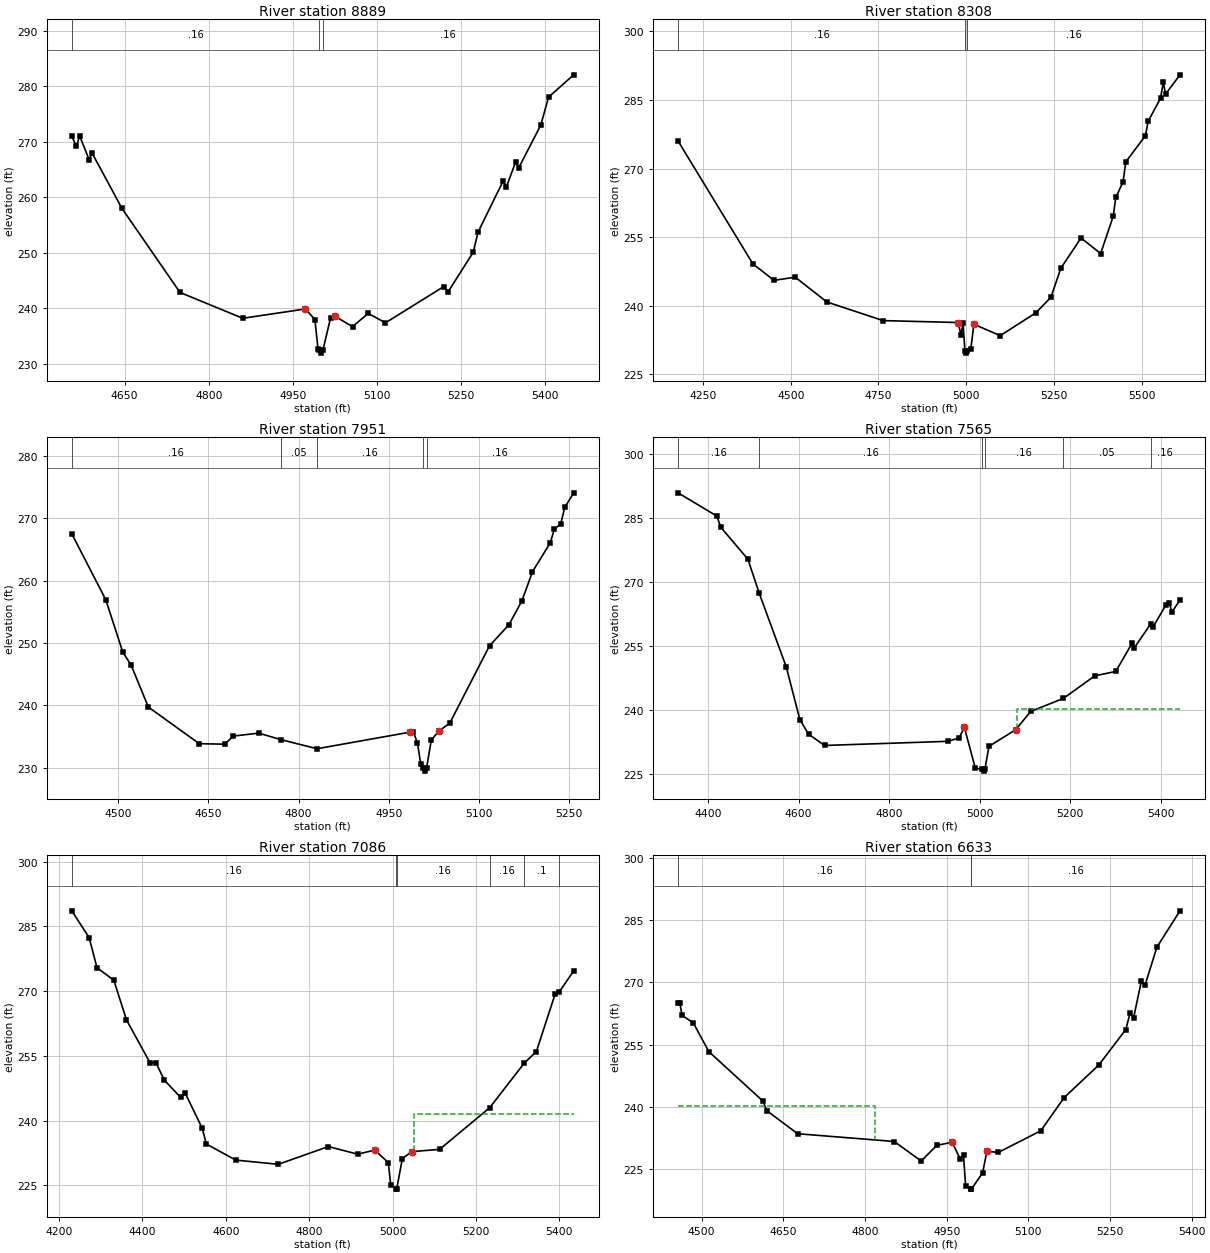
Type RM Length L Ch R = 1 ,8889    ,581,581,581
BEGIN DESCRIPTION:
UNT058 IN BECR 14.0
END DESCRIPTION:
XS GIS Cut Line= 3
      3785599.64     10490610.17      3785199.61     10490810.19
      3784799.58      10491010.2
#Sta/Elev= 30
  4555.9  271.02  4564.3  269.17  4569.9   271.1  4586.7  266.82  4592.3  267.94
  4645.4  257.99  4748.8  242.83  4860.6  238.17  4972.4  239.85  4989.2  237.94
  4994.8  232.62  4997.4  232.38  5000.1  231.88  5003.4  232.38  5017.1  238.22
  5025.5  238.49  5056.3  236.66  5084.2  239.05    5115  237.35  5218.4  243.86
  5226.8  242.97  5271.5   250.1  5279.9   253.7  5324.6  262.92  5330.2   261.8
  5346.9  266.36  5352.5  265.32  5391.7  273.02  5405.6  278.07  5450.4   282.1
#Mann= 3 ,-1 , 0
  4555.9     .16       0  4997.4     .07       0  5003.4     .16       0
Bank Sta=4972.4,5025.5
XS Rating Curve= 0 ,0
Exp/Cntr=0.3,0.1

Type RM Length L Ch R = 1 ,8308    ,357,357,357
BEGIN DESCRIPTION:
UNT058 IN BECR 13.0
END DESCRIPTION:
XS GIS Cut Line= 4
      3785652.28      10490236.2      3785042.94     10490283.07
      3784876.27     10490616.41      3784533.58     10490901.98
#Sta/Elev= 30
  4179.1  276.05  4392.4  249.17  4452.6  245.58  4512.8  246.28    4603  240.85
  4763.5  236.78  4977.1  236.36  4985.2  233.56  4990.8  236.32  4996.4  230.17
  4999.2  229.67  5002.4  230.17  5013.2  230.61  5021.8  235.98    5097   233.5
  5198.2  238.47  5241.2  241.86  5269.8  248.26  5327.1  254.85    5383  251.44
  5418.9  259.62    5426  263.71  5446.8  267.09  5454.6  271.48  5510.6  277.21
  5518.4  280.39  5553.6  285.38  5561.4   288.9  5567.9   286.3    5609  290.52
#Mann= 3 ,-1 , 0
  4179.1     .16       0  4996.4     .07       0  5002.4     .16       0
Bank Sta=4977.1,5021.8
XS Rating Curve= 0 ,0
Exp/Cntr=0.3,0.1

Type RM Length L Ch R = 1 ,7951    ,386,386,386
BEGIN DESCRIPTION:
UNT058 IN BECR 12.0
END DESCRIPTION:
XS GIS Cut Line= 3
      3785049.59      10489960.2      3784649.61     10490360.19
      3784399.63     10490460.18
#Sta/Elev= 30
  4422.8  267.53  4479.3  256.97  4507.6  248.57  4521.8  246.41  4550.1  239.75
  4634.9  233.87  4677.3  233.79  4691.5  235.09  4733.9  235.56  4770.3  234.53
  4830.8  233.06  4984.9  235.71  4991.2  235.71  4997.9  233.97  5003.3  230.62
    5007  229.97  5009.8  229.47    5013  229.97  5020.8  234.43  5032.9  235.85
  5051.7  237.18  5117.7  249.57    5150  252.94  5171.6  256.77  5189.1  261.43
  5218.7  266.07  5225.4  268.22  5236.2  269.15  5242.9  271.75  5257.7  274.09
#Mann= 5 ,-1 , 0
  4422.8     .16       0  4770.3     .05       0  4830.8     .16       0
    5007     .07       0    5013     .16       0
Bank Sta=4984.9,5032.9
XS Rating Curve= 0 ,0
Exp/Cntr=0.3,0.1

Type RM Length L Ch R = 1 ,7565    ,479,479,479
BEGIN DESCRIPTION:
UNT058 IN BECR 11.0
END DESCRIPTION:
XS GIS Cut Line= 3
      3785049.64     10489810.18      3784399.61     10490060.19
       3784299.6     10490460.22
#Sta/Elev= 30
  4333.6  290.85  4419.3  285.41  4427.9  282.81  4487.9  275.33  4512.6  267.46
  4572.6  250.16  4602.6  237.85  4621.8  234.43  4657.2  231.78  4930.4  232.75
  4955.1  233.57  4965.8  236.12  4990.4  226.41  5005.6  226.28  5008.4  225.78
  5011.6  226.28  5020.4  231.57    5080   235.5  5112.5  239.74  5184.7  242.77
  5254.2  248.06  5300.6  249.09  5336.7  255.72  5341.9  254.66  5377.5  260.18
  5383.1   259.5  5411.4  264.64  5419.2   265.2  5424.3  262.91  5442.4   265.8
#Mann= 6 ,-1 , 0
  4333.6     .16       0  4512.6     .16       0  5005.6     .07       0
  5011.6     .16       0  5184.7     .05       0  5377.5     .16       0
#XS Ineff= 2 , 0
                         5081.36          240.38
Permanent Ineff=
       F       F
Bank Sta=4965.8,5080
XS Rating Curve= 0 ,0
Exp/Cntr=0.3,0.1

Type RM Length L Ch R = 1 ,7086    ,453,453,453
BEGIN DESCRIPTION:
UNT058 IN BECR 10.0
END DESCRIPTION:
XS GIS Cut Line= 3
      3784999.61     10489760.19      3784249.61     10489660.19
      3783849.57     10489460.17
#Sta/Elev= 30
  4230.6  288.59  4272.2  282.41  4291.1  275.42  4331.5  272.52  4361.8  263.34
  4418.5  253.37  4432.4  253.43  4452.6  249.39  4491.6  245.39    4503   246.3
  4543.3  238.29  4553.4  234.58  4624.1  230.86  4726.2  229.89    4846     234
  4916.6  232.23    4957  233.18    4990  230.28  4995.6  225.12  5009.4  224.14
  5009.9  224.14  5023.6  231.21  5045.9  232.82    5113  233.35  5233.2  243.01
  5316.3  253.37    5345     256  5389.7  269.24  5399.9  269.81  5434.5  274.67
#Mann= 6 ,-1 , 0
  4230.6     .16       0  5009.4     .07       0  5009.9     .16       0
  5233.2     .16       0  5316.3      .1       0  5399.9     .16       0
#XS Ineff= 2 , 0
                         5051.14          241.65
Permanent Ineff=
       F       F
Bank Sta=4957,5045.9
XS Rating Curve= 0 ,0
Exp/Cntr=0.3,0.1

Type RM Length L Ch R = 1 ,6633    ,472,472,472
BEGIN DESCRIPTION:
UNT058 IN BECR 9.0
END DESCRIPTION:
XS GIS Cut Line= 3
      3784849.62      10489610.2      3784449.61     10489260.19
      3784199.63     10488960.22
#Sta/Elev= 30
  4456.6  265.08  4459.9  265.08  4463.7  262.05  4484.6  260.23  4513.1  253.32
  4612.7  241.38  4619.4  239.11  4676.3  233.55  4853.8  231.68  4903.2  226.98
  4931.7  230.74  4960.1   231.5  4974.4  227.58    4981  228.32  4984.8  221.02
    4995  220.22  4995.5  220.22  5016.1  224.16  5023.9  229.32  5044.8  229.05
  5122.9  234.26  5165.8  242.24  5229.6  250.11  5279.1  258.63  5286.9  262.57
  5293.4  261.43  5307.7  270.31  5314.2  269.24  5336.3  278.47  5378.6  287.19
#Mann= 3 ,-1 , 0
  4456.6     .16       0    4995     .07       0  4995.5     .16       0
#XS Ineff= 2 , 0
         4818.75  240.23
Permanent Ineff=
       F       F
Bank Sta=4960.1,5023.9
XS Rating Curve= 0 ,0
Exp/Cntr=0.3,0.1

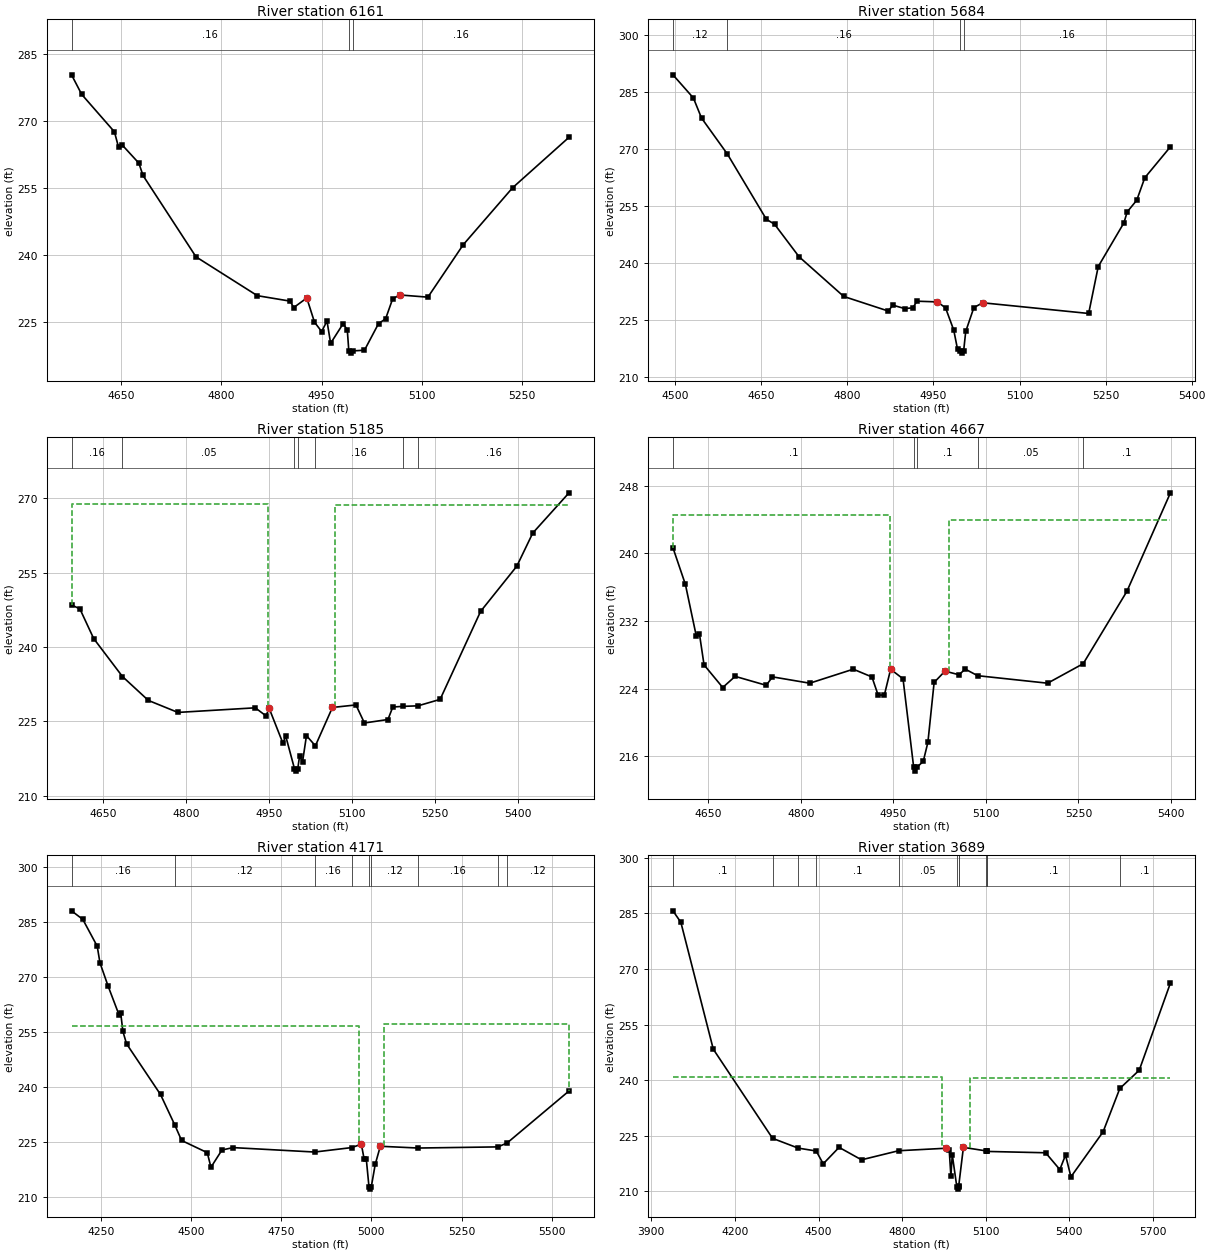
Type RM Length L Ch R = 1 ,6161    ,477,477,477
BEGIN DESCRIPTION:
UNT058 IN BECR 8.0
END DESCRIPTION:
XS GIS Cut Line= 3
      3785199.63      10489210.2      3784799.61     10489060.19
      3784499.56     10488960.17
#Sta/Elev= 30
  4576.4  280.26  4591.6  275.88  4640.5  267.51  4646.7  264.03  4652.1  264.57
    4677  260.51  4683.2  257.75  4762.4  239.55  4854.1  230.86  4903.1  229.64
  4908.4   228.2    4928  230.34  4939.5  224.93  4950.2  222.84  4958.2  225.19
  4963.6  220.21  4982.3  224.59  4988.5  223.23  4990.8  218.51  4993.6  218.01
  4996.8  218.51  5014.2  218.66  5035.2  224.61  5045.8  225.69  5056.3  230.15
  5066.9  231.02    5109  230.53  5161.7  242.24  5235.5  254.99  5319.9  266.29
#Mann= 3 ,-1 , 0
  4576.4     .16       0  4990.8     .07       0  4996.8     .16       0
Bank Sta=4928,5066.9
XS Rating Curve= 0 ,0
Exp/Cntr=0.3,0.1

Type RM Length L Ch R = 1 ,5684    ,499,499,499
BEGIN DESCRIPTION:
UNT058 IN BECR 7.0
END DESCRIPTION:
XS GIS Cut Line= 3
      3785299.61     10489060.19      3784899.61     10488710.19
      3784599.63      10488560.2
#Sta/Elev= 30
  4496.1  289.55  4531.7  283.46  4545.9  278.17  4591.1  268.66  4658.9  251.52
  4673.1  250.23  4715.8  241.67  4793.7  231.21  4871.5  227.36  4879.1  228.93
    4900  228.01  4914.2  228.22  4921.3  229.96  4956.9  229.78  4971.1  228.21
  4985.4  222.35    4992  217.32  4996.6  216.79  4999.4  216.29  5002.6  216.79
  5006.3     222  5020.5  228.29    5036  229.54  5220.5  226.73  5237.2  239.09
    5282   250.6  5287.6  253.46  5304.3  256.54  5318.3  262.45    5363  270.61
#Mann= 4 ,-1 , 0
  4496.1     .12       0  4591.1     .16       0  4996.6     .07       0
  5002.6     .16       0
Bank Sta=4956.9,5036
XS Rating Curve= 0 ,0
Exp/Cntr=0.3,0.1

Type RM Length L Ch R = 1 ,5185    ,518,518,518
BEGIN DESCRIPTION:
UNT058 IN BECR 6.0
END DESCRIPTION:
XS GIS Cut Line= 3
      3785399.61     10488410.19      3784999.61     10488260.19
      3784599.61     10488510.19
#Sta/Elev= 30
  4593.1  248.49  4608.2  247.69  4633.1  241.71  4685.1  234.05  4731.9  229.23
  4785.3  226.81  4925.1  227.74  4944.6   226.1    4950  227.69  4974.9  220.64
  4980.2     222  4995.9  215.47  4998.7  214.97  5001.9  215.47  5005.2  218.08
  5010.5  216.84  5017.6  222.13  5033.7  220.07  5064.5  227.81    5107  228.32
  5122.3  224.68  5164.8  225.38  5173.6   227.9  5191.4  228.03  5219.1  228.14
  5259.1  229.44  5332.2  247.18  5397.7  256.31  5426.5  262.99    5492   271.1
#Mann= 7 ,-1 , 0
  4593.1     .16       0  4685.1     .05       0  4995.9     .03       0
  5001.9     .05       0  5033.7     .16       0  5191.4     .12       0
  5219.1     .16       0
#XS Ineff= 2 , 0
         4947.24  268.77  5068.5          268.65
Permanent Ineff=
       F       F
Bank Sta=4950,5064.5
XS Rating Curve= 0 ,0
Exp/Cntr=0.3,0.1

Type RM Length L Ch R = 1 ,4667    ,496,496,496
BEGIN DESCRIPTION:
UNT058 IN BECR 5.0
END DESCRIPTION:
XS GIS Cut Line= 3
      3785399.64     10487860.19      3784999.61     10487810.19
      3784599.57     10487860.19
#Sta/Elev= 30
  4592.9  240.68  4613.1  236.33  4630.7  230.23  4635.8  230.49  4643.3   226.8
  4673.6  224.12  4693.7  225.44  4744.1  224.38  4754.2  225.38  4814.6  224.63
  4885.2  226.29  4915.4  225.37  4925.5  223.21  4935.6  223.24  4945.7  226.28
  4965.8  225.15    4983  214.71  4985.7  214.21    4989  214.71  4998.6  215.37
  5006.1  217.62  5016.2  224.72  5033.8  226.06  5056.5  225.63  5066.6   226.3
  5086.7  225.52  5200.1  224.63  5257.8  226.94  5328.6  235.51  5399.2  247.19
#Mann= 5 ,-1 , 0
  4592.9      .1       0    4983     .07       0    4989      .1       0
  5086.7     .05       0  5257.8      .1       0
#XS Ineff= 2 , 0
         4944.62  244.59 5039.76          243.99
Permanent Ineff=
       F       F
Bank Sta=4945.7,5033.8
XS Rating Curve= 0 ,0
Exp/Cntr=0.3,0.1

Type RM Length L Ch R = 1 ,4171    ,482,482,482
BEGIN DESCRIPTION:
UNT058 IN BECR 4.0
END DESCRIPTION:
XS GIS Cut Line= 3
      3785799.57     10487460.18      3784999.61     10487310.19
       3784599.6      10487710.2
#Sta/Elev= 30
  4168.5  288.01  4199.8  285.67  4239.7  278.38  4247.3  273.86  4270.2  267.43
  4299.9  259.76    4305  260.06  4310.9  255.18  4321.1  251.79  4415.2     238
  4454.3  229.81  4473.7  225.48  4544.9  222.16  4555.1  218.18  4585.6  222.88
  4616.1  223.54  4842.7  222.33  4945.3  223.54  4972.2  224.46  4979.9  220.41
  4985.9  220.41  4993.5  212.73  4996.3  212.23  4999.5  212.73  5010.7  218.98
  5024.8   223.9  5129.6  223.42    5351  223.73  5376.6  224.81  5548.1  238.96
#Mann= 9 ,-1 , 0
  4168.5     .16       0  4454.3     .12       0  4842.7     .16       0
  4945.3     .12       0  4993.5     .07       0  4999.5     .12       0
  5129.6     .16       0    5351     .05       0  5376.6     .12       0
#XS Ineff= 2 , 0
         4966.93  256.59 5035.17          257.09
Permanent Ineff=
       F       F
Bank Sta=4972.2,5024.8
XS Rating Curve= 0 ,0
Exp/Cntr=0.3,0.1

Type RM Length L Ch R = 1 ,3689    ,553,553,553
BEGIN DESCRIPTION:
UNT058 IN BECR 3.0
END DESCRIPTION:
XS GIS Cut Line= 3
      3785799.57     10487410.16      3784999.61     10486860.19
      3784199.63     10487010.19
#Sta/Elev= 30
  3977.7  285.71  4006.1   282.6  4122.4  248.37    4335  224.32  4426.9  221.68
  4491.6   220.9  4516.8  217.44  4573.7  221.88  4654.2  218.52  4787.1  220.97
  4958.6  221.65  4968.8  221.21  4974.8  214.15  4979.8  219.84  4996.3  211.11
  4999.1  210.61  5002.3  211.11  5002.9  211.49  5019.7  221.88  5100.7  220.93
  5104.2  220.83  5105.9  220.78  5314.7  220.42  5365.6  215.89    5386  219.79
  5405.5  213.93  5520.8  226.07  5580.8  237.77  5650.5   242.7  5762.4  266.23
#Mann= 12 ,-1 , 0
  3977.7      .1       0    4335     .05       0  4426.9      .1       0
  4491.6      .1       0  4787.1     .05       0  4996.3     .03       0
  5002.3     .05       0  5002.9      .1       0  5100.7     .12       0
  5104.2     .16       0  5105.9      .1       0  5580.8      .1       0
#XS Ineff= 2 , 0
         4943.32  240.94 5044.89          240.47
Permanent Ineff=
       F       F
Bank Sta=4958.6,5019.7
XS Rating Curve= 0 ,0
Exp/Cntr=0.3,0.1