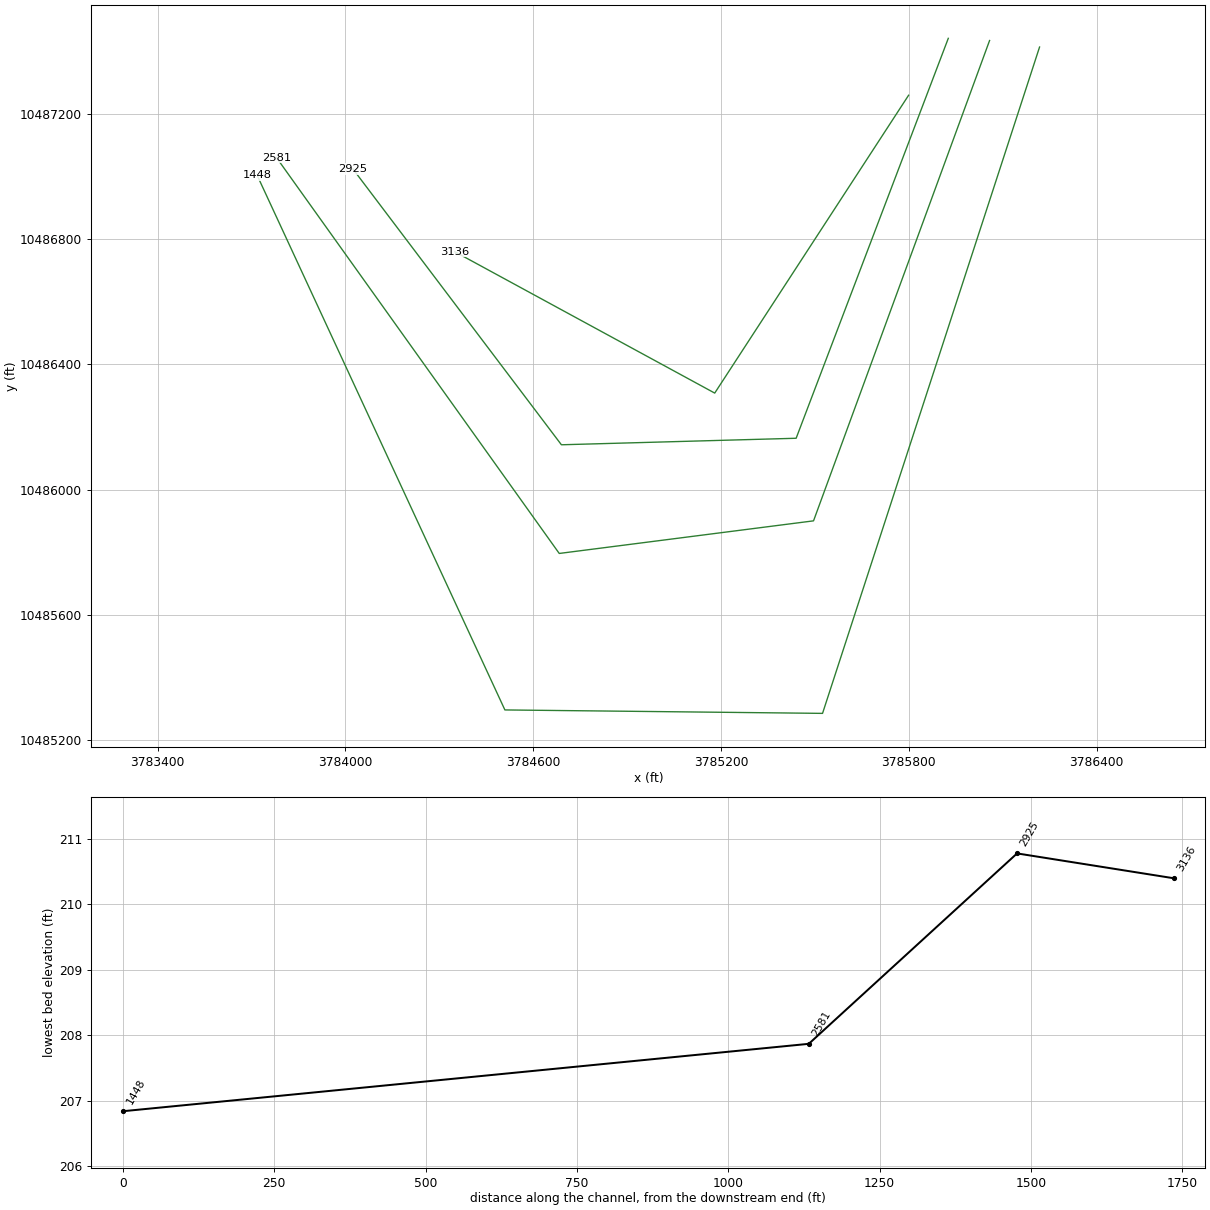
HEC-RAS study UNT058 IN BECR.prj: UNT058 IN BECR Base Level Engineering

--- UNT058 IN BECR.g01 (geometry) --- (continued)

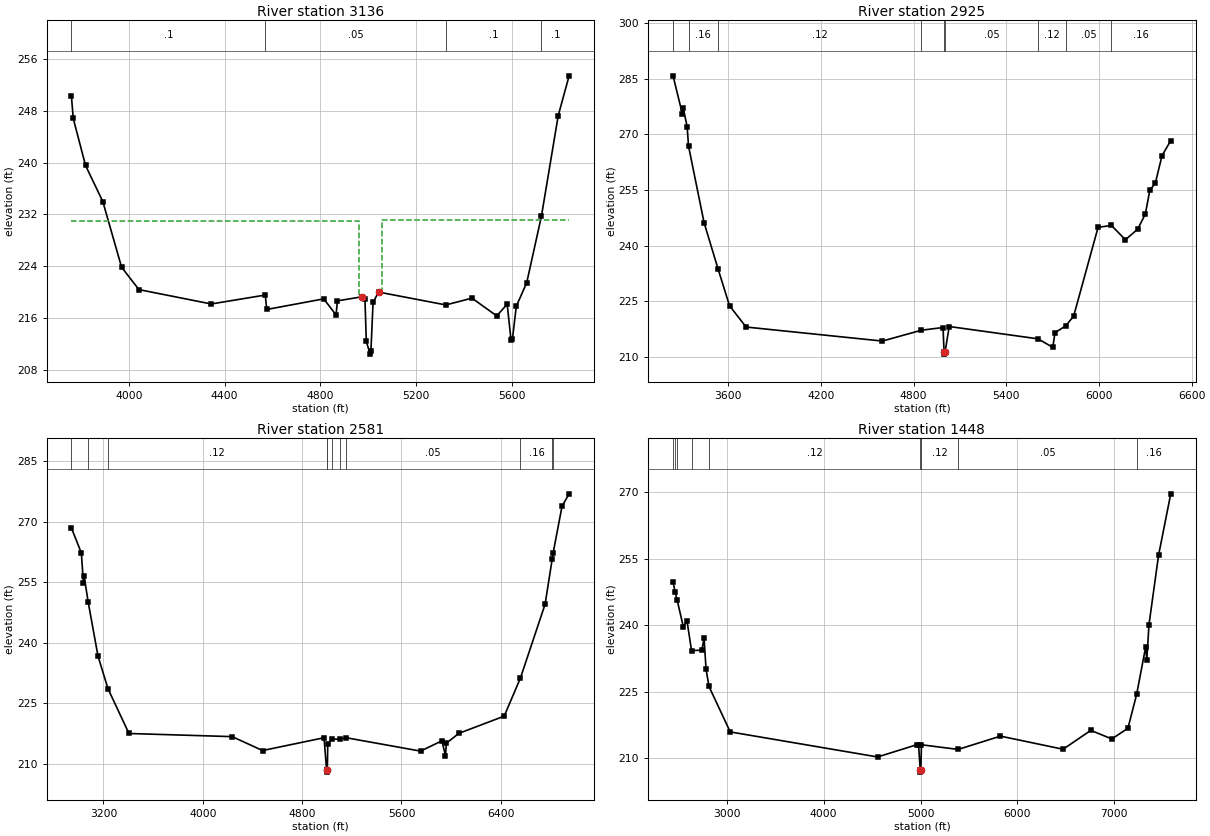
Type RM Length L Ch R = 1 ,3136    ,259,259,259
BEGIN DESCRIPTION:
UNT058 IN BECR 2.0
END DESCRIPTION:
XS GIS Cut Line= 3
      3785799.63     10487260.22      3785180.12     10486308.56
      3784349.61     10486760.19
#Sta/Elev= 30
  3759.7  250.24  3767.3  246.82  3818.7  239.55    3891  233.97  3969.5  223.82
    4042  220.37  4344.4  218.15  4570.3  219.53  4576.2   217.3  4814.7  218.94
  4866.1  216.46    4872  218.63  4976.6  219.27  4986.9  218.98  4992.7  212.37
  5008.6   210.4  5011.9   210.9    5021  218.39  5043.8  219.99  5325.2     218
  5434.5  219.05    5538  216.31  5581.7  218.11  5597.9  212.55  5603.6  212.69
  5619.7  217.78  5663.4  221.44    5725  231.73  5795.1  247.25  5840.6   253.4
#Mann= 4 ,-1 , 0
  3759.7      .1       0  4570.3     .05       0  5325.2      .1       0
    5725      .1       0
#XS Ineff= 2 , 0
         4962.98  230.94 5057.99           231.1
Permanent Ineff=
       F       F
Bank Sta=4976.6,5043.8
XS Rating Curve= 0 ,0
Exp/Cntr=0.3,0.1

Type RM Length L Ch R = 1 ,2925    ,344,344,344
BEGIN DESCRIPTION:
Mapping XS 7b5c1d74
END DESCRIPTION:
XS GIS Cut Line= 4
       3785926.4     10487442.05      3785440.27     10486164.23
      3784690.27      10486143.4      3784024.16     10487024.61
#Sta/Elev= 30
  3242.4  285.76  3303.5  275.35  3308.8  276.98  3333.6  272.09  3342.5  266.84
  3443.3  246.19  3533.2  233.81  3607.9  223.83  3715.2  218.08  4597.6   214.3
  4850.2  217.22  4990.4  217.95    4997  211.28  4999.8  210.78    5003  211.28
  5030.4  218.22  5605.1   214.9  5700.7  212.61  5715.3  216.59  5783.9  218.36
    5836  221.02  5994.1  244.94  6080.7  245.45  6171.1   241.6  6250.1  244.43
  6300.1  248.51  6329.2  254.96  6364.6  256.82  6408.3  264.29  6464.5  268.28
#Mann= 9 ,-1 , 0
  3242.4     .12       0  3342.5     .16       0  3533.2     .12       0
  4850.2     .05       0    4997     .03       0    5003     .05       0
  5605.1     .12       0  5783.9     .05       0  6080.7     .16       0
Bank Sta=4997,5003
XS Rating Curve= 0 ,0
Exp/Cntr=0.3,0.1

Type RM Length L Ch R = 1 ,2581    ,1133,1133,1133
BEGIN DESCRIPTION:
Mapping XS c3ed33de
END DESCRIPTION:
XS GIS Cut Line= 4
      3786058.33     10487435.08      3785495.83     10485900.34
      3784683.33     10485796.18      3783780.56     10487060.05
#Sta/Elev= 30
  2942.7   268.4  3022.5  262.22  3039.6  254.69  3044.9  256.52  3077.3  250.08
  3156.3  236.69  3236.7  228.57  3405.9  217.45    4237  216.67  4481.6  213.22
  4976.7   216.4    4997  208.37  4999.8  207.87    5003  208.37  5006.5   214.8
  5040.2  216.05  5105.3  216.04  5152.5  216.41  5753.5  213.08  5925.6  215.63
  5954.4  211.92  5961.2  215.03    6062  217.48    6427  221.75  6558.2  231.24
  6756.3   249.5  6814.1  260.81  6820.7  262.17  6892.7  273.78  6949.6  276.87
#Mann= 11 ,-1 , 0
  2942.7     .12       0  3077.3     .16       0  3236.7     .12       0
    4997     .07       0    5003     .12       0  5040.2     .05       0
  5105.3     .12       0  5152.5     .05       0  6558.2     .16       0
  6814.1     .05       0  6820.7     .16       0
Bank Sta=4997,5003
XS Rating Curve= 0 ,0
Exp/Cntr=0.3,0.1

Type RM Length L Ch R = 1 ,1448    ,0,0,0
BEGIN DESCRIPTION:
UNT058 IN BECR 1.0
END DESCRIPTION:
XS GIS Cut Line= 4
      3786218.05     10487414.24      3785524.61     10485285.19
      3784509.71     10485296.18      3783718.07     10487004.47
#Sta/Elev= 30
  2445.8  249.66  2468.5  247.37  2488.4  245.62  2551.9  239.62  2589.1  241.02
  2636.6  234.25  2743.4  234.35  2765.6   237.1  2786.6  230.04  2816.4  226.17
  3035.9  215.91  4557.3  210.26    4960  213.01    4980  212.89    4997  207.34
  4999.8  206.84    5003  207.34    5010  213.01    5388  211.96  5825.5  214.96
  6471.7     212  6757.7  216.26  6974.9  214.32  7140.8  216.74  7231.3  224.42
  7324.1   235.1  7335.5  232.11  7358.1   240.1  7456.7  255.71  7582.7  269.61
#Mann= 9 ,-1 , 0
  2445.8     .12       0  2468.5     .16       0  2488.4     .12       0
  2636.6     .16       0  2816.4     .12       0    4997     .07       0
    5003     .12       0    5388     .05       0  7231.3     .16       0
Bank Sta=4997,5003
XS Rating Curve= 0 ,0
Exp/Cntr=0.3,0.1

Chan Stop Cuts=-1
Use User Specified Reach Order=0
Composite Channel Slope=5