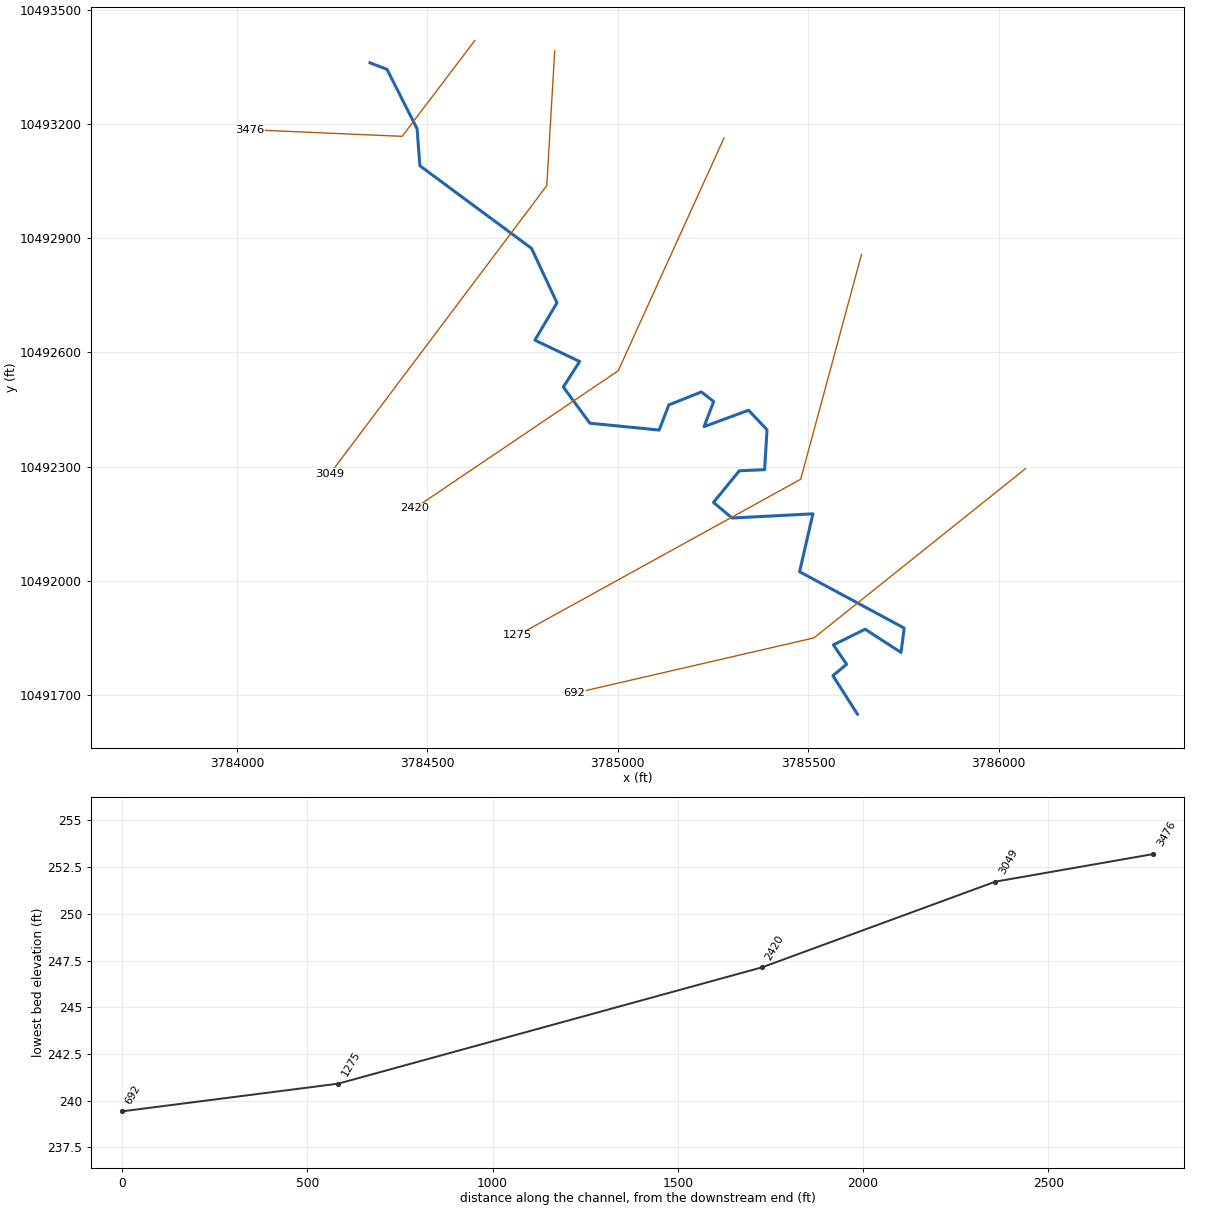
--- UNT059 IN BECR.prj (project) ---

Proj Title=UNT059 IN BECR Base Level Engineering
Current Plan=p01
Default Exp/Contr=0.3,0.1
English Units
Geom File=g01
Flow File=f01
Plan File=p01
BEGIN DESCRIPTION:
UNT059 IN BECR
END DESCRIPTION:

--- UNT059 IN BECR.p01 (plan) ---

Plan Title=Multiple Run
Short Identifier=Multiple
Geom File=g01
Flow File=f01
Subcritical Flow
K Sum by GR= 0
Std Step Tol= 0.01
Critical Tol= 0.01
Num of Std Step Trials= 20
Max Error Tol= 0.3
Flow Tol Ratio= 0.001
Split Flow NTrial= 30
Split Flow Tol= 0.02
Split Flow Ratio= 0.02
Log Output Level= 0
Friction Slope Method= 1
Unsteady Friction Slope Method= 2
Unsteady Bridges Friction Slope Method= 1
Parabolic Critical Depth
Global Vel Dist=  1 , 1 , 1
Global Log Level= 0
CheckData=True
Encroach Param= -1, 0, 0, 0
BEGIN DESCRIPTION:
Multiple Run
END DESCRIPTION:

--- UNT059 IN BECR.f01 (steady flow) ---

Flow Title=Multiple
Number of Profiles=7
Profile Names=10-year,25-year,50-year,1pct_min,100-year,1pct_plu,500-year
River Rch & RM= UNT059 IN BECR,Reach-1,3476
     351     461     550     484     654     884     927
Boundary for River Rch & Prof#=UNT059 IN BECR,Reach-1,1
Up Type=0
Dn Type=3
Dn Slope=0.005
Boundary for River Rch & Prof#=UNT059 IN BECR,Reach-1,2
Up Type=0
Dn Type=3
Dn Slope=0.005
Boundary for River Rch & Prof#=UNT059 IN BECR,Reach-1,3
Up Type=0
Dn Type=3
Dn Slope=0.005
Boundary for River Rch & Prof#=UNT059 IN BECR,Reach-1,4
Up Type=0
Dn Type=3
Dn Slope=0.005
Boundary for River Rch & Prof#=UNT059 IN BECR,Reach-1,5
Up Type=0
Dn Type=3
Dn Slope=0.005
Boundary for River Rch & Prof#=UNT059 IN BECR,Reach-1,6
Up Type=0
Dn Type=3
Dn Slope=0.005
Boundary for River Rch & Prof#=UNT059 IN BECR,Reach-1,7
Up Type=0
Dn Type=3
Dn Slope=0.005

--- UNT059 IN BECR.g01 (geometry) ---

Geom Title=Existing Conditions

River Reach=UNT059 IN BECR,Reach-1
Reach XY= 30
      3784349.61     10493360.19      3784394.25     10493343.00
      3784473.25     10493187.00      3784480.50     10493090.00
      3784773.75     10492873.00      3784840.50     10492730.00
      3784782.50     10492632.00      3784900.00     10492576.00
      3784857.25     10492509.00      3784926.75     10492414.00
      3785108.75     10492396.00      3785134.25     10492462.00
      3785219.75     10492496.00      3785252.00     10492471.00
      3785226.75     10492405.00      3785343.50     10492448.00
      3785392.00     10492397.00      3785385.75     10492292.00
      3785319.25     10492289.00      3785251.50     10492206.00
      3785300.25     10492165.00      3785512.50     10492176.00
      3785477.50     10492024.00      3785752.25     10491876.00
      3785743.75     10491812.00      3785649.75     10491873.00
      3785566.25     10491832.00      3785601.00     10491781.00
      3785565.00     10491751.00      3785629.50     10491650.00

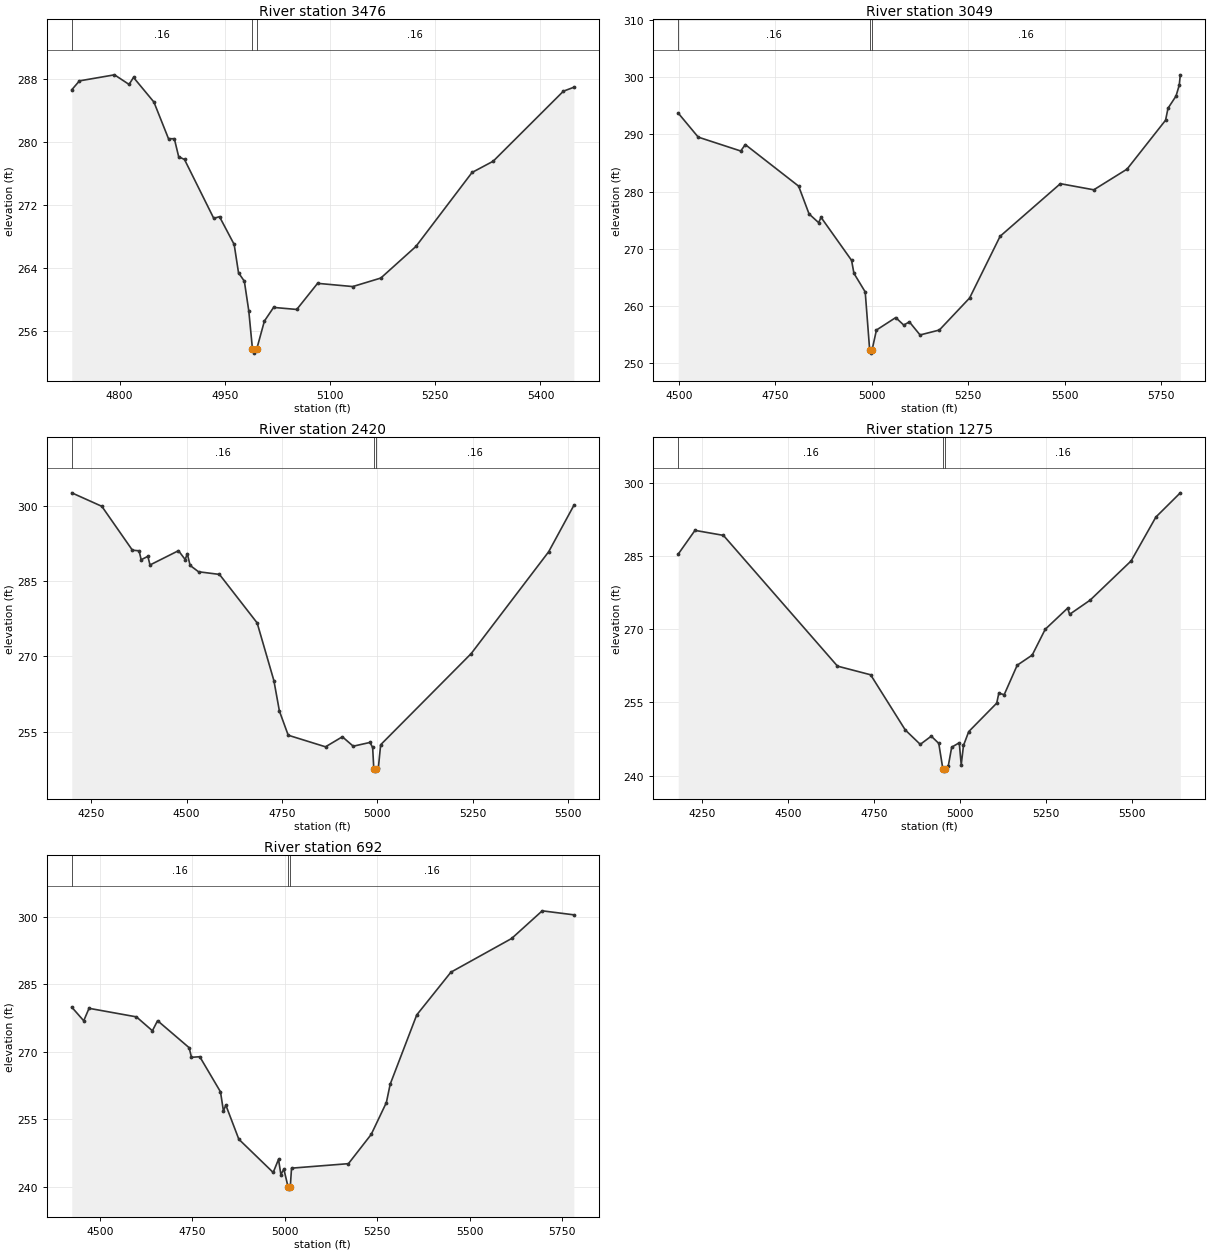
Type RM Length L Ch R = 1,3476,427,427,427
BEGIN DESCRIPTION:
UNT059 IN BECR 4.0
END DESCRIPTION:
XS GIS Cut Line= 3
      3784624.99     10493418.95      3784434.00     10493167.19
      3784034.68     10493184.55
#Sta/Elev= 30
  4731.9  286.67  4742.8  287.80  4792.8  288.57  4813.6  287.35  4819.9  288.24
  4849.0  285.11  4869.8  280.45  4878.1  280.45  4884.3  278.16  4892.6  277.81
  4934.3  270.33  4942.5  270.54  4963.4  267.01  4969.6  263.41  4977.9  262.34
  4984.2  258.59  4989.5  253.70  4992.2  253.20  4995.5  253.70  5006.5  257.28
  5019.6  259.01  5052.6  258.75  5082.3  262.07  5132.4  261.66  5172.4  262.74
  5222.5  266.76  5302.5  276.16  5332.6  277.59  5432.7  286.49  5447.6  286.99
#Mann=3,-1,0
  4731.9    0.16       0  4989.5    0.07       0  4995.5    0.16       0
Bank Sta=4989.5,4995.5
Exp/Cntr=0.3,0.1

Type RM Length L Ch R = 1,3049,629,629,629
BEGIN DESCRIPTION:
UNT059 IN BECR 3.0
END DESCRIPTION:
XS GIS Cut Line= 3
      3784834.63     10493391.88      3784813.80     10493037.73
      3784244.47     10492280.93
#Sta/Elev= 30
  4498.2  293.72  4550.0  289.52  4660.2  287.09  4672.1  288.21  4810.4  280.94
  4837.4  276.08  4862.2  274.55  4868.5  275.48  4947.6  267.96  4953.8  265.68
  4983.0  262.43  4994.6  252.22  4997.3  251.72  5000.6  252.22  5012.1  255.76
  5062.1  257.94  5082.9  256.63  5097.5  257.19  5125.2  254.90  5175.2  255.76
  5253.7  261.37  5332.8  272.17  5489.0  281.37  5575.7  280.30  5661.9  283.92
  5761.8  292.48  5768.1  294.57  5788.9  296.71  5797.2  298.60  5800.0  300.42
#Mann=3,-1,0
  4498.2    0.16       0  4994.6    0.07       0  5000.6    0.16       0
Bank Sta=4994.6,5000.6
Exp/Cntr=0.3,0.1

Type RM Length L Ch R = 1,2420,1145,1145,1145
BEGIN DESCRIPTION:
UNT059 IN BECR 2.0
END DESCRIPTION:
XS GIS Cut Line= 3
      3785279.10     10493162.76      3785001.30     10492551.61
      3784466.54     10492190.48
#Sta/Elev= 30
  4198.9  302.64  4277.7  299.95  4357.9  291.20  4375.4  291.08  4380.9  289.29
  4398.5  289.98  4404.0  288.25  4478.7  291.10  4496.3  289.34  4501.8  290.50
  4509.3  288.16  4531.3  286.90  4586.2  286.37  4685.0  276.70  4729.0  265.17
  4743.4  259.12  4766.5  254.30  4864.3  251.99  4908.5  253.99  4937.0  252.11
  4980.9  252.86  4987.9  251.86  4990.9  247.64  4993.7  247.14  4996.9  247.64
  5002.9  247.83  5008.9  252.40  5246.3  270.58  5449.5  290.89  5515.5  300.13
#Mann=3,-1,0
  4198.9    0.16       0  4990.9    0.07       0  4996.9    0.16       0
Bank Sta=4990.9,4996.9
Exp/Cntr=0.3,0.1

Type RM Length L Ch R = 1,1275,583,583,583
BEGIN DESCRIPTION:
Mapping XS a42c13ef
END DESCRIPTION:
XS GIS Cut Line= 3
      3785640.19     10492857.17      3785480.47     10492266.89
      3784737.44     10491857.19
#Sta/Elev= 30
  4180.4  285.36  4229.1  290.21  4311.7  289.19  4643.5  262.41  4739.8  260.64
  4840.6  249.34  4884.2  246.39  4916.2  248.07  4938.0  246.59  4949.8  241.41
  4952.5  240.91  4955.8  241.41  4965.5  241.91  4975.6  245.81  4997.6  246.72
  5003.3  242.17  5009.9  246.16  5025.1  249.00  5106.5  254.83  5112.6  256.85
  5128.3  256.57  5166.1  262.60  5209.7  264.67  5247.5  269.95  5312.8  274.29
  5318.5  273.02  5378.1  275.92  5497.4  283.96  5569.4  292.94  5640.4  297.90
#Mann=3,-1,0
  4180.4    0.16       0  4949.8    0.07       0  4955.8    0.16       0
Bank Sta=4949.8,4955.8
Exp/Cntr=0.3,0.1

Type RM Length L Ch R = 1,692,0,0,0
BEGIN DESCRIPTION:
UNT059 IN BECR 1.0
END DESCRIPTION:
XS GIS Cut Line= 3
      3786070.75     10492294.67      3785515.19     10491850.23
      3784885.69     10491704.96
#Sta/Elev= 30
  4424.3  279.88  4456.6  276.85  4471.0  279.62  4599.1  277.72  4642.3  274.63
  4656.3  276.87  4741.6  270.87  4748.0  268.73  4770.4  268.86  4826.4  261.06
  4834.4  256.79  4840.8  258.12  4876.0  250.52  4968.9  243.13  4983.3  246.05
  4989.7  242.67  4997.7  243.88  5009.1  239.93  5011.8  239.43  5015.1  239.93
  5018.5  244.09  5172.3  245.09  5233.9  251.59  5274.9  258.67  5285.2  262.74
  5357.0  278.15  5449.4  287.65  5613.6  295.14  5696.3  301.29  5781.8  300.40
#Mann=3,-1,0
  4424.3    0.16       0  5009.1    0.07       0  5015.1    0.16       0
Bank Sta=5009.1,5015.1
Exp/Cntr=0.3,0.1

Chan Stop Cuts=-1