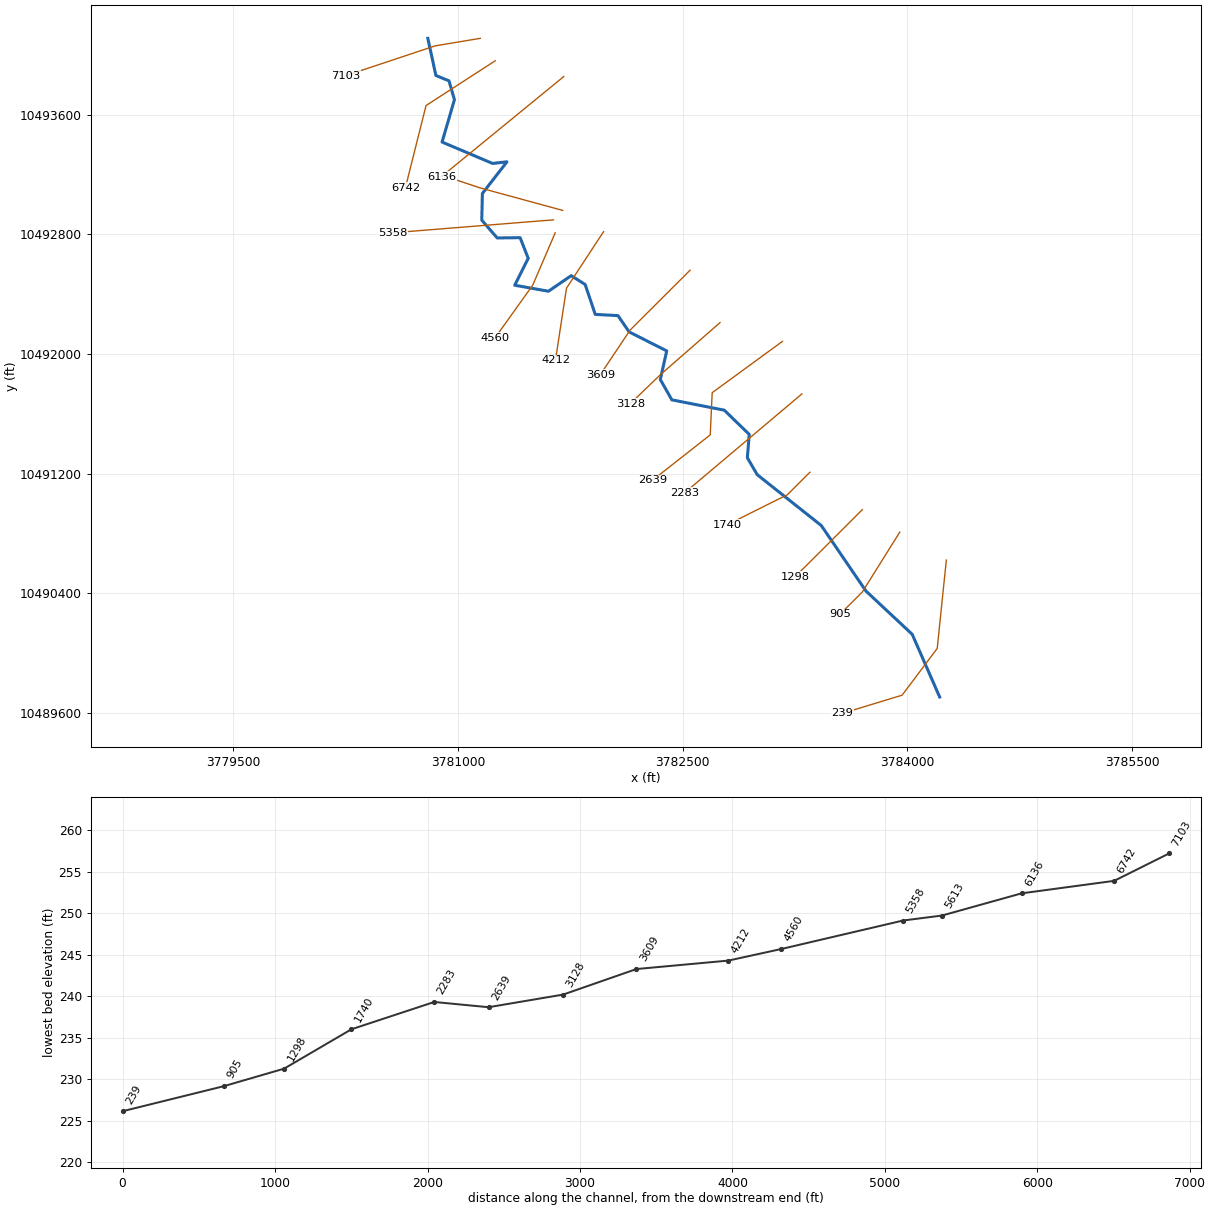
--- UNT060 IN BECR.prj (project) ---

Proj Title=UNT060 IN BECR Base Level Engineering
Current Plan=p01
Default Exp/Contr=0.3,0.1
English Units
Geom File=g01
Flow File=f01
Plan File=p01
Y Axis Title=Elevation
X Axis Title(PF)=Main Channel Distance
X Axis Title(XS)=Station
BEGIN DESCRIPTION:
UNT060 IN BECR
END DESCRIPTION:
DSS Export Rating Curves= 0
DSS Export Rating Curve Sorted= 0
DSS Export Volume Flow Curves= 0
DXF OffsetX= 0
DXF OffsetY= 0
DXF ScaleX= 1
DXF ScaleY= 10

--- UNT060 IN BECR.p01 (plan) ---

Plan Title=Multiple Run
Short Identifier=Multiple
Geom File=g01
Flow File=f01
Subcritical Flow
K Sum by GR= 0
Std Step Tol= 0.01
Critical Tol= 0.01
Num of Std Step Trials= 20
Max Error Tol= 0.3
Flow Tol Ratio= 0.001
Split Flow NTrial= 30
Split Flow Tol= 0.02
Split Flow Ratio= 0.02
Log Output Level= 0
Friction Slope Method= 1
Unsteady Friction Slope Method= 2
Unsteady Bridges Friction Slope Method= 1
Parabolic Critical Depth
Global Vel Dist=  1 , 1 , 1
Global Log Level= 0
CheckData=True
Encroach Param= -1, 0, 0, 0
BEGIN DESCRIPTION:
Multiple Run
END DESCRIPTION:

--- UNT060 IN BECR.f01 (steady flow) ---

Flow Title=Multiple
Number of Profiles=7
Profile Names=10-year,25-year,50-year,1pct_min,100-year,1pct_plu,500-year
River Rch & RM= UNT060 IN BECR,Reach-1,7103
     717     979    1197    1076    1455    1967    2156
River Rch & RM= UNT060 IN BECR,Reach-1,5613
     800    1095    1340    1205    1630    2204    2417
Boundary for River Rch & Prof#=UNT060 IN BECR,Reach-1,1
Up Type=0
Dn Type=3
Dn Slope=0.005
Boundary for River Rch & Prof#=UNT060 IN BECR,Reach-1,2
Up Type=0
Dn Type=3
Dn Slope=0.005
Boundary for River Rch & Prof#=UNT060 IN BECR,Reach-1,3
Up Type=0
Dn Type=3
Dn Slope=0.005
Boundary for River Rch & Prof#=UNT060 IN BECR,Reach-1,4
Up Type=0
Dn Type=3
Dn Slope=0.005
Boundary for River Rch & Prof#=UNT060 IN BECR,Reach-1,5
Up Type=0
Dn Type=3
Dn Slope=0.005
Boundary for River Rch & Prof#=UNT060 IN BECR,Reach-1,6
Up Type=0
Dn Type=3
Dn Slope=0.005
Boundary for River Rch & Prof#=UNT060 IN BECR,Reach-1,7
Up Type=0
Dn Type=3
Dn Slope=0.005

--- UNT060 IN BECR.g01 (geometry) ---

Geom Title=Existing Conditions
Program Version=4.10

River Reach=UNT060 IN BECR  ,Reach-1
Reach XY= 30
      3780799.61     10494110.19       3780853.5       10493862.
        3780941.       10493826.      3780977.25       10493700.
      3780894.75       10493417.        3781232.       10493274.
      3781327.75       10493285.      3781163.75       10493073.
      3781159.75       10492895.      3781262.75       10492776.
       3781415.5       10492778.      3781469.75       10492640.
       3781379.5       10492460.      3781604.75       10492420.
       3781756.5       10492524.      3781849.75       10492465.
        3781917.       10492265.       3782068.5       10492257.
      3782143.25       10492148.        3782394.       10492021.
      3782351.25       10491830.        3782428.       10491694.
        3782778.       10491625.      3782944.75       10491463.
        3782932.       10491307.      3782997.75       10491194.
       3783425.5       10490854.      3783723.75       10490416.
      3784032.25       10490127.       3784215.5       10489708.

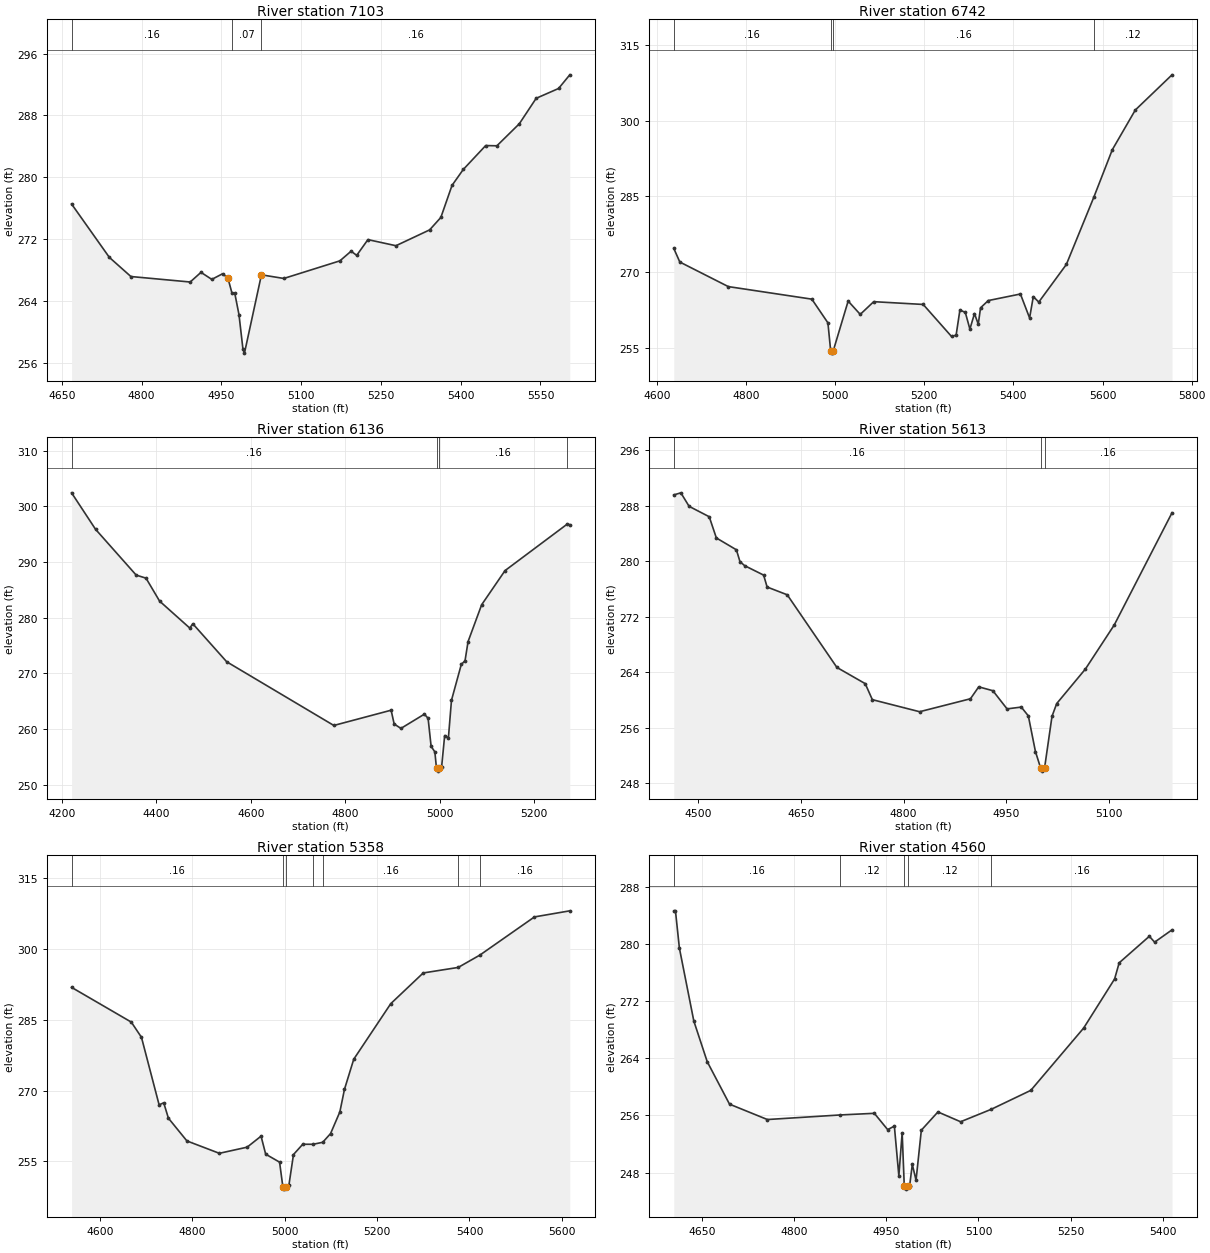
Type RM Length L Ch R = 1 ,7103    ,361,361,361
BEGIN DESCRIPTION:
UNT060 IN BECR 15.0
END DESCRIPTION:
XS GIS Cut Line= 3
      3781149.62     10494110.19      3780849.61     10494060.19
      3780249.61     10493860.19
#Sta/Elev= 30
  4668.5  276.53  4739.5  269.62    4780  267.14  4891.5  266.43  4911.8  267.68
  4932.1  266.77  4952.4   267.5  4962.5  266.92  4970.1  264.97  4975.3  264.97
  4983.2  262.21  4990.7  257.72  4993.5  257.22  5025.4  267.36  5067.5  266.89
  5172.9  269.17    5194  270.42  5204.5  269.88  5225.6  271.92  5278.3  271.13
  5341.6  273.18  5362.7  274.79  5383.7  278.94  5404.8     281    5447   284.1
  5468.1  284.07  5510.2  286.92  5541.9  290.22    5584  291.49  5605.1  293.26
#Mann= 3 ,-1 , 0
  4668.5     .16       0  4970.1     .07       0  5025.4     .16       0
Bank Sta=4962.5,5025.4
XS Rating Curve= 0 ,0
Exp/Cntr=0.3,0.1

Type RM Length L Ch R = 1 ,6742    ,606,606,606
BEGIN DESCRIPTION:
UNT060 IN BECR 14.0
END DESCRIPTION:
XS GIS Cut Line= 3
      3781249.59     10493960.17      3780787.76     10493660.99
      3780649.62     10493110.22
#Sta/Elev= 30
  4637.8  274.67  4651.3  271.97  4760.1   267.1  4947.6  264.61  4983.7  259.91
  4989.8  254.41  4992.6  253.91  4995.8  254.41  5029.1  264.23  5056.2  261.59
  5086.5  264.11  5197.5  263.56  5261.1  257.21  5271.4  257.48  5279.9  262.45
    5292  261.99  5302.3  258.67  5312.6  261.75  5321.1  259.65  5326.2  262.89
  5343.5  264.33  5415.7  265.63  5436.3  260.88  5444.6  265.11  5456.9  264.03
  5518.8  271.49  5580.3  284.79  5621.9  294.23  5673.5   302.1  5755.9  309.08
#Mann= 4 ,-1 , 0
  4637.8     .16       0  4989.8     .07       0  4995.8     .16       0
  5580.3     .12       0
Bank Sta=4989.8,4995.8
XS Rating Curve= 0 ,0
Exp/Cntr=0.3,0.1

Type RM Length L Ch R = 1 ,6136    ,523,523,523
BEGIN DESCRIPTION:
UNT060 IN BECR 13.0
END DESCRIPTION:
XS GIS Cut Line= 2
      3781706.85      10493854.8      3780890.87     10493186.38
#Sta/Elev= 30
  4220.5  302.44  4271.2  295.89  4357.3  287.65  4378.1   287.1  4406.8  282.98
  4470.7  278.13  4477.2   278.9  4548.9  272.07  4775.7  260.62    4897  263.36
  4903.5  260.88  4917.8  260.09  4967.4  262.65  4975.3  261.91  4981.7  256.87
  4989.6  255.87  4993.1  252.91  4995.8  252.41  4999.1  252.91    5004  253.22
  5010.4  258.81  5018.3  258.38  5024.8  265.14  5045.6  271.59  5053.5  272.25
  5059.9  275.69  5088.7  282.32  5138.2  288.46  5269.9  296.82  5275.3  296.71
#Mann= 4 ,-1 , 0
  4220.5     .16       0  4993.1     .07       0  4999.1     .16       0
  5269.9     .12       0
Bank Sta=4993.1,4999.1
XS Rating Curve= 0 ,0
Exp/Cntr=0.3,0.1

Type RM Length L Ch R = 1 ,5613    ,255,255,255
BEGIN DESCRIPTION:
UNT060 IN BECR 12.0
END DESCRIPTION:
XS GIS Cut Line= 3
      3781699.57      10492960.2      3781149.61     10493110.19
      3780999.58      10493160.2
#Sta/Elev= 30
  4464.2  289.58  4474.5  289.88  4486.6  287.93    4516  286.43  4526.4  283.37
  4555.7  281.66  4560.9  279.96  4567.8  279.37  4595.5  278.01  4600.6  276.29
    4630  275.17  4702.6  264.69    4744  262.35  4754.4  260.04  4823.5   258.3
  4897.8  260.17  4909.9  261.89  4930.6  261.33  4951.3  258.71  4972.1  258.97
  4982.4   257.7  4992.8  252.55  5000.2  250.23  5002.9  249.73  5006.2  250.23
    5017  257.64  5023.9  259.48  5065.9  264.47    5108  270.82  5192.4     287
#Mann= 3 ,-1 , 0
  4464.2     .16       0  5000.2     .07       0  5006.2     .16       0
Bank Sta=5000.2,5006.2
XS Rating Curve= 0 ,0
Exp/Cntr=0.3,0.1

Type RM Length L Ch R = 1 ,5358    ,798,798,798
BEGIN DESCRIPTION:
UNT060 IN BECR 11.0
END DESCRIPTION:
XS GIS Cut Line= 2
      3781638.49      10492897.1      3780563.38      10492810.4
#Sta/Elev= 30
  4538.6  291.83  4667.9  284.48  4689.9  281.26  4728.1  266.97  4738.1   267.4
  4748.2  264.15  4788.3  259.33  4858.5  256.71  4918.7  258.01  4948.8  260.34
  4958.8  256.53  4988.9  254.84    4996  249.63  4998.7  249.13    5002  249.63
    5009   249.9    5019  256.45  5039.1  258.63  5061.2  258.62  5082.3  259.04
  5099.3  260.89  5119.4  265.47  5129.4  270.25  5149.5  276.63  5229.7  288.39
  5299.9  294.88  5375.6  296.05  5422.5  298.66  5540.7  306.74  5617.2  308.03
#Mann= 7 ,-1 , 0
  4538.6     .16       0    4996     .07       0    5002     .16       0
  5061.2     .12       0  5082.3     .16       0  5375.6     .12       0
  5422.5     .16       0
Bank Sta=4996,5002
XS Rating Curve= 0 ,0
Exp/Cntr=0.3,0.1

Type RM Length L Ch R = 1 ,4560    ,348,348,348
BEGIN DESCRIPTION:
UNT060 IN BECR 10.0
END DESCRIPTION:
XS GIS Cut Line= 3
      3781649.61     10492810.18      3781499.61     10492460.19
      3781249.61     10492110.19
#Sta/Elev= 30
  4604.1  284.61  4606.8  284.61  4613.2   279.4  4636.7   269.2  4658.5  263.52
  4694.8  257.58  4756.4  255.43  4874.8  256.07  4930.5   256.3  4952.2  254.02
  4963.1  254.51  4970.4  247.56  4975.8  253.58  4979.2   246.2  4981.9   245.7
  4985.2   246.2    4988   246.2  4992.3  249.15  4998.4  246.95    5007  253.94
    5034  256.49  5070.9  255.12  5120.5  256.85  5185.2  259.51  5271.2  268.22
  5321.6  275.09    5329  277.34  5378.1  281.05  5386.7  280.23    5415  281.95
#Mann= 5 ,-1 , 0
  4604.1     .16       0  4874.8     .12       0  4979.2     .07       0
  4985.2     .12       0  5120.5     .16       0
Bank Sta=4979.2,4985.2
XS Rating Curve= 0 ,0
Exp/Cntr=0.3,0.1

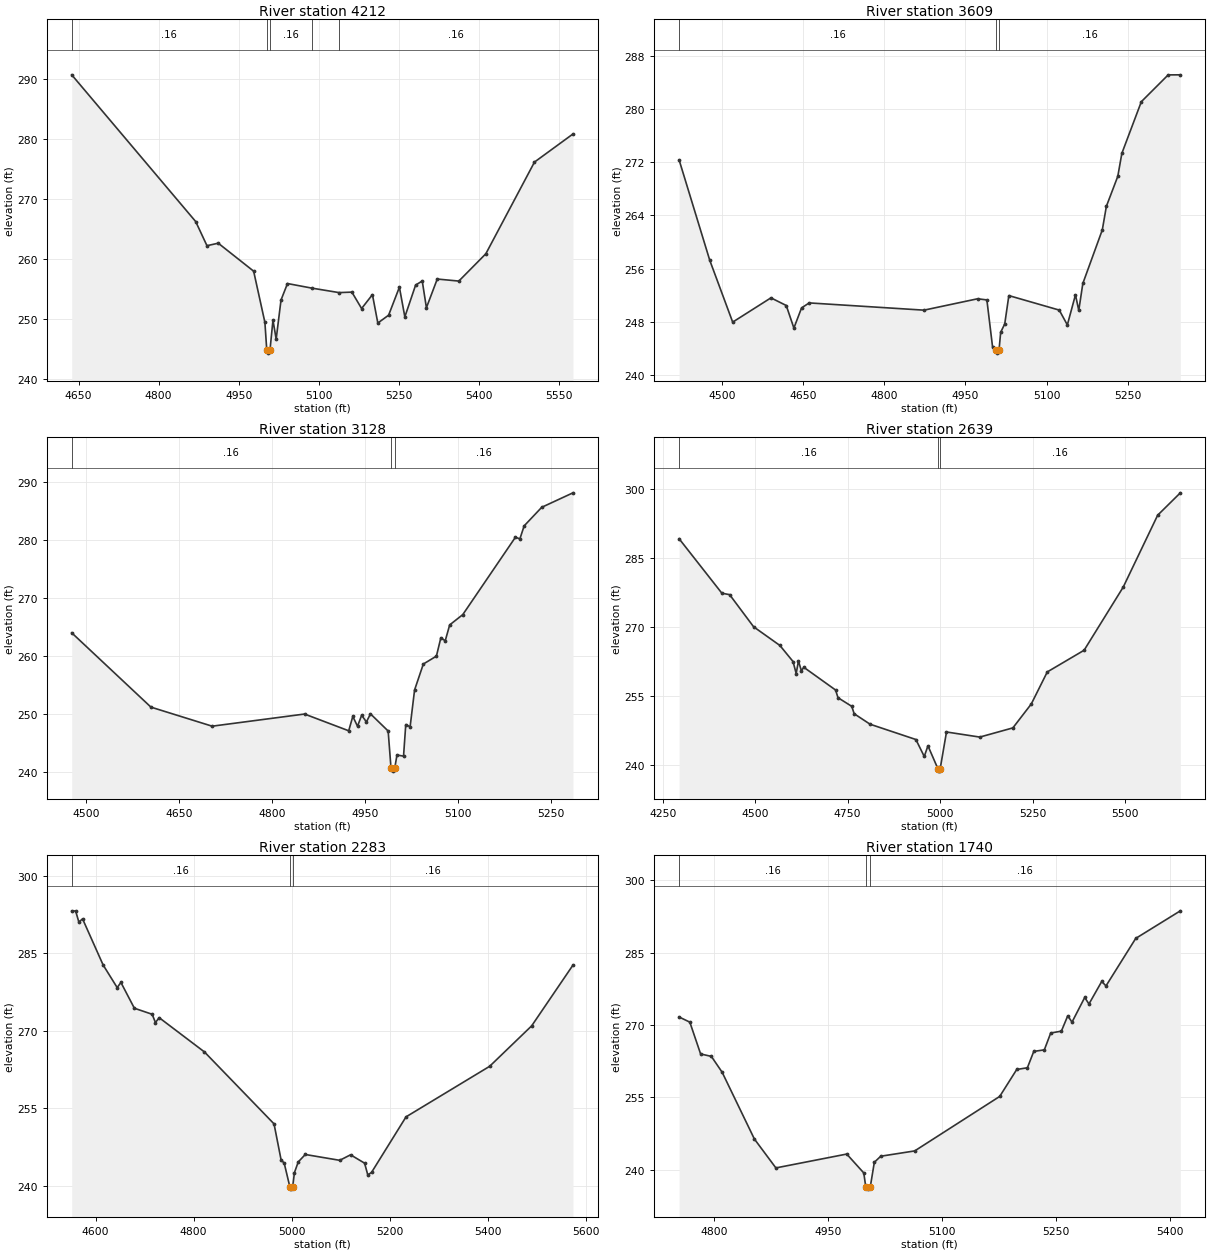
Type RM Length L Ch R = 1 ,4212    ,603,603,603
BEGIN DESCRIPTION:
UNT060 IN BECR 9.0
END DESCRIPTION:
XS GIS Cut Line= 3
      3781972.63     10492818.24      3781725.23     10492440.63
      3781651.45     10491958.88
#Sta/Elev= 30
  4637.2  290.65  4869.4  266.21  4890.5  262.19  4911.6  262.61  4977.9  257.95
    4999  249.42  5002.5   244.8  5005.2   244.3  5008.5   244.8  5014.1  249.79
  5020.1  246.64  5029.2  253.15  5041.3  255.89  5086.7  255.13  5137.9  254.38
  5161.9  254.46  5180.1  251.73  5200.4  254.04  5210.5  249.31  5230.7  250.62
  5250.9  255.28  5261.1  250.34  5281.3  255.64  5293.7  256.31  5301.5  251.86
  5321.8  256.64  5362.2   256.3  5412.8  260.85  5503.9  276.12    5576   280.8
#Mann= 5 ,-1 , 0
  4637.2     .16       0  5002.5     .07       0  5008.5     .16       0
  5086.7     .12       0  5137.9     .16       0
Bank Sta=5002.5,5008.5
XS Rating Curve= 0 ,0
Exp/Cntr=0.3,0.1

Type RM Length L Ch R = 1 ,3609    ,481,481,481
BEGIN DESCRIPTION:
UNT060 IN BECR 8.0
END DESCRIPTION:
XS GIS Cut Line= 3
      3782549.61     10492560.19      3782149.61     10492160.19
      3781949.63     10491860.22
#Sta/Elev= 30
    4421  272.33  4477.6  257.25    4520  247.94  4590.7  251.59    4619  250.44
  4633.1  247.05  4647.3  250.08  4661.4  250.83  4873.5  249.74  4972.5  251.45
  4989.7  251.28  5000.2  244.22  5006.2  243.78    5009  243.28  5012.2  243.78
  5015.2  246.41  5022.7  247.67  5030.3  251.93  5123.4  249.75  5138.4  247.52
  5153.4  252.05  5159.5   249.7    5167  253.75    5203  261.81  5210.5  265.35
  5231.6  269.86  5239.1  273.31  5275.1  281.08  5324.7  285.11  5347.2  285.12
#Mann= 3 ,-1 , 0
    4421     .16       0  5006.2     .07       0  5012.2     .16       0
Bank Sta=5006.2,5012.2
XS Rating Curve= 0 ,0
Exp/Cntr=0.3,0.1

Type RM Length L Ch R = 1 ,3128    ,489,489,489
BEGIN DESCRIPTION:
UNT060 IN BECR 7.0
END DESCRIPTION:
XS GIS Cut Line= 3
      3782749.64     10492210.21      3782349.61     10491860.19
      3782150.56     10491668.05
#Sta/Elev= 30
  4477.1  263.99  4604.8  251.21  4703.5  247.93  4852.5  250.02  4923.7  247.14
  4930.3  249.61  4937.9  247.92  4944.6  249.82  4952.2  248.66  4958.8  250.05
  4987.3   247.1  4991.9   240.7  4994.6   240.2  4997.9   240.7  5001.5  242.97
  5012.1  242.78  5015.7  248.21  5022.7  247.82  5029.9  254.16    5044  258.62
  5065.1  259.98  5072.3  263.15  5079.3  262.61  5086.5  265.35  5107.6  267.12
  5192.5  280.43  5199.7  280.15  5206.6  282.39  5234.9  285.58  5285.3  288.07
#Mann= 3 ,-1 , 0
  4477.1     .16       0  4991.9     .07       0  4997.9     .16       0
Bank Sta=4991.9,4997.9
XS Rating Curve= 0 ,0
Exp/Cntr=0.3,0.1

Type RM Length L Ch R = 1 ,2639    ,356,356,356
BEGIN DESCRIPTION:
UNT060 IN BECR 6.0
END DESCRIPTION:
XS GIS Cut Line= 4
      3783166.19     10492084.71      3782697.45     10491741.84
      3782684.43     10491459.72      3782298.16     10491155.91
#Sta/Elev= 30
  4294.5  289.26  4410.1   277.4    4431  277.09  4495.8   270.1  4566.9  266.03
  4602.4  262.53  4610.9  259.92    4617  262.66  4624.8  260.56  4631.7  261.27
  4717.4  256.33  4723.9  254.66  4761.1  252.78  4767.6  251.17  4810.6  248.89
  4934.4  245.56    4957  241.87    4967  244.19    4994  239.18  4996.8  238.68
    5000  239.18  5017.1   247.2  5107.1  246.09  5196.5  248.09  5246.2  253.29
  5289.5  260.27    5389  264.99  5494.7  278.73  5587.8  294.38  5649.1  299.25
#Mann= 3 ,-1 , 0
  4294.5     .16       0    4994     .07       0    5000     .16       0
Bank Sta=4994,5000
XS Rating Curve= 0 ,0
Exp/Cntr=0.3,0.1

Type RM Length L Ch R = 1 ,2283    ,543,543,543
BEGIN DESCRIPTION:
UNT060 IN BECR 5.0
END DESCRIPTION:
XS GIS Cut Line= 2
      3783296.47     10491733.93      3782515.78     10491074.68
#Sta/Elev= 30
  4551.5  293.22  4559.5  293.18    4566  291.05  4573.6  291.66  4615.5  282.73
  4644.1  278.36  4651.8  279.34  4679.2  274.35  4715.5  273.18  4722.1  271.58
  4729.8  272.52  4822.1  265.88  4963.9  251.95  4978.2  245.02  4984.7  244.32
    4996  239.81  4998.7  239.31    5002  239.81  5005.5  242.52  5013.3  244.58
  5027.6  246.02  5097.8  244.89  5119.9  245.96  5148.5  244.34    5155  242.07
  5162.6  242.54    5233  253.31  5403.4   263.1  5489.1  270.94  5573.3  282.71
#Mann= 3 ,-1 , 0
  4551.5     .16       0    4996     .07       0    5002     .16       0
Bank Sta=4996,5002
XS Rating Curve= 0 ,0
Exp/Cntr=0.3,0.1

Type RM Length L Ch R = 1 ,1740    ,442,442,442
BEGIN DESCRIPTION:
UNT060 IN BECR 4.0
END DESCRIPTION:
XS GIS Cut Line= 3
       3783349.6     10491210.18      3783199.61     10491060.19
      3782799.63      10490860.2
#Sta/Elev= 30
  4754.5  271.65  4768.6  270.59  4782.8     264  4796.9   263.5  4811.1  260.22
  4853.5   246.4  4881.8  240.41    4975  243.28  4997.4  239.37    5000  236.52
  5002.7  236.02    5006  236.52  5011.3  241.58  5019.7  242.83  5064.4  243.93
  5176.2  255.21  5198.6  260.79  5212.6  261.14    5221  264.53  5234.9  264.85
  5243.3  268.34  5257.3  268.72  5265.7   271.9  5271.3  270.59    5288  275.69
  5293.6  274.35  5310.4  279.01    5316  278.09  5355.1  287.92  5413.8  293.63
#Mann= 3 ,-1 , 0
  4754.5     .16       0    5000     .07       0    5006     .16       0
Bank Sta=5000,5006
XS Rating Curve= 0 ,0
Exp/Cntr=0.3,0.1

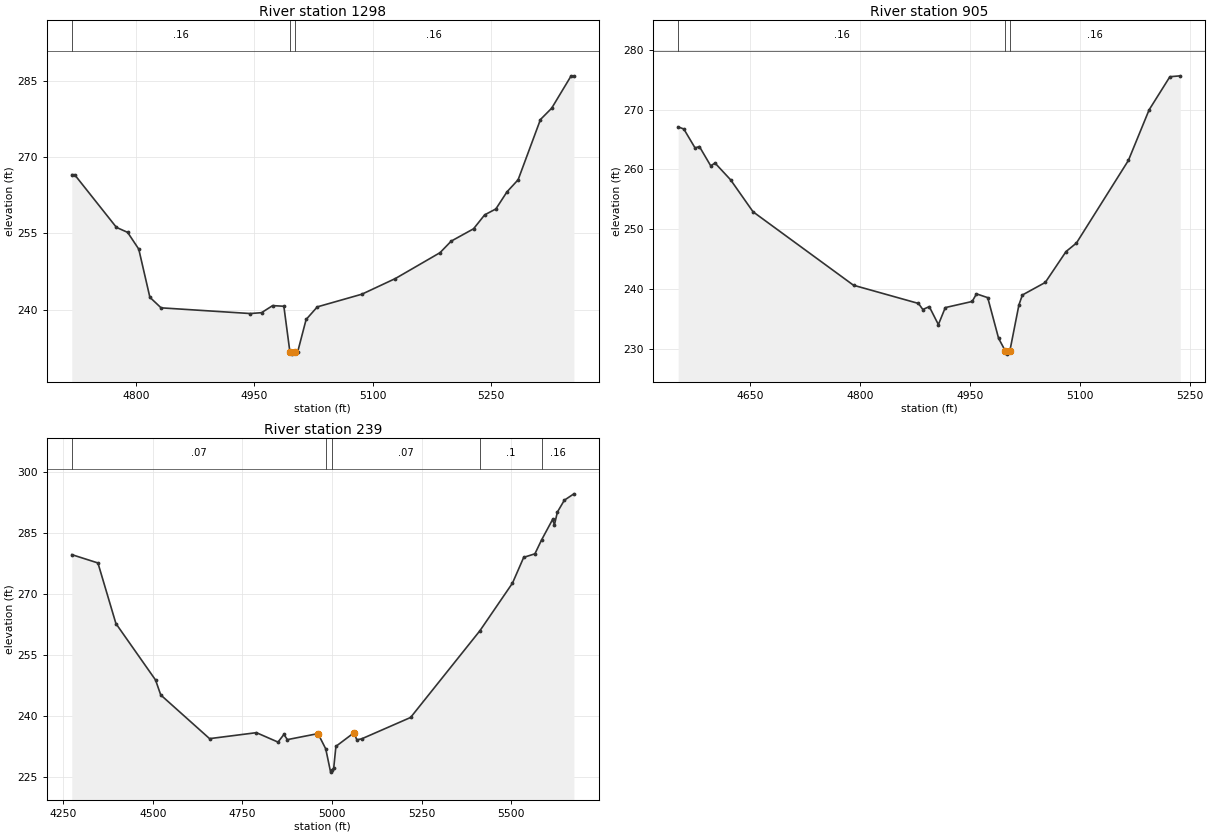
Type RM Length L Ch R = 1 ,1298    ,393,393,393
BEGIN DESCRIPTION:
UNT060 IN BECR 3.0
END DESCRIPTION:
XS GIS Cut Line= 3
      3783699.64     10490960.22      3783499.61     10490760.19
      3783249.64     10490510.22
#Sta/Elev= 30
  4718.5  266.51  4722.1  266.51  4775.1  256.16  4789.3  255.18  4803.4  251.89
  4817.5  242.43  4831.7  240.36  4944.8  239.24    4959  239.41  4973.1   240.8
  4987.3  240.67  4994.9  231.77  4997.6  231.27  5000.9  231.77  5004.9  231.77
  5015.5  238.07  5029.7  240.55  5086.2  243.04  5128.7  246.12  5185.2  251.19
  5199.4  253.46  5227.7  255.88  5241.8  258.62    5256  259.78  5270.1  263.14
  5284.2  265.51  5312.5  277.34  5326.7  279.56  5351.4  285.92  5354.9  285.92
#Mann= 3 ,-1 , 0
  4718.5     .16       0  4994.9     .07       0  5000.9     .16       0
Bank Sta=4994.9,5000.9
XS Rating Curve= 0 ,0
Exp/Cntr=0.3,0.1

Type RM Length L Ch R = 1 ,905     ,666,666,666
BEGIN DESCRIPTION:
UNT060 IN BECR 2.0
END DESCRIPTION:
XS GIS Cut Line= 3
      3783949.63     10490810.22      3783699.61     10490410.19
      3783549.58     10490260.16
#Sta/Elev= 30
  4552.5  267.11  4560.2  266.75  4575.5  263.59  4581.4  263.83  4596.8  260.61
  4602.7  261.07  4623.9  258.27  4654.5  252.93  4791.3  240.67  4879.8  237.63
  4885.7  236.62  4894.5   237.1  4906.9   234.1  4916.3  236.94  4952.9  237.96
  4958.8  239.23  4974.1   238.6  4988.9  231.81  4998.2  229.67    5001  229.17
  5004.2  229.67  5016.6  237.39  5021.3  239.04  5052.5  241.14  5080.8   246.3
  5094.9  247.71  5165.7  261.51  5193.9  269.95  5222.2  275.48  5236.4  275.63
#Mann= 3 ,-1 , 0
  4552.5     .16       0  4998.2     .07       0  5004.2     .16       0
Bank Sta=4998.2,5004.2
XS Rating Curve= 0 ,0
Exp/Cntr=0.3,0.1

Type RM Length L Ch R = 1 ,239     ,0,0,0
BEGIN DESCRIPTION:
UNT060 IN BECR 1.0
END DESCRIPTION:
XS GIS Cut Line= 4
      3784259.98     10490622.79      3784199.22     10490032.52
      3783964.84     10489720.02      3783565.54     10489598.49
#Sta/Elev= 30
  4273.6  279.66  4346.6  277.61  4396.8   262.7  4507.4  248.81  4521.9  245.13
  4658.2  234.38  4788.9  235.85  4849.2  233.53  4865.6  235.41  4875.4  234.14
  4960.8  235.62  4982.4  231.86    4996  226.14  4999.2  226.64  5004.6  227.08
  5010.8  232.48  5060.8   235.8  5069.2   234.1  5082.4  234.32  5219.2  239.59
  5412.9  260.96  5503.5  272.64  5534.9  278.99  5566.2  279.86  5584.6  283.25
  5615.5  288.31  5620.7     287  5628.9  290.13  5648.3  293.05    5675  294.62
#Mann= 5 ,-1 , 0
  4273.6     .07       0  4982.4     .05       0  4999.2     .07       0
  5412.9      .1       0  5584.6     .16       0
Bank Sta=4960.8,5060.8
XS Rating Curve= 0 ,0
Exp/Cntr=0.3,0.1

Chan Stop Cuts=-1
Use User Specified Reach Order=0
Composite Channel Slope=5