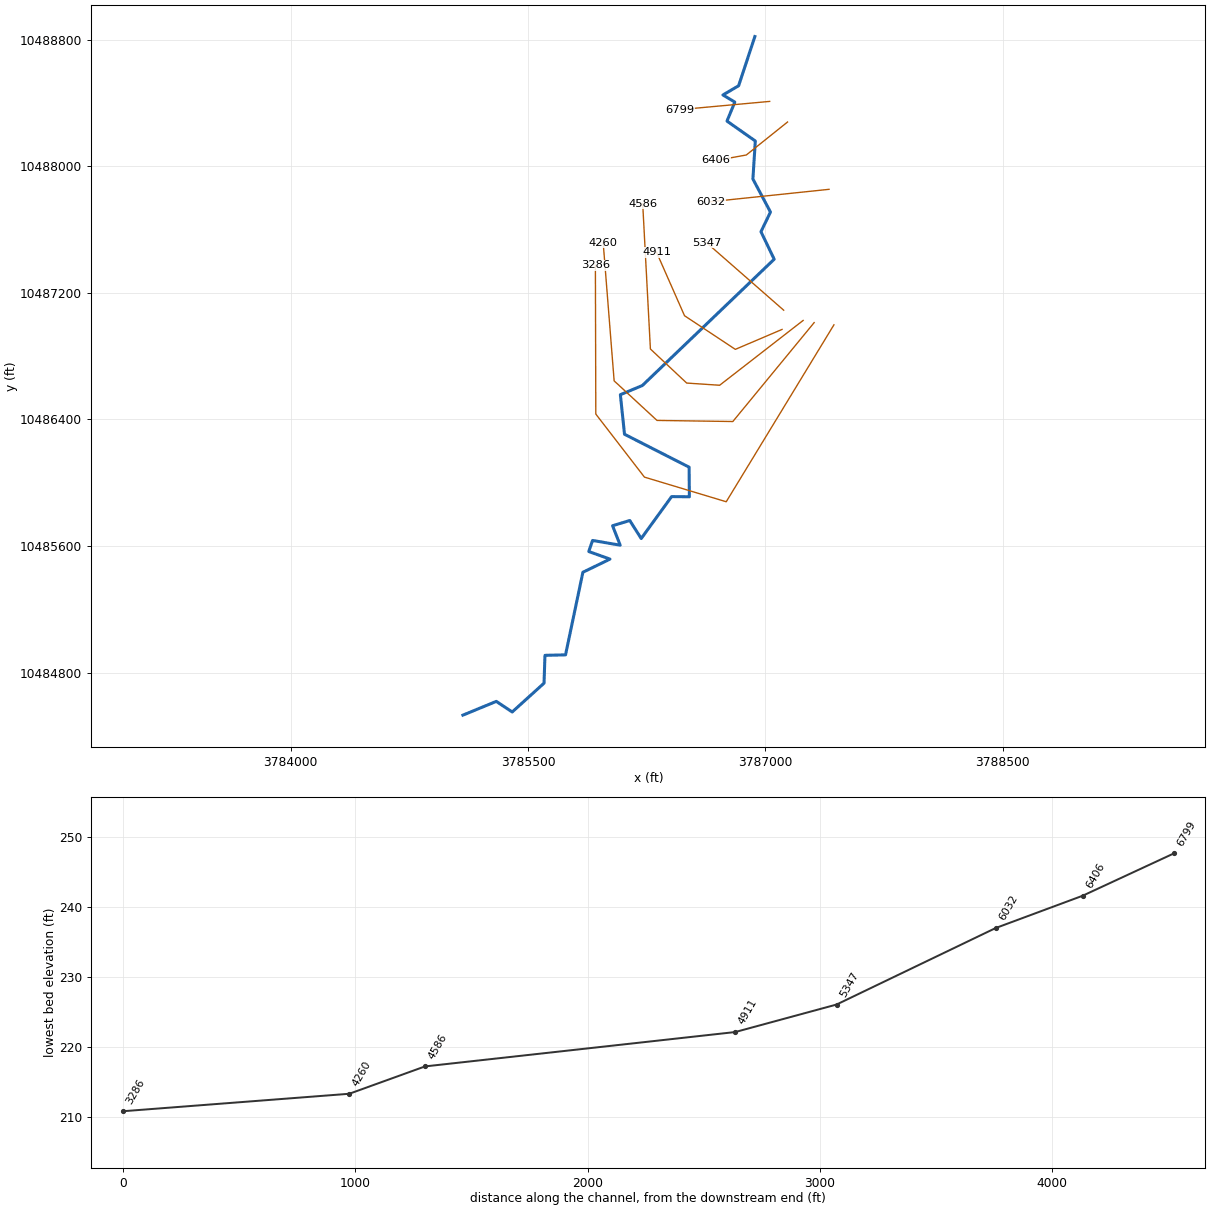
--- UNT061 IN BECR.prj (project) ---

Proj Title=UNT061 IN BECR Base Level Engineering
Current Plan=p01
Default Exp/Contr=0.3,0.1
English Units
Geom File=g01
Flow File=f01
Plan File=p01
Y Axis Title=Elevation
X Axis Title(PF)=Main Channel Distance
X Axis Title(XS)=Station
BEGIN DESCRIPTION:
UNT061 IN BECR
END DESCRIPTION:
DSS Export Rating Curves= 0
DSS Export Rating Curve Sorted= 0
DSS Export Volume Flow Curves= 0
DXF OffsetX= 0
DXF OffsetY= 0
DXF ScaleX= 1
DXF ScaleY= 10

--- UNT061 IN BECR.p01 (plan) ---

Plan Title=Multiple Run
Short Identifier=Multiple
Geom File=g01
Flow File=f01
Subcritical Flow
K Sum by GR= 0
Std Step Tol= 0.01
Critical Tol= 0.01
Num of Std Step Trials= 20
Max Error Tol= 0.3
Flow Tol Ratio= 0.001
Split Flow NTrial= 30
Split Flow Tol= 0.02
Split Flow Ratio= 0.02
Log Output Level= 0
Friction Slope Method= 1
Unsteady Friction Slope Method= 2
Unsteady Bridges Friction Slope Method= 1
Parabolic Critical Depth
Global Vel Dist=  1 , 1 , 1
Global Log Level= 0
CheckData=True
Encroach Param= -1, 0, 0, 0
BEGIN DESCRIPTION:
Multiple Run
END DESCRIPTION:

--- UNT061 IN BECR.f01 (steady flow) ---

Flow Title=Multiple
Program Version=4.10
Number of Profiles= 7
Profile Names=10-year,25-year,50-year,1pct_min,100-year,1pct_plu,500-year
River Rch & RM=UNT061 IN BECR,Reach-1         ,6799
     255     325     379     326     441     596     597
Boundary for River Rch & Prof#=UNT061 IN BECR,Reach-1         , 1
Up Type= 0
Dn Type= 3
Dn Slope=0.009
Boundary for River Rch & Prof#=UNT061 IN BECR,Reach-1         , 2
Up Type= 0
Dn Type= 3
Dn Slope=0.009
Boundary for River Rch & Prof#=UNT061 IN BECR,Reach-1         , 3
Up Type= 0
Dn Type= 3
Dn Slope=0.009
Boundary for River Rch & Prof#=UNT061 IN BECR,Reach-1         , 4
Up Type= 0
Dn Type= 3
Dn Slope=0.009
Boundary for River Rch & Prof#=UNT061 IN BECR,Reach-1         , 5
Up Type= 0
Dn Type= 3
Dn Slope=0.009
Boundary for River Rch & Prof#=UNT061 IN BECR,Reach-1         , 6
Up Type= 0
Dn Type= 3
Dn Slope=0.009
Boundary for River Rch & Prof#=UNT061 IN BECR,Reach-1         , 7
Up Type= 0
Dn Type= 3
Dn Slope=0.009
DSS Import GetInterval= 0
DSS Import GetPeak= 0
DSS Import FillOption= 0

--- UNT061 IN BECR.g01 (geometry) ---

Geom Title=Existing Conditions
Program Version=4.10

River Reach=UNT061 IN BECR  ,Reach-1
Reach XY= 30
      3786933.68     10488819.09        3786831.       10488508.
      3786731.75       10488450.        3786807.       10488405.
       3786757.5       10488285.       3786936.5       10488159.
      3786921.25       10487919.      3787032.25       10487710.
      3786972.25       10487586.      3787055.75       10487412.
      3786222.75       10486614.      3786083.75       10486556.
        3786110.       10486306.      3786518.25       10486098.
      3786519.75       10485911.       3786407.5       10485912.
       3786215.5       10485647.      3786143.25       10485761.
       3786034.5       10485728.      3786082.75       10485605.
      3785908.25       10485635.        3785884.       10485565.
      3786018.25       10485517.        3785847.       10485434.
      3785737.25       10484912.      3785607.25       10484909.
       3785601.5       10484733.      3785400.25       10484551.
      3785299.75       10484618.      3785088.75       10484531.

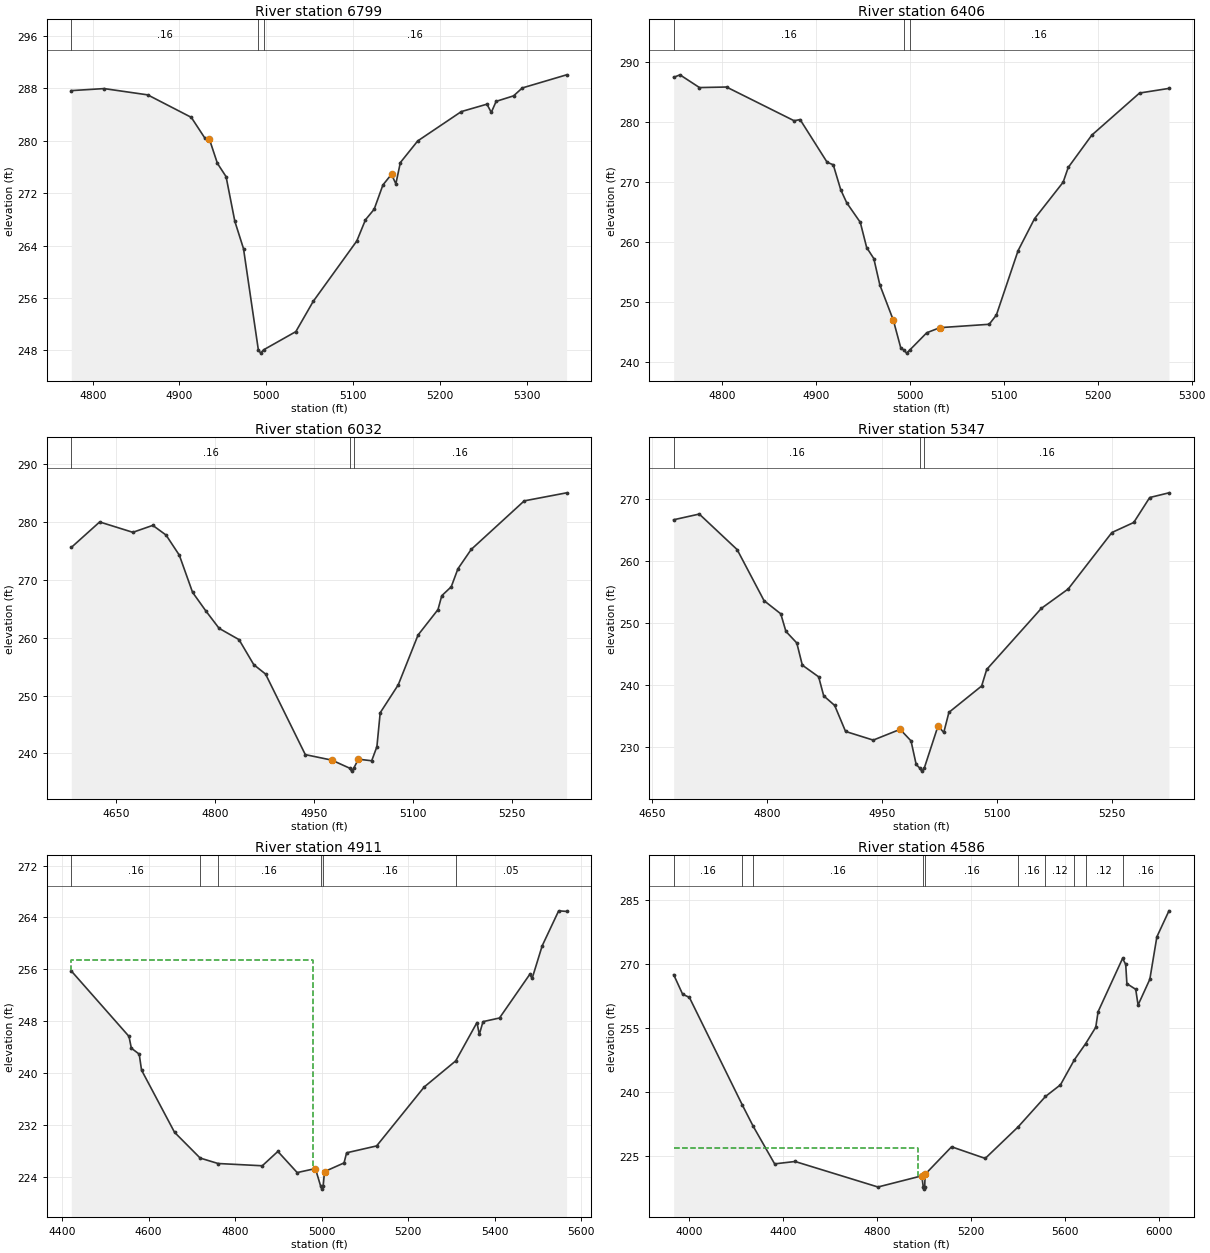
Type RM Length L Ch R = 1 ,6799    ,393,393,393
BEGIN DESCRIPTION:
UNT061 IN BECR 6.0
END DESCRIPTION:
XS GIS Cut Line= 2
      3787027.29      10488409.3      3786458.77     10488357.22
#Sta/Elev= 30
  4775.3  287.66  4813.1  287.97  4863.4  287.01  4913.6  283.58  4929.3   280.4
  4934.3  280.32  4943.7  276.56  4953.7  274.53  4963.8  267.71  4973.8  263.53
  4990.9  248.09  4993.6  247.59  4996.9  248.09  5034.1  250.87  5054.1  255.48
  5104.4  264.71  5114.4  267.95  5124.4  269.55  5134.5  273.26  5144.4  274.89
  5149.4  273.43  5154.6  276.68  5174.6  279.98  5224.9  284.46  5254.4  285.59
  5259.4  284.33    5265  286.02  5285.1  286.86  5295.2  288.07  5346.2  290.07
#Mann= 3 ,-1 , 0
  4775.3     .16       0  4990.9     .07       0  4996.9     .16       0
Bank Sta=4934.3,5144.4
XS Rating Curve= 0 ,0
Exp/Cntr=0.3,0.1

Type RM Length L Ch R = 1 ,6406    ,374,374,374
BEGIN DESCRIPTION:
UNT061 IN BECR 5.0
END DESCRIPTION:
XS GIS Cut Line= 3
      3787140.16     10488279.08      3786879.75     10488070.76
      3786688.76     10488036.03
#Sta/Elev= 30
  4748.2  287.45  4754.9  287.87  4775.7  285.75  4804.5  285.84  4876.5  280.23
  4882.9  280.42  4911.7  273.31  4918.2   272.9  4926.2  268.73  4932.6  266.56
    4947  263.32  4953.8  259.12  4961.4  257.29  4967.8  252.92  4982.2  247.03
  4990.2  242.38  4993.6  242.05  4996.3  241.55  4999.6  242.05  5017.8  244.94
  5031.8  245.79  5084.3  246.35    5092   247.9  5115.1  258.61  5132.6  263.92
  5163.1     270  5168.5  272.45  5193.6  277.83  5244.5  284.84  5275.8  285.61
#Mann= 3 ,-1 , 0
  4748.2     .16       0  4993.6     .07       0  4999.6     .16       0
Bank Sta=4982.2,5031.8
XS Rating Curve= 0 ,0
Exp/Cntr=0.3,0.1

Type RM Length L Ch R = 1 ,6032    ,685,685,685
BEGIN DESCRIPTION:
UNT061 IN BECR 4.0
END DESCRIPTION:
XS GIS Cut Line= 2
      3787402.39      10487853.7      3786655.77     10487775.57
#Sta/Elev= 30
  4581.7  275.58  4624.7  279.98    4675  278.19  4705.2  279.39  4725.3  277.72
  4745.4  274.25  4765.5  267.83  4785.6  264.62  4805.7  261.61  4835.9  259.66
  4858.3  255.33  4876.1  253.72  4936.4   239.8  4976.6  238.85  5003.8  237.45
  5006.5  236.95  5009.8  237.45  5016.8  239.01    5037  238.74  5044.9  241.17
  5049.9  247.03  5077.2  251.84  5107.3  260.46  5137.5  264.85  5143.2  267.24
  5157.6  268.79  5167.7  271.89  5187.8  275.23  5268.2  283.62  5332.4  285.01
#Mann= 3 ,-1 , 0
  4581.7     .16       0  5003.8     .07       0  5009.8     .16       0
Bank Sta=4976.6,5016.8
XS Rating Curve= 0 ,0
Exp/Cntr=0.3,0.1

Type RM Length L Ch R = 1 ,5347    ,436,436,436
BEGIN DESCRIPTION:
UNT061 IN BECR 3.0
END DESCRIPTION:
XS GIS Cut Line= 2
      3787115.91     10487089.79      3786629.75     10487515.18
#Sta/Elev= 30
  4678.1  266.64  4711.5  267.56  4760.9  261.82    4796  253.57  4817.8  251.45
  4824.5  248.61  4838.7  246.74  4845.9  243.16  4867.2  241.27  4873.8   238.2
  4888.1  236.65  4902.3  232.45  4938.4  231.05  4973.5  232.79  4987.7  230.92
  4994.4  227.12    4999  226.54  5001.7  226.04    5005  226.54  5022.9  233.33
  5030.4  232.28  5037.1  235.53  5079.8  239.79  5086.4  242.46  5157.6  252.32
  5192.7  255.46  5249.7  264.58  5278.2   266.2    5299  270.23  5324.1  270.99
#Mann= 3 ,-1 , 0
  4678.1     .16       0    4999     .07       0    5005     .16       0
Bank Sta=4973.5,5022.9
XS Rating Curve= 0 ,0
Exp/Cntr=0.3,0.1

Type RM Length L Ch R = 1 ,4911    ,1335,1335,1335
BEGIN DESCRIPTION:
UNT061 IN BECR 2.0
END DESCRIPTION:
XS GIS Cut Line= 4
      3787105.42     10486968.32      3786810.31     10486842.46
      3786489.13     10487055.13      3786311.97     10487456.98
#Sta/Elev= 30
  4421.3  255.75  4554.7  245.66  4560.1  243.85  4578.3  242.93  4583.7  240.47
    4660  230.88  4719.2  226.91  4760.6  226.07  4862.9  225.72  4898.9  227.93
  4943.6  224.67  4985.7  225.29  4997.7  222.62  5000.5  222.12  5003.7  222.62
  5006.8  224.82  5051.9  226.16  5057.9  227.72  5127.3  228.78  5237.2  237.86
  5310.2  241.89  5359.3   247.8  5364.7  245.97  5373.3  247.94  5411.4   248.5
  5481.4  255.23  5486.8  254.59  5510.1  259.63  5548.2  265.02  5566.5  264.93
#Mann= 6 ,-1 , 0
  4421.3     .16       0  4719.2     .05       0  4760.6     .16       0
  4997.7     .07       0  5003.7     .16       0  5310.2     .05       0
#XS Ineff= 2 , 0
          4980.9  257.41
Permanent Ineff=
       F       F
Bank Sta=4985.7,5006.8
XS Rating Curve= 0 ,0
Exp/Cntr=0.3,0.1

Type RM Length L Ch R = 1 ,4586    ,326,326,326
BEGIN DESCRIPTION:
Mapping XS 195121be
END DESCRIPTION:
XS GIS Cut Line= 5
      3787238.84     10487025.32       3786711.1     10486615.62
      3786502.77     10486629.51       3786273.6     10486844.79
      3786224.99     10487761.48
#Sta/Elev= 30
  3933.9  267.58    3972     263  4000.9  262.23  4226.9  236.91  4272.5  231.99
  4363.9  223.15  4450.8  223.71  4803.9  217.72  4990.5  220.34    4997  217.72
  4999.8  217.22    5003  217.72  5004.7  220.69  5117.5  227.16  5260.8  224.43
    5401  231.84  5517.4  238.98  5581.3  241.72  5640.6  247.61  5688.1  251.35
  5731.5  255.23  5741.5  258.89  5845.7   271.4  5859.1     270  5864.1  265.46
  5901.7  264.14  5911.7  260.45  5961.8   266.5  5991.8  276.46  6043.2  282.57
#Mann= 10 ,-1 , 0
  3933.9     .16       0  4226.9     .05       0  4272.5     .16       0
    4997     .07       0    5003     .16       0    5401     .16       0
  5517.4     .12       0  5640.6     .16       0  5688.1     .12       0
  5845.7     .16       0
#XS Ineff= 2 , 0
         4976.14  226.83
Permanent Ineff=
       F       F
Bank Sta=4990.5,5004.7
XS Rating Curve= 0 ,0
Exp/Cntr=0.3,0.1

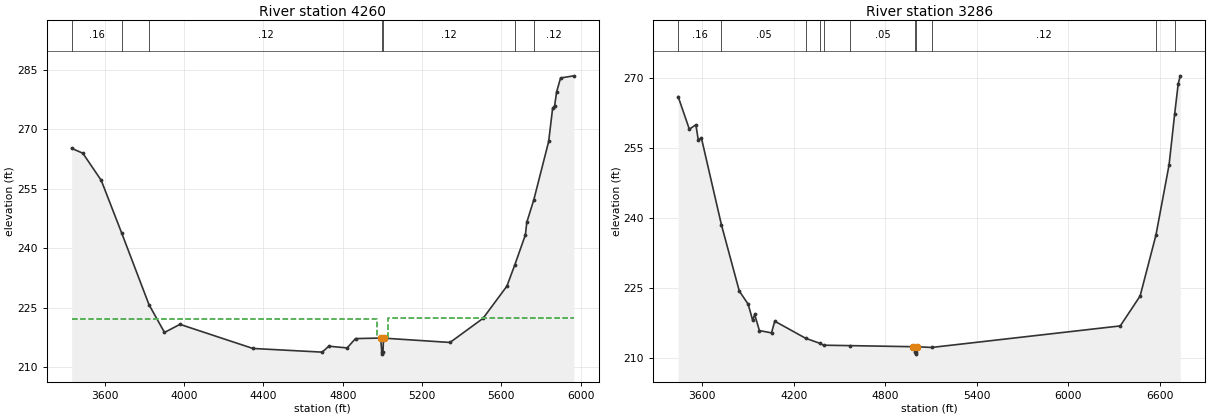
Type RM Length L Ch R = 1 ,4260    ,974,974,974
BEGIN DESCRIPTION:
Mapping XS d1ac9175
END DESCRIPTION:
XS GIS Cut Line= 5
      3787308.34     10487011.47      3786794.44     10486386.46
      3786315.27      10486393.4      3786044.44      10486643.4
      3785975.12     10487516.79
#Sta/Elev= 30
  3432.7  265.16  3489.2  263.91  3581.8   257.1  3685.2   243.8  3822.8  225.78
    3901  218.78  3979.2  220.82  4346.7  214.75  4696.7  213.82  4729.7  215.32
  4822.1  214.88  4864.6  217.23  4991.6  217.37    4997  213.82  4999.8  213.32
    5003  213.82  5005.8  217.35  5341.3  216.26  5507.8  222.33  5628.1  230.44
  5668.3  235.84  5721.5  243.36  5728.4  246.51  5763.9  252.18  5838.8  266.88
  5858.9  275.26  5868.9  275.86  5878.9  279.37    5899  282.87  5965.8  283.41
#Mann= 7 ,-1 , 0
  3432.7     .16       0  3685.2     .05       0  3822.8     .12       0
    4997     .07       0    5003     .12       0  5668.3     .16       0
  5763.9     .12       0
#XS Ineff= 2 , 0
         4972.16  222.27 5030.11          222.37
Permanent Ineff=
       F       F
Bank Sta=4991.6,5005.8
XS Rating Curve= 0 ,0
Exp/Cntr=0.3,0.1

Type RM Length L Ch R = 1 ,3286    ,0,0,0
BEGIN DESCRIPTION:
UNT061 IN BECR 1.0
END DESCRIPTION:
XS GIS Cut Line= 5
       3787433.3     10486997.53      3786752.77     10485879.51
      3786235.88     10486035.18      3785928.58     10486433.62
      3785925.98     10487373.77
#Sta/Elev= 30
  3442.3  265.96    3516  258.97  3558.6  259.93  3574.1  256.75  3595.4  257.04
  3726.3   238.5  3843.4  224.33  3901.5  221.52  3930.9  218.07  3944.1  219.32
  3975.1  215.87  4054.5  215.38  4075.8  217.88  4277.9  214.23  4374.3  213.11
  4395.6  212.74  4567.3  212.65  4978.9  212.42    4997  211.33  4999.8  210.83
    5003  211.33  5005.1  212.41    5104  212.26  6340.7  216.87  6470.7  223.26
  6574.6  236.31  6660.7  251.35  6697.4  262.26  6720.7  268.73  6734.3   270.4
#Mann= 11 ,-1 , 0
  3442.3     .16       0  3726.3     .05       0  4277.9     .12       0
  4374.3     .05       0  4395.6     .12       0  4567.3     .05       0
    4997     .03       0    5003     .05       0    5104     .12       0
  6574.6     .16       0  6697.4     .12       0
Bank Sta=4978.9,5005.1
XS Rating Curve= 0 ,0
Exp/Cntr=0.3,0.1

Chan Stop Cuts=-1
Use User Specified Reach Order=0
Composite Channel Slope=5