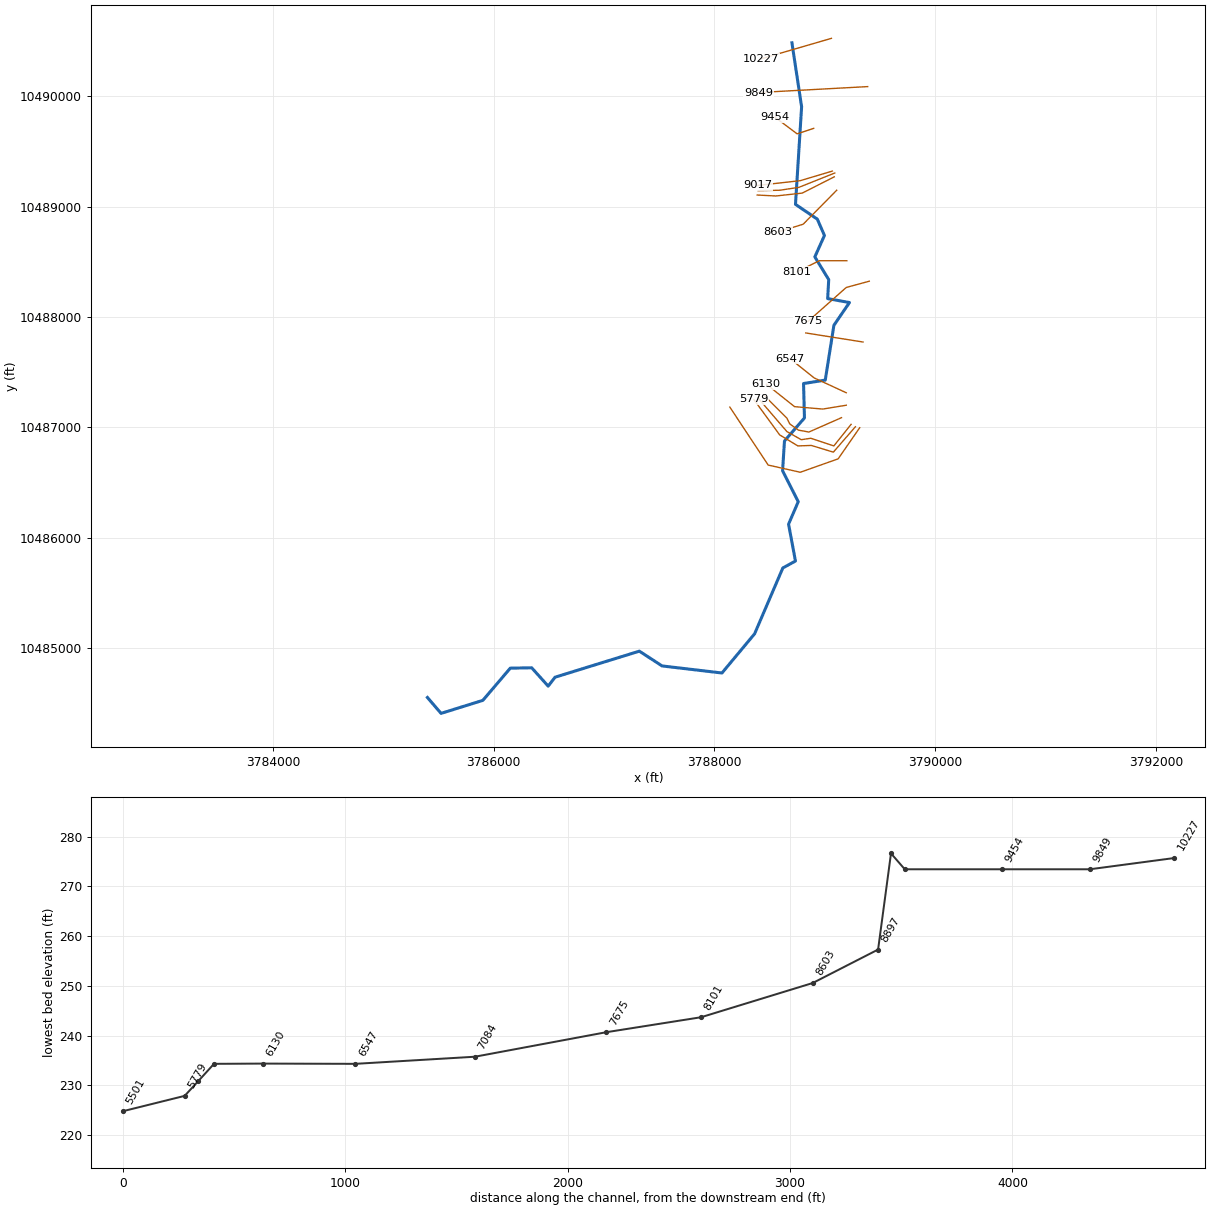
--- UNT062 IN BECR.prj (project) ---

Proj Title=UNT062 IN BECR Base Level Engineering
Current Plan=p01
Default Exp/Contr=0.3,0.1
English Units
Geom File=g01
Flow File=f01
Plan File=p01
Y Axis Title=Elevation
X Axis Title(PF)=Main Channel Distance
X Axis Title(XS)=Station
BEGIN DESCRIPTION:
UNT062 IN BECR
END DESCRIPTION:
DSS Export Rating Curves= 0
DSS Export Rating Curve Sorted= 0
DSS Export Volume Flow Curves= 0
DXF OffsetX= 0
DXF OffsetY= 0
DXF ScaleX= 1
DXF ScaleY= 10

--- UNT062 IN BECR.p01 (plan) ---

Plan Title=Multiple Run
Short Identifier=Multiple
Geom File=g01
Flow File=f01
Subcritical Flow
K Sum by GR= 0
Std Step Tol= 0.01
Critical Tol= 0.01
Num of Std Step Trials= 20
Max Error Tol= 0.3
Flow Tol Ratio= 0.001
Split Flow NTrial= 30
Split Flow Tol= 0.02
Split Flow Ratio= 0.02
Log Output Level= 0
Friction Slope Method= 1
Unsteady Friction Slope Method= 2
Unsteady Bridges Friction Slope Method= 1
Parabolic Critical Depth
Global Vel Dist=  1 , 1 , 1
Global Log Level= 0
CheckData=True
Encroach Param= -1, 0, 0, 0
BEGIN DESCRIPTION:
Multiple Run
END DESCRIPTION:

--- UNT062 IN BECR.f01 (steady flow) ---

Flow Title=Multiple
Program Version=4.10
Number of Profiles= 7
Profile Names=10-year,25-year,50-year,1pct_min,100-year,1pct_plu,500-year
River Rch & RM=UNT062 IN BECR,Reach-1         ,10227
     361     471     558     487     659     891     919
Boundary for River Rch & Prof#=UNT062 IN BECR,Reach-1         , 1
Up Type= 0
Dn Type= 3
Dn Slope=0.005
Boundary for River Rch & Prof#=UNT062 IN BECR,Reach-1         , 2
Up Type= 0
Dn Type= 3
Dn Slope=0.005
Boundary for River Rch & Prof#=UNT062 IN BECR,Reach-1         , 3
Up Type= 0
Dn Type= 3
Dn Slope=0.005
Boundary for River Rch & Prof#=UNT062 IN BECR,Reach-1         , 4
Up Type= 0
Dn Type= 3
Dn Slope=0.005
Boundary for River Rch & Prof#=UNT062 IN BECR,Reach-1         , 5
Up Type= 0
Dn Type= 3
Dn Slope=0.005
Boundary for River Rch & Prof#=UNT062 IN BECR,Reach-1         , 6
Up Type= 0
Dn Type= 3
Dn Slope=0.005
Boundary for River Rch & Prof#=UNT062 IN BECR,Reach-1         , 7
Up Type= 0
Dn Type= 3
Dn Slope=0.005
DSS Import GetInterval= 0
DSS Import GetPeak= 0
DSS Import FillOption= 0

--- UNT062 IN BECR.g01 (geometry) ---

Geom Title=Existing Conditions
Program Version=4.10

River Reach=UNT062 IN BECR  ,Reach-1
Reach XY= 30
      3788702.27     10490485.45        3788790.       10489906.
       3788734.5       10489021.      3788932.25       10488887.
        3788997.       10488739.      3788909.75       10488545.
       3789035.5       10488339.        3789026.       10488167.
      3789223.25       10488131.       3789082.5       10487925.
      3789004.25       10487428.       3788807.5       10487397.
      3788815.75       10487085.      3788634.75       10486876.
       3788617.5       10486606.       3788759.5       10486326.
      3788671.75       10486122.      3788734.25       10485788.
      3788619.75       10485725.        3788364.       10485128.
       3788068.5       10484773.        3787526.       10484837.
        3787320.       10484971.      3786556.75       10484735.
        3786494.       10484654.        3786345.       10484820.
        3786151.       10484817.      3785902.25       10484525.
      3785523.75       10484407.      3785400.25       10484551.

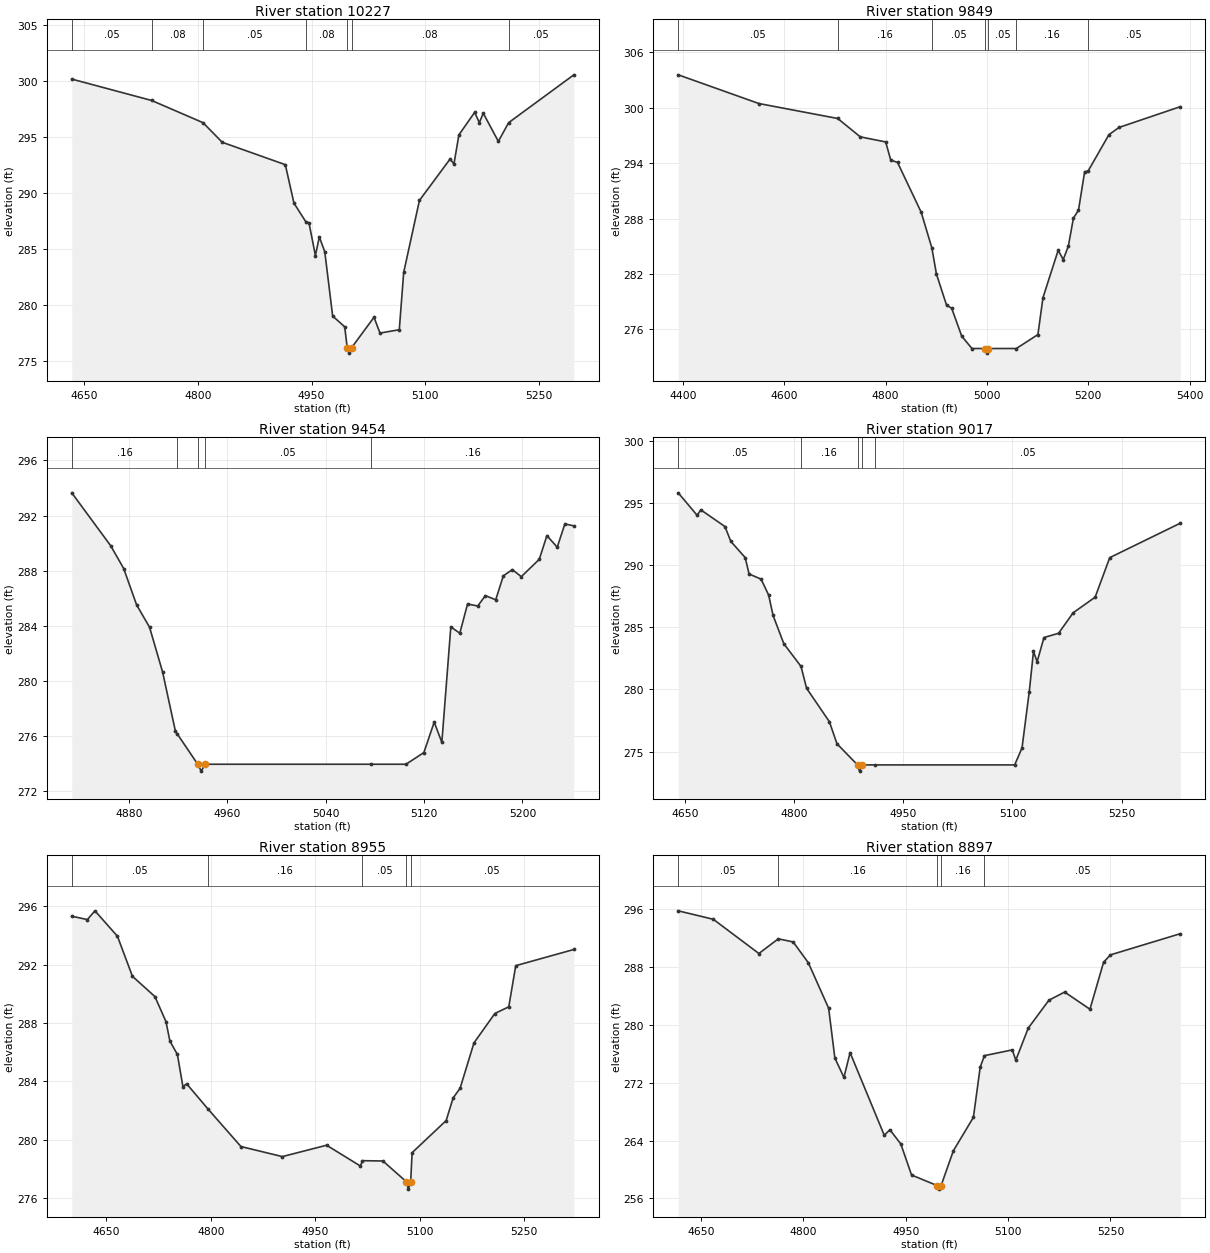
Type RM Length L Ch R = 1 ,10227   ,378,378,378
BEGIN DESCRIPTION:
UNT062 IN BECR 9.0
END DESCRIPTION:
XS GIS Cut Line= 2
      3789060.37     10490526.11      3788423.87     10490340.53
#Sta/Elev= 30
  4633.3  300.14  4738.8  298.23  4806.6  296.25    4832   294.5  4915.3   292.5
  4926.7  289.07  4942.4   287.4  4946.6   287.3    4955  284.39  4960.2  286.05
  4967.4  284.73  4977.8  278.99  4993.7  278.03    4997  276.18  4999.8  275.68
    5003  276.18  5032.4  278.88  5040.3  277.47  5065.8  277.77  5071.6  282.88
  5092.4  289.31  5132.8     293    5138  292.57  5144.5  295.16  5165.3  297.17
  5171.5  296.25  5176.7  297.09  5196.6  294.58  5210.2  296.25  5296.3  300.52
#Mann= 7 ,-1 , 0
  4633.3     .05       0  4738.8     .08       0  4806.6     .05       0
  4942.4     .08       0    4997     .07       0    5003     .08       0
  5210.2     .05       0
Bank Sta=4997,5003
XS Rating Curve= 0 ,0
Exp/Cntr=0.3,0.1

Type RM Length L Ch R = 1 ,9849    ,395,395,395
BEGIN DESCRIPTION:
Mapping XS 69afcc9e
END DESCRIPTION:
XS GIS Cut Line= 2
      3789388.53     10490088.61      3788398.89     10490034.78
#Sta/Elev= 30
  4390.6  303.58  4549.8  300.47  4705.4  298.85    4750  296.86  4800.1  296.31
  4810.1  294.34  4823.5  294.09  4870.2  288.69  4891.2  284.84  4900.3     282
  4920.3  278.62  4930.3   278.3  4950.3  275.26  4970.4  273.93    4997  273.93
  4999.8  273.43    5003  273.93    5058  273.93  5100.6  275.44  5110.6  279.44
  5140.6  284.57  5150.6  283.57  5160.7  285.02  5170.7  288.06  5180.7  288.91
  5192.9   293.1  5199.3  293.12  5240.8   297.1  5260.8  297.88  5381.7  300.13
#Mann= 7 ,-1 , 0
  4390.6     .05       0  4705.4     .16       0  4891.2     .05       0
    4997    .033       0    5003     .05       0    5058     .16       0
  5199.3     .05       0
Bank Sta=4997,5003
XS Rating Curve= 0 ,0
Exp/Cntr=0.3,0.1

Type RM Length L Ch R = 1 ,9454    ,437,437,437
BEGIN DESCRIPTION:
UNT062 IN BECR 8.0
END DESCRIPTION:
XS GIS Cut Line= 3
      3788899.61     10489710.19      3788749.61     10489660.19
      3788549.62     10489810.18
#Sta/Elev= 30
  4833.7  293.65  4865.3  289.81  4875.9  288.15  4886.4  285.51  4896.9  283.89
  4907.5  280.64    4918  276.31  4919.4  276.14  4936.1  273.93  4938.9  273.43
  4942.1  273.93  5077.2  273.93  5105.4  273.93  5119.9  274.78  5128.3  276.99
  5134.5  275.52  5141.8  283.91  5149.1  283.45  5155.4  285.57  5163.7  285.43
  5169.9  286.18  5178.3  285.88  5184.5  287.62  5191.8  288.07  5199.1  287.56
  5213.7  288.82  5219.9  290.54  5228.3   289.7  5234.5  291.39  5241.8  291.25
#Mann= 5 ,-1 , 0
  4833.7     .16       0  4919.4     .05       0  4936.1    .033       0
  4942.1     .05       0  5077.2     .16       0
Bank Sta=4936.1,4942.1
XS Rating Curve= 0 ,0
Exp/Cntr=0.3,0.1

Type RM Length L Ch R = 1 ,9017    ,62,62,62
BEGIN DESCRIPTION:
Mapping XS 65c1f774
END DESCRIPTION:
XS GIS Cut Line= 3
      3789068.85     10489322.78      3788778.01     10489235.96
      3788393.15     10489192.72
#Sta/Elev= 30
  4640.1   295.8    4666     294  4671.2  294.43  4704.4  293.09  4712.4   291.9
  4732.3  290.59  4737.5  289.28  4754.1  288.86  4764.5  287.58  4770.6  285.94
  4785.4  283.67    4809  281.85  4816.7  280.09    4848  277.41  4858.5  275.63
  4886.8  273.93  4889.5  273.43  4892.8  273.93    4911  273.93    5103  273.93
  5113.1  275.29  5123.1  279.83  5128.9  283.06  5133.9  282.22  5143.3  284.17
  5163.4  284.51  5183.5  286.16  5213.7  287.41  5233.8  290.59  5330.9  293.36
#Mann= 5 ,-1 , 0
  4640.1     .05       0    4809     .16       0  4886.8    .033       0
  4892.8     .16       0    4911     .05       0
Bank Sta=4886.8,4892.8
XS Rating Curve= 0 ,0
Exp/Cntr=0.3,0.1

Type RM Length L Ch R = 1 ,8955    ,58,58,58
BEGIN DESCRIPTION:
Mapping XS 37dfb03b
END DESCRIPTION:
XS GIS Cut Line= 4
      3789090.54     10489305.42      3788764.99      10489175.2
      3788591.38     10489149.16      3788396.11     10489144.82
#Sta/Elev= 30
  4600.1  295.33  4622.5   295.1  4633.4   295.7  4665.7  293.96  4687.3  291.21
  4719.6  289.82  4735.5   288.1  4741.1  286.77  4751.9  285.85  4759.8  283.65
  4765.2  283.84  4796.1   282.1  4843.2  279.54  4902.7  278.85  4966.3  279.63
    5015   278.2  5017.7  278.57  5047.2  278.55  5081.1  277.12  5083.8  276.62
  5087.1  277.12  5089.2  279.12  5138.1  281.32  5148.1  282.87  5158.1  283.53
  5178.1  286.65  5208.1  288.66  5228.1  289.12  5238.1  291.94  5321.6  293.05
#Mann= 5 ,-1 , 0
  4600.1     .05       0  4796.1     .16       0  5017.7     .05       0
  5081.1     .07       0  5087.1     .05       0
Bank Sta=5081.1,5087.1
XS Rating Curve= 0 ,0
Exp/Cntr=0.3,0.1

Type RM Length L Ch R = 1 ,8897    ,294,294,294
BEGIN DESCRIPTION:
UNT062 IN BECR 7.0
END DESCRIPTION:
XS GIS Cut Line= 4
      3789086.14     10489270.67      3788795.37     10489123.11
      3788556.65     10489097.07      3788387.38     10489105.75
#Sta/Elev= 30
  4616.7  295.76  4668.1  294.59  4734.9  289.86  4763.3  291.89  4785.1  291.46
  4807.3  288.59  4837.1  282.29  4846.2  275.42  4859.5  272.73  4868.5  276.16
  4918.6  264.73  4926.8   265.5  4942.8  263.54  4958.6  259.24  4995.9  257.79
  4998.6  257.29  5001.9  257.79  5019.9   262.6  5049.2  267.21  5059.2  274.16
  5065.4  275.74  5106.3  276.54  5111.3  275.11  5129.6  279.55  5159.8   283.4
  5182.9  284.53    5220  282.16    5240  288.66    5250  289.67  5352.4   292.6
#Mann= 5 ,-1 , 0
  4616.7     .05       0  4763.3     .16       0  4995.9     .07       0
  5001.9     .16       0  5065.4     .05       0
Bank Sta=4995.9,5001.9
XS Rating Curve= 0 ,0
Exp/Cntr=0.3,0.1

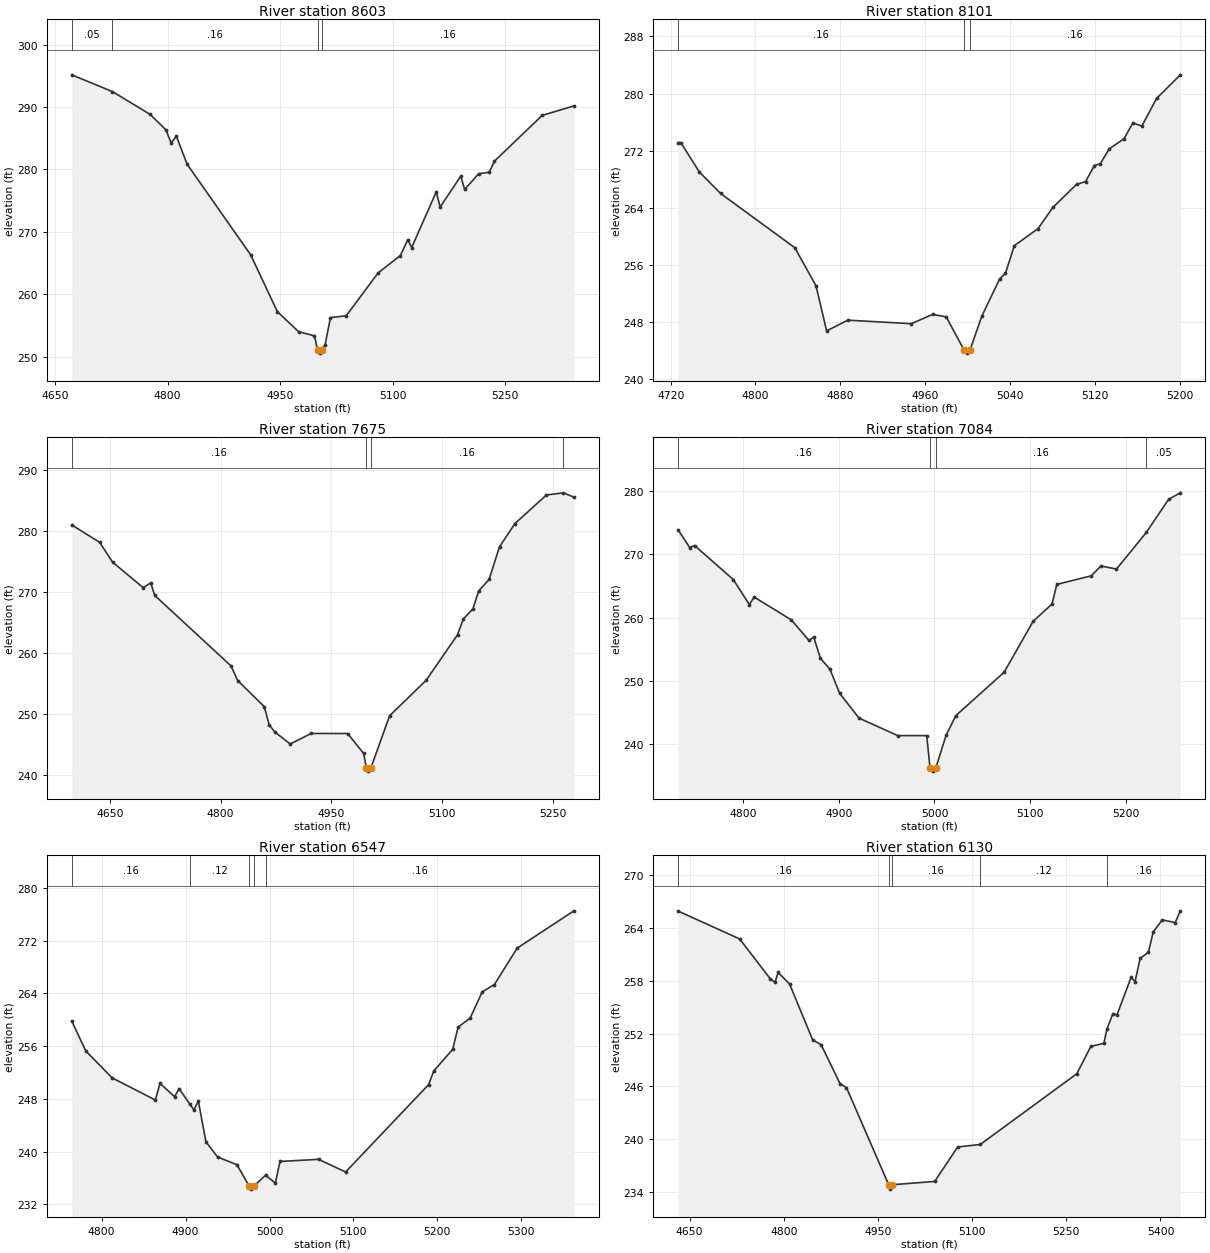
Type RM Length L Ch R = 1 ,8603    ,502,502,502
BEGIN DESCRIPTION:
UNT062 IN BECR 6.0
END DESCRIPTION:
XS GIS Cut Line= 3
      3789107.88     10489149.17      3788804.05       10488841.
      3788578.35     10488771.55
#Sta/Elev= 30
  4672.4  295.17  4726.6  292.48  4776.5  288.85  4797.7  286.37  4804.8  284.25
  4811.8  285.33    4826  280.85  4910.8   266.3  4946.2  257.22  4974.5     254
  4995.7  253.33  4999.8  251.06  5002.6  250.56  5005.8  251.06  5009.8  251.88
    5017  256.25  5038.1  256.56  5080.6  263.43  5110.1   266.2    5120  268.74
  5125.2  267.48  5157.9  276.41  5163.1  273.98  5190.6  278.93  5195.8  276.79
  5214.4  279.32  5228.5  279.55  5235.4  281.33  5299.1  288.67  5341.3  290.19
#Mann= 4 ,-1 , 0
  4672.4     .05       0  4726.6     .16       0  4999.8     .07       0
  5005.8     .16       0
Bank Sta=4999.8,5005.8
XS Rating Curve= 0 ,0
Exp/Cntr=0.3,0.1

Type RM Length L Ch R = 1 ,8101    ,426,426,426
BEGIN DESCRIPTION:
UNT062 IN BECR 5.0
END DESCRIPTION:
XS GIS Cut Line= 3
      3789199.63     10488510.19      3788949.61     10488510.19
      3788749.63      10488410.2
#Sta/Elev= 30
  4727.1  273.14  4729.6  273.14  4747.1  269.02  4767.1  266.02  4837.1  258.43
  4857.1  253.11  4867.1  246.79  4887.1  248.29  4947.1   247.8  4967.1   249.1
  4979.9  248.76  4996.5  244.18  4999.2  243.68  5002.5  244.18  5013.5  248.86
  5030.2  254.03  5035.8  254.85  5044.2  258.72  5066.6  261.11  5080.5  264.07
  5102.9   267.3  5111.3  267.68  5119.7  269.93  5125.3  270.19  5133.6  272.25
  5147.6  273.68    5156  275.89  5164.4  275.45  5178.4  279.33  5200.7  282.62
#Mann= 3 ,-1 , 0
  4727.1     .16       0  4996.5     .07       0  5002.5     .16       0
Bank Sta=4996.5,5002.5
XS Rating Curve= 0 ,0
Exp/Cntr=0.3,0.1

Type RM Length L Ch R = 1 ,7675    ,591,591,591
BEGIN DESCRIPTION:
UNT062 IN BECR 4.0
END DESCRIPTION:
XS GIS Cut Line= 3
      3789402.96     10488324.49      3789194.67     10488268.08
      3788847.48     10487959.95
#Sta/Elev= 30
  4598.5  280.98  4636.2  278.14  4653.8  274.89  4695.2  270.71  4705.5  271.49
  4710.7  269.46  4814.3  257.88  4823.2   255.5  4859.2  251.23  4865.8  248.27
  4873.4  247.09  4894.3  245.11  4922.7  246.84  4972.1  246.83  4993.8  243.56
  4997.5  241.17  5000.2  240.67  5003.5  241.17  5028.9  249.73  5078.3  255.53
  5120.9     263  5128.5  265.54  5141.9  267.27  5149.4  270.16  5163.6  272.05
  5177.8  277.42  5198.7  281.21  5241.3  285.89  5264.3  286.24  5278.5  285.52
#Mann= 4 ,-1 , 0
  4598.5     .16       0  4997.5     .07       0  5003.5     .16       0
  5264.3     .05       0
Bank Sta=4997.5,5003.5
XS Rating Curve= 0 ,0
Exp/Cntr=0.3,0.1

Type RM Length L Ch R = 1 ,7084    ,537,537,537
BEGIN DESCRIPTION:
UNT062 IN BECR 3.0
END DESCRIPTION:
XS GIS Cut Line= 2
      3789346.56     10487773.29      3788827.52     10487855.47
#Sta/Elev= 30
  4731.8  273.84  4743.9  271.05    4749  271.37  4789.5  265.99  4806.3  262.03
  4811.3  263.23  4850.2  259.63  4868.6  256.38  4873.7  256.89  4880.6  253.57
  4890.7  251.82  4900.8  248.02  4921.1  244.11  4961.6  241.35  4991.9  241.35
  4995.4  236.24  4998.1  235.74  5001.4  236.24  5012.2   241.4  5022.3  244.49
  5072.9  251.36  5103.3   259.4    5123  262.13  5128.1  265.23  5164.1  266.58
  5174.2  268.14  5190.5  267.65  5221.8  273.45  5245.1  278.67  5257.3  279.69
#Mann= 4 ,-1 , 0
  4731.8     .16       0  4995.4     .07       0  5001.4     .16       0
  5221.8     .05       0
Bank Sta=4995.4,5001.4
XS Rating Curve= 0 ,0
Exp/Cntr=0.3,0.1

Type RM Length L Ch R = 1 ,6547    ,417,417,417
BEGIN DESCRIPTION:
UNT062 IN BECR 2.0
END DESCRIPTION:
XS GIS Cut Line= 3
      3789194.64     10487313.24      3788903.88     10487447.77
      3788686.85     10487621.39
#Sta/Elev= 30
  4764.4  259.81    4781  255.28  4812.6  251.18    4864  247.83  4869.5  250.35
  4886.9  248.33  4892.4  249.55    4905  247.21  4909.8  246.36  4915.3  247.64
  4924.2   241.5  4938.2  239.18  4961.2  238.01  4975.6  234.81  4978.3  234.31
  4981.6  234.81  4995.3  236.42    5007  235.22  5012.5  238.51  5058.4  238.83
  5090.7  236.91  5189.5  250.16  5195.9  252.26  5218.3  255.53  5224.7  258.89
  5239.1  260.26  5253.5  264.25  5267.9  265.33  5295.1  270.87  5362.7  276.53
#Mann= 5 ,-1 , 0
  4764.4     .16       0    4905     .12       0  4975.6     .07       0
  4981.6     .12       0  4995.3     .16       0
Bank Sta=4975.6,4981.6
XS Rating Curve= 0 ,0
Exp/Cntr=0.3,0.1

Type RM Length L Ch R = 1 ,6130    ,219,219,219
BEGIN DESCRIPTION:
Mapping XS b17b3910
END DESCRIPTION:
XS GIS Cut Line= 4
      3789194.69     10487200.37        3788982.     10487165.65
      3788725.92     10487187.35      3788469.84     10487391.35
#Sta/Elev= 30
  4631.7  265.88  4729.5  262.73  4778.7  258.18  4785.9  257.81    4791  258.92
  4809.1  257.62  4845.9  251.29  4859.6  250.71  4889.7  246.29  4899.8  245.87
    4967  234.86  4969.8  234.36    4973  234.86  5040.3  235.23    5077  239.14
  5112.9  239.42  5266.7  247.44  5289.1  250.54  5309.9  250.89  5314.6  252.49
  5324.3  254.27  5330.7  254.11  5353.2  258.37  5359.5  257.88  5367.6  260.51
  5380.8  261.22  5388.4  263.51  5402.8  264.88  5423.6  264.58  5431.6  265.91
#Mann= 5 ,-1 , 0
  4631.7     .16       0    4967     .07       0    4973     .16       0
  5112.9     .12       0  5314.6     .16       0
Bank Sta=4967,4973
XS Rating Curve= 0 ,0
Exp/Cntr=0.3,0.1

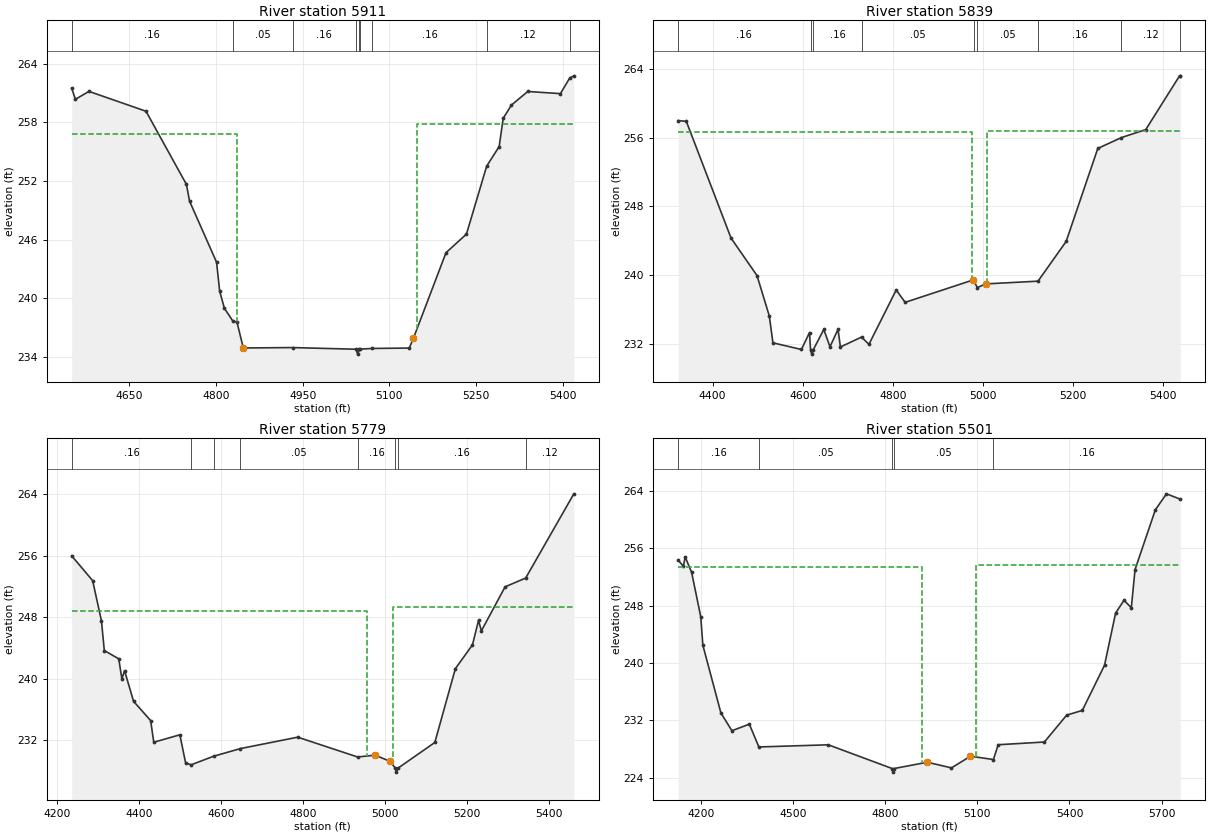
Type RM Length L Ch R = 1 ,5911    ,72,72,72
BEGIN DESCRIPTION:
Mapping XS e68847bb
END DESCRIPTION:
XS GIS Cut Line= 6
      3789151.31     10487087.54      3788856.13     10486957.32
      3788760.65     10486974.68      3788682.52      10487031.1
      3788656.48     10487083.18      3788448.15     10487291.51
#Sta/Elev= 30
  4550.2  261.49  4556.8  260.36  4580.1  261.17  4678.8  259.14  4748.8  251.66
  4754.2  249.95  4800.9  243.71  4806.3  240.75  4814.4  239.01  4829.1  237.69
  4836.2  237.59  4847.2  234.94  4932.4  234.98  5042.2  234.81    5045  234.31
  5048.2  234.81  5048.8  234.82  5070.7  234.89  5134.3  234.93  5141.4  235.91
  5197.9  244.68  5233.3  246.58  5268.3  253.53  5289.9  255.53  5296.9  258.42
  5311.1  259.77  5339.4  261.16  5395.9  260.94    5412  262.54  5419.1  262.76
#Mann= 9 ,-1 , 0
  4550.2     .16       0  4829.1     .05       0  4932.4     .16       0
  5042.2     .07       0  5048.2     .16       0  5048.8     .05       0
  5070.7     .16       0  5268.3     .12       0    5412     .16       0
#XS Ineff= 2 , 0
         4837.01  256.78 5147.24          257.79
Permanent Ineff=
       F       F
Bank Sta=4847.2,5141.4
XS Rating Curve= 0 ,0
Exp/Cntr=0.3,0.1

Type RM Length L Ch R = 1 ,5839    ,60,60,60
BEGIN DESCRIPTION:
Mapping XS f2df7fa0
END DESCRIPTION:
XS GIS Cut Line= 6
      3789238.06     10487026.74      3789081.83     10486831.45
      3788873.49     10486900.89      3788786.69     10486887.87
      3788656.48     10486961.66      3788391.74     10487269.79
#Sta/Elev= 30
  4323.7  258.02  4341.9  257.93  4441.1  244.31  4498.6  239.95  4525.9  235.24
    4534   232.1  4597.2  231.32  4615.1   233.3  4617.4  231.28  4620.2  230.78
  4623.4  231.28  4646.8  233.66  4660.5  231.64  4678.4  233.67  4683.6  231.61
  4730.5  232.77  4746.9  231.92  4807.4  238.26  4827.2  236.82  4978.5  239.44
  4978.9  239.36  4987.5  238.54  5005.5  238.97  5121.9  239.29  5184.3  243.92
  5254.5  254.77    5307  256.04  5360.9  256.97  5435.9  263.24  5437.5  263.24
#Mann= 9 ,-1 , 0
  4323.7     .16       0  4617.4     .03       0  4623.4     .16       0
  4730.5     .05       0  4978.9     .16       0  4987.5     .05       0
  5121.9     .16       0    5307     .12       0  5435.9     .16       0
#XS Ineff= 2 , 0
         4974.41  256.72  5008.4          256.78
Permanent Ineff=
       F       F
Bank Sta=4978.5,5005.5
XS Rating Curve= 0 ,0
Exp/Cntr=0.3,0.1

Type RM Length L Ch R = 1 ,5779    ,278,278,278
BEGIN DESCRIPTION:
Mapping XS cc2c9dc3
END DESCRIPTION:
XS GIS Cut Line= 6
      3789277.16     10487005.08      3789077.49     10486775.02
      3788877.83     10486835.79      3788756.31     10486831.45
      3788591.38     10486931.27      3788357.01     10487252.44
#Sta/Elev= 30
  4235.9  255.97  4287.1  252.75  4308.6  247.52  4315.6  243.66  4350.8  242.59
  4358.4  239.99    4365  241.05  4386.9  237.07  4428.6  234.57  4436.3  231.75
  4499.9  232.72  4514.1  229.03  4527.9  228.83    4582  229.93  4647.8  230.93
  4787.5  232.41  4933.5  229.84  4976.3  230.07  5013.2  229.27  5025.7  228.37
  5028.4  227.87  5031.7  228.37    5122  231.72  5172.2  241.32  5213.9   244.4
  5228.6  247.58  5235.6  246.22  5293.5  251.94  5343.7  253.08  5461.2  264.02
#Mann= 8 ,-1 , 0
  4235.9     .16       0  4527.9     .05       0    4582     .16       0
  4647.8     .05       0  4933.5     .16       0  5025.7     .07       0
  5031.7     .16       0  5343.7     .12       0
#XS Ineff= 2 , 0
         4956.96  248.85 5019.42          249.26
Permanent Ineff=
       F       F
Bank Sta=4976.3,5013.2
XS Rating Curve= 0 ,0
Exp/Cntr=0.3,0.1

Type RM Length L Ch R = 1 ,5501    ,0,0,0
BEGIN DESCRIPTION:
UNT062 IN BECR 1.0
END DESCRIPTION:
XS GIS Cut Line= 5
      3789316.18     10486996.35      3789120.89     10486714.26
      3788778.01     10486592.73      3788487.21     10486657.84
      3788139.96     10487183.05
#Sta/Elev= 30
  4126.2  254.34  4143.2  253.51  4149.2  254.79  4170.2  252.63  4199.9  246.44
  4206.7  242.48  4265.5  233.03  4301.3  230.55    4358  231.47  4388.9  228.29
    4615  228.59  4822.9  225.28  4825.6  224.78  4828.9  225.28  4937.4  226.16
  5015.9  225.37  5077.8     227  5152.4  226.54    5168   228.6  5318.4  228.98
  5390.6  232.72  5441.8  233.39    5514  239.68  5550.1  246.96  5577.4  248.74
  5601.3   247.7  5613.4  253.03  5679.5  261.36  5715.7  263.59  5760.7  262.84
#Mann= 5 ,-1 , 0
  4126.2     .16       0  4388.9     .05       0  4822.9     .03       0
  4828.9     .05       0  5152.4     .16       0
#XS Ineff= 2 , 0
          4918.9  253.45 5094.88           253.7
Permanent Ineff=
       F       F
Bank Sta=4937.4,5077.8
XS Rating Curve= 0 ,0
Exp/Cntr=0.3,0.1

Chan Stop Cuts=-1
Use User Specified Reach Order=0
Composite Channel Slope=5