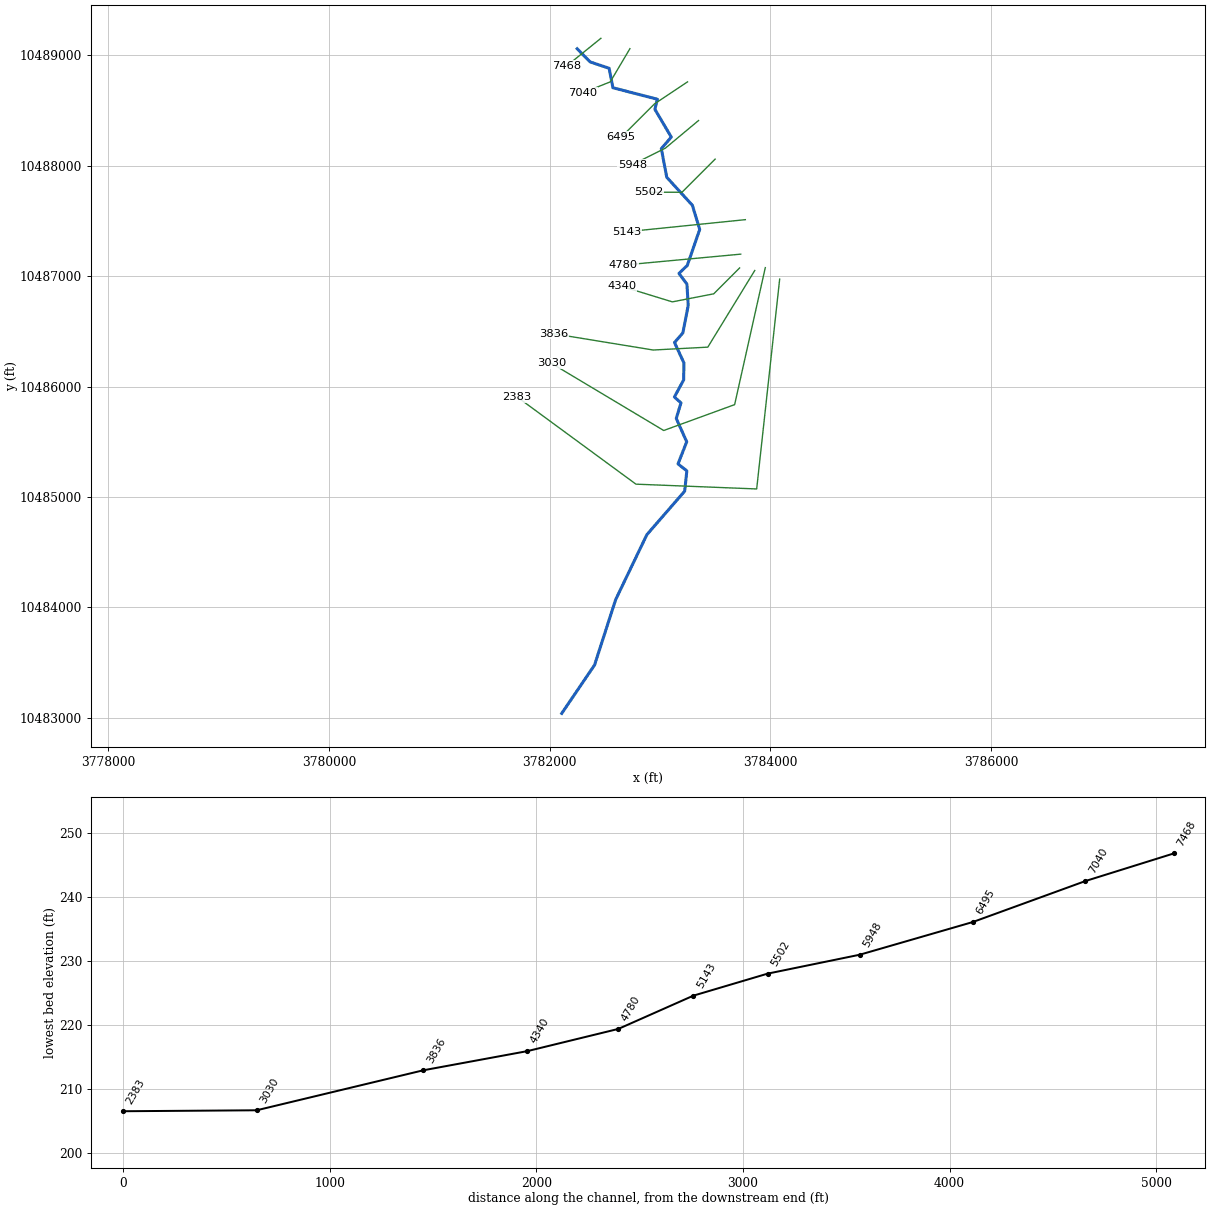
--- UNT063 IN BECR.prj (project) ---

Proj Title=UNT063 IN BECR Base Level Engineering
Current Plan=p01
Default Exp/Contr=0.3,0.1
English Units
Geom File=g01
Flow File=f01
Plan File=p01
Y Axis Title=Elevation
X Axis Title(PF)=Main Channel Distance
X Axis Title(XS)=Station
BEGIN DESCRIPTION:
UNT063 IN BECR
END DESCRIPTION:
DSS Export Rating Curves= 0
DSS Export Rating Curve Sorted= 0
DSS Export Volume Flow Curves= 0
DXF OffsetX= 0
DXF OffsetY= 0
DXF ScaleX= 1
DXF ScaleY= 10

--- UNT063 IN BECR.p01 (plan) ---

Plan Title=Multiple Run
Short Identifier=Multiple
Geom File=g01
Flow File=f01
Subcritical Flow
K Sum by GR= 0
Std Step Tol= 0.01
Critical Tol= 0.01
Num of Std Step Trials= 20
Max Error Tol= 0.3
Flow Tol Ratio= 0.001
Split Flow NTrial= 30
Split Flow Tol= 0.02
Split Flow Ratio= 0.02
Log Output Level= 0
Friction Slope Method= 1
Unsteady Friction Slope Method= 2
Unsteady Bridges Friction Slope Method= 1
Parabolic Critical Depth
Global Vel Dist=  1 , 1 , 1
Global Log Level= 0
CheckData=True
Encroach Param= -1, 0, 0, 0
BEGIN DESCRIPTION:
Multiple Run
END DESCRIPTION:

--- UNT063 IN BECR.f01 (steady flow) ---

Flow Title=Multiple
Number of Profiles=7
Profile Names=10-year,25-year,50-year,1pct_min,100-year,1pct_plu,500-year
River Rch & RM= UNT063 IN BECR,Reach-1,7468
     415     549     656     578     781    1057    1111
Boundary for River Rch & Prof#=UNT063 IN BECR,Reach-1,1
Up Type=0
Dn Type=3
Dn Slope=0.005
Boundary for River Rch & Prof#=UNT063 IN BECR,Reach-1,2
Up Type=0
Dn Type=3
Dn Slope=0.005
Boundary for River Rch & Prof#=UNT063 IN BECR,Reach-1,3
Up Type=0
Dn Type=3
Dn Slope=0.005
Boundary for River Rch & Prof#=UNT063 IN BECR,Reach-1,4
Up Type=0
Dn Type=3
Dn Slope=0.005
Boundary for River Rch & Prof#=UNT063 IN BECR,Reach-1,5
Up Type=0
Dn Type=3
Dn Slope=0.005
Boundary for River Rch & Prof#=UNT063 IN BECR,Reach-1,6
Up Type=0
Dn Type=3
Dn Slope=0.005
Boundary for River Rch & Prof#=UNT063 IN BECR,Reach-1,7
Up Type=0
Dn Type=3
Dn Slope=0.005

--- UNT063 IN BECR.g01 (geometry) ---

Geom Title=Existing Conditions
Program Version=4.10

River Reach=UNT063 IN BECR  ,Reach-1
Reach XY= 30
      3782249.61     10489060.19      3782367.25       10488941.
       3782539.5       10488883.       3782573.5       10488707.
      3782976.25       10488603.      3782953.75       10488512.
      3783102.25       10488260.      3783012.25       10488155.
      3783061.25       10487896.       3783293.5       10487642.
        3783360.       10487423.      3783247.25       10487097.
        3783172.       10487025.        3783244.       10486928.
      3783255.75       10486735.       3783207.5       10486486.
      3783131.64     10486398.93       3783216.5       10486215.
        3783215.       10486061.       3783130.5       10485905.
      3783190.25       10485852.       3783147.5       10485711.
      3783242.25       10485499.      3783163.25       10485299.
      3783243.25       10485236.      3783223.75       10485052.
      3782881.25       10484658.      3782598.25       10484069.
      3782407.25       10483477.        3782110.       10483039.

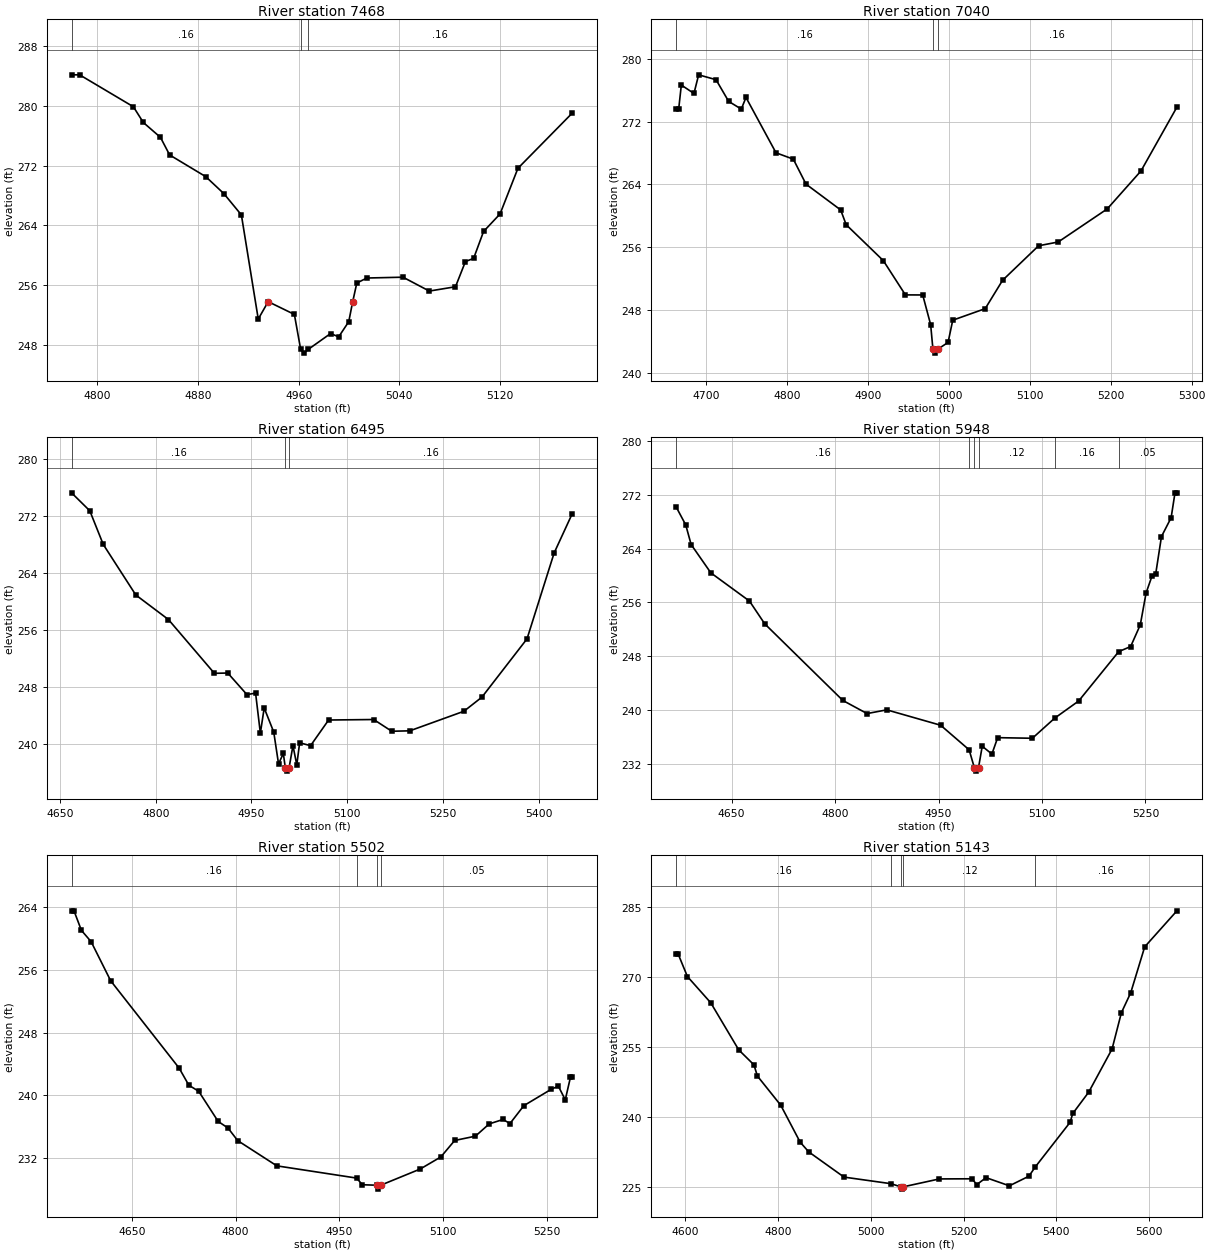
Type RM Length L Ch R = 1 ,7468    ,428,428,428
BEGIN DESCRIPTION:
UNT063 IN BECR 8.0
END DESCRIPTION:
XS GIS Cut Line= 2
      3782464.57     10489154.58      3782155.04     10488904.87
#Sta/Elev= 30
  4779.6  284.16    4786  284.16  4828.7  279.88  4836.6  277.77  4850.2  275.78
  4857.5  273.42  4886.2  270.51  4900.6  268.23  4914.5  265.38  4927.9  251.42
  4935.8  253.75  4956.6  252.04  4961.6  247.35  4964.3  246.85  4967.6  247.35
  4985.4  249.48  4991.8  249.03  4999.8  251.07 5002.84  253.67  5006.2  256.25
  5014.2  256.92  5042.9  257.03  5063.8  255.17  5084.6  255.75  5092.5  259.13
    5099  259.55  5106.9  263.16    5120  265.51  5134.2  271.63  5177.3  279.02
#Mann= 3 ,-1 , 0
  4779.6     .16       0  4961.6     .07       0  4967.6     .16       0
Bank Sta=4935.8,5002.84
XS Rating Curve= 0 ,0
Exp/Cntr=0.3,0.1

Type RM Length L Ch R = 1 ,7040    ,545,545,545
BEGIN DESCRIPTION:
UNT063 IN BECR 7.0
END DESCRIPTION:
XS GIS Cut Line= 3
       3782727.6     10489060.82      3782549.61     10488760.19
      3782299.64      10488660.2
#Sta/Elev= 30
  4663.2  273.54  4666.1  273.54  4669.4  276.64    4685  275.57  4690.8  277.94
  4712.3  277.32  4727.9  274.56  4743.5  273.58  4749.3  275.06  4786.4  268.02
  4807.8  267.21  4823.5  264.03  4866.3  260.75  4873.1  258.87    4919   254.3
  4946.3  249.94  4967.7  249.93  4977.5  246.15  4980.3  243.03  4983.1  242.53
  4986.3  243.03    4999  243.89  5004.8  246.72  5044.9  248.19  5066.4   251.8
  5110.9  256.19  5135.1  256.67  5195.7  260.88  5237.4  265.71  5281.8  273.83
#Mann= 3 ,-1 , 0
  4663.2     .16       0  4980.3     .07       0  4986.3     .16       0
Bank Sta=4980.3,4986.3
XS Rating Curve= 0 ,0
Exp/Cntr=0.3,0.1

Type RM Length L Ch R = 1 ,6495    ,547,547,547
BEGIN DESCRIPTION:
UNT063 IN BECR 6.0
END DESCRIPTION:
XS GIS Cut Line= 3
      3783249.64     10488760.21      3782949.61     10488560.19
      3782649.57     10488260.15
#Sta/Elev= 30
  4667.9  275.27  4696.5  272.74  4717.5  268.02  4768.6   260.9  4819.7  257.45
  4891.8  249.88  4912.8  249.92  4942.9  246.88  4956.4   247.1  4963.9  241.46
  4969.9  245.01  4984.9  241.61  4992.4  237.14  4999.9   238.6    5003  236.62
  5005.7  236.12    5009  236.62    5015  239.71    5021  236.99  5025.5  240.11
  5042.6   239.7  5070.9  243.31  5141.6  243.38  5169.9  241.73  5198.2  241.79
    5283  244.54  5311.3  246.53    5382  254.73  5424.5  266.81  5452.8  272.32
#Mann= 3 ,-1 , 0
  4667.9     .16       0    5003     .07       0    5009     .16       0
Bank Sta=5003,5009
XS Rating Curve= 0 ,0
Exp/Cntr=0.3,0.1

Type RM Length L Ch R = 1 ,5948    ,446,446,446
BEGIN DESCRIPTION:
UNT063 IN BECR 5.0
END DESCRIPTION:
XS GIS Cut Line= 3
       3783349.6     10488410.18      3783049.61     10488160.19
      3782749.62     10488010.19
#Sta/Elev= 30
  4569.8  270.12  4583.5  267.49  4591.3  264.59  4619.9  260.39  4675.9  256.21
    4698  252.84  4811.3  241.48  4846.4  239.54    4875  240.09  4953.1  237.81
  4994.4  234.17    5002  231.51  5004.8  231.01    5008  231.51  5013.4   234.7
  5027.4  233.54  5035.8  235.97  5086.1  235.88  5118.6  238.87  5153.2   241.4
  5211.3  248.72  5228.6  249.47  5242.6  252.69    5251  257.41  5259.4  259.87
    5265  260.27  5273.3  265.77  5287.3  268.56  5292.9  272.25  5295.7  272.25
#Mann= 6 ,-1 , 0
  4569.8     .16       0  4994.4     .12       0    5002     .07       0
    5008     .12       0  5118.6     .16       0  5211.3     .05       0
Bank Sta=5002,5008
XS Rating Curve= 0 ,0
Exp/Cntr=0.3,0.1

Type RM Length L Ch R = 1 ,5502    ,359,359,359
BEGIN DESCRIPTION:
UNT063 IN BECR 4.0
END DESCRIPTION:
XS GIS Cut Line= 3
      3783499.62      10488060.2      3783199.61     10487760.19
      3782899.58     10487760.19
#Sta/Elev= 30
  4562.7  263.57  4566.2  263.57  4576.9  261.08    4591  259.63  4619.3  254.64
  4718.3   243.5  4732.4  241.31  4746.6  240.54  4774.8  236.69    4789  235.85
  4803.1  234.24  4859.7  231.02  4975.1  229.46  4983.4  228.61    5004  228.55
  5006.7  228.05    5010  228.55    5067  230.61    5097  232.16    5117  234.26
    5147  234.81    5167  236.38    5187  236.94    5197  236.42    5217   238.7
    5257  240.81    5267  241.19    5277  239.45  5284.5  242.33    5287  242.33
#Mann= 4 ,-1 , 0
  4562.7     .16       0  4975.1     .05       0    5004     .03       0
    5010     .05       0
Bank Sta=5004,5010
XS Rating Curve= 0 ,0
Exp/Cntr=0.3,0.1

Type RM Length L Ch R = 1 ,5143    ,363,363,363
BEGIN DESCRIPTION:
UNT063 IN BECR 3.0
END DESCRIPTION:
XS GIS Cut Line= 2
      3783773.42     10487511.89      3782700.58     10487402.52
#Sta/Elev= 30
  4581.3  274.76  4585.7  274.76  4605.2  270.05  4655.5  264.44  4715.8  254.37
  4748.5  251.18    4756  248.78  4806.3  242.54  4848.1  234.65  4866.6  232.57
  4942.6  227.18  5043.9  225.77  5064.6  225.11  5067.4  224.61  5070.6  225.11
    5148  226.79  5218.4  226.82  5228.5  225.58  5248.6  227.06  5298.8  225.32
  5340.8  227.37  5354.8  229.38  5429.5  238.88  5435.4  240.78  5469.7  245.34
    5520  254.56  5540.1  262.32  5560.2  266.58  5590.3  276.39  5659.7  284.09
#Mann= 5 ,-1 , 0
  4581.3     .16       0  5043.9     .12       0  5064.6     .07       0
  5070.6     .12       0  5354.8     .16       0
Bank Sta=5064.6,5070.6
XS Rating Curve= 0 ,0
Exp/Cntr=0.3,0.1

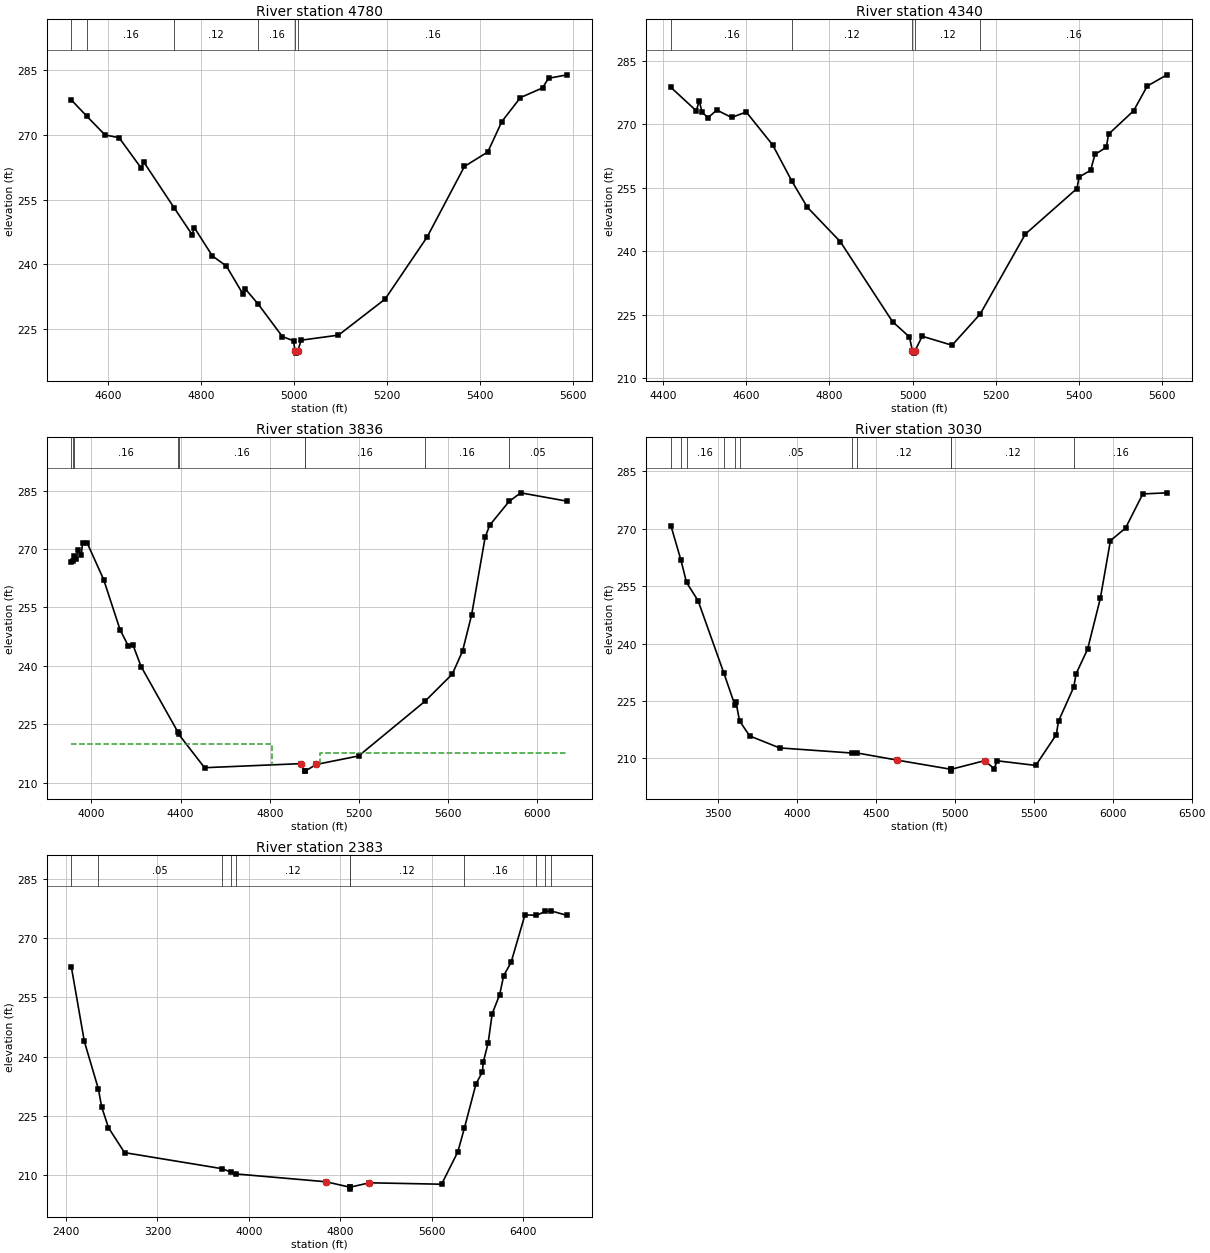
Type RM Length L Ch R = 1 ,4780    ,440,440,440
BEGIN DESCRIPTION:
Mapping XS 760c2059
END DESCRIPTION:
XS GIS Cut Line= 2
      3783731.78     10487199.39      3782669.28     10487100.44
#Sta/Elev= 30
  4520.2  278.09  4553.6  274.31  4592.7  269.98  4622.8  269.36  4670.7  262.27
  4675.7  263.76  4741.2  253.12  4779.9   246.9  4784.9  248.48  4823.7  241.93
  4853.8  239.59    4889  233.18    4894  234.36  4922.5  230.73  4974.3  223.24
  4998.2  222.27  5001.5  219.91  5004.2  219.41  5007.5  219.91  5014.5  222.41
  5094.9  223.58  5195.3  231.94  5285.7  246.33    5366  262.69  5416.2  266.04
  5446.4  273.09  5486.5  278.65  5533.9  280.88  5546.8  283.12  5587.3  283.92
#Mann= 6 ,-1 , 0
  4520.2     .05       0  4553.6     .16       0  4741.2     .12       0
  4922.5     .16       0  5001.5     .07       0  5007.5     .16       0
Bank Sta=5001.5,5007.5
XS Rating Curve= 0 ,0
Exp/Cntr=0.3,0.1

Type RM Length L Ch R = 1 ,4340    ,504,504,504
BEGIN DESCRIPTION:
UNT063 IN BECR 2.0
END DESCRIPTION:
XS GIS Cut Line= 4
      3783721.38      10487074.4      3783486.99     10486840.02
      3783111.99      10486767.1      3782654.15     10486907.58
#Sta/Elev= 30
  4419.1  278.68  4479.9  273.16    4487  275.51    4494  272.77  4508.2  271.56
  4529.4  273.34  4564.8  271.59  4600.1  272.88  4663.7  265.08  4709.8  256.54
  4746.9  250.39  4826.3  242.24  4951.7  223.37  4992.4  219.76  4999.6  216.44
  5002.3  215.94  5005.6  216.44    5023  219.93  5094.8   217.8  5162.5  225.18
  5271.1  244.06  5395.1  254.81  5400.3  257.54  5427.8  259.09  5438.4  262.87
  5465.8  264.56    5471  267.64  5531.3  273.17    5564     279  5611.5  281.66
#Mann= 5 ,-1 , 0
  4419.1     .16       0  4709.8     .12       0  4999.6     .07       0
  5005.6     .12       0  5162.5     .16       0
Bank Sta=4999.6,5005.6
XS Rating Curve= 0 ,0
Exp/Cntr=0.3,0.1

Type RM Length L Ch R = 1 ,3836    ,806,806,806
BEGIN DESCRIPTION:
Mapping XS 90610ce1
END DESCRIPTION:
XS GIS Cut Line= 4
      3783858.68     10487051.39      3783433.33     10486356.94
      3782938.53      10486330.9      3782035.75     10486478.47
#Sta/Elev= 30
  3910.1  266.78  3917.3  266.97  3922.5  268.11  3933.1  267.46  3938.9  269.78
  3954.4  268.38  3960.2  271.45  3981.9  271.48    4055  262.18  4128.5   249.3
  4165.2  245.17  4186.5  245.36  4223.2  239.79  4387.3  223.06  4391.5  222.42
  4507.6  213.82  4938.5  214.86  4958.3  212.94  4958.8  212.94  5008.6  214.66
  5198.8  216.84    5496  230.88  5618.8  237.88  5664.7  243.78  5705.2  253.03
    5766  273.01  5786.3  276.12  5873.3  282.24  5925.7  284.46  6134.7   282.3
#Mann= 9 ,-1 , 0
  3910.1     .16       0  3917.3     .05       0  3922.5     .16       0
  4387.3     .05       0  4391.5     .16       0  4958.3     .07       0
  4958.8     .16       0    5496     .16       0  5873.3     .05       0
#XS Ineff= 2 , 0
         4809.09  219.94 5026.92          217.55
Permanent Ineff=
       F       F
Bank Sta=4938.5,5008.6
XS Rating Curve= 0 ,0
Exp/Cntr=0.3,0.1

Type RM Length L Ch R = 1 ,3030    ,647,647,647
BEGIN DESCRIPTION:
Mapping XS c45860e7
END DESCRIPTION:
XS GIS Cut Line= 4
      3783954.17     10487077.46      3783676.38     10485836.11
      3783034.02     10485601.73      3782018.35      10486209.4
#Sta/Elev= 30
  3204.3  270.75  3267.5  261.78  3302.6  255.99  3375.7  251.22  3538.9  232.32
  3608.5  223.97  3615.5  224.78  3638.2  219.82  3702.2  215.89  3891.2  212.76
  4348.2  211.42  4381.6  211.44  4632.6  209.59  4973.8  207.19  4976.5  206.69
  4979.8  207.19  5190.4  209.43  5248.7  207.36  5270.2  209.38  5513.2  208.18
  5643.1  216.22  5657.2  219.76  5753.9  228.66    5768  232.08  5841.2  238.54
  5921.7   251.8  5985.9  266.92  6081.2  270.17  6190.7  279.11  6343.7   279.4
#Mann= 11 ,-1 , 0
  3204.3     .16       0  3267.5     .05       0  3302.6     .16       0
  3538.9     .05       0  3608.5     .16       0  3638.2     .05       0
  4348.2     .07       0  4381.6     .12       0  4973.8     .07       0
  4979.8     .12       0  5753.9     .16       0
Bank Sta=4632.6,5190.4
XS Rating Curve= 0 ,0
Exp/Cntr=0.3,0.1

Type RM Length L Ch R = 1 ,2383    ,0,0,0
BEGIN DESCRIPTION:
UNT063 IN BECR 1.0
END DESCRIPTION:
XS GIS Cut Line= 4
      3784084.37     10486973.26      3783876.03     10485072.22
      3782782.28     10485115.62      3781706.12     10485905.39
#Sta/Elev= 30
  2446.2  262.69    2560  243.85  2683.1  231.82  2710.8   227.4  2771.2  222.06
    2912  215.76  3765.3  211.71  3840.8  210.87  3886.3  210.38  4675.3   208.4
  4882.5  207.04  4885.2  206.54  4888.5  207.04  5055.6  208.14  5687.6  207.78
  5829.6  215.97  5886.1  221.86  5988.5  233.13  6044.9  236.17  6051.9  238.57
  6095.1  243.49  6130.6   250.9  6195.4  255.62  6230.9  260.48  6295.7  263.82
  6416.9  275.82  6516.8  275.73    6597   276.7    6643  276.85  6788.1  275.68
#Mann= 11 ,-1 , 0
  2446.2     .16       0  2683.1     .05       0  3765.3     .07       0
  3840.8     .05       0  3886.3     .12       0  4882.5     .07       0
  4888.5     .12       0  5886.1     .16       0  6516.8     .05       0
    6597     .16       0    6643     .05       0
Bank Sta=4675.3,5055.6
XS Rating Curve= 0 ,0
Exp/Cntr=0.3,0.1

Chan Stop Cuts=-1
Use User Specified Reach Order=0
Composite Channel Slope=5