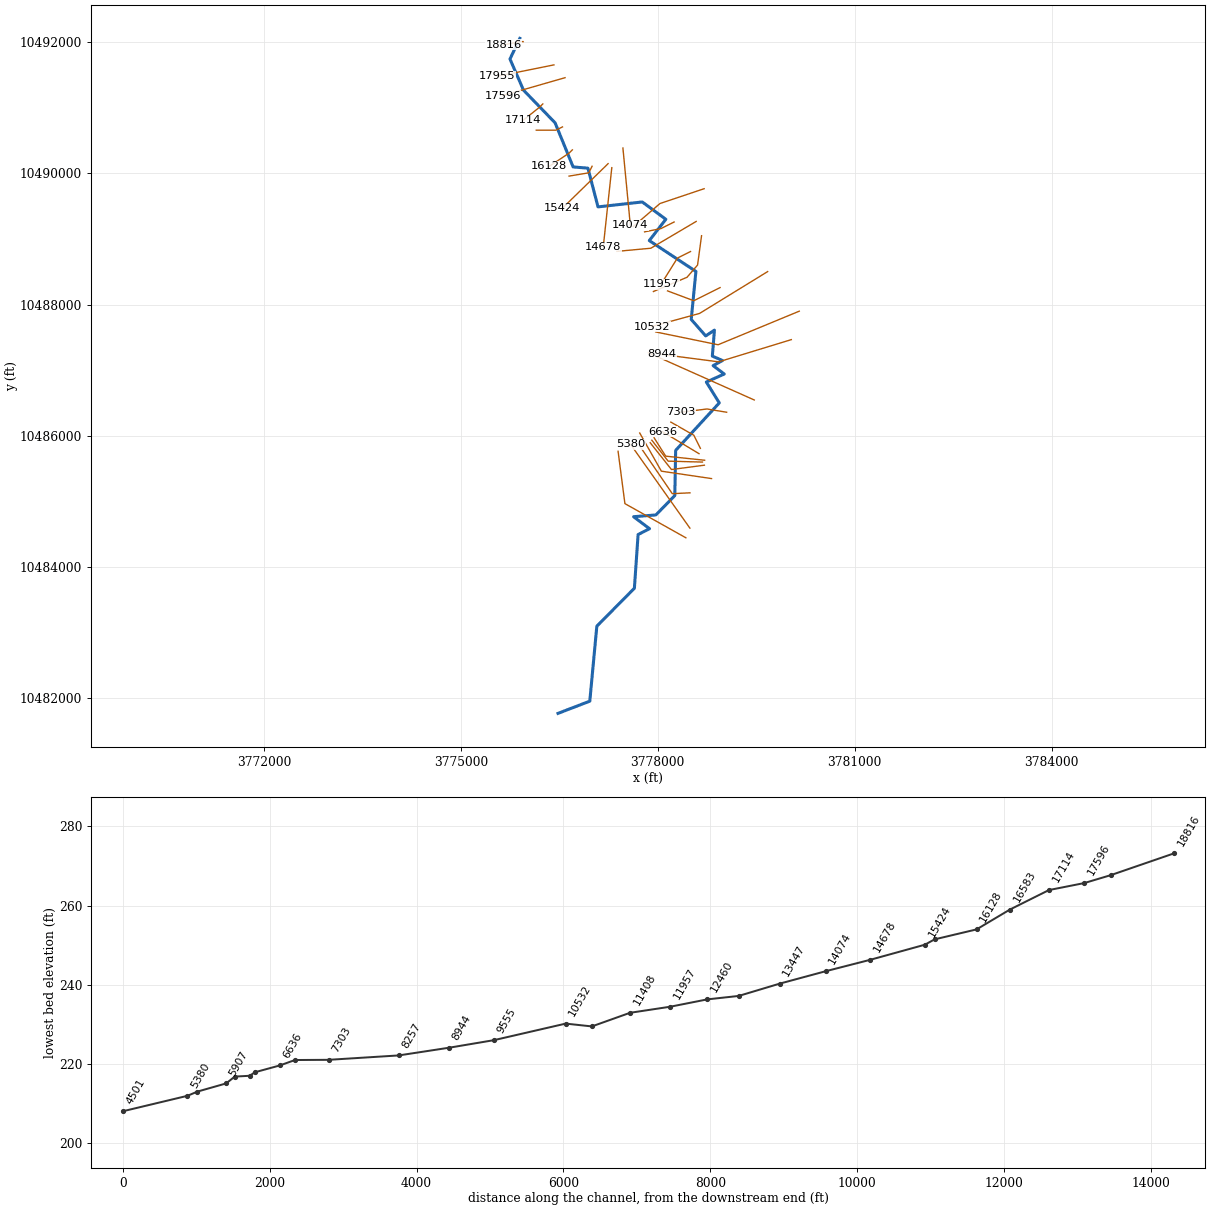
--- UNT064 IN BECR.prj (project) ---

Proj Title=UNT064 IN BECR Base Level Engineering
Current Plan=p01
Default Exp/Contr=0.3,0.1
English Units
Geom File=g01
Flow File=f01
Plan File=p01
Y Axis Title=Elevation
X Axis Title(PF)=Main Channel Distance
X Axis Title(XS)=Station
BEGIN DESCRIPTION:
UNT064 IN BECR
END DESCRIPTION:
DSS Export Rating Curves= 0
DSS Export Rating Curve Sorted= 0
DSS Export Volume Flow Curves= 0
DXF OffsetX= 0
DXF OffsetY= 0
DXF ScaleX= 1
DXF ScaleY= 10

--- UNT064 IN BECR.p01 (plan) ---

Plan Title=Multiple Run
Short Identifier=Multiple
Geom File=g01
Flow File=f01
Subcritical Flow
K Sum by GR= 0
Std Step Tol= 0.01
Critical Tol= 0.01
Num of Std Step Trials= 20
Max Error Tol= 0.3
Flow Tol Ratio= 0.001
Split Flow NTrial= 30
Split Flow Tol= 0.02
Split Flow Ratio= 0.02
Log Output Level= 0
Friction Slope Method= 1
Unsteady Friction Slope Method= 2
Unsteady Bridges Friction Slope Method= 1
Parabolic Critical Depth
Global Vel Dist=  1 , 1 , 1
Global Log Level= 0
CheckData=True
Encroach Param= -1, 0, 0, 0
BEGIN DESCRIPTION:
Multiple Run
END DESCRIPTION:

--- UNT064 IN BECR.f01 (steady flow) ---

Flow Title=Multiple
Number of Profiles=7
Profile Names=10-year,25-year,50-year,1pct_min,100-year,1pct_plu,500-year
River Rch & RM= UNT064 IN BECR,Reach-1,18816
     634     861    1049     939    1270    1718    1870
River Rch & RM= UNT064 IN BECR,Reach-1,13447
     785    1071    1309    1174    1588    2147    2344
River Rch & RM= UNT064 IN BECR,Reach-1,2696
     824    1126    1377    1236    1672    2261    2473
Boundary for River Rch & Prof#=UNT064 IN BECR,Reach-1,1
Up Type=0
Dn Type=3
Dn Slope=0.005
Boundary for River Rch & Prof#=UNT064 IN BECR,Reach-1,2
Up Type=0
Dn Type=3
Dn Slope=0.005
Boundary for River Rch & Prof#=UNT064 IN BECR,Reach-1,3
Up Type=0
Dn Type=3
Dn Slope=0.005
Boundary for River Rch & Prof#=UNT064 IN BECR,Reach-1,4
Up Type=0
Dn Type=3
Dn Slope=0.005
Boundary for River Rch & Prof#=UNT064 IN BECR,Reach-1,5
Up Type=0
Dn Type=3
Dn Slope=0.005
Boundary for River Rch & Prof#=UNT064 IN BECR,Reach-1,6
Up Type=0
Dn Type=3
Dn Slope=0.005
Boundary for River Rch & Prof#=UNT064 IN BECR,Reach-1,7
Up Type=0
Dn Type=3
Dn Slope=0.005

--- UNT064 IN BECR.g01 (geometry) ---

Geom Title=Existing Conditions
Program Version=4.10

River Reach=UNT064 IN BECR  ,Reach-1
Reach XY= 30
      3775899.61     10492060.19       3775749.5       10491745.
      3775954.75       10491271.      3776436.75       10490772.
        3776711.       10490100.      3776936.75       10490081.
      3777090.25       10489491.      3777763.75       10489566.
      3778123.25       10489302.       3777871.5       10488977.
       3778581.5       10488507.      3778510.25       10487775.
      3778730.75       10487524.      3778863.75       10487612.
      3778831.75       10487216.        3778987.       10487149.
      3778844.25       10487071.      3779013.25       10486943.
      3778740.25       10486821.      3778937.75       10486503.
        3778273.       10485779.      3778260.25       10485090.
      3777971.75       10484795.       3777632.5       10484768.
       3777875.5       10484585.        3777701.       10484496.
      3777644.25       10483677.      3777072.25       10483099.
      3776965.25       10481956.      3776480.75       10481770.

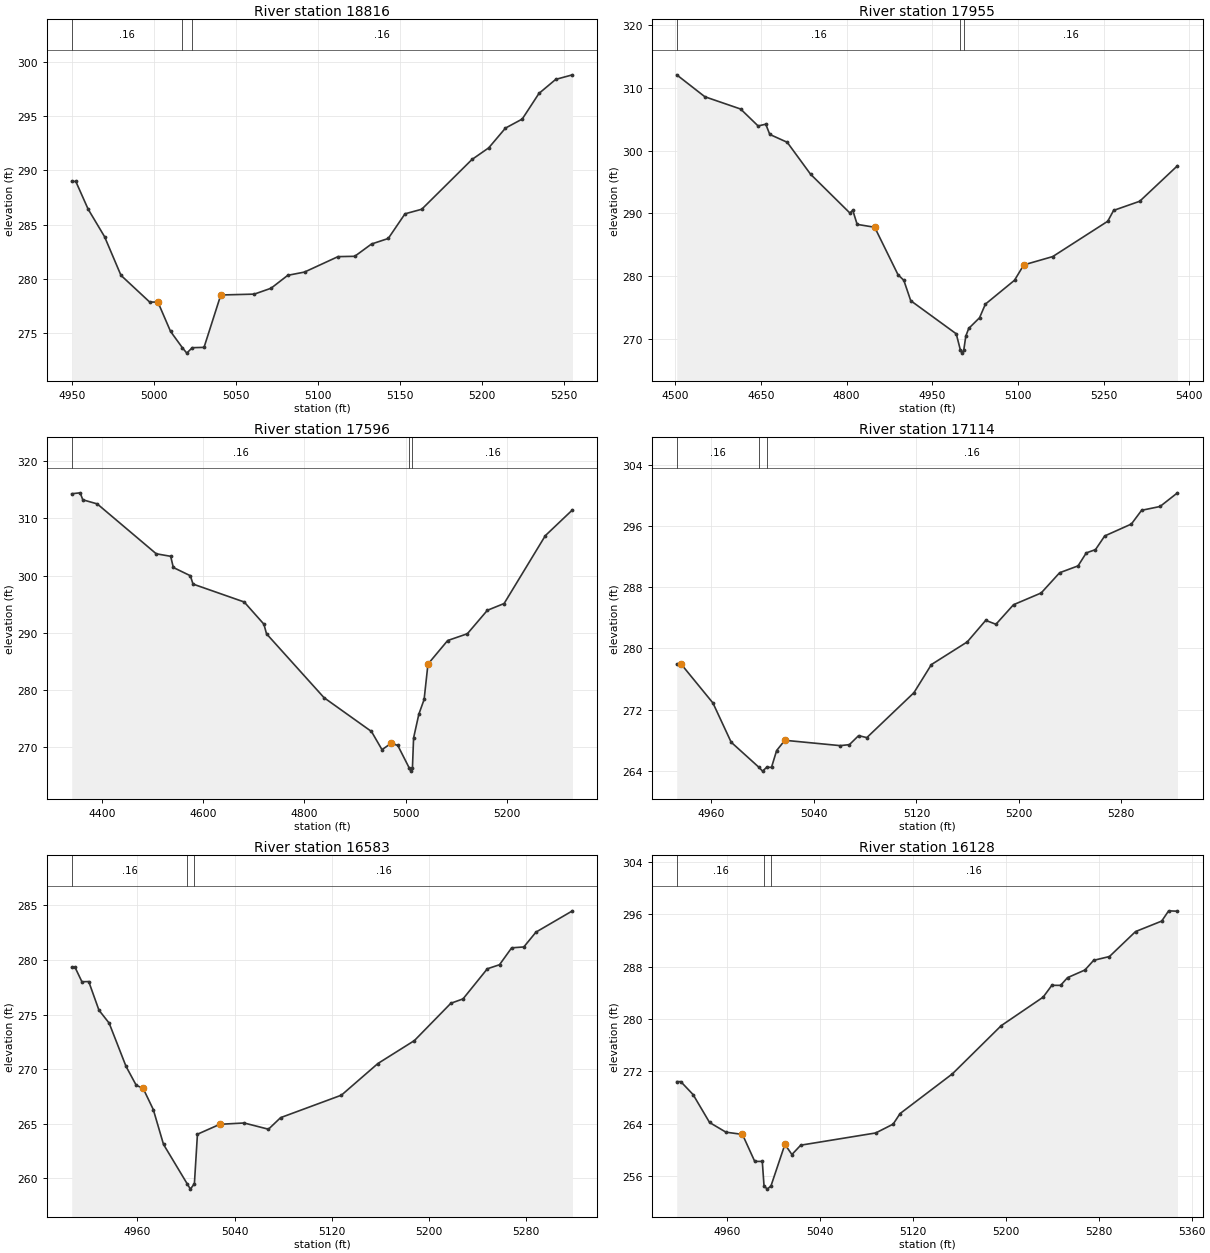
Type RM Length L Ch R = 1 ,18816   ,861,861,861
BEGIN DESCRIPTION:
UNT064 IN BECR 32.0
END DESCRIPTION:
XS GIS Cut Line= 3
      3775949.61     10492010.19      3775899.61     10492010.19
      3775649.56     10491960.18
#Sta/Elev= 30
    4950  288.99  4952.5  288.99    4960  286.44    4970  283.91    4980  280.35
  4997.5  277.89  5002.5  277.89  5010.2  275.19  5017.4  273.69  5020.1  273.19
  5023.4  273.69  5030.6  273.72  5040.8  278.54  5061.2  278.62  5071.4  279.16
  5081.6  280.35  5091.8  280.65  5112.2  282.07  5122.4   282.1  5132.6  283.23
  5142.8  283.74    5153  286.01  5163.2  286.43  5193.8  291.01    5204  292.08
  5214.2   293.9  5224.4  294.73  5234.6  297.09  5244.8  298.38    5255   298.8
#Mann= 3 ,-1 , 0
    4950     .16       0  5017.4     .07       0  5023.4     .16       0
Bank Sta=5002.5,5040.8
XS Rating Curve= 0 ,0
Exp/Cntr=0.3,0.1

Type RM Length L Ch R = 1 ,17955   ,359,359,359
BEGIN DESCRIPTION:
UNT064 IN BECR 31.0
END DESCRIPTION:
XS GIS Cut Line= 2
       3776419.3     10491655.67      3775559.96     10491482.07
#Sta/Elev= 30
  4502.6  312.11  4551.9  308.61  4614.5  306.65  4645.1  303.95  4658.5  304.23
  4665.5   302.6  4696.1  301.34  4736.9  296.25  4805.7  290.06  4810.8  290.49
  4818.5  288.24  4849.2  287.78    4890  280.21  4900.2  279.31  4912.3  276.06
    4992  270.77  4999.2  268.19  5001.9  267.69  5005.2  268.19  5008.7   270.4
  5013.8  271.63  5032.8  273.34    5043  275.51    5094  279.32  5110.2  281.77
  5160.9   283.1  5257.2  288.74  5267.5  290.47  5313.2  291.93  5379.3   297.6
#Mann= 3 ,-1 , 0
  4502.6     .16       0  4999.2     .07       0  5005.2     .16       0
Bank Sta=4849.2,5110.2
XS Rating Curve= 0 ,0
Exp/Cntr=0.3,0.1

Type RM Length L Ch R = 1 ,17596   ,482,482,482
BEGIN DESCRIPTION:
UNT064 IN BECR 30.0
END DESCRIPTION:
XS GIS Cut Line= 2
      3776588.61     10491460.37      3775638.06     10491186.92
#Sta/Elev= 30
  4340.6  314.34  4357.3   314.5  4362.5  313.28    4391  312.56  4507.6  303.81
  4536.1  303.37  4541.3  301.41    4575  299.96  4580.2   298.5  4681.3  295.36
  4720.2  291.47  4725.4  289.78    4839  278.58  4932.7  272.65  4953.5  269.46
  4971.7  270.59  4984.7   270.2  5007.6   266.2  5010.3   265.7  5013.6   266.2
  5015.9  271.52  5026.3  275.69  5036.7  278.27  5044.3  284.47  5083.2   288.6
  5122.1  289.79  5161.6   293.9  5194.7  295.09  5276.1  306.99  5329.7  311.51
#Mann= 3 ,-1 , 0
  4340.6     .16       0  5007.6     .07       0  5013.6     .16       0
Bank Sta=4971.7,5044.3
XS Rating Curve= 0 ,0
Exp/Cntr=0.3,0.1

Type RM Length L Ch R = 1 ,17114   ,531,531,531
BEGIN DESCRIPTION:
UNT064 IN BECR 29.0
END DESCRIPTION:
XS GIS Cut Line= 3
      3776249.64     10491060.22      3776199.61     10491010.19
      3775949.62      10490810.2
#Sta/Elev= 30
  4932.9  277.92  4936.5  277.92  4961.2  272.85  4975.4  267.72  4997.1  264.43
  4999.9  263.93  5003.1  264.43  5006.9  264.43  5010.9  266.63  5017.3  267.97
  5060.5  267.27  5067.7   267.4  5074.9  268.58  5081.3  268.32  5118.1  274.21
  5131.7  277.89  5159.7  280.86  5174.1  283.68  5182.1  283.17  5195.8  285.73
  5217.4  287.27  5231.8  289.92  5246.2  290.82  5252.6  292.52  5259.8  292.95
    5267  294.74  5287.8   296.3  5295.8   298.1  5310.2   298.6  5323.8  300.39
#Mann= 3 ,-1 , 0
  4932.9     .16       0  4997.1     .07       0  5003.1     .16       0
Bank Sta=4936.5,5017.3
XS Rating Curve= 0 ,0
Exp/Cntr=0.3,0.1

Type RM Length L Ch R = 1 ,16583   ,455,455,455
BEGIN DESCRIPTION:
UNT064 IN BECR 28.0
END DESCRIPTION:
XS GIS Cut Line= 3
      3776549.63      10490710.2      3776449.61     10490660.19
      3776149.64     10490660.19
#Sta/Elev= 30
  4906.1  279.32  4908.9  279.32  4914.5  278.01  4920.1  278.03  4928.5  275.41
  4936.9  274.22  4950.8  270.25  4959.2  268.52  4964.8  268.25  4973.2   266.3
  4981.6  263.11    5001  259.51  5003.7  259.01    5007  259.51  5009.5  264.04
  5027.9  264.95  5047.9  265.07  5067.9   264.5  5077.9  265.56  5127.9  267.62
  5157.9  270.52  5187.9  272.62  5217.9  276.04  5227.9  276.44  5247.9   279.2
  5257.9  279.57  5267.9  281.12  5277.9   281.2  5287.9  282.56  5317.9  284.51
#Mann= 3 ,-1 , 0
  4906.1     .16       0    5001     .07       0    5007     .16       0
Bank Sta=4964.8,5027.9
XS Rating Curve= 0 ,0
Exp/Cntr=0.3,0.1

Type RM Length L Ch R = 1 ,16128   ,572,572,572
BEGIN DESCRIPTION:
UNT064 IN BECR 27.0
END DESCRIPTION:
XS GIS Cut Line= 3
       3776699.6     10490360.18      3776649.61     10490310.19
      3776349.57     10490110.16
#Sta/Elev= 30
  4916.5  270.43    4920  270.43  4930.6  268.45  4944.8  264.18  4958.9   262.7
  4973.1  262.36  4983.7  258.23  4990.2  258.23  4991.7  254.49  4994.5  253.99
  4997.7  254.49  5009.7  260.84  5015.7  259.28  5023.3  260.71  5087.9  262.58
  5102.9  263.93  5108.9  265.55    5154  271.63    5196  278.99  5232.1  283.35
  5239.6  285.16  5247.1  285.15  5253.1  286.33  5268.1   287.5  5275.6  288.98
  5289.2  289.56  5311.7  293.38  5334.2  294.98  5340.2  296.55  5347.8  296.49
#Mann= 3 ,-1 , 0
  4916.5     .16       0  4991.7     .07       0  4997.7     .16       0
Bank Sta=4973.1,5009.7
XS Rating Curve= 0 ,0
Exp/Cntr=0.3,0.1

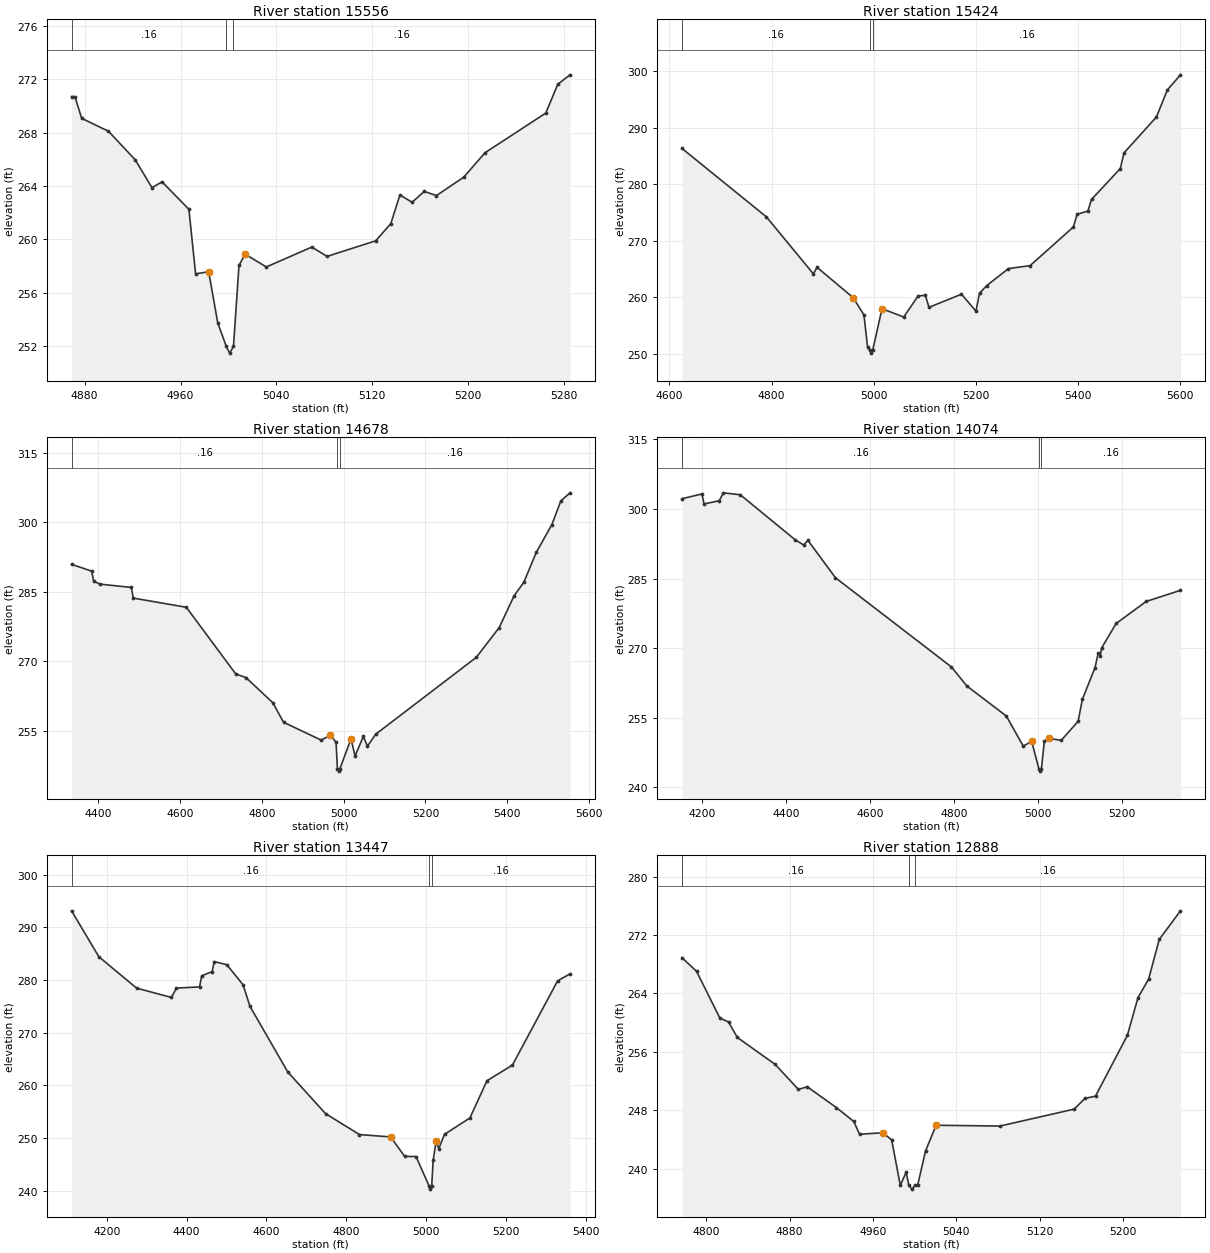
Type RM Length L Ch R = 1 ,15556   ,132,132,132
BEGIN DESCRIPTION:
UNT064 IN BECR 26.0
END DESCRIPTION:
XS GIS Cut Line= 3
      3776999.62     10490110.22      3776949.61     10490010.19
      3776649.58     10489960.18
#Sta/Elev= 30
  4869.1   270.7  4871.9   270.7  4877.5  269.07  4899.9   268.1  4922.2  265.96
  4936.2  263.87  4944.6  264.31    4967  262.25  4972.6  257.41  4983.5  257.57
  4991.1  253.73  4998.2  251.97    5001  251.47  5004.2  251.97  5008.8  258.04
  5013.9  258.89  5031.6  257.93  5069.6  259.42  5082.3  258.72  5122.9  259.89
  5135.5  261.18  5143.1  263.32  5153.3  262.78  5163.4  263.59  5173.6  263.28
  5196.4  264.66  5214.1  266.49  5264.8  269.46  5274.9  271.63  5285.1  272.33
#Mann= 3 ,-1 , 0
  4869.1     .16       0  4998.2     .07       0  5004.2     .16       0
Bank Sta=4983.5,5013.9
XS Rating Curve= 0 ,0
Exp/Cntr=0.3,0.1

Type RM Length L Ch R = 1 ,15424   ,746,746,746
BEGIN DESCRIPTION:
UNT064 IN BECR 25.0
END DESCRIPTION:
XS GIS Cut Line= 2
      3777243.97     10490149.59      3776545.21     10489468.19
#Sta/Elev= 30
  4624.6  286.32  4789.9  274.21  4881.9  264.13  4888.9   265.3  4959.6  259.94
  4980.8  256.88  4987.9  251.22  4991.9  250.62  4994.7  250.12  4997.9  250.62
  5016.2  257.98  5058.7   256.5  5086.9  260.24  5101.1  260.34  5108.1  258.22
  5171.8  260.54  5200.1  257.55  5207.1  260.71  5221.2  262.06  5263.7  265.07
  5306.1  265.59    5391  272.44  5398.1  274.68  5419.3  275.24  5426.4   277.3
  5482.8  282.77    5490  285.53  5553.6   291.9  5574.9  296.67  5600.6  299.34
#Mann= 3 ,-1 , 0
  4624.6     .16       0  4991.9     .07       0  4997.9     .16       0
Bank Sta=4959.6,5016.2
XS Rating Curve= 0 ,0
Exp/Cntr=0.3,0.1

Type RM Length L Ch R = 1 ,14678   ,604,604,604
BEGIN DESCRIPTION:
UNT064 IN BECR 24.0
END DESCRIPTION:
XS GIS Cut Line= 3
      3777300.41     10490088.86      3777230.96     10489446.48
       3777170.2     10488877.94
#Sta/Elev= 30
  4335.5  290.95  4384.4  289.48  4389.5  287.32  4404.6  286.67  4481.3  285.97
  4486.3  283.66  4615.8  281.68  4736.5  267.29  4761.6  266.49    4827  261.09
  4853.4  256.85  4945.2     253  4967.8  254.02  4981.6  252.56    4985   246.8
  4987.7   246.3    4991   246.8  5018.1  253.27  5028.2  249.57  5048.3  253.81
  5058.4  251.69  5078.5  254.27  5324.3  270.86  5380.2  277.29  5416.6  284.15
  5440.5  287.09  5470.7  293.51  5508.9  299.52    5531  304.67  5553.4  306.39
#Mann= 3 ,-1 , 0
  4335.5     .16       0    4985     .07       0    4991     .16       0
Bank Sta=4967.8,5018.1
XS Rating Curve= 0 ,0
Exp/Cntr=0.3,0.1

Type RM Length L Ch R = 1 ,14074   ,627,627,627
BEGIN DESCRIPTION:
UNT064 IN BECR 23.0
END DESCRIPTION:
XS GIS Cut Line= 3
      3777469.68     10490388.27      3777565.16      10489394.4
      3777582.52     10489207.75
#Sta/Elev= 30
  4153.2  302.22  4200.6  303.25  4205.6  301.09  4241.7  301.78  4251.7  303.49
  4291.9  303.07  4422.5  293.35  4442.6  292.23  4452.7  293.24  4518.2  285.17
  4794.2  265.91  4830.8  261.81  4924.8  255.32    4965  248.83  4985.1  249.85
  5002.2  243.93  5004.9  243.43  5008.2  243.93  5015.2  249.89  5025.3  250.48
  5055.4  250.08  5095.6  254.18  5105.6   258.9  5135.8  265.78  5143.3  268.89
  5148.4  268.28  5151.3     270    5186  275.29  5257.5  280.05  5339.1  282.45
#Mann= 3 ,-1 , 0
  4153.2     .16       0  5002.2     .07       0  5008.2     .16       0
Bank Sta=4985.1,5025.3
XS Rating Curve= 0 ,0
Exp/Cntr=0.3,0.1

Type RM Length L Ch R = 1 ,13447   ,559,559,559
BEGIN DESCRIPTION:
UNT064 IN BECR 22.0
END DESCRIPTION:
XS GIS Cut Line= 3
      3778706.66     10489767.66      3778033.91     10489541.96
       3777625.9     10489190.38
#Sta/Elev= 30
  4112.2  293.16  4180.3  284.45  4274.9  278.48  4362.2   276.7  4374.8  278.48
  4432.6  278.71  4437.9  280.81  4464.1  281.61  4469.4  283.52  4500.9  282.92
  4541.6   279.1  4558.8  275.02  4653.4  262.56    4748  254.64  4833.1  250.65
    4911  250.21  4946.3  246.51  4974.7  246.48  5007.9  240.79  5010.6  240.29
  5013.9  240.79  5017.5  245.73  5025.1  249.36  5031.7  247.98    5046   250.7
  5109.6  253.81  5152.4  260.89    5216  263.85  5329.1  279.84  5360.4   281.2
#Mann= 3 ,-1 , 0
  4112.2     .16       0  5007.9     .07       0  5013.9     .16       0
Bank Sta=4911,5025.1
XS Rating Curve= 0 ,0
Exp/Cntr=0.3,0.1

Type RM Length L Ch R = 1 ,12888   ,428,428,428
BEGIN DESCRIPTION:
UNT064 IN BECR 21.0
END DESCRIPTION:
XS GIS Cut Line= 3
      3778249.62     10489260.19      3778049.61     10489160.19
      3777799.58     10489110.18
#Sta/Elev= 30
  4776.7  268.88  4790.7  267.01    4813  260.62  4821.4  260.07  4829.8  257.96
  4866.2  254.26  4888.5  250.83  4896.9  251.21  4924.9  248.35  4941.6  246.45
  4947.2   244.7  4969.6   244.9    4978  243.92  4986.3  237.69  4991.9   239.5
  4994.5  237.68  4997.3  237.18  5000.5  237.68  5002.9  237.68  5010.5  242.41
  5020.7  245.93  5081.9  245.82  5153.3  248.14  5163.5   249.6  5173.7  249.92
  5204.3  258.24  5214.5  263.42  5224.7  265.94  5234.9  271.38  5255.3   275.3
#Mann= 3 ,-1 , 0
  4776.7     .16       0  4994.5     .07       0  5000.5     .16       0
Bank Sta=4969.6,5020.7
XS Rating Curve= 0 ,0
Exp/Cntr=0.3,0.1

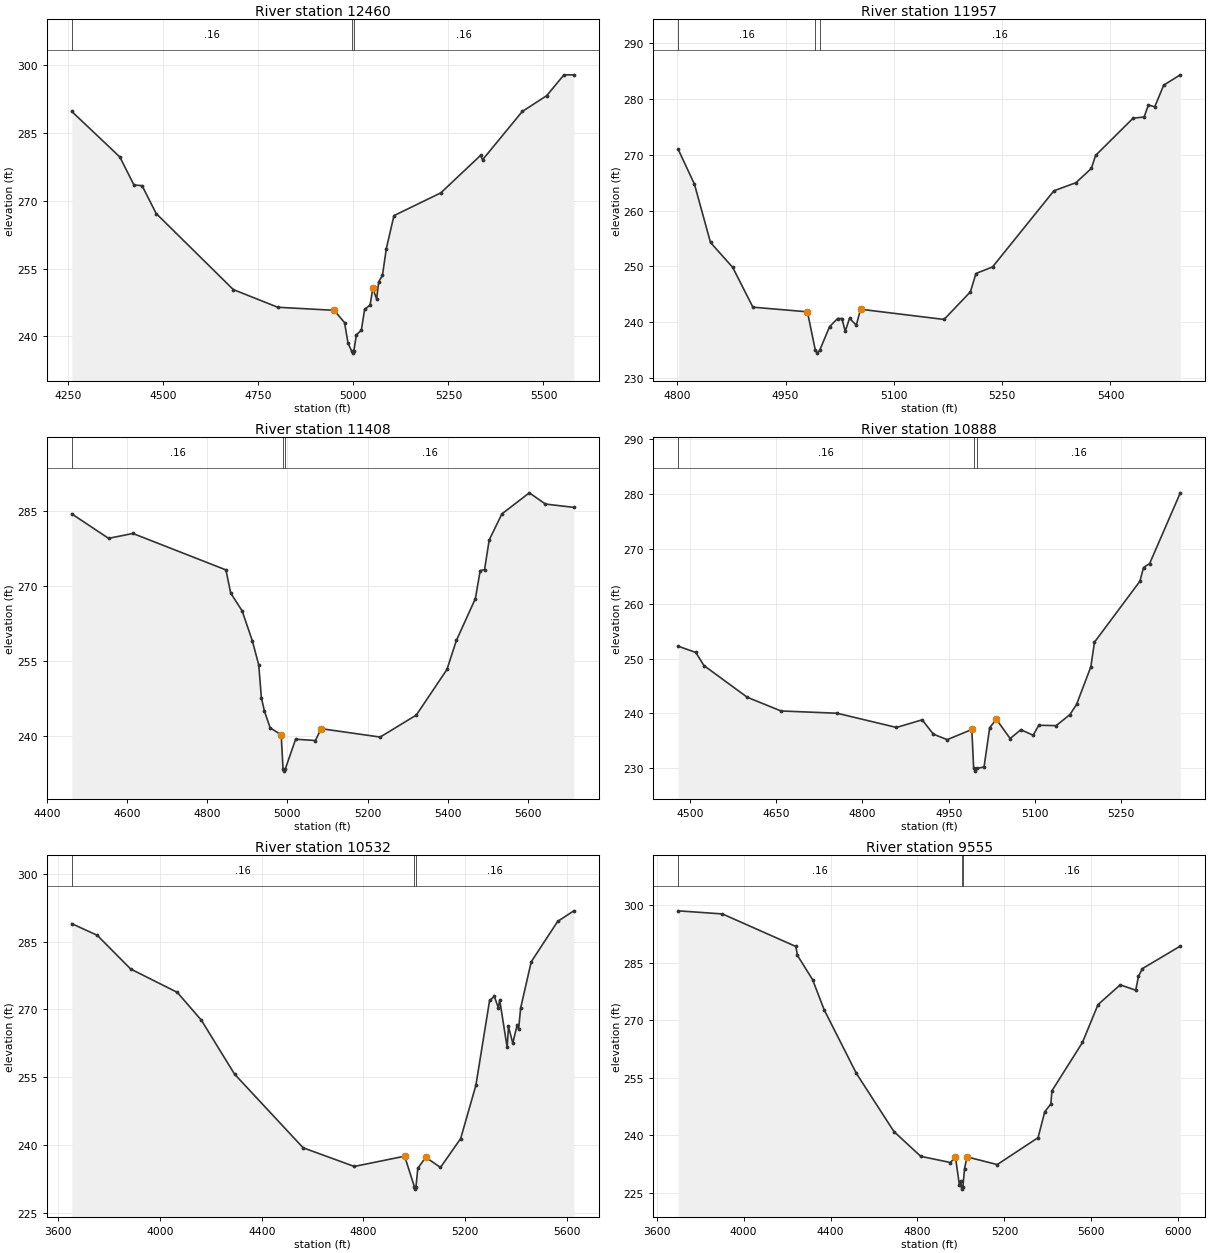
Type RM Length L Ch R = 1 ,12460   ,503,503,503
BEGIN DESCRIPTION:
UNT064 IN BECR 20.0
END DESCRIPTION:
XS GIS Cut Line= 3
      3778585.11     10489268.52      3777895.02     10488860.54
      3777378.49     10488812.79
#Sta/Elev= 30
  4259.5  289.78  4385.9  279.71    4423  273.51  4444.4  273.36  4481.5   267.2
  4684.3  250.37  4801.3  246.46  4949.6  245.78  4976.9  243.06  4986.1  238.49
  4995.3  236.81  4998.1  236.31  5001.3  236.81  5008.1  240.38    5021  241.37
  5029.6  245.97  5044.2  246.97    5051  250.63  5061.2   248.3  5066.6  252.08
  5076.6  253.52  5086.7  259.42  5106.8  266.73  5230.1  271.77  5334.7  280.07
  5339.7  279.08  5444.2  289.77  5508.5  293.27  5553.8  297.87  5579.9  297.88
#Mann= 3 ,-1 , 0
  4259.5     .16       0  4995.3     .07       0  5001.3     .16       0
Bank Sta=4949.6,5051
XS Rating Curve= 0 ,0
Exp/Cntr=0.3,0.1

Type RM Length L Ch R = 1 ,11957   ,549,549,549
BEGIN DESCRIPTION:
UNT064 IN BECR 19.0
END DESCRIPTION:
XS GIS Cut Line= 3
      3778499.61     10488810.19      3778299.61     10488710.19
      3778049.61     10488310.19
#Sta/Elev= 30
  4801.4  270.99  4823.8  264.78  4846.1   254.3  4876.9  249.83  4904.8   242.7
  4980.3  241.87  4991.3  234.96    4994  234.46  4997.3  234.96    5011  239.22
  5022.2  240.67    5028  240.67  5032.7  238.38  5038.6   240.7    5048  239.48
  5053.9  242.33  5169.5   240.5    5206  245.45  5213.7  248.74  5236.7  249.92
  5321.6  263.57  5352.2  265.03  5373.5  267.59  5379.4  269.92  5431.3  276.59
  5446.6  276.81  5452.5  278.96  5461.3  278.64  5473.7  282.52  5496.7  284.37
#Mann= 3 ,-1 , 0
  4801.4     .16       0  4991.3     .07       0  4997.3     .16       0
Bank Sta=4980.3,5053.9
XS Rating Curve= 0 ,0
Exp/Cntr=0.3,0.1

Type RM Length L Ch R = 1 ,11408   ,520,520,520
BEGIN DESCRIPTION:
UNT064 IN BECR 18.0
END DESCRIPTION:
XS GIS Cut Line= 4
      3778667.59     10489051.53      3778606.83     10488604.46
      3778446.24     10488417.83      3777934.38     10488200.94
#Sta/Elev= 30
  4461.7  284.43  4553.5  279.53  4614.4   280.5  4846.5  273.21  4858.4  268.57
  4886.9  265.02  4912.5     259  4928.4  254.19    4935  247.64  4942.6  244.94
  4956.9   241.6  4984.5  240.18    4989  233.42  4991.8  232.92    4995  233.42
  5020.5  239.31  5069.9  239.05  5084.2  241.42  5231.5  239.74  5321.7  244.14
  5398.2  253.27  5421.8  259.09  5469.2  267.46  5481.2  273.06  5492.1  273.26
  5503.7  279.21  5535.5  284.43  5603.9  288.64  5644.2  286.39    5715  285.73
#Mann= 3 ,-1 , 0
  4461.7     .16       0    4989     .07       0    4995     .16       0
Bank Sta=4984.5,5084.2
XS Rating Curve= 0 ,0
Exp/Cntr=0.3,0.1

Type RM Length L Ch R = 1 ,10888   ,356,356,356
BEGIN DESCRIPTION:
UNT064 IN BECR 17.0
END DESCRIPTION:
XS GIS Cut Line= 3
      3778949.59     10488260.18      3778549.61     10488060.19
       3778149.6     10488210.19
#Sta/Elev= 30
  4479.1  252.27  4509.8  251.13  4523.8  248.75  4599.3  242.96    4658  240.46
  4755.8  240.04  4859.2  237.45  4903.9  238.84  4923.5  236.22  4947.6  235.22
  4990.4  237.08  4993.6  229.98  4996.3  229.48  4999.6  229.98  5011.7  230.24
  5021.5  237.41  5033.1  238.94  5057.1  235.43  5075.8  237.04  5097.2  236.03
    5107  237.85  5137.2  237.78  5161.2  239.79  5172.8  241.65  5197.7  248.53
    5204  253.01  5283.2  264.14  5289.4  266.63  5300.1  267.36  5353.5  280.26
#Mann= 3 ,-1 , 0
  4479.1     .16       0  4993.6     .07       0  4999.6     .16       0
Bank Sta=4990.4,5033.1
XS Rating Curve= 0 ,0
Exp/Cntr=0.3,0.1

Type RM Length L Ch R = 1 ,10532   ,977,977,977
BEGIN DESCRIPTION:
UNT064 IN BECR 16.0
END DESCRIPTION:
XS GIS Cut Line= 3
      3779674.57     10488504.66      3778637.21     10487866.62
      3777908.02     10487666.96
#Sta/Elev= 30
  3653.1  288.95  3753.1  286.38  3884.5  278.92    4068  273.74  4162.7  267.58
  4292.9  255.66  4562.7  239.34  4763.8  235.21  4961.8  237.48  5000.3  230.69
    5003  230.19  5006.3  230.69  5013.6   234.8  5044.7  237.24  5102.7  234.99
    5182  241.39  5241.7  253.13  5295.8  271.96  5314.3  272.85  5330.3  270.33
  5335.5  272.07  5364.8  261.55    5370  266.19  5386.9  262.49  5404.5  266.61
  5409.7  265.56    5418  270.32  5459.5  280.52  5563.2  289.44    5627  291.79
#Mann= 3 ,-1 , 0
  3653.1     .16       0  5000.3     .07       0  5006.3     .16       0
Bank Sta=4961.8,5044.7
XS Rating Curve= 0 ,0
Exp/Cntr=0.3,0.1

Type RM Length L Ch R = 1 ,9555    ,611,611,611
BEGIN DESCRIPTION:
UNT064 IN BECR 15.0
END DESCRIPTION:
XS GIS Cut Line= 3
      3780156.27     10487901.32      3778919.33     10487389.19
      3777968.76     10487584.51
#Sta/Elev= 30
  3699.6  298.56  3902.8  297.75  4240.5  289.27    4248  286.93  4317.6  280.61
  4370.8  272.76  4518.6  256.22  4691.7  241.02  4814.9  234.56  4951.5  232.95
  4974.5  234.41    4993  227.01  4998.4  228.18  5002.6  226.51  5005.4  226.01
  5008.6  226.51  5016.4  231.36  5027.7  234.42  5166.6  232.41  5354.6  239.43
  5385.2  246.16  5413.3  248.21  5418.4  251.65  5558.7  264.24  5630.2  274.11
  5732.3  279.26  5803.8  277.87  5816.3  281.48  5834.4   283.5  6008.8  289.37
#Mann= 3 ,-1 , 0
  3699.6     .16       0  5002.6     .07       0  5008.6     .16       0
Bank Sta=4974.5,5027.7
XS Rating Curve= 0 ,0
Exp/Cntr=0.3,0.1

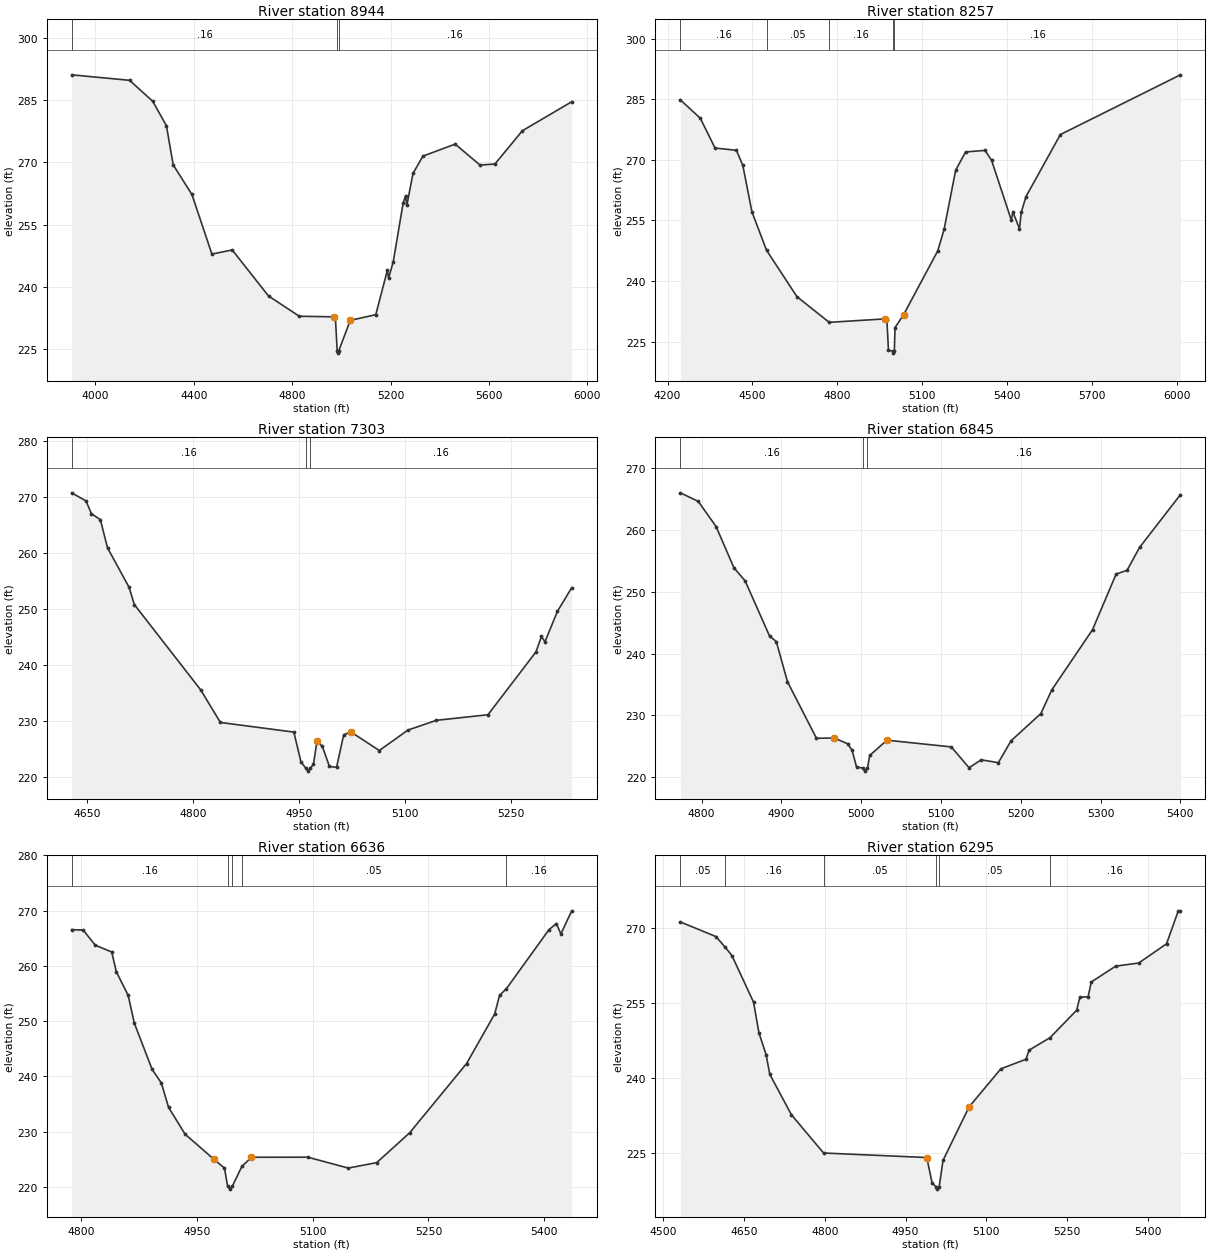
Type RM Length L Ch R = 1 ,8944    ,687,687,687
BEGIN DESCRIPTION:
UNT064 IN BECR 14.0
END DESCRIPTION:
XS GIS Cut Line= 3
      3780034.77     10487467.31      3778928.01     10487128.77
      3778059.99     10487241.61
#Sta/Elev= 30
  3903.2  291.04  4138.7  289.72  4232.8  284.67  4288.4   278.8    4316  269.38
    4392  262.26  4473.3  247.93  4555.9  248.92  4703.4  237.85  4828.6  232.97
  4970.1  232.83  4975.4  232.56  4982.7   224.6  4985.5   224.1  4988.7   224.6
  5035.7  231.98  5139.6  233.35  5186.5  244.01  5191.5  242.17  5210.2  245.97
  5250.6  260.16  5260.6  261.94  5265.6  259.61  5290.9  267.34  5331.2  271.49
  5462.3  274.37  5563.2  269.34  5623.7  269.58  5735.3  277.58  5935.9  284.56
#Mann= 3 ,-1 , 0
  3903.2     .16       0  4982.7     .07       0  4988.7     .16       0
Bank Sta=4970.1,5035.7
XS Rating Curve= 0 ,0
Exp/Cntr=0.3,0.1

Type RM Length L Ch R = 1 ,8257    ,954,954,954
BEGIN DESCRIPTION:
UNT064 IN BECR 13.0
END DESCRIPTION:
XS GIS Cut Line= 2
      3779470.51     10486547.19      3777855.97     10487267.65
#Sta/Elev= 30
  4245.5  284.84  4315.9  280.31  4367.9  272.93  4443.6  272.36  4466.2  268.63
  4498.4  257.14    4550  247.63  4657.5  236.13  4771.7  229.77  4969.2  230.63
  4975.7  230.29  4981.2  222.87    4996  222.65  4998.7  222.15    5002  222.65
  5004.4  228.48  5034.9  231.68  5155.4  247.46  5177.9  252.79  5218.9  267.45
  5253.9  271.96  5322.7  272.34  5345.9  269.87  5415.6  255.08  5421.1  257.12
  5444.3  252.95    5451  257.07  5467.5  260.91  5589.1  276.26  6013.5  291.05
#Mann= 5 ,-1 , 0
  4245.5     .16       0    4550     .05       0  4771.7     .16       0
    4996     .07       0    5002     .16       0
Bank Sta=4969.2,5034.9
XS Rating Curve= 0 ,0
Exp/Cntr=0.3,0.1

Type RM Length L Ch R = 1 ,7303    ,458,458,458
BEGIN DESCRIPTION:
UNT064 IN BECR 12.0
END DESCRIPTION:
XS GIS Cut Line= 3
      3779049.65     10486360.18      3778749.61     10486410.19
       3778349.6     10486360.19
#Sta/Elev= 30
  4628.7  270.73    4649  269.28  4656.6  267.01  4669.3  265.93  4679.4  260.91
  4709.8  253.89  4717.4  250.77  4811.2  235.55  4839.1  229.73    4943  228.01
    4953   222.7  4960.1  221.54  4962.9  221.04  4966.1  221.54  4970.7  222.23
  4975.7   226.4  4983.3  225.48  4993.3  221.87  5003.4  221.73  5013.5  227.52
  5023.6  228.04  5063.9  224.72  5104.2  228.36  5144.5  230.11  5217.6  231.11
  5285.6  242.35  5293.2  245.09  5298.2  244.13  5315.8  249.56    5336  253.79
#Mann= 3 ,-1 , 0
  4628.7     .16       0  4960.1     .07       0  4966.1     .16       0
Bank Sta=4975.7,5023.6
XS Rating Curve= 0 ,0
Exp/Cntr=0.3,0.1

Type RM Length L Ch R = 1 ,6845    ,209,209,209
BEGIN DESCRIPTION:
UNT064 IN BECR 11.0
END DESCRIPTION:
XS GIS Cut Line= 3
      3778649.62     10485810.17      3778549.61     10486010.19
      3778199.64     10486210.17
#Sta/Elev= 30
  4773.4  266.03  4795.8  264.64  4818.1  260.58  4840.5   253.9  4854.5  251.79
  4885.2  242.84  4893.6  241.96  4907.6  235.46  4943.9  226.31  4966.3  226.35
    4983  225.42  4988.6  224.36  4994.2  221.64  5001.9  221.49  5004.7  220.99
  5007.9  221.49  5010.7  223.53  5032.3     226  5112.9  224.91  5135.2  221.54
  5150.4  222.82  5171.9  222.36  5187.8  225.89  5225.2  230.31  5238.9  234.14
    5290  243.89  5319.5  252.88  5333.2  253.49    5349  257.21  5400.1  265.73
#Mann= 3 ,-1 , 0
  4773.4     .16       0  5001.9     .07       0  5007.9     .16       0
Bank Sta=4966.3,5032.3
XS Rating Curve= 0 ,0
Exp/Cntr=0.3,0.1

Type RM Length L Ch R = 1 ,6636    ,341,341,341
BEGIN DESCRIPTION:
Mapping XS 828c0abe
END DESCRIPTION:
XS GIS Cut Line= 2
      3778629.23     10485728.53      3778074.17      10486063.3
#Sta/Elev= 30
  4787.5  266.58  4802.5  266.49    4818  263.77  4839.4  262.53  4845.4  258.94
  4860.7   254.7  4868.8  249.63  4891.8  241.28  4903.8  238.82  4913.1  234.41
  4934.5  229.56  4971.4  225.07  4985.6  223.42  4989.7  220.11  4992.5  219.61
  4995.7  220.11  5008.1  223.71  5020.6  225.38  5093.7  225.39  5146.1  223.42
    5183  224.41  5225.7  229.81  5299.4  242.33  5335.9  251.31  5342.2  254.69
  5351.1  255.89  5406.2  266.56  5415.9  267.68  5421.7  265.79  5435.7  269.98
#Mann= 5 ,-1 , 0
  4787.5     .16       0  4989.7     .07       0  4995.7     .16       0
  5008.1     .05       0  5351.1     .16       0
Bank Sta=4971.4,5020.6
XS Rating Curve= 0 ,0
Exp/Cntr=0.3,0.1

Type RM Length L Ch R = 1 ,6295    ,66,66,66
BEGIN DESCRIPTION:
UNT064 IN BECR 10.0
END DESCRIPTION:
XS GIS Cut Line= 3
      3778714.77     10485628.71      3778121.07      10485691.2
      3777944.27       10485972.
#Sta/Elev= 30
  4531.7  271.14  4597.9  268.22  4614.4  266.17  4627.4  264.44  4667.6  255.15
  4677.7  248.99  4690.9  244.69  4697.8  240.75    4738  232.69  4797.7  225.08
  4989.4  224.18  4999.4  219.03  5006.5  218.38  5009.2  217.88  5012.5  218.38
  5019.5  223.61    5068  234.28  5126.9  241.86  5173.6  243.77  5179.5  245.59
  5218.4  248.08  5267.8  253.55  5273.7  256.14    5289  256.22  5294.9  259.17
  5340.2  262.33  5383.2  262.96  5434.7  266.79  5456.2  273.25  5460.5  273.36
#Mann= 6 ,-1 , 0
  4531.7     .05       0  4614.4     .16       0  4797.7     .05       0
  5006.5     .03       0  5012.5     .05       0  5218.4     .16       0
Bank Sta=4989.4,5068
XS Rating Curve= 0 ,0
Exp/Cntr=0.3,0.1

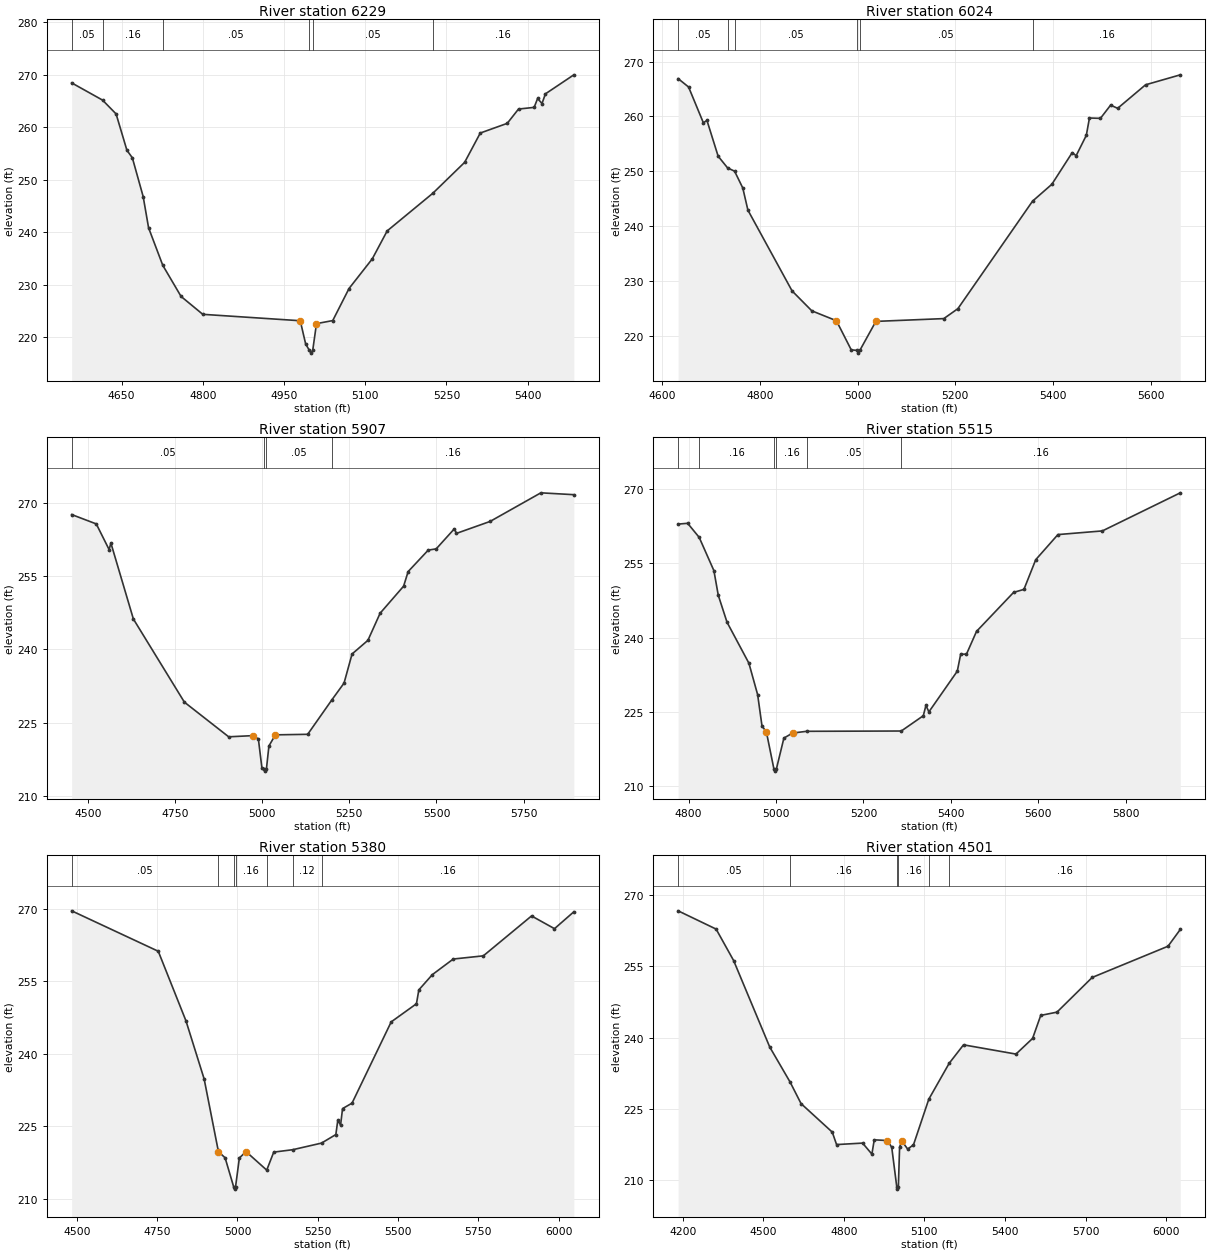
Type RM Length L Ch R = 1 ,6229    ,205,205,205
BEGIN DESCRIPTION:
Mapping XS ab643801
END DESCRIPTION:
XS GIS Cut Line= 3
      3778681.67     10485600.74      3778158.68     10485614.84
      3777910.23     10485933.82
#Sta/Elev= 30
  4557.9  268.41    4615  265.13    4640   262.5    4660  255.58    4670  254.16
    4690  246.78    4700  240.84  4726.2  233.71    4760  227.79  4800.1  224.39
  4980.1  223.17  4990.1  218.75  4997.1  217.51  4999.9  217.01  5003.1  217.51
  5010.1  222.62  5040.1   223.2  5070.2   229.3  5113.2  234.95  5140.7  240.26
  5224.9  247.41  5283.7  253.29  5312.6  258.87  5362.4  260.71  5383.2  263.43
  5412.1  263.75  5418.5  265.44  5426.6  264.48  5432.9  266.32  5485.4  269.94
#Mann= 6 ,-1 , 0
  4557.9     .05       0    4615     .16       0  4726.2     .05       0
  4997.1     .03       0  5003.1     .05       0  5224.9     .16       0
Bank Sta=4980.1,5010.1
XS Rating Curve= 0 ,0
Exp/Cntr=0.3,0.1

Type RM Length L Ch R = 1 ,6024    ,117,117,117
BEGIN DESCRIPTION:
Mapping XS 0f1b4aec
END DESCRIPTION:
XS GIS Cut Line= 3
      3778710.79     10485553.19      3778209.07     10485487.22
      3777885.22     10485895.94
#Sta/Elev= 30
  4632.9  266.89  4654.3  265.36  4684.5  258.84  4691.9  259.26  4714.8  252.73
    4734  250.61  4748.5  249.99  4765.2  246.93  4775.7  242.89  4866.1  228.15
  4906.4  224.52  4956.8  222.71  4987.1   217.4  4998.7   217.3  5001.4   216.8
  5004.7   217.3  5037.5  222.59  5176.5   223.1  5205.3  224.91  5358.1  244.53
  5397.6  247.61  5439.2  253.38  5447.3  252.83  5468.1  256.54  5474.5   259.7
    5497  259.64  5517.8  262.05  5532.2  261.47  5589.3  265.76  5660.4  267.58
#Mann= 6 ,-1 , 0
  4632.9     .05       0    4734     .16       0  4748.5     .05       0
  4998.7     .03       0  5004.7     .05       0  5358.1     .16       0
Bank Sta=4956.8,5037.5
XS Rating Curve= 0 ,0
Exp/Cntr=0.3,0.1

Type RM Length L Ch R = 1 ,5907    ,392,392,392
BEGIN DESCRIPTION:
UNT064 IN BECR 9.0
END DESCRIPTION:
XS GIS Cut Line= 3
      3778819.52     10485349.25      3778055.61      10485462.1
      3777725.77     10486043.68
#Sta/Elev= 30
  4453.4  267.63  4524.1  265.71  4560.9  260.45    4566  261.79  4630.5  246.24
  4776.8  229.21  4903.9  222.11  4973.5  222.35  4989.1  221.68  4999.2  215.77
  5006.3  215.58    5009  215.08  5012.3  215.58  5019.4  220.24    5038  222.51
  5130.6  222.62  5200.3  229.71  5234.9  233.11  5257.9  239.07  5303.4  241.87
  5338.4  247.42  5405.8  252.96  5418.8  255.95  5476.5  260.35  5499.3   260.6
  5551.5  264.72  5557.3  263.77  5653.9  266.22  5799.6  272.08  5894.2   271.7
#Mann= 4 ,-1 , 0
  4453.4     .05       0  5006.3     .03       0  5012.3     .05       0
  5200.3     .16       0
Bank Sta=4973.5,5038
XS Rating Curve= 0 ,0
Exp/Cntr=0.3,0.1

Type RM Length L Ch R = 1 ,5515    ,135,135,135
BEGIN DESCRIPTION:
Mapping XS 49812377
END DESCRIPTION:
XS GIS Cut Line= 3
      3778491.42     10485131.99      3778221.89     10485118.97
      3777725.92     10485845.35
#Sta/Elev= 30
  4775.9  262.95  4797.7  263.11  4824.1  260.27  4857.8  253.54  4867.8  248.57
  4887.8  243.12  4937.9  234.83  4957.9  228.47  4967.9  222.13  4977.9  220.94
    4995  213.51  4997.7  213.01    5001  213.51    5018  219.69    5038  220.71
  5070.1  221.06  5286.7  221.12  5337.1  224.21  5343.1  226.29  5349.9  224.99
  5414.9  233.22  5422.6  236.64  5435.9  236.66  5458.9  241.26  5543.7  249.14
  5567.4  249.75  5594.4  255.75  5645.2  260.83  5746.9  261.57  5925.3  269.27
#Mann= 6 ,-1 , 0
  4775.9     .05       0  4824.1     .16       0    4995     .07       0
    5001     .16       0  5070.1     .05       0  5286.7     .16       0
Bank Sta=4977.9,5038
XS Rating Curve= 0 ,0
Exp/Cntr=0.3,0.1

Type RM Length L Ch R = 1 ,5380    ,879,879,879
BEGIN DESCRIPTION:
UNT064 IN BECR 8.0
END DESCRIPTION:
XS GIS Cut Line= 2
      3778489.62     10484594.08      3777586.84     10485870.12
#Sta/Elev= 30
  4483.9  269.63  4753.5  261.25  4839.7  246.83  4896.3  234.78  4939.6  220.11
  4940.6  219.72  4961.5  218.45  4988.1  212.45  4990.8  211.95  4994.1  212.45
  5005.9  218.41  5026.8  219.72  5091.1  215.89  5112.9  219.62    5172  220.12
  5261.6  221.49  5306.2  223.26  5312.3  226.21    5321  225.23  5327.1  228.64
  5356.6  229.77  5478.5  246.61  5557.1  250.37  5564.6  253.25  5606.5   256.4
  5671.7  259.64  5765.3   260.3  5915.4  268.57  5986.8  265.93    6047  269.43
#Mann= 7 ,-1 , 0
  4483.9     .05       0  4939.6     .16       0  4988.1     .07       0
  4994.1     .16       0  5091.1     .05       0    5172     .12       0
  5261.6     .16       0
Bank Sta=4940.6,5026.8
XS Rating Curve= 0 ,0
Exp/Cntr=0.3,0.1

Type RM Length L Ch R = 1 ,4501    ,715,715,715
BEGIN DESCRIPTION:
UNT064 IN BECR 7.0
END DESCRIPTION:
XS GIS Cut Line= 3
      3778428.89     10484446.47      3777500.06     10484967.31
      3777395.94     10485765.55
#Sta/Elev= 30
  4182.9   266.7  4324.4  262.85  4389.5  256.23  4524.1  237.99  4599.9  230.61
  4640.7  226.07  4756.9  220.06  4772.9  217.44  4869.8  217.75  4904.4  215.43
  4913.2  218.44  4962.3  218.29  4978.3  216.87    4997  208.55  4999.7  208.05
    5003  208.55  5007.6  216.92  5015.9  218.19  5037.6  216.49  5059.3  217.39
  5116.3     227  5192.1  234.56  5245.6  238.46  5440.9  236.51  5502.8  239.81
  5533.1  244.66  5593.6  245.35  5724.7  252.66  6007.1  259.24  6052.8  262.78
#Mann= 6 ,-1 , 0
  4182.9     .05       0  4599.9     .16       0    4997     .07       0
    5003     .16       0  5116.3     .12       0  5192.1     .16       0
Bank Sta=4962.3,5015.9
XS Rating Curve= 0 ,0
Exp/Cntr=0.3,0.1