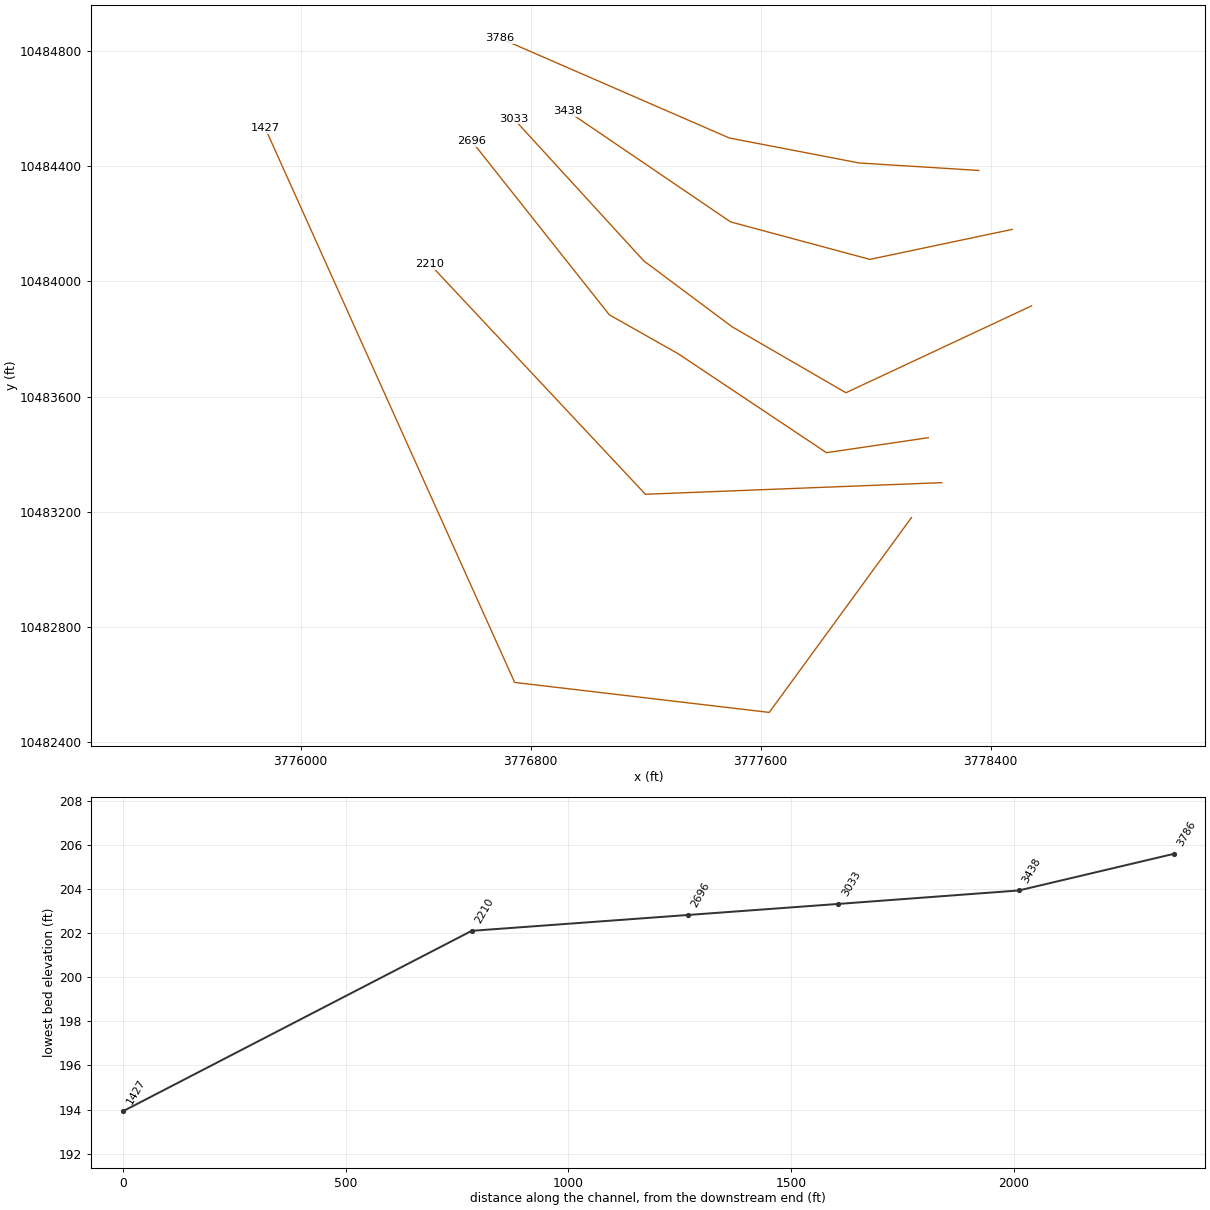
HEC-RAS study UNT064 IN BECR.prj: UNT064 IN BECR Base Level Engineering

--- UNT064 IN BECR.g01 (geometry) --- (continued)

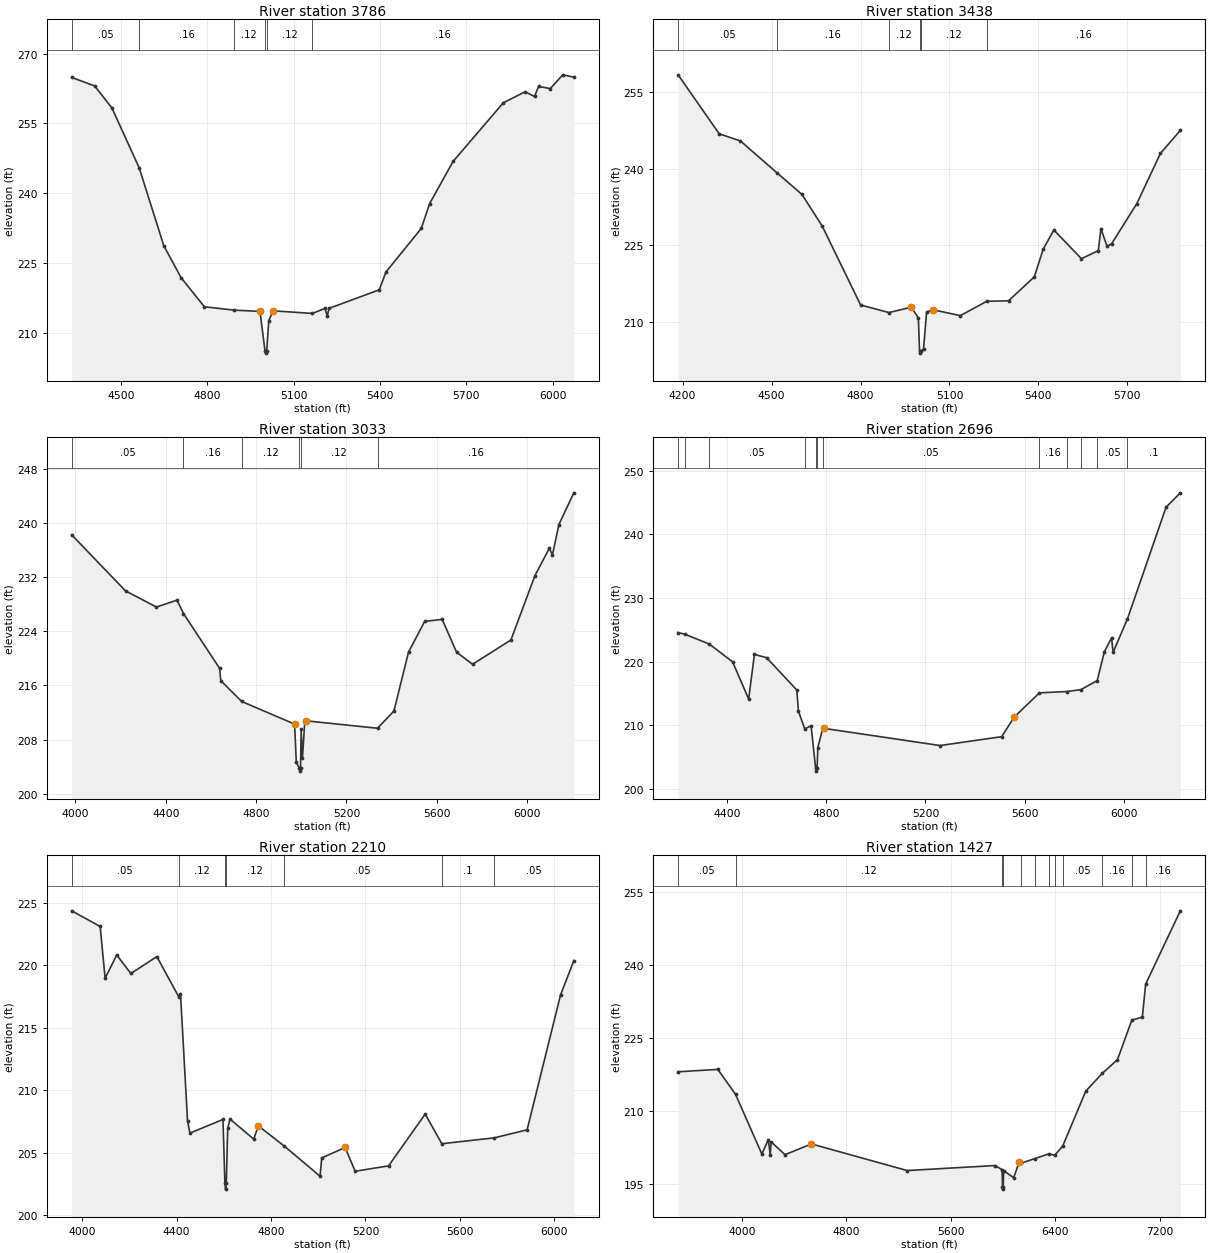
Type RM Length L Ch R = 1 ,3786    ,348,348,348
BEGIN DESCRIPTION:
UNT064 IN BECR 6.0
END DESCRIPTION:
XS GIS Cut Line= 4
      3778359.41     10484385.72      3777942.77     10484411.76
      3777491.38     10484498.56      3776694.37     10484845.09
#Sta/Elev= 30
  4327.8   264.9  4407.8  263.08  4467.9  258.32  4562.7  245.45  4648.2   228.7
  4708.3  221.82  4789.2  215.57  4891.4  214.84  4982.7  214.57  5000.1  206.09
  5002.8  205.59  5006.1  206.09  5013.2   212.6  5028.4  214.69  5164.8  214.13
  5208.6   215.2  5216.9  213.58  5222.4  215.21  5397.4  219.21  5420.8  223.05
  5543.5  232.42  5572.4  237.73  5653.9  246.82  5828.7  259.44  5904.7  261.82
  5937.4   260.8  5951.3  262.97    5992   262.5  6035.6  265.46    6074  264.96
#Mann= 6 ,-1 , 0
  4327.8     .05       0  4562.7     .16       0  4891.4     .12       0
  5000.1     .07       0  5006.1     .12       0  5164.8     .16       0
Bank Sta=4982.7,5028.4
XS Rating Curve= 0 ,0
Exp/Cntr=0.3,0.1

Type RM Length L Ch R = 1 ,3438    ,405,405,405
BEGIN DESCRIPTION:
UNT064 IN BECR 5.0
END DESCRIPTION:
XS GIS Cut Line= 4
      3778475.21     10484180.78      3777980.45     10484076.62
      3777496.07     10484206.83      3776928.33     10484592.27
#Sta/Elev= 30
    4185  258.33  4323.6   246.8  4395.1  245.41  4519.6  239.11  4602.5  234.96
    4671  228.76  4800.4  213.34  4896.1  211.86  4971.1  212.91  4995.1  210.84
  4999.1  204.43  5001.9  203.93  5005.1  204.43  5012.5  204.72  5022.8  211.91
  5043.5  212.42  5136.7  211.26  5225.7  214.06  5299.4  214.16  5386.2  218.85
  5416.1  224.26    5452  228.01  5544.9  222.39  5601.8  223.96  5610.7  228.24
  5631.7  224.78  5646.7  225.31  5731.8  233.16  5811.4  242.97  5878.4  247.47
#Mann= 6 ,-1 , 0
    4185     .05       0  4519.6     .16       0  4896.1     .12       0
  4999.1     .07       0  5005.1     .12       0  5225.7     .16       0
Bank Sta=4971.1,5043.5
XS Rating Curve= 0 ,0
Exp/Cntr=0.3,0.1

Type RM Length L Ch R = 1 ,3033    ,337,337,337
BEGIN DESCRIPTION:
UNT064 IN BECR 4.0
END DESCRIPTION:
XS GIS Cut Line= 5
      3778542.92     10483915.15      3777897.11     10483613.08
      3777501.28     10483842.24      3777193.99     10484071.41
      3776741.34     10484565.68
#Sta/Elev= 30
  3983.2  238.31  4221.7  230.01  4358.7  227.62  4450.1  228.64  4478.4  226.66
  4638.2  218.55  4643.8  216.71  4735.9  213.64  4970.6  210.28  4978.1  204.61
  4990.7  203.82  4993.5  203.32  4996.7  203.82  4999.6  209.51  5005.4  205.27
  5015.4  210.57  5021.2  210.77  5337.7  209.67  5410.4  212.22    5475  220.95
  5546.4  225.49  5624.1  225.79  5687.6  220.95  5758.5  219.14  5928.5  222.74
  6034.8  232.27  6098.3  236.31  6112.5  235.37  6140.8  239.82  6207.1  244.53
#Mann= 6 ,-1 , 0
  3983.2     .05       0  4478.4     .16       0  4735.9     .12       0
  4990.7     .07       0  4996.7     .12       0  5337.7     .16       0
Bank Sta=4970.6,5021.2
XS Rating Curve= 0 ,0
Exp/Cntr=0.3,0.1

Type RM Length L Ch R = 1 ,2696    ,486,486,486
BEGIN DESCRIPTION:
UNT064 IN BECR 3.0
END DESCRIPTION:
XS GIS Cut Line= 5
      3778183.58     10483456.83       3777829.4     10483404.74
      3777313.78     10483748.49       3777074.2     10483883.91
      3776596.15     10484486.66
#Sta/Elev= 30
    4204  224.58  4230.4  224.33  4329.8  222.77  4423.4  219.98  4488.1  214.14
  4511.2  221.15  4560.5  220.63  4681.9  215.55  4688.5  212.22  4713.8  209.46
  4739.5  209.94  4757.6  203.32  4760.3  202.82  4763.6  203.32  4766.6  206.51
  4785.6  209.42  4790.1  209.54  5258.7  206.84    5507  208.23  5556.7  211.28
  5658.9  215.11  5770.2  215.32    5826  215.62  5891.7  217.04  5920.5  221.58
  5949.3  223.74  5955.7  221.48  6013.2  226.71  6168.8  244.26  6226.2  246.52
#Mann= 12 ,-1 , 0
    4204     .05       0  4230.4     .12       0  4329.8     .05       0
  4713.8     .12       0  4757.6     .03       0  4763.6     .12       0
  4785.6     .05       0  5658.9     .16       0  5770.2     .05       0
    5826     .08       0  5891.7     .05       0  6013.2      .1       0
Bank Sta=4790.1,5556.7
XS Rating Curve= 0 ,0
Exp/Cntr=0.3,0.1

Type RM Length L Ch R = 1 ,2210    ,783,783,783
BEGIN DESCRIPTION:
UNT064 IN BECR 2.0
END DESCRIPTION:
XS GIS Cut Line= 3
      3778230.43     10483300.58      3777199.61     10483260.19
      3776449.61     10484060.19
#Sta/Elev= 30
    3955  224.35  4075.9   223.1  4096.8  218.96    4146  220.82    4206  219.34
  4316.1  220.69  4409.1  217.47  4416.2  217.74  4446.2  207.55  4456.2  206.58
  4596.3  207.67  4604.4   202.6  4607.2   202.1  4610.4   202.6  4616.3  206.98
  4626.3   207.7  4726.4   206.1  4746.4  207.16  4856.2  205.54  5007.9  203.13
  5014.7  204.59  5113.9  205.43  5156.4  203.53    5298  203.96  5453.3   208.1
  5523.7  205.73    5746   206.2  5885.1  206.84  6026.8  217.62  6083.2  220.37
#Mann= 7 ,-1 , 0
    3955     .05       0  4409.1     .12       0  4604.4     .03       0
  4610.4     .12       0  4856.2     .05       0  5523.7      .1       0
    5746     .05       0
Bank Sta=4746.4,5113.9
XS Rating Curve= 0 ,0
Exp/Cntr=0.3,0.1

Type RM Length L Ch R = 1 ,1427    ,0,0,0
BEGIN DESCRIPTION:
UNT064 IN BECR 1.0
END DESCRIPTION:
XS GIS Cut Line= 4
      3778125.08     10483179.14      3777630.27     10482502.03
      3776744.85      10482606.2      3775876.81     10484533.26
#Sta/Elev= 30
    3512  218.05    3816  218.54  3951.9  213.39  4152.7  201.15  4202.9   204.1
  4216.7  200.98  4223.8  203.64  4330.3     201  4532.5  203.21    5265  197.74
  5937.5  198.77  5992.2  197.92  5994.7  194.42  5997.4  193.92  6000.7  194.42
  6003.3  197.71  6080.1  196.28  6124.4   199.6  6138.2  199.27    6244  200.21
  6349.8  201.18  6394.7  200.89  6455.6  202.78  6632.3  214.08  6758.3  217.72
  6874.7  220.54  6984.5  228.67  7065.3   229.3  7090.3  236.06  7355.7  251.14
#Mann= 12 ,-1 , 0
    3512     .05       0  3951.9     .12       0  5994.7     .07       0
  6000.7     .12       0  6138.2     .05       0    6244      .1       0
  6349.8     .05       0  6394.7     .12       0  6455.6     .05       0
  6758.3     .16       0  6984.5     .05       0  7090.3     .16       0
Bank Sta=4532.5,6124.4
XS Rating Curve= 0 ,0
Exp/Cntr=0.3,0.1

Chan Stop Cuts=-1
Use User Specified Reach Order=0
Composite Channel Slope=5