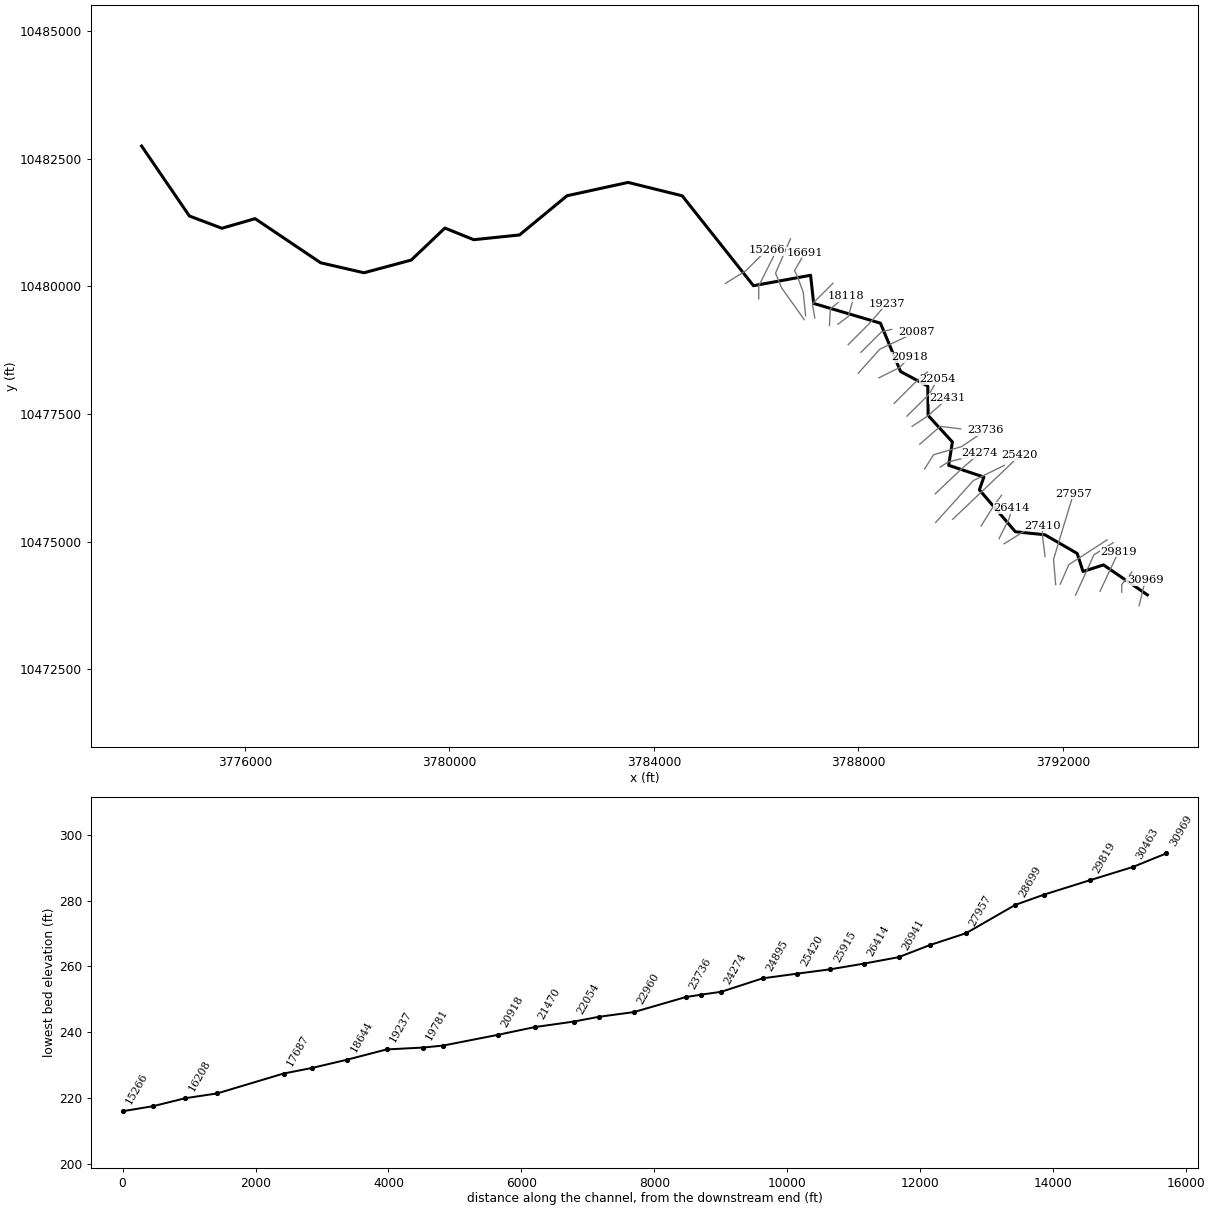
--- UNT065 IN BECR.prj (project) ---

Proj Title=UNT065 IN BECR Base Level Engineering
Current Plan=p01
Default Exp/Contr=0.3,0.1
English Units
Geom File=g01
Flow File=f01
Plan File=p01
Y Axis Title=Elevation
X Axis Title(PF)=Main Channel Distance
X Axis Title(XS)=Station
BEGIN DESCRIPTION:
UNT065 IN BECR
END DESCRIPTION:
DSS Export Rating Curves= 0
DSS Export Rating Curve Sorted= 0
DSS Export Volume Flow Curves= 0
DXF OffsetX= 0
DXF OffsetY= 0
DXF ScaleX= 1
DXF ScaleY= 10

--- UNT065 IN BECR.p01 (plan) ---

Plan Title=Multiple Run
Short Identifier=Multiple
Geom File=g01
Flow File=f01
Subcritical Flow
K Sum by GR= 0
Std Step Tol= 0.01
Critical Tol= 0.01
Num of Std Step Trials= 20
Max Error Tol= 0.3
Flow Tol Ratio= 0.001
Split Flow NTrial= 30
Split Flow Tol= 0.02
Split Flow Ratio= 0.02
Log Output Level= 0
Friction Slope Method= 1
Unsteady Friction Slope Method= 2
Unsteady Bridges Friction Slope Method= 1
Parabolic Critical Depth
Global Vel Dist=  1 , 1 , 1
Global Log Level= 0
CheckData=True
Encroach Param= -1, 0, 0, 0
BEGIN DESCRIPTION:
Multiple Run
END DESCRIPTION:

--- UNT065 IN BECR.f01 (steady flow) ---

Flow Title=Multiple
Number of Profiles=7
Profile Names=10-year,25-year,50-year,1pct_min,100-year,1pct_plu,500-year
River Rch & RM= UNT065 IN BECR,Reach-1,30969
     526     702     845     748    1011    1368    1453
River Rch & RM= UNT065 IN BECR,Reach-1,27410
     845    1155    1414    1270    1718    2323    2545
River Rch & RM= UNT065 IN BECR,Reach-1,24274
     994    1370    1685    1520    2055    2779    3070
River Rch & RM= UNT065 IN BECR,Reach-1,15725
    1271    1760    2171    1962    2653    3588    3979
Boundary for River Rch & Prof#=UNT065 IN BECR,Reach-1,1
Up Type=0
Dn Type=3
Dn Slope=0.005
Boundary for River Rch & Prof#=UNT065 IN BECR,Reach-1,2
Up Type=0
Dn Type=3
Dn Slope=0.005
Boundary for River Rch & Prof#=UNT065 IN BECR,Reach-1,3
Up Type=0
Dn Type=3
Dn Slope=0.005
Boundary for River Rch & Prof#=UNT065 IN BECR,Reach-1,4
Up Type=0
Dn Type=3
Dn Slope=0.005
Boundary for River Rch & Prof#=UNT065 IN BECR,Reach-1,5
Up Type=0
Dn Type=3
Dn Slope=0.005
Boundary for River Rch & Prof#=UNT065 IN BECR,Reach-1,6
Up Type=0
Dn Type=3
Dn Slope=0.005
Boundary for River Rch & Prof#=UNT065 IN BECR,Reach-1,7
Up Type=0
Dn Type=3
Dn Slope=0.005

--- UNT065 IN BECR.g01 (geometry) ---

Geom Title=Existing Conditions
Program Version=4.10

River Reach=UNT065 IN BECR  ,Reach-1
Reach XY= 30
      3793649.61     10473960.19       3792792.5       10474546.
      3792392.25       10474418.      3792278.25       10474770.
       3791647.5       10475136.      3791068.75       10475196.
        3790365.       10476017.        3790453.       10476267.
      3789764.25       10476497.        3789838.       10476954.
      3789363.25       10477472.       3789356.5       10478049.
      3788823.75       10478334.      3788430.25       10479281.
      3787123.75       10479668.        3787064.       10480219.
      3785946.75       10480015.       3784552.5       10481776.
      3783494.25       10482038.      3782300.75       10481777.
      3781370.75       10481009.      3780475.75       10480916.
      3779911.25       10481144.      3779253.25       10480517.
      3778328.75       10480268.      3777481.25       10480464.
        3776199.       10481328.       3775549.5       10481140.
       3774914.5       10481380.        3773979.       10482751.

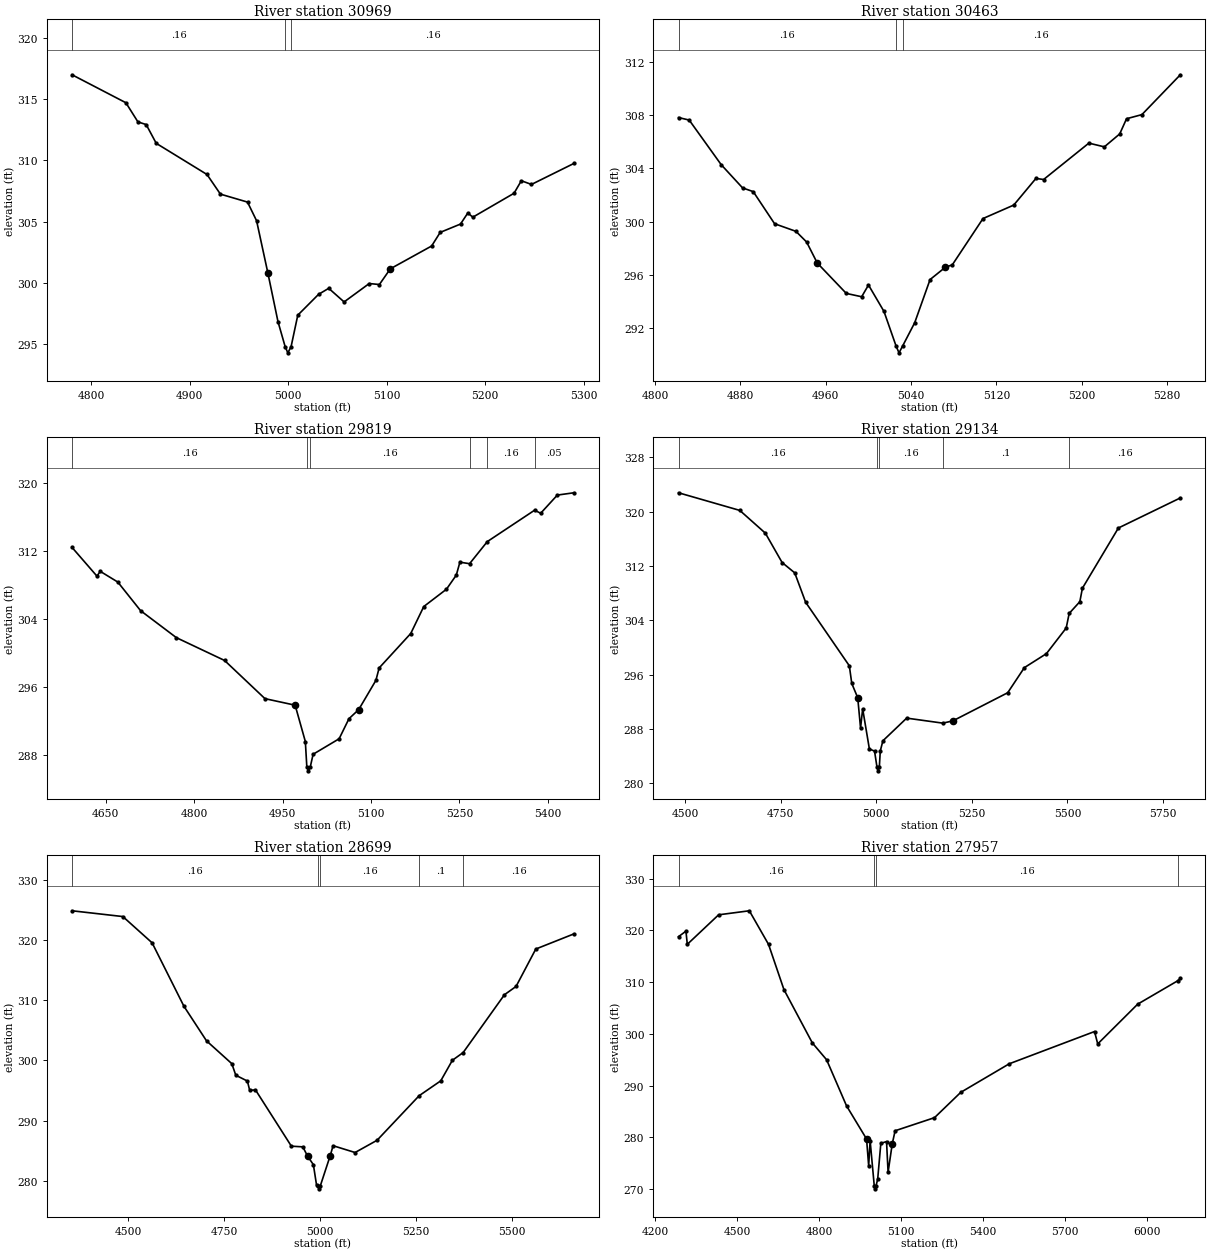
Type RM Length L Ch R = 1 ,30969   ,506,506,506
BEGIN DESCRIPTION:
UNT065 IN BECR 34.0
END DESCRIPTION:
XS GIS Cut Line= 2
      3793489.62     10473747.14      3793609.42     10474241.95
#Sta/Elev= 30
  4780.8  316.97  4835.4  314.69  4847.6  313.13    4856  312.91  4866.2  311.38
  4917.7  308.84  4931.3  307.24  4958.8  306.59    4968  305.07  4979.4  300.83
  4989.7  296.85    4997   294.8  4999.7   294.3    5003   294.8  5009.8  297.37
  5030.9  299.07  5041.2  299.56  5056.8  298.45  5082.3  299.95  5092.6  299.87
  5103.7  301.15  5145.6  303.01  5154.3  304.12  5174.9   304.8  5182.3   305.7
  5187.4  305.36  5229.2  307.31  5236.6  308.33  5246.9  308.03  5289.9  309.74
#Mann= 3 ,-1 , 0
  4780.8     .16       0    4997     .07       0    5003     .16       0
Bank Sta=4979.4,5103.7
XS Rating Curve= 0 ,0
Exp/Cntr=0.3,0.1

Type RM Length L Ch R = 1 ,30463   ,644,644,644
BEGIN DESCRIPTION:
UNT065 IN BECR 33.0
END DESCRIPTION:
XS GIS Cut Line= 3
      3793149.61     10474010.16      3793149.61     10474160.19
      3793349.62      10474410.2
#Sta/Elev= 30
  4822.1  307.82  4832.1  307.63  4862.1  304.28  4882.1  302.54  4892.1  302.26
  4912.1  299.85  4932.1  299.28  4942.1  298.48  4952.1   296.9  4979.3  294.62
  4993.7  294.37  5000.1  295.25  5014.6  293.27    5026  290.66  5028.7  290.16
    5032  290.66  5043.4  292.42  5057.8  295.66  5072.2  296.59  5078.6  296.76
  5107.4  300.24  5136.2  301.25    5157  303.25  5164.2  303.17  5206.6   305.9
  5221.1  305.62  5235.5  306.59  5241.9  307.73  5256.3  308.04  5292.3  311.03
#Mann= 3 ,-1 , 0
  4822.1     .16       0    5026     .07       0    5032     .16       0
Bank Sta=4952.1,5072.2
XS Rating Curve= 0 ,0
Exp/Cntr=0.3,0.1

Type RM Length L Ch R = 1 ,29819   ,685,685,685
BEGIN DESCRIPTION:
UNT065 IN BECR 32.0
END DESCRIPTION:
XS GIS Cut Line= 2
      3792725.28     10474029.95      3793086.38     10474800.76
#Sta/Elev= 30
  4592.9  312.42  4635.1  309.05  4640.7  309.61  4670.5  308.35  4709.1  304.99
  4769.9  301.81  4851.6  299.13  4920.1  294.64  4971.3  293.87  4988.6   289.6
  4991.1  286.65  4993.9  286.15  4997.1  286.65  5001.8   288.1  5045.9  289.92
  5062.6  292.28  5079.1  293.35  5108.3  296.79  5113.8  298.25  5167.4   302.3
  5189.5  305.47    5228  307.51  5244.7  309.17  5250.8  310.69  5267.2  310.51
  5297.3  313.11  5377.5   316.8  5387.8  316.44  5416.1  318.58  5444.1  318.85
#Mann= 6 ,-1 , 0
  4592.9     .16       0  4991.1     .07       0  4997.1     .16       0
  5267.2      .1       0  5297.3     .16       0  5377.5     .05       0
Bank Sta=4971.3,5079.1
XS Rating Curve= 0 ,0
Exp/Cntr=0.3,0.1

Type RM Length L Ch R = 1 ,29134   ,435,435,435
BEGIN DESCRIPTION:
UNT065 IN BECR 31.0
END DESCRIPTION:
XS GIS Cut Line= 3
      3792246.08     10473953.49      3792607.21     10474745.19
       3792982.2      10474981.3
#Sta/Elev= 30
  4482.3  322.79  4642.7  320.19  4709.5  316.84  4753.4  312.51  4786.4  310.99
    4815  306.65  4929.3  297.29  4935.7  294.69  4951.3  292.58  4958.7  288.11
  4964.2  290.95  4981.8  285.03  4995.3  284.72  5001.8  282.31  5004.6  281.81
  5007.8  282.31  5010.3  284.73  5017.2  286.24  5079.4  289.58  5173.9  288.84
  5200.1  289.17  5343.8  293.32  5387.4  297.02  5445.1  299.08  5496.9  302.86
  5504.7  305.01  5532.6  306.74  5539.3  308.72  5633.5   317.6  5795.6  322.03
#Mann= 5 ,-1 , 0
  4482.3     .16       0  5001.8     .07       0  5007.8     .16       0
  5173.9      .1       0  5504.7     .16       0
Bank Sta=4951.3,5200.1
XS Rating Curve= 0 ,0
Exp/Cntr=0.3,0.1

Type RM Length L Ch R = 1 ,28699   ,742,742,742
BEGIN DESCRIPTION:
UNT065 IN BECR 30.0
END DESCRIPTION:
XS GIS Cut Line= 3
      3791947.47     10474168.78      3792114.15     10474550.75
      3792862.89     10475036.04
#Sta/Elev= 30
  4353.3  324.85  4485.8  323.89  4562.1  319.53  4645.1     309    4704  303.26
    4770  299.47  4780.4  297.55  4810.7  296.58  4816.6  295.05  4831.8  295.11
  4925.4  285.77  4955.3  285.66  4967.6  284.12  4982.8   282.7  4991.1   279.3
  4994.9  279.19  4997.7  278.69  5000.9  279.19  5026.8  284.21  5034.2  285.85
  5091.6  284.72  5148.9  286.75  5258.7  294.15  5315.1  296.62  5345.4  300.03
  5373.6  301.32  5481.2  310.91  5511.5  312.29    5563   318.5  5662.3  321.01
#Mann= 5 ,-1 , 0
  4353.3     .16       0  4994.9     .07       0  5000.9     .16       0
  5258.7      .1       0  5373.6     .16       0
Bank Sta=4967.6,5026.8
XS Rating Curve= 0 ,0
Exp/Cntr=0.3,0.1

Type RM Length L Ch R = 1 ,27957   ,547,547,547
BEGIN DESCRIPTION:
UNT065 IN BECR 29.0
END DESCRIPTION:
XS GIS Cut Line= 3
       3791857.2     10474161.87      3791815.54     10474654.91
      3792204.43     10475939.64
#Sta/Elev= 30
  4284.4   318.8  4311.5  319.86  4316.5  317.32  4431.1  323.02  4543.6   323.8
  4613.9  317.31  4670.3  308.57  4774.3  298.27  4826.5  295.02  4899.6   286.1
  4972.8  279.71  4980.5  274.54  4985.8   279.4  5001.1  270.58  5003.9  270.08
  5007.1  270.58  5013.5  271.94    5025  278.86  5045.9  279.22  5051.6  273.29
  5066.8  278.77  5077.3   281.3  5221.5  283.83  5317.6  288.72  5495.2  294.24
  5807.4  300.47  5819.1  298.08  5965.4  305.76  6112.1  310.28  6121.5  310.72
#Mann= 4 ,-1 , 0
  4284.4     .16       0  5001.1     .07       0  5007.1     .16       0
  6112.1     .05       0
Bank Sta=4972.8,5066.8
XS Rating Curve= 0 ,0
Exp/Cntr=0.3,0.1

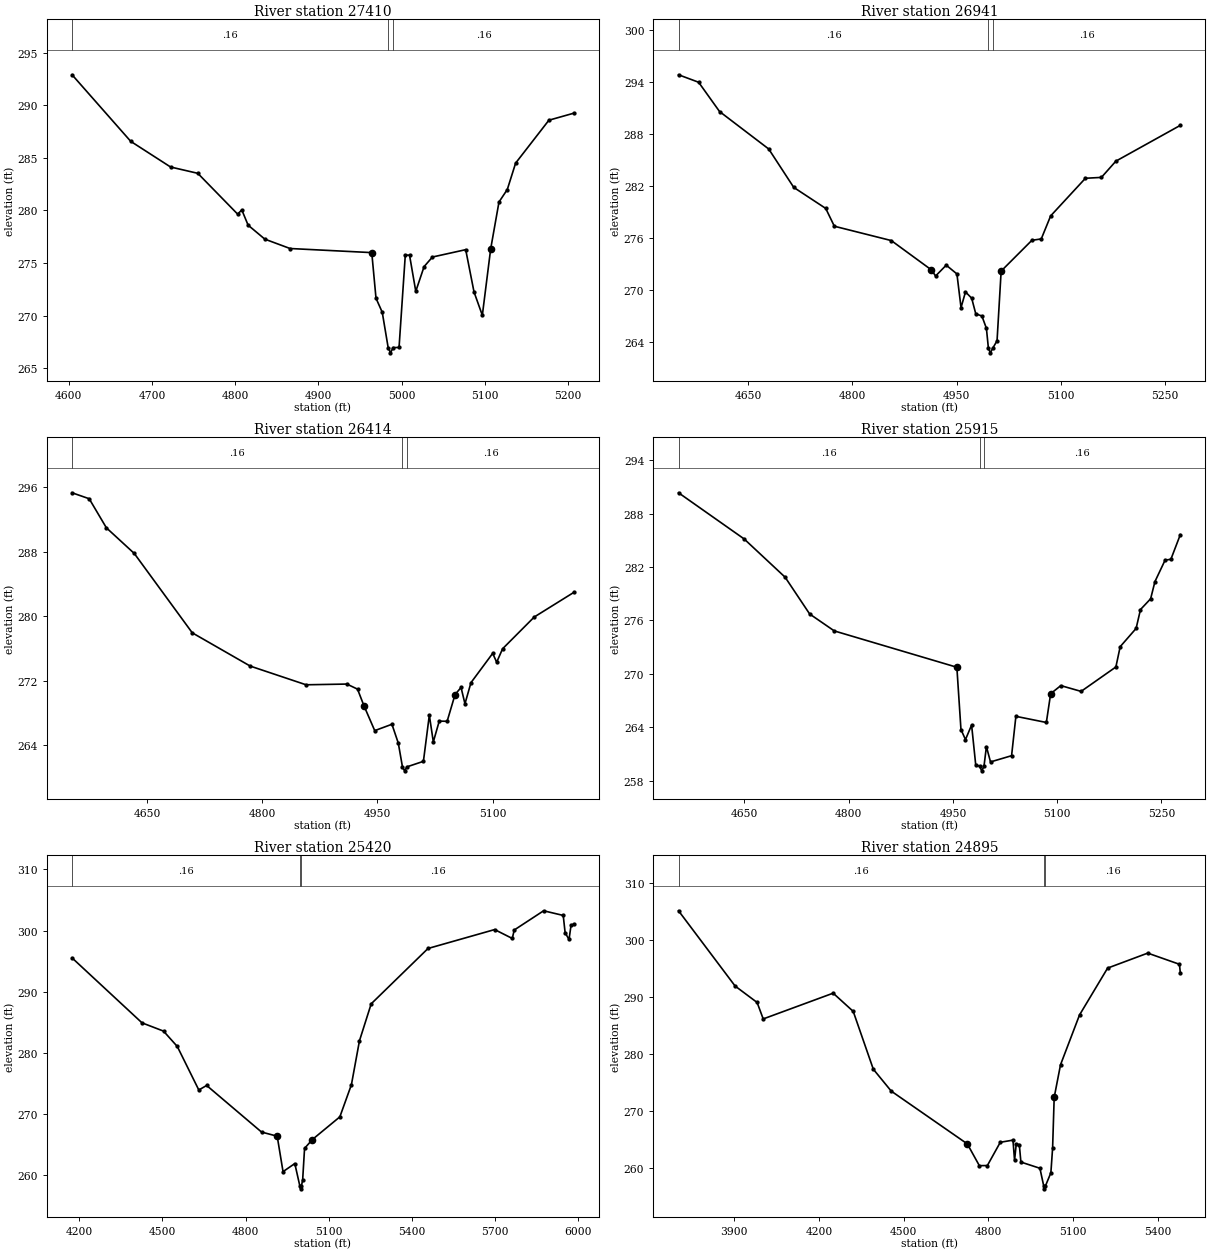
Type RM Length L Ch R = 1 ,27410   ,469,469,469
BEGIN DESCRIPTION:
UNT065 IN BECR 28.0
END DESCRIPTION:
XS GIS Cut Line= 3
       3791649.6     10474710.23      3791599.61     10475110.19
      3791599.61     10475310.22
#Sta/Elev= 30
  4603.9  292.89  4674.4  286.56  4722.3  284.12    4755  283.52  4802.9  279.64
  4807.9  280.04  4815.5  278.59  4835.6  277.26  4865.9  276.37  4964.1  275.98
  4969.2  271.64  4976.7  270.31  4983.8  266.95  4986.6  266.45  4989.8  266.95
  4996.9  266.96  5004.4  275.74  5009.5  275.74    5017   272.3    5027  274.65
    5037  275.56    5077  276.26    5087  272.24    5097  270.02    5107  276.32
    5117  280.79    5127  281.98    5137  284.49    5177  288.57    5207  289.24
#Mann= 3 ,-1 , 0
  4603.9     .16       0  4983.8     .07       0  4989.8     .16       0
Bank Sta=4964.1,5107
XS Rating Curve= 0 ,0
Exp/Cntr=0.3,0.1

Type RM Length L Ch R = 1 ,26941   ,527,527,527
BEGIN DESCRIPTION:
UNT065 IN BECR 27.0
END DESCRIPTION:
XS GIS Cut Line= 3
      3790849.61     10474960.19      3791249.61     10475210.19
      3791399.61     10475410.19
#Sta/Elev= 30
    4550  294.79  4578.9  293.93    4609  290.56  4679.7  286.25  4715.7  281.83
  4761.7  279.41  4774.1  277.36    4856  275.71  4913.8  272.33  4919.7  271.63
    4935  272.88  4950.4  271.87  4956.3  267.99  4962.7   269.8  4971.6  269.08
  4977.5  267.28  4986.3  267.03  4992.8  265.61  4995.7  263.29  4998.5  262.79
  5001.7  263.29  5008.1  264.18    5014   272.2  5058.2  275.74  5071.7   275.9
  5085.2  278.55  5135.2  282.88  5158.2  282.98    5179  284.85  5271.7  288.97
#Mann= 3 ,-1 , 0
    4550     .16       0  4995.7     .07       0  5001.7     .16       0
Bank Sta=4913.8,5014
XS Rating Curve= 0 ,0
Exp/Cntr=0.3,0.1

Type RM Length L Ch R = 1 ,26414   ,499,499,499
BEGIN DESCRIPTION:
UNT065 IN BECR 26.0
END DESCRIPTION:
XS GIS Cut Line= 3
      3790749.61      10475060.2      3790949.61     10475460.19
      3790999.62     10475660.23
#Sta/Elev= 30
  4552.3  295.33  4574.6  294.59    4597  290.98  4633.3   287.8  4708.8  277.95
  4784.3  273.82    4857   271.5  4910.1  271.59    4924  270.96  4932.4  268.89
  4946.4  265.81  4968.8   266.6  4977.1  264.26  4982.5  261.32  4985.3  260.82
  4988.5  261.32  5009.8     262  5017.5  267.73  5022.7  264.41  5030.4  266.99
  5040.7  266.97    5051  270.29  5058.8  271.17  5063.9  269.14  5071.7  271.76
    5100   275.4  5105.2   274.3  5112.9  275.97  5154.1  279.91  5205.7  282.97
#Mann= 3 ,-1 , 0
  4552.3     .16       0  4982.5     .07       0  4988.5     .16       0
Bank Sta=4932.4,5051
XS Rating Curve= 0 ,0
Exp/Cntr=0.3,0.1

Type RM Length L Ch R = 1 ,25915   ,495,495,495
BEGIN DESCRIPTION:
UNT065 IN BECR 25.0
END DESCRIPTION:
XS GIS Cut Line= 3
      3790399.63     10475310.22      3790649.61     10475710.19
      3790799.63     10475910.22
#Sta/Elev= 30
  4555.4  290.34  4649.7  285.16  4708.7  280.86    4744  276.73  4779.4  274.83
  4955.7  270.75  4961.6  263.76  4968.1  262.63  4976.9  264.26  4982.8  259.81
  4988.7  259.62  4991.4  259.12  4994.7  259.62  4998.2  261.84  5004.1  260.12
  5034.4  260.82  5040.6  265.24  5084.4  264.55  5090.6  267.78  5105.2  268.69
  5134.4  268.04  5184.4  270.78  5190.6  273.06  5213.5  275.11  5219.8  277.23
  5234.4  278.44  5240.6  280.37  5255.2  282.78  5263.5  282.87  5277.1  285.64
#Mann= 3 ,-1 , 0
  4555.4     .16       0  4988.7     .07       0  4994.7     .16       0
Bank Sta=4955.7,5090.6
XS Rating Curve= 0 ,0
Exp/Cntr=0.3,0.1

Type RM Length L Ch R = 1 ,25420   ,525,525,525
BEGIN DESCRIPTION:
UNT065 IN BECR 24.0
END DESCRIPTION:
XS GIS Cut Line= 2
      3789843.29     10475439.61      3791155.21     10476689.06
#Sta/Elev= 30
  4173.8  295.53  4426.3  284.92    4504  283.57  4553.7  281.06  4631.4  273.95
  4659.7  274.69  4857.8  267.08  4914.4   266.4  4935.5  260.61    4978  261.93
    4996   258.3  4998.8   257.8    5002   258.3  5006.3  259.24  5013.2  264.41
  5041.5  265.86  5140.6  269.56  5182.4  274.82  5211.4  281.99  5253.8  288.03
  5458.9  297.07  5699.5  300.16  5763.1  298.71  5770.3  300.09  5876.3  303.23
  5947.1  302.47    5954  299.63  5968.1  298.54  5975.4  300.89  5985.5  301.04
#Mann= 3 ,-1 , 0
  4173.8     .16       0    4996     .07       0    5002     .16       0
Bank Sta=4914.4,5041.5
XS Rating Curve= 0 ,0
Exp/Cntr=0.3,0.1

Type RM Length L Ch R = 1 ,24895   ,621,621,621
BEGIN DESCRIPTION:
UNT065 IN BECR 23.0
END DESCRIPTION:
XS GIS Cut Line= 3
        3789510.     10475377.15      3790246.09     10476196.58
      3790850.23     10476495.18
#Sta/Elev= 30
  3703.5  305.17  3903.7  291.96  3981.5  289.08  4003.1  286.19  4250.6  290.71
  4321.6  287.51  4392.6  277.37  4456.1  273.52  4725.2  264.26  4767.8  260.44
  4796.2  260.46  4841.9  264.54  4886.8  264.92  4892.4  261.37  4898.2  264.17
  4909.2  264.13  4914.8  261.07  4982.1  259.98  4995.6  256.87  4998.3  256.37
  5001.6  256.87  5020.9  259.19    5027  263.52  5032.6  272.42    5055  278.14
  5122.3  286.89  5221.6  295.11  5363.6  297.74  5475.8  295.78  5478.9  294.26
#Mann= 3 ,-1 , 0
  3703.5     .16       0  4995.6     .07       0  5001.6     .16       0
Bank Sta=4725.2,5032.6
XS Rating Curve= 0 ,0
Exp/Cntr=0.3,0.1

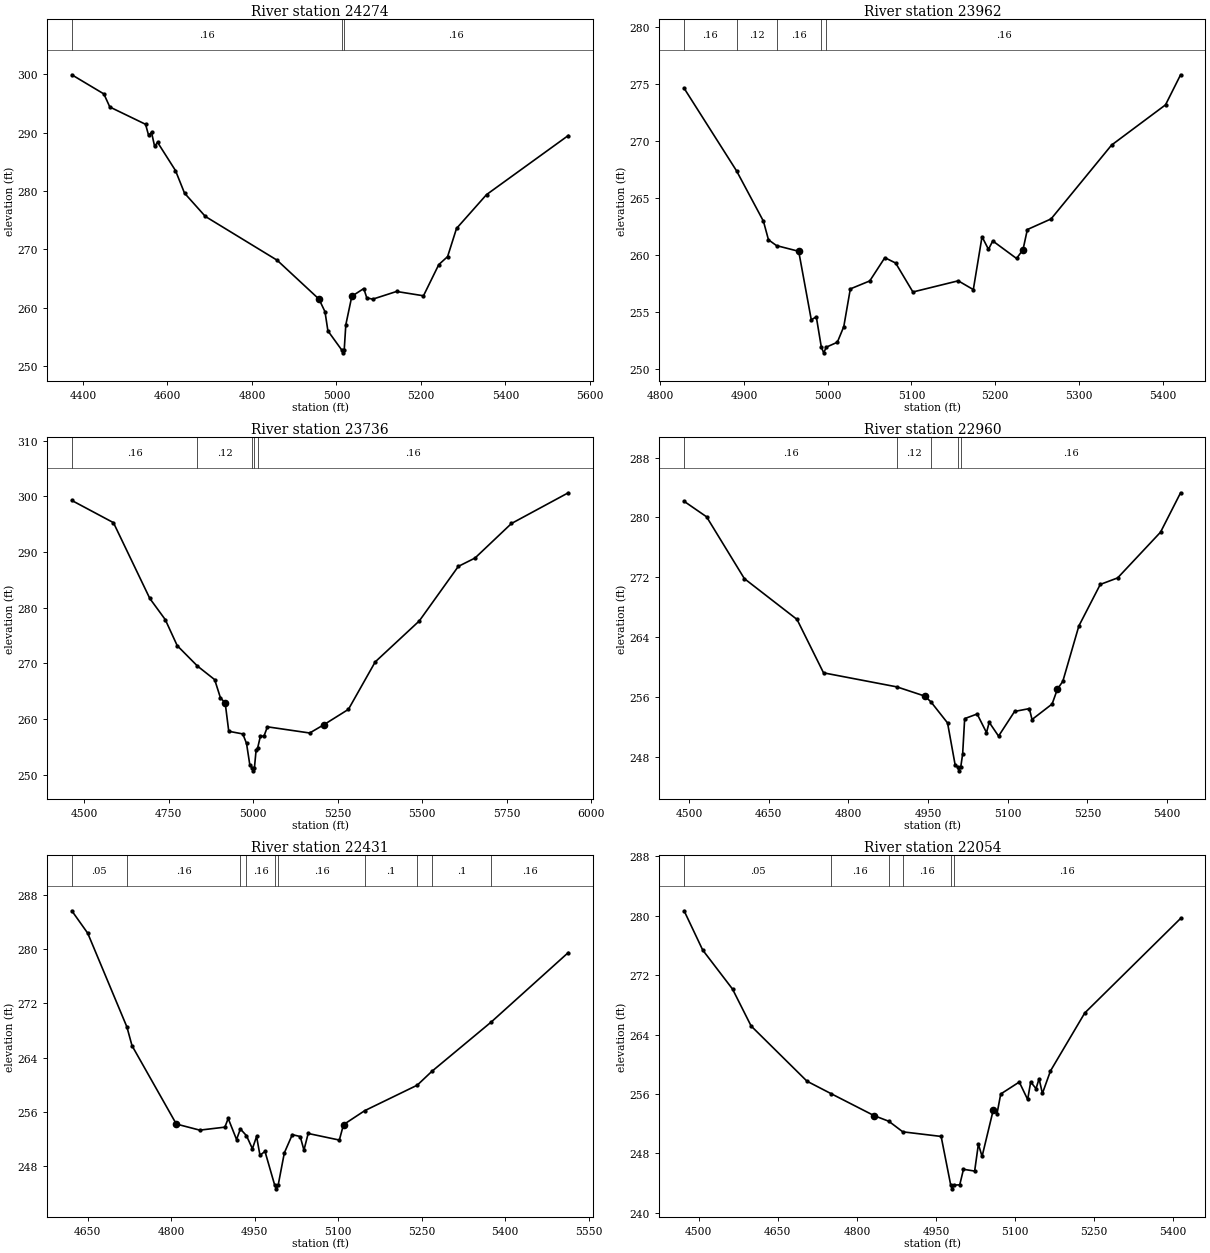
Type RM Length L Ch R = 1 ,24274   ,312,312,312
BEGIN DESCRIPTION:
UNT065 IN BECR 22.0
END DESCRIPTION:
XS GIS Cut Line= 3
      3789503.07     10475939.67      3790044.71     10476453.52
       3790371.1     10476731.31
#Sta/Elev= 30
  4373.7  299.91  4449.6  296.63  4463.7  294.39  4548.3  291.43  4555.5  289.53
  4562.4  290.06  4569.7  287.65  4576.6  288.35  4619.1  283.51  4640.5  279.64
  4689.8  275.65  4859.7  268.15  4958.8  261.49    4973  259.33  4979.9  256.05
  5012.5  252.79  5015.2  252.29  5018.5  252.79  5022.3   257.1  5036.5  261.98
  5064.8   263.3  5071.9  261.71  5085.9  261.48  5142.4   262.8  5206.1  262.06
  5242.3   267.4  5263.2  268.77  5284.3  273.59  5355.4  279.39  5548.9  289.51
#Mann= 3 ,-1 , 0
  4373.7     .16       0  5012.5     .07       0  5018.5     .16       0
Bank Sta=4958.8,5036.5
XS Rating Curve= 0 ,0
Exp/Cntr=0.3,0.1

Type RM Length L Ch R = 1 ,23962   ,226,226,226
BEGIN DESCRIPTION:
UNT065 IN BECR 21.0
END DESCRIPTION:
XS GIS Cut Line= 3
      3789599.57     10476460.16      3789749.61     10476560.19
      3790149.58     10476660.18
#Sta/Elev= 30
  4828.6  274.61  4891.2  267.36  4923.3  262.94  4929.3  261.31  4938.9   260.8
  4965.4   260.3  4980.4  254.29  4986.4  254.55  4992.4  251.89  4995.2  251.39
  4998.4  251.89  5011.5  252.32  5019.2  253.69    5027     257  5050.2   257.7
  5068.2  259.74  5081.1  259.27  5101.7  256.73  5155.8  257.71  5173.8  256.94
  5184.2  261.58  5191.9  260.47    5197  261.21  5225.4  259.67  5233.1  260.44
  5238.3  262.21  5266.6  263.14  5338.8  269.62  5403.2  273.15  5421.2  275.79
#Mann= 5 ,-1 , 0
  4828.6     .16       0  4891.2     .12       0  4938.9     .16       0
  4992.4     .07       0  4998.4     .16       0
Bank Sta=4965.4,5233.1
XS Rating Curve= 0 ,0
Exp/Cntr=0.3,0.1

Type RM Length L Ch R = 1 ,23736   ,776,776,776
BEGIN DESCRIPTION:
UNT065 IN BECR 20.0
END DESCRIPTION:
XS GIS Cut Line= 4
      3789294.68     10476425.71      3789468.32     10476703.52
      3790016.93     10476863.25      3790489.13     10477182.68
#Sta/Elev= 30
  4463.3  299.26  4586.5  295.27  4694.1  281.65  4739.8  277.85  4775.2  273.17
  4835.1   269.5    4886  267.06  4902.9  263.83  4917.2  262.84  4927.7  257.78
  4969.3   257.3  4980.3  255.59  4990.1  251.72  4997.6  251.17  5000.3  250.67
  5003.6  251.17  5008.6  254.37  5013.5  254.85  5021.4  256.91  5031.8  256.89
  5042.1  258.58  5167.2  257.47  5208.9  258.95  5281.8  261.72  5361.1  270.25
  5491.5  277.61    5607  287.41  5656.3  288.91  5764.2  295.12  5932.4  300.64
#Mann= 5 ,-1 , 0
  4463.3     .16       0  4835.1     .12       0  4997.6     .07       0
  5003.6     .12       0  5013.5     .16       0
Bank Sta=4917.2,5208.9
XS Rating Curve= 0 ,0
Exp/Cntr=0.3,0.1

Type RM Length L Ch R = 1 ,22960   ,529,529,529
BEGIN DESCRIPTION:
UNT065 IN BECR 19.0
END DESCRIPTION:
XS GIS Cut Line= 3
      3789199.58     10476910.16      3789599.61     10477260.19
      3789999.65     10477210.18
#Sta/Elev= 30
  4490.6  282.16  4532.9  280.09  4604.1  271.82  4703.2  266.37  4753.1  259.23
  4891.4  257.35  4943.8  256.12  4955.3  255.35  4986.6  252.53  5000.8  246.95
  5005.4  246.63  5008.1  246.13  5011.4  246.63    5015  248.38  5018.8  253.11
  5042.3  253.73  5059.9  251.24    5065  252.62  5082.6  250.77  5112.8  254.07
  5140.6  254.45  5145.6  252.99  5183.4  255.06  5193.5  257.07  5203.5  258.08
  5233.8   265.5  5274.1  271.05  5306.8  271.92  5387.5  278.03  5425.3   283.3
#Mann= 5 ,-1 , 0
  4490.6     .16       0  4891.4     .12       0  4955.3     .16       0
  5005.4     .07       0  5011.4     .16       0
Bank Sta=4943.8,5193.5
XS Rating Curve= 0 ,0
Exp/Cntr=0.3,0.1

Type RM Length L Ch R = 1 ,22431   ,377,377,377
BEGIN DESCRIPTION:
UNT065 IN BECR 18.0
END DESCRIPTION:
XS GIS Cut Line= 3
      3789049.58     10477260.17      3789349.61     10477460.19
      3789749.61     10477810.19
#Sta/Elev= 30
  4621.3  285.62  4649.9  282.32  4720.3  268.52  4729.5  265.76  4809.1  254.23
  4851.2  253.33  4896.3  253.77  4902.3  255.05  4917.3  251.95  4924.2   253.5
  4935.1  252.52  4945.8  250.59  4953.3   252.4  4959.4  249.63  4968.4   250.2
    4986  245.19  4988.8  244.69    4992  245.19  5003.2  249.99  5017.5  252.67
  5031.7  252.39  5038.4  250.39    5046  252.84    5102  251.87  5109.5  254.14
  5147.7   256.2    5242  259.95  5268.2  261.98  5375.1  269.26  5513.4  279.47
#Mann= 10 ,-1 , 0
  4621.3     .05       0  4720.3     .16       0  4924.2     .12       0
  4935.1     .16       0    4986     .07       0    4992     .16       0
  5147.7      .1       0    5242     .16       0  5268.2      .1       0
  5375.1     .16       0
Bank Sta=4809.1,5109.5
XS Rating Curve= 0 ,0
Exp/Cntr=0.3,0.1

Type RM Length L Ch R = 1 ,22054   ,584,584,584
BEGIN DESCRIPTION:
UNT065 IN BECR 17.0
END DESCRIPTION:
XS GIS Cut Line= 3
      3788949.63     10477460.21      3789385.36     10477892.25
       3789546.8     10478178.68
#Sta/Elev= 30
    4472  280.65  4507.3  275.37  4563.9  270.12  4599.2  265.15  4705.3  257.72
  4750.6  256.06  4832.6  253.09  4860.6  252.33  4887.1  250.91  4959.9  250.29
  4978.1  243.74  4980.8  243.24  4984.1  243.74  4995.2  243.78  5002.3  245.87
  5023.5  245.63  5030.6  249.25  5037.6   247.6  5058.9  253.87  5065.9  253.33
    5073     256  5108.2  257.61  5124.1  255.26  5129.9  257.62    5140  256.72
  5145.8  258.05  5152.1  256.07  5167.4   259.1  5232.5   266.9  5414.4  279.62
#Mann= 6 ,-1 , 0
    4472     .05       0  4750.6     .16       0  4860.6     .12       0
  4887.1     .16       0  4978.1     .07       0  4984.1     .16       0
Bank Sta=4832.6,5058.9
XS Rating Curve= 0 ,0
Exp/Cntr=0.3,0.1

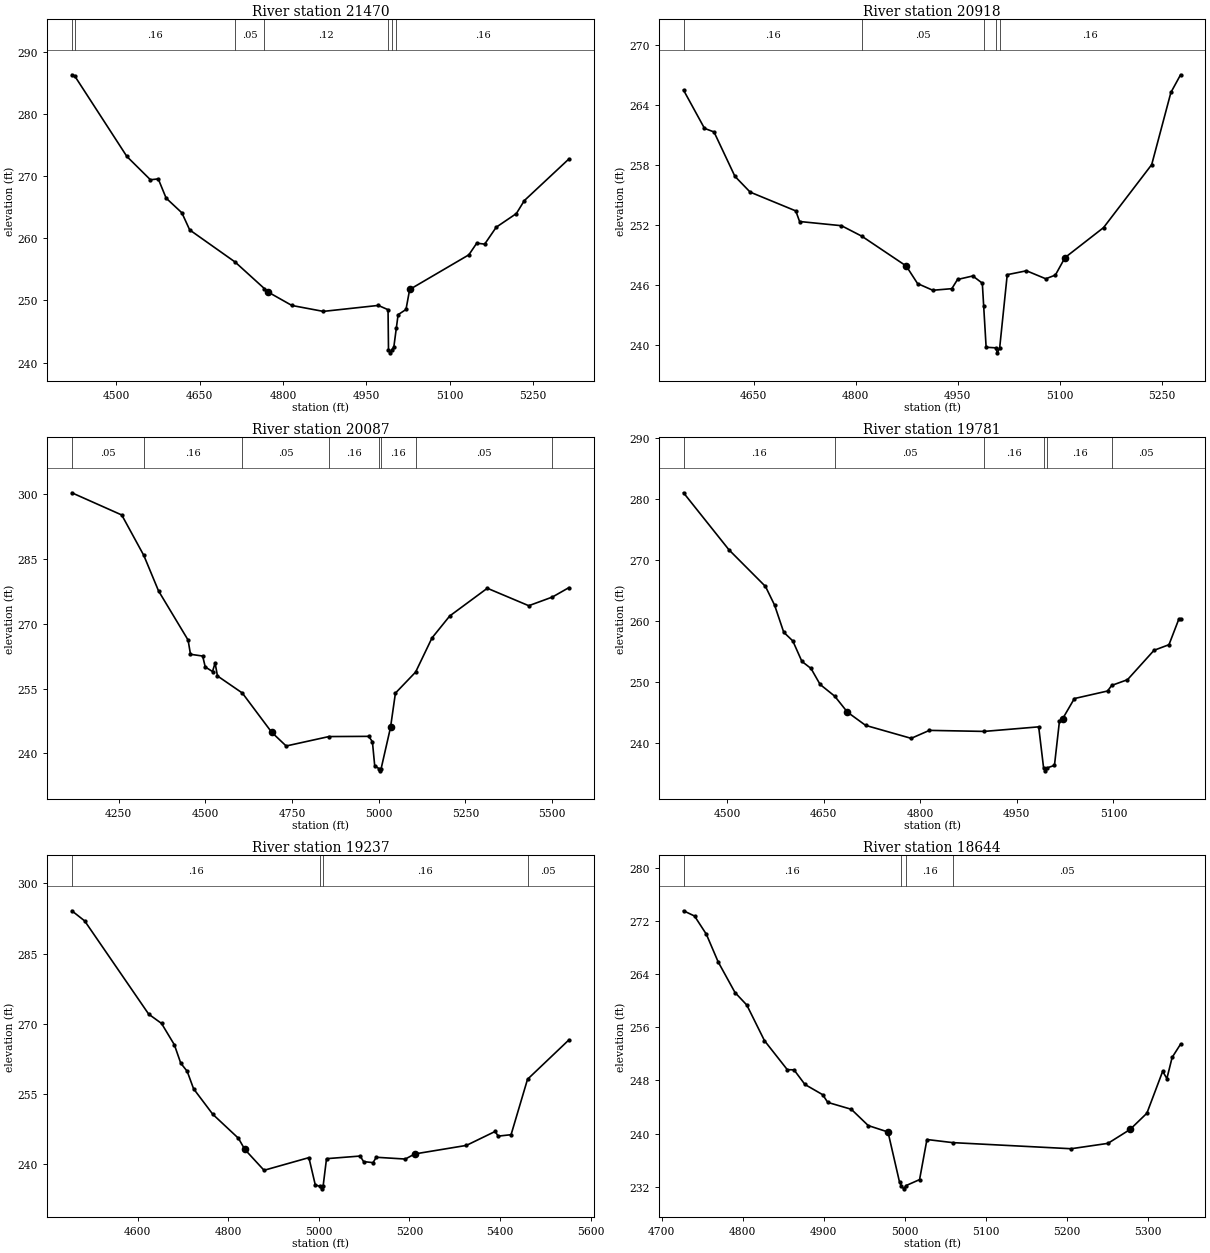
Type RM Length L Ch R = 1 ,21470   ,552,552,552
BEGIN DESCRIPTION:
UNT065 IN BECR 16.0
END DESCRIPTION:
XS GIS Cut Line= 3
      3788699.62      10477710.2      3789099.61     10478110.19
      3789348.87     10478324.51
#Sta/Elev= 30
  4419.8  286.26  4424.9  286.08  4518.8  273.14  4561.2  269.39  4575.3  269.53
  4589.5  266.44  4617.8  264.08  4631.9  261.33  4713.5  256.18  4766.2  251.91
  4773.3  251.33  4815.8  249.19  4872.3  248.24  4971.3   249.2  4988.8  248.51
  4989.6  242.08  4992.4  241.58  4995.6  242.08  4999.2  242.51  5003.7  245.55
  5006.9  247.71  5021.1  248.55  5027.7  251.76  5134.2  257.33  5148.4   259.2
  5162.7  259.05  5183.5  261.77  5219.7  263.96    5234  266.04  5314.2  272.73
#Mann= 7 ,-1 , 0
  4419.8     .05       0  4424.9     .16       0  4713.5     .05       0
  4766.2     .12       0  4989.6     .07       0  4995.6     .12       0
  5003.7     .16       0
Bank Sta=4773.3,5027.7
XS Rating Curve= 0 ,0
Exp/Cntr=0.3,0.1

Type RM Length L Ch R = 1 ,20918   ,831,831,831
BEGIN DESCRIPTION:
UNT065 IN BECR 15.0
END DESCRIPTION:
XS GIS Cut Line= 3
      3788399.58     10478210.17      3788799.61     10478410.19
      3788999.62     10478610.19
#Sta/Elev= 30
    4547  265.53  4577.8   261.7  4591.8  261.34  4622.5   256.9  4644.9  255.32
  4711.9  253.44  4717.5  252.38    4779  251.96  4808.9  250.91  4874.1  247.93
  4890.8  246.17  4913.2   245.5  4941.1  245.66  4949.5  246.58  4971.9  246.93
  4985.9  246.21  4987.9  243.92  4991.5   239.8  5005.4  239.74  5008.1  239.24
  5011.4  239.74  5022.5  247.06  5050.8  247.45  5079.1  246.65  5093.2  247.02
  5107.4  248.77    5164  251.77  5234.7  258.07  5262.9  265.29  5277.1  267.06
#Mann= 5 ,-1 , 0
    4547     .16       0  4808.9     .05       0  4987.9     .16       0
  5005.4     .07       0  5011.4     .16       0
Bank Sta=4874.1,5107.4
XS Rating Curve= 0 ,0
Exp/Cntr=0.3,0.1

Type RM Length L Ch R = 1 ,20087   ,306,306,306
BEGIN DESCRIPTION:
UNT065 IN BECR 14.0
END DESCRIPTION:
XS GIS Cut Line= 3
      3787996.11     10478300.77      3788419.71     10478772.97
      3789141.91     10479113.24
#Sta/Elev= 30
  4115.3  300.29  4259.2  295.15  4322.8  285.79  4365.3  277.57  4450.4  266.21
  4457.3  262.92  4492.4  262.51  4499.9  259.98  4520.8  258.93  4528.3   260.9
    4535  257.91  4606.7  253.96  4691.3  244.88  4733.1   241.7  4856.3  243.88
  4971.1  243.93  4981.7  242.68  4988.3  237.14  5000.8  236.45  5003.5  235.95
  5006.8  236.45  5033.9     246    5048  253.93  5106.2   258.8  5153.4   266.7
  5204.5  271.78  5312.9   278.2  5432.3  274.16  5500.3  276.16    5548  278.34
#Mann= 8 ,-1 , 0
  4115.3     .05       0  4322.8     .16       0  4606.7     .05       0
  4856.3     .16       0  5000.8     .07       0  5006.8     .16       0
  5106.2     .05       0  5500.3     .16       0
Bank Sta=4691.3,5033.9
XS Rating Curve= 0 ,0
Exp/Cntr=0.3,0.1

Type RM Length L Ch R = 1 ,19781   ,544,544,544
BEGIN DESCRIPTION:
UNT065 IN BECR 13.0
END DESCRIPTION:
XS GIS Cut Line= 3
      3788049.62      10478710.2      3788449.61     10479110.19
      3788649.58     10479160.18
#Sta/Elev= 30
  4432.5  281.05  4503.2  271.66  4559.8  265.65  4573.9  262.59  4588.1  258.13
  4602.2   256.7  4616.3  253.34  4630.5  252.17  4644.6  249.55  4667.3  247.62
    4687     245  4715.3  242.82    4786  240.69  4814.3     242  4899.3  241.83
    4984  242.58  4991.6  235.85  4994.4  235.35  4997.6  235.85  5008.5  236.25
  5016.2  243.48  5021.4  243.95  5039.4  247.23  5090.9  248.47  5097.4  249.39
  5121.9  250.33  5163.1  255.16  5186.3  256.08  5201.8  260.34  5204.3  260.34
#Mann= 6 ,-1 , 0
  4432.5     .16       0  4667.3     .05       0  4899.3     .16       0
  4991.6     .07       0  4997.6     .16       0  5097.4     .05       0
Bank Sta=4687,5021.4
XS Rating Curve= 0 ,0
Exp/Cntr=0.3,0.1

Type RM Length L Ch R = 1 ,19237   ,593,593,593
BEGIN DESCRIPTION:
UNT065 IN BECR 12.0
END DESCRIPTION:
XS GIS Cut Line= 3
      3787799.59     10478860.17      3788199.61     10479260.19
      3788549.59     10479660.17
#Sta/Elev= 30
    4455  294.14  4483.3  291.98  4624.7  272.07    4653  270.09  4681.3  265.54
  4695.4  261.61  4709.6  259.88  4723.7  256.15  4766.2  250.69  4822.7  245.58
  4836.9  243.19  4879.3  238.74  4978.3  241.44  4992.4  235.62  5003.6  235.28
  5006.3  234.78  5009.6  235.28  5017.2  241.22  5091.4  241.78    5099   240.6
  5119.9  240.37    5127  241.52  5191.1  241.14    5212  242.23  5325.9  244.05
  5389.4  247.03  5396.1  246.03  5424.6  246.34  5460.9  258.17  5552.2  266.57
#Mann= 4 ,-1 , 0
    4455     .16       0  5003.6     .07       0  5009.6     .16       0
  5460.9     .05       0
Bank Sta=4836.9,5212
XS Rating Curve= 0 ,0
Exp/Cntr=0.3,0.1

Type RM Length L Ch R = 1 ,18644   ,526,526,526
BEGIN DESCRIPTION:
UNT065 IN BECR 11.0
END DESCRIPTION:
XS GIS Cut Line= 3
      3787599.57     10479260.16      3787799.61     10479410.19
       3787899.6     10479760.14
#Sta/Elev= 30
  4726.8  273.55  4740.4  272.76    4755  270.02  4769.6  265.85  4790.4  261.24
    4805  259.35  4826.8  253.99    4855  249.62  4863.3  249.59  4876.8  247.39
  4898.7  245.85    4905  244.69  4934.1  243.65    4955   241.2  4979.4  240.23
  4993.7  232.65  4995.9  232.17  4998.7  231.67  5001.9  232.17  5018.4  233.06
  5027.5   239.1  5059.4  238.63  5205.6  237.71  5251.1  238.52  5278.4  240.61
  5299.2  243.06  5318.7  249.37  5323.9  248.28  5330.4  251.47  5340.8  253.46
#Mann= 4 ,-1 , 0
  4726.8     .16       0  4995.9     .07       0  5001.9     .16       0
  5059.4     .05       0
Bank Sta=4979.4,5278.4
XS Rating Curve= 0 ,0
Exp/Cntr=0.3,0.1

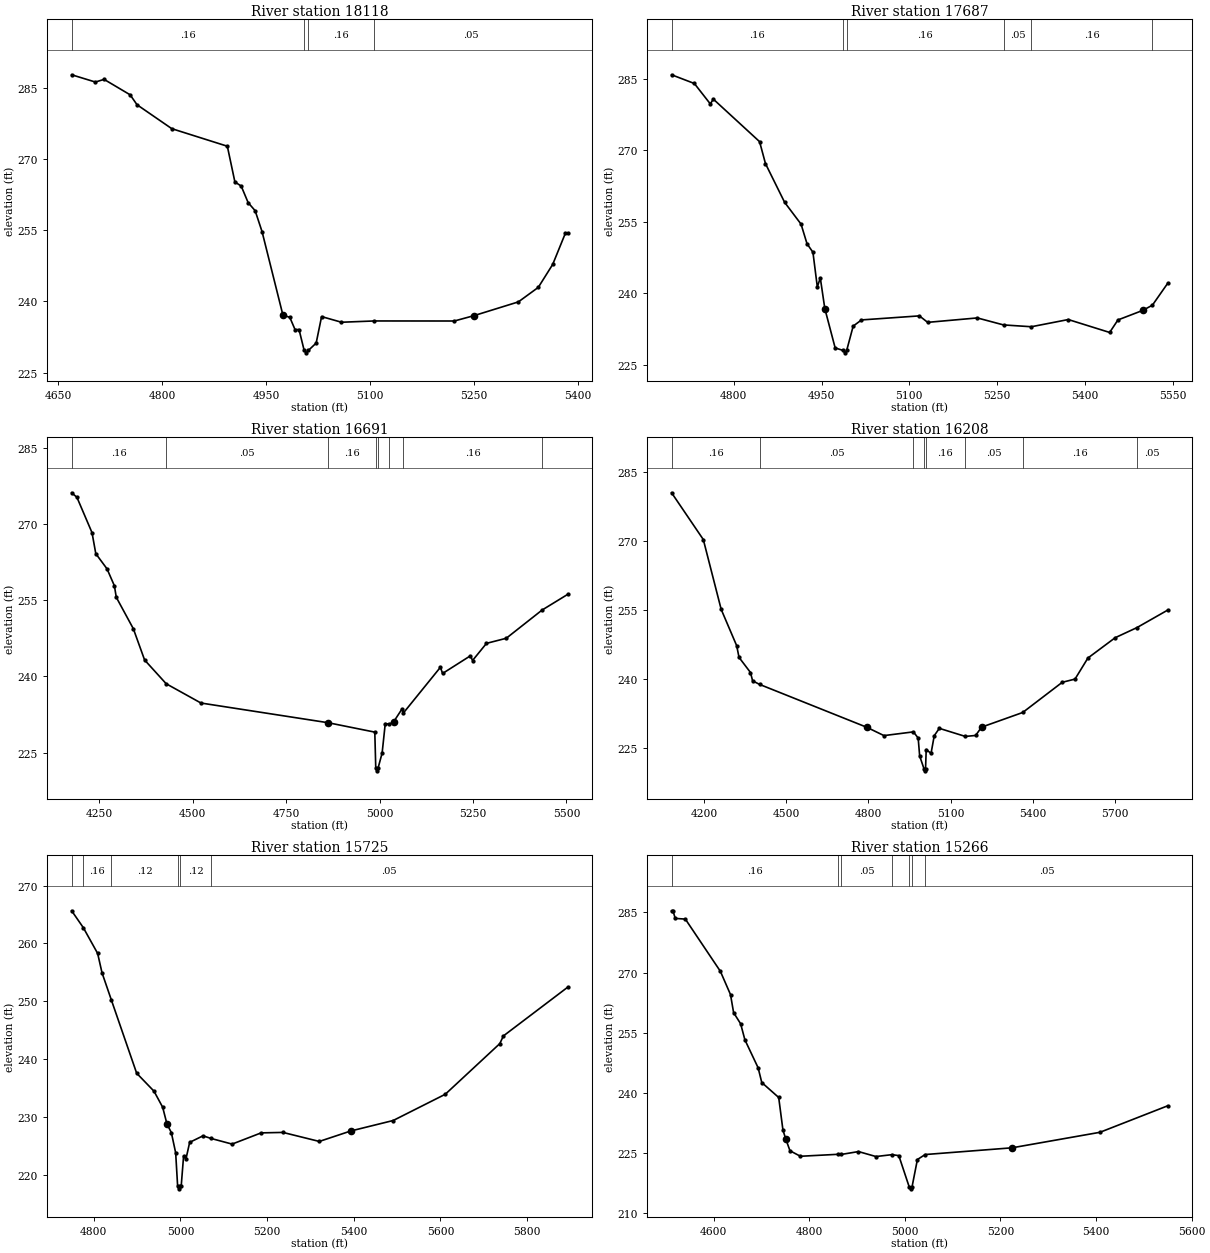
Type RM Length L Ch R = 1 ,18118   ,431,431,431
BEGIN DESCRIPTION:
UNT065 IN BECR 10.0
END DESCRIPTION:
XS GIS Cut Line= 3
      3787432.23     10479236.01      3787449.61     10479560.19
      3787749.64     10479810.21
#Sta/Elev= 30
  4669.4  287.78  4703.6  286.25  4716.2  286.81  4753.7  283.56  4763.7  281.46
  4813.8  276.42  4893.9  272.72  4904.8  265.19  4913.9  264.32  4923.9  260.83
    4934  259.13    4944   254.7    4974  237.15    4984  236.64  4991.5  234.08
  4997.3  234.08  5004.7  229.67  5007.5  229.17  5010.7  229.67    5022  231.23
  5029.8  236.81  5058.5  235.62  5105.7  235.89  5221.2  235.88  5249.8  237.02
  5313.6  239.91  5342.3  242.97  5363.1  247.81  5381.3  254.36  5384.6  254.36
#Mann= 4 ,-1 , 0
  4669.4     .16       0  5004.7     .07       0  5010.7     .16       0
  5105.7     .05       0
Bank Sta=4974,5249.8
XS Rating Curve= 0 ,0
Exp/Cntr=0.3,0.1

Type RM Length L Ch R = 1 ,17687   ,996,996,996
BEGIN DESCRIPTION:
UNT065 IN BECR 9.0
END DESCRIPTION:
XS GIS Cut Line= 3
      3787145.77     10479381.83      3787099.61     10479660.19
      3787499.58     10480060.16
#Sta/Elev= 30
  4693.6  285.84  4732.5  284.01  4759.8  279.72  4764.9  280.73    4844   271.8
  4854.1  267.18  4886.8  259.06  4914.9  254.48  4925.1  250.36  4935.2  248.58
  4942.7  241.29  4947.8  243.19  4955.5  236.76  4973.2  228.49  4986.9  227.96
  4989.6  227.46  4992.9  227.96    5004  233.07  5018.2  234.37  5117.2  235.22
  5131.3  233.86  5216.2  234.79    5261  233.32  5308.6  232.94  5371.7  234.45
  5442.4  231.74  5456.6  234.37    5499  236.37  5515.5  237.47  5541.4  242.02
#Mann= 6 ,-1 , 0
  4693.6     .16       0  4986.9     .07       0  4992.9     .16       0
    5261     .05       0  5308.6     .16       0  5515.5     .05       0
Bank Sta=4955.5,5499
XS Rating Curve= 0 ,0
Exp/Cntr=0.3,0.1

Type RM Length L Ch R = 1 ,16691   ,483,483,483
BEGIN DESCRIPTION:
UNT065 IN BECR 8.0
END DESCRIPTION:
XS GIS Cut Line= 5
      3786966.49     10479425.94      3786919.98     10479889.19
      3786799.61     10480210.19      3786749.61     10480310.19
      3786954.44     10480661.88
#Sta/Elev= 30
    4176   276.1  4190.1  275.21  4230.5  268.26  4240.6  264.13  4270.7  261.14
  4290.4  257.81  4295.4  255.56  4341.1  249.37  4371.2  243.23    4429  238.56
    4522  234.77  4862.2   230.9  4987.2  229.05  4989.8  221.94  4992.5  221.44
  4995.8  221.94  5006.8  224.93  5015.2  230.73  5025.8  230.61  5037.5  231.06
  5059.9  233.59  5063.8  232.82  5162.8   241.8  5168.6  240.58    5243  244.05
  5248.8  243.13  5286.1   246.5    5339   247.5  5434.9  253.05  5503.2  256.12
#Mann= 8 ,-1 , 0
    4176     .16       0    4429     .05       0  4862.2     .16       0
  4989.8     .07       0  4995.8     .16       0  5025.8     .12       0
  5063.8     .16       0  5434.9     .05       0
Bank Sta=4862.2,5037.5
XS Rating Curve= 0 ,0
Exp/Cntr=0.3,0.1

Type RM Length L Ch R = 1 ,16208   ,483,483,483
BEGIN DESCRIPTION:
UNT065 IN BECR 7.0
END DESCRIPTION:
XS GIS Cut Line= 4
      3786940.53     10479349.36      3786496.09     10479974.36
      3786378.04     10480259.08      3786669.71     10480932.71
#Sta/Elev= 30
  4082.3  280.49    4198  270.31  4263.2  255.11  4319.7  247.21  4328.3  244.66
  4370.1  241.37  4377.8  239.56  4403.7  238.77  4794.4  229.45    4857  227.64
  4964.4  228.45  4981.8   227.1  4987.2   223.2  5002.7  220.47  5005.4  219.97
  5008.7  220.47  5011.1  224.61  5028.7  223.76  5040.4  227.62  5058.9  229.22
  5153.7  227.46  5191.3  227.67  5213.1  229.48  5363.1  232.67  5507.3  239.24
  5553.9  239.94  5600.9  244.52  5700.3  248.94  5779.6  251.14  5891.5  254.94
#Mann= 8 ,-1 , 0
  4082.3     .16       0  4403.7     .05       0  4964.4     .16       0
  5002.7     .07       0  5008.7     .16       0  5153.7     .05       0
  5363.1     .16       0  5779.6     .05       0
Bank Sta=4794.4,5213.1
XS Rating Curve= 0 ,0
Exp/Cntr=0.3,0.1

Type RM Length L Ch R = 1 ,15725   ,459,459,459
BEGIN DESCRIPTION:
UNT065 IN BECR 6.0
END DESCRIPTION:
XS GIS Cut Line= 3
      3786049.61     10479760.23      3786049.61     10480010.19
      3786449.61      10480810.2
#Sta/Elev= 30
    4749  265.66  4775.9  262.74    4809  258.28    4819  254.95  4840.7  250.21
    4899  237.56    4939  234.45    4959  231.68    4969  228.75    4979   227.3
    4989  223.79  4993.5  218.06  4996.2  217.56  4999.5  218.06  5001.8  218.06
  5007.3  223.25  5012.9  222.78  5021.3   225.6  5052.1  226.73  5070.5  226.28
  5119.2   225.3  5186.2  227.24  5236.5  227.32  5320.4  225.76  5393.1  227.57
  5490.9  229.38  5611.1  233.92  5736.9  242.68  5745.2  244.01  5893.4  252.43
#Mann= 6 ,-1 , 0
    4749     .12       0  4775.9     .16       0  4840.7     .12       0
  4993.5     .07       0  4999.5     .12       0  5070.5     .05       0
Bank Sta=4969,5393.1
XS Rating Curve= 0 ,0
Exp/Cntr=0.3,0.1

Type RM Length L Ch R = 1 ,15266   ,470,470,470
BEGIN DESCRIPTION:
UNT065 IN BECR 5.0
END DESCRIPTION:
XS GIS Cut Line= 3
      3785399.64     10480060.21      3785799.61     10480310.19
      3786199.58     10480710.16
#Sta/Elev= 30
  4512.3  285.41  4515.2  285.41  4519.9  283.51  4541.1  283.33  4614.3  270.31
  4635.5   264.5    4642  259.99  4656.7  257.21  4665.6  253.21  4693.3  246.22
  4700.9  242.55  4736.3  238.82  4745.2  230.67  4751.1  228.45  4759.9  225.52
  4781.7  224.15  4859.3  224.63    4867   224.6  4903.2  225.32  4939.7  224.08
  4973.2  224.55  4987.5  224.31  5009.2  216.52    5012  216.02  5015.2  216.52
  5026.4  223.34  5042.7  224.58  5224.4  226.26  5408.2  230.13  5549.6  236.73
#Mann= 7 ,-1 , 0
  4512.3     .16       0  4859.3     .12       0    4867     .05       0
  4973.2     .16       0  5009.2     .07       0  5015.2     .16       0
  5042.7     .05       0
Bank Sta=4751.1,5224.4
XS Rating Curve= 0 ,0
Exp/Cntr=0.3,0.1