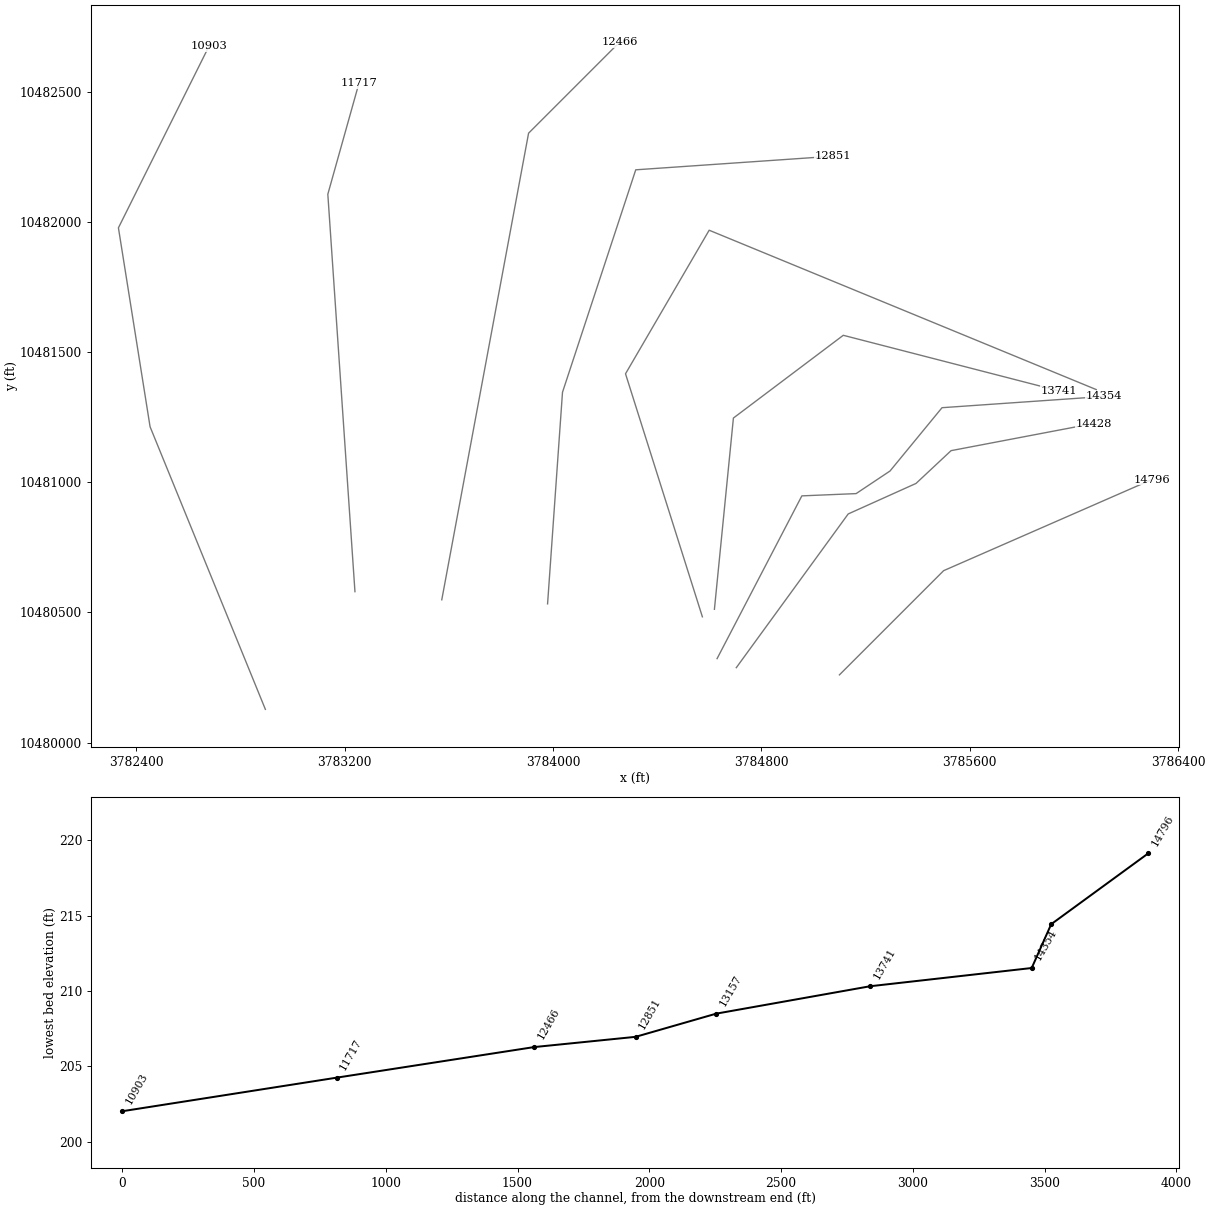
HEC-RAS study UNT065 IN BECR.prj: UNT065 IN BECR Base Level Engineering

--- UNT065 IN BECR.g01 (geometry) --- (continued)

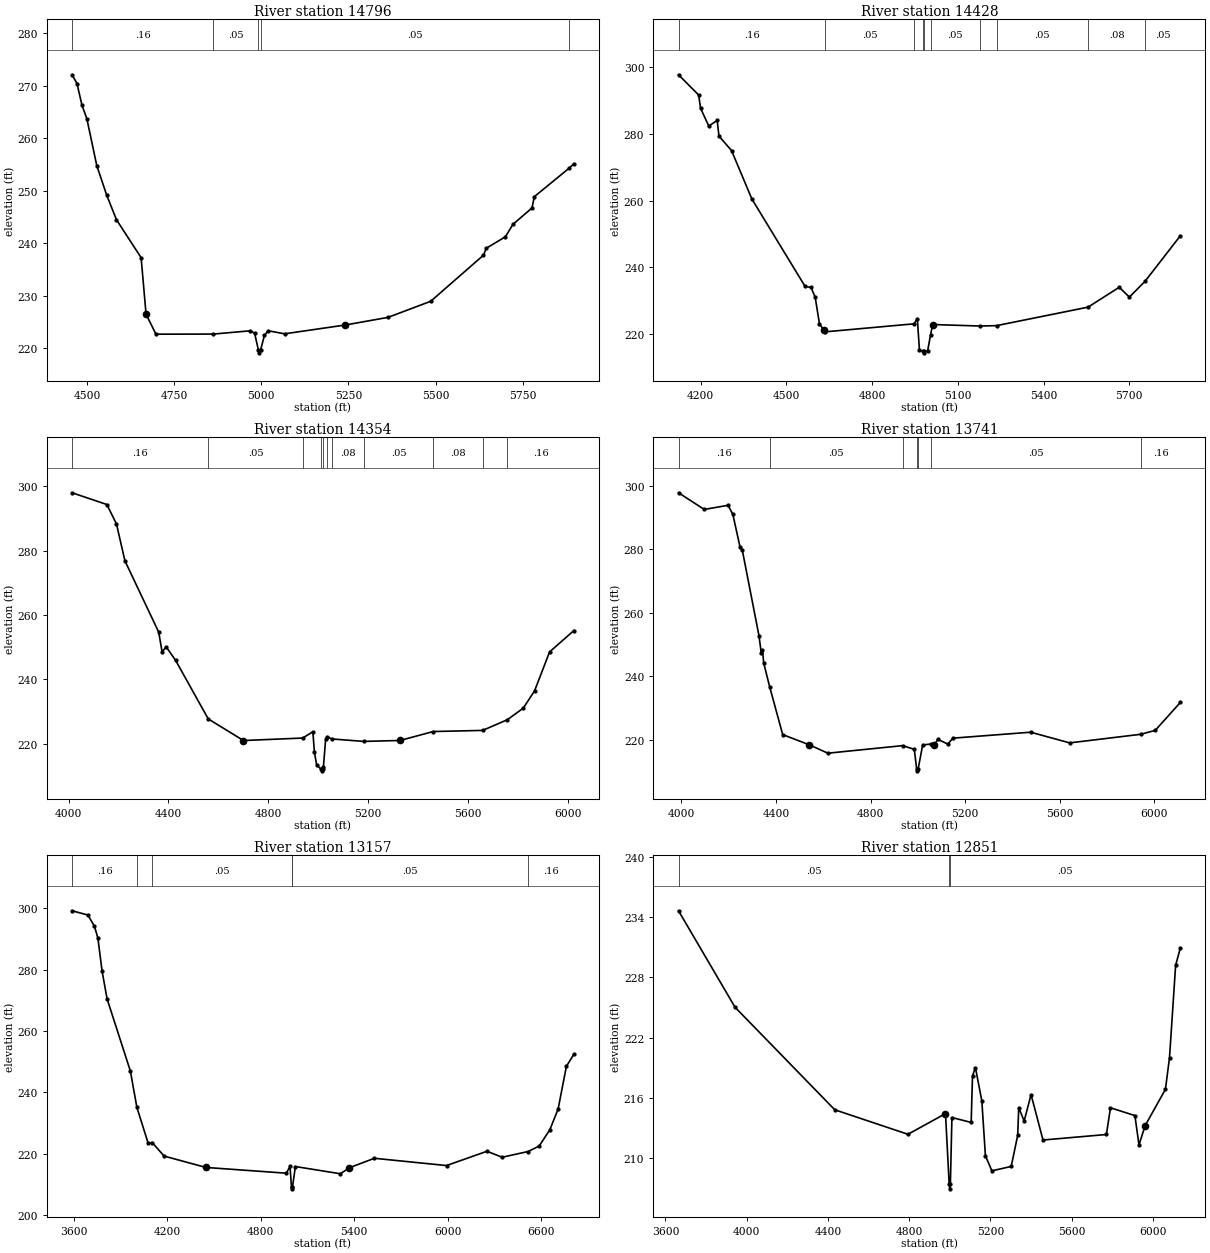
Type RM Length L Ch R = 1 ,14796   ,368,368,368
BEGIN DESCRIPTION:
UNT065 IN BECR 4.0
END DESCRIPTION:
XS GIS Cut Line= 3
      3785099.58     10480260.16      3785499.61     10480660.19
      3786299.57     10481010.17
#Sta/Elev= 30
  4457.5  272.04  4471.7  270.36  4485.8  266.27    4500  263.65  4528.3  254.78
  4556.5   249.2  4584.8  244.46  4655.5  237.25  4669.7  226.48    4698  222.69
  4862.3  222.71  4966.7  223.32  4980.8  222.92  4991.9  219.64  4994.7  219.14
  4997.9  219.64  5009.1  222.44  5019.7  223.34  5066.9  222.76  5241.5  224.44
  5363.6  225.89    5486  228.95  5637.2  237.72  5645.4  239.04    5700  241.22
  5721.8  243.59  5776.4   246.7    5783  248.85  5882.7  254.26  5896.4  255.12
#Mann= 5 ,-1 , 0
  4457.5     .16       0  4862.3     .05       0  4991.9     .03       0
  4997.9     .05       0  5882.7     .08       0
Bank Sta=4669.7,5241.5
XS Rating Curve= 0 ,0
Exp/Cntr=0.3,0.1

Type RM Length L Ch R = 1 ,14428   ,74,74,74
BEGIN DESCRIPTION:
UNT065 IN BECR 3.0
END DESCRIPTION:
XS GIS Cut Line= 5
      3784703.57     10480287.75      3785133.25       10480878.
      3785393.66     10480995.19      3785528.21     10481121.06
      3786074.79     10481225.17
#Sta/Elev= 30
  4122.3  297.63  4192.7  291.58  4199.5  287.59  4228.2  282.29  4257.6  283.97
  4263.8   279.3  4307.8  274.96  4378.9  260.48  4565.1  234.33    4586  234.01
  4600.7  231.05  4615.4  223.18    4630  221.29  4636.4  220.73  4946.6  223.12
  4958.1  224.69  4965.5  215.26    4977  214.94  4979.7  214.44    4983  214.94
  4994.1  215.01  5004.4  219.81  5011.8  222.91  5178.1  222.46  5235.5  222.58
  5555.6  228.11  5664.8  234.06  5700.3  231.12  5755.4  235.88  5878.6  249.45
#Mann= 10 ,-1 , 0
  4122.3     .16       0  4636.4     .05       0  4946.6     .08       0
    4977     .07       0    4983     .08       0  5004.4     .05       0
  5178.1     .08       0  5235.5     .05       0  5555.6     .08       0
  5755.4     .05       0
Bank Sta=4630,5011.8
XS Rating Curve= 0 ,0
Exp/Cntr=0.3,0.1

Type RM Length L Ch R = 1 ,14354   ,613,613,613
BEGIN DESCRIPTION:
Mapping XS d32444bb
END DESCRIPTION:
XS GIS Cut Line= 6
      3784629.79     10480322.48       3784955.3     10480947.45
      3785163.63     10480956.13      3785293.84     10481042.93
      3785493.49     10481285.99      3786116.59     10481329.26
#Sta/Elev= 30
  4014.1  297.97  4153.4  294.32  4191.9  288.26  4225.7  276.81    4361  254.64
  4374.4  248.52  4390.9  250.06  4428.7  245.86  4559.3  227.66  4700.3  220.95
  4937.6  221.73  4978.1  223.68  4984.1  217.43  4993.1  213.41  5011.1  212.03
  5013.9  211.53  5017.1  212.03  5020.2  212.62  5029.2  221.33  5035.4  222.15
  5053.4  221.45  5181.1  220.68  5326.9  220.97    5460  223.75  5657.6   224.1
  5756.5  227.41  5820.1     231  5865.5  236.38  5925.7   248.5  6022.9  255.13
#Mann= 11 ,-1 , 0
  4014.1     .16       0  4559.3     .05       0  4937.6     .08       0
  5011.1     .07       0  5017.1     .08       0  5035.4     .05       0
  5053.4     .08       0  5181.1     .05       0    5460     .08       0
  5657.6     .05       0  5756.5     .16       0
Bank Sta=4700.3,5326.9
XS Rating Curve= 0 ,0
Exp/Cntr=0.3,0.1

Type RM Length L Ch R = 1 ,13741   ,584,584,584
BEGIN DESCRIPTION:
Mapping XS fc877455
END DESCRIPTION:
XS GIS Cut Line= 4
      3784619.56     10480511.93      3784692.48     10481246.27
      3785114.35     10481563.97      3785942.49     10481350.43
#Sta/Elev= 30
    3988  297.77  4096.8  292.53  4197.3  293.83  4217.4  291.05  4247.5  280.87
  4257.6  279.72  4327.9  252.87  4337.8   247.4  4342.8  248.35    4348  244.27
  4373.1  236.78  4428.4  221.71    4539  218.56  4619.3  215.87  4935.6  218.25
  4984.6  217.08  4994.8  210.82  4997.5  210.32  5000.8  210.82    5020  218.45
  5055.9  218.77  5069.9  218.56  5084.5  220.22  5126.2  218.74    5148   220.6
  5476.4  222.47  5641.6  219.11  5941.4  221.81  6003.1  223.04  6109.3  231.83
#Mann= 7 ,-1 , 0
    3988     .16       0  4373.1     .05       0  4935.6     .16       0
  4994.8     .07       0  5000.8     .16       0  5055.9     .05       0
  5941.4     .16       0
Bank Sta=4539,5069.9
XS Rating Curve= 0 ,0
Exp/Cntr=0.3,0.1

Type RM Length L Ch R = 1 ,13157   ,306,306,306
BEGIN DESCRIPTION:
UNT065 IN BECR 2.0
END DESCRIPTION:
XS GIS Cut Line= 4
      3784573.34     10480483.06      3784278.21      10481416.2
      3784599.39     10481967.41      3786085.62     10481355.57
#Sta/Elev= 30
  3587.1  299.23    3689  297.84  3730.9  294.16  3752.9  290.35    3780  279.51
  3812.3  270.44  3961.7  246.93  4003.4  235.11  4076.1  223.36  4102.4  223.59
  4178.2  219.19  4447.2  215.48  4963.9   213.6  4987.1  215.85    4997     209
  4999.8   208.5    5003     209  5021.8  215.78  5310.7  213.42  5369.4  215.39
  5529.3  218.47  5992.8   216.1    6253  220.76  6350.3  218.81  6517.4  220.68
  6588.2  222.48  6656.5  227.76  6709.8  234.53  6763.1  248.47    6811   252.4
#Mann= 6 ,-1 , 0
  3587.1     .16       0  4003.4     .08       0  4102.4     .05       0
    4997     .04       0    5003     .05       0  6517.4     .16       0
Bank Sta=4447.2,5369.4
XS Rating Curve= 0 ,0
Exp/Cntr=0.3,0.1

Type RM Length L Ch R = 1 ,12851   ,385,385,385
BEGIN DESCRIPTION:
Mapping XS cf9f48af
END DESCRIPTION:
XS GIS Cut Line= 4
      3783978.94     10480532.75      3784036.23     10481345.22
      3784317.48     10482199.39      3785072.72     10482251.48
#Sta/Elev= 30
  3664.5  234.64  3942.6  225.04  4433.8  214.83  4794.2  212.39    4979  214.45
  4997.1  207.46  4999.8  206.96  5003.1  207.46  5010.6  214.06  5105.4  213.57
    5112  218.22  5126.4  219.03    5158  215.71  5175.5  210.26  5207.3  208.75
  5302.6  209.19  5334.4  212.28  5339.7  215.05  5366.2  213.71  5400.4  216.34
  5459.1  211.82  5771.3  212.37  5791.4  215.03  5911.7  214.25  5931.7  211.33
  5961.8  213.24    6062  216.87  6082.1  220.03  6112.1   229.2  6135.3  230.94
#Mann= 3 ,-1 , 0
  3664.5     .05       0  4997.1     .04       0  5003.1     .05       0
Bank Sta=4979,5961.8
XS Rating Curve= 0 ,0
Exp/Cntr=0.3,0.1

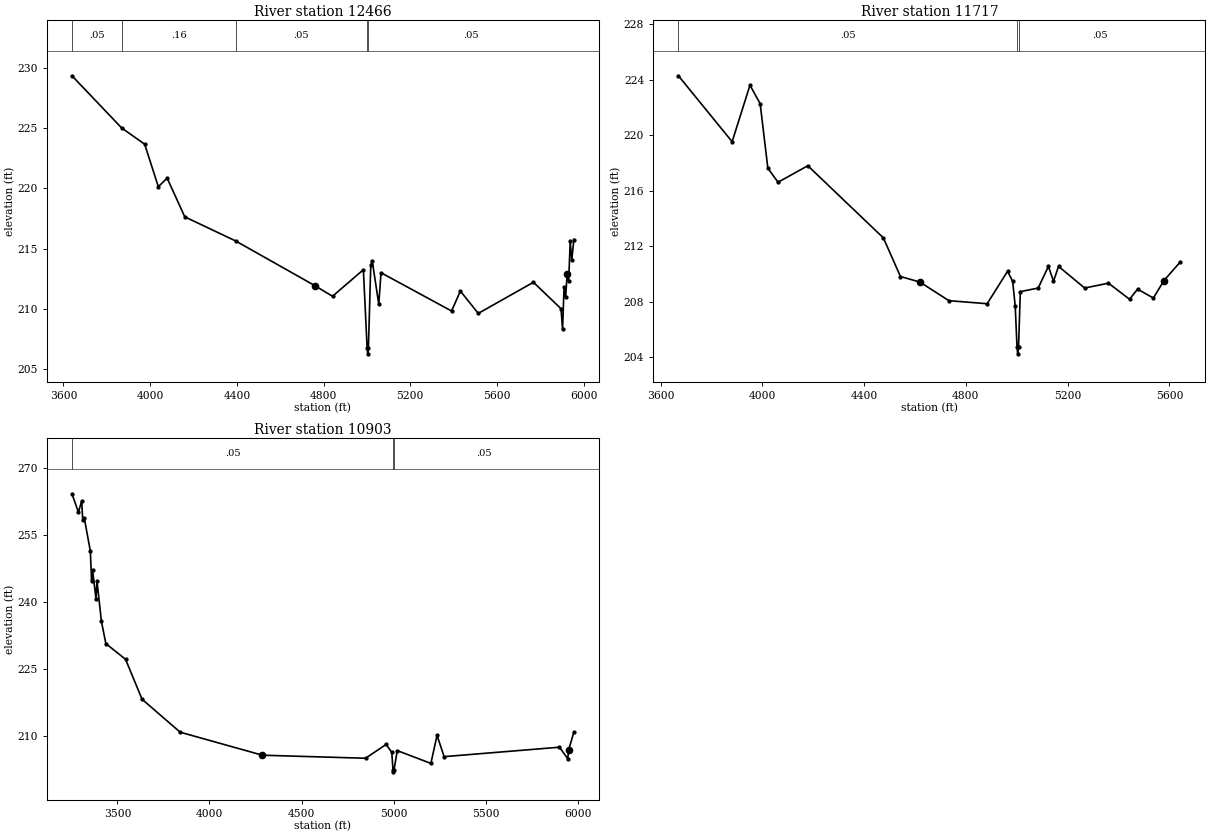
Type RM Length L Ch R = 1 ,12466   ,749,749,749
BEGIN DESCRIPTION:
Mapping XS 4d110feb
END DESCRIPTION:
XS GIS Cut Line= 3
      3783572.69     10480548.37      3783906.02     10482340.02
      3784254.77     10482688.77
#Sta/Elev= 30
    3639  229.32  3868.2     225  3974.5  223.65  4037.5  220.13  4078.2  220.84
  4159.6  217.63  4393.6  215.64  4759.7  211.93  4841.1  211.05  4983.5  213.25
  5000.8  206.78  5003.6  206.28  5006.8  206.78  5017.7  213.64  5024.2     214
  5054.7  210.39  5064.9     213  5390.4  209.83  5431.1  211.48  5513.6  209.63
  5768.1  212.21  5895.4  210.02  5902.5  208.33  5909.5  211.81  5916.6  210.96
  5923.7  212.88  5930.7  212.28  5937.8  215.61  5944.9  214.03  5954.6  215.75
#Mann= 5 ,-1 , 0
    3639     .05       0  3868.2     .16       0  4393.6     .05       0
  5000.8     .04       0  5006.8     .05       0
Bank Sta=4759.7,5923.7
XS Rating Curve= 0 ,0
Exp/Cntr=0.3,0.1

Type RM Length L Ch R = 1 ,11717   ,814,814,814
BEGIN DESCRIPTION:
Mapping XS 8bad236b
END DESCRIPTION:
XS GIS Cut Line= 3
      3783239.35     10480579.61      3783135.18     10482105.64
       3783254.8      10482532.1
#Sta/Elev= 30
  3670.3  224.28  3881.4  219.53  3951.5   223.6  3991.6  222.27  4021.7  217.63
  4061.8  216.61  4178.8   217.8  4475.9   212.6  4542.9  209.82  4619.5  209.42
  4733.3  208.08  4883.7  207.86  4963.9   210.2  4983.9  209.47    4994  207.68
    5001  204.75  5003.7  204.25    5007  204.75    5014  208.73  5084.2  208.99
  5124.3  210.55  5144.3  209.48  5164.3  210.55  5266.8  208.99  5360.4  209.34
  5443.5  208.18  5474.6  208.91    5537  208.27  5578.5  209.53  5642.8  210.87
#Mann= 3 ,-1 , 0
  3670.3     .05       0    5001     .03       0    5007     .05       0
Bank Sta=4619.5,5578.5
XS Rating Curve= 0 ,0
Exp/Cntr=0.3,0.1

Type RM Length L Ch R = 1 ,10903   ,0,0,0
BEGIN DESCRIPTION:
Mapping XS 9cb32907
END DESCRIPTION:
XS GIS Cut Line= 4
      3782895.38     10480127.72      3782452.68     10481212.77
      3782331.15     10481976.66      3782679.44     10482675.04
#Sta/Elev= 30
  3253.1  264.23  3288.2  260.11  3306.2  262.65  3311.6  258.26  3320.6   258.7
    3353   251.4  3359.7  244.82  3365.1  247.14  3383.7  240.72  3389.1  244.69
  3413.2  235.67  3437.2  230.71  3544.2   227.2  3633.8  218.26  3840.9  210.89
  4287.4  205.74  4847.7  205.06    4959  208.15    4990  206.39  4996.5  202.52
  4999.3  202.02  5002.5  202.52  5019.8  206.77  5202.4  203.91    5236  210.18
  5274.3  205.42  5900.9  207.53  5945.6  204.96  5951.2  207.01  5978.9  210.88
#Mann= 3 ,-1 , 0
  3253.1     .05       0  4996.5     .03       0  5002.5     .05       0
Bank Sta=4287.4,5951.2
XS Rating Curve= 0 ,0
Exp/Cntr=0.3,0.1

Chan Stop Cuts=-1
Use User Specified Reach Order=0
Composite Channel Slope=5