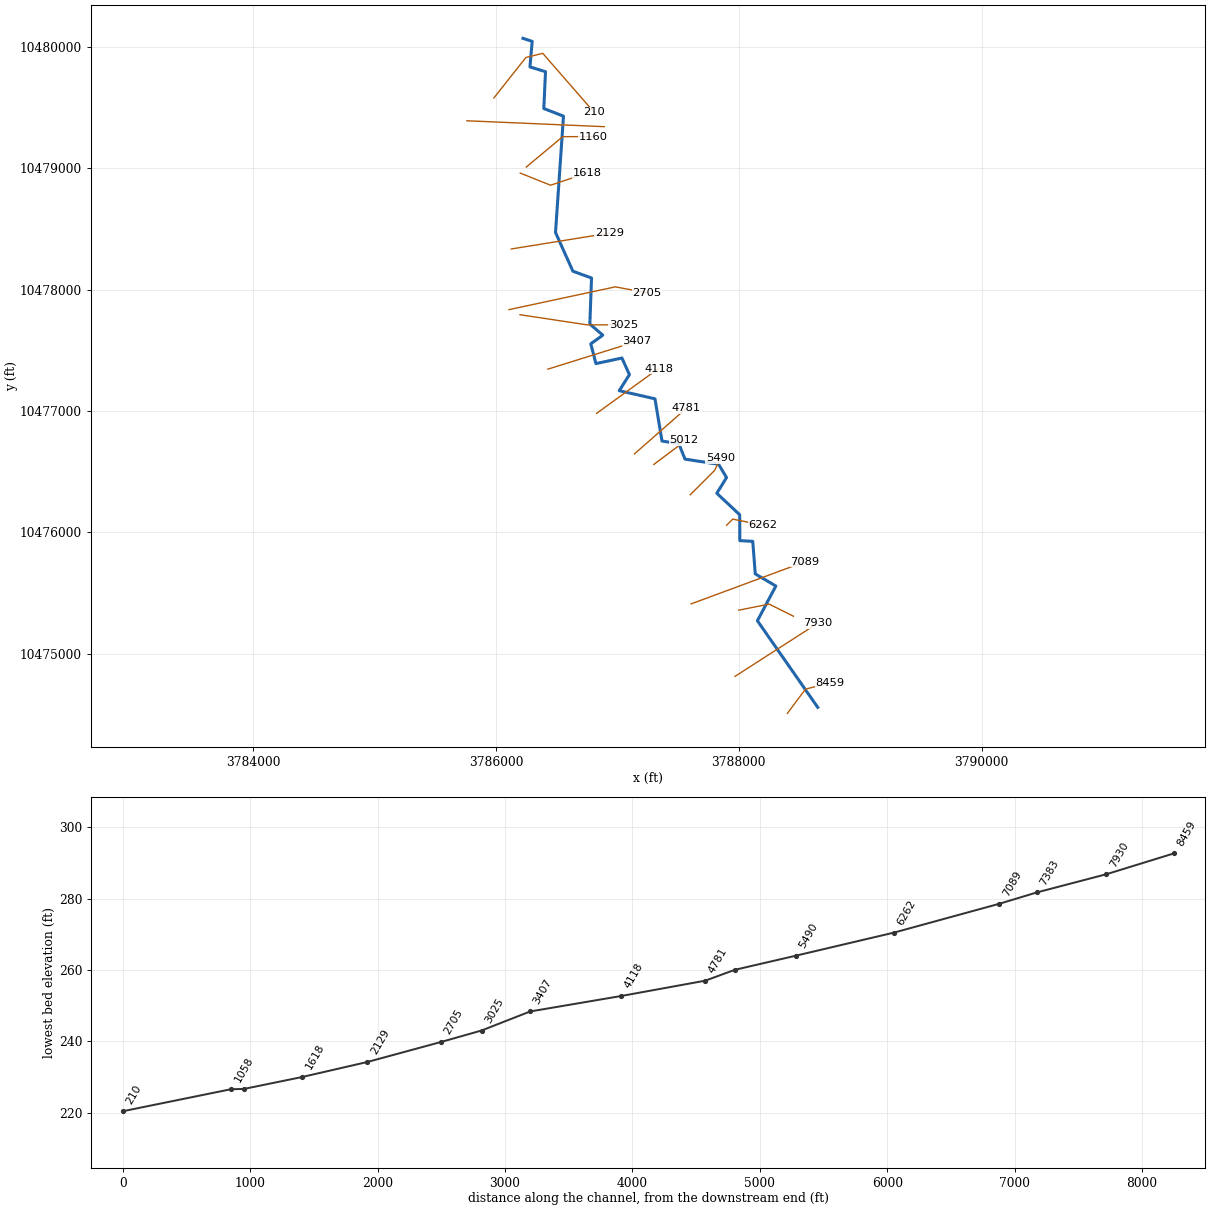
--- UNT067 IN BECR.prj (project) ---

Proj Title=UNT067 IN BECR Base Level Engineering
Current Plan=p01
Default Exp/Contr=0.3,0.1
English Units
Geom File=g01
Flow File=f01
Plan File=p01
BEGIN DESCRIPTION:
UNT067 IN BECR
END DESCRIPTION:

--- UNT067 IN BECR.p01 (plan) ---

Plan Title=Multiple Run
Short Identifier=Multiple
Geom File=g01
Flow File=f01
Subcritical Flow
K Sum by GR= 0
Std Step Tol= 0.01
Critical Tol= 0.01
Num of Std Step Trials= 20
Max Error Tol= 0.3
Flow Tol Ratio= 0.001
Split Flow NTrial= 30
Split Flow Tol= 0.02
Split Flow Ratio= 0.02
Log Output Level= 0
Friction Slope Method= 1
Unsteady Friction Slope Method= 2
Unsteady Bridges Friction Slope Method= 1
Parabolic Critical Depth
Global Vel Dist=  1 , 1 , 1
Global Log Level= 0
CheckData=True
Encroach Param= -1, 0, 0, 0
BEGIN DESCRIPTION:
Multiple Run
END DESCRIPTION:

--- UNT067 IN BECR.f01 (steady flow) ---

Flow Title=Multiple
Number of Profiles=7
Profile Names=10-year,25-year,50-year,1pct_min,100-year,1pct_plu,500-year
River Rch & RM= UNT067 IN BECR,Reach-1,8459
     373     489     581     508     688     930     965
Boundary for River Rch & Prof#=UNT067 IN BECR,Reach-1,1
Up Type=0
Dn Type=3
Dn Slope=0.005
Boundary for River Rch & Prof#=UNT067 IN BECR,Reach-1,2
Up Type=0
Dn Type=3
Dn Slope=0.005
Boundary for River Rch & Prof#=UNT067 IN BECR,Reach-1,3
Up Type=0
Dn Type=3
Dn Slope=0.005
Boundary for River Rch & Prof#=UNT067 IN BECR,Reach-1,4
Up Type=0
Dn Type=3
Dn Slope=0.005
Boundary for River Rch & Prof#=UNT067 IN BECR,Reach-1,5
Up Type=0
Dn Type=3
Dn Slope=0.005
Boundary for River Rch & Prof#=UNT067 IN BECR,Reach-1,6
Up Type=0
Dn Type=3
Dn Slope=0.005
Boundary for River Rch & Prof#=UNT067 IN BECR,Reach-1,7
Up Type=0
Dn Type=3
Dn Slope=0.005

--- UNT067 IN BECR.g01 (geometry) ---

Geom Title=Existing Conditions

River Reach=UNT067 IN BECR,Reach-1
Reach XY= 30
      3788649.61     10474560.19      3788153.00     10475273.00
      3788305.00     10475559.00      3788135.25     10475659.00
      3788114.75     10475927.00      3788008.00     10475933.00
      3788007.25     10476146.00      3787818.75     10476323.00
      3787898.50     10476452.00      3787833.50     10476562.00
      3787557.00     10476604.00      3787505.25     10476732.00
      3787367.00     10476753.00      3787309.25     10477101.00
      3787015.00     10477168.00      3787098.75     10477300.00
      3787037.25     10477437.00      3786823.00     10477391.00
      3786780.75     10477554.00      3786879.75     10477625.00
      3786773.00     10477717.00      3786786.75     10478096.00
      3786633.25     10478152.00      3786490.10     10478471.10
      3786555.75     10479429.00      3786393.75     10479492.00
      3786407.75     10479795.00      3786279.50     10479835.00
      3786298.00     10480045.00      3786222.25     10480070.00

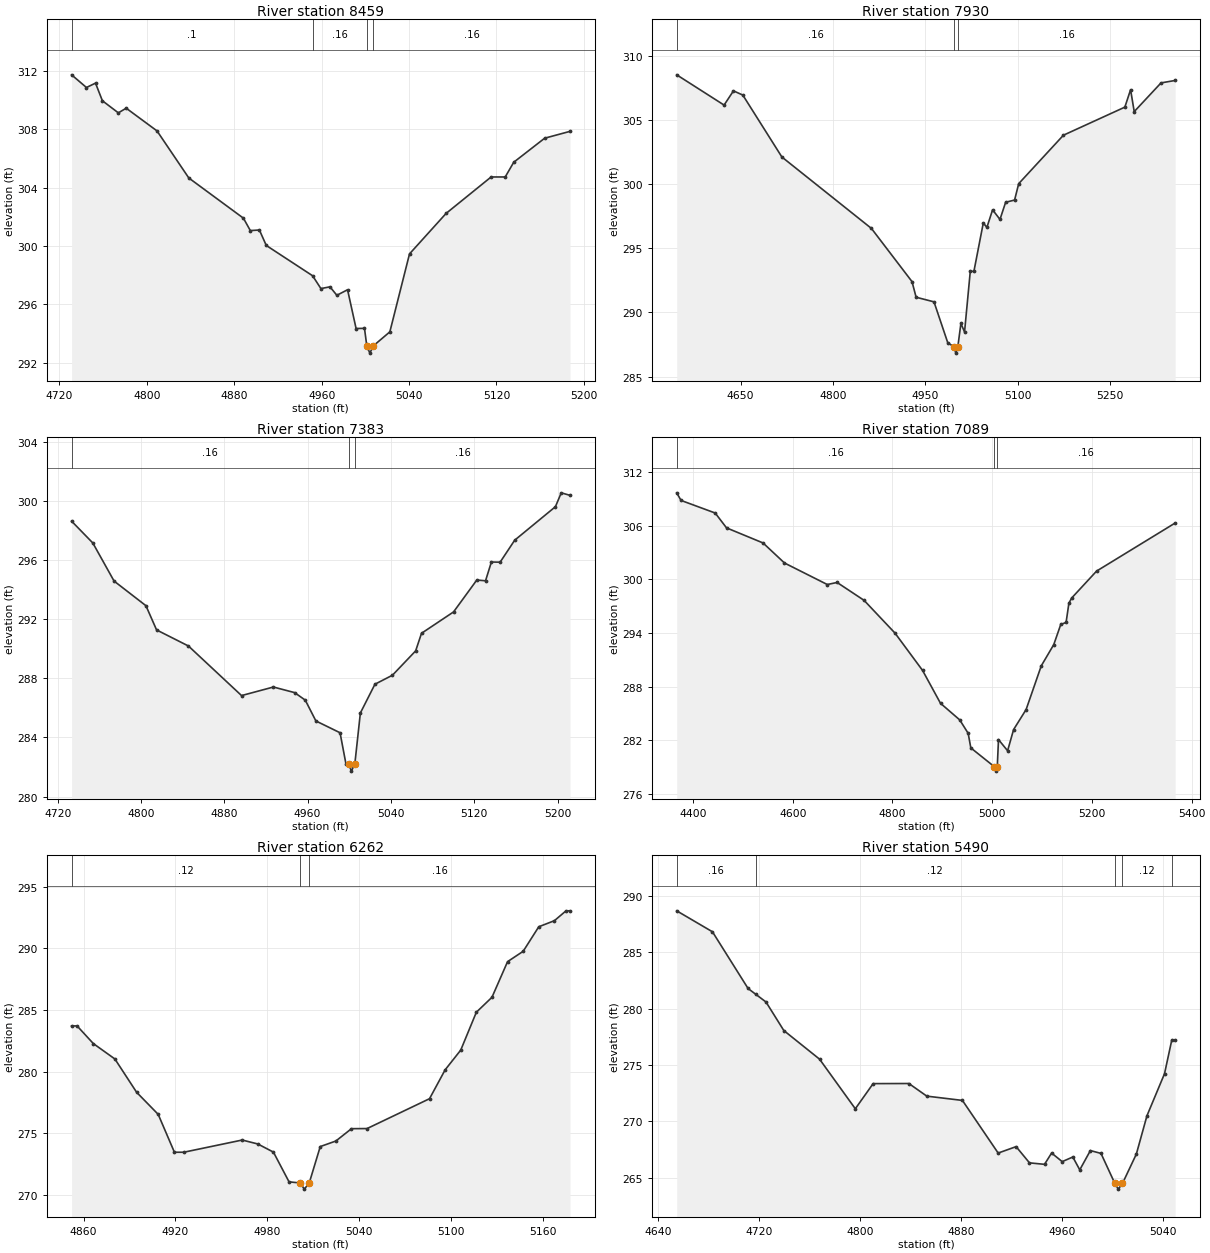
Type RM Length L Ch R = 1,8459,529,529,529
BEGIN DESCRIPTION:
UNT067 IN BECR 16.0
END DESCRIPTION:
XS GIS Cut Line= 3
      3788399.58     10474510.15      3788549.61     10474710.19
      3788749.61     10474760.19
#Sta/Elev= 30
  4731.1  311.75  4744.7  310.88  4753.0  311.18  4759.3  309.97  4773.9  309.14
  4781.1  309.46  4809.3  307.90  4838.4  304.67  4888.4  301.91  4894.7  301.06
  4903.0  301.10  4909.3  300.04  4951.7  297.96  4959.3  297.08  4967.6  297.20
  4973.9  296.62  4983.7  297.00  4991.5  294.34  4999.2  294.35  5001.3  293.15
  5004.1  292.65  5007.3  293.15  5022.4  294.11  5040.4  299.46  5073.9  302.24
  5115.1  304.74  5128.0  304.74  5135.8  305.75  5164.1  307.40  5187.3  307.87
#Mann=4,-1,0
  4731.1     0.1       0  4951.7    0.16       0  5001.3    0.07       0
  5007.3    0.16       0
Bank Sta=5001.3,5007.3
Exp/Cntr=0.3,0.1

Type RM Length L Ch R = 1,7930,547,547,547
BEGIN DESCRIPTION:
UNT067 IN BECR 15.0
END DESCRIPTION:
XS GIS Cut Line= 2
      3787968.33     10474814.64      3788648.84     10475252.12
#Sta/Elev= 30
  4546.4  308.54  4623.3  306.18  4638.5  307.29  4653.7  306.96  4717.1  302.13
  4862.4  296.56  4928.3  292.41  4935.0  291.19  4964.0  290.83  4986.5  287.62
  4996.7  287.33  4999.4  286.83  5002.7  287.33  5007.7  289.15  5013.6  288.48
  5022.9  293.21  5028.8  293.21  5044.0  296.98  5049.9  296.64  5059.1  298.01
  5071.1  297.26  5080.3  298.60  5094.8  298.77  5101.5  300.05  5174.1  303.83
  5273.8  306.02  5283.1  307.38  5289.0  305.67  5332.5  307.91  5355.4  308.10
#Mann=3,-1,0
  4546.4    0.16       0  4996.7    0.07       0  5002.7    0.16       0
Bank Sta=4996.7,5002.7
Exp/Cntr=0.3,0.1

Type RM Length L Ch R = 1,7383,294,294,294
BEGIN DESCRIPTION:
UNT067 IN BECR 14.0
END DESCRIPTION:
XS GIS Cut Line= 3
      3787999.58     10475360.18      3788249.61     10475410.19
      3788449.62     10475310.18
#Sta/Elev= 30
  4733.4  298.66  4753.8  297.18  4774.2  294.60  4804.8  292.93  4815.0  291.29
  4845.6  290.20  4896.6  286.84  4927.2  287.42  4947.6  287.04  4957.8  286.53
  4968.0  285.12  4991.2  284.32  4996.8  282.23  4999.4  282.22  5002.1  281.72
  5005.4  282.22  5010.7  285.66  5024.7  287.61  5041.5  288.22  5063.8  289.87
  5069.4  291.06  5100.2  292.51  5122.5  294.67  5130.9  294.62  5136.5  295.89
  5144.9  295.88  5158.9  297.37  5198.0  299.64  5203.6  300.58  5212.0  300.41
#Mann=3,-1,0
  4733.4    0.16       0  4999.4    0.07       0  5005.4    0.16       0
Bank Sta=4999.4,5005.4
Exp/Cntr=0.3,0.1

Type RM Length L Ch R = 1,7089,827,827,827
BEGIN DESCRIPTION:
UNT067 IN BECR 13.0
END DESCRIPTION:
XS GIS Cut Line= 2
      3787607.23     10475411.86      3788544.69     10475759.08
#Sta/Elev= 30
  4367.2  309.69  4375.9  308.84  4444.4  307.43  4467.1  305.77  4540.4  304.08
  4583.3  301.84  4669.2  299.43  4688.9  299.66  4743.0  297.66  4805.1  293.99
  4860.3  289.82  4896.3  286.14  4934.9  284.28  4951.8  282.78  4957.1  281.15
  5004.2  279.05  5007.0  278.55  5010.2  279.05  5012.6  282.08  5030.9  280.83
  5042.9  283.20  5068.0  285.44  5098.4  290.33  5123.5  292.71  5137.5  294.96
  5148.2  295.19  5153.8  297.33  5159.2  297.91  5209.3  300.93  5366.9  306.31
#Mann=3,-1,0
  4367.2    0.16       0  5004.2    0.07       0  5010.2    0.16       0
Bank Sta=5004.2,5010.2
Exp/Cntr=0.3,0.1

Type RM Length L Ch R = 1,6262,772,772,772
BEGIN DESCRIPTION:
UNT067 IN BECR 12.0
END DESCRIPTION:
XS GIS Cut Line= 3
      3787899.59     10476060.17      3787949.61     10476110.19
      3788199.62     10476060.19
#Sta/Elev= 30
  4852.2  283.70  4855.8  283.70  4866.4  282.27  4880.5  281.02  4894.7  278.32
  4908.8  276.53  4919.4  273.46  4925.5  273.46  4963.7  274.45  4973.9  274.13
  4984.1  273.47  4994.3  271.06  5001.5  270.97  5004.3  270.47  5007.5  270.97
  5014.7  273.92  5024.9  274.37  5035.1  275.37  5045.3  275.38  5086.1  277.80
  5096.3  280.14  5106.5  281.74  5116.7  284.81  5126.9  286.02  5137.1  288.91
  5147.3  289.75  5157.5  291.74  5167.7  292.23  5175.3  293.03  5177.9  293.03
#Mann=3,-1,0
  4852.2    0.12       0  5001.5    0.07       0  5007.5    0.16       0
Bank Sta=5001.5,5007.5
Exp/Cntr=0.3,0.1

Type RM Length L Ch R = 1,5490,478,478,478
BEGIN DESCRIPTION:
UNT067 IN BECR 11.0
END DESCRIPTION:
XS GIS Cut Line= 3
      3787599.63     10476310.21      3787799.61     10476510.19
      3787849.60     10476610.18
#Sta/Elev= 30
  4654.8  288.68  4683.1  286.82  4711.3  281.79  4717.2  281.29  4725.5  280.59
  4739.6  278.06  4767.9  275.52  4796.2  271.12  4810.3  273.35  4838.6  273.36
  4852.8  272.24  4881.0  271.86  4909.3  267.19  4923.5  267.76  4934.1  266.32
  4946.0  266.19  4951.6  267.19  4960.0  266.43  4968.4  266.84  4973.9  265.70
  4982.3  267.41  4990.7  267.16  5001.7  264.49  5004.4  263.99  5007.7  264.49
  5018.7  267.10  5027.1  270.50  5041.0  274.23  5046.7  277.19  5049.4  277.19
#Mann=5,-1,0
  4654.8    0.16       0  4717.2    0.12       0  5001.7    0.07       0
  5007.7    0.12       0  5046.7    0.16       0
Bank Sta=5001.7,5007.7
Exp/Cntr=0.3,0.1

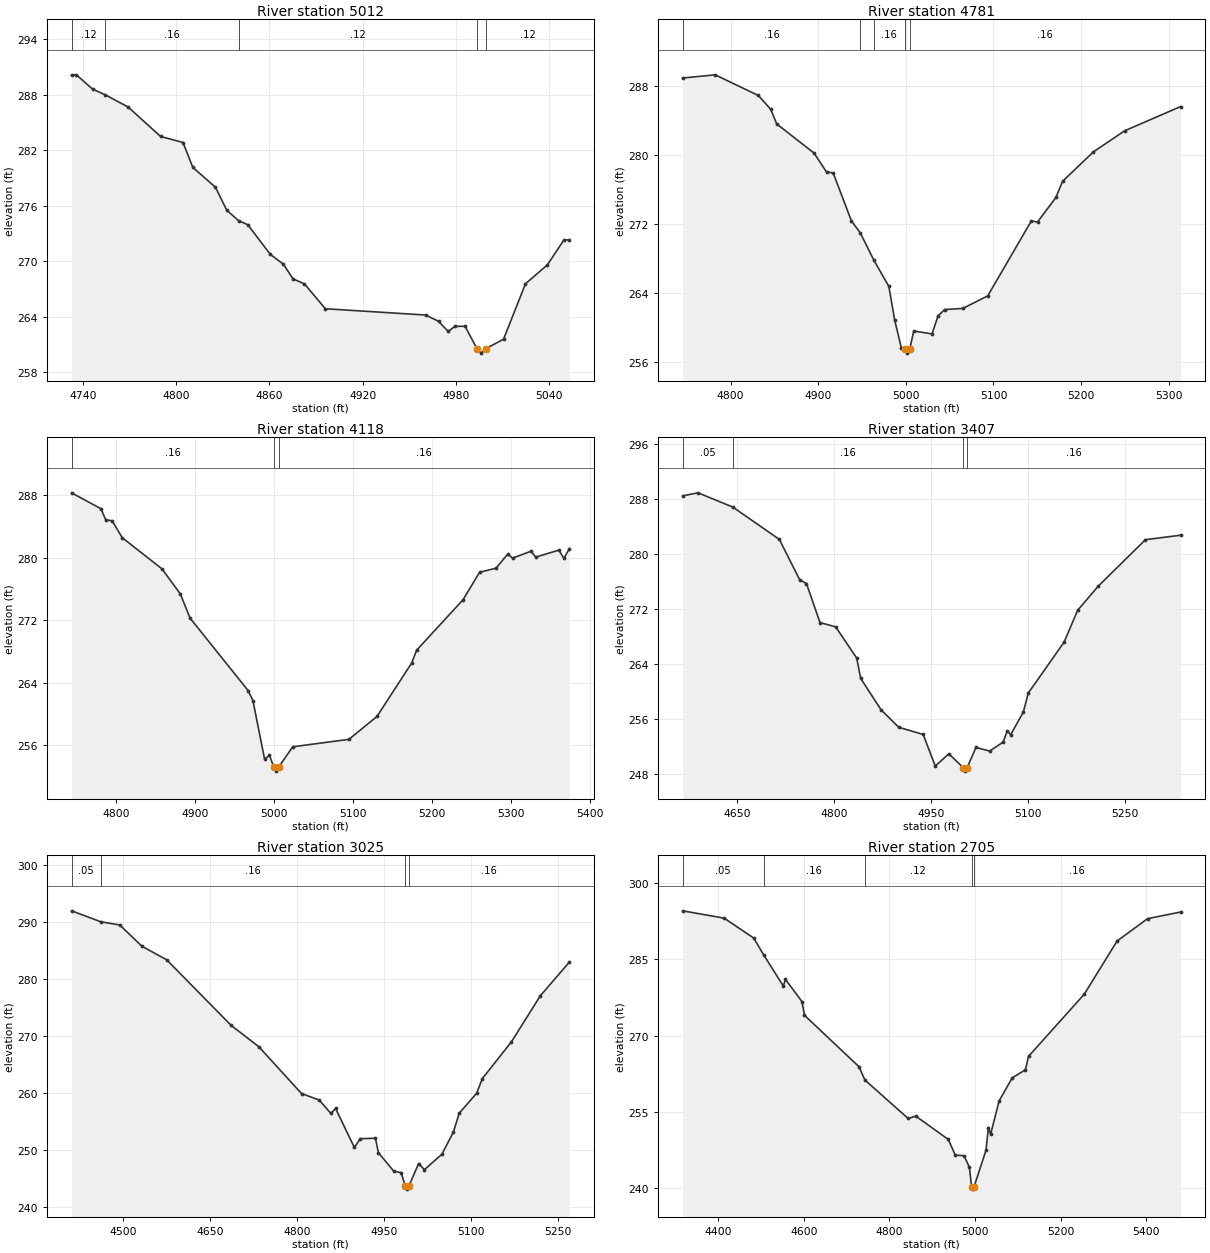
Type RM Length L Ch R = 1,5012,231,231,231
BEGIN DESCRIPTION:
UNT067 IN BECR 10.0
END DESCRIPTION:
XS GIS Cut Line= 3
      3787299.63     10476560.20      3787499.61     10476710.19
      3787549.62     10476760.20
#Sta/Elev= 30
  4732.5  290.14  4735.6  290.14  4746.0  288.60  4754.3  287.97  4768.9  286.66
  4789.8  283.48  4804.3  282.82  4810.6  280.13  4825.2  277.98  4832.5  275.49
  4840.1  274.37  4846.0  273.93  4860.6  270.71  4868.9  269.67  4875.2  268.07
  4882.5  267.53  4896.0  264.84  4960.6  264.16  4968.9  263.48  4975.2  262.38
  4979.4  262.94  4986.0  262.94  4993.6  260.54  4996.4  260.04  4999.6  260.54
  5010.8  261.55  5024.9  267.54  5039.0  269.58  5049.7  272.29  5053.2  272.29
#Mann=5,-1,0
  4732.5    0.12       0  4754.3    0.16       0  4840.1    0.12       0
  4993.6    0.07       0  4999.6    0.12       0
Bank Sta=4993.6,4999.6
Exp/Cntr=0.3,0.1

Type RM Length L Ch R = 1,4781,663,663,663
BEGIN DESCRIPTION:
UNT067 IN BECR 9.0
END DESCRIPTION:
XS GIS Cut Line= 2
      3787140.54     10476647.43      3787567.65     10477022.46
#Sta/Elev= 30
  4745.2  288.97  4782.3  289.34  4831.6  286.94  4845.8  285.33  4852.5  283.64
  4895.2  280.25  4909.4  278.05  4917.0  277.95  4937.9  272.36  4947.8  271.01
  4963.6  267.78  4980.6  264.76  4987.2  260.87  4994.8  257.64  4998.5  257.51
  5001.2  257.01  5004.5  257.51  5009.0  259.58  5029.9  259.24  5036.7  261.32
  5044.2  262.07  5065.0  262.20  5093.5  263.66  5143.2  272.36  5150.4  272.25
  5171.3  275.09  5178.9  276.97  5214.0  280.38  5249.7  282.83  5313.6  285.65
#Mann=5,-1,0
  4745.2    0.16       0  4947.8    0.12       0  4963.6    0.16       0
  4998.5    0.07       0  5004.5    0.16       0
Bank Sta=4998.5,5004.5
Exp/Cntr=0.3,0.1

Type RM Length L Ch R = 1,4118,711,711,711
BEGIN DESCRIPTION:
UNT067 IN BECR 8.0
END DESCRIPTION:
XS GIS Cut Line= 2
      3786828.08     10476980.80      3787338.50     10477350.59
#Sta/Elev= 30
  4743.8  288.27  4781.0  286.24  4787.1  284.81  4795.1  284.70  4808.0  282.53
  4858.3  278.55  4881.5  275.35  4893.9  272.25  4967.3  263.00  4973.5  261.68
  4988.2  254.23  4994.4  254.71  4999.9  253.20  5002.6  252.70  5005.9  253.20
  5023.8  255.81  5094.9  256.76  5130.5  259.69  5174.6  266.55  5180.7  268.16
  5239.5  274.61  5260.4  278.12  5281.3  278.64  5296.0  280.44  5302.1  279.92
  5325.4  280.80  5331.5  280.06  5360.9  280.95  5367.1  279.89  5374.1  281.13
#Mann=3,-1,0
  4743.8    0.16       0  4999.9    0.07       0  5005.9    0.16       0
Bank Sta=4999.9,5005.9
Exp/Cntr=0.3,0.1

Type RM Length L Ch R = 1,3407,382,382,382
BEGIN DESCRIPTION:
UNT067 IN BECR 7.0
END DESCRIPTION:
XS GIS Cut Line= 2
      3786427.00     10477345.37      3787161.37     10477574.53
#Sta/Elev= 30
  4566.0  288.46  4589.7  288.90  4643.4  286.83  4715.4  282.12  4746.8  276.24
  4757.3  275.69  4778.2  270.01  4802.4  269.39  4834.9  264.85  4841.1  261.88
  4872.6  257.31  4899.9  254.77  4937.6  253.73  4956.3  249.13  4977.3  250.91
  4999.6  248.89  5002.4  248.39  5005.6  248.89  5019.2  251.84  5040.4  251.31
  5061.1  252.61  5067.6  254.25  5072.9  253.69  5092.5  257.01  5100.1  259.76
  5155.4  267.17  5176.3  271.80  5208.1  275.31  5281.1  282.08  5335.3  282.73
#Mann=4,-1,0
  4566.0    0.05       0  4643.4    0.16       0  4999.6    0.07       0
  5005.6    0.16       0
Bank Sta=4999.6,5005.6
Exp/Cntr=0.3,0.1

Type RM Length L Ch R = 1,3025,320,320,320
BEGIN DESCRIPTION:
UNT067 IN BECR 6.0
END DESCRIPTION:
XS GIS Cut Line= 3
      3786197.44     10477793.81      3786749.61     10477710.19
      3787049.64     10477710.19
#Sta/Elev= 30
  4411.5  291.88  4462.3  289.95  4494.6  289.40  4532.9  285.66  4575.5  283.29
  4686.8  271.77  4734.3  268.05  4808.1  259.82  4838.5  258.69  4858.7  256.33
  4866.8  257.20  4899.2  250.36  4909.3  251.90  4935.6  251.98  4940.6  249.45
  4967.4  246.17  4980.0  245.95  4987.0  243.55  4989.7  243.05  4993.0  243.55
  5010.0  247.54  5020.0  246.47  5050.0  249.15  5070.0  253.07  5080.0  256.36
  5110.0  259.87  5120.0  262.46  5170.0  268.89  5220.0  276.99  5270.0  282.89
#Mann=4,-1,0
  4411.5    0.05       0  4462.3    0.16       0  4987.0    0.07       0
  4993.0    0.16       0
Bank Sta=4987,4993
Exp/Cntr=0.3,0.1

Type RM Length L Ch R = 1,2705,576,576,576
BEGIN DESCRIPTION:
UNT067 IN BECR 5.0
END DESCRIPTION:
XS GIS Cut Line= 3
      3786107.21     10477835.47      3786982.21     10478022.97
      3787245.32     10477974.50
#Sta/Elev= 30
  4317.3  294.54  4414.2  293.10  4483.4  289.17  4506.2  285.91  4552.2  279.75
  4557.3  281.05  4595.9  276.69  4601.7  274.00  4728.8  263.90  4742.9  261.26
  4843.7  253.71  4861.8  254.17  4937.4  249.59  4953.8  246.51  4974.3  246.39
  4986.9  244.08  4991.7  240.32  4994.5  239.82  4997.7  240.32  5025.4  247.43
  5031.2  251.93  5036.3  250.60  5056.1  257.16  5086.8  261.71  5117.5  263.28
  5124.9  265.93  5255.2  278.17  5331.5  288.60  5402.7  293.00  5479.7  294.30
#Mann=5,-1,0
  4317.3    0.05       0  4506.2    0.16       0  4742.9    0.12       0
  4991.7    0.07       0  4997.7    0.16       0
Bank Sta=4991.7,4997.7
Exp/Cntr=0.3,0.1

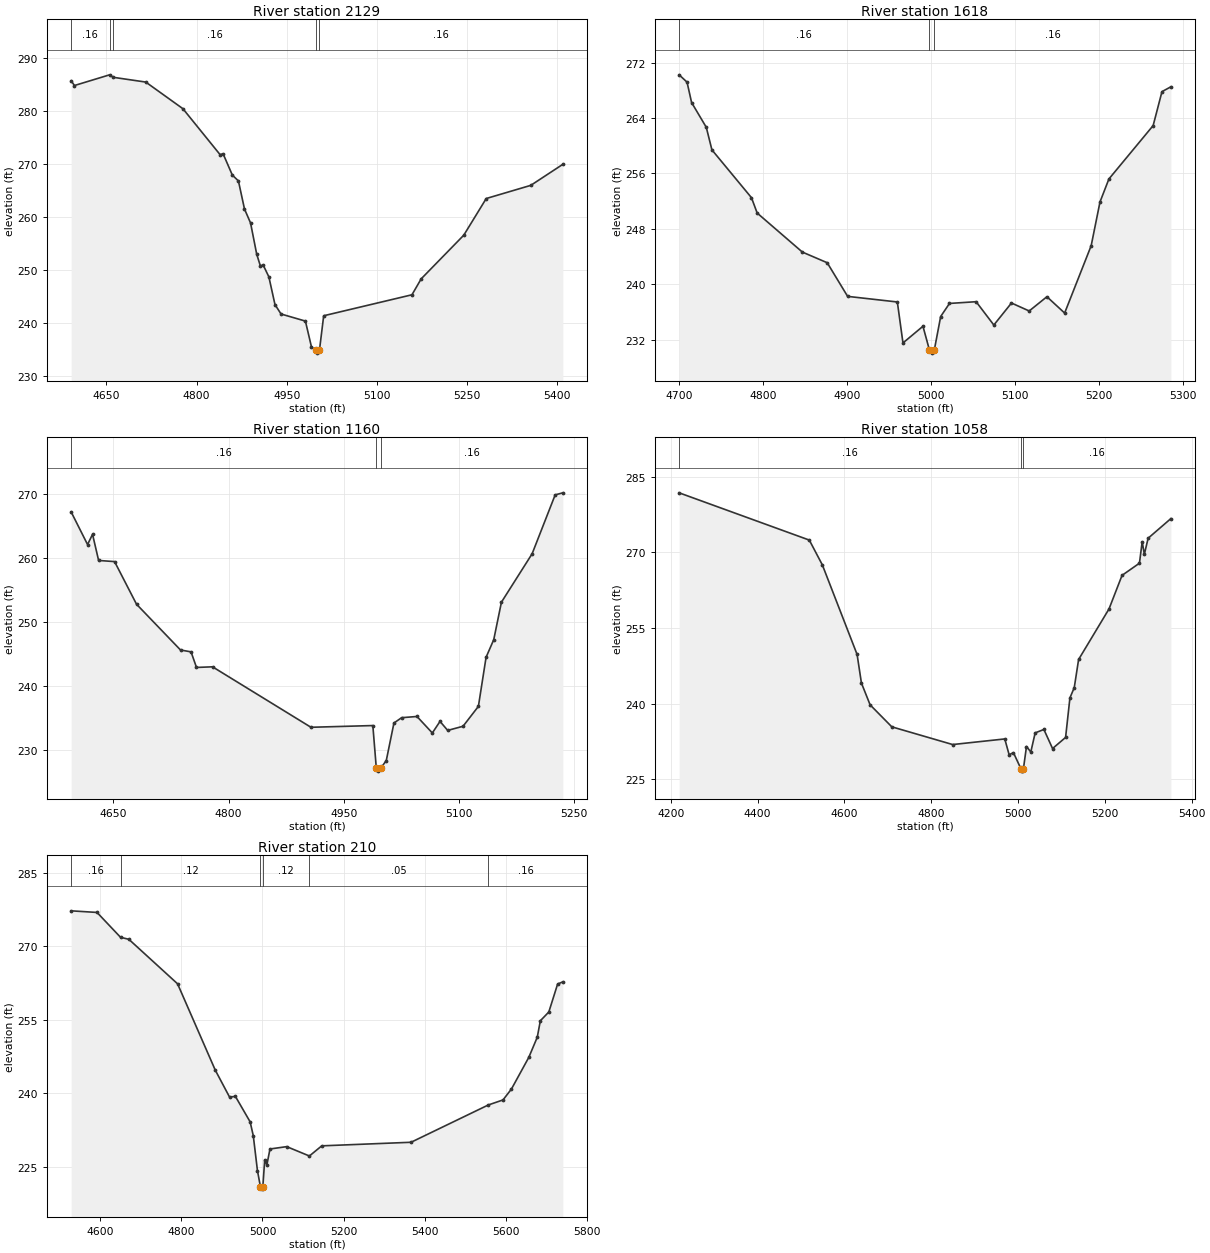
Type RM Length L Ch R = 1,2129,511,511,511
BEGIN DESCRIPTION:
UNT067 IN BECR 4.0
END DESCRIPTION:
XS GIS Cut Line= 2
      3786124.97     10478334.96      3786932.24     10478465.17
#Sta/Elev= 30
  4591.5  285.76  4597.1  284.87  4655.5  286.89  4661.6  286.42  4715.6  285.52
  4777.4  280.48  4839.2  271.79  4844.2  271.96  4859.6  267.92  4869.7  266.82
  4879.8  261.50  4889.9  258.86  4900.1  252.96  4906.0  250.81  4911.1  250.85
  4920.3  248.68  4930.5  243.42  4940.6  241.64  4981.1  240.30  4991.2  235.40
  4998.4  234.74  5001.1  234.24  5004.4  234.74  5011.5  241.31  5158.3  245.28
  5173.6  248.29  5244.5  256.56  5281.8  263.49  5355.9  265.98  5409.2  269.96
#Mann=5,-1,0
  4591.5    0.16       0  4655.5    0.05       0  4661.6    0.16       0
  4998.4    0.07       0  5004.4    0.16       0
Bank Sta=4998.4,5004.4
Exp/Cntr=0.3,0.1

Type RM Length L Ch R = 1,1618,458,458,458
BEGIN DESCRIPTION:
UNT067 IN BECR 3.0
END DESCRIPTION:
XS GIS Cut Line= 3
      3786199.63     10478960.18      3786449.61     10478860.19
      3786749.64     10478960.20
#Sta/Elev= 30
  4700.5  270.25  4709.9  269.19  4715.3  266.25  4732.8  262.67  4739.5  259.41
  4786.6  252.50  4793.4  250.28  4847.2  244.64  4876.8  243.10  4901.1  238.24
  4960.3  237.43  4967.0  231.51  4990.8  233.92  4998.4  230.54  5001.1  230.04
  5004.4  230.54  5011.9  235.33  5022.4  237.22  5054.1  237.47  5075.2  234.10
  5096.2  237.28  5117.3  236.13  5138.4  238.19  5159.5  235.83  5191.1  245.56
  5201.6  251.88  5212.2  255.20  5264.9  262.92  5275.4  267.82  5286.0  268.52
#Mann=3,-1,0
  4700.5    0.16       0  4998.4    0.07       0  5004.4    0.16       0
Bank Sta=4998.4,5004.4
Exp/Cntr=0.3,0.1

Type RM Length L Ch R = 1,1160,102,102,102
BEGIN DESCRIPTION:
UNT067 IN BECR 2.0
END DESCRIPTION:
XS GIS Cut Line= 3
      3786249.64     10479010.21      3786549.61     10479260.19
      3786799.64     10479260.19
#Sta/Elev= 30
  4595.0  267.25  4616.4  262.14  4622.9  263.74  4630.8  259.65  4651.6  259.47
  4680.2  252.80  4737.5  245.64  4751.2  245.35  4758.3  242.91  4779.2  243.01
  4907.4  233.55  4988.0  233.82  4992.5  227.19  4995.2  226.69  4998.5  227.19
  5005.5  228.34  5015.5  234.22  5025.5  235.05  5045.5  235.24  5065.5  232.66
  5075.5  234.47  5085.5  233.06  5105.5  233.71  5125.5  236.82  5135.5  244.50
  5145.5  247.26  5155.5  253.12  5195.5  260.70  5225.5  269.91  5235.5  270.23
#Mann=3,-1,0
  4595.0    0.16       0  4992.5    0.07       0  4998.5    0.16       0
Bank Sta=4992.5,4998.5
Exp/Cntr=0.3,0.1

Type RM Length L Ch R = 1,1058,848,848,848
BEGIN DESCRIPTION:
Mapping XS 69df50b2
END DESCRIPTION:
XS GIS Cut Line= 2
      3785760.02     10479391.02      3786891.98     10479342.41
#Sta/Elev= 30
  4219.1  281.78  4519.0  272.41  4549.0  267.50  4629.1  249.74  4639.1  244.07
  4659.1  239.75  4709.1  235.39  4849.3  231.88  4969.4  232.99  4979.4  229.86
  4989.4  230.27  5006.4  227.11  5009.2  226.61  5012.4  227.11  5019.4  231.49
  5029.4  230.41  5039.4  234.19  5059.5  234.87  5079.5  231.09  5109.5  233.29
  5119.5  241.13  5129.5  243.17  5139.5  248.74  5209.6  258.77  5239.6  265.42
  5279.7  267.83  5286.0  272.09  5291.0  269.60  5299.7  272.78  5352.1  276.67
#Mann=3,-1,0
  4219.1    0.16       0  5006.4    0.07       0  5012.4    0.16       0
Bank Sta=5006.4,5012.4
Exp/Cntr=0.3,0.1

Type RM Length L Ch R = 1,210,0,0,0
BEGIN DESCRIPTION:
UNT067 IN BECR 1.0
END DESCRIPTION:
XS GIS Cut Line= 4
      3785982.20     10479578.51      3786246.09     10479911.86
      3786384.98     10479946.58      3786808.59     10479460.48
#Sta/Elev= 30
  4527.9  277.23  4591.8  276.90  4649.8  271.83  4670.3  271.42  4790.5  262.34
  4883.5  244.73  4918.7  239.24  4933.2  239.37  4969.5  234.18  4977.3  231.35
  4987.6  224.21  4994.9  220.95  4997.7  220.45  5000.9  220.95  5005.5  226.45
  5010.7  225.35  5018.5  228.64  5059.8  229.12  5115.7  227.21  5146.2  229.28
  5366.5  230.01  5557.1  237.62  5593.4  238.65  5614.3  240.89  5657.0  247.33
  5677.9  251.44  5685.5  254.80  5706.4  256.59  5728.1  262.29  5741.0  262.74
#Mann=6,-1,0
  4527.9    0.16       0  4649.8    0.12       0  4994.9    0.07       0
  5000.9    0.12       0  5115.7    0.05       0  5557.1    0.16       0
Bank Sta=4994.9,5000.9
Exp/Cntr=0.3,0.1

Chan Stop Cuts=-1