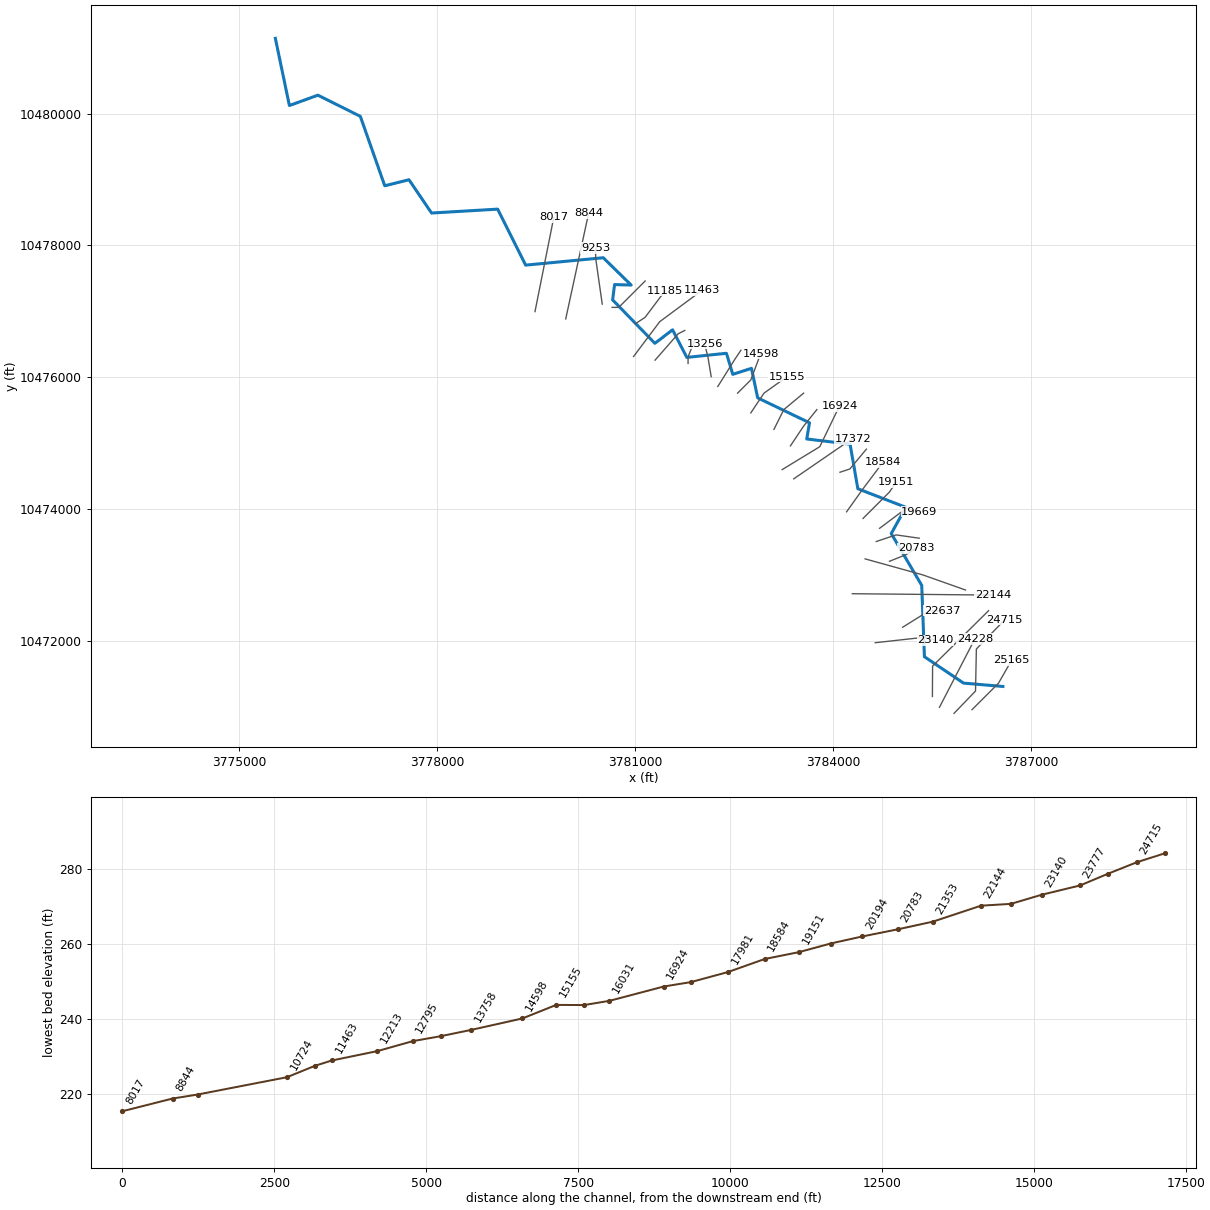
--- UNT068 IN BECR.prj (project) ---

Proj Title=UNT068 IN BECR Base Level Engineering
Current Plan=p01
Default Exp/Contr=0.3,0.1
English Units
Geom File=g01
Flow File=f01
Plan File=p01
BEGIN DESCRIPTION:
UNT068 IN BECR
END DESCRIPTION:

--- UNT068 IN BECR.p01 (plan) ---

Plan Title=Multiple Run
Short Identifier=Multiple
Geom File=g01
Flow File=f01
Subcritical Flow
K Sum by GR= 0
Std Step Tol= 0.01
Critical Tol= 0.01
Num of Std Step Trials= 20
Max Error Tol= 0.3
Flow Tol Ratio= 0.001
Split Flow NTrial= 30
Split Flow Tol= 0.02
Split Flow Ratio= 0.02
Log Output Level= 0
Friction Slope Method= 1
Unsteady Friction Slope Method= 2
Unsteady Bridges Friction Slope Method= 1
Parabolic Critical Depth
Global Vel Dist=  1 , 1 , 1
Global Log Level= 0
CheckData=True
Encroach Param= -1, 0, 0, 0
BEGIN DESCRIPTION:
Multiple Run
END DESCRIPTION:

--- UNT068 IN BECR.f01 (steady flow) ---

Flow Title=Multiple
Number of Profiles=7
Profile Names=10-year,25-year,50-year,1pct_min,100-year,1pct_plu,500-year
River Rch & RM= UNT068 IN BECR,Reach-1,25165
     866    1187    1455    1309    1771    2394    2631
River Rch & RM= UNT068 IN BECR,Reach-1,13256
    1054    1454    1790    1616    2185    2956    3270
River Rch & RM= UNT068 IN BECR,Reach-1,4938
    1246    1734    2146    1947    2633    3560    3978
Boundary for River Rch & Prof#=UNT068 IN BECR,Reach-1,1
Up Type=0
Dn Type=3
Dn Slope=0.005
Boundary for River Rch & Prof#=UNT068 IN BECR,Reach-1,2
Up Type=0
Dn Type=3
Dn Slope=0.005
Boundary for River Rch & Prof#=UNT068 IN BECR,Reach-1,3
Up Type=0
Dn Type=3
Dn Slope=0.005
Boundary for River Rch & Prof#=UNT068 IN BECR,Reach-1,4
Up Type=0
Dn Type=3
Dn Slope=0.005
Boundary for River Rch & Prof#=UNT068 IN BECR,Reach-1,5
Up Type=0
Dn Type=3
Dn Slope=0.005
Boundary for River Rch & Prof#=UNT068 IN BECR,Reach-1,6
Up Type=0
Dn Type=3
Dn Slope=0.005
Boundary for River Rch & Prof#=UNT068 IN BECR,Reach-1,7
Up Type=0
Dn Type=3
Dn Slope=0.005

--- UNT068 IN BECR.g01 (geometry) ---

Geom Title=Existing Conditions

River Reach=UNT068 IN BECR,Reach-1
Reach XY= 30
      3786567.25     10471312.00      3785971.00     10471363.00
      3785378.75     10471763.00      3785337.75     10472845.00
      3784876.50     10473630.00      3785096.75     10474029.00
      3784370.25     10474310.00      3784252.75     10474986.00
      3783596.50     10475065.00      3783638.50     10475310.00
      3782853.75     10475688.00      3782759.75     10476136.00
      3782476.50     10476045.00      3782380.75     10476364.00
      3781780.25     10476302.00      3781564.75     10476720.00
      3781296.75     10476515.00      3780657.00     10477174.00
      3780686.75     10477406.00      3780937.25     10477399.00
      3780515.00     10477813.00      3779339.75     10477701.00
      3778916.00     10478550.00      3777915.00     10478491.00
      3777572.75     10478996.00      3777206.25     10478904.00
      3776836.50     10479957.00      3776194.00     10480278.00
      3775762.25     10480121.00      3775549.50     10481140.00

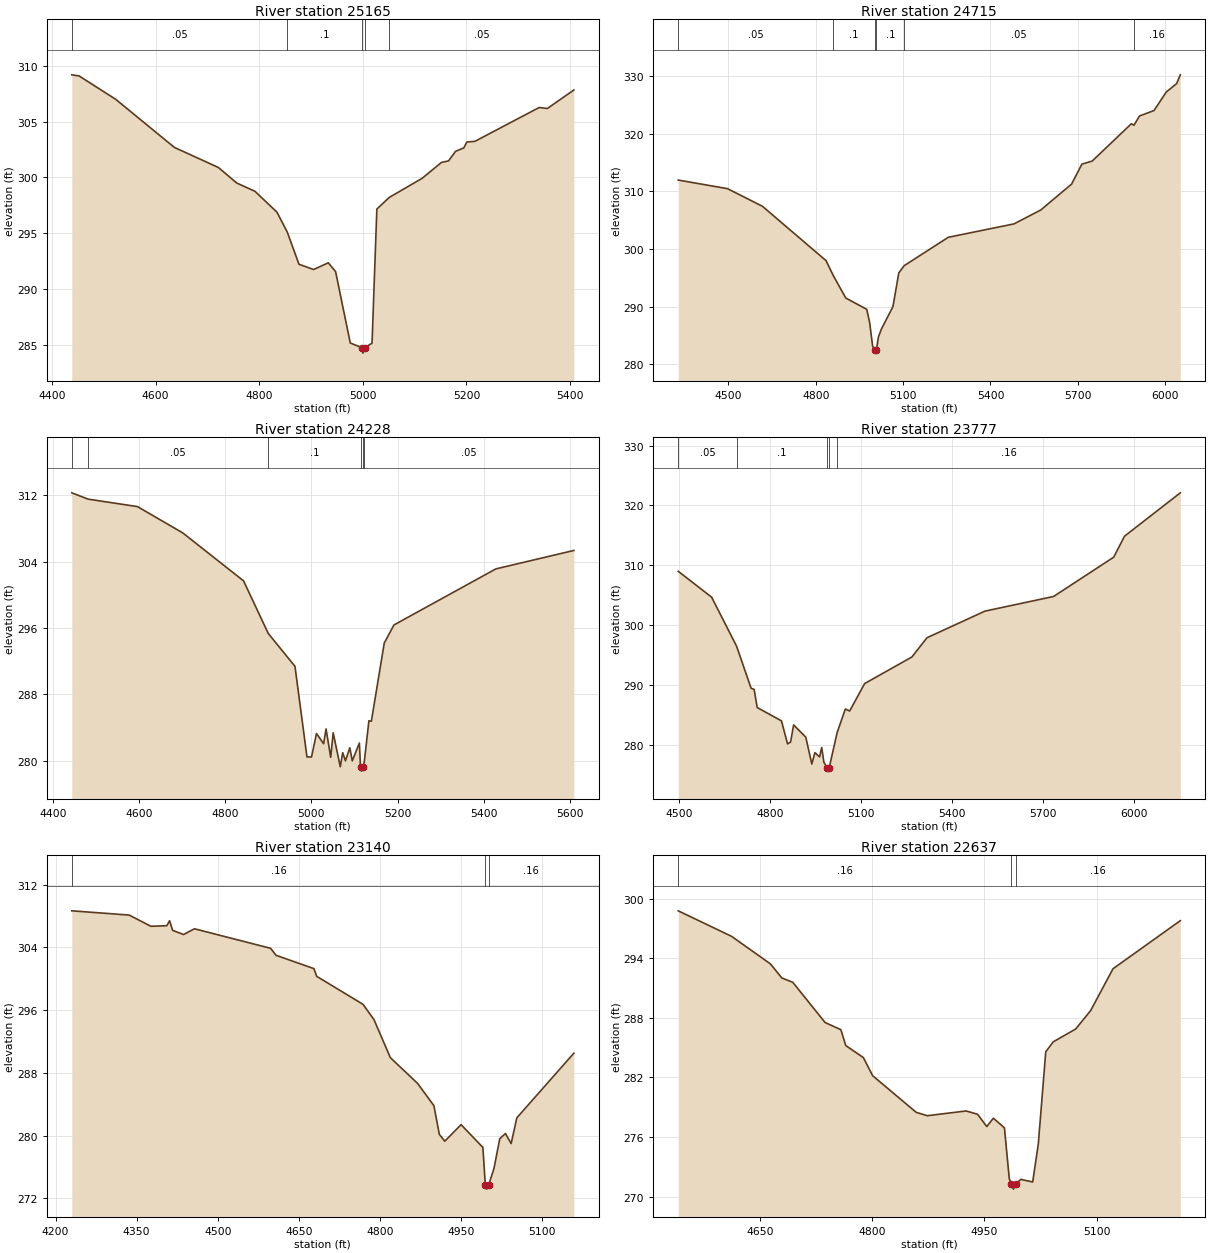
Type RM Length L Ch R = 1,25165,450,450,450
BEGIN DESCRIPTION:
UNT068 IN BECR 40.0
END DESCRIPTION:
XS GIS Cut Line= 3
      3786099.59     10470960.17      3786499.61     10471360.19
      3786699.60     10471710.17
#Sta/Elev= 30
  4438.4  309.19  4452.6  309.09  4523.3  306.99  4636.4  302.68  4721.3  300.88
  4756.6  299.49  4792.0  298.74  4834.4  296.87  4854.3  295.08  4876.8  292.20
  4905.1  291.73  4933.4  292.33  4947.5  291.54  4975.8  285.14  4997.6  284.73
  5000.3  284.23  5003.6  284.73  5017.8  285.12  5027.1  297.15  5051.2  298.20
  5114.2  299.90  5151.7  301.33  5165.4  301.47  5179.0  302.33  5194.9  302.64
  5200.6  303.16  5216.5  303.23  5340.3  306.26  5356.1  306.17  5407.2  307.83
#Mann=5,-1,0
  4438.4    0.05       0  4854.3     0.1       0  4997.6    0.07       0
  5003.6     0.1       0  5051.2    0.05       0
Bank Sta=4997.6,5003.6
Exp/Cntr=0.3,0.1

Type RM Length L Ch R = 1,24715,487,487,487
BEGIN DESCRIPTION:
UNT068 IN BECR 39.0
END DESCRIPTION:
XS GIS Cut Line= 4
      3785826.90     10470903.86      3786152.39     10471242.37
      3786165.41     10471880.39      3786594.88     10472322.88
#Sta/Elev= 30
  4327.6  311.94  4496.7  310.45  4616.8  307.39  4835.0  297.97  4860.6  295.32
  4903.1  291.47  4975.1  289.51  4985.1  287.19  4995.1  283.17  5002.1  282.41
  5004.8  281.91  5008.1  282.41  5015.1  284.69  5025.1  286.06  5065.1  289.99
  5085.1  295.82  5103.5  297.08  5255.1  302.01  5480.6  304.33  5572.6  306.74
  5678.6  311.24  5713.9  314.70  5749.4  315.24  5883.7  321.70  5893.0  321.46
  5911.9  323.06  5961.6  324.00  6004.0  327.23  6039.3  328.67  6052.0  330.20
#Mann=6,-1,0
  4327.6    0.05       0  4860.6     0.1       0  5002.1    0.07       0
  5008.1     0.1       0  5103.5    0.05       0  5893.0    0.16       0
Bank Sta=5002.1,5008.1
Exp/Cntr=0.3,0.1

Type RM Length L Ch R = 1,24228,451,451,451
BEGIN DESCRIPTION:
UNT068 IN BECR 38.0
END DESCRIPTION:
XS GIS Cut Line= 2
      3785606.38     10470996.19      3786141.09     10472030.89
#Sta/Elev= 30
  4444.2  312.27  4482.2  311.51  4596.7  310.61  4701.8  307.44  4842.7  301.67
  4900.1  295.33  4962.0  291.38  4989.8  280.47  5000.3  280.46  5011.9  283.29
  5028.4  282.06  5034.1  283.84  5044.9  280.42  5050.6  283.38  5067.1  279.29
  5072.7  280.98  5079.1  280.00  5089.2  281.57  5094.9  279.99  5111.4  282.14
  5114.0  279.26  5116.8  278.76  5120.0  279.26  5122.8  279.90  5133.5  284.82
  5139.2  284.77  5169.1  294.18  5191.6  296.36  5428.0  303.11  5608.9  305.33
#Mann=6,-1,0
  4444.2    0.07       0  4482.2    0.05       0  4900.1     0.1       0
  5114.0    0.07       0  5120.0     0.1       0  5122.8    0.05       0
Bank Sta=5114,5120
Exp/Cntr=0.3,0.1

Type RM Length L Ch R = 1,23777,637,637,637
BEGIN DESCRIPTION:
UNT068 IN BECR 37.0
END DESCRIPTION:
XS GIS Cut Line= 3
      3785499.61     10471160.24      3785502.21     10471621.19
      3786349.58     10472460.16
#Sta/Elev= 30
  4497.6  309.02  4607.6  304.70  4689.7  296.53  4737.6  289.50  4747.6  289.31
  4757.6  286.29  4837.6  284.06  4857.6  280.22  4867.6  280.53  4877.6  283.39
  4917.6  281.35  4937.6  276.86  4947.6  278.76  4963.1  278.06  4970.1  279.62
  4977.2  277.17  4988.4  276.18  4991.1  275.68  4994.4  276.18  5021.0  282.13
  5047.9  286.04  5062.1  285.71  5111.5  290.29  5267.1  294.72  5316.7  297.93
  5507.5  302.37  5733.8  304.82  5931.8  311.38  5967.2  314.87  6151.0  322.11
#Mann=5,-1,0
  4497.6    0.05       0  4689.7     0.1       0  4988.4    0.07       0
  4994.4     0.1       0  5021.0    0.16       0
Bank Sta=4988.4,4994.4
Exp/Cntr=0.3,0.1

Type RM Length L Ch R = 1,23140,503,503,503
BEGIN DESCRIPTION:
UNT068 IN BECR 36.0
END DESCRIPTION:
XS GIS Cut Line= 3
      3784634.20     10471975.36      3785399.61     10472060.19
      3785549.60     10472010.19
#Sta/Elev= 30
  4230.0  308.65  4336.1  308.11  4376.3  306.68  4405.7  306.75  4410.8  307.39
  4416.5  306.16  4436.7  305.63  4456.8  306.36  4597.6  303.87  4607.7  302.98
  4677.7  301.28  4682.8  300.30  4768.4  296.73  4788.8  294.77  4819.0  289.93
  4869.3  286.65  4899.5  283.81  4909.5  280.16  4919.6  279.28  4949.7  281.39
  4990.0  278.49  4994.6  273.67  4997.3  273.17  5000.6  273.67  5010.6  275.82
  5021.2  279.59  5031.7  280.26  5042.3  278.98  5052.8  282.26  5158.2  290.50
#Mann=3,-1,0
  4230.0    0.16       0  4994.6    0.07       0  5000.6    0.16       0
Bank Sta=4994.6,5000.6
Exp/Cntr=0.3,0.1

Type RM Length L Ch R = 1,22637,493,493,493
BEGIN DESCRIPTION:
UNT068 IN BECR 35.0
END DESCRIPTION:
XS GIS Cut Line= 3
      3785049.57     10472210.17      3785449.61     10472460.19
      3785649.57     10472460.19
#Sta/Elev= 30
  4540.4  298.77  4611.8  296.20  4663.7  293.43  4679.0  292.01  4693.7  291.57
  4736.8  287.53  4758.0  286.80  4764.5  285.21  4788.1  283.99  4800.5  282.17
  4858.8  278.48  4873.6  278.14  4925.5  278.62  4940.8  278.29  4953.2  277.05
  4962.0  277.89  4976.8  276.92  4983.3  271.79  4986.1  271.25  4988.9  270.75
  4992.1  271.25  4998.6  271.73  5014.6  271.47  5022.1  275.28  5032.1  284.58
  5042.1  285.58  5072.1  286.87  5092.1  288.72  5122.1  292.94  5212.1  297.78
#Mann=3,-1,0
  4540.4    0.16       0  4986.1    0.07       0  4992.1    0.16       0
Bank Sta=4986.1,4992.1
Exp/Cntr=0.3,0.1

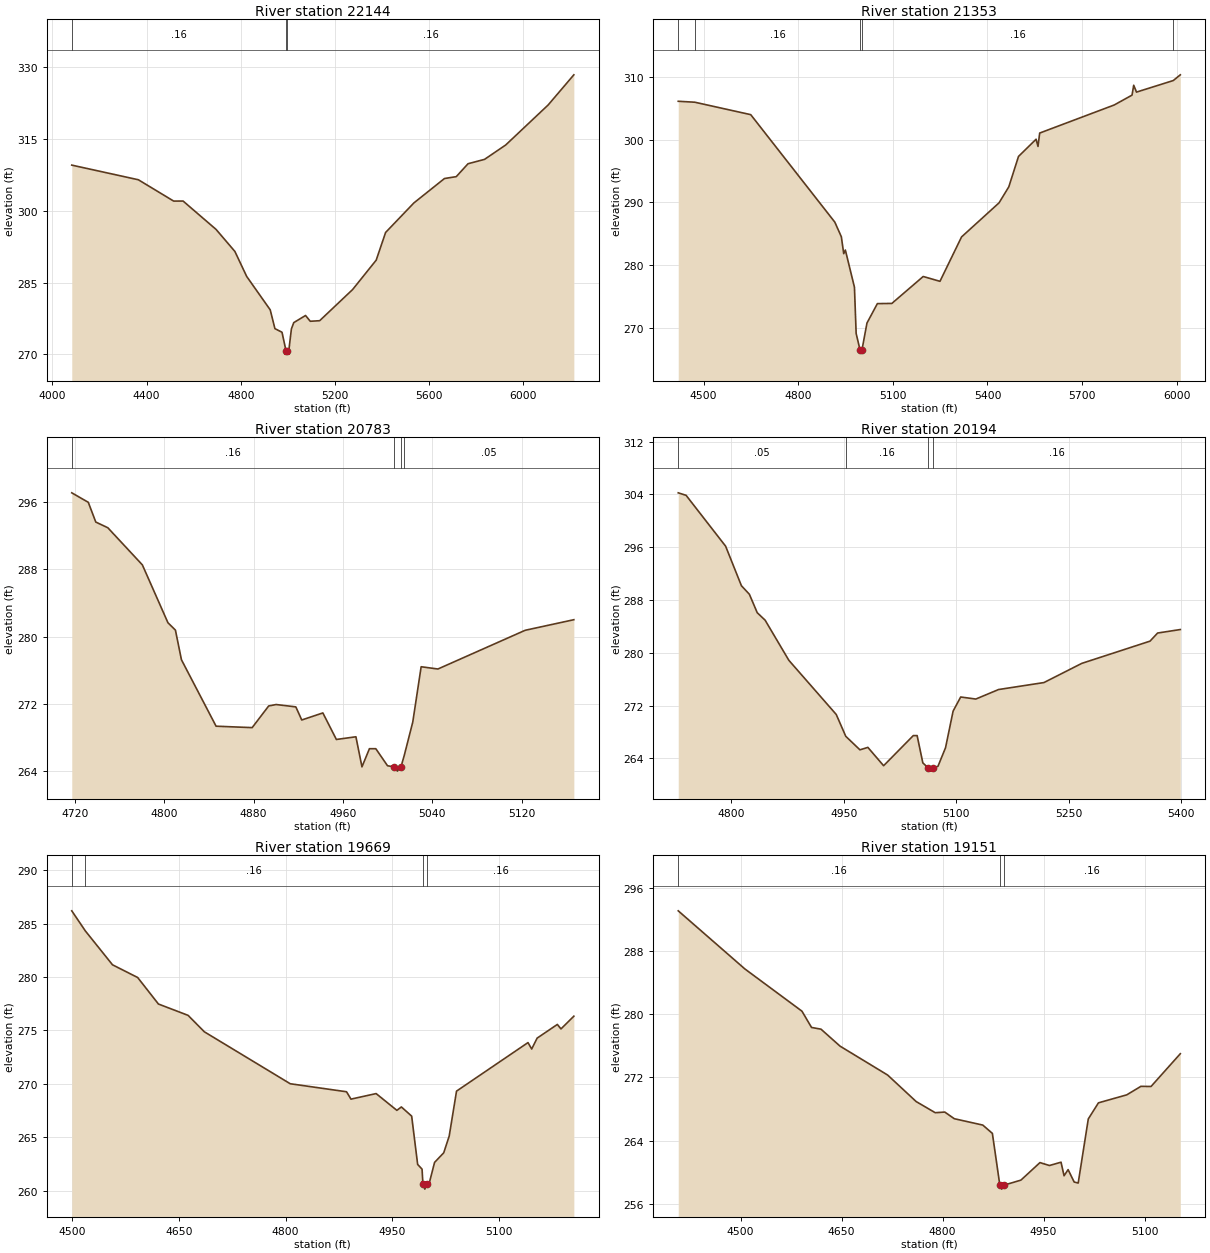
Type RM Length L Ch R = 1,22144,791,791,791
BEGIN DESCRIPTION:
UNT068 IN BECR 34.0
END DESCRIPTION:
XS GIS Cut Line= 2
      3784286.95     10472718.41      3786418.85     10472697.58
#Sta/Elev= 30
  4081.9  309.57  4364.6  306.51  4514.6  302.05  4554.6  302.06  4694.6  296.13
  4774.6  291.52  4824.6  286.30  4924.6  279.31  4944.6  275.38  4974.6  274.63
  4991.6  270.76  4994.4  270.26  4997.6  270.76  5004.6  271.23  5014.6  275.33
  5024.6  276.64  5074.6  278.13  5094.6  276.92  5134.6  277.04  5274.6  283.56
  5374.6  289.70  5414.6  295.49  5534.6  301.66  5664.6  306.77  5714.6  307.16
  5764.6  309.86  5834.6  310.77  5924.6  313.78  6104.7  322.14  6213.9  328.45
#Mann=3,-1,0
  4081.9    0.16       0  4991.6    0.07       0  4997.6    0.16       0
Bank Sta=4991.6,4997.6
Exp/Cntr=0.3,0.1

Type RM Length L Ch R = 1,21353,570,570,570
BEGIN DESCRIPTION:
UNT068 IN BECR 33.0
END DESCRIPTION:
XS GIS Cut Line= 3
      3784481.35     10473246.20      3785356.38     10473003.13
      3786000.47     10472774.59
#Sta/Elev= 30
  4419.8  306.09  4472.3  305.94  4649.6  303.96  4916.2  286.85  4936.9  284.52
  4944.4  281.83  4949.6  282.41  4978.4  276.49  4983.8  269.13  4996.2  266.50
  4998.9  266.00  5002.2  266.50  5018.1  270.79  5051.1  273.88  5097.0  273.91
  5196.4  278.20  5249.5  277.43  5318.0  284.50  5436.8  289.92  5467.7  292.47
  5498.5  297.31  5554.2  300.05  5560.3  298.90  5565.6  301.03  5801.9  305.50
  5858.4  307.07  5863.7  308.64  5872.5  307.55  5989.1  309.39  6011.4  310.30
#Mann=5,-1,0
  4419.8    0.05       0  4472.3    0.16       0  4996.2    0.07       0
  5002.2    0.16       0  5989.1    0.05       0
Bank Sta=4996.2,5002.2
Exp/Cntr=0.3,0.1

Type RM Length L Ch R = 1,20783,589,589,589
BEGIN DESCRIPTION:
UNT068 IN BECR 32.0
END DESCRIPTION:
XS GIS Cut Line= 3
      3784849.65     10473210.21      3785099.61     10473310.19
      3785249.62     10473410.19
#Sta/Elev= 30
  4717.2  297.11  4732.0  295.98  4738.7  293.63  4749.5  292.95  4780.4  288.53
  4803.3  281.64  4810.0  280.76  4815.4  277.23  4846.4  269.32  4878.7  269.15
  4893.5  271.73  4900.2  271.90  4917.8  271.62  4923.1  270.06  4942.0  270.90
  4954.1  267.74  4971.6  268.06  4977.0  264.48  4983.7  266.64  4989.4  266.64
  4999.9  264.61  5005.9  264.47  5008.7  263.97  5011.9  264.47  5014.8  265.80
  5022.5  269.82  5030.0  276.40  5045.0  276.13  5123.1  280.74  5166.7  282.00
#Mann=4,-1,0
  4717.2    0.16       0  5005.9    0.07       0  5011.9    0.16       0
  5014.8    0.05       0
Bank Sta=5005.9,5011.9
Exp/Cntr=0.3,0.1

Type RM Length L Ch R = 1,20194,525,525,525
BEGIN DESCRIPTION:
UNT068 IN BECR 31.0
END DESCRIPTION:
XS GIS Cut Line= 3
      3784649.62     10473510.19      3784949.61     10473610.19
      3785299.64     10473560.18
#Sta/Elev= 30
  4729.0  304.25  4739.5  303.87  4792.2  296.16  4813.3  290.16  4823.9  288.87
  4834.4  286.07  4844.9  284.94  4876.6  278.85  4939.8  270.64  4952.5  267.33
  4971.4  265.28  4982.0  265.65  5003.0  262.87  5042.6  267.44  5047.7  267.44
  5055.3  263.30  5062.4  262.55  5065.2  262.05  5068.4  262.55  5075.5  262.78
  5085.6  265.60  5095.7  271.15  5105.8  273.29  5126.0  272.98  5156.3  274.42
  5216.9  275.48  5267.4  278.39  5358.4  281.76  5368.5  282.99  5398.8  283.52
#Mann=4,-1,0
  4729.0    0.05       0  4952.5    0.16       0  5062.4    0.07       0
  5068.4    0.16       0
Bank Sta=5062.4,5068.4
Exp/Cntr=0.3,0.1

Type RM Length L Ch R = 1,19669,518,518,518
BEGIN DESCRIPTION:
UNT068 IN BECR 30.0
END DESCRIPTION:
XS GIS Cut Line= 3
      3784699.60     10473710.18      3785099.61     10474010.19
      3785299.64     10473960.18
#Sta/Elev= 30
  4499.2  286.19  4518.3  284.31  4556.5  281.14  4591.9  279.95  4621.1  277.47
  4662.8  276.41  4685.7  274.87  4806.5  270.01  4885.7  269.26  4891.9  268.57
  4927.3  269.09  4956.5  267.52  4962.8  267.84  4977.3  266.98  4985.7  262.46
  4991.9  262.02  4993.1  260.65  4995.8  260.15  4999.1  260.65  5001.8  260.65
  5009.5  262.65  5022.4  263.55  5030.1  265.12  5040.4  269.32  5140.9  273.86
  5146.1  273.26  5153.8  274.28  5182.2  275.56  5187.3  275.14  5205.4  276.33
#Mann=4,-1,0
  4499.2    0.05       0  4518.3    0.16       0  4993.1    0.07       0
  4999.1    0.16       0
Bank Sta=4993.1,4999.1
Exp/Cntr=0.3,0.1

Type RM Length L Ch R = 1,19151,567,567,567
BEGIN DESCRIPTION:
UNT068 IN BECR 29.0
END DESCRIPTION:
XS GIS Cut Line= 3
      3784449.62     10473860.20      3784849.61     10474260.19
      3784949.58     10474410.15
#Sta/Elev= 30
  4407.3  293.11  4506.3  285.75  4591.1  280.40  4605.3  278.34  4619.4  278.12
  4647.7  275.97  4718.4  272.31  4760.8  268.95  4789.1  267.54  4803.3  267.62
  4817.4  266.78  4859.8  265.97  4874.0  264.92  4885.1  258.36  4887.9  257.86
  4891.1  258.36  4916.4  259.00  4944.7  261.22  4958.8  260.85  4976.0  261.27
  4980.5  259.55  4986.5  260.33  4995.5  258.76  5001.5  258.63  5016.5  266.75
  5031.6  268.79  5073.6  269.80  5094.7  270.88  5109.7  270.86  5153.2  275.01
#Mann=3,-1,0
  4407.3    0.16       0  4885.1    0.07       0  4891.1    0.16       0
Bank Sta=4885.1,4891.1
Exp/Cntr=0.3,0.1

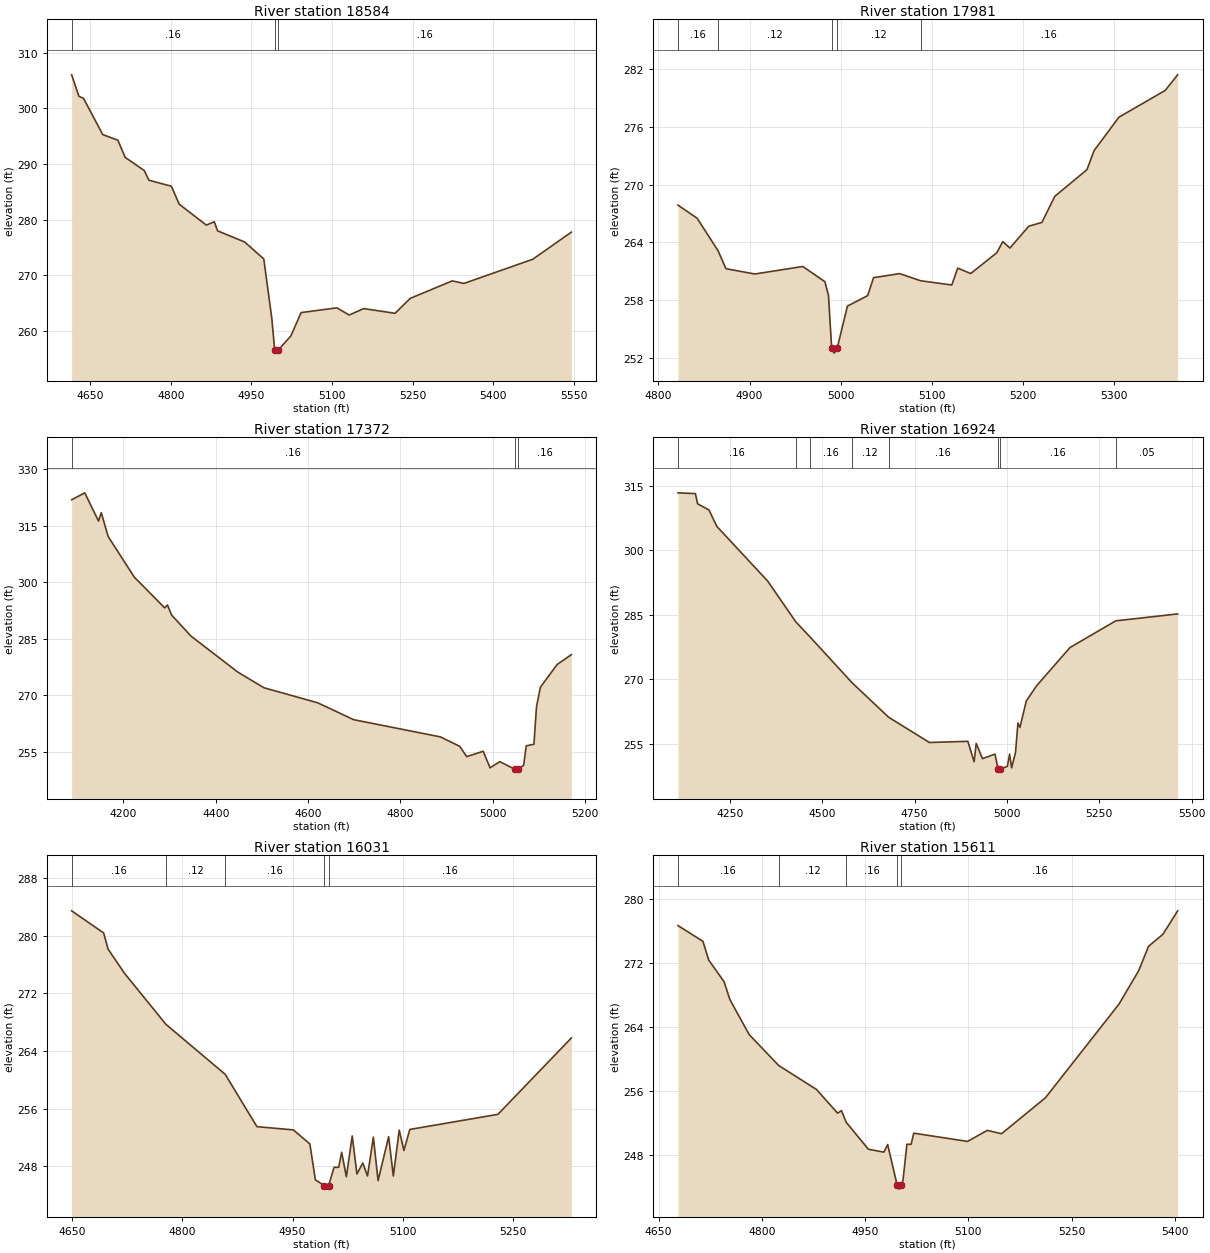
Type RM Length L Ch R = 1,18584,603,603,603
BEGIN DESCRIPTION:
UNT068 IN BECR 28.0
END DESCRIPTION:
XS GIS Cut Line= 3
      3784199.60     10473960.18      3784449.61     10474310.19
      3784749.59     10474710.16
#Sta/Elev= 30
  4615.4  306.05  4628.9  302.19  4637.5  301.82  4673.2  295.31  4701.4  294.30
  4715.0  291.21  4750.6  288.84  4759.2  287.10  4801.0  286.02  4815.7  282.78
  4866.1  279.03  4880.9  279.63  4887.0  278.00  4937.4  275.99  4973.0  272.95
  4987.8  262.38  4993.4  256.51  4996.1  256.01  4999.4  256.51  5023.4  259.10
  5042.5  263.30  5109.1  264.15  5132.0  262.86  5159.1  264.02  5217.4  263.17
  5245.5  265.85  5323.7  269.00  5345.5  268.54  5473.7  272.89  5545.5  277.77
#Mann=3,-1,0
  4615.4    0.16       0  4993.4    0.07       0  4999.4    0.16       0
Bank Sta=4993.4,4999.4
Exp/Cntr=0.3,0.1

Type RM Length L Ch R = 1,17981,609,609,609
BEGIN DESCRIPTION:
UNT068 IN BECR 27.0
END DESCRIPTION:
XS GIS Cut Line= 3
      3784099.57     10474560.18      3784249.61     10474610.19
      3784499.63     10474910.21
#Sta/Elev= 30
  4821.4  267.87  4842.5  266.51  4865.6  263.12  4874.1  261.28  4905.8  260.73
  4958.5  261.51  4982.8  259.93  4986.7  258.51  4990.2  253.03  4993.0  252.53
  4996.2  253.03  5007.5  257.40  5029.7  258.49  5036.2  260.35  5064.8  260.77
  5087.9  260.03  5122.1  259.59  5128.6  261.34  5142.9  260.78  5171.6  262.94
  5178.1  264.09  5185.9  263.42  5206.7  265.69  5221.0  266.07  5235.3  268.79
  5270.5  271.54  5278.3  273.51  5305.6  276.98  5356.4  279.75  5370.1  281.37
#Mann=5,-1,0
  4821.4    0.16       0  4865.6    0.12       0  4990.2    0.07       0
  4996.2    0.12       0  5087.9    0.16       0
Bank Sta=4990.2,4996.2
Exp/Cntr=0.3,0.1

Type RM Length L Ch R = 1,17372,448,448,448
BEGIN DESCRIPTION:
UNT068 IN BECR 26.0
END DESCRIPTION:
XS GIS Cut Line= 3
      3783399.64     10474460.21      3784199.61     10475010.19
      3784299.62     10475060.20
#Sta/Elev= 30
  4087.8  321.94  4116.2  323.78  4146.0  316.29  4152.0  318.50  4166.9  312.17
  4223.7  301.36  4289.4  293.22  4295.4  293.99  4304.3  291.32  4346.2  285.74
  4447.7  276.16  4504.5  271.99  4620.9  268.00  4698.7  263.52  4886.8  258.94
  4928.7  256.43  4943.6  253.70  4979.4  255.13  4994.3  250.73  5015.3  252.37
  5048.1  250.35  5050.9  249.85  5054.1  250.35  5067.0  251.38  5072.6  256.56
  5089.3  257.00  5094.9  266.99  5103.3  272.15  5139.6  278.18  5170.4  280.79
#Mann=3,-1,0
  4087.8    0.16       0  5048.1    0.07       0  5054.1    0.16       0
Bank Sta=5048.1,5054.1
Exp/Cntr=0.3,0.1

Type RM Length L Ch R = 1,16924,893,893,893
BEGIN DESCRIPTION:
UNT068 IN BECR 25.0
END DESCRIPTION:
XS GIS Cut Line= 3
      3783224.47     10474600.38      3783793.88     10474947.58
      3784092.39     10475565.43
#Sta/Elev= 30
  4109.1  313.38  4156.4  313.20  4162.3  310.84  4193.2  309.38  4214.5  305.57
  4352.0  292.87  4428.4  283.36  4467.5  279.80  4580.6  269.22  4679.5  261.20
  4790.0  255.32  4894.1  255.59  4911.1  250.84  4916.7  255.09  4933.7  251.57
  4967.7  252.62  4975.8  249.16  4978.6  248.66  4981.8  249.16  5001.0  249.76
  5007.1  252.60  5012.6  249.42  5023.2  253.02  5029.7  259.86  5035.2  258.84
  5052.3  264.97  5080.4  268.53  5170.8  277.41  5294.6  283.61  5462.2  285.22
#Mann=8,-1,0
  4109.1    0.16       0  4428.4    0.12       0  4467.5    0.16       0
  4580.6    0.12       0  4679.5    0.16       0  4975.8    0.07       0
  4981.8    0.16       0  5294.6    0.05       0
Bank Sta=4975.8,4981.8
Exp/Cntr=0.3,0.1

Type RM Length L Ch R = 1,16031,420,420,420
BEGIN DESCRIPTION:
UNT068 IN BECR 24.0
END DESCRIPTION:
XS GIS Cut Line= 3
      3783349.61     10474960.19      3783549.61     10475260.19
      3783749.60     10475510.18
#Sta/Elev= 30
  4649.1  283.46  4692.7  280.39  4698.7  278.15  4721.2  274.78  4777.6  267.70
  4858.2  260.78  4901.5  253.51  4951.1  253.06  4973.6  251.11  4981.1  246.13
  4993.1  245.34  4995.9  244.84  4999.1  245.34  5006.6  247.87  5012.9  247.87
  5016.9  249.96  5023.3  246.55  5031.3  252.22  5037.7  246.94  5045.7  248.47
  5052.1  246.66  5060.1  252.05  5066.5  246.02  5080.9  252.11  5087.3  246.66
  5095.3  253.03  5101.7  250.20  5109.7  253.12  5229.8  255.22  5329.8  265.82
#Mann=5,-1,0
  4649.1    0.16       0  4777.6    0.12       0  4858.2    0.16       0
  4993.1    0.07       0  4999.1    0.16       0
Bank Sta=4993.1,4999.1
Exp/Cntr=0.3,0.1

Type RM Length L Ch R = 1,15611,456,456,456
BEGIN DESCRIPTION:
UNT068 IN BECR 23.0
END DESCRIPTION:
XS GIS Cut Line= 3
      3783099.60     10475210.18      3783249.61     10475510.19
      3783549.58     10475760.17
#Sta/Elev= 30
  4678.2  276.64  4714.5  274.67  4722.9  272.33  4745.3  269.61  4753.7  267.39
  4781.6  263.03  4824.5  259.16  4879.5  256.16  4910.2  253.20  4915.8  253.52
  4922.5  252.08  4954.9  248.69  4977.3  248.33  4982.9  249.28  4996.6  244.21
  4999.4  243.71  5002.6  244.21  5005.2  244.87  5010.8  249.31  5016.9  249.31
  5020.8  250.70  5098.9  249.67  5127.5  251.05  5148.3  250.63  5212.1  255.13
  5318.9  266.83  5347.5  271.00  5361.8  274.05  5382.7  275.55  5404.1  278.48
#Mann=5,-1,0
  4678.2    0.16       0  4824.5    0.12       0  4922.5    0.16       0
  4996.6    0.07       0  5002.6    0.16       0
Bank Sta=4996.6,5002.6
Exp/Cntr=0.3,0.1

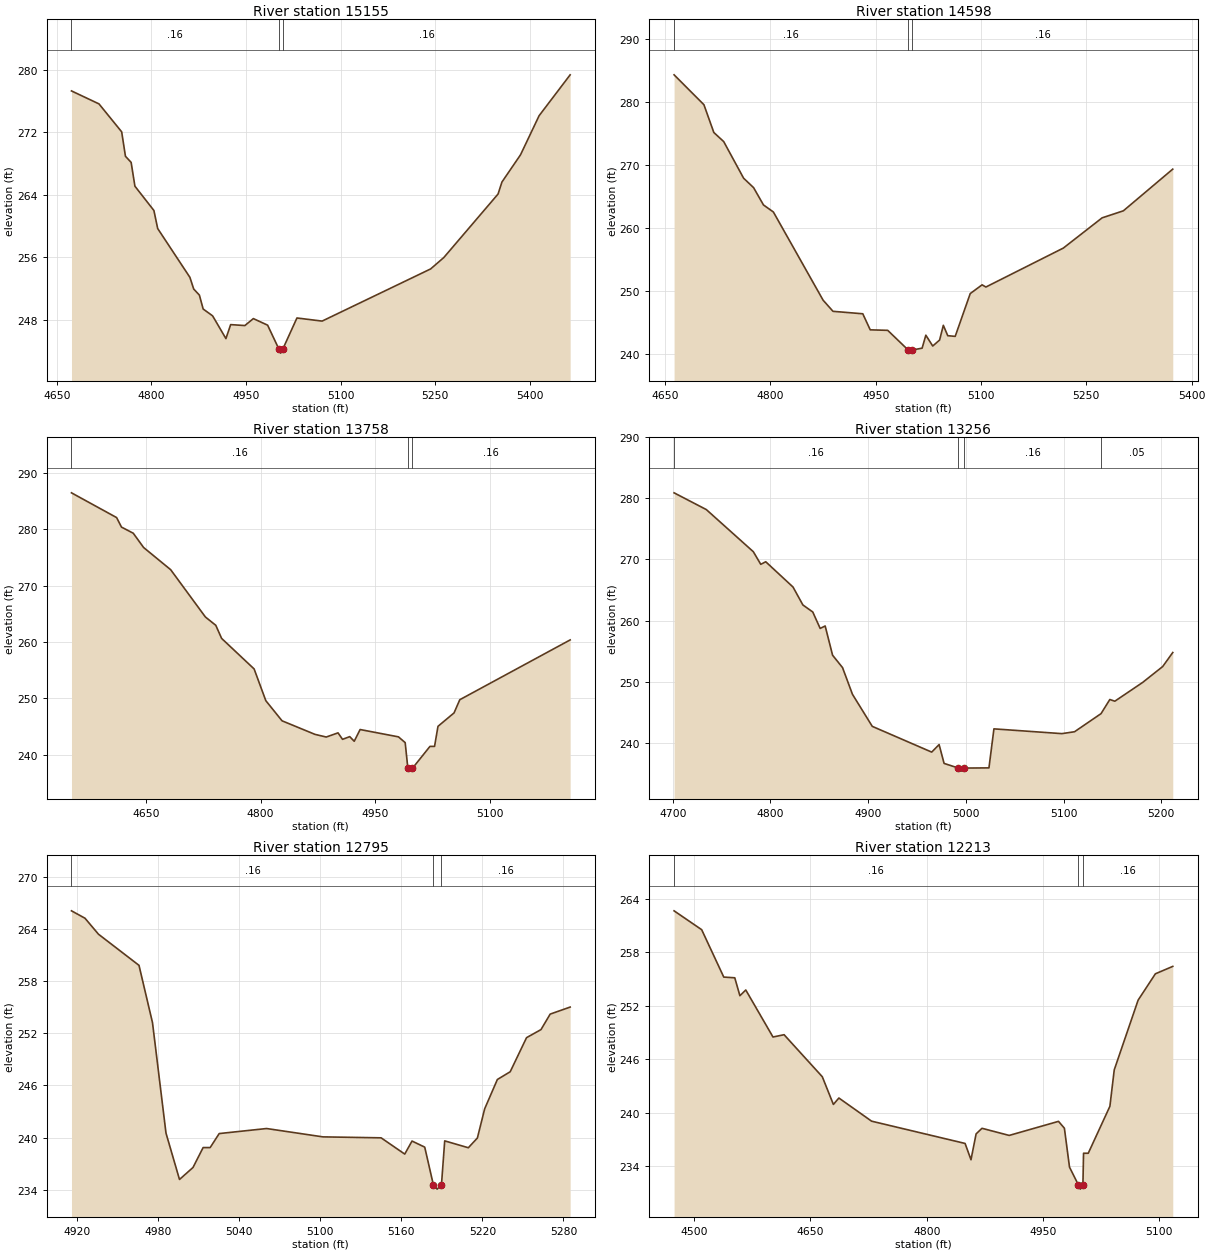
Type RM Length L Ch R = 1,15155,557,557,557
BEGIN DESCRIPTION:
UNT068 IN BECR 22.0
END DESCRIPTION:
XS GIS Cut Line= 3
      3782749.61     10475460.20      3782949.61     10475760.19
      3783299.64     10476010.21
#Sta/Elev= 30
  4673.2  277.32  4716.8  275.66  4752.8  272.08  4758.8  268.95  4767.8  268.17
  4773.8  265.12  4803.9  262.01  4809.9  259.70  4861.0  253.45  4867.0  251.96
  4876.0  251.18  4882.0  249.40  4897.0  248.52  4918.1  245.61  4925.6  247.40
  4948.1  247.28  4961.6  248.17  4984.2  247.33  5002.2  244.25  5005.0  243.75
  5008.2  244.25  5030.7  248.25  5070.6  247.85  5242.7  254.53  5263.6  255.99
  5349.6  264.12  5355.7  265.65  5385.2  269.14  5414.7  274.15  5463.9  279.38
#Mann=3,-1,0
  4673.2    0.16       0  5002.2    0.07       0  5008.2    0.16       0
Bank Sta=5002.2,5008.2
Exp/Cntr=0.3,0.1

Type RM Length L Ch R = 1,14598,840,840,840
BEGIN DESCRIPTION:
UNT068 IN BECR 21.0
END DESCRIPTION:
XS GIS Cut Line= 3
      3782549.59     10475760.17      3782749.61     10475960.19
      3782899.62     10476360.22
#Sta/Elev= 30
  4663.0  284.34  4705.5  279.59  4719.6  275.18  4733.7  273.73  4762.0  267.92
  4776.2  266.42  4790.3  263.67  4804.4  262.55  4875.2  248.54  4889.3  246.77
  4931.7  246.38  4942.3  243.83  4967.2  243.75  4996.3  240.63  4999.0  240.13
  5002.3  240.63  5016.2  240.92  5021.5  242.98  5031.3  241.26  5041.1  242.21
  5046.4  244.55  5052.7  242.90  5063.3  242.79  5084.7  249.59  5101.6  250.98
  5107.0  250.63  5217.3  256.82  5272.5  261.62  5302.8  262.74  5373.1  269.36
#Mann=3,-1,0
  4663.0    0.16       0  4996.3    0.07       0  5002.3    0.16       0
Bank Sta=4996.3,5002.3
Exp/Cntr=0.3,0.1

Type RM Length L Ch R = 1,13758,502,502,502
BEGIN DESCRIPTION:
UNT068 IN BECR 20.0
END DESCRIPTION:
XS GIS Cut Line= 3
      3782249.61     10475860.19      3782499.61     10476260.19
      3782599.63     10476410.21
#Sta/Elev= 30
  4552.8  286.46  4611.8  282.07  4618.2  280.38  4633.6  279.29  4647.1  276.76
  4682.5  272.82  4727.9  264.43  4741.5  262.95  4749.1  260.63  4791.6  255.21
  4806.9  249.58  4828.1  246.01  4871.2  243.60  4885.9  243.13  4901.3  243.87
  4907.2  242.72  4916.6  243.20  4922.5  242.38  4930.2  244.46  4980.3  243.16
  4989.1  242.14  4992.6  237.58  4995.4  237.08  4998.6  237.58  5021.5  241.47
  5027.5  241.47  5032.0  245.03  5053.0  247.41  5060.5  249.75  5204.8  260.36
#Mann=3,-1,0
  4552.8    0.16       0  4992.6    0.07       0  4998.6    0.16       0
Bank Sta=4992.6,4998.6
Exp/Cntr=0.3,0.1

Type RM Length L Ch R = 1,13256,461,461,461
BEGIN DESCRIPTION:
UNT068 IN BECR 19.0
END DESCRIPTION:
XS GIS Cut Line= 3
      3782149.61     10476010.18      3782099.61     10476310.19
      3782049.61     10476510.18
#Sta/Elev= 30
  4701.4  280.90  4734.4  278.16  4782.5  271.27  4790.1  269.21  4795.2  269.63
  4823.1  265.50  4833.2  262.57  4843.3  261.42  4850.9  258.73  4856.0  259.13
  4863.6  254.35  4873.8  252.32  4883.9  247.97  4904.2  242.72  4965.0  238.51
  4972.6  239.74  4977.7  236.66  4992.4  235.90  4995.2  235.40  4998.4  235.90
  5023.6  235.93  5028.7  242.31  5098.3  241.53  5111.2  241.84  5138.3  244.80
  5147.3  247.11  5152.4  246.83  5180.8  249.89  5201.4  252.50  5211.7  254.79
#Mann=4,-1,0
  4701.4    0.16       0  4992.4    0.07       0  4998.4    0.16       0
  5138.3    0.05       0
Bank Sta=4992.4,4998.4
Exp/Cntr=0.3,0.1

Type RM Length L Ch R = 1,12795,582,582,582
BEGIN DESCRIPTION:
UNT068 IN BECR 18.0
END DESCRIPTION:
XS GIS Cut Line= 3
      3781799.61     10476210.17      3781799.61     10476310.19
      3781899.62     10476560.21
#Sta/Elev= 30
  4915.7  266.08  4925.7  265.23  4935.7  263.39  4965.7  259.81  4975.7  253.22
  4985.7  240.51  4995.7  235.18  5005.7  236.56  5013.2  238.85  5018.4  238.85
  5025.1  240.46  5060.2  241.04  5101.9  240.08  5145.0  239.97  5162.5  238.10
  5167.9  239.60  5177.3  238.90  5183.7  234.57  5186.5  234.07  5189.7  234.57
  5192.1  239.62  5209.6  238.83  5216.3  239.95  5221.7  243.31  5231.1  246.68
  5240.6  247.57  5252.7  251.49  5263.4  252.42  5270.2  254.20  5285.0  255.01
#Mann=3,-1,0
  4915.7    0.16       0  5183.7    0.07       0  5189.7    0.16       0
Bank Sta=5183.7,5189.7
Exp/Cntr=0.3,0.1

Type RM Length L Ch R = 1,12213,750,750,750
BEGIN DESCRIPTION:
UNT068 IN BECR 17.0
END DESCRIPTION:
XS GIS Cut Line= 3
      3781299.62     10476260.20      3781649.61     10476660.19
      3781749.61     10476710.19
#Sta/Elev= 30
  4474.1  262.66  4509.7  260.54  4538.2  255.22  4552.4  255.14  4559.0  253.13
  4566.6  253.77  4601.7  248.49  4616.0  248.75  4665.3  244.03  4679.6  240.92
  4686.7  241.64  4728.9  239.04  4849.5  236.54  4857.1  234.71  4863.7  237.61
  4871.3  238.24  4906.4  237.44  4970.0  239.02  4977.6  238.25  4984.2  233.88
  4995.5  231.91  4998.2  231.41  5001.5  231.91  5002.3  235.44  5008.4  235.44
  5036.3  240.71  5041.9  244.80  5072.7  252.63  5095.0  255.59  5117.4  256.42
#Mann=3,-1,0
  4474.1    0.16       0  4995.5    0.07       0  5001.5    0.16       0
Bank Sta=4995.5,5001.5
Exp/Cntr=0.3,0.1

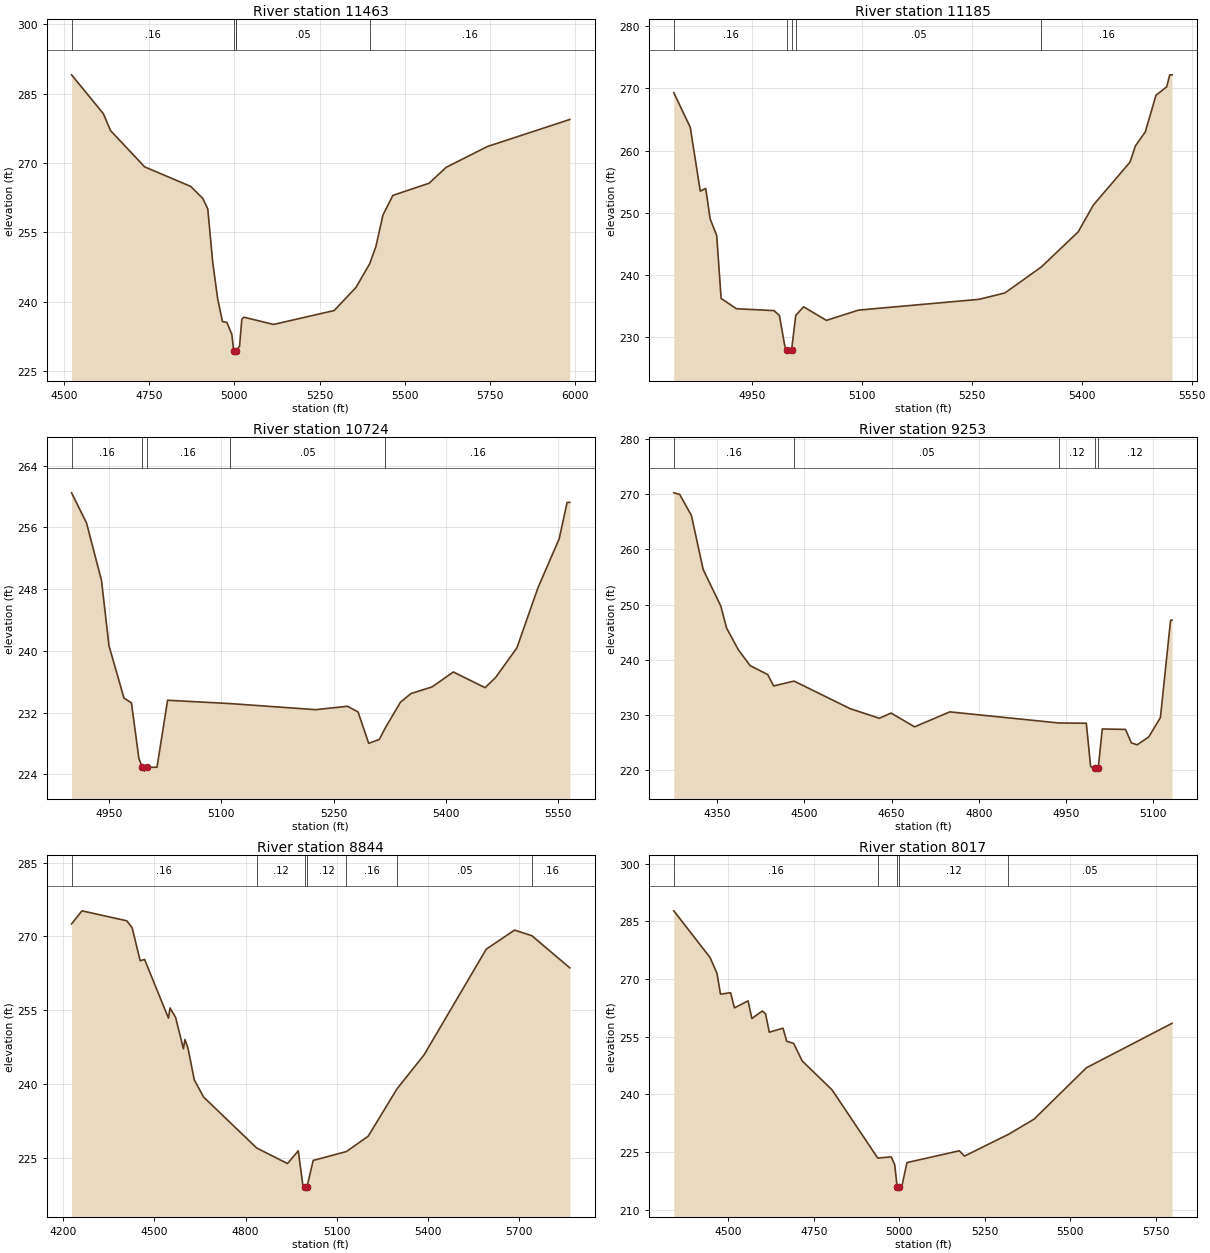
Type RM Length L Ch R = 1,11463,278,278,278
BEGIN DESCRIPTION:
UNT068 IN BECR 16.0
END DESCRIPTION:
XS GIS Cut Line= 3
      3780974.44     10476315.63      3781370.27     10476843.41
      3782015.38     10477322.04
#Sta/Elev= 30
  4521.8  289.11  4615.0  280.72  4636.3  277.05  4736.3  269.20  4871.7  264.97
  4907.1  262.36  4921.7  260.11  4936.3  248.54  4950.8  240.64  4965.0  235.73
  4977.9  235.54  4992.5  232.93  4997.8  229.40  5000.6  228.90  5003.8  229.40
  5005.2  229.51  5015.0  230.37  5021.7  236.24  5027.9  236.67  5115.0  235.11
  5292.8  238.11  5356.8  243.10  5397.2  248.24  5415.3  251.94  5436.1  258.77
  5465.3  263.03  5571.7  265.66  5621.8  269.10  5742.8  273.60  5984.8  279.45
#Mann=5,-1,0
  4521.8    0.16       0  4997.8    0.07       0  5003.8    0.16       0
  5005.2    0.05       0  5397.2    0.16       0
Bank Sta=4997.8,5003.8
Exp/Cntr=0.3,0.1

Type RM Length L Ch R = 1,11185,461,461,461
BEGIN DESCRIPTION:
UNT068 IN BECR 15.0
END DESCRIPTION:
XS GIS Cut Line= 3
      3780999.60     10476810.18      3781149.61     10476910.19
      3781449.61     10477310.19
#Sta/Elev= 30
  4842.9  269.31  4865.4  263.75  4879.0  253.50  4886.5  253.92  4892.5  249.05
  4901.5  246.37  4907.5  236.27  4928.5  234.61  4979.6  234.31  4987.1  233.53
  4994.6  228.52  4997.7  227.98  5000.4  227.48  5003.7  227.98  5009.4  233.54
  5020.2  234.92  5051.3  232.74  5095.1  234.39  5259.7  236.12  5295.1  237.15
  5344.8  241.33  5395.1  246.96  5415.9  251.28  5465.9  258.17  5473.2  260.76
  5486.7  263.02  5501.3  268.90  5515.9  270.25  5520.1  272.18  5523.2  272.18
#Mann=5,-1,0
  4842.9    0.16       0  4997.7    0.07       0  5003.7    0.16       0
  5009.4    0.05       0  5344.8    0.16       0
Bank Sta=4997.7,5003.7
Exp/Cntr=0.3,0.1

Type RM Length L Ch R = 1,10724,1471,1471,1471
BEGIN DESCRIPTION:
UNT068 IN BECR 14.0
END DESCRIPTION:
XS GIS Cut Line= 3
      3780649.63     10477060.19      3780749.61     10477060.19
      3781149.63     10477460.21
#Sta/Elev= 30
  4899.8  260.47  4919.8  256.56  4939.8  249.11  4949.8  240.66  4969.8  233.90
  4979.8  233.27  4989.8  226.04  4994.3  224.93  4997.0  224.43  5000.3  224.93
  5013.9  224.93  5028.1  233.61  5111.0  233.18  5226.1  232.39  5268.5  232.83
  5282.6  232.09  5296.8  228.03  5310.9  228.53  5319.1  230.05  5339.2  233.35
  5353.3  234.48  5381.6  235.34  5409.9  237.27  5452.3  235.24  5466.5  236.57
  5494.8  240.39  5523.0  248.19  5551.3  254.51  5561.9  259.23  5565.5  259.23
#Mann=5,-1,0
  4899.8    0.16       0  4994.3    0.07       0  5000.3    0.16       0
  5111.0    0.05       0  5319.1    0.16       0
Bank Sta=4994.3,5000.3
Exp/Cntr=0.3,0.1

Type RM Length L Ch R = 1,9253,409,409,409
BEGIN DESCRIPTION:
UNT068 IN BECR 13.0
END DESCRIPTION:
XS GIS Cut Line= 3
      3780499.61     10477110.17      3780399.61     10477810.19
      3780399.61     10477960.16
#Sta/Elev= 30
  4275.3  270.24  4285.4  269.96  4305.6  266.14  4325.8  256.35  4356.1  249.73
  4366.2  245.71  4386.4  241.79  4406.6  238.92  4436.9  237.30  4447.0  235.24
  4482.2  236.12  4578.4  231.13  4628.9  229.38  4649.1  230.32  4689.5  227.83
  4750.1  230.54  4937.3  228.53  4984.9  228.48  4992.4  220.64  4999.4  220.30
  5002.2  219.80  5005.4  220.30  5012.4  227.44  5052.4  227.36  5062.4  224.92
  5072.4  224.57  5092.4  226.01  5112.4  229.51  5129.9  247.16  5132.4  247.16
#Mann=5,-1,0
  4275.3    0.16       0  4482.2    0.05       0  4937.3    0.12       0
  4999.4    0.07       0  5005.4    0.12       0
Bank Sta=4999.4,5005.4
Exp/Cntr=0.3,0.1

Type RM Length L Ch R = 1,8844,827,827,827
BEGIN DESCRIPTION:
UNT068 IN BECR 12.0
END DESCRIPTION:
XS GIS Cut Line= 2
      3779946.66     10476885.10      3780293.88     10478489.26
#Sta/Elev= 30
  4226.9  272.55  4261.1  275.20  4408.7  273.18  4426.5  271.76  4452.8  265.08
  4467.4  265.34  4546.1  253.43  4551.2  255.49  4569.7  253.56  4595.3  247.21
  4600.5  249.10  4610.7  247.27  4631.1  240.91  4661.8  237.43  4836.7  227.08
  4938.1  223.93  4973.7  226.52  4989.2  219.39  4996.5  219.24  4999.2  218.74
  5002.5  219.24  5022.9  224.56  5132.5  226.37  5204.1  229.48  5298.8  239.07
  5388.3  246.00  5593.0  267.43  5686.3  271.29  5743.2  270.15  5868.2  263.63
#Mann=7,-1,0
  4226.9    0.16       0  4836.7    0.12       0  4996.5    0.07       0
  5002.5    0.12       0  5132.5    0.16       0  5298.8    0.05       0
  5743.2    0.16       0
Bank Sta=4996.5,5002.5
Exp/Cntr=0.3,0.1

Type RM Length L Ch R = 1,8017,337,337,337
BEGIN DESCRIPTION:
UNT068 IN BECR 11.0
END DESCRIPTION:
XS GIS Cut Line= 2
      3779481.38     10476996.18      3779765.94     10478425.93
#Sta/Elev= 30
  4340.3  287.72  4446.4  275.58  4466.7  271.44  4476.9  266.05  4506.5  266.42
  4517.7  262.48  4557.6  264.30  4568.7  259.71  4599.3  261.68  4608.7  260.94
  4619.7  256.15  4659.8  257.20  4670.7  253.80  4691.1  253.23  4716.0  248.67
  4803.2  241.18  4937.0  223.42  4976.6  223.73  4986.7  221.69  4993.9  215.84
  4996.7  215.34  4999.9  215.84  5007.1  215.93  5022.6  222.25  5175.9  225.31
  5190.7  223.93  5319.3  229.58  5394.6  233.55  5547.5  246.90  5798.1  258.46
#Mann=5,-1,0
  4340.3    0.16       0  4937.0    0.12       0  4993.9    0.07       0
  4999.9    0.12       0  5319.3    0.05       0
Bank Sta=4993.9,4999.9
Exp/Cntr=0.3,0.1