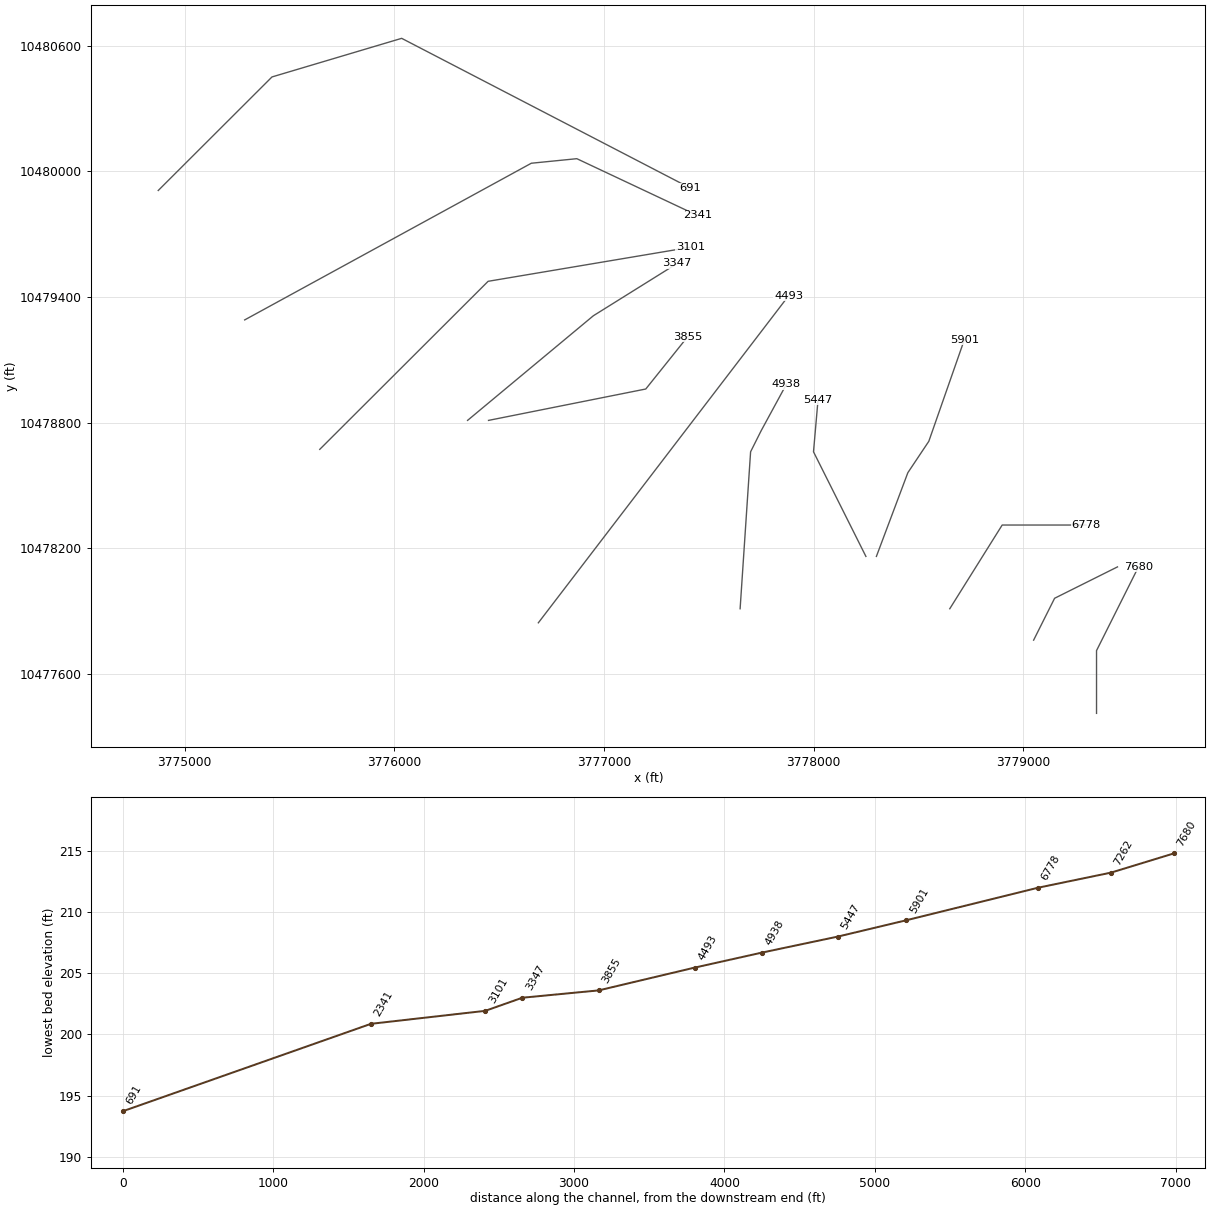
HEC-RAS study UNT068 IN BECR.prj: UNT068 IN BECR Base Level Engineering

--- UNT068 IN BECR.g01 (geometry) --- (continued)

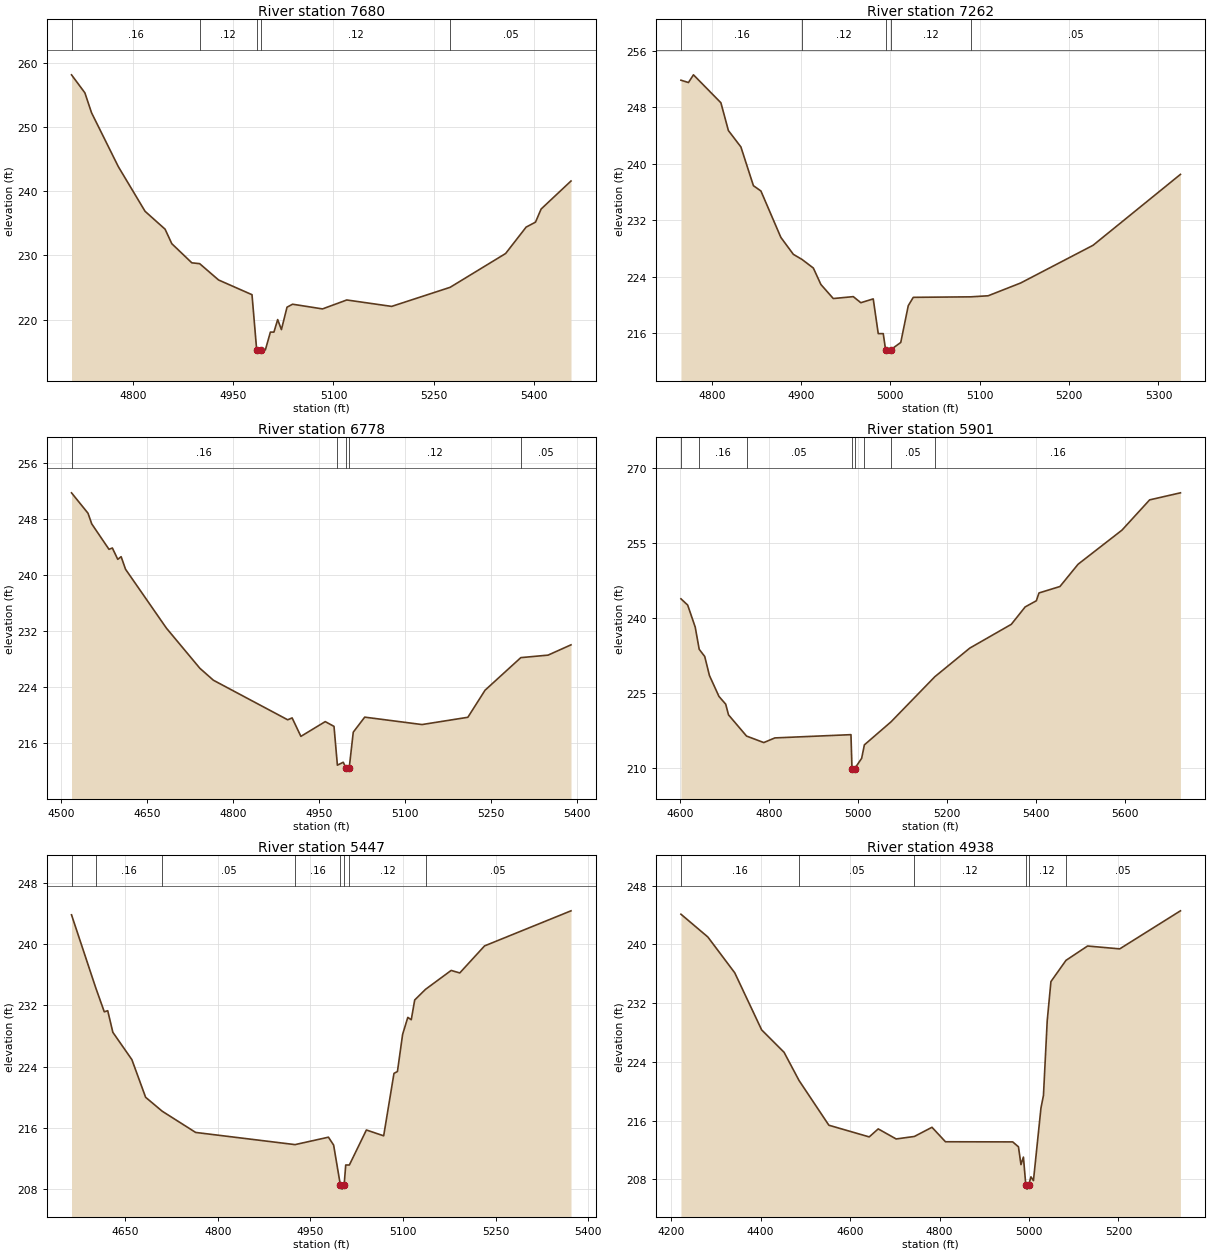
Type RM Length L Ch R = 1,7680,418,418,418
BEGIN DESCRIPTION:
UNT068 IN BECR 10.0
END DESCRIPTION:
XS GIS Cut Line= 3
      3779349.61     10477410.20      3779349.61     10477710.19
      3779549.61     10478110.18
#Sta/Elev= 30
  4708.1  258.09  4728.1  255.29  4738.1  252.18  4778.1  243.81  4818.1  236.86
  4848.1  234.07  4858.1  231.82  4888.1  228.84  4899.8  228.71  4928.1  226.17
  4978.1  223.88  4985.1  215.29  4987.8  214.79  4991.1  215.29  4998.1  215.29
  5005.6  218.06  5010.9  218.06  5016.5  220.01  5022.1  218.45  5030.5  221.94
  5038.8  222.40  5083.6  221.67  5119.9  223.06  5187.0  222.06  5274.5  225.03
  5357.5  230.29  5388.2  234.40  5402.2  235.17  5410.6  237.21  5455.3  241.57
#Mann=5,-1,0
  4708.1    0.16       0  4899.8    0.12       0  4985.1    0.07       0
  4991.1    0.12       0  5274.5    0.05       0
Bank Sta=4985.1,4991.1
Exp/Cntr=0.3,0.1

Type RM Length L Ch R = 1,7262,484,484,484
BEGIN DESCRIPTION:
UNT068 IN BECR 9.0
END DESCRIPTION:
XS GIS Cut Line= 3
      3779049.60     10477760.17      3779149.61     10477960.19
      3779449.57     10478110.17
#Sta/Elev= 30
  4765.6  251.82  4774.0  251.49  4779.6  252.58  4810.3  248.63  4818.7  244.70
  4832.7  242.38  4846.7  236.90  4855.1  236.15  4877.4  229.59  4891.4  227.19
  4901.1  226.47  4913.8  225.25  4922.2  222.93  4936.1  220.94  4958.5  221.21
  4966.9  220.35  4980.8  220.89  4986.4  215.98  4992.0  215.98  4994.6  213.72
  4997.4  213.22  5000.6  213.72  5011.6  214.73  5020.0  219.93  5025.6  221.11
  5089.8  221.18  5109.4  221.33  5145.8  223.14  5226.8  228.47  5324.6  238.50
#Mann=5,-1,0
  4765.6    0.16       0  4901.1    0.12       0  4994.6    0.07       0
  5000.6    0.12       0  5089.8    0.05       0
Bank Sta=4994.6,5000.6
Exp/Cntr=0.3,0.1

Type RM Length L Ch R = 1,6778,877,877,877
BEGIN DESCRIPTION:
UNT068 IN BECR 8.0
END DESCRIPTION:
XS GIS Cut Line= 3
      3778649.63     10477910.22      3778899.61     10478310.19
      3779299.65     10478310.19
#Sta/Elev= 30
  4517.6  251.79  4546.4  248.87  4552.9  247.35  4583.0  243.71  4588.9  243.90
  4598.3  242.28  4604.2  242.66  4611.9  240.86  4683.2  232.44  4741.6  226.70
  4765.2  224.99  4894.9  219.33  4902.6  219.60  4917.9  216.96  4960.4  219.07
  4975.7  218.39  4980.9  213.50  4981.6  212.84  4991.8  213.26  4996.3  212.49
  4999.0  211.99  5002.3  212.49  5009.3  217.56  5029.3  219.71  5129.3  218.65
  5209.3  219.69  5239.3  223.56  5301.7  228.22  5349.3  228.58  5389.3  230.05
#Mann=5,-1,0
  4517.6    0.16       0  4980.9    0.12       0  4996.3    0.07       0
  5002.3    0.12       0  5301.7    0.05       0
Bank Sta=4996.3,5002.3
Exp/Cntr=0.3,0.1

Type RM Length L Ch R = 1,5901,454,454,454
BEGIN DESCRIPTION:
UNT068 IN BECR 7.0
END DESCRIPTION:
XS GIS Cut Line= 4
      3778299.62     10478160.22      3778449.61     10478560.19
      3778549.61     10478710.19      3778719.11     10479195.71
#Sta/Elev= 30
  4602.5  243.78  4617.6  242.53  4634.5  238.14  4643.5  233.69  4655.9  232.25
  4666.5  228.44  4687.9  224.26  4703.0  222.72  4709.3  220.58  4749.8  216.34
  4788.5  215.04  4813.4  215.97  4984.3  216.62  4986.6  209.83  4989.4  209.33
  4992.6  209.83  5008.3  211.89  5014.4  214.58  5074.2  219.18  5172.6  228.20
  5251.2  233.93  5344.4  238.68  5375.5  242.16  5400.6  243.39  5406.5  244.95
  5453.6  246.24  5494.4  250.70  5592.9  257.51  5655.0  263.56  5724.2  264.97
#Mann=8,-1,0
  4602.5    0.12       0  4643.5    0.16       0  4749.8    0.05       0
  4986.6    0.03       0  4992.6    0.05       0  5014.4    0.16       0
  5074.2    0.05       0  5172.6    0.16       0
Bank Sta=4986.6,4992.6
Exp/Cntr=0.3,0.1

Type RM Length L Ch R = 1,5447,509,509,509
BEGIN DESCRIPTION:
UNT068 IN BECR 6.0
END DESCRIPTION:
XS GIS Cut Line= 4
      3778249.59     10478160.22      3778049.61     10478560.19
      3777999.61     10478660.19      3778021.38     10478909.76
#Sta/Elev= 30
  4562.7  243.81  4602.1  234.25  4615.8  231.15  4621.4  231.29  4629.7  228.47
  4660.5  224.91  4682.8  219.99  4709.7  218.17  4763.9  215.40  4925.0  213.81
  4979.1  214.78  4987.5  213.75  4998.5  208.50  5001.2  208.00  5004.5  208.50
  5007.1  211.15  5013.0  211.15  5040.6  215.72  5068.6  214.96  5085.3  223.11
  5090.9  223.35  5099.3  228.20  5107.7  230.42  5113.3  230.11  5118.9  232.69
  5136.4  234.08  5178.0  236.55  5191.9  236.22  5232.1  239.75  5372.2  244.33
#Mann=8,-1,0
  4562.7    0.12       0  4602.1    0.16       0  4709.7    0.05       0
  4925.0    0.16       0  4998.5    0.07       0  5004.5    0.16       0
  5013.0    0.12       0  5136.4    0.05       0
Bank Sta=4998.5,5004.5
Exp/Cntr=0.3,0.1

Type RM Length L Ch R = 1,4938,445,445,445
BEGIN DESCRIPTION:
UNT068 IN BECR 5.0
END DESCRIPTION:
XS GIS Cut Line= 4
      3777649.61     10477910.18      3777699.61     10478660.19
      3777749.61     10478760.19      3777870.32     10478982.68
#Sta/Elev= 30
  4221.9  244.11  4282.0  241.01  4342.2  236.13  4402.3  228.36  4452.4  225.31
  4486.1  221.45  4552.6  215.38  4642.8  213.79  4662.9  214.88  4703.0  213.51
  4743.7  213.85  4783.1  215.10  4813.2  213.13  4963.5  213.11  4976.4  212.44
  4982.0  210.02  4987.5  211.04  4992.9  207.18  4995.7  206.68  4998.9  207.18
  5004.3  208.35  5009.9  207.84  5026.7  217.72  5032.3  219.45  5040.7  229.62
  5049.0  234.94  5082.7  237.83  5130.9  239.78  5202.8  239.39  5338.5  244.57
#Mann=6,-1,0
  4221.9    0.16       0  4486.1    0.05       0  4743.7    0.12       0
  4992.9    0.07       0  4998.9    0.12       0  5082.7    0.05       0
Bank Sta=4992.9,4998.9
Exp/Cntr=0.3,0.1

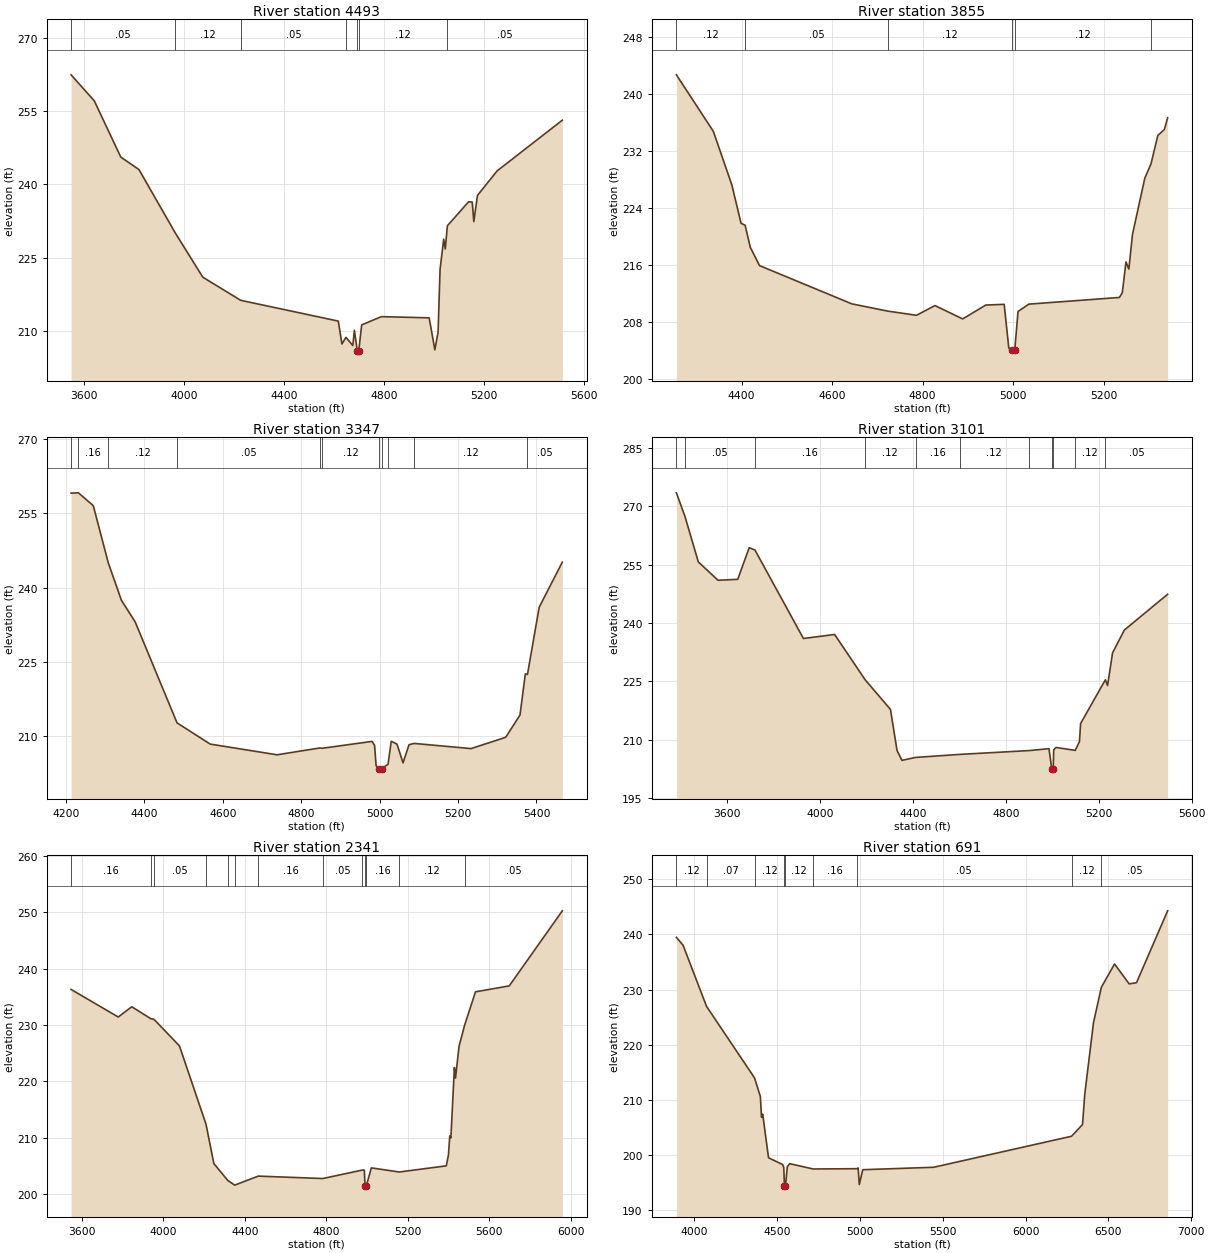
Type RM Length L Ch R = 1,4493,638,638,638
BEGIN DESCRIPTION:
UNT068 IN BECR 4.0
END DESCRIPTION:
XS GIS Cut Line= 2
      3776687.17     10477842.95      3777880.68     10479405.35
#Sta/Elev= 30
  3547.0  262.38  3639.8  257.06  3745.8  245.56  3818.5  243.01  3964.1  230.03
  4074.1  220.99  4225.9  216.26  4616.5  212.01  4631.0  207.33  4647.0  208.68
  4674.6  207.02  4680.9  210.13  4692.4  205.96  4695.2  205.46  4698.4  205.96
  4710.0  211.23  4788.9  212.92  4980.2  212.68  5002.9  206.14  5015.8  209.75
  5023.8  222.61  5038.3  228.76  5044.6  226.77  5053.1  231.51  5138.0  236.42
  5152.6  236.34  5158.9  232.36  5173.4  237.71  5252.3  242.74  5513.1  253.10
#Mann=7,-1,0
  3547.0    0.05       0  3964.1    0.12       0  4225.9    0.05       0
  4647.0    0.12       0  4692.4    0.07       0  4698.4    0.12       0
  5053.1    0.05       0
Bank Sta=4692.4,4698.4
Exp/Cntr=0.3,0.1

Type RM Length L Ch R = 1,3855,508,508,508
BEGIN DESCRIPTION:
UNT068 IN BECR 3.0
END DESCRIPTION:
XS GIS Cut Line= 3
      3776449.62     10478810.19      3777199.61     10478960.19
      3777399.61     10479210.19
#Sta/Elev= 30
  4256.1  242.74  4337.7  234.79  4378.5  227.27  4398.9  221.86  4407.9  221.58
  4419.3  218.48  4439.7  215.91  4643.6  210.53  4722.8  209.51  4786.4  208.92
  4827.2  210.29  4888.4  208.41  4939.4  210.36  4980.1  210.46  4990.3  204.31
  4997.5  204.10  5000.3  203.60  5003.5  204.10  5010.7  209.46  5034.5  210.49
  5234.6  211.43  5241.0  212.10  5249.1  216.43  5255.5  215.42  5263.5  220.30
  5290.7  228.21  5304.3  230.20  5319.5  234.22  5333.9  235.05  5341.1  236.69
#Mann=6,-1,0
  4256.1    0.12       0  4407.9    0.05       0  4722.8    0.12       0
  4997.5    0.07       0  5003.5    0.12       0  5304.3    0.05       0
Bank Sta=4997.5,5003.5
Exp/Cntr=0.3,0.1

Type RM Length L Ch R = 1,3347,246,246,246
BEGIN DESCRIPTION:
UNT068 IN BECR 2.0
END DESCRIPTION:
XS GIS Cut Line= 3
      3776349.62     10478810.20      3776949.61     10479310.19
      3777349.60     10479560.18
#Sta/Elev= 30
  4213.3  259.01  4232.0  259.08  4269.9  256.49  4308.0  245.00  4341.5  237.45
  4376.7  233.07  4483.4  212.73  4568.0  208.45  4738.5  206.29  4847.8  207.67
  4853.2  207.60  4980.6  208.99  4987.2  208.21  4991.1  204.11  4999.0  203.50
  5001.7  203.00  5005.0  203.50  5021.6  204.37  5029.7  209.01  5044.4  208.45
  5059.8  204.67  5075.1  208.33  5088.2  208.58  5233.1  207.54  5321.6  209.81
  5358.1  214.31  5371.7  222.59  5377.1  222.48  5407.0  236.02  5466.0  245.11
#Mann=11,-1,0
  4213.3    0.12       0  4232.0    0.16       0  4308.0    0.12       0
  4483.4    0.05       0  4847.8    0.16       0  4853.2    0.12       0
  4999.0    0.07       0  5005.0    0.12       0  5021.6    0.16       0
  5088.2    0.12       0  5377.1    0.05       0
Bank Sta=4999,5005
Exp/Cntr=0.3,0.1

Type RM Length L Ch R = 1,3101,760,760,760
BEGIN DESCRIPTION:
Mapping XS 60d62549
END DESCRIPTION:
XS GIS Cut Line= 3
      3775644.62     10478671.81      3776447.60     10479474.79
      3777413.29     10479637.55
#Sta/Elev= 30
  3381.6  273.50  3418.5  267.42  3475.9  255.74  3560.8  251.01  3645.6  251.25
  3695.1  259.39  3719.8  258.79  3928.5  236.04  4062.8  237.07  4193.9  225.45
  4303.2  217.80  4331.5  207.25  4352.7  204.70  4411.1  205.45  4600.8  206.23
  4899.6  207.21  4985.7  207.71  4997.9  202.43  5000.7  201.93  5003.9  202.43
  5006.0  207.43  5016.1  208.02  5098.8  207.27  5116.9  209.51  5121.9  214.18
  5228.5  225.42  5237.9  223.93  5259.5  232.35  5310.2  238.21  5496.5  247.41
#Mann=11,-1,0
  3381.6    0.16       0  3418.5    0.05       0  3719.8    0.16       0
  4193.9    0.12       0  4411.1    0.16       0  4600.8    0.12       0
  4899.6    0.16       0  4997.9    0.07       0  5003.9    0.16       0
  5098.8    0.12       0  5228.5    0.05       0
Bank Sta=4997.9,5003.9
Exp/Cntr=0.3,0.1

Type RM Length L Ch R = 1,2341,1650,1650,1650
BEGIN DESCRIPTION:
Mapping XS 48d38774
END DESCRIPTION:
XS GIS Cut Line= 4
      3775286.55     10479290.32      3776653.76     10480039.03
      3776870.78     10480060.73      3777445.28     10479789.74
#Sta/Elev= 30
  3546.6  236.30  3778.1  231.41  3844.5  233.23  3938.1  231.11  3953.9  230.99
  4078.7  226.28  4209.2  212.37  4247.5  205.41  4316.5  202.39  4350.1  201.58
  4465.6  203.18  4782.5  202.75  4975.9  204.25  4986.6  204.24  4989.8  201.37
  4992.6  200.87  4995.8  201.37  5020.9  204.64  5158.4  203.91  5388.7  205.00
  5399.6  206.93  5406.0  210.32  5411.5  209.97  5428.7  222.44  5434.3  220.58
  5451.5  226.19  5478.8  229.94  5532.3  235.88  5698.1  236.93  5958.7  250.25
#Mann=13,-1,0
  3546.6    0.16       0  3938.1    0.12       0  3953.9    0.05       0
  4209.2    0.12       0  4316.5    0.05       0  4350.1    0.12       0
  4465.6    0.16       0  4782.5    0.05       0  4975.9    0.16       0
  4989.8    0.07       0  4995.8    0.16       0  5158.4    0.12       0
  5478.8    0.05       0
Bank Sta=4989.8,4995.8
Exp/Cntr=0.3,0.1

Type RM Length L Ch R = 1,691,0,0,0
BEGIN DESCRIPTION:
UNT068 IN BECR 1.0
END DESCRIPTION:
XS GIS Cut Line= 4
      3774874.22     10479908.79      3775416.78     10480451.35
      3776035.27     10480635.82      3777413.28     10479919.68
#Sta/Elev= 30
  3891.6  239.48  3931.8  238.05  4073.6  226.94  4363.2  213.95  4398.5  210.56
  4405.5  206.79  4412.6  207.35  4447.9  199.43  4532.8  198.20  4539.9  197.66
  4543.9  194.23  4546.7  193.73  4549.9  194.23  4561.1  197.81  4575.2  198.36
  4717.2  197.39  4980.9  197.44  4988.9  197.58  4995.8  194.56  5016.7  197.26
  5444.4  197.70  6277.4  203.34  6343.5  205.47  6357.3  211.04  6409.8  223.99
  6457.5  230.43  6536.9  234.64  6625.3  231.02  6669.5  231.24  6857.3  244.30
#Mann=9,-1,0
  3891.6    0.12       0  4073.6    0.07       0  4363.2    0.12       0
  4543.9    0.03       0  4549.9    0.12       0  4717.2    0.16       0
  4980.9    0.05       0  6277.4    0.12       0  6457.5    0.05       0
Bank Sta=4543.9,4549.9
Exp/Cntr=0.3,0.1

Chan Stop Cuts=-1