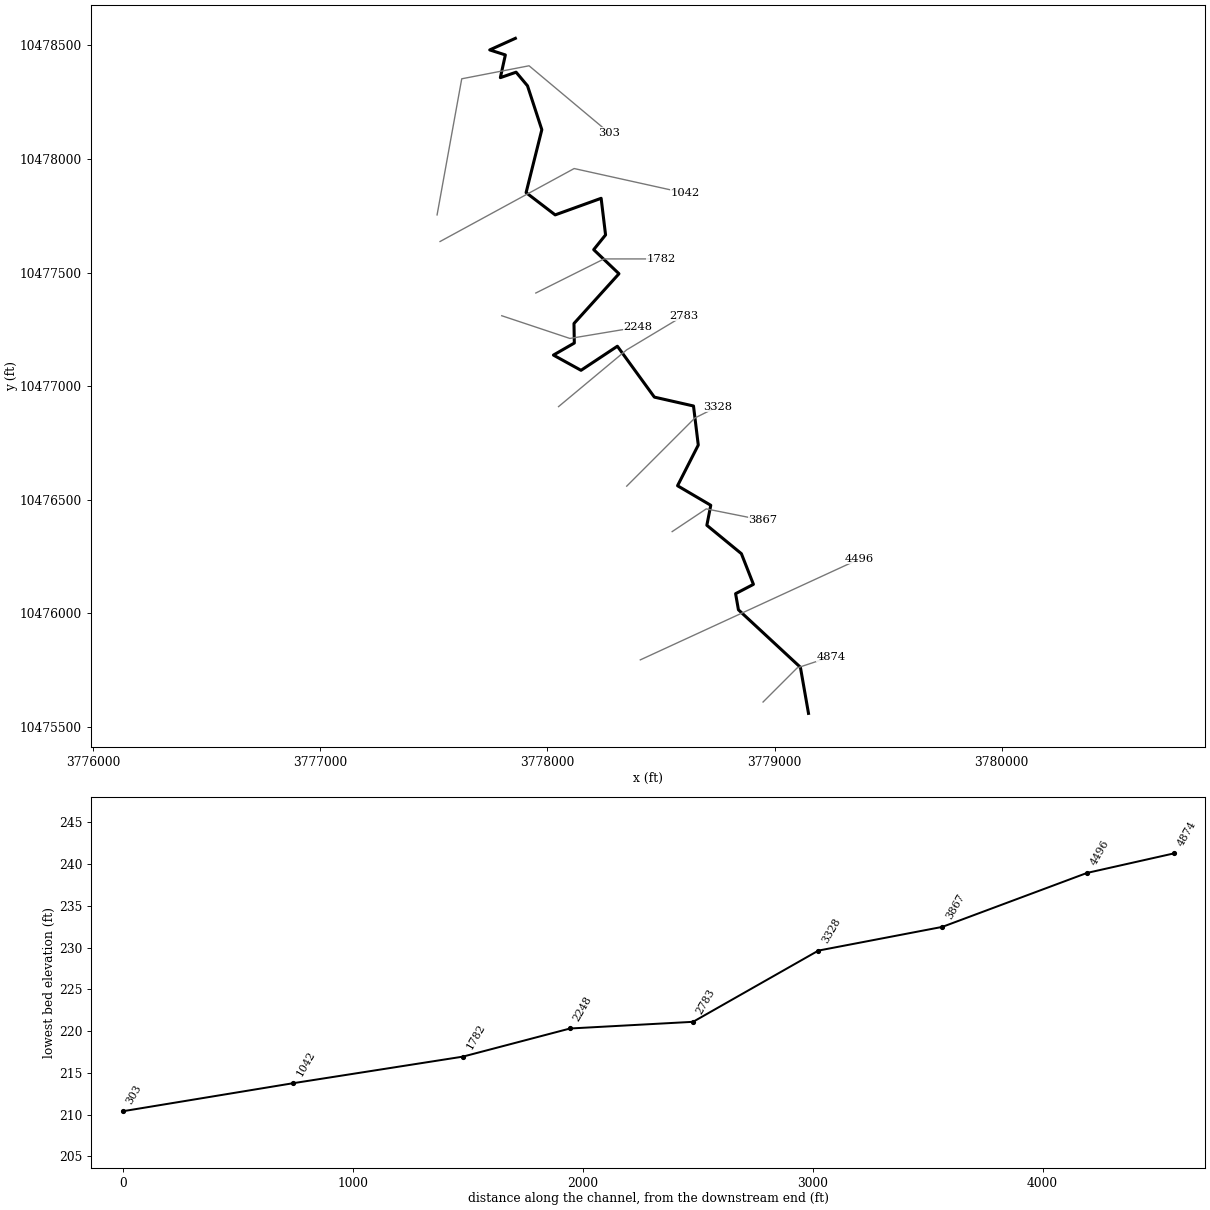
--- UNT069 IN BECR.prj (project) ---

Proj Title=UNT069 IN BECR Base Level Engineering
Current Plan=p01
Default Exp/Contr=0.3,0.1
English Units
Geom File=g01
Flow File=f01
Plan File=p01
BEGIN DESCRIPTION:
UNT069 IN BECR
END DESCRIPTION:

--- UNT069 IN BECR.p01 (plan) ---

Plan Title=Multiple Run
Short Identifier=Multiple
Geom File=g01
Flow File=f01
Subcritical Flow
K Sum by GR= 0
Std Step Tol= 0.01
Critical Tol= 0.01
Num of Std Step Trials= 20
Max Error Tol= 0.3
Flow Tol Ratio= 0.001
Split Flow NTrial= 30
Split Flow Tol= 0.02
Split Flow Ratio= 0.02
Log Output Level= 0
Friction Slope Method= 1
Unsteady Friction Slope Method= 2
Unsteady Bridges Friction Slope Method= 1
Parabolic Critical Depth
Global Vel Dist=  1 , 1 , 1
Global Log Level= 0
CheckData=True
Encroach Param= -1, 0, 0, 0
BEGIN DESCRIPTION:
Multiple Run
END DESCRIPTION:

--- UNT069 IN BECR.f01 (steady flow) ---

Flow Title=Multiple
Number of Profiles=7
Profile Names=10-year,25-year,50-year,1pct_min,100-year,1pct_plu,500-year
River Rch & RM= UNT069 IN BECR,Reach-1,4874
     321     418     496     433     586     793     820
Boundary for River Rch & Prof#=UNT069 IN BECR,Reach-1,1
Up Type=0
Dn Type=3
Dn Slope=0.005
Boundary for River Rch & Prof#=UNT069 IN BECR,Reach-1,2
Up Type=0
Dn Type=3
Dn Slope=0.005
Boundary for River Rch & Prof#=UNT069 IN BECR,Reach-1,3
Up Type=0
Dn Type=3
Dn Slope=0.005
Boundary for River Rch & Prof#=UNT069 IN BECR,Reach-1,4
Up Type=0
Dn Type=3
Dn Slope=0.005
Boundary for River Rch & Prof#=UNT069 IN BECR,Reach-1,5
Up Type=0
Dn Type=3
Dn Slope=0.005
Boundary for River Rch & Prof#=UNT069 IN BECR,Reach-1,6
Up Type=0
Dn Type=3
Dn Slope=0.005
Boundary for River Rch & Prof#=UNT069 IN BECR,Reach-1,7
Up Type=0
Dn Type=3
Dn Slope=0.005

--- UNT069 IN BECR.g01 (geometry) ---

Geom Title=Existing Conditions

River Reach=UNT069 IN BECR,Reach-1
Reach XY= 30
      3779149.61     10475560.19      3779114.00     10475763.00
      3778841.25     10476016.00      3778828.75     10476087.00
      3778907.25     10476128.00      3778854.25     10476263.00
      3778702.25     10476388.00      3778719.50     10476476.00
      3778573.25     10476562.00      3778664.50     10476741.00
      3778643.50     10476913.00      3778471.25     10476952.00
      3778308.50     10477176.00      3778148.50     10477070.00
      3778027.00     10477137.00      3778119.00     10477190.00
      3778117.50     10477276.00      3778315.50     10477495.00
      3778204.25     10477601.00      3778256.50     10477666.00
      3778237.00     10477827.00      3778034.75     10477754.00
      3777906.75     10477852.00      3777976.00     10478129.00
      3777913.00     10478322.00      3777862.75     10478382.00
      3777793.50     10478358.00      3777815.50     10478458.00
      3777746.75     10478480.00      3777859.50     10478531.00

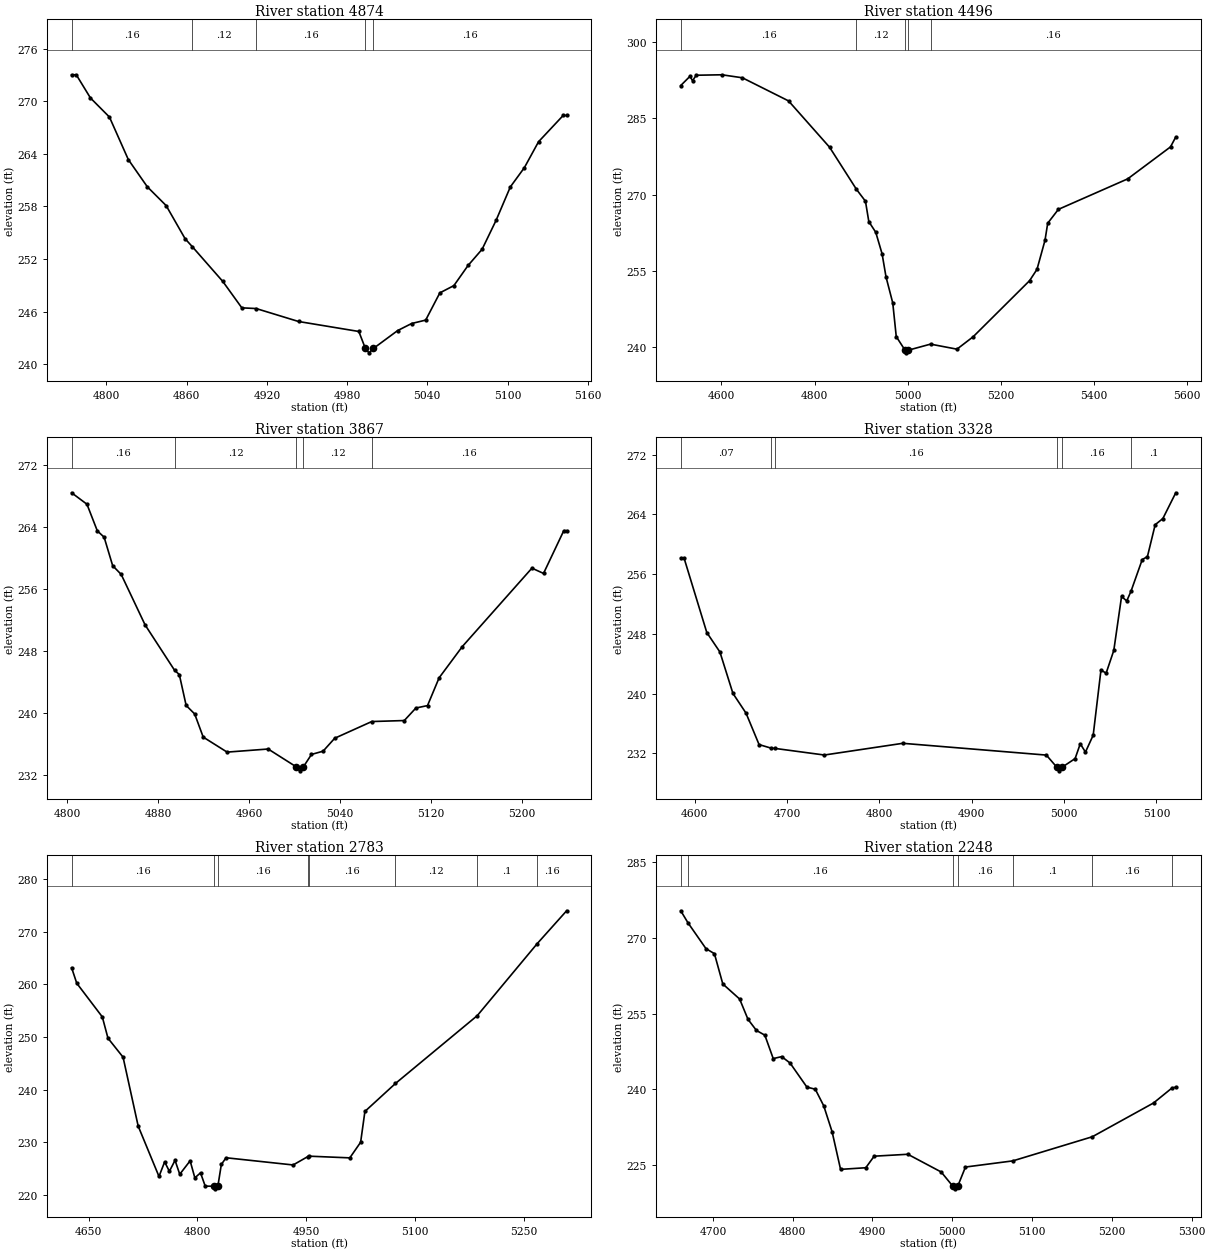
Type RM Length L Ch R = 1,4874,378,378,378
BEGIN DESCRIPTION:
UNT069 IN BECR 9.0
END DESCRIPTION:
XS GIS Cut Line= 3
      3778949.61     10475610.19      3779099.61     10475760.19
      3779249.56     10475810.17
#Sta/Elev= 30
  4774.0  273.04  4777.5  273.04  4788.1  270.39  4802.3  268.21  4816.4  263.36
  4830.6  260.25  4844.7  258.10  4858.9  254.31  4864.3  253.40  4887.1  249.43
  4901.3  246.42  4912.0  246.34  4943.7  244.86  4988.8  243.72  4993.7  241.78
  4996.4  241.28  4999.7  241.78  5017.8  243.82  5028.3  244.63  5038.8  245.02
  5049.4  248.13  5059.9  248.96  5070.5  251.26  5081.0  253.11  5091.5  256.43
  5102.1  260.23  5112.6  262.43  5123.2  265.39  5141.6  268.39  5144.2  268.39
#Mann=5,-1,0
  4774.0    0.16       0  4864.3    0.12       0  4912.0    0.16       0
  4993.7    0.07       0  4999.7    0.16       0
Bank Sta=4993.7,4999.7
Exp/Cntr=0.3,0.1

Type RM Length L Ch R = 1,4496,629,629,629
BEGIN DESCRIPTION:
UNT069 IN BECR 8.0
END DESCRIPTION:
XS GIS Cut Line= 2
      3778409.41     10475795.65      3779374.61     10476240.06
#Sta/Elev= 30
  4512.7  291.43  4532.5  293.24  4538.0  292.37  4545.9  293.45  4601.0  293.54
  4645.0  292.95  4744.1  288.41  4832.2  279.31  4889.9  271.04  4909.2  268.71
  4916.4  264.71  4931.3  262.61  4944.9  258.38  4953.3  253.86  4967.8  248.73
  4975.3  242.13  4994.3  239.44  4997.1  238.94  5000.3  239.44  5048.9  240.65
  5105.6  239.66  5140.4  242.10  5261.5  253.11  5277.4  255.33  5294.6  261.04
  5300.4  264.39  5323.3  267.11  5472.1  273.10  5564.0  279.38  5575.3  281.32
#Mann=5,-1,0
  4512.7    0.16       0  4889.9    0.12       0  4994.3    0.07       0
  5000.3    0.12       0  5048.9    0.16       0
Bank Sta=4994.3,5000.3
Exp/Cntr=0.3,0.1

Type RM Length L Ch R = 1,3867,539,539,539
BEGIN DESCRIPTION:
UNT069 IN BECR 7.0
END DESCRIPTION:
XS GIS Cut Line= 3
      3778549.59     10476360.18      3778699.61     10476460.19
      3778949.56     10476410.20
#Sta/Elev= 30
  4804.0  268.41  4817.5  266.93  4826.6  263.49  4832.6  262.67  4840.1  258.99
  4847.6  257.86  4868.6  251.34  4894.5  245.48  4898.7  244.92  4904.7  240.93
  4912.2  239.83  4919.7  236.84  4940.7  234.90  4976.8  235.30  5001.7  232.98
  5004.4  232.48  5007.7  232.98  5014.9  234.60  5025.1  235.02  5035.3  236.69
  5067.9  238.85  5096.5  238.98  5106.7  240.60  5116.9  240.91  5127.1  244.50
  5147.5  248.54  5208.7  258.67  5218.9  257.99  5236.7  263.51  5239.2  263.51
#Mann=5,-1,0
  4804.0    0.16       0  4894.5    0.12       0  5001.7    0.07       0
  5007.7    0.12       0  5067.9    0.16       0
Bank Sta=5001.7,5007.7
Exp/Cntr=0.3,0.1

Type RM Length L Ch R = 1,3328,545,545,545
BEGIN DESCRIPTION:
UNT069 IN BECR 6.0
END DESCRIPTION:
XS GIS Cut Line= 3
      3778349.64     10476560.22      3778649.61     10476860.19
      3778749.59     10476910.18
#Sta/Elev= 30
  4584.9  258.19  4588.4  258.19  4613.1  248.18  4627.3  245.57  4641.4  240.02
  4655.6  237.37  4669.7  233.16  4682.8  232.68  4687.3  232.64  4740.4  231.76
  4825.3  233.33  4980.8  231.75  4992.0  230.14  4994.7  229.64  4998.0  230.14
  5011.9  231.28  5017.5  233.27  5023.1  232.15  5031.5  234.42  5039.9  243.15
  5045.5  242.73  5053.8  245.78  5062.2  253.01  5067.8  252.41  5072.4  253.70
  5084.6  257.96  5090.2  258.35  5098.6  262.63  5106.9  263.45  5120.9  266.91
#Mann=6,-1,0
  4584.9    0.07       0  4682.8    0.05       0  4687.3    0.16       0
  4992.0    0.07       0  4998.0    0.16       0  5072.4     0.1       0
Bank Sta=4992,4998
Exp/Cntr=0.3,0.1

Type RM Length L Ch R = 1,2783,535,535,535
BEGIN DESCRIPTION:
UNT069 IN BECR 5.0
END DESCRIPTION:
XS GIS Cut Line= 3
      3778049.64     10476910.22      3778349.61     10477160.19
      3778599.60     10477310.18
#Sta/Elev= 30
  4626.7  263.16  4633.8  260.21  4669.0  253.81  4676.8  249.76  4697.6  246.15
  4718.4  233.05  4747.1  223.46  4754.9  226.24  4761.4  224.44  4769.2  226.53
  4775.7  223.88  4790.0  226.44  4796.5  223.20  4804.3  224.15  4810.8  221.62
  4822.2  221.61  4824.9  221.11  4828.2  221.61  4833.0  225.75  4839.5  227.02
  4931.9  225.65  4952.2  227.25  4954.2  227.32  5010.0  227.00  5024.9  229.97
  5030.8  235.83  5072.9  241.15  5185.6  254.05  5268.1  267.73  5308.7  273.99
#Mann=8,-1,0
  4626.7    0.16       0  4822.2    0.07       0  4828.2    0.16       0
  4952.2    0.12       0  4954.2    0.16       0  5072.9    0.12       0
  5185.6     0.1       0  5268.1    0.16       0
Bank Sta=4822.2,4828.2
Exp/Cntr=0.3,0.1

Type RM Length L Ch R = 1,2248,466,466,466
BEGIN DESCRIPTION:
UNT069 IN BECR 4.0
END DESCRIPTION:
XS GIS Cut Line= 3
      3777799.62     10477310.19      3778099.61     10477210.19
      3778399.65     10477260.20
#Sta/Elev= 30
  4659.7  275.41  4668.7  273.04  4691.3  267.91  4701.9  266.91  4712.4  260.91
  4733.5  257.92  4744.0  253.89  4754.6  251.69  4765.1  250.76  4775.6  246.12
  4786.2  246.51  4796.7  245.24  4817.8  240.47  4828.3  240.05  4838.9  236.76
  4849.4  231.61  4860.0  224.17  4891.6  224.49  4902.1  226.78  4944.3  227.16
  4986.1  223.65  5000.8  220.81  5003.5  220.31  5006.8  220.81  5016.5  224.63
  5075.9  225.85  5175.5  230.63  5252.2  237.32  5275.1  240.26  5280.1  240.46
#Mann=7,-1,0
  4659.7    0.05       0  4668.7    0.16       0  5000.8    0.07       0
  5006.8    0.16       0  5075.9     0.1       0  5175.5    0.16       0
  5275.1    0.12       0
Bank Sta=5000.8,5006.8
Exp/Cntr=0.3,0.1

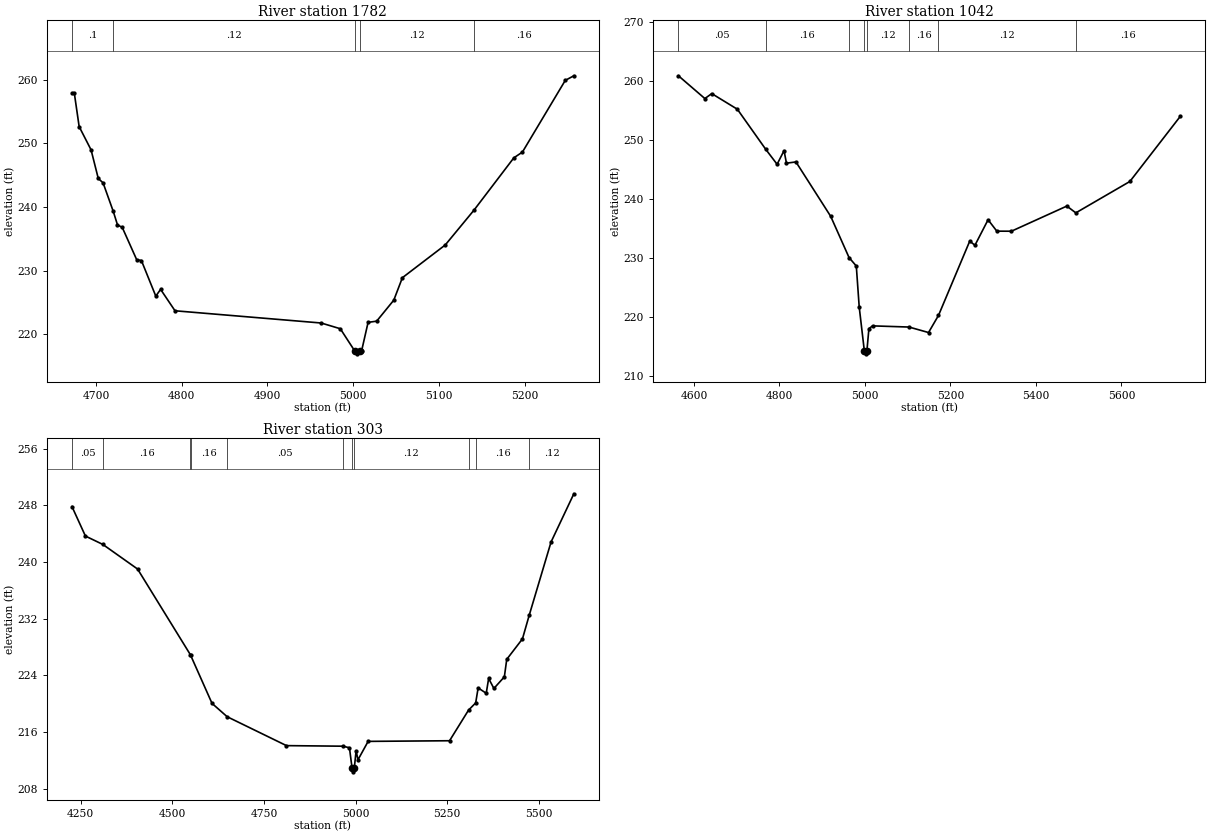
Type RM Length L Ch R = 1,1782,740,740,740
BEGIN DESCRIPTION:
UNT069 IN BECR 3.0
END DESCRIPTION:
XS GIS Cut Line= 3
      3777949.62     10477410.19      3778249.61     10477560.19
      3778499.61     10477560.19
#Sta/Elev= 30
  4672.0  257.83  4674.8  257.83  4680.4  252.61  4694.3  248.96  4702.7  244.47
  4708.3  243.78  4720.2  239.30  4725.1  237.19  4730.7  236.78  4747.5  231.72
  4753.0  231.59  4769.8  226.00  4775.4  227.06  4792.2  223.70  4962.7  221.78
  4985.0  220.88  5001.6  217.44  5004.4  216.94  5007.6  217.44  5009.9  217.44
  5017.4  221.88  5027.4  222.07  5047.4  225.37  5057.4  228.89  5107.4  234.03
  5141.0  239.51  5187.4  247.71  5197.4  248.61  5247.4  259.87  5257.4  260.59
#Mann=5,-1,0
  4672.0     0.1       0  4720.2    0.12       0  5001.6    0.07       0
  5007.6    0.12       0  5141.0    0.16       0
Bank Sta=5001.6,5007.6
Exp/Cntr=0.3,0.1

Type RM Length L Ch R = 1,1042,739,739,739
BEGIN DESCRIPTION:
UNT069 IN BECR 2.0
END DESCRIPTION:
XS GIS Cut Line= 3
      3777528.07     10477636.81      3778118.32     10477957.97
      3778608.79     10477849.46
#Sta/Elev= 30
  4563.6  260.87  4625.5  257.01  4641.6  257.85  4701.5  255.20  4767.9  248.41
  4794.5  245.87  4810.7  248.18  4816.4  246.06  4838.6  246.27  4919.9  237.05
  4962.8  230.07  4979.8  228.63  4986.6  221.69  4998.6  214.25  5001.4  213.75
  5004.6  214.25  5009.3  218.02  5017.8  218.49  5103.2  218.29  5148.8  217.36
  5172.1  220.26  5245.2  232.85  5257.4  232.15  5288.1  236.47  5308.6  234.54
  5342.7  234.53  5472.4  238.79  5493.4  237.64  5619.9  242.96  5737.9  254.00
#Mann=8,-1,0
  4563.6    0.05       0  4767.9    0.16       0  4962.8    0.12       0
  4998.6    0.07       0  5004.6    0.12       0  5103.2    0.16       0
  5172.1    0.12       0  5493.4    0.16       0
Bank Sta=4998.6,5004.6
Exp/Cntr=0.3,0.1

Type RM Length L Ch R = 1,303,0,0,0
BEGIN DESCRIPTION:
UNT069 IN BECR 1.0
END DESCRIPTION:
XS GIS Cut Line= 4
      3777515.01     10477753.95      3777623.52     10478352.94
      3777919.82     10478410.23      3778272.17     10478115.16
#Sta/Elev= 30
  4225.9  247.85  4262.7  243.68  4310.2  242.50  4405.0  239.03  4549.1  226.94
  4549.9  226.85  4608.3  220.06  4649.6  218.18  4811.5  214.10  4965.7  214.02
  4983.4  213.80  4990.6  210.90  4993.4  210.40  4996.6  210.90  5001.6  213.38
  5006.7  212.10  5034.4  214.70  5256.7  214.79  5308.5  219.11  5328.0  220.13
  5334.7  222.25  5356.8  221.49  5363.4  223.58  5377.7  222.17  5406.3  223.81
  5412.8  226.28  5455.7  229.17  5474.1  232.50  5533.8  242.85  5596.0  249.65
#Mann=11,-1,0
  4225.9    0.05       0  4310.2    0.16       0  4549.1    0.05       0
  4549.9    0.16       0  4649.6    0.05       0  4965.7    0.12       0
  4990.6    0.07       0  4996.6    0.12       0  5308.5    0.05       0
  5328.0    0.16       0  5474.1    0.12       0
Bank Sta=4990.6,4996.6
Exp/Cntr=0.3,0.1

Chan Stop Cuts=-1