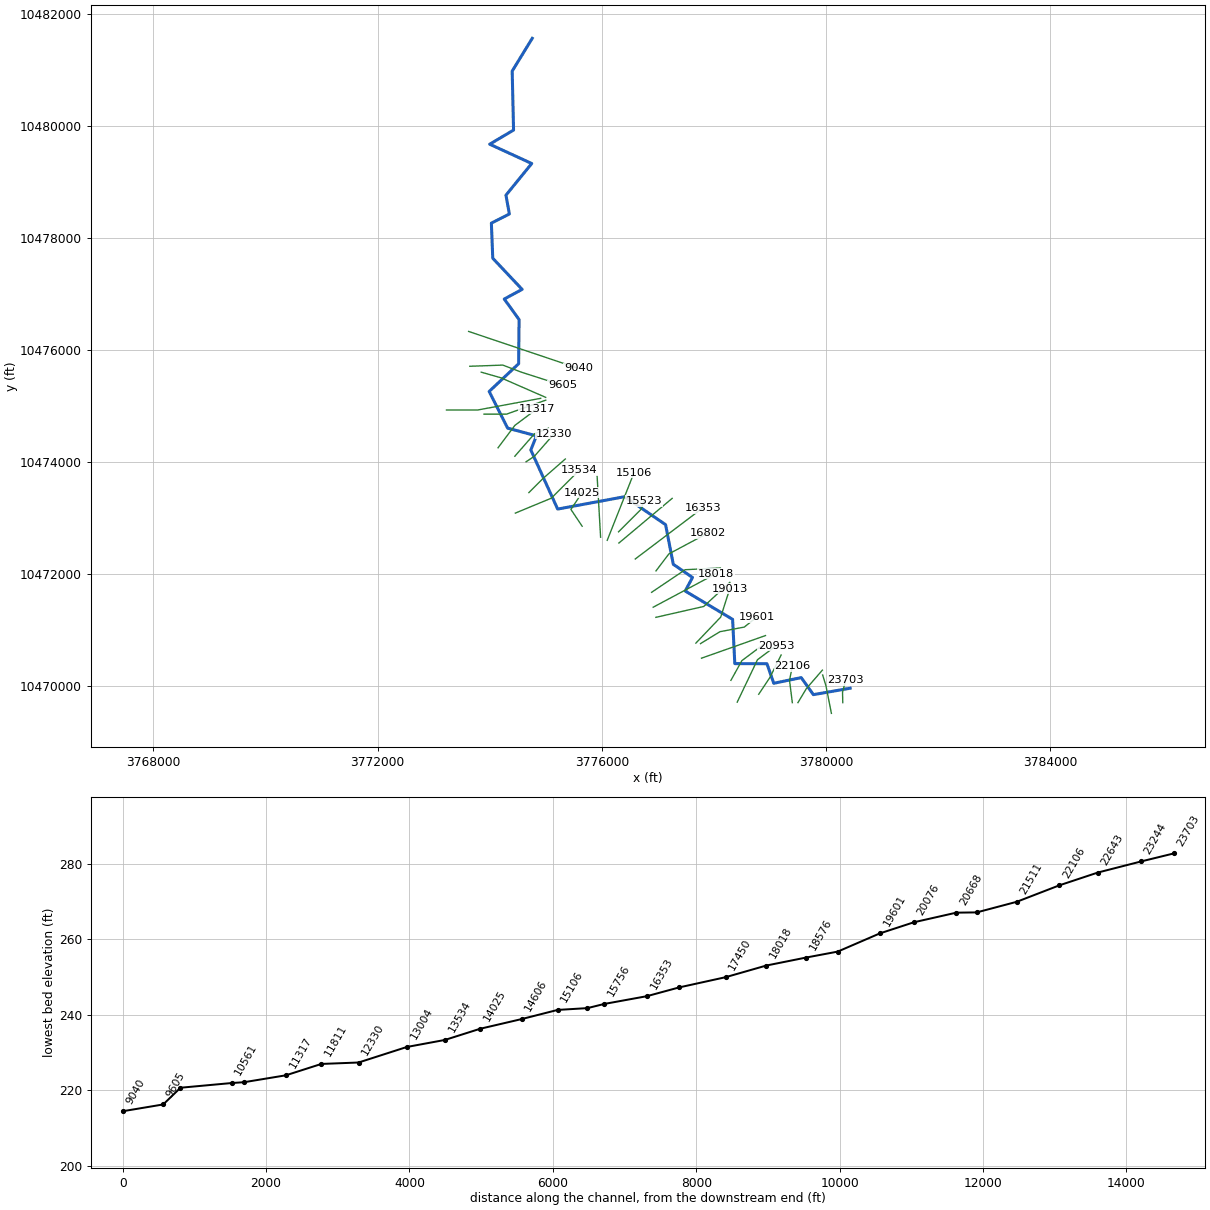
--- UNT070 IN BECR.prj (project) ---

Proj Title=UNT070 IN BECR Base Level Engineering
Current Plan=p01
Default Exp/Contr=0.3,0.1
English Units
Geom File=g01
Flow File=f01
Plan File=p01
Y Axis Title=Elevation
X Axis Title(PF)=Main Channel Distance
X Axis Title(XS)=Station
BEGIN DESCRIPTION:
UNT070 IN BECR
END DESCRIPTION:
DSS Export Rating Curves= 0
DSS Export Rating Curve Sorted= 0
DSS Export Volume Flow Curves= 0
DXF OffsetX= 0
DXF OffsetY= 0
DXF ScaleX= 1
DXF ScaleY= 10

--- UNT070 IN BECR.p01 (plan) ---

Plan Title=Multiple Run
Short Identifier=Multiple
Geom File=g01
Flow File=f01
Subcritical Flow
K Sum by GR= 0
Std Step Tol= 0.01
Critical Tol= 0.01
Num of Std Step Trials= 20
Max Error Tol= 0.3
Flow Tol Ratio= 0.001
Split Flow NTrial= 30
Split Flow Tol= 0.02
Split Flow Ratio= 0.02
Log Output Level= 0
Friction Slope Method= 1
Unsteady Friction Slope Method= 2
Unsteady Bridges Friction Slope Method= 1
Parabolic Critical Depth
Global Vel Dist=  1 , 1 , 1
Global Log Level= 0
CheckData=True
Encroach Param= -1, 0, 0, 0
BEGIN DESCRIPTION:
Multiple Run
END DESCRIPTION:

--- UNT070 IN BECR.f01 (steady flow) ---

Flow Title=Multiple
Number of Profiles=7
Profile Names=10-year,25-year,50-year,1pct_min,100-year,1pct_plu,500-year
River Rch & RM= UNT070 IN BECR,Reach-1,23703
     499     663     796     703     951    1286    1360
River Rch & RM= UNT070 IN BECR,Reach-1,22106
     710     963    1170    1045    1413    1911    2068
River Rch & RM= UNT070 IN BECR,Reach-1,13534
     950    1307    1605    1447    1956    2646    2917
River Rch & RM= UNT070 IN BECR,Reach-1,10734
    1045    1444    1779    1607    2173    2939    3256
River Rch & RM= UNT070 IN BECR,Reach-1,7891
    1071    1478    1819    1641    2219    3001    3316
Boundary for River Rch & Prof#=UNT070 IN BECR,Reach-1,1
Up Type=0
Dn Type=3
Dn Slope=0.005
Boundary for River Rch & Prof#=UNT070 IN BECR,Reach-1,2
Up Type=0
Dn Type=3
Dn Slope=0.005
Boundary for River Rch & Prof#=UNT070 IN BECR,Reach-1,3
Up Type=0
Dn Type=3
Dn Slope=0.005
Boundary for River Rch & Prof#=UNT070 IN BECR,Reach-1,4
Up Type=0
Dn Type=3
Dn Slope=0.005
Boundary for River Rch & Prof#=UNT070 IN BECR,Reach-1,5
Up Type=0
Dn Type=3
Dn Slope=0.005
Boundary for River Rch & Prof#=UNT070 IN BECR,Reach-1,6
Up Type=0
Dn Type=3
Dn Slope=0.005
Boundary for River Rch & Prof#=UNT070 IN BECR,Reach-1,7
Up Type=0
Dn Type=3
Dn Slope=0.005

--- UNT070 IN BECR.g01 (geometry) ---

Geom Title=Existing Conditions
Program Version=4.10

River Reach=UNT070 IN BECR  ,Reach-1
Reach XY= 30
      3780430.79     10469967.71       3779775.5       10469853.
        3779558.       10470157.       3779068.5       10470056.
      3778946.75       10470405.      3778373.25       10470407.
      3778334.25       10471197.       3777488.5       10471703.
       3777618.5       10471945.      3777275.92     10472180.26
      3777138.25       10472888.      3776408.25       10473387.
        3775213.       10473166.      3774734.25       10474221.
       3774834.5       10474473.       3774320.5       10474611.
        3773991.       10475266.        3774517.       10475761.
      3774524.75       10476550.       3774260.5       10476916.
      3774579.25       10477088.      3774055.25       10477644.
       3774030.5       10478271.      3774351.75       10478434.
       3774290.5       10478770.      3774750.25       10479335.
      3774000.25       10479680.      3774426.25       10479932.
      3774401.75       10480985.       3774759.5       10481570.

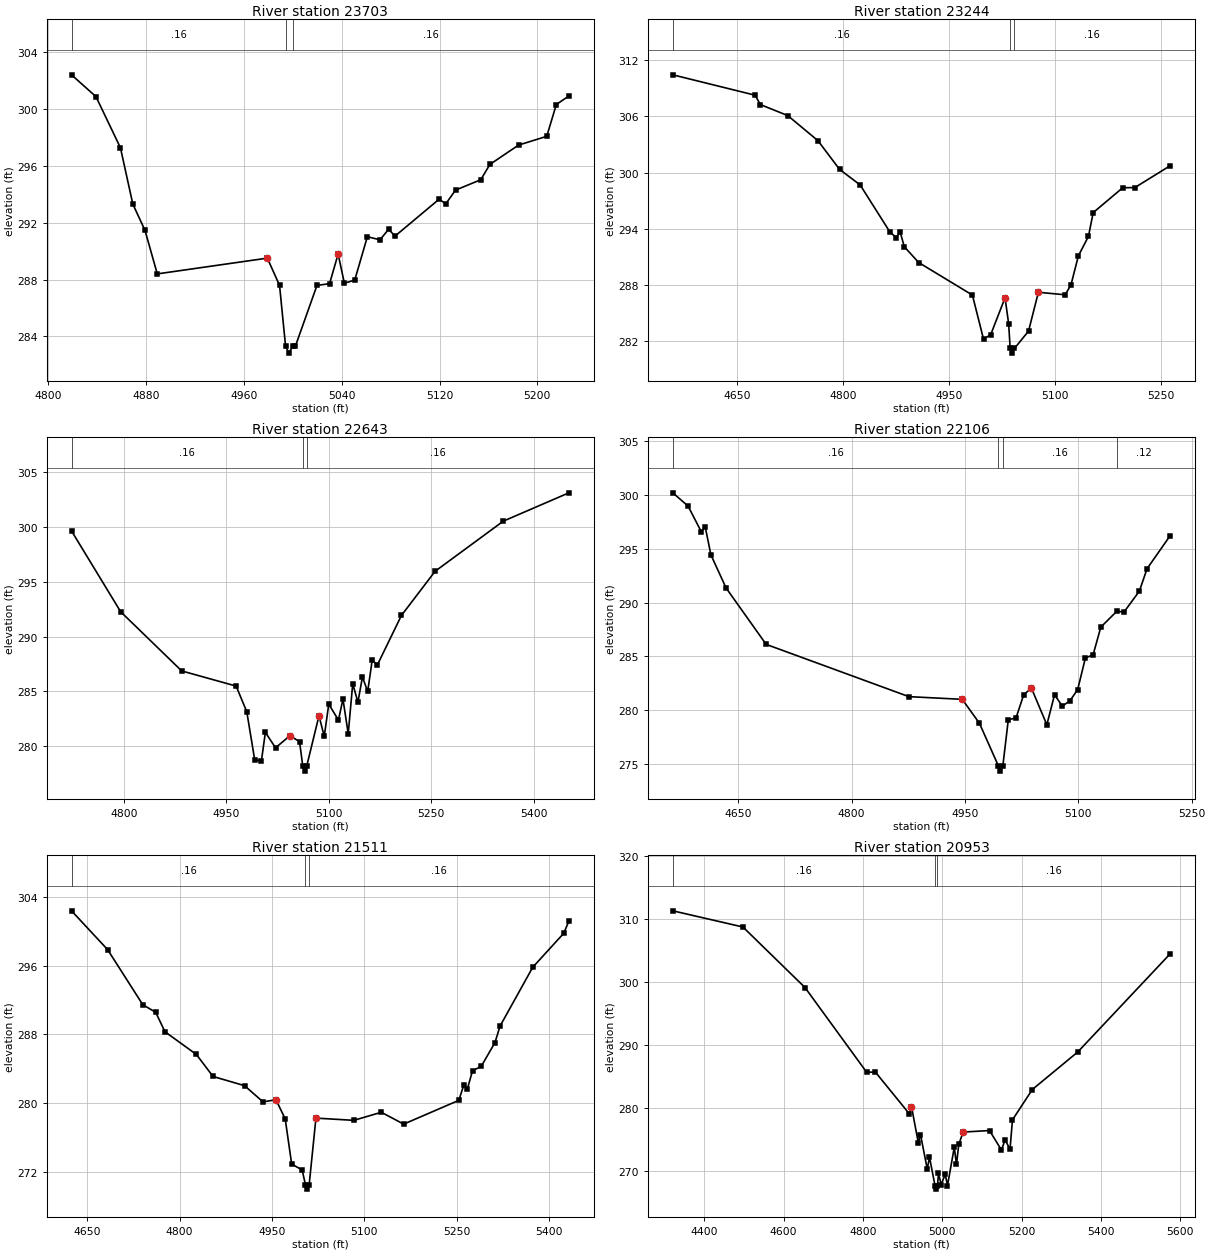
Type RM Length L Ch R = 1 ,23703   ,459,459,459
BEGIN DESCRIPTION:
UNT070 IN BECR 44.0
END DESCRIPTION:
XS GIS Cut Line= 3
      3780299.61     10469710.15      3780295.25       10469891.
       3780349.6     10470110.16
#Sta/Elev= 30
  4819.1  302.42  4839.1  300.88  4859.1  297.28  4869.2  293.32  4879.2  291.46
  4889.2   288.4  4979.2  289.51  4989.2  287.59  4994.1  283.32  4996.8  282.82
  5000.1  283.32  5002.2  283.32  5019.8  287.59  5030.1  287.71  5037.1   289.8
  5042.2  287.74  5050.7  287.97    5061  291.02  5071.3   290.8  5078.4  291.54
  5083.6  291.06  5119.8  293.67    5125  293.32  5133.1   294.3  5153.7  295.03
  5161.2  296.11  5184.6  297.47  5207.7  298.09  5215.5  300.33  5225.8  300.93
#Mann= 3 ,-1 , 0
  4819.1     .16       0  4994.1     .07       0  5000.1     .16       0
Bank Sta=4979.2,5037.1
XS Rating Curve= 0 ,0
Exp/Cntr=0.3,0.1

Type RM Length L Ch R = 1 ,23244   ,601,601,601
BEGIN DESCRIPTION:
UNT070 IN BECR 43.0
END DESCRIPTION:
XS GIS Cut Line= 3
      3780096.77     10469518.67      3779999.61     10470010.19
      3779940.51     10470204.46
#Sta/Elev= 30
  4559.3  310.45  4675.8  308.27  4683.2  307.27    4722  306.09  4764.7  303.41
  4795.3  300.34  4824.5  298.67  4866.7  293.63  4875.8  293.03  4880.9  293.69
    4887  292.06  4907.4  290.37  4983.4  286.89  4999.2  282.16  5009.4  282.67
  5029.6   286.6  5034.7  283.84  5036.9  281.18  5039.7  280.68  5042.9  281.18
  5062.9  283.04  5076.8  287.19  5114.8  286.92    5123     288  5133.5   291.1
  5147.7  293.17  5154.4  295.71  5196.2  298.37  5213.4  298.39  5263.4  300.73
#Mann= 3 ,-1 , 0
  4559.3     .16       0  5036.9     .07       0  5042.9     .16       0
Bank Sta=5029.6,5076.8
XS Rating Curve= 0 ,0
Exp/Cntr=0.3,0.1

Type RM Length L Ch R = 1 ,22643   ,537,537,537
BEGIN DESCRIPTION:
UNT070 IN BECR 42.0
END DESCRIPTION:
XS GIS Cut Line= 3
       3779499.6     10469710.17      3779649.61     10469960.19
      3779935.37     10470290.32
#Sta/Elev= 30
  4723.3  299.61  4795.2  292.26  4884.6  286.87  4964.3  285.49  4979.9  283.15
  4991.5  278.77  5001.3  278.68  5007.1  281.28    5022  279.87  5042.9  280.97
  5057.1  280.44  5061.8  278.25  5064.5  277.75  5067.8  278.25  5085.6  282.79
  5093.3  280.91  5099.9  283.85  5114.1  282.39  5120.7  284.31  5128.4  281.15
    5135  285.71  5142.6  284.02  5149.2  286.32  5156.9     285  5163.5  287.84
  5171.1  287.42  5206.3  291.92  5255.6  295.94  5355.4   300.5  5451.5  303.08
#Mann= 3 ,-1 , 0
  4723.3     .16       0  5061.8     .07       0  5067.8     .16       0
Bank Sta=5042.9,5085.6
XS Rating Curve= 0 ,0
Exp/Cntr=0.3,0.1

Type RM Length L Ch R = 1 ,22106   ,595,595,595
BEGIN DESCRIPTION:
UNT070 IN BECR 41.0
END DESCRIPTION:
XS GIS Cut Line= 3
      3779399.61     10469710.19      3779349.61     10470110.19
      3779399.62     10470360.22
#Sta/Elev= 30
  4563.4  300.18  4583.6  298.95  4601.2  296.55  4606.2  297.05  4613.8  294.42
  4633.9  291.35  4686.9  286.12  4875.8  281.27  4946.4  281.02  4969.1   278.8
  4994.1  274.86  4996.9  274.36  5000.1  274.86  5007.3  279.13  5017.5  279.29
  5027.7  281.45  5037.9  282.06  5058.3  278.66  5068.5  281.45  5078.7  280.39
  5088.9  280.89  5099.1  281.93  5109.3  284.86  5119.5  285.15  5129.7  287.72
    5151   289.2  5160.3  289.11  5180.7  291.06  5190.9  293.14  5221.5  296.21
#Mann= 4 ,-1 , 0
  4563.4     .16       0  4994.1     .07       0  5000.1     .16       0
    5151     .12       0
Bank Sta=4946.4,5037.9
XS Rating Curve= 0 ,0
Exp/Cntr=0.3,0.1

Type RM Length L Ch R = 1 ,21511   ,558,558,558
BEGIN DESCRIPTION:
UNT070 IN BECR 40.0
END DESCRIPTION:
XS GIS Cut Line= 3
      3778799.62     10469860.21      3778999.61     10470160.19
      3779199.59     10470560.15
#Sta/Elev= 30
  4624.6   302.4  4683.2  297.88  4740.3  291.47  4761.3  290.58  4776.3  288.32
  4827.4  285.67  4854.4  283.11  4905.5  282.04  4935.6  280.15  4956.6   280.4
  4971.6  278.16  4982.1  272.91  4999.1  272.22  5004.5  270.49  5007.2  269.99
  5010.5  270.49  5021.5  278.26    5083     278  5127.7  278.94    5164  277.56
  5253.5  280.33  5261.8  282.14  5267.4  281.65  5275.8  283.78  5289.8  284.28
  5312.2  287.05  5320.5  288.98  5373.6  295.83    5424  299.79  5432.3  301.22
#Mann= 3 ,-1 , 0
  4624.6     .16       0  5004.5     .07       0  5010.5     .16       0
Bank Sta=4956.6,5021.5
XS Rating Curve= 0 ,0
Exp/Cntr=0.3,0.1

Type RM Length L Ch R = 1 ,20953   ,285,285,285
BEGIN DESCRIPTION:
UNT070 IN BECR 39.0
END DESCRIPTION:
XS GIS Cut Line= 3
      3778416.64     10469719.24      3778777.75     10470476.17
      3779110.43     10470725.67
#Sta/Elev= 30
  4320.4  311.36  4497.3  308.79  4653.8  299.18    4809  285.76  4831.6  285.74
  4916.9  279.14  4922.4  280.27  4939.6  274.56  4945.1  275.85  4962.2  270.36
  4967.8  272.25  4981.9  267.68  4984.7  267.18  4987.9  267.68  4990.5  269.68
  4997.3   267.9  5007.6  269.55  5013.2  267.73  5030.3  273.81  5035.9   271.1
  5041.6  274.28  5052.7  276.24  5119.2  276.48  5149.3  273.39  5158.5  275.01
  5170.9   273.5  5177.1  278.18  5227.1  282.99  5341.7  288.95  5574.9  304.54
#Mann= 3 ,-1 , 0
  4320.4     .16       0  4981.9     .07       0  4987.9     .16       0
Bank Sta=4922.4,5052.7
XS Rating Curve= 0 ,0
Exp/Cntr=0.3,0.1

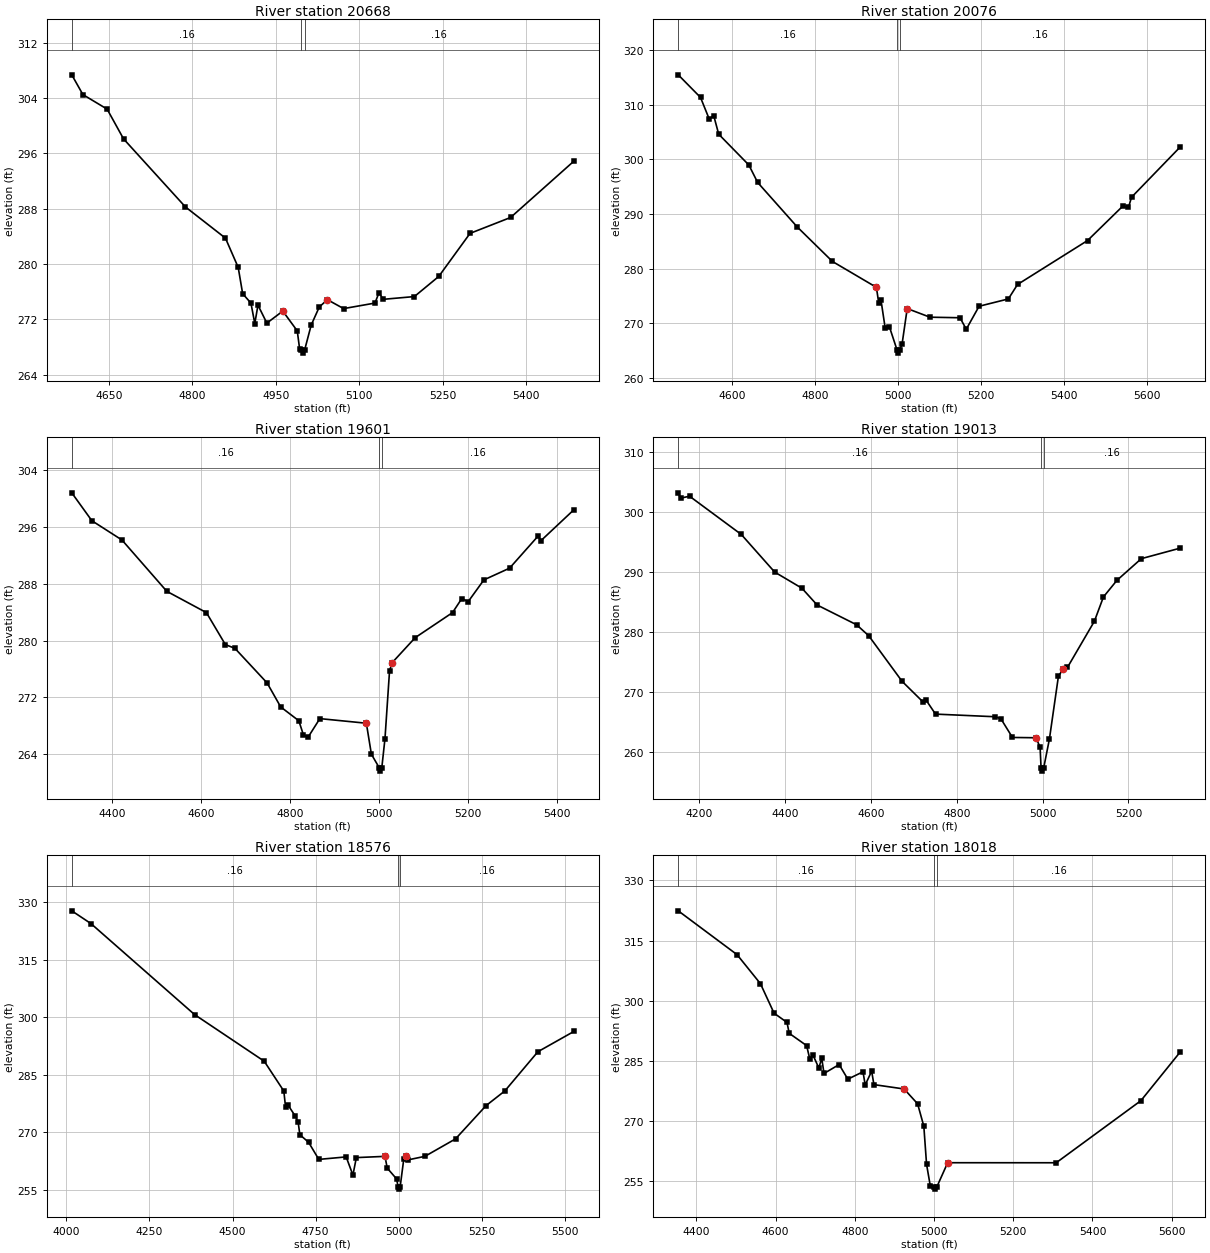
Type RM Length L Ch R = 1 ,20668   ,592,592,592
BEGIN DESCRIPTION:
UNT070 IN BECR 38.0
END DESCRIPTION:
XS GIS Cut Line= 3
      3778304.21     10470108.91      3778499.61     10470460.19
      3778899.63     10470760.21
#Sta/Elev= 30
  4583.4  307.36  4603.4   304.5  4646.9   302.4  4676.4   298.1  4787.5  288.26
  4859.5  283.74  4882.4  279.51  4890.4  275.71  4905.3  274.34  4912.2  271.39
  4917.9  274.05  4933.9  271.45  4962.5  273.19  4988.5  270.33  4992.7  267.75
  4995.9  267.61  4998.7  267.11  5001.9  267.61  5013.5  271.16  5028.1  273.79
  5042.7  274.84  5071.8  273.55  5128.1  274.35  5135.4  275.86  5142.7  274.89
  5198.9  275.29  5242.7   278.2  5298.9  284.43  5371.8  286.73  5485.4  294.87
#Mann= 3 ,-1 , 0
  4583.4     .16       0  4995.9     .07       0  5001.9     .16       0
Bank Sta=4962.5,5042.7
XS Rating Curve= 0 ,0
Exp/Cntr=0.3,0.1

Type RM Length L Ch R = 1 ,20076   ,475,475,475
BEGIN DESCRIPTION:
UNT070 IN BECR 37.0
END DESCRIPTION:
XS GIS Cut Line= 2
      3777779.02     10470503.91      3778920.55     10470907.57
#Sta/Elev= 30
  4469.5  315.45  4523.2  311.32  4544.4  307.33    4555  308.01  4567.1  304.59
  4639.8  298.96    4661  295.77  4756.5  287.63  4841.4  281.32  4947.4  276.59
    4953  273.71  4958.3  274.33  4968.6  269.13  4978.6  269.41  4997.5  265.06
  5000.2  264.56  5003.5  265.06  5009.5  266.32  5021.7  272.71  5076.6  271.13
    5149  271.03  5164.1  268.93    5195  273.13  5265.6  274.47  5287.7  277.11
  5456.6  285.15  5541.4  291.43  5555.3   291.2  5562.6  293.06  5680.3  302.28
#Mann= 3 ,-1 , 0
  4469.5     .16       0  4997.5     .07       0  5003.5     .16       0
Bank Sta=4947.4,5021.7
XS Rating Curve= 0 ,0
Exp/Cntr=0.3,0.1

Type RM Length L Ch R = 1 ,19601   ,588,588,588
BEGIN DESCRIPTION:
UNT070 IN BECR 36.0
END DESCRIPTION:
XS GIS Cut Line= 4
      3777761.72     10470764.35      3778108.92     10470977.01
      3778542.95     10471059.47        3778760.     10471233.12
#Sta/Elev= 30
  4310.1  300.83  4355.2   296.9  4422.8  294.18  4523.4  286.95  4612.3  283.95
  4654.9  279.44  4676.2  278.92  4748.5  274.04    4779  270.66  4819.7  268.71
  4829.9  266.74  4840.1  266.35  4866.9  269.01  4971.3  268.36  4982.6  263.99
    5000  262.11  5002.7  261.61    5006  262.11  5013.1   266.2  5023.3  275.71
  5028.7  276.86  5080.9  280.42  5164.7  283.95  5185.5  285.93  5199.9   285.5
  5235.1  288.56  5292.7  290.21  5356.8  294.74  5363.2  294.09    5437  298.44
#Mann= 3 ,-1 , 0
  4310.1     .16       0    5000     .07       0    5006     .16       0
Bank Sta=4971.3,5028.7
XS Rating Curve= 0 ,0
Exp/Cntr=0.3,0.1

Type RM Length L Ch R = 1 ,19013   ,437,437,437
BEGIN DESCRIPTION:
UNT070 IN BECR 35.0
END DESCRIPTION:
XS GIS Cut Line= 3
       3777679.2     10470772.99      3778121.94     10471237.43
      3778282.52     10471740.88
#Sta/Elev= 30
  4150.7  303.15  4156.1  302.27  4177.2  302.58  4297.7  296.21  4375.4  289.95
  4438.9  287.26  4474.4  284.46  4566.3  281.17  4594.6  279.34  4672.3  271.75
    4722  268.25  4728.9  268.55  4750.3  266.28  4889.7  265.84  4902.7   265.5
  4929.6  262.39  4984.2  262.34    4994  260.78  4996.3  257.28    4999  256.78
  5002.3  257.28  5015.7  262.11  5036.7  272.57  5047.2  273.75  5057.7  274.05
  5120.6  281.76  5141.6   285.8  5173.1  288.57  5229.9  292.18  5320.8  293.94
#Mann= 3 ,-1 , 0
  4150.7     .16       0  4996.3     .07       0  5002.3     .16       0
Bank Sta=4984.2,5047.2
XS Rating Curve= 0 ,0
Exp/Cntr=0.3,0.1

Type RM Length L Ch R = 1 ,18576   ,558,558,558
BEGIN DESCRIPTION:
UNT070 IN BECR 34.0
END DESCRIPTION:
XS GIS Cut Line= 3
       3776965.2      10471233.1      3777819.42     10471427.55
      3778284.63     10471858.05
#Sta/Elev= 30
  4016.5  327.77  4074.2  324.44  4385.7  300.73  4595.3  288.56  4654.2  280.79
  4659.3  276.69  4667.1  277.11  4687.6  274.39  4697.2  272.75  4702.4  269.41
  4728.7  267.43  4759.4  262.97  4841.7  263.62    4862  258.88  4872.3  263.44
  4958.4  263.76  4965.2   260.7  4993.6  257.85  4997.9  255.72  5000.7  255.22
  5003.9  255.72  5015.1  263.16  5021.9   263.9  5029.1  262.87  5078.6  263.77
  5170.5  268.31  5262.3  276.98    5319  280.83  5418.3  291.04  5526.4  296.32
#Mann= 3 ,-1 , 0
  4016.5     .16       0  4997.9     .07       0  5003.9     .16       0
Bank Sta=4958.4,5021.9
XS Rating Curve= 0 ,0
Exp/Cntr=0.3,0.1

Type RM Length L Ch R = 1 ,18018   ,568,568,568
BEGIN DESCRIPTION:
UNT070 IN BECR 33.0
END DESCRIPTION:
XS GIS Cut Line= 2
      3776916.61     10471413.65      3778034.61     10472010.84
#Sta/Elev= 30
  4354.2  322.43  4502.7  311.51  4561.7  304.28  4596.1  296.93  4628.7  294.63
  4634.4  291.91  4678.3  288.85  4686.4  285.48  4694.5  286.47  4709.1  283.27
  4716.5  285.67  4722.2  281.91  4760.4  284.13  4782.3  280.49  4820.6  282.32
  4826.2  279.04  4842.5  282.48  4848.2  279.13  4924.5  278.04  4958.5  274.35
  4974.2  268.76  4981.1  259.28  4990.5   253.9  5000.8  253.59  5003.6  253.09
  5006.8  253.59  5034.4  259.67  5308.4  259.66  5522.2  275.13  5621.7  287.29
#Mann= 3 ,-1 , 0
  4354.2     .16       0  5000.8     .07       0  5006.8     .16       0
Bank Sta=4924.5,5034.4
XS Rating Curve= 0 ,0
Exp/Cntr=0.3,0.1

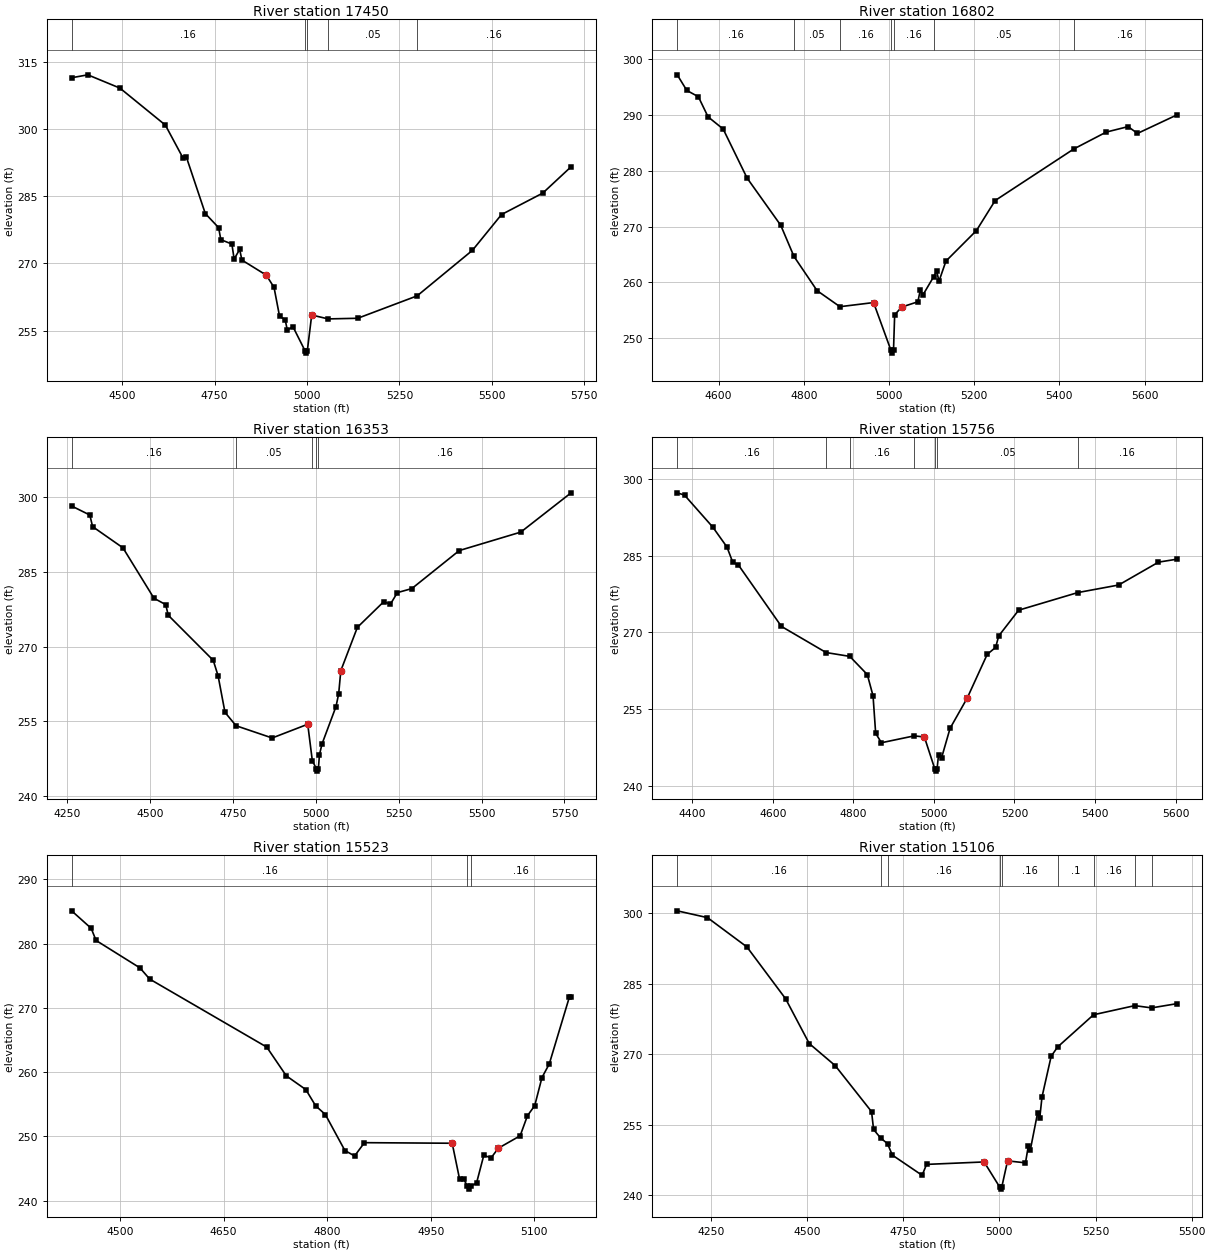
Type RM Length L Ch R = 1 ,17450   ,648,648,648
BEGIN DESCRIPTION:
UNT070 IN BECR 32.0
END DESCRIPTION:
XS GIS Cut Line= 3
      3776889.32     10471680.15      3777488.26     10472083.78
      3778116.08     10472114.09
#Sta/Elev= 30
  4363.5   311.4  4407.2  312.05  4494.1  309.09    4617  300.84  4665.3  293.42
    4674  293.67    4725  281.12    4761  277.98    4767   275.3  4796.9  274.32
    4803  270.98    4818  273.12    4824  270.75  4889.9  267.39  4910.9  264.66
  4925.9  258.19  4940.9  257.48  4946.9  255.11  4961.9  255.92  4994.9   250.5
  4997.6     250  5000.9   250.5  5012.8   258.5  5057.2  257.63  5137.2  257.77
    5298  262.77  5447.5  272.92  5526.2   280.9  5637.7  285.68  5714.3  291.55
#Mann= 5 ,-1 , 0
  4363.5     .16       0  4994.9     .07       0  5000.9     .16       0
  5057.2     .05       0    5298     .16       0
Bank Sta=4889.9,5012.8
XS Rating Curve= 0 ,0
Exp/Cntr=0.3,0.1

Type RM Length L Ch R = 1 ,16802   ,449,449,449
BEGIN DESCRIPTION:
UNT070 IN BECR 31.0
END DESCRIPTION:
XS GIS Cut Line= 3
      3776967.42     10472062.07      3777197.46      10472365.9
      3777895.43     10472738.73
#Sta/Elev= 30
  4503.1  297.21  4525.6  294.41  4552.7  293.28  4575.5  289.67  4610.9  287.49
  4667.1  278.69  4746.1  270.22  4777.1  264.64  4831.4   258.5    4885  255.62
    4964  256.36  5004.8  247.79  5007.6  247.29  5010.8  247.79  5013.5  254.15
  5029.8  255.55    5068   256.5  5073.7  258.62  5079.4  257.67  5104.8  260.96
  5111.9  262.01  5117.6   260.2  5133.9   263.8  5205.4  269.27  5249.4  274.66
  5434.2  283.92  5510.2  286.94  5561.5  287.92  5583.5   286.7  5675.5     290
#Mann= 7 ,-1 , 0
  4503.1     .16       0  4777.1     .05       0    4885     .16       0
  5004.8     .07       0  5010.8     .16       0  5104.8     .05       0
  5434.2     .16       0
Bank Sta=4964,5029.8
XS Rating Curve= 0 ,0
Exp/Cntr=0.3,0.1

Type RM Length L Ch R = 1 ,16353   ,597,597,597
BEGIN DESCRIPTION:
UNT070 IN BECR 30.0
END DESCRIPTION:
XS GIS Cut Line= 2
      3776597.18     10472274.77       3777798.6     10473184.51
#Sta/Elev= 30
    4263  298.24  4317.9  296.43  4326.2   294.1  4417.8  289.84  4511.4  279.71
  4546.8  278.43  4554.5  276.29  4690.3  267.23  4704.9  264.12  4725.7  256.78
  4759.1  254.09  4868.1  251.63  4975.4  254.39  4989.3  247.04  5001.5  245.47
  5004.2  244.97  5007.5  245.47  5010.8  248.29  5018.7  250.47  5060.7  257.95
  5068.8  260.53  5075.2  265.15  5125.2  273.86  5204.2  278.98  5225.1  278.54
  5245.9  280.84  5289.5  281.65  5432.6  289.29  5618.3     293    5770  300.89
#Mann= 5 ,-1 , 0
    4263     .16       0  4759.1     .05       0  4989.3     .16       0
  5001.5     .07       0  5007.5     .16       0
Bank Sta=4975.4,5075.2
XS Rating Curve= 0 ,0
Exp/Cntr=0.3,0.1

Type RM Length L Ch R = 1 ,15756   ,233,233,233
BEGIN DESCRIPTION:
UNT070 IN BECR 29.0
END DESCRIPTION:
XS GIS Cut Line= 2
      3776305.55     10472559.52      3777255.76     10473357.14
#Sta/Elev= 30
  4362.3   297.3  4380.4  296.85  4450.7  290.59  4485.8  286.71  4500.1  283.75
  4514.4  283.18  4621.1  271.19  4732.1  266.08  4790.9  265.33  4834.4  261.78
  4848.7  257.62  4855.2   250.3  4869.5  248.45  4950.8  249.79  4976.2  249.58
  5001.8   243.4  5004.6   242.9  5007.8   243.4  5011.3  246.01  5019.1  245.55
    5040  251.26  5082.9  257.23  5132.3  265.73  5153.2  267.09  5160.9  269.33
  5210.4  274.36  5357.2   277.8  5458.8  279.28  5557.7  283.75  5602.9  284.32
#Mann= 7 ,-1 , 0
  4362.3     .16       0  4732.1     .12       0  4790.9     .16       0
  4950.8     .05       0  5001.8    .035       0  5007.8     .05       0
  5357.2     .16       0
Bank Sta=4976.2,5082.9
XS Rating Curve= 0 ,0
Exp/Cntr=0.3,0.1

Type RM Length L Ch R = 1 ,15523   ,417,417,417
BEGIN DESCRIPTION:
UNT070 IN BECR 28.0
END DESCRIPTION:
XS GIS Cut Line= 3
      3776299.61     10472760.19      3776699.61     10473160.19
      3776749.61     10473310.19
#Sta/Elev= 30
  4429.7  285.11    4458  282.39  4465.1   280.5  4528.7  276.23  4542.8  274.49
  4712.5   263.9  4740.8  259.43  4769.1  257.29  4783.3  254.77  4797.4  253.41
  4825.7  247.81  4839.8  246.96    4854  249.03  4981.2  248.94  4991.9  243.37
    4998  243.37  5002.9   242.3  5005.7   241.8  5008.9   242.3  5016.5  242.75
    5027  247.06  5037.6  246.67  5048.1  248.17  5079.7   250.1  5090.3  253.23
  5100.8  254.79  5111.3  259.16  5121.9  261.28  5150.9  271.64  5153.5  271.64
#Mann= 3 ,-1 , 0
  4429.7     .16       0  5002.9     .07       0  5008.9     .16       0
Bank Sta=4981.2,5048.1
XS Rating Curve= 0 ,0
Exp/Cntr=0.3,0.1

Type RM Length L Ch R = 1 ,15106   ,500,500,500
BEGIN DESCRIPTION:
UNT070 IN BECR 27.0
END DESCRIPTION:
XS GIS Cut Line= 2
      3776097.18     10472608.09       3776576.1     10473815.79
#Sta/Elev= 30
  4161.9   300.5  4240.6  299.05  4343.2  292.82  4443.9  281.79  4505.3  272.28
  4572.9  267.58  4667.4   257.8  4672.7     254  4691.2  252.17  4708.9     251
  4721.4  248.56  4798.9  244.26  4810.5  246.58  4960.2   247.1  5000.3  241.82
    5003  241.32  5006.3  241.82  5021.2  247.33  5067.8  246.91  5075.2  250.48
  5080.6  249.74  5099.5   257.6  5104.9  256.43  5110.8  260.93  5134.6  269.56
  5151.3  271.54  5244.9   278.4  5352.1  280.34  5395.9  279.86  5461.1  280.75
#Mann= 9 ,-1 , 0
  4161.9     .16       0  4691.2     .05       0  4708.9     .16       0
  5000.3     .07       0  5006.3     .16       0  5151.3      .1       0
  5244.9     .16       0  5352.1      .1       0  5395.9     .16       0
Bank Sta=4960.2,5021.2
XS Rating Curve= 0 ,0
Exp/Cntr=0.3,0.1

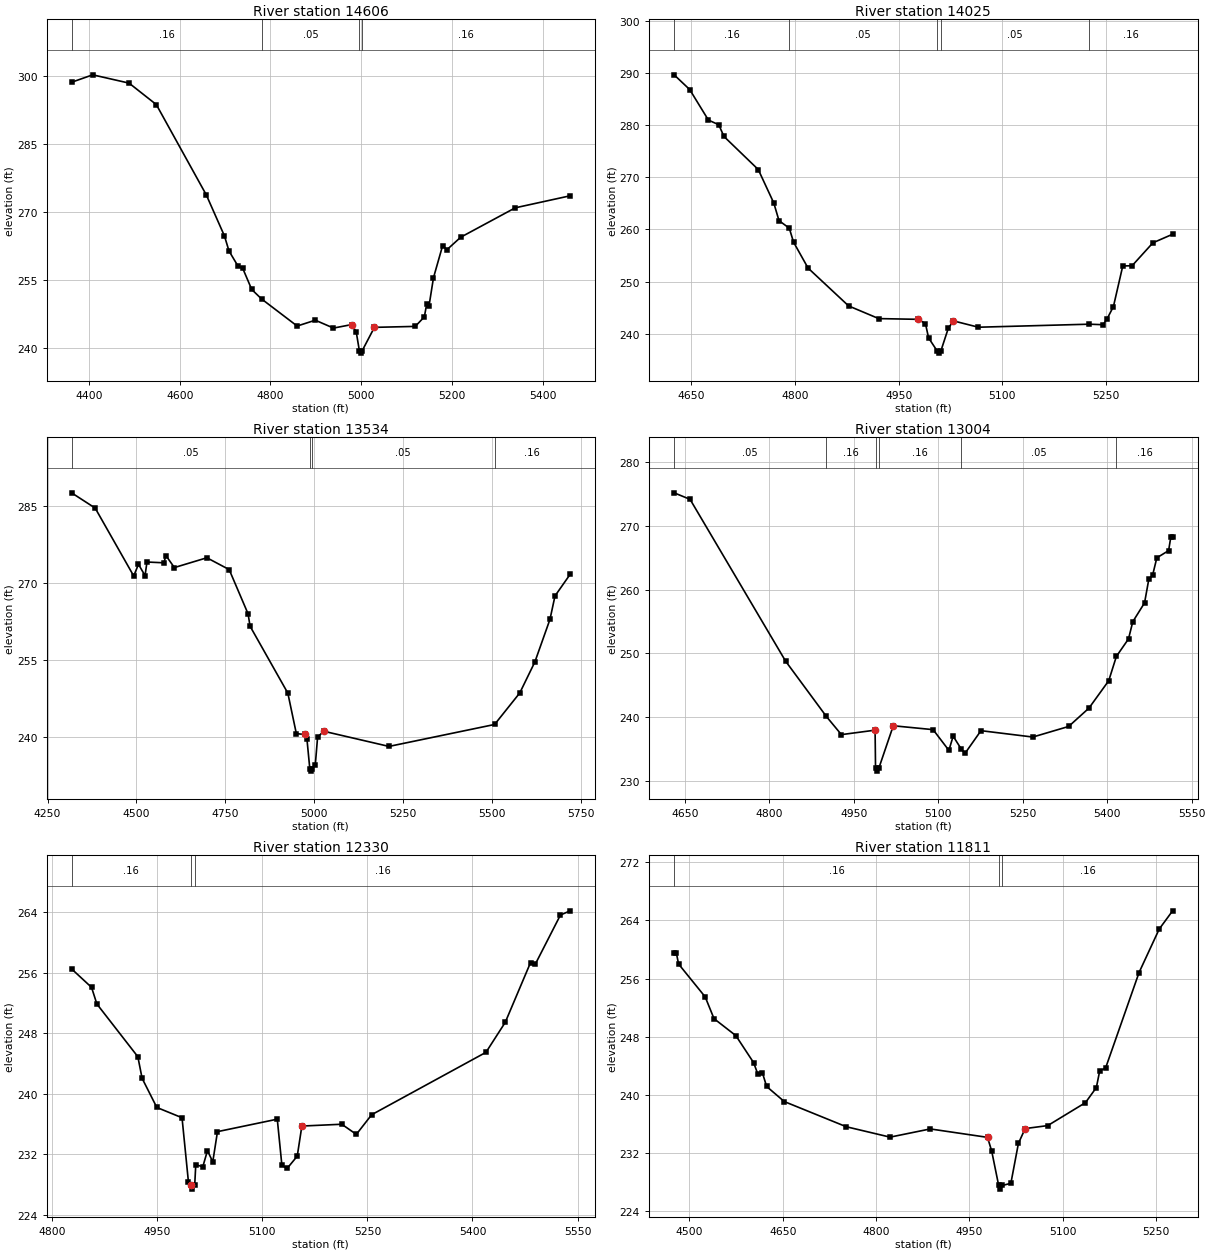
Type RM Length L Ch R = 1 ,14606   ,581,581,581
BEGIN DESCRIPTION:
UNT070 IN BECR 26.0
END DESCRIPTION:
XS GIS Cut Line= 2
      3775979.14     10472663.71      3775916.64     10473760.93
#Sta/Elev= 30
  4361.6   298.7  4408.2  300.34  4488.3  298.51  4548.4  293.77  4658.6  273.83
  4698.6  264.77  4708.6  261.46  4728.7  258.07  4738.7  257.67  4758.7  252.96
  4780.3  250.87  4858.9  244.88  4898.9  246.17    4939  244.43  4979.1   245.2
  4989.1   243.6  4996.1   239.4  4998.9   238.9  5002.1   239.4  5029.2  244.59
  5119.3   244.8  5139.3  246.91  5144.5  249.74  5149.5  249.25  5159.4  255.53
  5179.4  262.56  5189.4  261.76  5219.5  264.49  5339.7  270.98  5460.6  273.63
#Mann= 4 ,-1 , 0
  4361.6     .16       0  4780.3     .05       0  4996.1     .07       0
  5002.1     .16       0
Bank Sta=4979.1,5029.2
XS Rating Curve= 0 ,0
Exp/Cntr=0.3,0.1

Type RM Length L Ch R = 1 ,14025   ,491,491,491
BEGIN DESCRIPTION:
UNT070 IN BECR 25.0
END DESCRIPTION:
XS GIS Cut Line= 3
      3775649.62     10472860.18      3775449.61     10473160.19
       3775649.6     10473460.17
#Sta/Elev= 30
  4625.1   289.6  4647.6  286.79  4674.7  280.94  4689.7  280.04  4697.2   277.8
  4746.8  271.47  4769.3  265.06  4776.8  261.69  4791.7  260.24  4797.9  257.56
  4818.9   252.6  4877.5  245.36  4921.1  242.93  4978.2  242.79  4988.7  241.96
  4993.2  239.24  5005.2  236.82    5008  236.32  5011.2  236.82  5021.7  241.07
  5029.2  242.49  5065.3  241.28  5225.7  241.86  5245.6  241.76  5251.6  242.93
  5260.6  245.24  5274.1  253.01  5287.6  253.05  5317.7  257.44  5346.2  259.08
#Mann= 5 ,-1 , 0
  4625.1     .16       0  4791.7     .05       0  5005.2    .035       0
  5011.2     .05       0  5225.7     .16       0
Bank Sta=4978.2,5029.2
XS Rating Curve= 0 ,0
Exp/Cntr=0.3,0.1

Type RM Length L Ch R = 1 ,13534   ,530,530,530
BEGIN DESCRIPTION:
UNT070 IN BECR 24.0
END DESCRIPTION:
XS GIS Cut Line= 3
      3774458.35     10473094.24      3775099.61     10473360.19
      3775599.59     10473860.17
#Sta/Elev= 30
  4317.7  287.53    4384  284.56  4492.3  271.35  4505.7  273.61  4524.2  271.41
  4529.6  274.06  4577.3  273.91  4582.8  275.33  4606.6  272.98    4698  274.89
  4760.7  272.59  4813.9  263.96  4819.3  261.58  4925.6  248.54  4949.5  240.66
  4973.4  240.49  4979.4  239.53  4987.3  233.86    4990  233.36  4993.3  233.86
  5002.7  234.53  5009.2  239.95  5026.1  241.13  5209.9  238.17  5506.8  242.44
  5577.6  248.58    5620  254.61  5662.5  262.91  5676.6  267.46    5719  271.65
#Mann= 4 ,-1 , 0
  4317.7     .05       0  4987.3    .035       0  4993.3     .05       0
  5506.8     .16       0
Bank Sta=4973.4,5026.1
XS Rating Curve= 0 ,0
Exp/Cntr=0.3,0.1

Type RM Length L Ch R = 1 ,13004   ,674,674,674
BEGIN DESCRIPTION:
UNT070 IN BECR 23.0
END DESCRIPTION:
XS GIS Cut Line= 3
      3774699.63     10473460.21      3774949.61     10473710.19
      3775349.59     10474060.17
#Sta/Elev= 30
  4631.2  275.18  4659.5  274.16  4829.2  248.75  4901.5  240.08  4928.2  237.23
    4988  237.93  4988.8     232  4991.6   231.5  4994.8     232  5020.3  238.62
    5091  238.01    5119  234.76  5126.6  236.98  5140.9  234.98  5147.5  234.27
    5176  237.85    5268  236.85  5331.6  238.51  5367.7  241.39  5402.8  245.69
  5416.4  249.51  5437.9  252.25  5445.5  254.95  5466.4  257.91    5474  261.64
  5480.6  262.22  5488.2  264.98  5509.1  266.11  5512.9  268.18  5516.2  268.18
#Mann= 6 ,-1 , 0
  4631.2     .05       0  4901.5     .16       0  4988.8     .07       0
  4994.8     .16       0  5140.9     .05       0  5416.4     .16       0
Bank Sta=4988,5020.3
XS Rating Curve= 0 ,0
Exp/Cntr=0.3,0.1

Type RM Length L Ch R = 1 ,12330   ,519,519,519
BEGIN DESCRIPTION:
UNT070 IN BECR 22.0
END DESCRIPTION:
XS GIS Cut Line= 3
      3774649.61     10474010.19      3774799.61     10474110.19
      3775149.62      10474510.2
#Sta/Elev= 30
  4827.6   256.5  4856.1  254.06  4863.7  251.86  4922.2  244.89  4928.3  242.03
  4949.3  238.18  4985.3  236.82  4994.4  228.37  4997.4  227.88  5000.1  227.38
  5003.4  227.88  5004.9   230.6    5015  230.35  5021.6  232.47  5029.2  230.99
  5035.9  234.98  5121.3  236.63  5127.9  230.52  5135.5  230.13  5149.8  231.74
  5156.4  235.72  5213.4  235.96  5234.2  234.62  5256.1  237.22  5419.3  245.47
  5446.8  249.43  5482.9  257.33  5489.6   257.1  5525.6  263.62  5539.4  264.18
#Mann= 3 ,-1 , 0
  4827.6     .16       0  4997.4     .07       0  5003.4     .16       0
Bank Sta=4997.4,5156.4
XS Rating Curve= 0 ,0
Exp/Cntr=0.3,0.1

Type RM Length L Ch R = 1 ,11811   ,494,494,494
BEGIN DESCRIPTION:
UNT070 IN BECR 21.0
END DESCRIPTION:
XS GIS Cut Line= 3
      3774449.59     10474110.16      3774799.61     10474510.19
      3775049.61     10474610.19
#Sta/Elev= 30
  4475.5  259.59  4478.9  259.59  4482.7     258  4525.4  253.48  4539.6  250.48
  4574.7  248.14  4603.2  244.42  4609.8  242.89  4617.4  243.01  4624.1  241.14
  4652.5  239.06  4752.2  235.59  4822.4  234.16    4887  235.29    4979  234.13
  4985.7  232.23  4996.9   227.5  4999.7     227  5002.9   227.5  5016.5  227.81
  5028.6   233.3  5039.4  235.34  5075.7  235.75  5136.3  238.91  5153.8  240.99
  5159.2  243.29  5168.6  243.67  5222.4  256.83  5254.8  262.82  5276.3  265.33
#Mann= 3 ,-1 , 0
  4475.5     .16       0  4996.9     .07       0  5002.9     .16       0
Bank Sta=4979,5039.4
XS Rating Curve= 0 ,0
Exp/Cntr=0.3,0.1

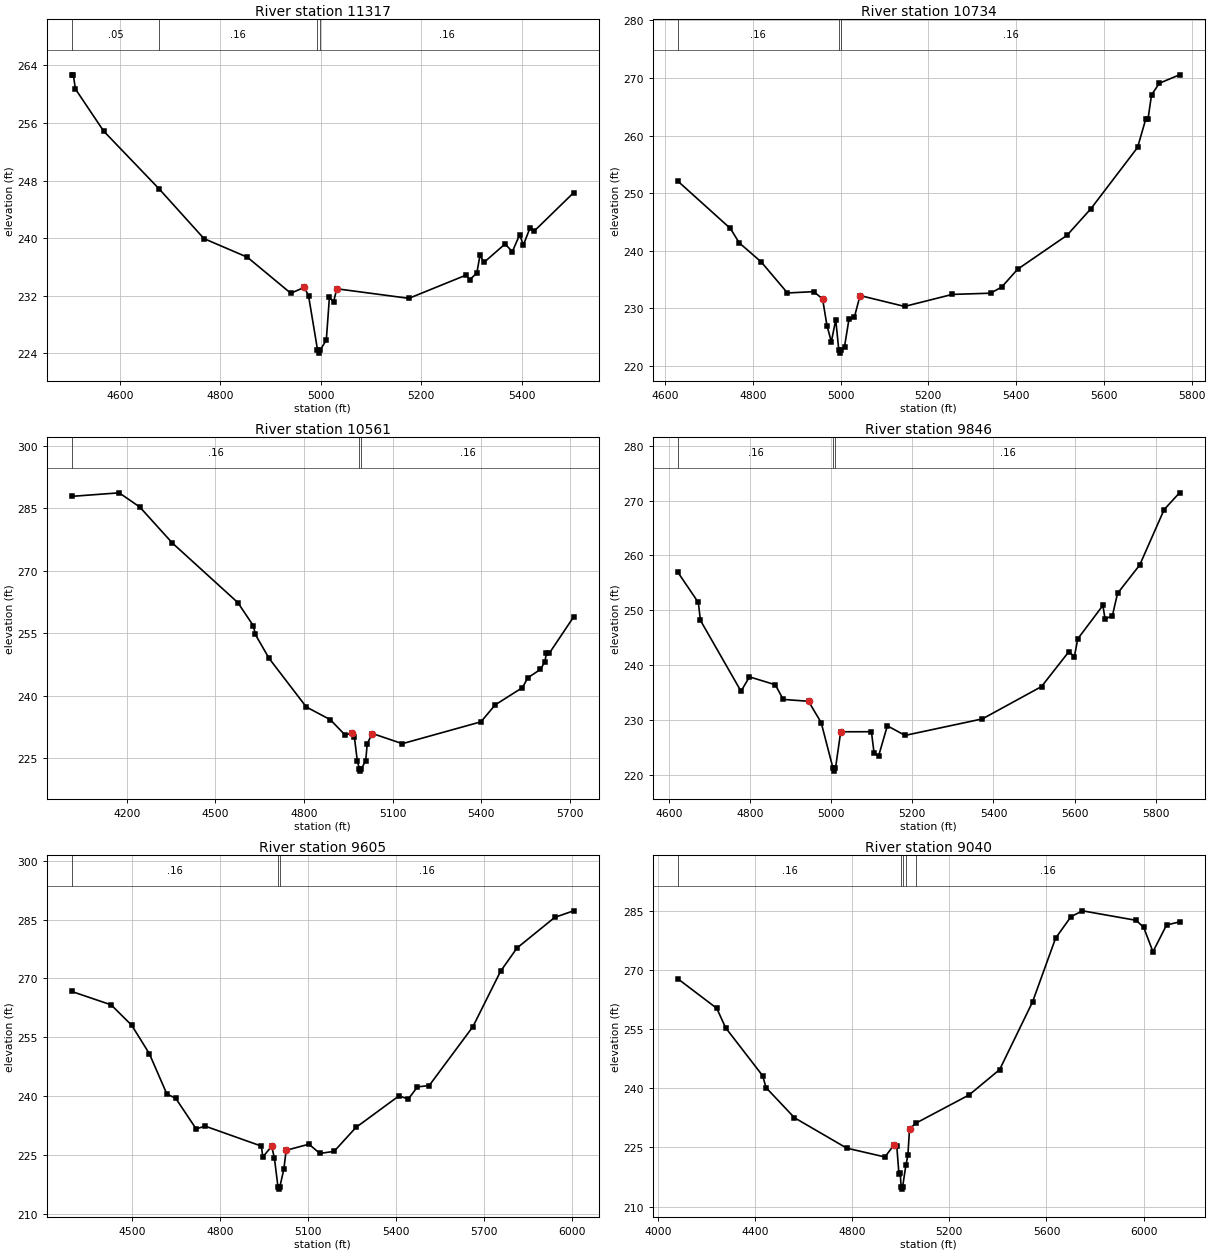
Type RM Length L Ch R = 1 ,11317   ,583,583,583
BEGIN DESCRIPTION:
UNT070 IN BECR 20.0
END DESCRIPTION:
XS GIS Cut Line= 3
      3774149.61     10474260.19      3774449.61     10474660.19
      3774849.61     10474960.19
#Sta/Elev= 30
  4503.6   262.7  4506.7   262.7  4510.9  260.73  4567.1  254.88  4677.5  246.85
  4767.1  239.92  4853.6  237.33  4940.1  232.32  4967.1  233.14  4975.5  231.98
  4993.3  224.49  4996.1  223.99  4999.3  224.49  5010.9   225.8  5017.1  231.73
  5025.5  231.13  5031.7  232.94  5175.5  231.61  5290.1  234.86  5296.3  234.17
  5310.9  235.13  5317.1  237.57  5325.5  236.63  5367.1  239.17  5381.7  238.11
  5396.3  240.46  5403.6  239.02  5417.1  241.44  5425.5  240.98  5503.6  246.29
#Mann= 4 ,-1 , 0
  4503.6     .05       0  4677.5     .16       0  4993.3     .07       0
  4999.3     .16       0
Bank Sta=4967.1,5031.7
XS Rating Curve= 0 ,0
Exp/Cntr=0.3,0.1

Type RM Length L Ch R = 1 ,10734   ,173,173,173
BEGIN DESCRIPTION:
UNT070 IN BECR 19.0
END DESCRIPTION:
XS GIS Cut Line= 3
      3773899.65     10474860.19      3774299.61     10474860.19
      3774999.65      10475110.2
#Sta/Elev= 30
  4629.1  252.08  4749.1  243.83  4769.1  241.34  4819.1  238.03  4879.1  232.62
  4939.1  232.85  4959.1  231.58  4969.1  226.95  4979.1  224.13  4989.1  227.97
  4996.1  222.66  4998.8  222.16  5002.1  222.66  5009.1  223.28  5019.1  228.01
  5031.7  228.46  5044.5  232.17  5145.9  230.28  5254.7  232.37  5341.8  232.58
  5367.3  233.65  5403.4  236.74  5515.9  242.64  5570.6  247.28  5676.8  257.92
  5695.4  262.83  5700.7  262.92  5708.6  267.04  5726.2  269.08  5772.4  270.55
#Mann= 3 ,-1 , 0
  4629.1     .16       0  4996.1     .07       0  5002.1     .16       0
Bank Sta=4959.1,5044.5
XS Rating Curve= 0 ,0
Exp/Cntr=0.3,0.1

Type RM Length L Ch R = 1 ,10561   ,715,715,715
BEGIN DESCRIPTION:
UNT070 IN BECR 18.0
END DESCRIPTION:
XS GIS Cut Line= 3
       3773229.1      10474934.5      3773784.69      10474934.5
      3774909.67     10475142.83
#Sta/Elev= 30
  4013.3  287.89  4173.8  288.74  4243.8  285.33  4353.8  276.71  4575.8   262.4
  4628.7   256.8  4634.9  254.78  4681.6  249.02  4807.8  237.34  4889.2  234.28
    4940  230.55  4961.3  231.16  4970.5  230.22  4980.7  224.34  4987.9  222.44
  4990.6  221.94  4993.9  222.44  5009.1  224.46  5014.2  228.53  5031.5  230.97
  5133.2  228.53  5399.6  233.78  5447.4  237.83    5540  241.99  5558.3  244.35
  5601.1  246.36  5616.2  248.24  5621.4  250.37  5631.6   250.3    5713  258.92
#Mann= 3 ,-1 , 0
  4013.3     .16       0  4987.9     .07       0  4993.9     .16       0
Bank Sta=4961.3,5031.5
XS Rating Curve= 0 ,0
Exp/Cntr=0.3,0.1

Type RM Length L Ch R = 1 ,9846    ,241,241,241
BEGIN DESCRIPTION:
UNT070 IN BECR 17.0
END DESCRIPTION:
XS GIS Cut Line= 3
      3773849.58      10475610.2      3774199.61     10475510.19
      3774999.56     10475160.21
#Sta/Elev= 30
  4621.5  256.96  4672.2  251.43  4677.4  248.17  4777.5  235.25  4798.3  237.87
    4862  236.43  4881.5  233.76  4943.9  233.42  4975.1  229.54  5004.4  221.19
  5007.1  220.69  5010.4  221.19  5023.3  227.86    5099  227.87  5105.6  223.96
  5116.5   223.4  5138.3  228.95    5182   227.2  5372.6  230.21  5518.4   236.1
  5585.9  242.46  5599.5  241.56  5607.7  244.79  5669.7  250.88  5675.1  248.44
  5693.1  248.99  5705.9  253.09  5760.5  258.25  5820.9  268.37  5858.7  271.41
#Mann= 3 ,-1 , 0
  4621.5     .16       0  5004.4     .07       0  5010.4     .16       0
Bank Sta=4943.9,5023.3
XS Rating Curve= 0 ,0
Exp/Cntr=0.3,0.1

Type RM Length L Ch R = 1 ,9605    ,565,565,565
BEGIN DESCRIPTION:
UNT070 IN BECR 16.0
END DESCRIPTION:
XS GIS Cut Line= 4
      3773645.35     10475715.51      3774235.65     10475736.34
      3774562.04     10475611.34      3775296.41     10475375.79
#Sta/Elev= 30
  4293.7  266.67    4428  263.26  4498.1  258.06  4558.1  250.84  4618.2   240.5
  4648.2  239.44  4718.2   231.6  4748.2  232.34  4940.2  227.24  4945.5  224.48
  4975.6  227.19    4985  224.12  4997.2  216.76    5000  216.26  5003.2  216.76
  5017.1  221.35  5024.9  226.16  5102.8  227.72  5139.7  225.37  5188.4  225.88
  5262.8  231.98  5409.9  240.05  5441.4  239.23  5472.9  242.34  5512.8  242.67
  5661.9  257.69  5756.4  271.84  5812.4  277.76  5940.9  285.56  6005.1  287.24
#Mann= 3 ,-1 , 0
  4293.7     .16       0  4997.2     .07       0  5003.2     .16       0
Bank Sta=4975.6,5024.9
XS Rating Curve= 0 ,0
Exp/Cntr=0.3,0.1

Type RM Length L Ch R = 1 ,9040    ,499,499,499
BEGIN DESCRIPTION:
UNT070 IN BECR 15.0
END DESCRIPTION:
XS GIS Cut Line= 2
      3773624.95     10476337.29      3775583.31     10475677.55
#Sta/Elev= 30
  4081.4  267.73    4242  260.24  4278.7   255.3  4430.9  243.18  4445.1  240.15
  4562.1  232.53  4777.3  224.84  4934.7   222.6  4972.7  225.71  4983.3   225.5
  4992.4  218.26  4997.7  218.52  5001.4  214.96  5004.1  214.46  5007.4  214.96
  5021.1   220.6  5029.2  223.01    5036  229.73  5064.2  231.23  5281.1   238.3
  5407.1  244.72  5542.5  261.84  5637.5  277.99  5700.8  283.43  5748.2  284.92
  5968.6  282.52  6000.1  280.78  6038.5  274.55  6094.6  281.34  6147.9  282.11
#Mann= 5 ,-1 , 0
  4081.4     .16       0  5001.4     .07       0  5007.4     .16       0
  5021.1     .12       0  5064.2     .16       0
Bank Sta=4972.7,5036
XS Rating Curve= 0 ,0
Exp/Cntr=0.3,0.1