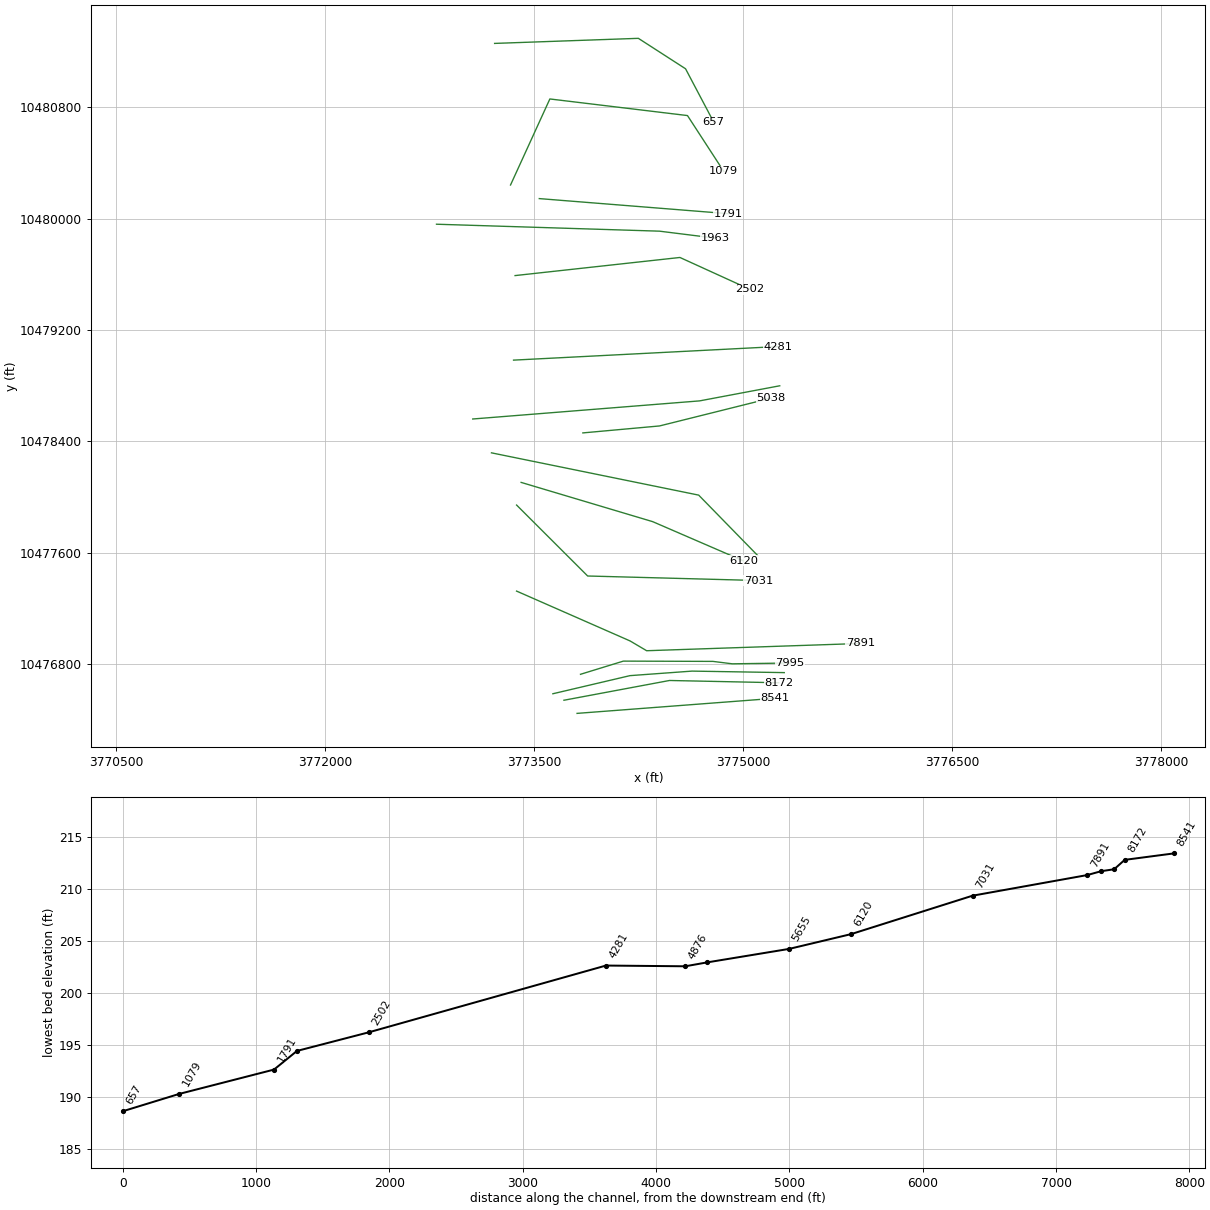
HEC-RAS study UNT070 IN BECR.prj: UNT070 IN BECR Base Level Engineering

--- UNT070 IN BECR.g01 (geometry) --- (continued)

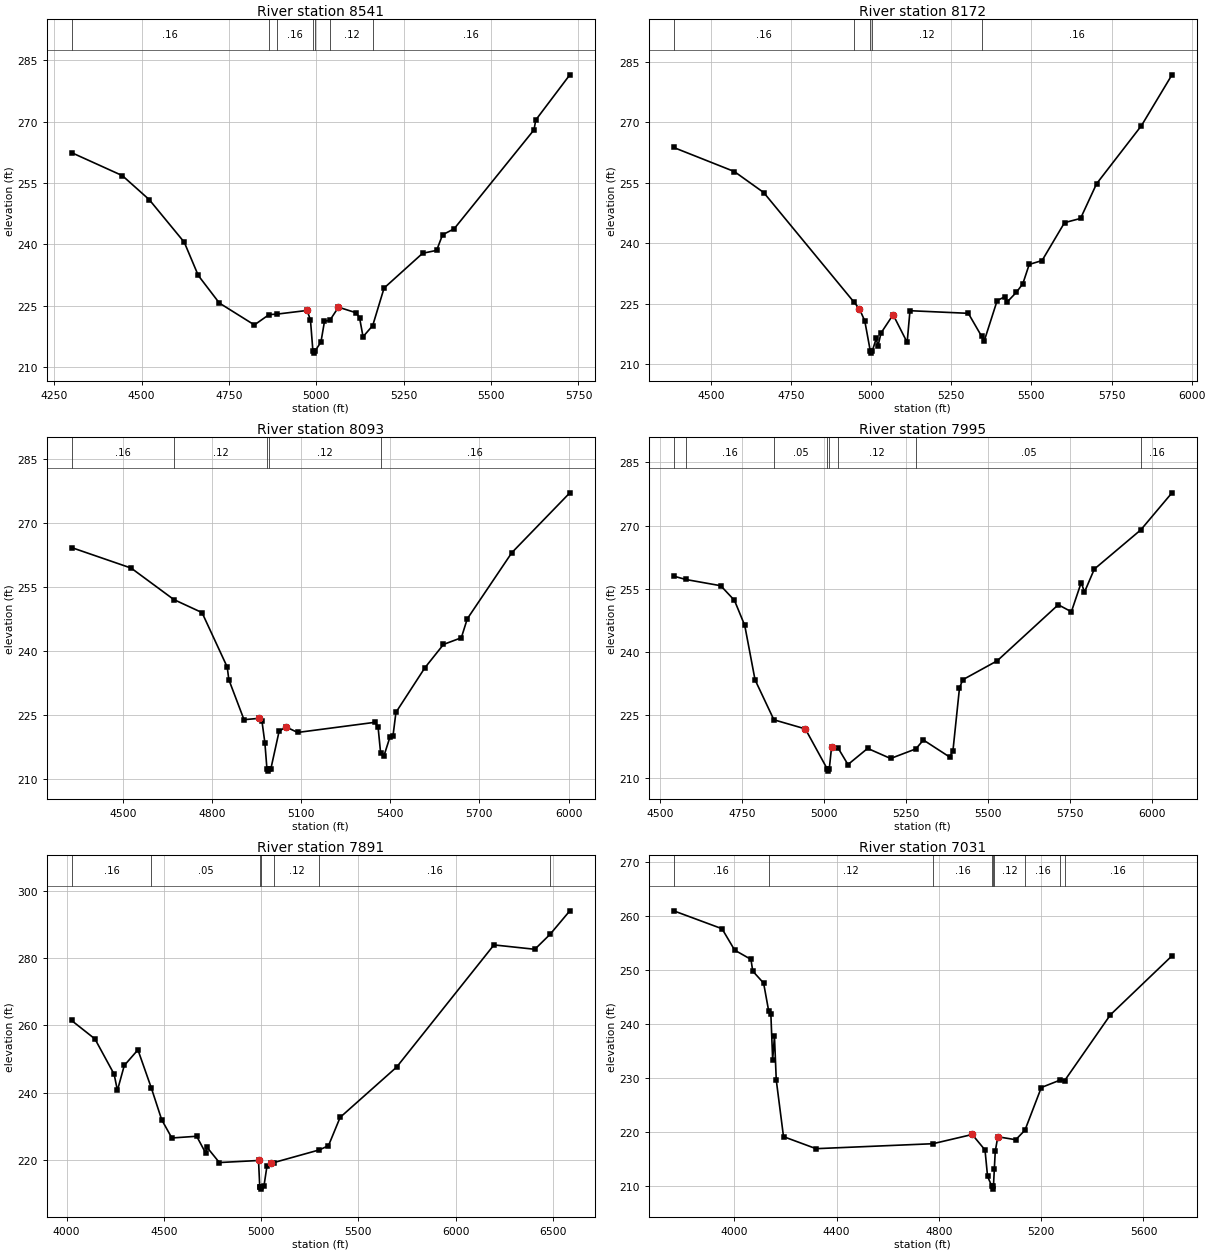
Type RM Length L Ch R = 1 ,8541    ,369,369,369
BEGIN DESCRIPTION:
UNT070 IN BECR 14.0
END DESCRIPTION:
XS GIS Cut Line= 2
      3773808.14     10476444.27       3775229.6     10476552.77
#Sta/Elev= 30
  4299.7  262.44  4444.9  256.82  4521.8  250.95  4622.1  240.52  4662.2  232.39
  4722.4  225.65  4822.7  220.29  4864.8  222.82  4886.9  222.93  4973.4  223.83
  4983.2   221.5  4990.2  213.89  4992.9  213.39  4996.2  213.89  5013.2  216.11
  5023.3  221.16  5039.2  221.49  5063.4  224.63  5113.5  223.27  5123.6  222.09
  5133.6   217.4  5161.3  220.13  5193.8  229.31  5304.1  237.82  5344.2  238.53
  5361.1  242.34  5394.3  243.81  5622.8  268.02  5627.8  270.43  5725.3  281.48
#Mann= 7 ,-1 , 0
  4299.7     .16       0  4864.8     .12       0  4886.9     .16       0
  4990.2     .07       0  4996.2     .16       0  5039.2     .12       0
  5161.3     .16       0
Bank Sta=4973.4,5063.4
XS Rating Curve= 0 ,0
Exp/Cntr=0.3,0.1

Type RM Length L Ch R = 1 ,8172    ,79,79,79
BEGIN DESCRIPTION:
Mapping XS b894d30e
END DESCRIPTION:
XS GIS Cut Line= 3
      3773713.86     10476538.68      3774471.36     10476680.71
      3775254.78     10476664.29
#Sta/Elev= 30
  4384.3  263.76  4573.3   257.8  4664.9   252.6  4946.9  225.39  4963.6  223.74
  4980.3  220.76  4997.6  213.27  5000.4  212.77  5003.6  213.27  5016.2  216.43
  5021.3  214.47  5031.1  217.78  5068.7  222.29  5112.5  215.44  5121.3  223.29
  5303.3  222.64  5344.6  216.97  5353.3  215.88  5393.3   225.8  5418.5   226.8
  5423.5  225.37  5453.3  227.86  5473.3  229.97  5493.3  234.77  5533.3  235.72
  5603.4  245.12  5653.4  246.17  5703.4  254.77  5843.4  269.18  5938.6  281.78
#Mann= 5 ,-1 , 0
  4384.3     .16       0  4946.9     .12       0  4997.6     .07       0
  5003.6     .12       0  5344.6     .16       0
Bank Sta=4963.6,5068.7
XS Rating Curve= 0 ,0
Exp/Cntr=0.3,0.1

Type RM Length L Ch R = 1 ,8093    ,98,98,98
BEGIN DESCRIPTION:
UNT070 IN BECR 13.0
END DESCRIPTION:
XS GIS Cut Line= 4
      3773634.54     10476585.33      3774187.91     10476715.53
      3774632.78     10476748.08      3775294.64     10476737.23
#Sta/Elev= 30
  4327.8  264.19  4528.2  259.39  4671.9  252.02  4766.7  248.97  4851.5  236.23
  4856.9  233.28    4908  223.91  4958.2  224.22  4968.2  223.67  4978.2  218.49
  4985.2  212.37    4988  211.87  4991.2  212.37  4998.3   212.4    5026  221.17
  5048.4  222.23  5088.5  220.92  5349.2   223.3  5359.2  222.11  5367.7  216.06
  5379.2  215.52  5399.2  219.88  5409.2  220.06  5419.2  225.62  5516.6  236.06
  5579.2  241.52  5639.2  243.08  5659.2  247.51  5809.2     263  6004.3     277
#Mann= 5 ,-1 , 0
  4327.8     .16       0  4671.9     .12       0  4985.2     .07       0
  4991.2     .12       0  5367.7     .16       0
Bank Sta=4958.2,5048.4
XS Rating Curve= 0 ,0
Exp/Cntr=0.3,0.1

Type RM Length L Ch R = 1 ,7995    ,104,104,104
BEGIN DESCRIPTION:
Mapping XS b7751bbc
END DESCRIPTION:
XS GIS Cut Line= 5
      3773832.68     10476725.16      3774139.95     10476819.85
      3774782.49     10476817.92      3774921.62     10476800.53
      3775336.29      10476806.3
#Sta/Elev= 30
  4542.3  257.99  4579.1  257.19  4685.6  255.71  4727.4  252.24  4758.8  246.29
  4790.2  233.37  4847.7  223.87  4943.5  221.71  5010.5  212.18  5013.2  211.68
  5016.5  212.18  5023.5  217.37  5043.3  217.18  5073.5  213.24  5133.5  217.08
  5203.5  214.68  5280.5  216.96  5303.5  219.07  5383.5  215.03  5393.5  216.48
  5413.5  231.41  5423.5  233.38  5528.5  237.88  5714.6  251.19  5754.6  249.53
  5784.6  256.45  5794.6   254.2  5824.6  259.66  5966.2  268.97  6061.3  277.77
#Mann= 8 ,-1 , 0
  4542.3     .12       0  4579.1     .16       0  4847.7     .05       0
  5010.5     .04       0  5016.5     .05       0  5043.3     .12       0
  5280.5     .05       0  5966.2     .16       0
Bank Sta=4943.5,5023.5
XS Rating Curve= 0 ,0
Exp/Cntr=0.3,0.1

Type RM Length L Ch R = 1 ,7891    ,860,860,860
BEGIN DESCRIPTION:
UNT070 IN BECR 12.0
END DESCRIPTION:
XS GIS Cut Line= 4
      3773374.06     10477323.19      3774187.91      10476965.1
      3774307.26     10476894.57       3775839.4     10476946.65
#Sta/Elev= 30
  4025.7  261.43  4145.7  255.95  4244.5  245.45  4261.2  240.63  4296.6  248.07
  4366.7   252.7  4436.3  241.25  4488.8  231.94    4541  226.51  4668.6  227.02
  4715.3  221.99  4720.7  223.81  4785.3  219.21  4986.5  219.82  4992.8  212.05
  4995.6  211.81  4998.4  211.31  5001.6  211.81  5014.2  212.12  5029.9  218.15
  5051.3  219.08  5065.7  219.21  5299.7  222.98    5346  224.22    5406  232.64
  5696.2  247.57  6196.5  283.89  6406.6  282.59    6485  287.04  6586.5  294.02
#Mann= 7 ,-1 , 0
  4025.7     .16       0  4436.3     .05       0  4995.6     .04       0
  5001.6     .05       0  5065.7     .12       0  5299.7     .16       0
    6485     .05       0
Bank Sta=4986.5,5051.3
XS Rating Curve= 0 ,0
Exp/Cntr=0.3,0.1

Type RM Length L Ch R = 1 ,7031    ,911,911,911
BEGIN DESCRIPTION:
UNT070 IN BECR 11.0
END DESCRIPTION:
XS GIS Cut Line= 3
      3773374.11     10477941.65      3773884.09     10477431.68
      3775110.24     10477399.13
#Sta/Elev= 30
  3763.6  260.93  3952.4  257.61  4001.9  253.64  4065.5  251.93  4072.6  249.75
    4115  247.53    4135  242.32  4143.3  241.85  4150.4  233.33  4157.4  237.65
  4164.5  229.54  4192.8  219.06  4320.1  216.83  4776.8  217.75  4930.5  219.46
  4980.5  216.59  4990.5  211.69  5007.5  209.83  5010.3  209.33  5013.5  209.83
  5016.9  212.98  5020.5  216.31  5030.5  219.04  5100.6  218.49  5136.7  220.26
  5200.6  228.17  5274.3  229.55    5292  229.46  5470.7  241.65  5711.4  252.58
#Mann= 9 ,-1 , 0
  3763.6     .16       0    4135     .12       0  4776.8     .16       0
  5007.5     .07       0  5013.5     .16       0  5016.9     .12       0
  5136.7     .16       0  5274.3     .12       0    5292     .16       0
Bank Sta=4930.5,5030.5
XS Rating Curve= 0 ,0
Exp/Cntr=0.3,0.1

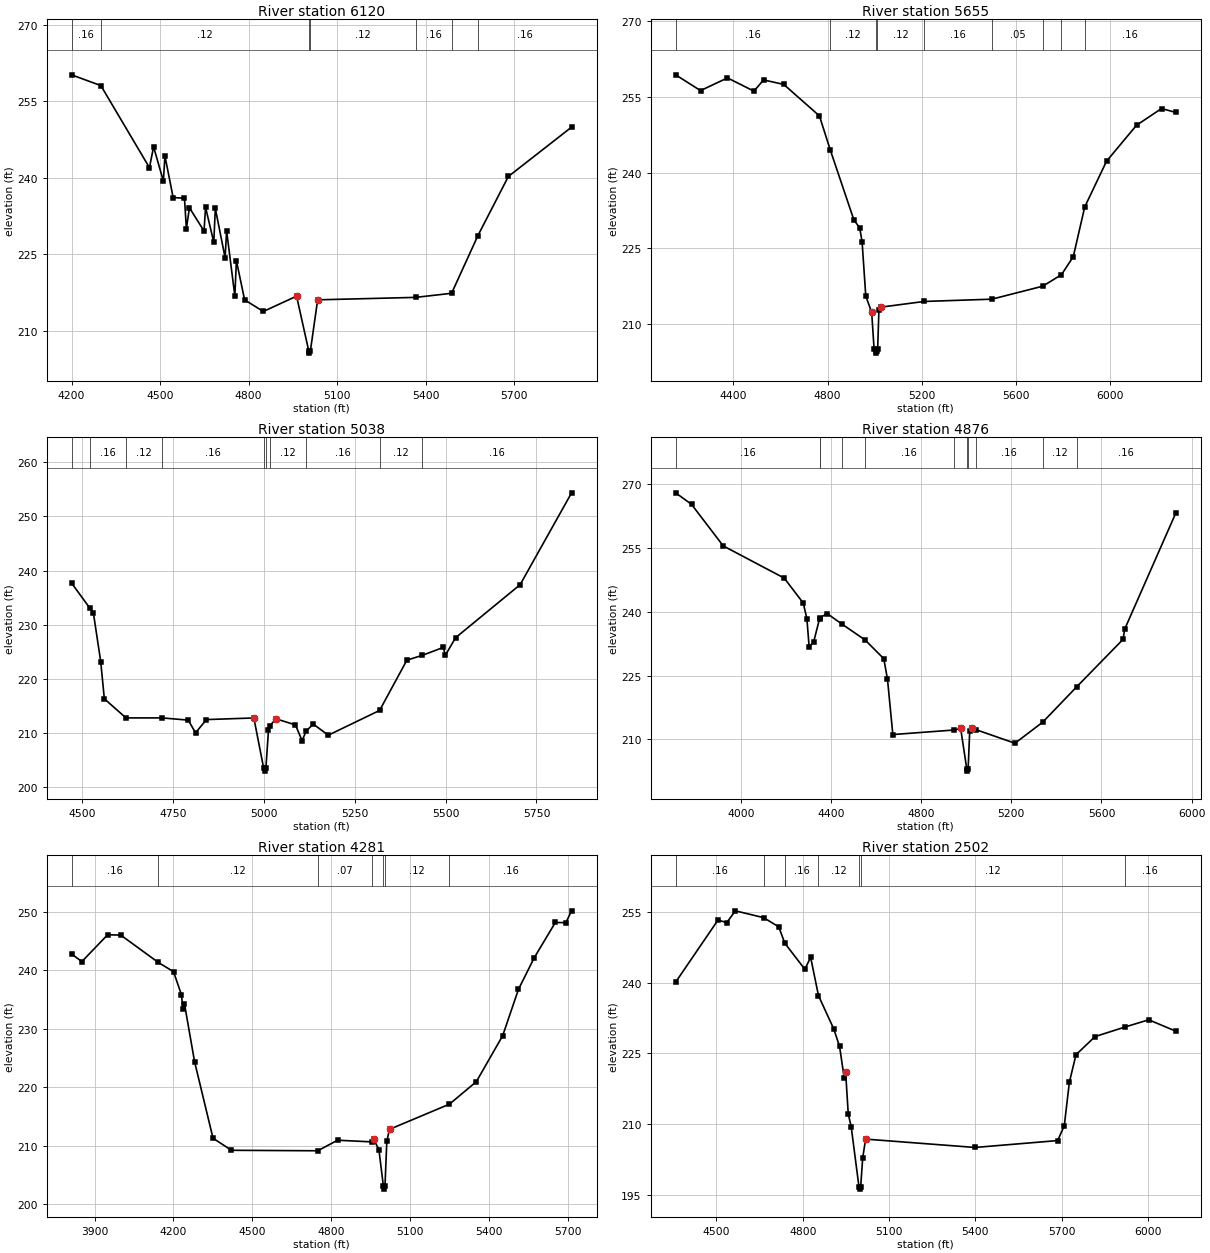
Type RM Length L Ch R = 1 ,6120    ,465,465,465
BEGIN DESCRIPTION:
UNT070 IN BECR 10.0
END DESCRIPTION:
XS GIS Cut Line= 3
      3773406.69     10478104.41      3774350.67      10477822.3
      3775001.74     10477540.17
#Sta/Elev= 30
    4200  260.15  4299.4  258.04    4464  241.97  4478.1  246.05  4511.3  239.33
  4516.5  244.26  4544.4  236.11  4582.7  235.99  4589.2  230.04  4599.6  234.11
    4649  229.56  4654.2   234.2  4682.1  227.34  4687.3     234  4720.4  224.34
  4725.6  229.58  4753.5  216.82  4758.7  223.76  4786.6  216.07  4850.1   213.8
  4962.7   216.8  5003.7  206.14  5006.4  205.64  5009.7  206.14  5034.1  216.08
  5366.6  216.56  5488.1  217.36  5577.3  228.66  5680.5  240.24  5894.8  249.91
#Mann= 7 ,-1 , 0
    4200     .16       0  4299.4     .12       0  5003.7     .07       0
  5009.7     .12       0  5366.6     .16       0  5488.1     .12       0
  5577.3     .16       0
Bank Sta=4962.7,5034.1
XS Rating Curve= 0 ,0
Exp/Cntr=0.3,0.1

Type RM Length L Ch R = 1 ,5655    ,617,617,617
BEGIN DESCRIPTION:
UNT070 IN BECR 9.0
END DESCRIPTION:
XS GIS Cut Line= 3
      3773193.94     10478316.89      3774680.53     10478013.06
       3775103.7     10477579.03
#Sta/Elev= 30
  4154.5  259.42  4260.1  256.29  4374.6  258.81  4486.9  256.18  4527.7  258.41
  4613.5  257.52  4764.9  251.28  4810.7  244.58  4911.3  230.65    4936  229.07
  4946.2  226.31  4961.8  215.57    4987  212.28  4997.2  204.99  5004.2  204.72
  5006.9  204.22  5010.2  204.72  5012.3  205.07  5017.7  212.82  5027.9  213.35
    5210  214.47  5497.2  214.92  5713.6   217.5  5792.8  219.78    5843  223.35
  5891.7  233.22  5984.3  242.29  6111.6  249.42  6217.8  252.73    6278  251.97
#Mann= 9 ,-1 , 0
  4154.5     .16       0  4810.7     .12       0  5004.2     .07       0
  5010.2     .12       0    5210     .16       0  5497.2     .05       0
  5713.6     .16       0  5792.8     .12       0  5891.7     .16       0
Bank Sta=4987,5027.9
XS Rating Curve= 0 ,0
Exp/Cntr=0.3,0.1

Type RM Length L Ch R = 1 ,5038    ,162,162,162
BEGIN DESCRIPTION:
UNT070 IN BECR 8.0
END DESCRIPTION:
XS GIS Cut Line= 3
      3773849.66     10478460.19      3774399.61     10478510.19
      3775199.57     10478710.18
#Sta/Elev= 30
  4469.9  237.69  4520.9     233  4530.1  232.14  4550.2  223.18  4560.2  216.29
  4619.8  212.76  4718.7  212.76  4791.2  212.35  4811.3     210  4841.4  212.45
  4971.9  212.75    4999  203.42  5001.8  202.92    5005  203.42  5012.1  210.46
  5015.4  211.23  5032.4   212.6  5086.5  211.46  5104.6  208.56  5116.2  210.35
  5135.5  211.62  5176.7  209.56  5318.1  214.14  5393.2  223.44  5435.9  224.33
  5493.7   225.8  5498.9  224.31  5527.2  227.58    5705  237.39  5846.7  254.37
#Mann= 10 ,-1 , 0
  4469.9     .12       0  4520.9     .16       0  4619.8     .12       0
  4718.7     .16       0    4999     .07       0    5005     .16       0
  5015.4     .12       0  5116.2     .16       0  5318.1     .12       0
  5435.9     .16       0
Bank Sta=4971.9,5032.4
XS Rating Curve= 0 ,0
Exp/Cntr=0.3,0.1

Type RM Length L Ch R = 1 ,4876    ,595,595,595
BEGIN DESCRIPTION:
UNT070 IN BECR 7.0
END DESCRIPTION:
XS GIS Cut Line= 3
      3773059.42     10478560.15      3774687.04     10478690.36
      3775262.08     10478798.86
#Sta/Elev= 30
  3711.3  267.91  3781.7   265.2  3922.2  255.45    4193  247.88  4277.2  242.03
  4293.3  238.38  4303.4   231.7  4323.4   232.9  4349.7  238.37  4351.4  238.59
  4383.6  239.54  4447.9  237.12  4551.6  233.35  4634.4  228.96  4650.9  224.13
  4674.6  211.14  4944.2   212.2  4975.5  212.57  5002.6  203.05  5005.4  202.55
  5008.6  203.05  5015.6  211.97  5024.6  212.58  5043.1  212.29  5216.3   209.1
  5339.6  214.06  5490.7  222.38  5695.8   233.5  5702.9  235.88  5929.3  263.12
#Mann= 11 ,-1 , 0
  3711.3     .16       0  4349.7     .12       0  4351.4     .16       0
  4447.9     .12       0  4551.6     .16       0  4944.2     .12       0
  5002.6     .07       0  5008.6     .12       0  5043.1     .16       0
  5339.6     .12       0  5490.7     .16       0
Bank Sta=4975.5,5024.6
XS Rating Curve= 0 ,0
Exp/Cntr=0.3,0.1

Type RM Length L Ch R = 1 ,4281    ,1779,1779,1779
BEGIN DESCRIPTION:
UNT070 IN BECR 6.0
END DESCRIPTION:
XS GIS Cut Line= 2
      3773352.41     10478983.33       3775251.3     10479080.99
#Sta/Elev= 30
  3812.4  242.78  3851.6  241.47  3949.8  246.06  3999.8  245.99  4142.2  241.33
  4200.1  239.75  4230.1  235.84  4236.6  233.36  4241.6  234.31  4280.2  224.38
  4350.3  211.32  4420.4  209.25  4748.6  209.17    4824  210.97  4953.4  210.69
  4961.1  211.13  4981.1  209.37  4998.2  203.12  5000.9  202.62  5004.2  203.12
  5011.2  210.83  5021.5  212.83  5249.4  217.13  5351.6  220.97  5451.8  228.82
  5511.8  236.74  5571.9  242.14    5652  248.15  5692.1  248.12  5713.8  250.14
#Mann= 7 ,-1 , 0
  3812.4     .16       0  4142.2     .12       0  4748.6     .07       0
  4953.4     .12       0  4998.2     .07       0  5004.2     .12       0
  5249.4     .16       0
Bank Sta=4961.1,5021.5
XS Rating Curve= 0 ,0
Exp/Cntr=0.3,0.1

Type RM Length L Ch R = 1 ,2502    ,539,539,539
BEGIN DESCRIPTION:
UNT070 IN BECR 5.0
END DESCRIPTION:
XS GIS Cut Line= 3
      3773363.21     10479590.96      3774545.98     10479721.17
      3775044.84     10479493.43
#Sta/Elev= 30
  4358.3  240.08  4505.6  253.25  4535.8  252.68  4565.9  255.19  4664.2  253.74
  4716.8  251.79  4737.6  248.34  4807.4   242.8  4827.5  245.34  4854.8  237.21
    4908  230.15  4928.1  226.44  4944.2   219.8  4949.2  220.96  4958.3  212.12
  4968.4  209.48  4995.5  196.71  4998.3  196.21  5001.5  196.71  5008.6   202.9
  5018.7  206.81    5399  205.04  5686.3   206.5  5709.3  209.67  5726.9  218.85
  5749.9  224.69    5816  228.53  5918.8  230.54  6002.9   232.1  6096.6  229.69
#Mann= 7 ,-1 , 0
  4358.3     .16       0  4664.2     .12       0  4737.6     .16       0
  4854.8     .12       0  4995.5     .07       0  5001.5     .12       0
  5918.8     .16       0
Bank Sta=4949.2,5018.7
XS Rating Curve= 0 ,0
Exp/Cntr=0.3,0.1

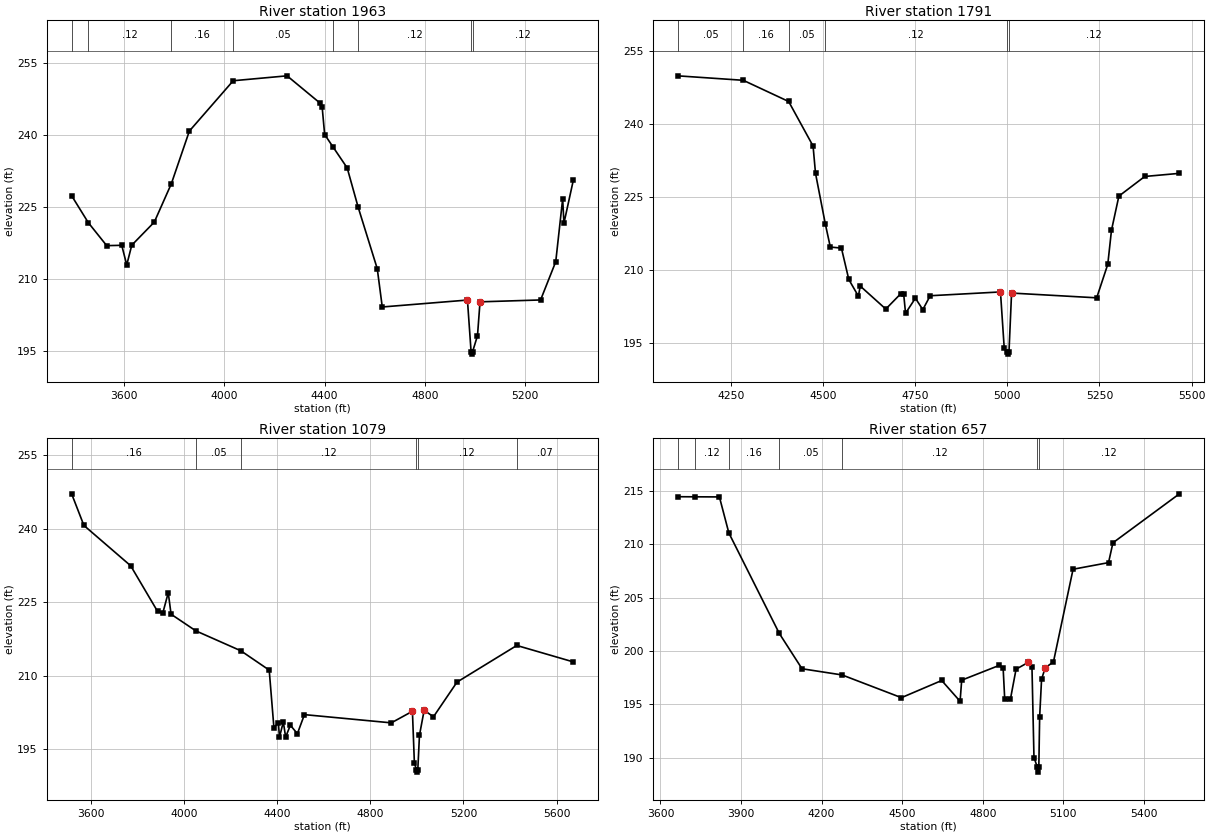
Type RM Length L Ch R = 1 ,1963    ,172,172,172
BEGIN DESCRIPTION:
UNT070 IN BECR 4.0
END DESCRIPTION:
XS GIS Cut Line= 3
       3772799.6     10479960.19      3774399.61     10479910.19
      3774799.61     10479860.19
#Sta/Elev= 30
  3389.6  227.35  3456.3  221.74  3529.7  216.97  3589.7  217.04  3609.7  212.96
  3629.7  217.06  3719.8  221.87  3787.9  229.85  3859.8  240.79  4034.9  251.25
    4250  252.27  4380.1  246.67  4390.1  245.81  4400.1  240.07  4434.9  237.38
  4490.1  233.13  4533.9  224.96  4610.2  212.18  4630.2  204.22  4970.4  205.66
  4984.9  194.92  4987.6  194.42  4990.9  194.92  5010.5  198.26  5020.6  205.29
  5262.5  205.68    5323  213.63  5350.7  226.71  5355.7  221.63  5393.5  230.64
#Mann= 8 ,-1 , 0
  3389.6     .16       0  3456.3     .12       0  3787.9     .16       0
  4034.9     .05       0  4434.9     .16       0  4533.9     .12       0
  4984.9     .07       0  4990.9     .12       0
Bank Sta=4970.4,5020.6
XS Rating Curve= 0 ,0
Exp/Cntr=0.3,0.1

Type RM Length L Ch R = 1 ,1791    ,712,712,712
BEGIN DESCRIPTION:
UNT070 IN BECR 3.0
END DESCRIPTION:
XS GIS Cut Line= 2
      3773536.87     10480144.35      3774893.23     10480035.84
#Sta/Elev= 30
  4106.1  249.87  4284.1  248.95  4407.2  244.59  4473.4  235.43    4480  229.83
  4506.6  219.41  4520.2  214.65  4550.3  214.44  4570.3  207.98  4596.3  204.55
  4601.3  206.63  4670.6   201.9  4710.8  205.02  4719.2  204.92  4724.2  201.04
  4750.9  204.14    4771  201.78    4791  204.64  4981.6  205.42  4991.7  193.95
  4998.7  193.13  5001.4  192.63  5004.7  193.13  5011.7  205.19  5242.5  204.21
  5272.6   211.1  5282.6  218.09  5302.7  225.13  5372.9  229.17  5466.8  229.81
#Mann= 6 ,-1 , 0
  4106.1     .05       0  4284.1     .16       0  4407.2     .05       0
  4506.6     .12       0  4998.7     .07       0  5004.7     .12       0
Bank Sta=4981.6,5011.7
XS Rating Curve= 0 ,0
Exp/Cntr=0.3,0.1

Type RM Length L Ch R = 1 ,1079    ,422,422,422
BEGIN DESCRIPTION:
UNT070 IN BECR 2.0
END DESCRIPTION:
XS GIS Cut Line= 4
      3773330.69     10480241.99      3773612.82      10480860.5
      3774600.23     10480741.14      3774860.67     10480339.63
#Sta/Elev= 30
    3519  247.11  3571.6  240.66  3772.4  232.42  3887.6  223.12  3910.6  222.84
  3933.6  226.92  3945.7  222.53  4052.1  219.13  4244.9  215.07  4366.8  211.12
    4387  199.36  4405.9  200.39  4410.9  197.44  4427.3  200.54  4437.3  197.45
  4457.5  199.86  4487.7  198.14  4517.9  202.03  4890.6  200.35  4981.3  202.71
  4989.7  192.16  4998.4  190.79  5001.2  190.29  5004.4  190.79  5011.5  197.81
  5031.6  202.92  5071.6  201.59  5172.6  208.67  5429.1  216.15    5672  212.79
#Mann= 6 ,-1 , 0
    3519     .16       0  4052.1     .05       0  4244.9     .12       0
  4998.4     .07       0  5004.4     .12       0  5429.1     .07       0
Bank Sta=4981.3,5031.6
XS Rating Curve= 0 ,0
Exp/Cntr=0.3,0.1

Type RM Length L Ch R = 1 ,657     ,0,0,0
BEGIN DESCRIPTION:
UNT070 IN BECR 1.0
END DESCRIPTION:
XS GIS Cut Line= 4
      3773216.59     10481259.78      3774247.81     10481296.24
      3774586.35     10481077.49      3774788.64     10480693.66
#Sta/Elev= 30
  3663.8  214.45  3728.5  214.44  3819.4  214.43  3854.6  211.05  4042.5  201.63
  4127.1  198.32  4276.4  197.74  4497.3  195.61  4647.4  197.22  4715.8  195.27
  4721.8  197.25    4861  198.63  4876.1  198.41  4882.1  195.45  4903.2  195.46
  4924.3  198.28  4969.8  198.92  4983.5  198.52    4991     190  5003.1  189.13
  5005.9  188.63  5009.1  189.13  5012.1  193.78  5019.3  197.35  5033.2  198.42
  5063.5  198.96  5136.6  207.65  5268.7  208.27  5285.1  210.13  5532.6  214.72
#Mann= 7 ,-1 , 0
  3663.8     .16       0  3728.5     .12       0  3854.6     .16       0
  4042.5     .05       0  4276.4     .12       0  5003.1     .07       0
  5009.1     .12       0
Bank Sta=4969.8,5033.2
XS Rating Curve= 0 ,0
Exp/Cntr=0.3,0.1

Chan Stop Cuts=-1
Use User Specified Reach Order=0
Composite Channel Slope=5