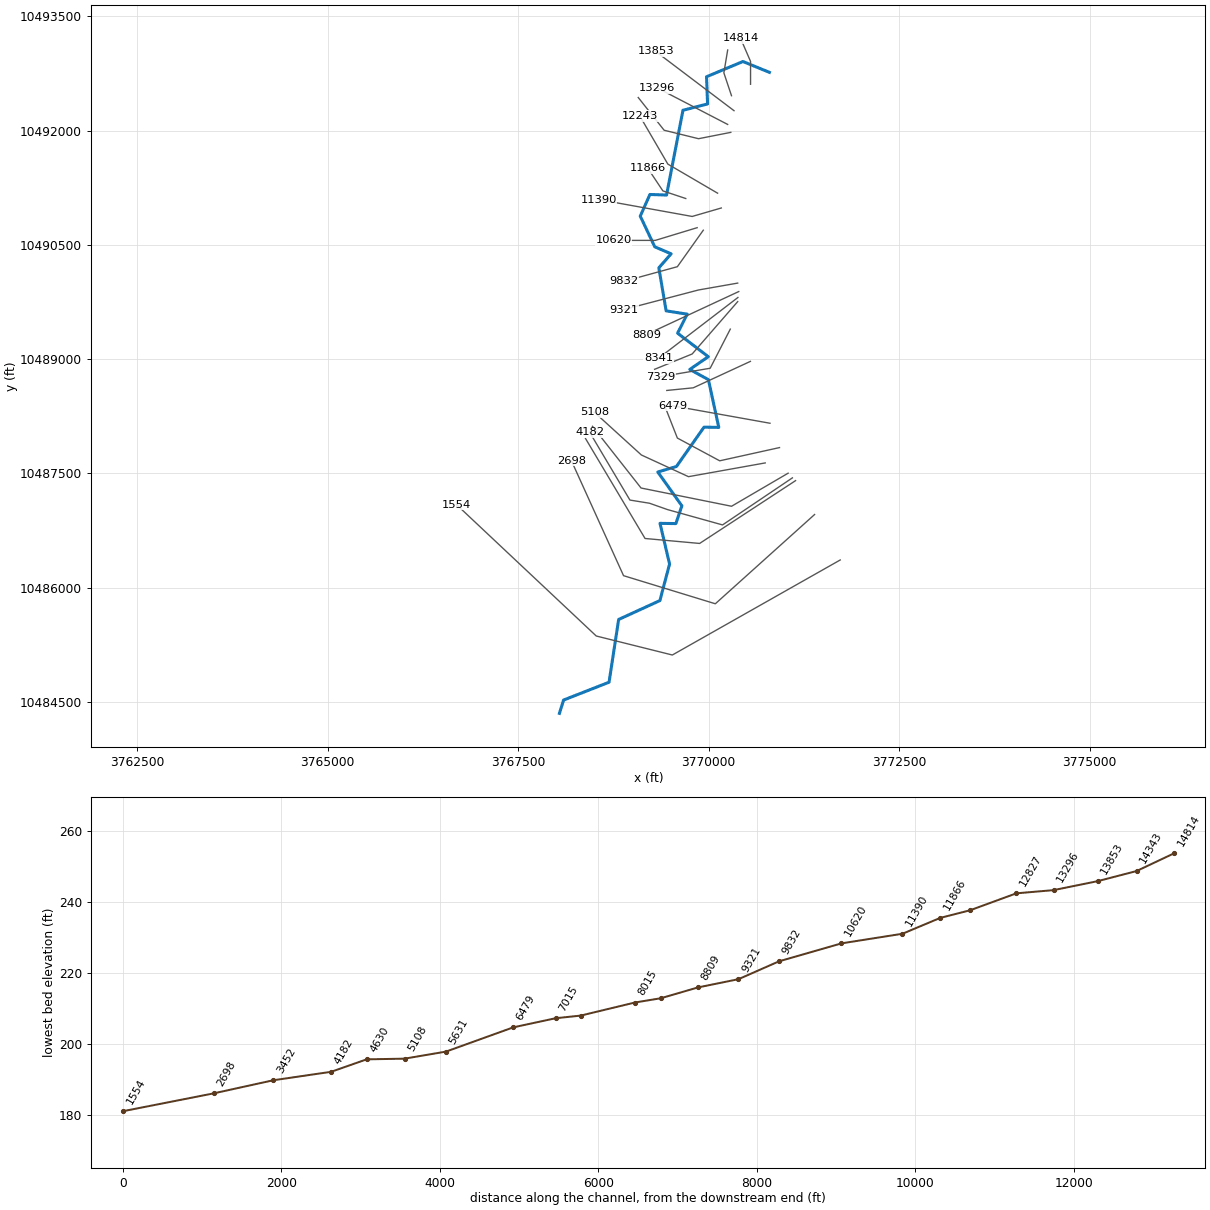
--- UNT071 IN BECR.prj (project) ---

Proj Title=UNT071 IN BECR Base Level Engineering
Current Plan=p01
Default Exp/Contr=0.3,0.1
English Units
Geom File=g01
Flow File=f01
Plan File=p01
Y Axis Title=Elevation
X Axis Title(PF)=Main Channel Distance
X Axis Title(XS)=Station
BEGIN DESCRIPTION:
UNT071 IN BECR
END DESCRIPTION:
DSS Export Rating Curves= 0
DSS Export Rating Curve Sorted= 0
DSS Export Volume Flow Curves= 0
DXF OffsetX= 0
DXF OffsetY= 0
DXF ScaleX= 1
DXF ScaleY= 10

--- UNT071 IN BECR.p01 (plan) ---

Plan Title=Multiple Run
Short Identifier=Multiple
Geom File=g01
Flow File=f01
Subcritical Flow
K Sum by GR= 0
Std Step Tol= 0.01
Critical Tol= 0.01
Num of Std Step Trials= 20
Max Error Tol= 0.3
Flow Tol Ratio= 0.001
Split Flow NTrial= 30
Split Flow Tol= 0.02
Split Flow Ratio= 0.02
Log Output Level= 0
Friction Slope Method= 1
Unsteady Friction Slope Method= 2
Unsteady Bridges Friction Slope Method= 1
Parabolic Critical Depth
Global Vel Dist=  1 , 1 , 1
Global Log Level= 0
CheckData=True
Encroach Param= -1, 0, 0, 0
BEGIN DESCRIPTION:
Multiple Run
END DESCRIPTION:

--- UNT071 IN BECR.f01 (steady flow) ---

Flow Title=Multiple
Program Version=4.10
Number of Profiles= 7
Profile Names=10-year,25-year,50-year,1pct_min,100-year,1pct_plu,500-year
River Rch & RM=UNT071 IN BECR,Reach-1         ,14814
     597     809     984     881    1191    1611    1750
River Rch & RM=UNT071 IN BECR,Reach-1         ,4182
     679     924    1128    1012    1368    1850    2020
Boundary for River Rch & Prof#=UNT071 IN BECR,Reach-1         , 1
Up Type= 0
Dn Type= 3
Dn Slope=0.004
Boundary for River Rch & Prof#=UNT071 IN BECR,Reach-1         , 2
Up Type= 0
Dn Type= 3
Dn Slope=0.004
Boundary for River Rch & Prof#=UNT071 IN BECR,Reach-1         , 3
Up Type= 0
Dn Type= 3
Dn Slope=0.004
Boundary for River Rch & Prof#=UNT071 IN BECR,Reach-1         , 4
Up Type= 0
Dn Type= 3
Dn Slope=0.004
Boundary for River Rch & Prof#=UNT071 IN BECR,Reach-1         , 5
Up Type= 0
Dn Type= 3
Dn Slope=0.004
Boundary for River Rch & Prof#=UNT071 IN BECR,Reach-1         , 6
Up Type= 0
Dn Type= 3
Dn Slope=0.004
Boundary for River Rch & Prof#=UNT071 IN BECR,Reach-1         , 7
Up Type= 0
Dn Type= 3
Dn Slope=0.004
DSS Import GetInterval= 0
DSS Import GetPeak= 0
DSS Import FillOption= 0

--- UNT071 IN BECR.g01 (geometry) ---

Geom Title=Existing Conditions
Program Version=4.10

River Reach=UNT071 IN BECR  ,Reach-1
Reach XY= 30
      3770797.12     10492766.83        3770450.       10492909.
      3769972.25       10492709.        3769986.       10492352.
        3769663.       10492269.      3769447.75       10491156.
       3769229.5       10491163.      3769102.75       10490879.
        3769293.       10490476.      3769507.75       10490384.
      3769346.25       10490200.      3769442.25       10489635.
        3769719.       10489592.       3769592.5       10489342.
      3769995.25       10489033.      3769752.25       10488866.
      3769996.75       10488732.        3770133.       10488105.
      3769939.25       10488108.      3769577.75       10487592.
        3769333.       10487519.      3769648.75       10487075.
       3769569.5       10486842.      3769361.75       10486845.
      3769487.25       10486310.      3769360.25       10485831.
      3768819.25       10485583.      3768693.25       10484759.
      3768096.75       10484525.        3768042.       10484350.

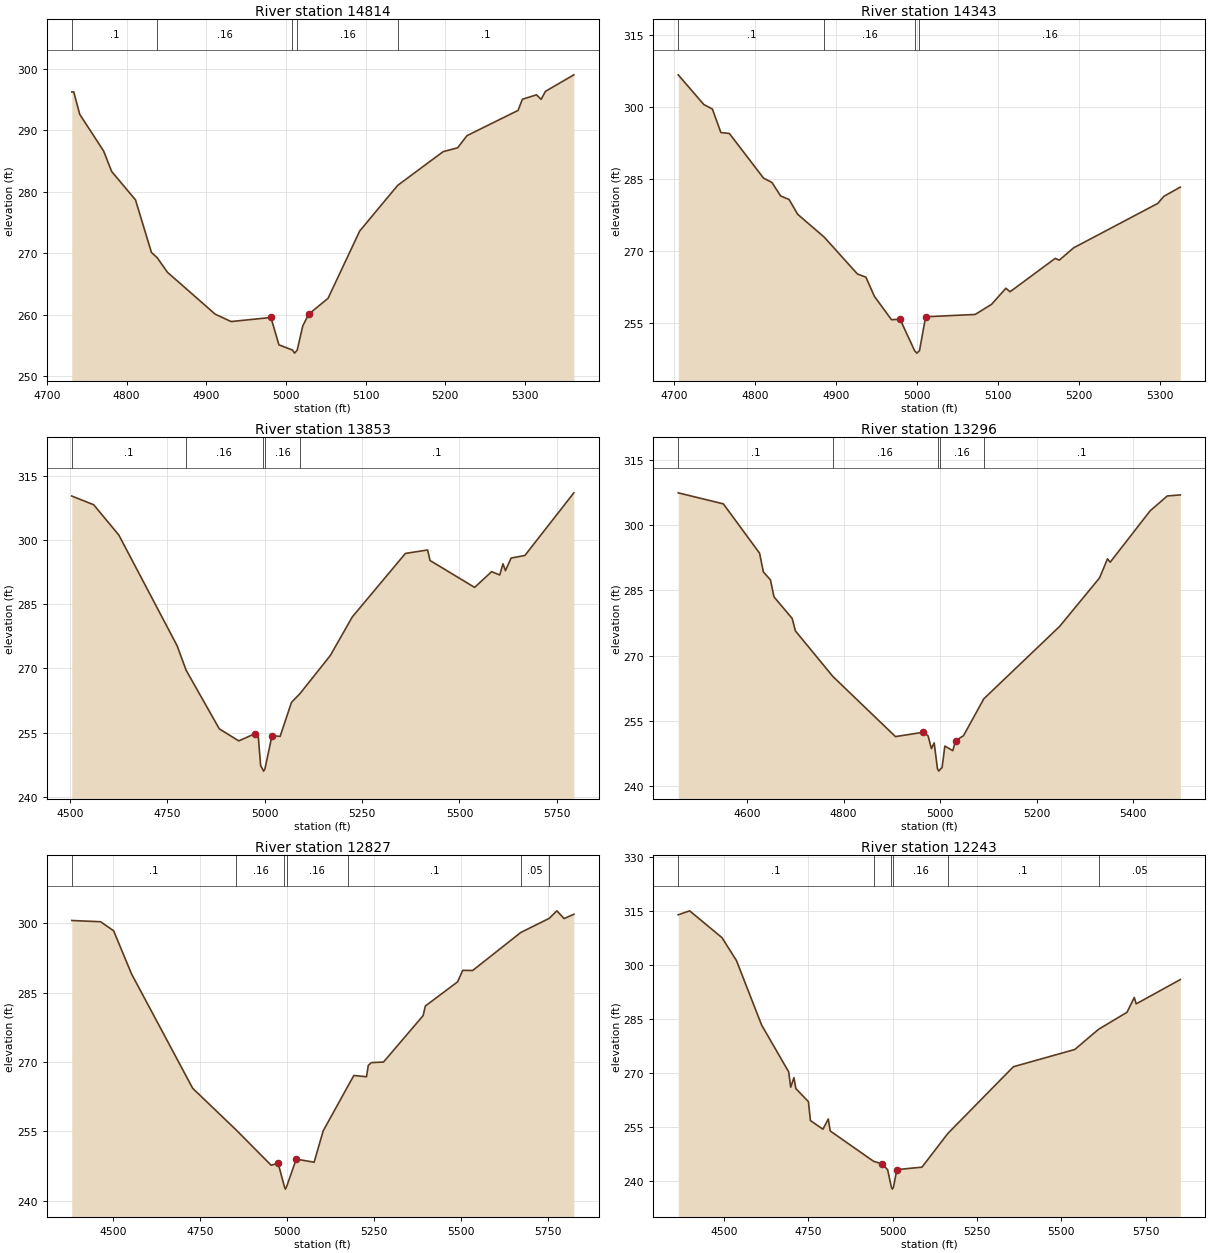
Type RM Length L Ch R = 1 ,14814   ,471,471,471
BEGIN DESCRIPTION:
UNT071 IN BECR 23.0
END DESCRIPTION:
XS GIS Cut Line= 3
      3770549.61     10492610.23      3770549.61     10492910.19
      3770418.48     10493213.28
#Sta/Elev= 30
  4731.3  296.22  4733.8  296.22  4741.3  292.58  4771.3  286.62  4781.3  283.31
  4811.3  278.68  4831.3  270.14  4838.7  269.26  4851.3  266.93  4911.3  260.11
  4931.3  258.91  4981.3  259.57  4991.3  255.13  5008.3  254.28    5011  253.78
  5014.3  254.28  5021.3  258.22  5028.8  260.12    5053  262.69  5092.7  273.62
  5140.3  281.03  5197.5  286.52  5215.6  287.14  5227.4  289.12  5291.5  293.22
  5296.9  295.03  5314.6  295.75  5320.4  295.01  5325.9  296.32  5361.5     299
#Mann= 5 ,-1 , 0
  4731.3      .1       0  4838.7     .16       0  5008.3     .07       0
  5014.3     .16       0  5140.3      .1       0
Bank Sta=4981.3,5028.8
XS Rating Curve= 0 ,0
Exp/Cntr=0.3,0.1

Type RM Length L Ch R = 1 ,14343   ,490,490,490
BEGIN DESCRIPTION:
UNT071 IN BECR 22.0
END DESCRIPTION:
XS GIS Cut Line= 3
      3770299.61     10492460.19      3770199.61     10492760.19
      3770249.61     10493060.22
#Sta/Elev= 30
  4704.8  306.74  4736.4  300.56    4747  299.62  4757.5  294.73    4768  294.53
  4810.2  285.24  4820.7  284.32  4831.3  281.53  4841.8  280.79  4852.4  277.71
  4885.3  272.94  4926.2  265.29  4936.7  264.62  4947.2  260.63  4968.3  255.77
  4978.9  255.87  4996.9  249.31  4999.7  248.81  5002.9  249.31  5010.5  256.38
  5071.7  256.86    5092  258.97  5109.7  262.32  5114.8  261.58  5170.6  268.53
  5175.6  268.16  5193.4  270.73  5297.3  279.97  5304.9  281.45  5325.2  283.37
#Mann= 4 ,-1 , 0
  4704.8      .1       0  4885.3     .16       0  4996.9     .07       0
  5002.9     .16       0
Bank Sta=4978.9,5010.5
XS Rating Curve= 0 ,0
Exp/Cntr=0.3,0.1

Type RM Length L Ch R = 1 ,13853   ,557,557,557
BEGIN DESCRIPTION:
UNT071 IN BECR 21.0
END DESCRIPTION:
XS GIS Cut Line= 2
      3770332.55     10492263.52      3769304.77      10493041.3
#Sta/Elev= 30
  4504.8  310.38  4561.1  308.34  4625.6  301.25  4775.4   275.3  4798.4  269.59
  4883.6  255.86  4933.5  253.05  4975.2  254.74  4983.4  254.28  4989.7  247.25
  4994.6  246.47  4997.3  245.97  5000.6  246.47  5018.8  254.27  5039.7  254.11
  5068.8  262.07  5090.6  264.11  5168.6  273.05  5224.9  282.07  5361.3  296.94
  5418.3  297.75  5424.6  295.28    5539  288.99  5582.7  292.68  5603.5  291.89
  5611.8  294.52  5618.1  292.91  5632.7  295.86    5668  296.46  5793.7  311.13
#Mann= 5 ,-1 , 0
  4504.8      .1       0  4798.4     .16       0  4994.6     .07       0
  5000.6     .16       0  5090.6      .1       0
Bank Sta=4975.2,5018.8
XS Rating Curve= 0 ,0
Exp/Cntr=0.3,0.1

Type RM Length L Ch R = 1 ,13296   ,469,469,469
BEGIN DESCRIPTION:
UNT071 IN BECR 20.0
END DESCRIPTION:
XS GIS Cut Line= 2
      3770249.23     10492082.95      3769325.63     10492562.11
#Sta/Elev= 30
  4457.3  307.42  4550.8  304.88  4625.9  293.54  4633.7  289.25  4648.4   287.4
  4655.8   283.5  4693.5  278.53  4700.1  275.68  4777.8   265.2  4907.5  251.38
  4965.5  252.38  4975.1  251.55    4982  248.62  4987.7  249.93  4994.6  243.94
  4997.4  243.44  5000.6  243.94  5004.1  244.24  5009.8   249.2  5026.3  248.15
  5031.9  250.41  5048.4  251.58  5090.6  260.07  5247.5  276.69  5330.4  287.86
  5346.9  292.25  5352.5  291.47  5435.3  303.29  5470.8   306.7  5497.8  306.94
#Mann= 5 ,-1 , 0
  4457.3      .1       0  4777.8     .16       0  4994.6     .07       0
  5000.6     .16       0  5090.6      .1       0
Bank Sta=4965.5,5031.9
XS Rating Curve= 0 ,0
Exp/Cntr=0.3,0.1

Type RM Length L Ch R = 1 ,12827   ,584,584,584
BEGIN DESCRIPTION:
UNT071 IN BECR 19.0
END DESCRIPTION:
XS GIS Cut Line= 4
       3770290.9     10491978.78      3769867.29     10491895.45
       3769415.9     10492006.56      3769076.41     10492436.12
#Sta/Elev= 30
  4381.2  300.61    4464  300.34  4501.6  298.39    4553  289.08    4729  264.34
  4854.9  255.27  4954.7   247.7  4974.7  248.16  4992.9  243.04  4995.7  242.54
  4998.9  243.04  5026.8  249.02  5078.3  248.36  5104.4  255.14  5176.3  264.92
  5192.6  267.11  5228.9  266.83  5234.1  269.29  5243.1  269.89  5277.8  270.01
  5391.8  280.05  5398.1  282.12  5491.1  287.36  5505.6  289.83  5534.4  289.81
  5672.5  298.01  5754.4  301.07  5776.5   302.7  5797.3  301.03  5825.3  301.95
#Mann= 7 ,-1 , 0
  4381.2      .1       0  4854.9     .16       0  4992.9     .07       0
  4998.9     .16       0  5176.3      .1       0  5672.5     .05       0
  5754.4      .1       0
Bank Sta=4974.7,5026.8
XS Rating Curve= 0 ,0
Exp/Cntr=0.3,0.1

Type RM Length L Ch R = 1 ,12243   ,377,377,377
BEGIN DESCRIPTION:
UNT071 IN BECR 18.0
END DESCRIPTION:
XS GIS Cut Line= 3
      3770117.31     10491180.16      3769464.51     10491562.12
      3769096.48     10492194.03
#Sta/Elev= 30
  4364.9  313.84  4398.7  314.94  4494.6   307.5  4537.5  301.13  4611.9  283.28
  4692.1  270.29  4698.2  266.04  4707.7  268.68  4713.5  265.64  4750.7  262.02
  4756.5  256.79  4793.7  254.38  4809.4  257.22  4815.2   253.9  4943.7  245.49
  4969.7  244.76  4985.4  243.12  4996.5  238.27  4999.2  237.77  5002.5  238.27
  5012.7  243.18    5087  243.86  5163.5  253.18  5357.9  271.71  5539.8  276.49
  5610.1  282.08  5694.5   286.8  5716.1  290.92  5721.8  289.14  5852.5  295.88
#Mann= 6 ,-1 , 0
  4364.9      .1       0  4943.7     .16       0  4996.5     .07       0
  5002.5     .16       0  5163.5      .1       0  5610.1     .05       0
Bank Sta=4969.7,5012.7
XS Rating Curve= 0 ,0
Exp/Cntr=0.3,0.1

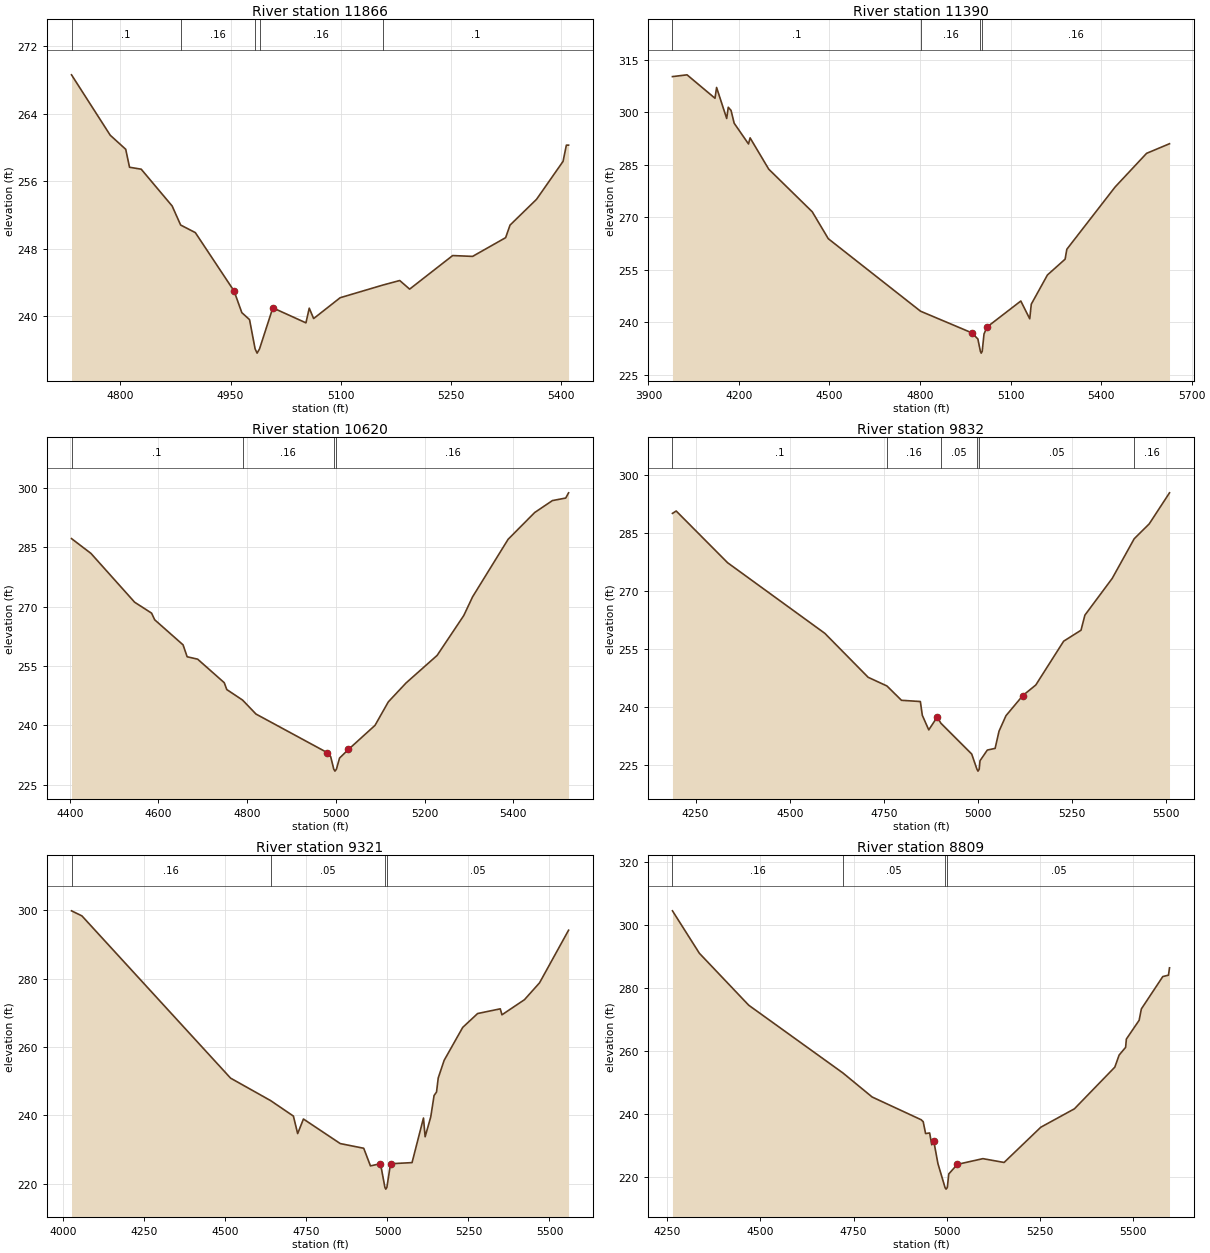
Type RM Length L Ch R = 1 ,11866   ,476,476,476
BEGIN DESCRIPTION:
UNT071 IN BECR 17.0
END DESCRIPTION:
XS GIS Cut Line= 3
       3769699.6     10491110.19      3769399.61     10491210.19
      3769199.59     10491510.21
#Sta/Elev= 30
  4733.5  268.62  4786.2  261.46  4807.3  259.79  4812.5  257.66  4828.4  257.43
  4870.5  253.07  4882.1  250.81  4902.1  249.91  4954.8  242.99  4965.4  240.42
  4975.9  239.59  4983.5  236.12  4986.2  235.62  4989.5  236.12  5007.6  240.99
  5052.7  239.21  5057.2  240.95  5063.2  239.72  5099.3  242.19  5157.4  243.69
  5180.4  244.23  5193.9  243.21  5252.5  247.19  5279.6  247.09  5324.6  249.31
  5330.6   250.8  5366.7  253.86  5402.8  258.36  5407.3  260.28  5410.3  260.28
#Mann= 5 ,-1 , 0
  4733.5      .1       0  4882.1     .16       0  4983.5     .07       0
  4989.5     .16       0  5157.4      .1       0
Bank Sta=4954.8,5007.6
XS Rating Curve= 0 ,0
Exp/Cntr=0.3,0.1

Type RM Length L Ch R = 1 ,11390   ,770,770,770
BEGIN DESCRIPTION:
UNT071 IN BECR 16.0
END DESCRIPTION:
XS GIS Cut Line= 3
      3770165.94     10490985.74      3769783.96     10490874.62
       3768554.8     10491096.84
#Sta/Elev= 30
  3979.7  310.18    4028  310.69  4120.7  303.99  4125.9  307.08  4159.4  298.21
  4164.6  301.42  4173.8  300.52  4184.2  296.86  4231.7  290.93  4236.9  292.68
  4298.7  283.73  4442.9  271.55    4496  263.86  4801.7  243.14  4971.3  236.97
  4991.7   235.2    5000  231.66  5002.7  231.16    5006  231.66    5012  236.64
  5022.2  238.63  5133.9  246.05  5163.5  240.97  5168.6  245.15  5222.1  253.49
  5280.7  258.01  5286.4  260.84  5446.3  278.63  5550.6  288.25  5626.6     291
#Mann= 4 ,-1 , 0
  3979.7      .1       0  4801.7     .16       0    5000     .07       0
    5006     .16       0
Bank Sta=4971.3,5022.2
XS Rating Curve= 0 ,0
Exp/Cntr=0.3,0.1

Type RM Length L Ch R = 1 ,10620   ,788,788,788
BEGIN DESCRIPTION:
UNT071 IN BECR 15.0
END DESCRIPTION:
XS GIS Cut Line= 3
      3769849.06     10490727.16      3769299.61     10490560.19
      3768753.18     10490560.49
#Sta/Elev= 30
    4404  287.23  4447.8  283.49  4546.4  271.14  4584.5  268.39  4591.6   266.7
  4655.5  260.37  4664.7  257.36  4688.4  256.75  4748.3  250.81  4754.1  249.07
  4789.6  246.42  4819.9  242.88  4980.8  233.11  4988.3  232.13  4995.3  228.95
    4998  228.45  5001.3  228.95  5008.3  231.75  5028.3  233.92  5088.3  240.02
  5118.3  245.96  5158.3  250.74  5228.3   257.7  5288.3  267.76  5308.3  272.51
  5388.3  287.04  5448.3  293.82  5488.3  296.84  5518.3  297.48  5524.7   298.8
#Mann= 4 ,-1 , 0
    4404      .1       0  4789.6     .16       0  4995.3     .07       0
  5001.3     .16       0
Bank Sta=4980.8,5028.3
XS Rating Curve= 0 ,0
Exp/Cntr=0.3,0.1

Type RM Length L Ch R = 1 ,9832    ,511,511,511
BEGIN DESCRIPTION:
UNT071 IN BECR 14.0
END DESCRIPTION:
XS GIS Cut Line= 3
       3769929.8     10490694.08      3769589.51      10490214.9
      3768882.87     10490020.92
#Sta/Elev= 30
  4188.5  290.05  4198.4  290.67    4335  277.29  4593.3  259.03  4708.4  247.66
  4758.4  245.41  4796.9  241.71  4847.1  241.39  4852.3  237.83  4869.4  234.06
  4891.9  237.38  4901.7  235.77  4983.5  227.81  4997.4  223.89  5000.2  223.39
  5003.4  223.89  5005.6  226.08    5025  228.84  5045.7  229.27  5056.1  233.73
  5074.5  237.72  5119.3  242.94  5153.7  245.66  5227.8     257  5273.9  259.83
  5284.2  263.73  5356.8  273.24  5415.2  283.49  5455.2  287.35    5509  295.37
#Mann= 6 ,-1 , 0
  4188.5      .1       0  4758.4     .16       0  4901.7     .05       0
  4997.4    .035       0  5003.4     .05       0  5415.2     .16       0
Bank Sta=4891.9,5119.3
XS Rating Curve= 0 ,0
Exp/Cntr=0.3,0.1

Type RM Length L Ch R = 1 ,9321    ,512,512,512
BEGIN DESCRIPTION:
UNT071 IN BECR 13.0
END DESCRIPTION:
XS GIS Cut Line= 3
      3770381.18     10489999.62      3769867.29     10489909.34
       3768888.1     10489652.39
#Sta/Elev= 30
  4024.9  299.82    4057  298.34  4515.9  250.85  4639.4  244.28  4709.7  239.75
  4722.9  234.62  4740.7  238.89  4854.4   231.7  4926.8  230.33  4947.5  225.17
  4978.5  225.82  4992.2  218.87  4994.9  218.37  4998.2  218.87  5009.5   225.8
  5075.9  226.13  5111.2  239.18  5116.3  233.69  5133.6  239.49  5143.9  245.77
  5151.5  246.79  5156.7   250.9  5174.9  256.05  5232.3   265.7  5278.3  269.76
  5348.2  271.14  5353.4  269.39    5423  273.82  5469.4  278.75    5559  294.15
#Mann= 4 ,-1 , 0
  4024.9     .16       0  4639.4     .05       0  4992.2    .035       0
  4998.2     .05       0
Bank Sta=4978.5,5009.5
XS Rating Curve= 0 ,0
Exp/Cntr=0.3,0.1

Type RM Length L Ch R = 1 ,8809    ,468,468,468
BEGIN DESCRIPTION:
UNT071 IN BECR 12.0
END DESCRIPTION:
XS GIS Cut Line= 3
      3770395.06      10489888.5       3769290.9     10489374.62
      3769194.15     10489312.42
#Sta/Elev= 30
  4264.4  304.44  4336.6  290.96    4469  274.45  4721.5  252.94  4799.9   245.3
  4931.3  238.08  4936.8  237.46  4943.2  233.69  4954.1  233.88  4959.7  230.12
  4965.3  231.21  4976.3  224.14  4995.4  216.54  4998.1  216.04  5001.4  216.54
  5005.4  220.87  5028.3   223.9  5096.9  225.72  5153.7  224.51  5252.1   235.7
  5342.3  241.55  5450.6  254.78  5462.2  258.62  5479.6  261.07  5481.6  263.71
  5515.9  269.68  5521.8  273.28  5579.3  283.56  5594.5     284  5597.3  286.33
#Mann= 4 ,-1 , 0
  4264.4     .16       0  4721.5     .05       0  4995.4    .035       0
  5001.4     .05       0
Bank Sta=4965.3,5028.3
XS Rating Curve= 0 ,0
Exp/Cntr=0.3,0.1

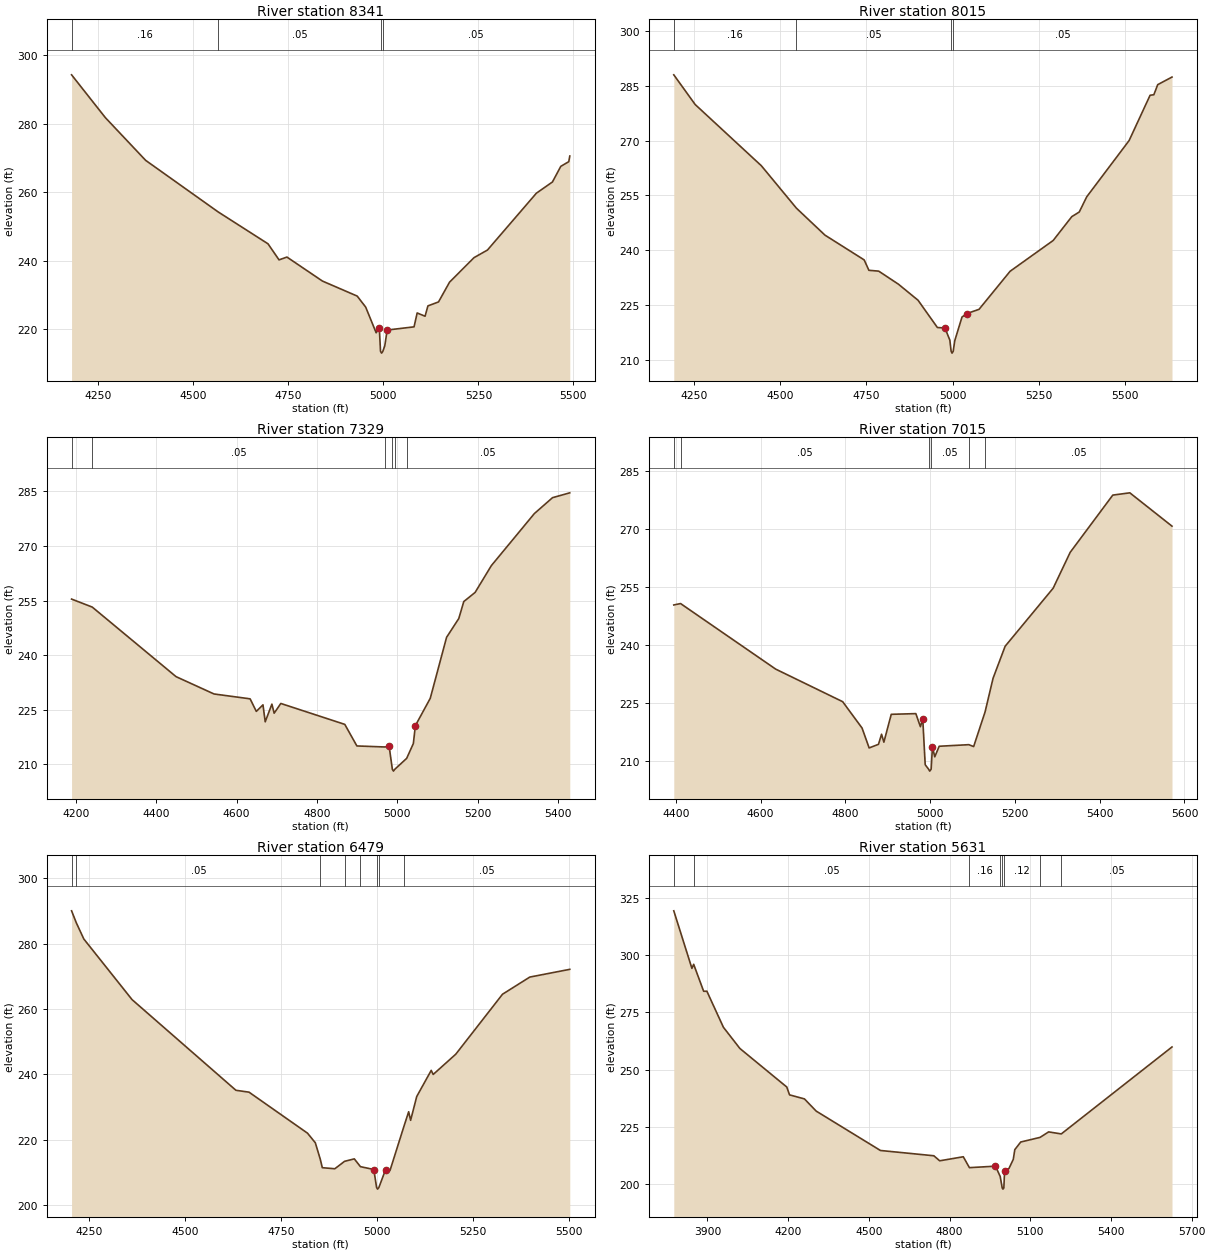
Type RM Length L Ch R = 1 ,8341    ,326,326,326
BEGIN DESCRIPTION:
UNT071 IN BECR 11.0
END DESCRIPTION:
XS GIS Cut Line= 2
      3770383.76     10489810.49      3769343.34     10489012.83
#Sta/Elev= 30
  4179.4  294.23  4268.4  281.72  4374.4  269.26  4565.2  254.21  4696.3  244.91
  4725.3  240.22  4746.1  241.04  4839.6  234.03    4931  229.65  4953.3  226.44
  4980.9  218.94  4989.1  220.48  4992.4   213.5  4995.2     213  4998.4   213.5
  5003.6  215.14  5009.9  219.74  5080.6  220.67  5088.8  224.72  5109.6  223.77
  5117.1  226.79    5145  227.94    5174  233.71  5238.4  240.87  5273.7  243.08
  5402.5  259.68  5444.7  262.95  5466.8  267.52  5487.7  268.88  5490.4  270.52
#Mann= 4 ,-1 , 0
  4179.4     .16       0  4565.2     .05       0  4992.4    .035       0
  4998.4     .05       0
Bank Sta=4989.1,5009.9
XS Rating Curve= 0 ,0
Exp/Cntr=0.3,0.1

Type RM Length L Ch R = 1 ,8015    ,686,686,686
BEGIN DESCRIPTION:
UNT071 IN BECR 10.0
END DESCRIPTION:
XS GIS Cut Line= 3
      3770381.16     10489756.54      3769783.96     10489069.06
      3769290.94     10488867.69
#Sta/Elev= 30
  4192.5  288.07  4254.4  279.94  4446.2  263.15  4547.7  251.53  4630.4  244.14
    4744  237.35  4757.7   234.5  4786.1  234.27  4843.1   230.7  4900.1  226.29
  4956.1  218.82    4978  218.69  4992.2  215.35  4995.9   212.3  4998.6   211.8
  5001.9   212.3  5006.5  215.24  5027.4  221.69  5041.6  222.65  5076.7   223.8
  5166.8  234.24  5291.5  242.67  5345.5  249.21  5367.1  250.48  5388.7  254.64
  5511.5  270.06  5572.3  282.48  5583.1  282.61  5594.4  285.38  5635.7  287.46
#Mann= 4 ,-1 , 0
  4192.5     .16       0  4547.7     .05       0  4995.9    .035       0
  5001.9     .05       0
Bank Sta=4978,5041.6
XS Rating Curve= 0 ,0
Exp/Cntr=0.3,0.1

Type RM Length L Ch R = 1 ,7329    ,314,314,314
BEGIN DESCRIPTION:
UNT071 IN BECR 9.0
END DESCRIPTION:
XS GIS Cut Line= 3
      3770283.95     10489395.43      3770020.07     10488881.56
      3769367.32     10488770.46
#Sta/Elev= 30
  4189.2   255.4  4240.7   253.2  4449.2  234.08  4543.6  229.32  4633.5  227.98
  4648.9  224.53  4665.5  226.33  4671.1  221.67  4687.7  226.53  4693.3  224.03
  4709.9  226.71  4869.1  220.96  4899.2  215.03  4968.4  214.75  4979.5   214.9
  4987.5  208.61  4990.2  208.11  4993.5  208.61  5023.1  211.62  5039.7  215.69
  5044.8  220.62  5081.8  228.13  5122.4  244.89  5152.8  250.06  5165.2  254.72
  5193.4  257.23  5233.9  264.61  5340.8   278.9  5386.1  283.28    5429  284.61
#Mann= 6 ,-1 , 0
  4189.2     .16       0  4240.7     .05       0  4968.4     .12       0
  4987.5     .07       0  4993.5     .12       0  5023.1     .05       0
Bank Sta=4979.5,5044.8
XS Rating Curve= 0 ,0
Exp/Cntr=0.3,0.1

Type RM Length L Ch R = 1 ,7015    ,536,536,536
BEGIN DESCRIPTION:
UNT071 IN BECR 8.0
END DESCRIPTION:
XS GIS Cut Line= 3
      3770547.87     10488971.85      3769797.84     10488624.62
      3769450.58     10488589.89
#Sta/Elev= 30
  4395.1   250.4  4411.1  250.77  4635.6  233.79  4793.6  225.36  4839.4  218.52
    4856  213.39  4878.1  214.32  4885.3  216.93  4890.8  214.88  4908.2  222.09
  4966.2  222.27    4977  218.89  4982.5  220.98  4988.3  209.04  4996.3  207.88
    4999  207.38  5002.3  207.88  5005.4  213.61  5010.9  211.08  5021.3  213.82
  5091.2  214.23  5102.6  213.74  5129.6  222.72  5148.4  231.42  5176.9  239.71
  5290.2  254.74  5330.4  264.03  5430.9  278.85  5471.1  279.44  5570.6  270.81
#Mann= 6 ,-1 , 0
  4395.1     .16       0  4411.1     .05       0  4996.3    .035       0
  5002.3     .05       0  5091.2     .12       0  5129.6     .05       0
Bank Sta=4982.5,5005.4
XS Rating Curve= 0 ,0
Exp/Cntr=0.3,0.1

Type RM Length L Ch R = 1 ,6479    ,848,848,848
BEGIN DESCRIPTION:
UNT071 IN BECR 7.0
END DESCRIPTION:
XS GIS Cut Line= 2
      3770804.76     10488159.35      3769527.05      10488388.5
#Sta/Elev= 30
  4204.9  290.08  4217.4  286.37  4236.8  281.45  4362.5  262.87  4633.1  235.09
  4667.3  234.51  4819.7  221.94    4840     219    4853  213.92  4858.2  211.37
  4890.8  211.04  4916.2  213.32  4941.6  214.07  4957.5  211.69  4992.4  210.81
  4999.6   205.3  5002.3   204.8  5005.6   205.3  5022.9  210.74  5034.6  210.52
  5070.6  223.94  5083.2  228.51  5088.3  225.89  5104.2  233.18    5142  241.19
  5147.1  239.94  5205.9  246.14  5327.7  264.52  5398.8  269.78    5503  272.15
#Mann= 8 ,-1 , 0
  4204.9     .16       0  4217.4     .05       0    4853     .12       0
  4916.2     .16       0  4957.5     .12       0  4999.6     .07       0
  5005.6     .12       0  5070.6     .05       0
Bank Sta=4992.4,5022.9
XS Rating Curve= 0 ,0
Exp/Cntr=0.3,0.1

Type RM Length L Ch R = 1 ,5631    ,523,523,523
BEGIN DESCRIPTION:
UNT071 IN BECR 6.0
END DESCRIPTION:
XS GIS Cut Line= 4
      3770929.75     10487839.89      3770145.07     10487666.28
      3769589.51      10487964.9      3769436.74     10488353.78
#Sta/Elev= 30
  3774.7  319.32  3842.1  294.23  3848.6  296.01  3885.7  284.25  3897.7  284.27
  3959.2  268.55  4020.6  259.29  4194.8  242.49    4205  239.08  4260.4  237.32
    4304  232.01    4543  214.83  4741.4  212.53  4763.3  210.33    4851  212.09
  4873.8  207.34  4970.6  207.99  4988.3  203.48  4995.7  198.48  4998.5  197.98
  5001.7  198.48  5004.6  205.81  5020.6  206.95  5036.9  210.98  5042.5  215.19
  5064.5  218.52  5136.4  220.54  5168.3  222.93  5215.3  222.05  5626.9  259.96
#Mann= 8 ,-1 , 0
  3774.7     .16       0  3848.6     .05       0  4873.8     .16       0
  4988.3     .12       0  4995.7     .07       0  5001.7     .12       0
  5136.4     .16       0  5215.3     .05       0
Bank Sta=4970.6,5004.6
XS Rating Curve= 0 ,0
Exp/Cntr=0.3,0.1

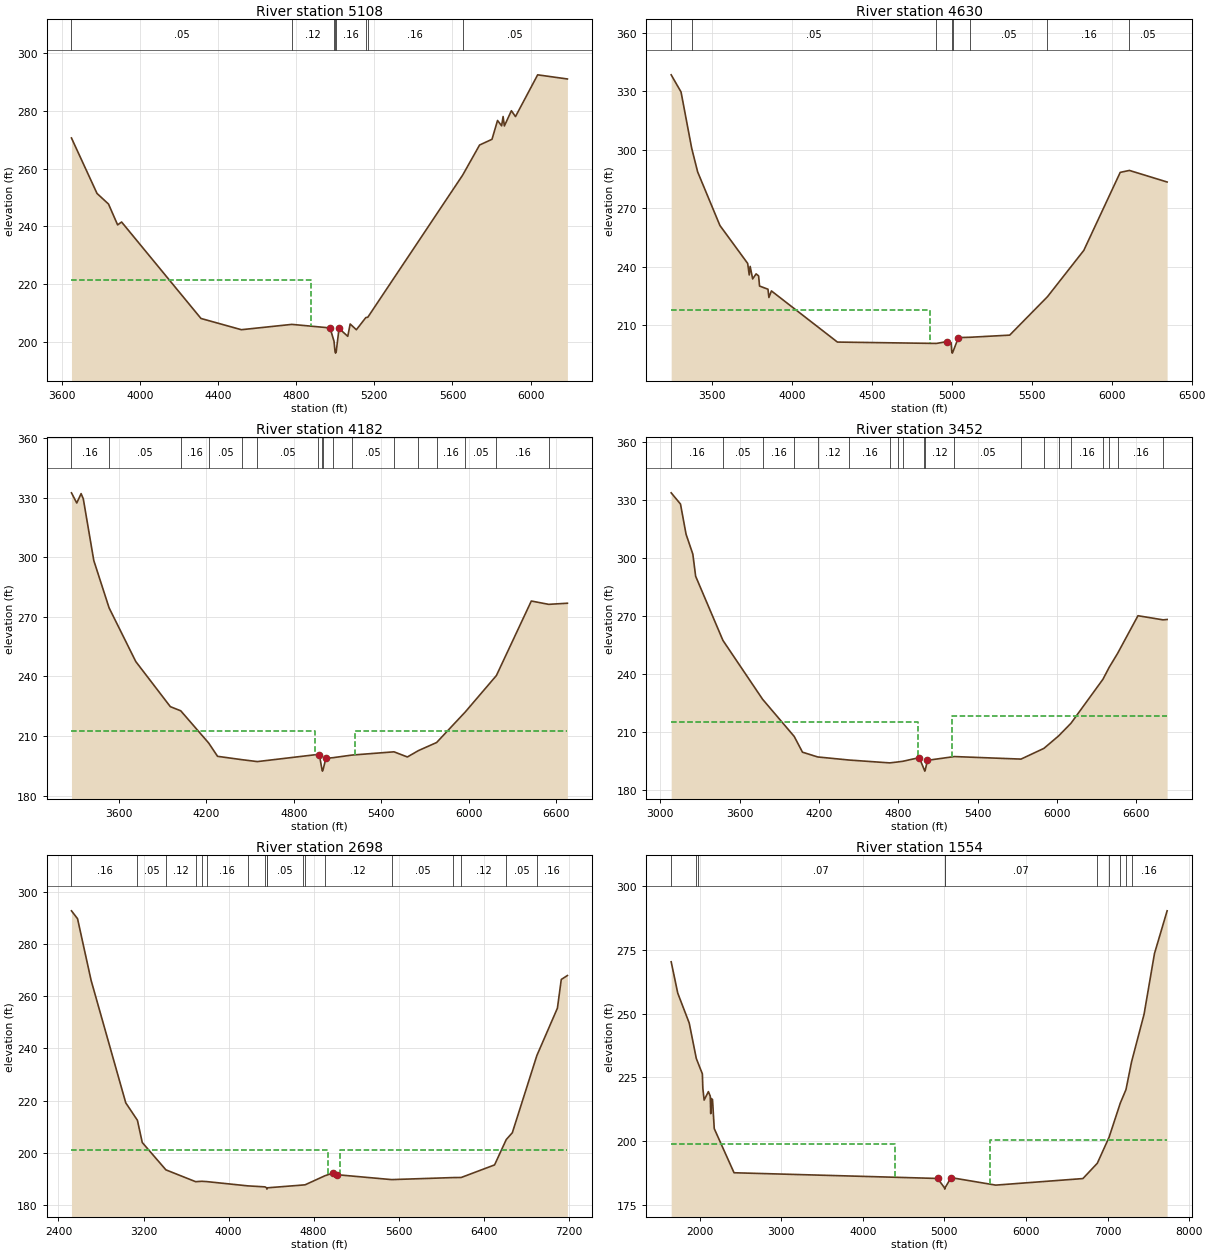
Type RM Length L Ch R = 1 ,5108    ,478,478,478
BEGIN DESCRIPTION:
UNT071 IN BECR 5.0
END DESCRIPTION:
XS GIS Cut Line= 4
      3770742.27      10487638.5      3769735.34     10487457.95
      3769117.29     10487742.67      3768499.21     10488305.19
#Sta/Elev= 30
  3649.4   270.6  3780.3  251.36  3839.1  247.69  3885.8  240.46  3906.1  241.46
  4312.5  208.01  4519.4  204.11  4777.7  205.96  4973.5  204.73  4993.7   200.1
  4998.9  196.49  5001.7  195.99  5004.9  196.49  5019.4  204.54  5064.1  201.82
  5076.3   206.1  5108.1   204.1  5156.6  208.32  5166.6  208.43  5652.2  257.71
    5739  268.16  5802.5  270.14  5830.9  276.67  5851.8  274.82  5859.3  278.04
    5866  274.78  5901.8  280.05  5922.8  278.02  6036.3   292.5  6188.6  291.06
#Mann= 8 ,-1 , 0
  3649.4     .05       0  4777.7     .12       0  4993.7     .16       0
  4998.9     .07       0  5004.9     .16       0  5156.6     .12       0
  5166.6     .16       0  5652.2     .05       0
#XS Ineff= 2 , 0
         4876.55  221.37
Permanent Ineff=
       F       F
Bank Sta=4973.5,5019.4
XS Rating Curve= 0 ,0
Exp/Cntr=0.3,0.1

Type RM Length L Ch R = 1 ,4630    ,448,448,448
BEGIN DESCRIPTION:
UNT071 IN BECR 4.0
END DESCRIPTION:
XS GIS Cut Line= 4
      3771042.63     10487503.52      3770300.45      10487069.5
      3769112.95     10487309.08      3768475.79     10488118.98
#Sta/Elev= 30
  3244.8  338.55  3306.5  329.75  3373.2  300.84  3410.5  288.72  3549.5  261.29
  3723.3   241.8  3732.9  235.88  3738.7   240.3  3754.4  233.86  3775.9  236.45
  3791.6   235.4  3797.4  230.21  3850.2  228.58    3856  224.34  3871.7  227.71
  4284.5  201.47  4903.5  200.77  4972.6  201.75  4995.5  201.09  5000.2   196.3
  5002.9   195.8  5006.2   196.3  5041.2  203.77  5112.6  203.93  5361.9  205.03
  5598.1  224.74  5825.4  248.49  6053.2  288.52  6110.6  289.51  6346.5  283.57
#Mann= 8 ,-1 , 0
  3244.8     .16       0  3373.2     .05       0  4903.5     .12       0
  5000.2     .07       0  5006.2     .12       0  5112.6     .05       0
  5598.1     .16       0  6110.6     .05       0
#XS Ineff= 2 , 0
         4864.13  217.76
Permanent Ineff=
       F       F
Bank Sta=4972.6,5041.2
XS Rating Curve= 0 ,0
Exp/Cntr=0.3,0.1

Type RM Length L Ch R = 1 ,4182    ,730,730,730
BEGIN DESCRIPTION:
Mapping XS bfa7dbed
END DESCRIPTION:
XS GIS Cut Line= 6
      3771099.06     10487442.45      3770182.37     10486824.38
      3769460.15     10487025.77      3769224.04      10487109.1
      3768967.09     10487150.77      3768439.32     10488039.64
#Sta/Elev= 30
  3276.6  332.39  3312.8  327.27  3342.8  331.99  3357.7  329.39  3429.7  298.31
  3534.6  274.48  3717.5  247.46  3954.4  224.74  4025.8  222.66    4217  206.46
  4278.2  199.74  4447.4  198.03  4551.1  197.09  4966.1   200.7  4976.3  200.47
  4994.6  192.79  4997.3  192.29  5000.6  192.79  5020.8  198.72  5069.8  199.06
  5197.9  200.36  5487.6  202.01  5579.3  199.42  5655.3  202.63  5779.8  206.69
  5976.2  222.07  6189.7  240.42    6429  277.92  6547.8  276.25  6676.4  276.81
#Mann= 17 ,-1 , 0
  3276.6     .16       0  3534.6     .05       0  4025.8     .16       0
    4217     .05       0  4447.4     .16       0  4551.1     .05       0
  4966.1     .16       0  4994.6     .04       0  5000.6     .16       0
  5069.8     .12       0  5197.9     .05       0  5487.6     .12       0
  5655.3     .05       0  5779.8     .16       0  5976.2     .05       0
  6189.7     .16       0  6547.8     .05       0
#XS Ineff= 2 , 0
         4947.21  212.72 5218.94          212.61
Permanent Ineff=
       F       F
Bank Sta=4976.3,5020.8
XS Rating Curve= 0 ,0
Exp/Cntr=0.3,0.1

Type RM Length L Ch R = 1 ,3452    ,754,754,754
BEGIN DESCRIPTION:
UNT071 IN BECR 3.0
END DESCRIPTION:
XS GIS Cut Line= 4
      3771140.32     10487405.89      3769881.61     10486581.22
      3769165.47     10486646.32      3768384.42     10487958.91
#Sta/Elev= 30
  3081.4   333.6  3151.8  327.81    3194  312.22  3245.3  301.93  3266.4  290.54
  3472.9   257.4    3773     227  4012.1  207.81  4074.5   199.7  4189.3  197.23
  4426.5  195.64  4734.8  194.16  4795.9  194.65  4834.4     195  4958.1  196.88
  4996.9  190.41  4999.7  189.91  5002.9  190.41    5020  195.49    5224  197.43
  5727.6  196.12  5900.5  201.65  6012.1   208.1  6105.9  214.66    6347  237.32
  6394.7  243.53  6458.6  250.76  6612.2  270.15  6802.4  268.01  6832.7  268.21
#Mann= 20 ,-1 , 0
  3081.4     .16       0  3472.9     .05       0    3773     .16       0
  4012.1     .05       0  4189.3     .12       0  4426.5     .16       0
  4734.8     .12       0  4795.9     .16       0  4834.4     .12       0
  4996.9     .07       0  5002.9     .12       0    5224     .05       0
  5727.6     .12       0  5900.5     .05       0  6012.1      .1       0
  6105.9     .16       0    6347     .05       0  6394.7     .08       0
  6458.6     .16       0  6802.4     .05       0
#XS Ineff= 2 , 0
         4950.31  215.46 5201.86          218.19
Permanent Ineff=
       F       F
Bank Sta=4958.1,5020
XS Rating Curve= 0 ,0
Exp/Cntr=0.3,0.1

Type RM Length L Ch R = 1 ,2698    ,1144,1144,1144
BEGIN DESCRIPTION:
UNT071 IN BECR 2.0
END DESCRIPTION:
XS GIS Cut Line= 4
      3771389.86     10486960.99      3770087.78     10485789.11
      3768883.35     10486158.04      3768199.99     10487665.77
#Sta/Elev= 30
  2522.1  292.62  2579.3  289.62  2707.1  266.01    3033  219.21  3142.8  212.53
  3188.4  204.03  3410.8  193.58  3690.2  189.06  3748.6  189.21  3794.4  189.09
    4180  187.46  4343.5  187.07  4358.9  186.71  4361.6  186.21  4364.9  186.71
  4699.1  187.78  4720.6  187.86  4907.8  191.33  4983.1  192.35    5025  191.71
  5534.3  189.85  6116.6  190.63  6189.7  190.66  6503.5  195.47  6613.3  205.15
  6670.6  207.77  6901.4  237.28  7094.9   255.4  7131.3  266.38  7188.9  267.88
#Mann= 18 ,-1 , 0
  2522.1     .16       0  3142.8     .05       0  3410.8     .12       0
  3690.2     .16       0  3748.6      .1       0  3794.4     .16       0
    4180      .1       0  4343.5     .05       0  4358.9     .07       0
  4364.9     .05       0  4699.1     .16       0  4720.6     .05       0
  4907.8     .12       0  5534.3     .05       0  6116.6     .07       0
  6189.7     .12       0  6613.3     .05       0  6901.4     .16       0
#XS Ineff= 2 , 0
         4934.78  201.01 5051.24          201.01
Permanent Ineff=
       F       F
Bank Sta=4983.1,5025
XS Rating Curve= 0 ,0
Exp/Cntr=0.3,0.1

Type RM Length L Ch R = 1 ,1554    ,0,0,0
BEGIN DESCRIPTION:
UNT071 IN BECR 1.0
END DESCRIPTION:
XS GIS Cut Line= 4
      3771726.25     10486364.21      3769523.54     10485116.37
      3768525.28     10485365.94      3766691.49     10487091.22
#Sta/Elev= 30
    1652  270.31  1732.8     258  1872.7  246.34  1959.6  232.45  1975.2  231.15
  2034.3  226.37  2040.1  220.74    2056   216.1  2107.9  219.41  2130.8  217.65
  2136.8  210.77  2142.5  216.73  2158.4  216.31    2180   204.9  2422.4  187.61
  4917.6  185.37  5002.2  181.69    5005  181.19  5008.2  181.69  5082.5   185.7
  5630.1  182.76  6698.2  185.33    6875  191.34  7018.9  201.52  7156.5  214.92
    7226  220.19  7294.1  231.03  7447.9  249.76  7575.4  273.54  7730.4  290.29
#Mann= 10 ,-1 , 0
    1652     .16       0  1959.6     .05       0  1975.2     .07       0
  5002.2     .05       0  5008.2     .07       0    6875     .12       0
  7018.9     .16       0  7156.5     .05       0    7226     .08       0
  7294.1     .16       0
#XS Ineff= 2 , 0
         4396.59  198.77 5553.98          200.28
Permanent Ineff=
       F       F
Bank Sta=4917.6,5082.5
XS Rating Curve= 0 ,0
Exp/Cntr=0.3,0.1

Chan Stop Cuts=-1
Use User Specified Reach Order=0
Composite Channel Slope=5