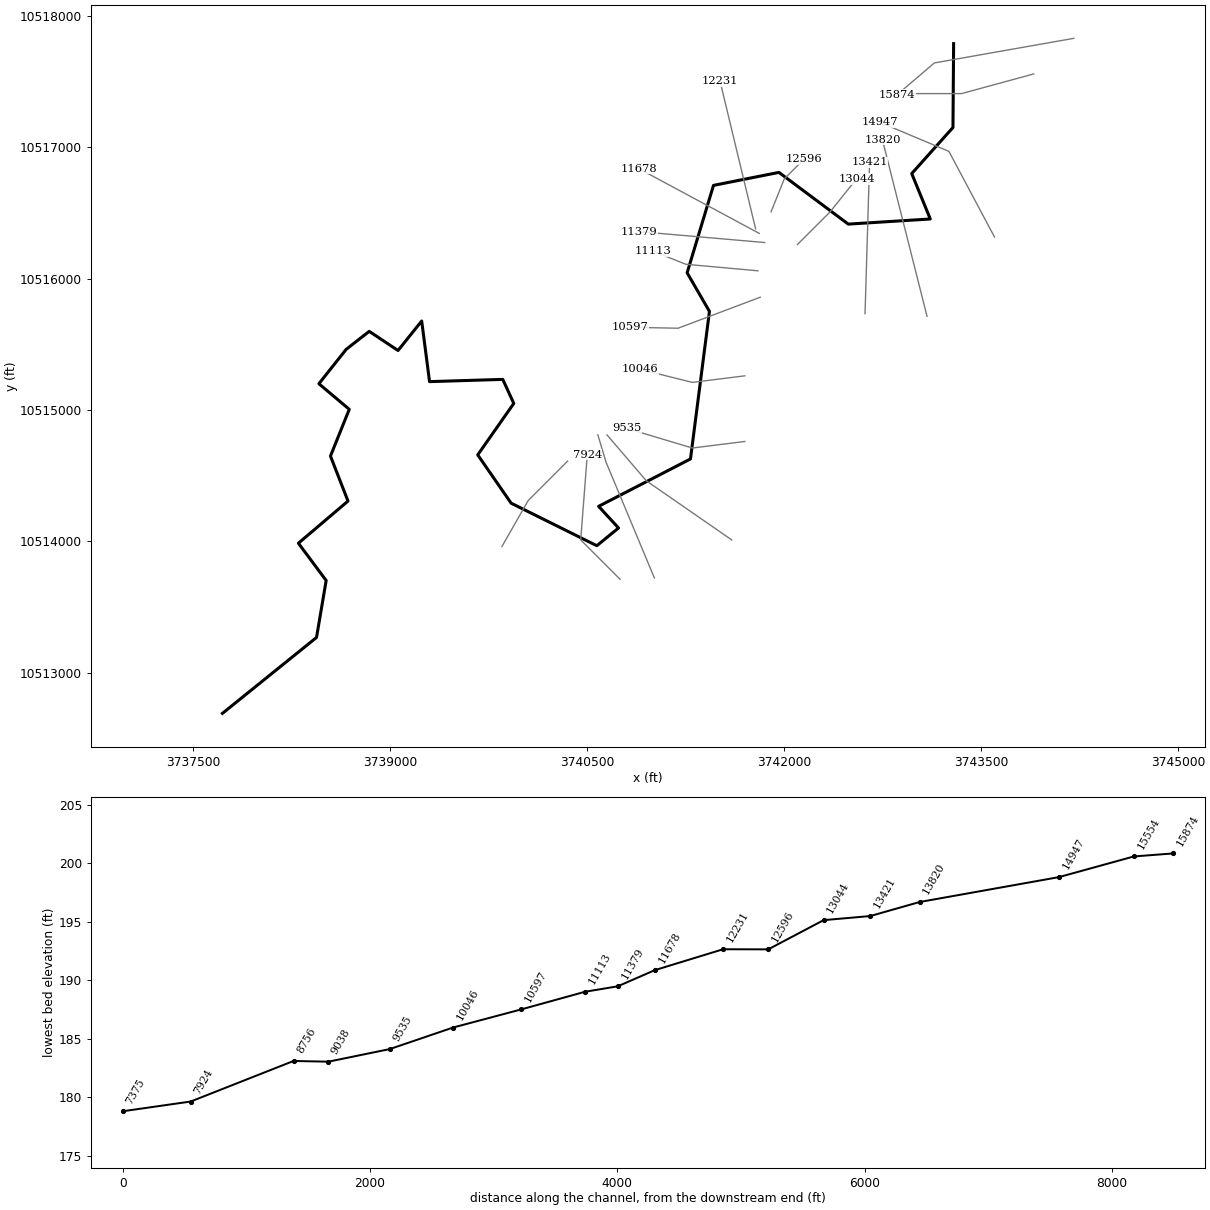
--- UNT073 IN BECR.prj (project) ---

Proj Title=UNT073 IN BECR Base Level Engineering
Current Plan=p01
Default Exp/Contr=0.3,0.1
English Units
Geom File=g01
Flow File=f01
Plan File=p01
Y Axis Title=Elevation
X Axis Title(PF)=Main Channel Distance
X Axis Title(XS)=Station
BEGIN DESCRIPTION:
UNT073 IN BECR
END DESCRIPTION:
DSS Export Rating Curves= 0
DSS Export Rating Curve Sorted= 0
DSS Export Volume Flow Curves= 0
DXF OffsetX= 0
DXF OffsetY= 0
DXF ScaleX= 1
DXF ScaleY= 10

--- UNT073 IN BECR.p01 (plan) ---

Plan Title=Multiple Run
Short Identifier=Multiple
Geom File=g01
Flow File=f01
Subcritical Flow
K Sum by GR= 0
Std Step Tol= 0.01
Critical Tol= 0.01
Num of Std Step Trials= 20
Max Error Tol= 0.3
Flow Tol Ratio= 0.001
Split Flow NTrial= 30
Split Flow Tol= 0.02
Split Flow Ratio= 0.02
Log Output Level= 0
Friction Slope Method= 1
Unsteady Friction Slope Method= 2
Unsteady Bridges Friction Slope Method= 1
Parabolic Critical Depth
Global Vel Dist=  1 , 1 , 1
Global Log Level= 0
CheckData=True
Encroach Param= -1, 0, 0, 0
BEGIN DESCRIPTION:
Multiple Run
END DESCRIPTION:

--- UNT073 IN BECR.f01 (steady flow) ---

Flow Title=Multiple
Program Version=4.10
Number of Profiles= 7
Profile Names=10-year,25-year,50-year,1pct_min,100-year,1pct_plu,500-year
River Rch & RM=UNT073 IN BECR,Reach-1         ,15874
    2258    3204    4017    3681    4978    6732    7683
Boundary for River Rch & Prof#=UNT073 IN BECR,Reach-1         , 1
Up Type= 0
Dn Type= 3
Dn Slope=0.003
Boundary for River Rch & Prof#=UNT073 IN BECR,Reach-1         , 2
Up Type= 0
Dn Type= 3
Dn Slope=0.003
Boundary for River Rch & Prof#=UNT073 IN BECR,Reach-1         , 3
Up Type= 0
Dn Type= 3
Dn Slope=0.003
Boundary for River Rch & Prof#=UNT073 IN BECR,Reach-1         , 4
Up Type= 0
Dn Type= 3
Dn Slope=0.003
Boundary for River Rch & Prof#=UNT073 IN BECR,Reach-1         , 5
Up Type= 0
Dn Type= 3
Dn Slope=0.003
Boundary for River Rch & Prof#=UNT073 IN BECR,Reach-1         , 6
Up Type= 0
Dn Type= 3
Dn Slope=0.003
Boundary for River Rch & Prof#=UNT073 IN BECR,Reach-1         , 7
Up Type= 0
Dn Type= 3
Dn Slope=0.003
DSS Import GetInterval= 0
DSS Import GetPeak= 0
DSS Import FillOption= 0

--- UNT073 IN BECR.g01 (geometry) ---

Geom Title=Existing Conditions
Program Version=4.10

River Reach=UNT073 IN BECR  ,Reach-1
Reach XY= 30
       3743289.5       10517791.       3743284.5       10517152.
       3742970.5       10516801.      3743111.75       10516455.
      3742487.25       10516416.        3741959.       10516810.
      3741460.75       10516711.        3741260.       10516045.
        3741430.       10515751.       3741285.5       10514627.
        3740586.       10514266.       3740737.5       10514101.
      3740572.25       10513966.      3739919.75       10514290.
      3739665.25       10514658.      3739939.75       10515050.
        3739856.       10515233.      3739298.25       10515216.
       3739238.5       10515678.      3739058.25       10515453.
        3738839.       10515599.       3738663.5       10515462.
       3738455.5       10515200.        3738687.       10515005.
      3738543.75       10514649.      3738677.25       10514306.
       3738299.5       10513985.        3738511.       10513701.
       3738437.5       10513267.      3737720.91     10512688.74

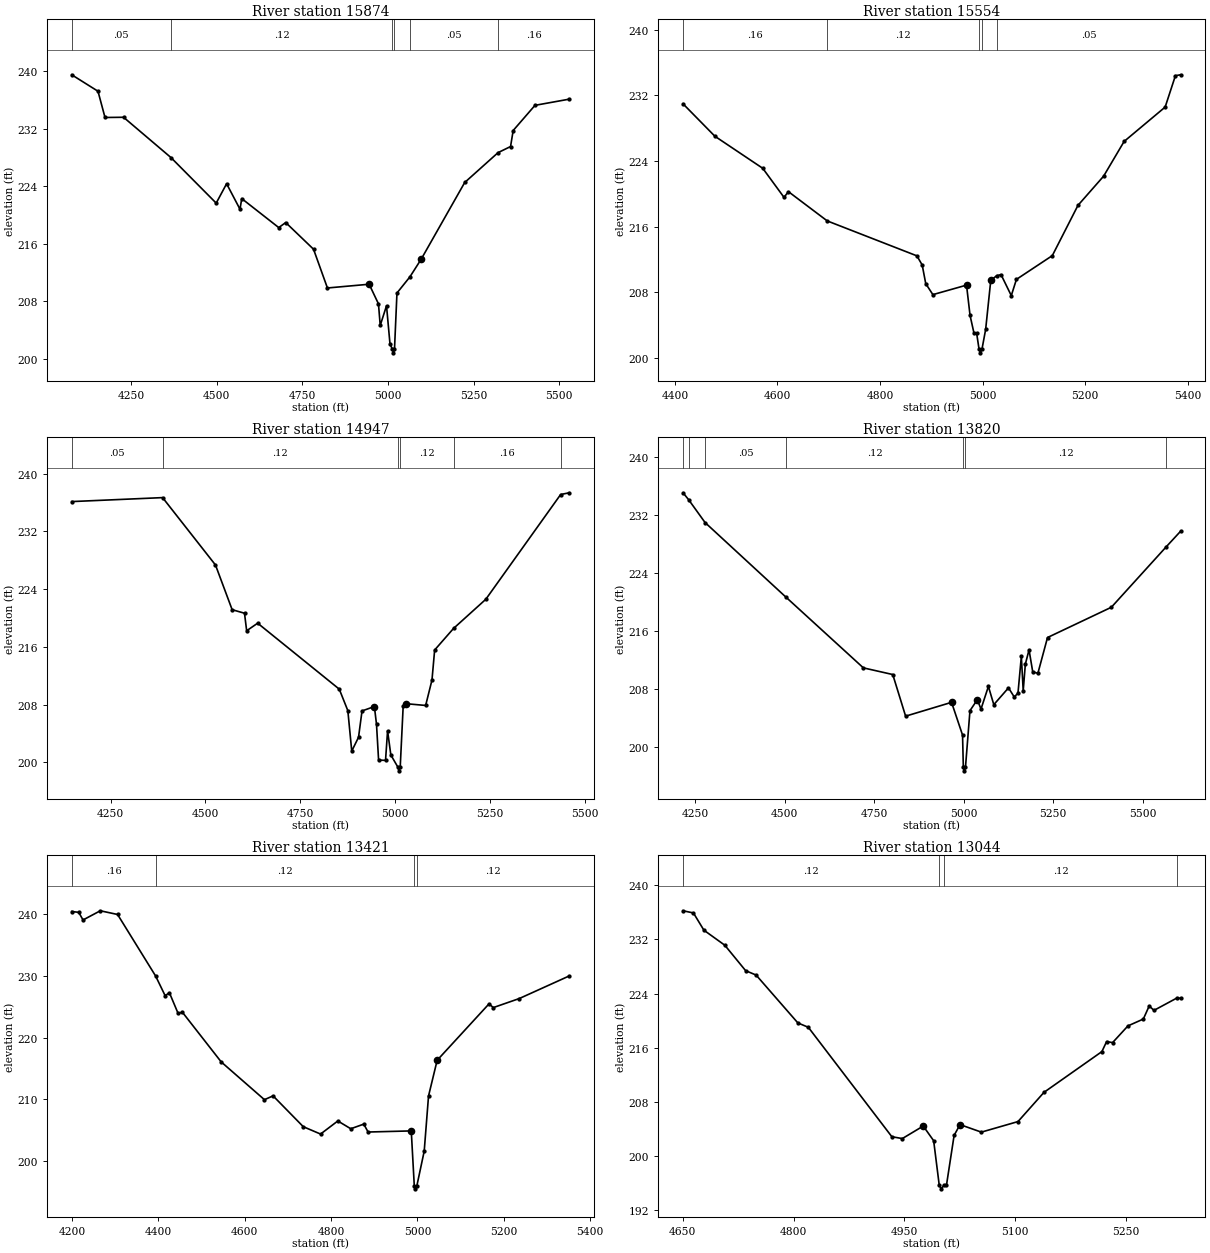
Type RM Length L Ch R = 1 ,15874   ,320,320,320
BEGIN DESCRIPTION:
UNT073 IN BECR 23.0
END DESCRIPTION:
XS GIS Cut Line= 3
      3744205.15     10517831.23      3743142.62     10517643.73
       3742857.9     10517400.67
#Sta/Elev= 30
  4076.4  239.53  4153.1  237.24  4173.6  233.59  4227.8  233.62  4366.2  228.02
  4498.4  221.68  4528.8  224.38  4567.9  220.83    4573  222.31  4681.1  218.28
  4701.5  218.98  4782.7  215.27  4823.3  209.88  4945.2   210.4  4972.4  207.67
  4977.5  204.67  4995.9  207.41  5006.1  202.07  5013.2  201.36    5016  200.86
  5019.2  201.36  5026.4  209.18  5064.3  211.43  5097.5  213.91  5224.3  224.55
  5321.6   228.7  5358.2  229.55  5365.9  231.78  5429.6  235.28  5529.7  236.14
#Mann= 6 ,-1 , 0
  4076.4     .05       0  4366.2     .12       0  5013.2     .07       0
  5019.2     .12       0  5064.3     .05       0  5321.6     .16       0
Bank Sta=4945.2,5097.5
XS Rating Curve= 0 ,0
Exp/Cntr=0.3,0.1

Type RM Length L Ch R = 1 ,15554   ,607,607,607
BEGIN DESCRIPTION:
UNT073 IN BECR 22.0
END DESCRIPTION:
XS GIS Cut Line= 3
      3743899.61     10517560.19      3743349.61     10517410.19
       3742949.6     10517410.19
#Sta/Elev= 30
  4415.8  230.98    4478  227.02  4571.3  223.11  4612.7  219.57  4621.4  220.26
  4697.1  216.69  4871.9  212.43  4882.2  211.31  4889.1  209.04    4903   207.7
  4968.6  208.86  4975.5  205.16  4983.3  202.96  4988.4  202.96  4992.9   201.1
  4995.6   200.6  4998.9   201.1  5005.9  203.46  5015.9  209.45  5027.5  210.01
  5035.9  210.14  5055.9  207.58  5065.9  209.56  5135.9  212.46  5185.9  218.59
  5235.9  222.15  5275.9  226.39  5355.9  230.58  5375.9  234.41  5385.9  234.52
#Mann= 5 ,-1 , 0
  4415.8     .16       0  4697.1     .12       0  4992.9     .07       0
  4998.9     .12       0  5027.5     .05       0
Bank Sta=4968.6,5015.9
XS Rating Curve= 0 ,0
Exp/Cntr=0.3,0.1

Type RM Length L Ch R = 1 ,14947   ,1127,1127,1127
BEGIN DESCRIPTION:
UNT073 IN BECR 21.0
END DESCRIPTION:
XS GIS Cut Line= 3
      3743600.94     10516317.36      3743253.73     10516970.12
      3742725.96     10517192.33
#Sta/Elev= 30
  4147.5  236.14  4387.1  236.69  4526.6  227.35  4570.5  221.16  4603.1  220.67
  4608.8  218.24  4637.8  219.29    4853  210.15  4875.6  207.17  4885.9  201.57
  4903.8  203.48    4913  207.13  4945.6  207.74  4951.2  205.28  4956.7  200.32
    4975  200.28  4980.4  204.38    4989  201.03  5007.7  199.33  5010.4  198.83
  5013.7  199.33  5021.5  207.76  5027.9  208.14  5080.8  207.89  5097.5  211.42
  5104.5  215.57  5154.3  218.56  5239.4   222.6  5436.8  237.12  5459.5  237.36
#Mann= 6 ,-1 , 0
  4147.5     .05       0  4387.1     .12       0  5007.7     .07       0
  5013.7     .12       0  5154.3     .16       0  5436.8     .12       0
Bank Sta=4945.6,5027.9
XS Rating Curve= 0 ,0
Exp/Cntr=0.3,0.1

Type RM Length L Ch R = 1 ,13820   ,399,399,399
BEGIN DESCRIPTION:
UNT073 IN BECR 20.0
END DESCRIPTION:
XS GIS Cut Line= 2
      3743087.05     10515713.22      3742746.78     10517060.41
#Sta/Elev= 30
    4216   235.1  4231.5  234.16  4277.6  230.99  4503.2   220.7  4719.7  210.92
  4801.8     210  4837.7  204.25    4966  206.16  4996.7  201.64  4998.9   197.2
  5001.6   196.7  5004.9   197.2  5017.4  205.01  5037.8  206.51  5048.3  205.24
  5068.9  208.36    5084  205.84    5125  208.16  5141.1   206.9  5151.5  207.43
  5160.9   212.5  5166.1  207.77  5172.1  211.44  5182.4  213.41  5192.7  210.37
  5207.1  210.17    5234  215.11  5412.3  219.29  5566.1  227.67  5605.5  229.78
#Mann= 7 ,-1 , 0
    4216     .05       0  4231.5     .12       0  4277.6     .05       0
  4503.2     .12       0  4998.9     .07       0  5004.9     .12       0
  5566.1     .16       0
Bank Sta=4966,5037.8
XS Rating Curve= 0 ,0
Exp/Cntr=0.3,0.1

Type RM Length L Ch R = 1 ,13421   ,377,377,377
BEGIN DESCRIPTION:
UNT073 IN BECR 19.0
END DESCRIPTION:
XS GIS Cut Line= 2
      3742614.84     10515734.04      3742649.54     10516886.01
#Sta/Elev= 30
  4199.3  240.45  4215.5  240.32  4225.5  239.08  4265.5  240.57  4305.5  239.97
  4393.6     230  4415.6  226.82  4425.6  227.28  4445.6  223.95  4455.6  224.13
  4545.6  216.07  4645.7  209.95  4665.7  210.57  4735.7  205.57  4775.7  204.38
  4815.7   206.5  4845.7  205.24  4875.8  205.99  4885.8  204.71  4985.8  204.89
  4992.8     196  4995.6   195.5  4998.8     196  5015.8  201.61  5025.8  210.55
  5045.8  216.34  5165.9  225.48  5175.9  224.88  5235.9  226.34  5351.8  230.01
#Mann= 4 ,-1 , 0
  4199.3     .16       0  4393.6     .12       0  4992.8     .07       0
  4998.8     .12       0
Bank Sta=4985.8,5045.8
XS Rating Curve= 0 ,0
Exp/Cntr=0.3,0.1

Type RM Length L Ch R = 1 ,13044   ,448,448,448
BEGIN DESCRIPTION:
UNT073 IN BECR 18.0
END DESCRIPTION:
XS GIS Cut Line= 3
      3742099.62      10516260.2      3742349.61     10516510.19
      3742549.61     10516760.19
#Sta/Elev= 30
  4650.3  236.24  4664.4  235.92  4678.6  233.37  4706.9  231.15  4735.1  227.39
  4749.3  226.74  4805.8  219.67    4820  219.02  4933.1  202.85  4947.3  202.58
  4975.6  204.43  4989.7  202.26  4997.3  195.65  5000.1  195.15  5003.3  195.65
    5007  195.65  5017.4  203.05  5025.4  204.64  5054.3  203.53  5103.9  205.09
  5139.1  209.41  5217.5  215.43  5223.9  216.91    5232  216.76  5252.8  219.23
  5273.6  220.24  5281.6  222.18    5288  221.52  5319.6  223.38    5324  223.29
#Mann= 4 ,-1 , 0
  4650.3     .12       0  4997.3     .07       0  5003.3     .12       0
  5319.6     .16       0
Bank Sta=4975.6,5025.4
XS Rating Curve= 0 ,0
Exp/Cntr=0.3,0.1

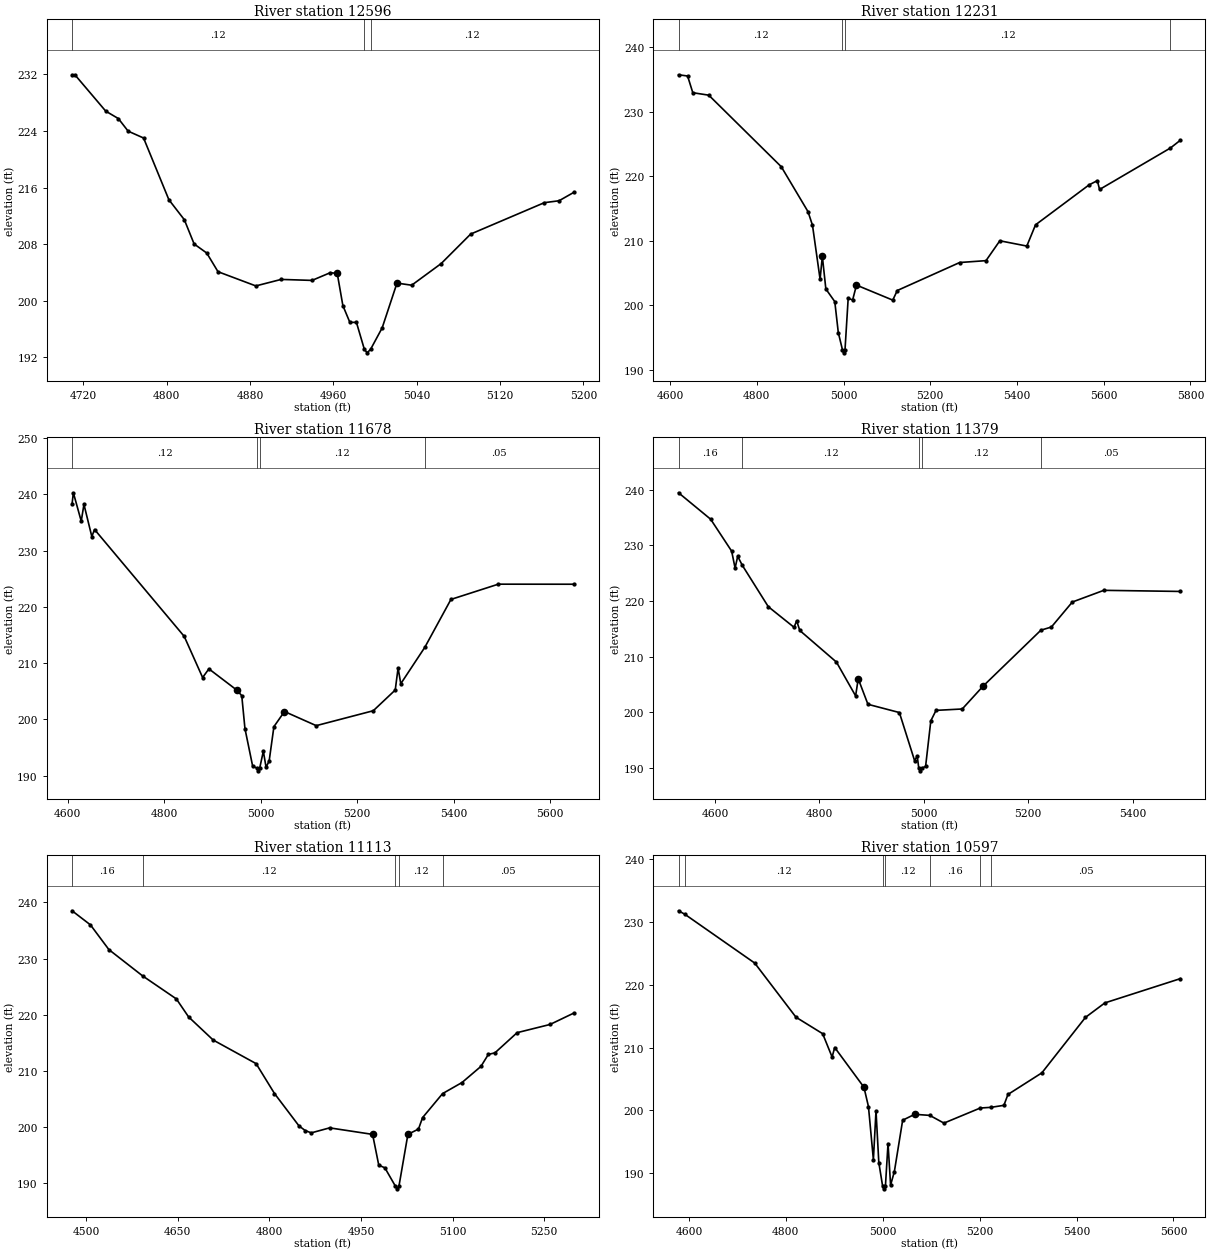
Type RM Length L Ch R = 1 ,12596   ,365,365,365
BEGIN DESCRIPTION:
UNT073 IN BECR 17.0
END DESCRIPTION:
XS GIS Cut Line= 3
      3741899.62     10516510.22      3741999.61     10516760.19
      3742149.64     10516910.22
#Sta/Elev= 30
  4709.4  231.96  4712.1  231.96  4741.7  226.82  4753.8  225.77  4763.2  223.99
    4778  223.02  4802.3  214.29  4817.1  211.47  4826.5  208.04  4838.6  206.76
  4849.4  204.12  4885.7  202.11    4910  203.03  4939.6  202.89  4957.1  203.98
  4963.8  203.88  4969.2  199.33  4975.9  196.96  4982.2  196.96  4989.8  193.15
  4992.5  192.65  4995.8  193.15  5006.9  196.18  5021.1  202.51  5035.2  202.21
  5063.5  205.27  5091.8  209.44  5162.5  213.88  5176.6  214.15  5190.8  215.34
#Mann= 3 ,-1 , 0
  4709.4     .12       0  4989.8     .07       0  4995.8     .12       0
Bank Sta=4963.8,5021.1
XS Rating Curve= 0 ,0
Exp/Cntr=0.3,0.1

Type RM Length L Ch R = 1 ,12231   ,553,553,553
BEGIN DESCRIPTION:
UNT073 IN BECR 16.0
END DESCRIPTION:
XS GIS Cut Line= 2
       3741781.5     10516379.88      3741510.68     10517504.84
#Sta/Elev= 30
  4619.6  235.76  4640.5  235.57  4652.5  232.98  4689.3   232.6  4856.5  221.51
  4918.2  214.54  4928.5  212.43    4946  204.07  4951.2  207.62  4959.3  202.56
  4979.9   200.6    4988   195.8  4997.5  193.16  5000.2  192.66  5003.5  193.16
  5010.8  201.11  5021.1  200.86  5029.9  203.16  5113.6  200.83    5124  202.32
  5267.9  206.66  5328.6  206.95  5360.5  210.03  5422.7  209.21  5442.8   212.5
  5566.2  218.69  5585.3  219.35  5590.5  217.98  5753.9  224.41  5776.7  225.61
#Mann= 4 ,-1 , 0
  4619.6     .12       0  4997.5     .07       0  5003.5     .12       0
  5753.9     .05       0
Bank Sta=4951.2,5029.9
XS Rating Curve= 0 ,0
Exp/Cntr=0.3,0.1

Type RM Length L Ch R = 1 ,11678   ,299,299,299
BEGIN DESCRIPTION:
Mapping XS e34c3e65
END DESCRIPTION:
XS GIS Cut Line= 2
      3741809.29     10516345.12      3740893.64     10516837.62
#Sta/Elev= 30
  4609.1  238.31  4611.8  240.28  4628.1  235.23  4633.7  238.22    4650  232.51
  4655.7  233.75  4841.5  214.76  4879.6  207.45  4892.6  208.99    4951  205.18
  4960.7  204.22  4967.3  198.38  4983.4  191.65  4991.9  191.37  4994.6  190.87
  4997.9  191.37  5005.4  194.35  5011.1   191.5  5017.5  192.64  5027.3  198.72
  5049.2  201.41    5115   198.9  5233.2  201.55  5278.7  205.23  5284.6  209.14
  5290.2  206.35    5340  212.82  5394.1  221.33  5492.3  224.04  5648.8  224.03
#Mann= 4 ,-1 , 0
  4609.1     .12       0  4991.9     .07       0  4997.9     .12       0
    5340     .05       0
Bank Sta=4951,5049.2
XS Rating Curve= 0 ,0
Exp/Cntr=0.3,0.1

Type RM Length L Ch R = 1 ,11379   ,266,266,266
BEGIN DESCRIPTION:
UNT073 IN BECR 15.0
END DESCRIPTION:
XS GIS Cut Line= 2
       3741850.9     10516275.68      3740893.62     10516358.92
#Sta/Elev= 30
  4530.3  239.43  4591.8  234.68    4632  228.95  4638.6  225.91  4643.6  228.02
  4652.3  226.42  4702.2  218.97  4751.5  215.27  4756.5  216.44  4762.5   214.7
  4832.7  209.02  4869.4  202.95  4874.4  206.02    4893  201.44  4953.2  199.96
  4982.3  191.33  4987.4  192.13  4990.3  189.99  4993.1  189.49  4996.3  189.99
  5003.4  190.27  5013.4  198.47  5023.4  200.35  5073.6   200.6  5113.8  204.73
  5224.2  214.75  5244.3  215.32  5284.4  219.81  5344.7  221.91  5491.2  221.71
#Mann= 5 ,-1 , 0
  4530.3     .16       0  4652.3     .12       0  4990.3     .07       0
  4996.3     .12       0  5224.2     .05       0
Bank Sta=4874.4,5113.8
XS Rating Curve= 0 ,0
Exp/Cntr=0.3,0.1

Type RM Length L Ch R = 1 ,11113   ,516,516,516
BEGIN DESCRIPTION:
UNT073 IN BECR 14.0
END DESCRIPTION:
XS GIS Cut Line= 3
      3741799.62     10516060.19      3741249.61     10516110.19
      3740999.65     10516210.17
#Sta/Elev= 30
    4477   238.5  4507.1  235.99  4537.3  231.59  4592.4  226.92  4647.7  222.82
  4667.8  219.61    4708   215.5  4778.3   211.3  4808.4  205.98  4848.5  200.22
  4858.6   199.4  4868.6  198.98  4898.7  199.87    4969  198.71  4979.1  193.23
  4989.1  192.76  5006.2  189.52    5009  189.02  5012.2  189.52  5026.8  198.72
  5044.1  199.65  5050.8  201.69  5083.6  205.97  5115.4  207.94  5146.4  210.81
  5158.5  212.94  5169.3  213.22  5205.6  216.81  5259.5  218.27  5298.5   220.3
#Mann= 5 ,-1 , 0
    4477     .16       0  4592.4     .12       0  5006.2     .07       0
  5012.2     .12       0  5083.6     .05       0
Bank Sta=4969,5026.8
XS Rating Curve= 0 ,0
Exp/Cntr=0.3,0.1

Type RM Length L Ch R = 1 ,10597   ,551,551,551
BEGIN DESCRIPTION:
UNT073 IN BECR 13.0
END DESCRIPTION:
XS GIS Cut Line= 3
      3741816.24     10515859.01      3741191.23     10515622.89
      3740823.92     10515629.82
#Sta/Elev= 30
  4578.6  231.76  4591.3  231.22  4735.8  223.44    4821  214.82    4876   212.2
  4895.5  208.49  4900.9     210  4961.2  203.68  4970.5  200.61  4980.7  192.16
  4986.1  199.93  4991.9   191.7  4999.6  188.01  5002.3  187.51  5005.6  188.01
  5010.9  194.72  5016.2  188.11    5024  190.26  5041.1  198.43  5065.9  199.37
    5097   199.2  5126.3  197.97  5201.2  200.37  5223.4  200.48    5250   200.8
  5258.4  202.53  5328.4  205.97  5418.4   214.8  5458.4   217.1  5614.1  220.96
#Mann= 7 ,-1 , 0
  4578.6     .16       0  4591.3     .12       0  4999.6     .07       0
  5005.6     .12       0    5097     .16       0  5201.2     .12       0
  5223.4     .05       0
Bank Sta=4961.2,5065.9
XS Rating Curve= 0 ,0
Exp/Cntr=0.3,0.1

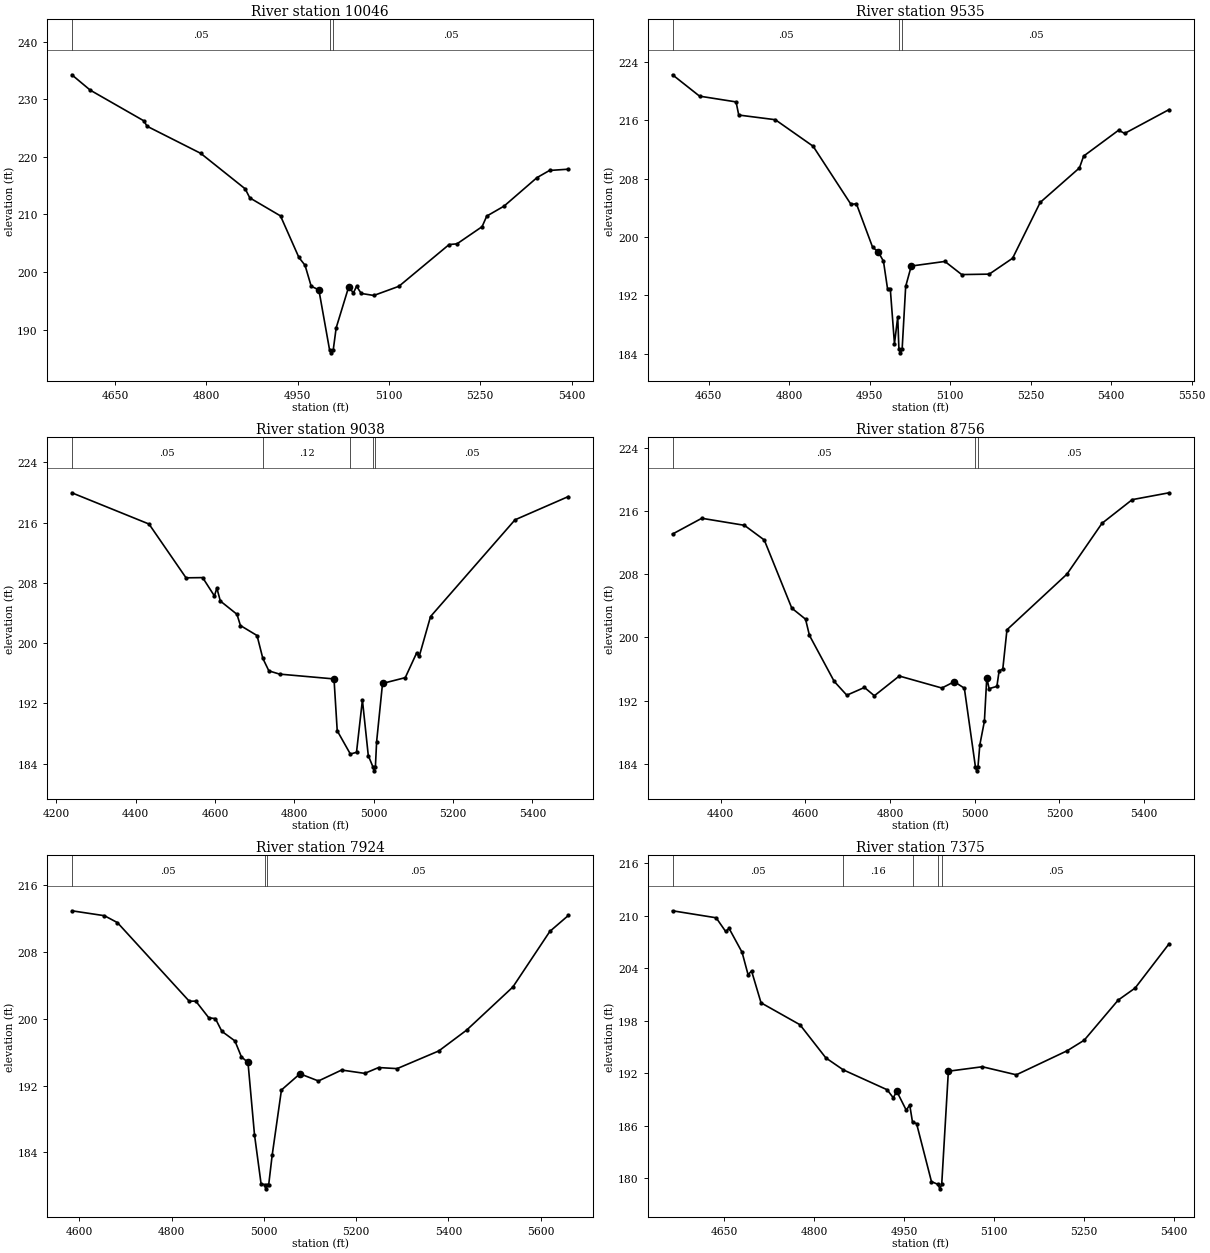
Type RM Length L Ch R = 1 ,10046   ,511,511,511
BEGIN DESCRIPTION:
UNT073 IN BECR 12.0
END DESCRIPTION:
XS GIS Cut Line= 3
      3741699.63     10515260.19      3741299.61     10515210.19
      3740899.65     10515310.18
#Sta/Elev= 30
  4579.2  234.23  4609.5  231.56  4697.6  226.23  4702.7   225.3  4790.9  220.59
  4863.9  214.43  4871.5  212.86  4921.9  209.73  4952.1  202.52  4962.2  201.16
  4972.3  197.52  4984.9  196.89  5002.5  186.46  5005.3  185.96  5008.5  186.46
  5013.3  190.29  5033.9  197.42  5041.6  196.34  5046.8  197.52  5054.5  196.27
  5075.1  195.92  5116.3  197.51  5198.8  204.76  5211.7  204.88  5252.9  207.86
  5260.6   209.7    5289  211.43  5343.1  216.38  5363.7  217.62  5394.6  217.84
#Mann= 3 ,-1 , 0
  4579.2     .05       0  5002.5     .03       0  5008.5     .05       0
Bank Sta=4984.9,5033.9
XS Rating Curve= 0 ,0
Exp/Cntr=0.3,0.1

Type RM Length L Ch R = 1 ,9535    ,497,497,497
BEGIN DESCRIPTION:
UNT073 IN BECR 11.0
END DESCRIPTION:
XS GIS Cut Line= 3
      3741699.58     10514760.19      3741299.61     10514710.19
      3740799.61     10514860.19
#Sta/Elev= 30
  4582.8  222.24  4633.2  219.31  4701.2  218.52  4706.2  216.72  4774.3  216.08
  4844.8  212.44  4915.3  204.47  4925.4  204.56  4955.7  198.57  4965.7  198.01
  4975.8  196.68  4983.4  192.91  4988.5  192.91  4996.3  185.38  5002.4  189.04
  5004.6  184.62  5007.4  184.12  5010.6  184.62  5017.2  193.23  5027.6  196.02
  5090.3  196.65  5121.6  194.85  5172.9  194.91  5216.4  197.09  5267.8  204.74
  5340.9  209.47  5348.7  211.09  5413.9  214.64  5425.2   214.2  5507.9  217.47
#Mann= 3 ,-1 , 0
  4582.8     .05       0  5004.6     .03       0  5010.6     .05       0
Bank Sta=4965.7,5027.6
XS Rating Curve= 0 ,0
Exp/Cntr=0.3,0.1

Type RM Length L Ch R = 1 ,9038    ,282,282,282
BEGIN DESCRIPTION:
UNT073 IN BECR 10.0
END DESCRIPTION:
XS GIS Cut Line= 3
      3741599.63     10514010.18      3740949.61     10514460.19
      3740649.59     10514810.21
#Sta/Elev= 30
  4238.8  219.95  4433.4   215.8  4526.7  208.66  4568.6  208.69  4598.3  206.25
  4604.4   207.3  4613.2  205.58  4655.1  203.82  4663.8  202.33  4705.7     201
  4720.2  197.98  4735.5  196.31  4762.5  195.88  4899.7  195.24  4907.8  188.36
  4940.9  185.27  4956.4   185.5  4971.3  192.44  4986.1  185.07    4998  183.54
  5000.8  183.04    5004  183.54  5007.1  186.91    5022  194.64  5079.3  195.41
  5107.9  198.68  5114.5  198.24    5143  203.52  5355.9  216.36  5490.4  219.45
#Mann= 5 ,-1 , 0
  4238.8     .05       0  4720.2     .12       0  4940.9     .05       0
    4998     .03       0    5004     .05       0
Bank Sta=4899.7,5022
XS Rating Curve= 0 ,0
Exp/Cntr=0.3,0.1

Type RM Length L Ch R = 1 ,8756    ,832,832,832
BEGIN DESCRIPTION:
UNT073 IN BECR 9.0
END DESCRIPTION:
XS GIS Cut Line= 3
      3741010.67     10513720.12      3740642.62     10514602.06
      3740580.11     10514810.43
#Sta/Elev= 30
    4286  213.09  4355.1  215.09  4455.8   214.2  4502.8  212.34  4567.8  203.71
  4600.3  202.31  4609.5  200.26    4668  194.43  4697.8  192.68  4739.5  193.66
  4762.9  192.61  4821.7  195.11  4922.4  193.59  4951.7  194.39  4975.5  193.57
  5001.7   183.6  5004.5   183.1  5007.7   183.6  5012.1   186.4  5022.9  189.38
  5028.5  194.89    5034  193.51  5052.4   193.8  5057.8   195.8  5066.3  195.97
  5076.2  200.97    5218  208.02  5300.7  214.45  5372.1  217.45  5459.2  218.32
#Mann= 3 ,-1 , 0
    4286     .05       0  5001.7     .03       0  5007.7     .05       0
Bank Sta=4951.7,5028.5
XS Rating Curve= 0 ,0
Exp/Cntr=0.3,0.1

Type RM Length L Ch R = 1 ,7924    ,549,549,549
BEGIN DESCRIPTION:
UNT073 IN BECR 8.0
END DESCRIPTION:
XS GIS Cut Line= 3
      3740749.57     10513710.22      3740449.61     10514010.19
      3740499.61     10514660.15
#Sta/Elev= 30
  4583.7  212.96  4654.4  212.37  4682.6  211.54  4838.2  202.12  4852.4  202.13
  4880.6  200.13  4894.8  200.04  4908.9  198.51  4937.2  197.36  4951.3  195.44
  4965.5  194.79  4979.6  186.12  4993.8  180.26  5001.4  180.13  5004.1  179.63
  5007.4  180.13  5010.4  180.13  5017.9  183.65    5038  191.48  5078.1  193.42
  5118.2  192.56  5168.4  193.87  5218.5  193.47  5248.6  194.17  5288.7  194.04
    5379  196.16  5439.2  198.65  5539.5  203.82  5619.7  210.49  5659.8   212.4
#Mann= 3 ,-1 , 0
  4583.7     .05       0  5001.4     .03       0  5007.4     .05       0
Bank Sta=4965.5,5078.1
XS Rating Curve= 0 ,0
Exp/Cntr=0.3,0.1

Type RM Length L Ch R = 1 ,7375    ,0,0,0
BEGIN DESCRIPTION:
UNT073 IN BECR 7.0
END DESCRIPTION:
XS GIS Cut Line= 3
      3739849.63     10513960.22      3740049.61     10514310.19
      3740349.58     10514610.16
#Sta/Elev= 30
  4564.1  210.55  4636.8  209.75  4652.6  208.19  4658.4  208.53    4680  205.81
    4690  203.25  4695.8  203.68  4711.6  200.04  4776.4  197.54  4819.6  193.75
  4848.5  192.39  4921.8  190.11  4931.9  189.19  4937.7  189.94  4953.5  187.78
  4959.3  188.38    4964  186.39  4970.7  186.26  4995.5  179.63  5006.6   179.3
  5009.4   178.8  5012.6   179.3  5023.7  192.23  5080.3  192.74  5136.9  191.82
  5221.7  194.57    5250  195.77  5306.6  200.35  5334.9  201.73  5391.4  206.78
#Mann= 5 ,-1 , 0
  4564.1     .05       0  4848.5     .16       0    4964     .05       0
  5006.6     .03       0  5012.6     .05       0
Bank Sta=4937.7,5023.7
XS Rating Curve= 0 ,0
Exp/Cntr=0.3,0.1

Chan Stop Cuts=-1
Use User Specified Reach Order=0
Composite Channel Slope=5