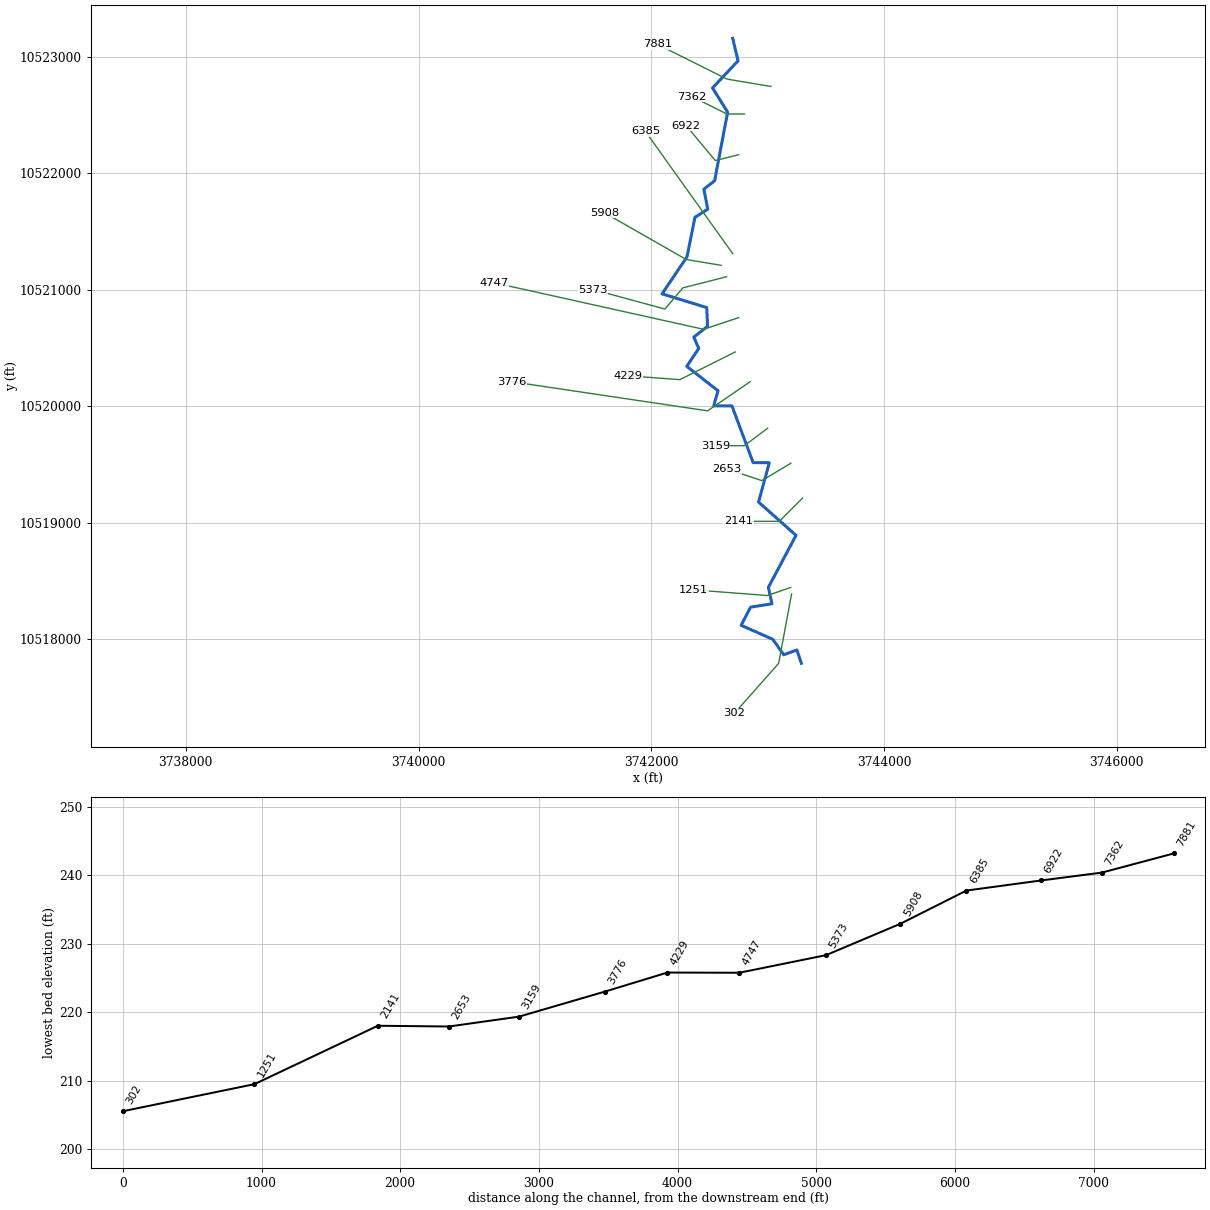
--- UNT074 IN BECR.prj (project) ---

Proj Title=UNT074 IN BECR Base Level Engineering
Current Plan=p01
Default Exp/Contr=0.3,0.1
English Units
Geom File=g01
Flow File=f01
Plan File=p01
Y Axis Title=Elevation
X Axis Title(PF)=Main Channel Distance
X Axis Title(XS)=Station
BEGIN DESCRIPTION:
UNT074 IN BECR
END DESCRIPTION:
DSS Export Rating Curves= 0
DSS Export Rating Curve Sorted= 0
DSS Export Volume Flow Curves= 0
DXF OffsetX= 0
DXF OffsetY= 0
DXF ScaleX= 1
DXF ScaleY= 10

--- UNT074 IN BECR.p01 (plan) ---

Plan Title=Multiple Run
Short Identifier=Multiple
Geom File=g01
Flow File=f01
Subcritical Flow
K Sum by GR= 0
Std Step Tol= 0.01
Critical Tol= 0.01
Num of Std Step Trials= 20
Max Error Tol= 0.3
Flow Tol Ratio= 0.001
Split Flow NTrial= 30
Split Flow Tol= 0.02
Split Flow Ratio= 0.02
Log Output Level= 0
Friction Slope Method= 1
Unsteady Friction Slope Method= 2
Unsteady Bridges Friction Slope Method= 1
Parabolic Critical Depth
Global Vel Dist=  1 , 1 , 1
Global Log Level= 0
CheckData=True
Encroach Param= -1, 0, 0, 0
BEGIN DESCRIPTION:
Multiple Run
END DESCRIPTION:

--- UNT074 IN BECR.f01 (steady flow) ---

Flow Title=Multiple
Program Version=4.10
Number of Profiles= 7
Profile Names=10-year,25-year,50-year,1pct_min,100-year,1pct_plu,500-year
River Rch & RM=UNT074 IN BECR,Reach-1         ,7881
     379     489     574     494     668     904     911
Boundary for River Rch & Prof#=UNT074 IN BECR,Reach-1         , 1
Up Type= 0
Dn Type= 1
Dn Known WS=213.52
Boundary for River Rch & Prof#=UNT074 IN BECR,Reach-1         , 2
Up Type= 0
Dn Type= 1
Dn Known WS=214.69
Boundary for River Rch & Prof#=UNT074 IN BECR,Reach-1         , 3
Up Type= 0
Dn Type= 1
Dn Known WS=215.58
Boundary for River Rch & Prof#=UNT074 IN BECR,Reach-1         , 4
Up Type= 0
Dn Type= 1
Dn Known WS=215.24
Boundary for River Rch & Prof#=UNT074 IN BECR,Reach-1         , 5
Up Type= 0
Dn Type= 1
Dn Known WS=216.45
Boundary for River Rch & Prof#=UNT074 IN BECR,Reach-1         , 6
Up Type= 0
Dn Type= 1
Dn Known WS=217.86
Boundary for River Rch & Prof#=UNT074 IN BECR,Reach-1         , 7
Up Type= 0
Dn Type= 1
Dn Known WS=218.53
DSS Import GetInterval= 0
DSS Import GetPeak= 0
DSS Import FillOption= 0

--- UNT074 IN BECR.g01 (geometry) ---

Geom Title=Existing Conditions
Program Version=4.10

River Reach=UNT074 IN BECR  ,Reach-1
Reach XY= 30
      3742699.54     10523160.19      3742745.25       10522967.
        3742526.       10522734.      3742655.75       10522526.
      3742544.25       10521937.       3742451.5       10521864.
      3742484.75       10521692.       3742375.5       10521623.
        3742306.       10521282.       3742092.4     10520964.87
        3742476.       10520847.       3742483.5       10520687.
       3742365.5       10520593.       3742407.5       10520496.
      3742304.75       10520342.       3742573.5       10520132.
        3742536.       10520003.        3742693.       10520002.
      3742874.75       10519515.        3743014.       10519514.
      3742921.25       10519176.      3743243.25       10518890.
      3743005.75       10518443.       3743036.5       10518302.
        3742853.       10518273.      3742771.75       10518117.
       3743043.5       10517997.        3743138.       10517864.
       3743250.5       10517905.       3743289.5       10517791.

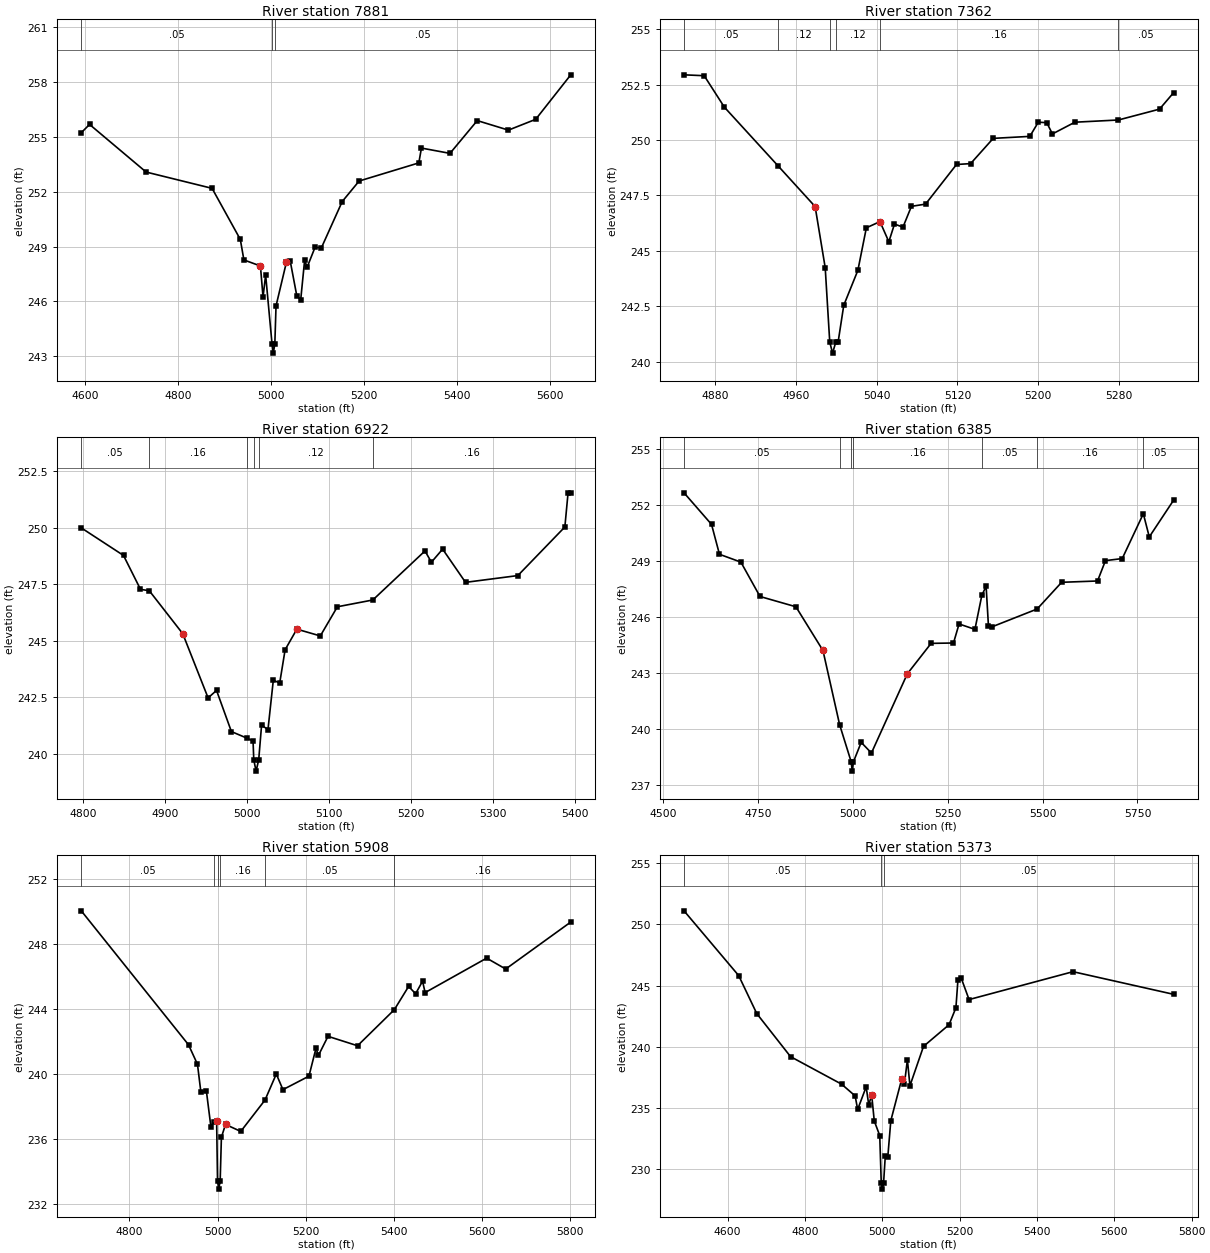
Type RM Length L Ch R = 1 ,7881    ,519,519,519
BEGIN DESCRIPTION:
UNT074 IN BECR 13.0
END DESCRIPTION:
XS GIS Cut Line= 3
      3743027.28     10522746.79      3742649.61     10522810.19
      3742049.59      10523110.2
#Sta/Elev= 30
  4591.7  255.22  4609.6  255.67  4731.3  253.07  4873.3  252.18  4934.1  249.39
  4941.8  248.27  4977.4  247.94    4983  246.24  4988.6  247.45  5002.4  243.68
  5005.1  243.18  5008.4  243.68    5011  245.76  5033.4  248.15  5041.7  248.19
  5055.7  246.31  5064.1  246.09  5072.5  248.24  5078.1  247.88  5094.8  248.95
  5108.8  248.94  5153.5  251.46  5189.9  252.58  5318.4  253.57    5324  254.38
  5385.5  254.09  5444.2  255.88  5511.3  255.36    5570  255.95  5645.5  258.38
#Mann= 3 ,-1 , 0
  4591.7     .05       0  5002.4     .03       0  5008.4     .05       0
Bank Sta=4977.4,5033.4
XS Rating Curve= 0 ,0
Exp/Cntr=0.3,0.1

Type RM Length L Ch R = 1 ,7362    ,440,440,440
BEGIN DESCRIPTION:
UNT074 IN BECR 12.0
END DESCRIPTION:
XS GIS Cut Line= 3
      3742799.64     10522510.19      3742649.61     10522510.19
      3742349.64     10522660.17
#Sta/Elev= 30
  4848.9  252.95  4868.9  252.91  4888.9  251.49  4942.3  248.83  4978.9     247
  4988.9  244.24  4993.4  240.88  4996.2  240.38  4999.4  240.88  5001.7  240.88
  5007.3  242.54  5021.3  244.12  5029.7  246.04  5043.2  246.32    5052  245.41
  5057.6  246.21    5066  246.07  5074.4  247.01  5088.4  247.11  5119.1   248.9
  5133.1  248.94  5155.5  250.08  5191.8  250.17  5200.2  250.81  5208.6  250.79
  5214.2  250.28  5236.5  250.81  5279.6  250.91  5320.4   251.4  5334.3  252.14
#Mann= 6 ,-1 , 0
  4848.9     .05       0  4942.3     .12       0  4993.4     .07       0
  4999.4     .12       0  5043.2     .16       0  5279.6     .05       0
Bank Sta=4978.9,5043.2
XS Rating Curve= 0 ,0
Exp/Cntr=0.3,0.1

Type RM Length L Ch R = 1 ,6922    ,537,537,537
BEGIN DESCRIPTION:
UNT074 IN BECR 11.0
END DESCRIPTION:
XS GIS Cut Line= 3
      3742749.61     10522160.19      3742549.61     10522110.19
      3742299.59     10522410.21
#Sta/Elev= 30
  4797.8  249.99  4849.3  248.77    4870  247.27  4880.7  247.21  4921.5  245.31
  4952.4  242.47  4962.7   242.8  4980.8  240.98  4999.7  240.69  5007.2  240.56
  5008.1  239.73  5010.9  239.23  5014.1  239.73  5017.6  241.26  5025.4  241.07
  5031.9  243.25  5039.7  243.13  5046.3   244.6  5060.6  245.51  5089.2  245.21
    5110   246.5  5153.2   246.8  5216.8  248.97  5224.6  248.47  5238.3  249.05
  5266.2  247.58    5330  247.88  5387.3  250.03  5391.2  251.54  5394.5  251.54
#Mann= 6 ,-1 , 0
  4797.8     .05       0  4880.7     .16       0  4999.7     .12       0
  5008.1     .07       0  5014.1     .12       0  5153.2     .16       0
Bank Sta=4921.5,5060.6
XS Rating Curve= 0 ,0
Exp/Cntr=0.3,0.1

Type RM Length L Ch R = 1 ,6385    ,477,477,477
BEGIN DESCRIPTION:
UNT074 IN BECR 10.0
END DESCRIPTION:
XS GIS Cut Line= 3
      3742699.59     10521310.21      3742449.61     10521660.19
      3741949.62     10522360.17
#Sta/Elev= 30
  4554.8  252.66  4627.3  250.97  4648.2  249.37  4704.7  248.95  4755.1  247.11
  4849.7  246.56    4921  244.22  4964.9  240.25  4995.4  238.26  4998.2  237.76
  5001.4  238.26  5021.8   239.3  5048.8  238.73  5143.4  242.97  5206.1   244.6
  5265.1  244.62  5279.8  245.64  5321.6  245.35  5339.8  247.17  5351.1  247.66
  5357.2  245.55  5365.9  245.48  5485.6  246.44  5550.2  247.87  5644.8  247.94
  5665.7  249.03  5709.9  249.14  5765.5  251.54  5781.2   250.3  5845.1  252.26
#Mann= 7 ,-1 , 0
  4554.8     .05       0  4964.9     .16       0  4995.4     .07       0
  5001.4     .16       0  5339.8     .05       0  5485.6     .16       0
  5765.5     .05       0
Bank Sta=4921,5143.4
XS Rating Curve= 0 ,0
Exp/Cntr=0.3,0.1

Type RM Length L Ch R = 1 ,5908    ,535,535,535
BEGIN DESCRIPTION:
UNT074 IN BECR 9.0
END DESCRIPTION:
XS GIS Cut Line= 3
      3742599.64     10521210.18      3742299.61     10521260.19
      3741599.61     10521660.19
#Sta/Elev= 30
  4690.6  250.03  4933.9  241.79  4954.2  240.59  4961.8  238.91  4974.5  238.93
  4984.6  236.76  4991.5  237.05  4997.7  237.08  4999.7  233.41  5002.4  232.91
  5005.7  233.41  5008.5   236.1  5017.8  236.89  5052.4  236.46  5107.4  238.39
    5133  239.99  5148.1  239.03  5207.1  239.86    5223  241.57  5228.7  241.14
  5250.3  242.31  5317.3  241.73  5400.8  243.95  5433.2  245.38    5449  244.93
  5464.8   245.7  5470.6     245  5610.2  247.12  5653.4  246.45    5801  249.34
#Mann= 6 ,-1 , 0
  4690.6     .05       0  4991.5     .16       0  4999.7     .07       0
  5005.7     .16       0  5107.4     .05       0  5400.8     .16       0
Bank Sta=4997.7,5017.8
XS Rating Curve= 0 ,0
Exp/Cntr=0.3,0.1

Type RM Length L Ch R = 1 ,5373    ,626,626,626
BEGIN DESCRIPTION:
UNT074 IN BECR 8.0
END DESCRIPTION:
XS GIS Cut Line= 4
       3742646.6     10521111.76      3742271.18     10521016.15
      3742117.27     10520834.26      3741499.34     10521002.15
#Sta/Elev= 30
  4487.1  251.11  4628.5  245.81  4675.3   242.7  4762.6  239.18  4894.5  236.93
  4929.6  235.97  4936.2  234.86  4958.2  236.71  4964.8  235.24  4972.5  236.04
  4979.1  233.92  4993.3  232.72  4997.2  228.84    5000  228.34  5003.2  228.84
  5007.6  231.04  5014.2     231  5021.9  233.94  5050.5  237.39  5057.1  236.95
  5064.8  238.92  5071.4   236.8  5106.5  240.02  5172.5  241.79  5190.3  243.18
  5195.5  245.45  5203.6  245.64  5224.3  243.85  5493.1  246.13  5753.1  244.28
#Mann= 3 ,-1 , 0
  4487.1     .05       0  4997.2     .03       0  5003.2     .05       0
Bank Sta=4972.5,5050.5
XS Rating Curve= 0 ,0
Exp/Cntr=0.3,0.1

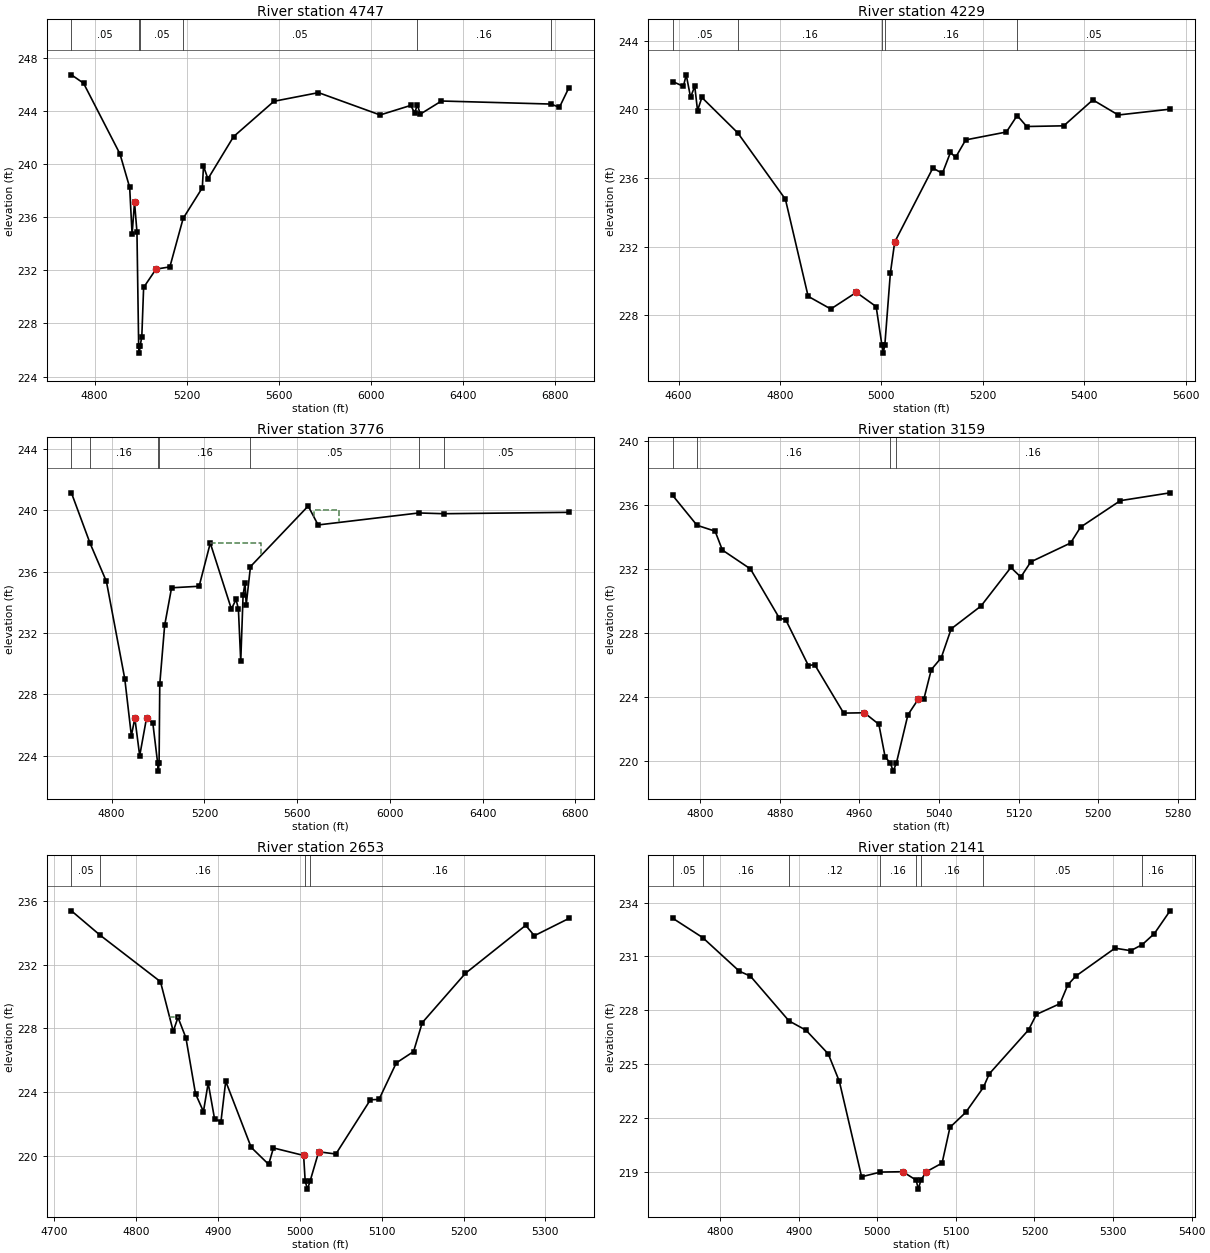
Type RM Length L Ch R = 1 ,4747    ,518,518,518
BEGIN DESCRIPTION:
UNT074 IN BECR 7.0
END DESCRIPTION:
XS GIS Cut Line= 3
       3742749.6     10520760.18      3742449.61     10520660.19
      3740649.63     10521060.18
#Sta/Elev= 30
  4699.7  246.71  4752.4  246.08  4910.5  240.76  4952.7  238.24  4963.2  234.71
  4973.8  237.13  4984.3  234.89  4991.8  226.27  4994.6  225.77  4997.8  226.27
  5005.4  227.01  5013.3  230.71  5067.1  232.09  5127.3  232.26    5185  235.91
  5268.2  238.21  5273.3  239.84  5292.5  238.88  5403.9  242.06  5579.3  244.72
  5772.7  245.37  6040.3  243.69  6173.5  244.41  6190.1  243.84  6202.2  244.45
  6214.5  243.75  6306.7  244.74  6782.8  244.51  6818.8  244.26  6859.8  245.73
#Mann= 6 ,-1 , 0
  4699.7     .05       0  4991.8     .07       0  4997.8     .05       0
    5185     .05       0  6202.2     .16       0  6782.8     .05       0
Bank Sta=4973.8,5067.1
XS Rating Curve= 0 ,0
Exp/Cntr=0.3,0.1

Type RM Length L Ch R = 1 ,4229    ,453,453,453
BEGIN DESCRIPTION:
UNT074 IN BECR 6.0
END DESCRIPTION:
XS GIS Cut Line= 3
      3742721.26     10520465.82      3742245.53     10520227.95
       3741797.8      10520260.6
#Sta/Elev= 30
  4588.4  241.62  4609.6  241.34  4615.2  242.01  4623.8   240.7    4632  241.35
  4637.5  239.93  4646.1  240.69  4716.8  238.63  4810.8  234.76  4855.6  229.11
  4900.3  228.37  4950.6  229.34  4989.7  228.51  5000.9   226.3  5003.7   225.8
  5006.9   226.3  5017.7  230.45  5026.3  232.27  5101.5  236.58  5120.3  236.27
  5136.2  237.49  5146.3   237.2  5166.3  238.22  5246.5  238.68  5267.8  239.64
  5286.6     239  5359.6  239.04    5417  240.55  5467.1  239.67  5569.2  240.01
#Mann= 5 ,-1 , 0
  4588.4     .05       0  4716.8     .16       0  5000.9     .07       0
  5006.9     .16       0  5267.8     .05       0
Bank Sta=4950.6,5026.3
XS Rating Curve= 0 ,0
Exp/Cntr=0.3,0.1

Type RM Length L Ch R = 1 ,3776    ,617,617,617
BEGIN DESCRIPTION:
UNT074 IN BECR 5.0
END DESCRIPTION:
XS GIS Cut Line= 3
       3742849.6     10520210.19      3742483.39     10519959.78
      3740799.65     10520210.18
#Sta/Elev= 30
  4626.3  241.12  4706.7  237.84  4777.3  235.35  4856.5  229.02    4885  225.31
  4899.9  226.46  4920.9  224.01  4950.7  226.49  4977.7  226.12  4998.5  223.51
  5001.2  223.01  5004.5  223.51  5007.5  228.68  5028.5  232.49  5058.4  234.94
  5177.3  235.04  5225.4  237.85  5316.4  233.56  5336.6  234.18  5346.7  233.56
  5356.8  230.15    5367  234.49  5375.3  235.25  5380.4  233.84  5398.8  236.32
  5647.8  240.26  5690.5  239.03  6125.2  239.81  6232.2  239.76  6772.2  239.85
#Mann= 7 ,-1 , 0
  4626.3     .05       0  4706.7     .16       0  4998.5     .07       0
  5004.5     .16       0  5398.8     .05       0  6125.2     .16       0
  6232.2     .05       0
#XS Ineff= 2 ,-1
 5225.85  5444.6  237.84 5671.88 5782.67  239.99
Permanent Ineff=
       F       F
Bank Sta=4899.9,4950.7
XS Rating Curve= 0 ,0
Exp/Cntr=0.3,0.1

Type RM Length L Ch R = 1 ,3159    ,506,506,506
BEGIN DESCRIPTION:
UNT074 IN BECR 4.0
END DESCRIPTION:
XS GIS Cut Line= 3
      3742999.64     10519810.21      3742799.61     10519660.19
      3742549.65     10519660.19
#Sta/Elev= 30
  4772.2  236.62  4796.7  234.75  4814.9  234.38  4822.2   233.2  4850.4  232.02
  4879.5  228.94  4885.8  228.85  4908.7  225.97  4914.9  226.04  4944.1     223
  4964.9  223.02  4979.5   222.3  4985.8  220.26  4991.1  219.87  4993.9  219.37
  4997.1  219.87  5008.7  222.89  5019.1  223.87  5024.7  223.87  5032.2  225.72
  5042.2  226.46  5052.2  228.27  5082.2   229.7  5112.2  232.11  5122.2  231.51
  5132.2  232.46  5172.2  233.64  5182.2  234.63  5222.2  236.29  5272.2  236.78
#Mann= 4 ,-1 , 0
  4772.2     .05       0  4796.7     .16       0  4991.1     .07       0
  4997.1     .16       0
Bank Sta=4964.9,5019.1
XS Rating Curve= 0 ,0
Exp/Cntr=0.3,0.1

Type RM Length L Ch R = 1 ,2653    ,512,512,512
BEGIN DESCRIPTION:
UNT074 IN BECR 3.0
END DESCRIPTION:
XS GIS Cut Line= 3
      3743199.59     10519510.18      3742949.61     10519360.19
      3742649.66     10519460.17
#Sta/Elev= 30
  4720.9  235.37  4755.8  233.85  4829.7  230.93  4845.3  227.82  4851.1  228.69
  4860.8  227.41  4872.5  223.91  4882.2  222.79    4888  224.58  4895.8  222.33
  4903.6  222.16  4909.4  224.69  4940.5  220.55  4961.9  219.48  4967.7  220.51
  5004.6  220.04  5006.5  218.43  5009.3  217.93  5012.5  218.43    5023  220.27
    5044  220.13  5086.2  223.53  5096.7  223.55  5117.8  225.84  5138.9  226.55
  5149.5  228.36  5202.2  231.45  5275.9  234.46  5286.5  233.81  5328.6  234.89
#Mann= 4 ,-1 , 0
  4720.9     .05       0  4755.8     .16       0  5006.5     .07       0
  5012.5     .16       0
#XS Ineff= 1 ,-1
 4841.19 4851.53  228.69
Permanent Ineff=
       F
Bank Sta=5004.6,5023
XS Rating Curve= 0 ,0
Exp/Cntr=0.3,0.1

Type RM Length L Ch R = 1 ,2141    ,890,890,890
BEGIN DESCRIPTION:
UNT074 IN BECR 2.0
END DESCRIPTION:
XS GIS Cut Line= 3
      3743299.58     10519210.16      3743099.61     10519010.19
      3742749.62     10519010.19
#Sta/Elev= 30
  4739.7  233.13  4777.9  232.05  4824.5  230.18  4838.7   229.9  4887.7  227.41
  4909.4  226.89  4937.7  225.57  4951.8  224.04  4980.1  218.73  5004.1  218.99
  5032.5  219.01  5049.5  218.54  5052.3  218.04  5055.5  218.54  5062.5  219.01
  5082.5  219.49  5092.5  221.48  5112.5  222.31  5135.1  223.71  5142.5  224.46
  5192.5  226.91  5202.5  227.77  5232.5  228.37  5242.5  229.42  5252.5   229.9
  5302.5  231.46  5322.5  231.32  5337.2  231.66  5352.5  232.27  5372.5  233.54
#Mann= 8 ,-1 , 0
  4739.7     .05       0  4777.9     .16       0  4887.7     .12       0
  5004.1     .16       0  5049.5     .07       0  5055.5     .16       0
  5135.1     .05       0  5337.2     .16       0
Bank Sta=5032.5,5062.5
XS Rating Curve= 0 ,0
Exp/Cntr=0.3,0.1

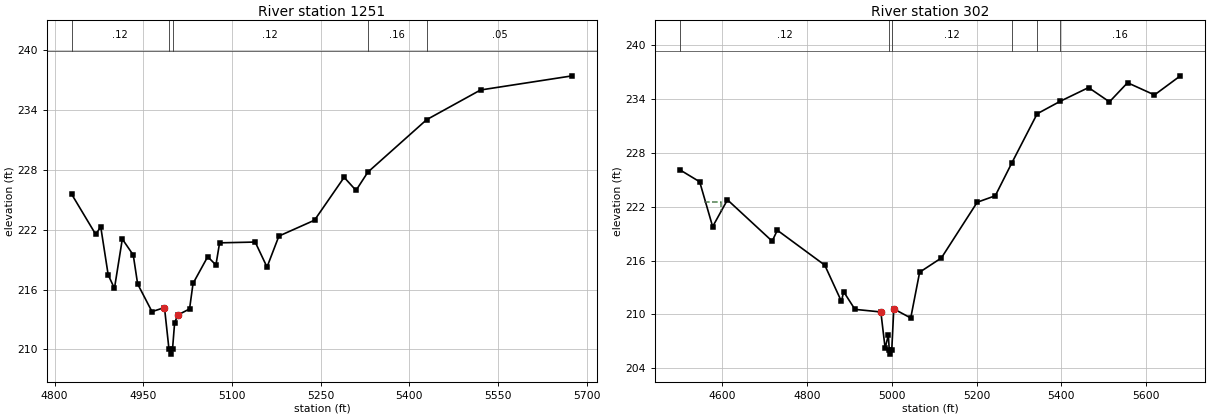
Type RM Length L Ch R = 1 ,1251    ,949,949,949
BEGIN DESCRIPTION:
Mapping XS 1ba4c369
END DESCRIPTION:
XS GIS Cut Line= 3
      3743198.17     10518442.34      3742996.79     10518372.89
      3742364.87      10518421.5
#Sta/Elev= 30
  4828.8  225.57  4869.6  221.53  4878.1  222.29  4890.7  217.47  4901.3  216.11
  4914.6  221.06  4933.1  219.46  4940.5  216.56  4964.8  213.78  4985.9  214.19
  4993.5  210.02  4996.3  209.52  4999.5  210.02    5003  212.63  5008.2  213.44
  5028.3  214.05  5034.2  216.61    5059  219.29  5072.9  218.46  5079.1  220.68
  5139.3  220.76  5159.3  218.25  5179.4  221.36  5239.6  222.95  5289.7  227.25
  5309.8  225.94  5329.8  227.77  5429.2  233.03  5520.4  236.01  5675.6  237.43
#Mann= 5 ,-1 , 0
  4828.8     .12       0  4993.5     .07       0  4999.5     .12       0
  5329.8     .16       0  5429.2     .05       0
Bank Sta=4985.9,5008.2
XS Rating Curve= 0 ,0
Exp/Cntr=0.3,0.1

Type RM Length L Ch R = 1 ,302     ,0,0,0
BEGIN DESCRIPTION:
UNT074 IN BECR 1.0
END DESCRIPTION:
XS GIS Cut Line= 3
      3743205.11     10518386.73      3743094.01     10517789.56
      3742713.31     10517360.41
#Sta/Elev= 30
  4499.5  226.13  4546.8  224.78  4577.4  219.78  4612.3  222.77  4717.8  218.16
  4729.9  219.38  4841.8  215.49  4881.2  211.44  4886.3  212.53    4913  210.56
  4974.1  210.27  4984.2  206.24  4991.8  207.69  4993.9  206.07  4996.6  205.57
  4999.9  206.07  5004.6  210.61  5044.6   209.6  5065.6   214.7  5116.9  216.29
  5201.4   222.5    5244  223.22  5282.7  226.85  5342.8  232.36  5397.5  233.76
    5464  235.28  5513.3  233.69    5556  235.82  5619.5  234.46  5680.6  236.59
#Mann= 6 ,-1 , 0
  4499.5     .12       0  4993.9     .07       0  4999.9     .12       0
  5282.7     .05       0  5342.8     .12       0  5397.5     .16       0
#XS Ineff= 1 ,-1
  4557.5 4597.27   222.5
Permanent Ineff=
       F
Bank Sta=4974.1,5004.6
XS Rating Curve= 0 ,0
Exp/Cntr=0.3,0.1

Chan Stop Cuts=-1
Use User Specified Reach Order=0
Composite Channel Slope=5