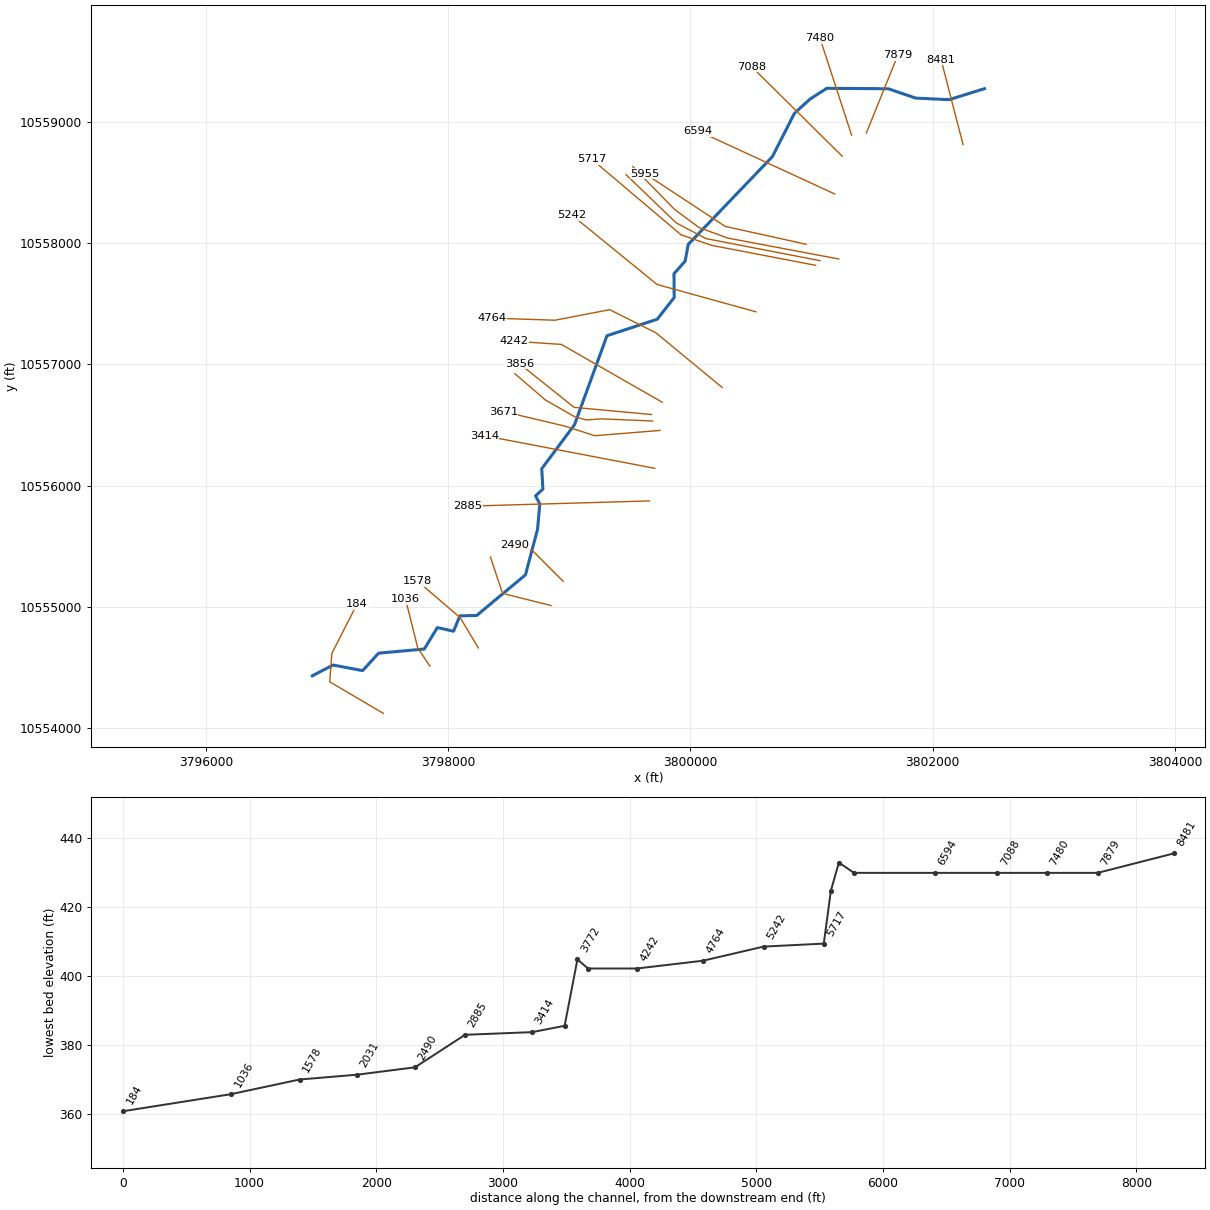
--- UNT078 IN BECR.prj (project) ---

Proj Title=UNT078 IN BECR Base Level Engineering
Current Plan=p01
Default Exp/Contr=0.3,0.1
English Units
Geom File=g01
Flow File=f01
Plan File=p01
Y Axis Title=Elevation
X Axis Title(PF)=Main Channel Distance
X Axis Title(XS)=Station
BEGIN DESCRIPTION:
UNT078 IN BECR
END DESCRIPTION:
DSS Export Rating Curves= 0
DSS Export Rating Curve Sorted= 0
DSS Export Volume Flow Curves= 0
DXF OffsetX= 0
DXF OffsetY= 0
DXF ScaleX= 1
DXF ScaleY= 10

--- UNT078 IN BECR.p01 (plan) ---

Plan Title=Multiple Run
Short Identifier=Multiple
Geom File=g01
Flow File=f01
Subcritical Flow
K Sum by GR= 0
Std Step Tol= 0.01
Critical Tol= 0.01
Num of Std Step Trials= 20
Max Error Tol= 0.3
Flow Tol Ratio= 0.001
Split Flow NTrial= 30
Split Flow Tol= 0.02
Split Flow Ratio= 0.02
Log Output Level= 0
Friction Slope Method= 1
Unsteady Friction Slope Method= 2
Unsteady Bridges Friction Slope Method= 1
Parabolic Critical Depth
Global Vel Dist=  1 , 1 , 1
Global Log Level= 0
CheckData=True
Encroach Param= -1, 0, 0, 0
BEGIN DESCRIPTION:
Multiple Run
END DESCRIPTION:

--- UNT078 IN BECR.f01 (steady flow) ---

Flow Title=Multiple
Program Version=4.10
Number of Profiles= 7
Profile Names=10-year,25-year,50-year,1pct_min,100-year,1pct_plu,500-year
River Rch & RM=UNT078 IN BECR,Reach-1         ,8481
     572     764     921     815    1102    1490    1583
River Rch & RM=UNT078 IN BECR,Reach-1         ,4764
     786    1071    1308    1173    1586    2145    2339
Boundary for River Rch & Prof#=UNT078 IN BECR,Reach-1         , 1
Up Type= 0
Dn Type= 3
Dn Slope=0.0057
Boundary for River Rch & Prof#=UNT078 IN BECR,Reach-1         , 2
Up Type= 0
Dn Type= 3
Dn Slope=0.0057
Boundary for River Rch & Prof#=UNT078 IN BECR,Reach-1         , 3
Up Type= 0
Dn Type= 3
Dn Slope=0.0057
Boundary for River Rch & Prof#=UNT078 IN BECR,Reach-1         , 4
Up Type= 0
Dn Type= 3
Dn Slope=0.0057
Boundary for River Rch & Prof#=UNT078 IN BECR,Reach-1         , 5
Up Type= 0
Dn Type= 3
Dn Slope=0.0057
Boundary for River Rch & Prof#=UNT078 IN BECR,Reach-1         , 6
Up Type= 0
Dn Type= 3
Dn Slope=0.0057
Boundary for River Rch & Prof#=UNT078 IN BECR,Reach-1         , 7
Up Type= 0
Dn Type= 3
Dn Slope=0.0057
DSS Import GetInterval= 0
DSS Import GetPeak= 0
DSS Import FillOption= 0

--- UNT078 IN BECR.g01 (geometry) ---

Geom Title=Existing Conditions
Program Version=4.10

River Reach=UNT078 IN BECR  ,Reach-1
Reach XY= 30
      3802427.25       10559276.        3802135.       10559185.
      3801859.75       10559198.      3801633.25       10559275.
      3801126.25       10559279.        3800990.       10559192.
      3800858.75       10559073.      3800676.75       10558715.
      3799981.75       10557990.       3799956.5       10557852.
       3799864.5       10557749.        3799866.       10557552.
      3799726.25       10557373.      3799311.25       10557237.
      3799043.75       10556503.        3798773.       10556139.
       3798782.5       10555971.        3798722.       10555915.
        3798757.       10555848.       3798738.5       10555640.
       3798638.5       10555263.        3798236.       10554928.
      3798097.25       10554925.       3798045.5       10554798.
       3797911.5       10554828.       3797803.5       10554651.
      3797426.75       10554617.        3797295.       10554473.
      3797050.25       10554519.       3796879.5       10554430.

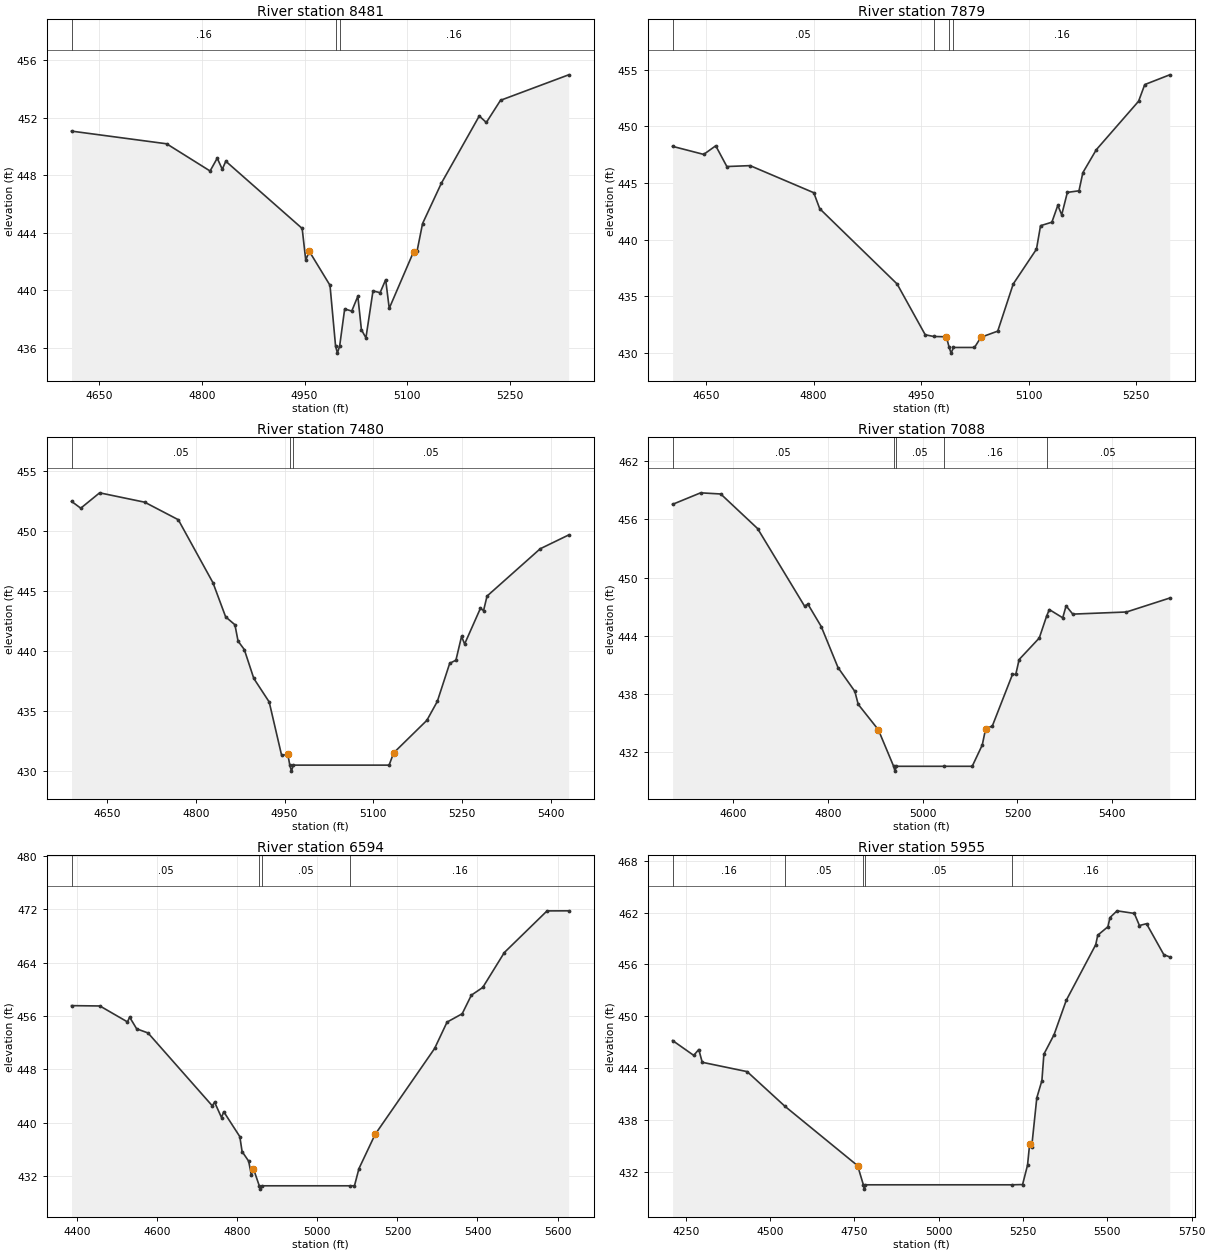
Type RM Length L Ch R = 1 ,8481    ,602,602,602
BEGIN DESCRIPTION:
UNT078 IN BECR 18.0
END DESCRIPTION:
XS GIS Cut Line= 2
      3802250.35     10558814.53      3802068.38     10559516.42
#Sta/Elev= 30
  4610.1  451.06  4748.8  450.18  4812.2  448.29  4822.6  449.18    4830  448.41
  4835.1  448.97  4946.5   444.3  4951.7  442.11  4956.9  442.71  4987.1  440.35
  4995.2  436.14  4997.9  435.64  5001.2  436.14  5008.5  438.71  5018.8  438.56
  5027.7  439.59  5032.9  437.27  5039.5   436.7  5049.8  439.96  5060.2  439.84
  5068.3  440.74  5073.5  438.75  5108.9  442.67  5114.1  442.73  5122.1  444.64
  5149.5  447.44  5204.8  452.11  5215.1  451.66  5235.8   453.2  5335.2  454.97
#Mann= 3 ,-1 , 0
  4610.1     .16       0  4995.2     .07       0  5001.2     .16       0
Bank Sta=4956.9,5108.9
XS Rating Curve= 0 ,0
Exp/Cntr=0.3,0.1

Type RM Length L Ch R = 1 ,7879    ,399,399,399
BEGIN DESCRIPTION:
UNT078 IN BECR 17.0
END DESCRIPTION:
XS GIS Cut Line= 2
      3801451.71     10558910.01      3801712.15     10559552.42
#Sta/Elev= 30
  4603.4  448.24  4646.8  447.53  4663.6  448.29  4679.1  446.46  4711.5  446.54
  4800.3  444.15  4808.6  442.74  4916.5   436.1  4955.7  431.62  4967.4  431.47
  4985.2  431.44  4989.1   430.5  4991.8     430  4995.1   430.5  5024.4   430.5
  5033.4   431.4  5056.8  431.94  5078.4   436.1  5110.8  439.17  5116.5  441.24
  5132.3  441.55  5140.6  443.04    5146   442.2  5153.9  444.18  5170.1  444.32
  5175.5  445.92  5194.2  447.94  5253.2  452.22  5261.8  453.69  5296.6  454.55
#Mann= 4 ,-1 , 0
  4603.4     .05       0  4967.4     .16       0  4989.1     .07       0
  4995.1     .16       0
Bank Sta=4985.2,5033.4
XS Rating Curve= 0 ,0
Exp/Cntr=0.3,0.1

Type RM Length L Ch R = 1 ,7480    ,392,392,392
BEGIN DESCRIPTION:
UNT078 IN BECR 16.0
END DESCRIPTION:
XS GIS Cut Line= 2
      3801330.21     10558892.66      3801069.79     10559691.27
#Sta/Elev= 30
    4590  452.47  4605.6   451.9  4637.5  453.18  4713.6   452.4  4770.4  450.94
    4829  445.69  4850.4  442.85  4866.1  442.19  4871.4  440.83  4881.9  440.13
    4898  437.72    4924  435.76    4945  431.31  4955.5   431.4  4958.8   430.5
  4961.6     430  4964.8   430.5  5126.6   430.5  5134.3  431.52  5190.4  434.23
    5208   435.8    5229  438.98  5239.5  439.24    5249  441.22  5254.2  440.59
  5280.9  443.56  5286.2  443.37  5292.1  444.58  5381.9  448.52    5430  449.67
#Mann= 3 ,-1 , 0
    4590     .05       0  4958.8    .033       0  4964.8     .05       0
Bank Sta=4955.5,5134.3
XS Rating Curve= 0 ,0
Exp/Cntr=0.3,0.1

Type RM Length L Ch R = 1 ,7088    ,494,494,494
BEGIN DESCRIPTION:
UNT078 IN BECR 15.0
END DESCRIPTION:
XS GIS Cut Line= 2
      3801252.09     10558719.07      3800506.44     10559456.05
#Sta/Elev= 30
  4472.8  457.56    4532  458.75  4574.4  458.63  4652.1  455.06  4751.1  447.05
  4758.2  447.25  4786.4  444.93  4821.8  440.69  4857.2  438.24  4864.3   436.9
  4906.7  434.28    4939   430.5  4941.8     430    4945   430.5  5044.3   430.5
  5104.7   430.5  5125.9   432.7    5133  434.37  5147.1  434.66  5189.6  439.99
  5196.6     440  5203.7  441.53  5246.1  443.75  5261.6  446.01  5267.3  446.69
  5295.6  445.84  5302.7  447.07  5316.8  446.22    5430  446.44  5521.2  447.88
#Mann= 5 ,-1 , 0
  4472.8     .05       0    4939    .033       0    4945     .05       0
  5044.3     .16       0  5261.6     .05       0
Bank Sta=4906.7,5133
XS Rating Curve= 0 ,0
Exp/Cntr=0.3,0.1

Type RM Length L Ch R = 1 ,6594    ,639,639,639
BEGIN DESCRIPTION:
UNT078 IN BECR 14.0
END DESCRIPTION:
XS GIS Cut Line= 2
      3801191.34     10558406.57      3800063.74       10558927.
#Sta/Elev= 30
  4385.9  457.54  4456.8  457.49  4525.6   455.1  4531.1  455.81  4548.6  454.06
    4577  453.44  4737.6   442.5  4743.2  443.06  4760.6  440.74  4766.1  441.62
  4806.3  437.88    4812  435.64  4828.4   434.2  4834.9  432.17  4840.4  433.06
  4854.9   430.5  4857.6     430  4860.9   430.5  5082.6   430.5  5092.7   430.5
  5103.9  433.08  5144.2   438.2  5292.9  451.11    5324  455.07  5361.8  456.32
  5384.7  459.11  5413.2  460.27  5467.1  465.51  5573.8  471.76  5627.8  471.77
#Mann= 4 ,-1 , 0
  4385.9     .05       0  4854.9    .033       0  4860.9     .05       0
  5082.6     .16       0
Bank Sta=4840.4,5144.2
XS Rating Curve= 0 ,0
Exp/Cntr=0.3,0.1

Type RM Length L Ch R = 1 ,5955    ,119,119,119
BEGIN DESCRIPTION:
UNT078 IN BECR 13.0
END DESCRIPTION:
XS GIS Cut Line= 3
      3800955.53     10557991.55      3800287.12     10558139.12
      3799627.39     10558573.15
#Sta/Elev= 30
  4210.7   447.2  4273.5  445.48  4288.4  446.16  4298.7  444.68  4431.8   443.6
  4544.2  439.58  4759.5  432.71  4776.5   430.5  4779.3     430  4782.5   430.5
  5216.6   430.5  5248.6  430.53  5263.3  432.77  5269.7  435.28  5275.7  434.92
  5290.8  440.57  5305.9  442.56  5311.8  445.62    5342  447.88  5378.2  451.86
  5465.5  458.29  5471.5  459.39  5501.7  460.37  5507.7  461.43  5528.7  462.21
    5580  461.91  5595.1  460.51  5616.1  460.72  5667.4  457.14  5684.9  456.87
#Mann= 5 ,-1 , 0
  4210.7     .16       0  4544.2     .05       0  4776.5    .033       0
  4782.5     .05       0  5216.6     .16       0
Bank Sta=4759.5,5269.7
XS Rating Curve= 0 ,0
Exp/Cntr=0.3,0.1

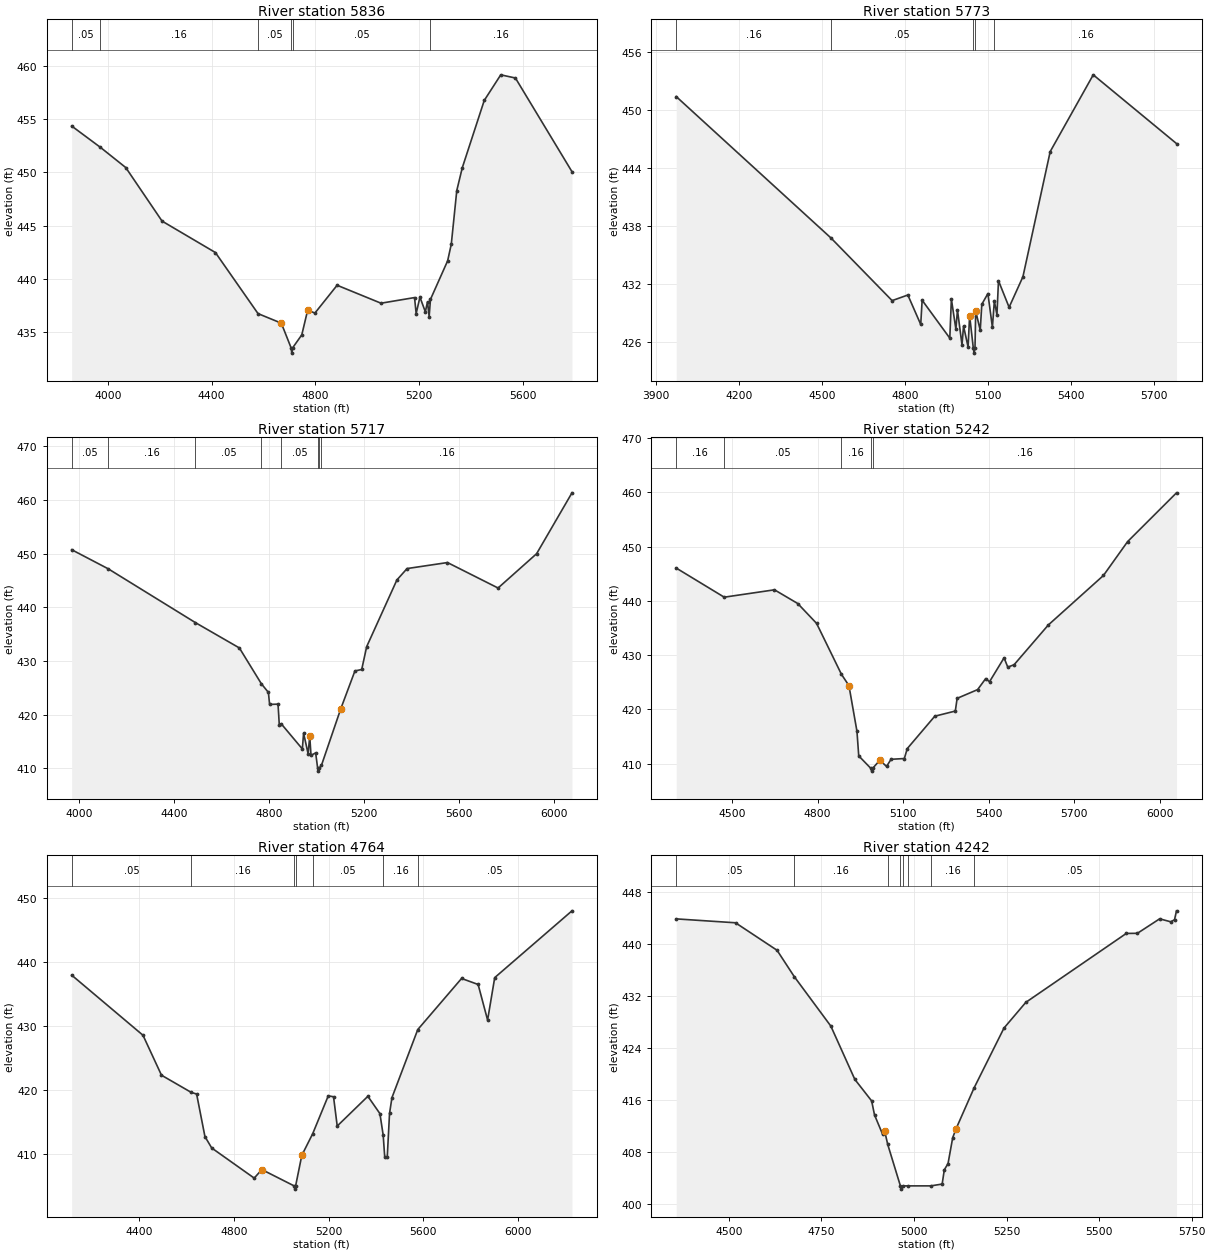
Type RM Length L Ch R = 1 ,5836    ,63,63,63
BEGIN DESCRIPTION:
Mapping XS 7a53dc07
END DESCRIPTION:
XS GIS Cut Line= 5
      3801224.67     10557870.01      3800304.48     10558043.63
      3800070.11     10558130.44      3799870.46     10558278.01
      3799523.89     10558633.23
#Sta/Elev= 30
  3859.9  454.37  3970.9  452.36  4068.6  450.46  4208.7  445.42  4414.6  442.46
  4579.1  436.71    4669  435.81  4706.7  433.49  4709.4  432.99  4712.7  433.49
    4748  434.71  4770.8  437.05  4798.6  436.76  4884.3  439.38  5053.7  437.69
  5183.1  438.22  5189.4  436.72    5204  438.26  5224.8  436.88  5233.2  437.83
  5239.5  436.42  5244.6  438.05  5310.9  441.68    5325  443.25  5346.2   448.3
  5367.4  450.44  5452.2  456.78  5515.9  459.19  5572.5  458.89  5790.8  450.07
#Mann= 6 ,-1 , 0
  3859.9     .05       0  3970.9     .16       0  4579.1     .05       0
  4706.7     .03       0  4712.7     .05       0  5244.6     .16       0
Bank Sta=4669,4770.8
XS Rating Curve= 0 ,0
Exp/Cntr=0.3,0.1

Type RM Length L Ch R = 1 ,5773    ,56,56,56
BEGIN DESCRIPTION:
Mapping XS 72c724b5
END DESCRIPTION:
XS GIS Cut Line= 4
       3801069.5     10557856.24      3800128.49     10558038.54
      3799881.96     10558168.75      3799469.35     10558565.76
#Sta/Elev= 30
  3972.8  451.41    4533  436.75  4753.9  430.27  4810.8  430.85  4857.4   427.8
  4862.5  430.31  4962.6  426.38  4968.3  430.42  4984.6  427.32  4990.3   429.3
  5006.7  425.69  5012.3  427.63  5028.7  425.47  5034.3  428.71  5047.7  425.33
  5050.4  424.83  5053.7  425.33  5056.3  429.19  5072.7   427.2  5078.4  429.89
  5100.4     431  5116.7  427.51  5123.7  430.23  5133.1  428.81  5138.7  432.33
  5177.1  429.58  5227.1  432.74  5325.8  445.71  5481.5  453.66  5782.7  446.54
#Mann= 5 ,-1 , 0
  3972.8     .16       0    4533     .05       0  5047.7     .03       0
  5053.7     .05       0  5123.7     .16       0
Bank Sta=5034.3,5056.3
XS Rating Curve= 0 ,0
Exp/Cntr=0.3,0.1

Type RM Length L Ch R = 1 ,5717    ,475,475,475
BEGIN DESCRIPTION:
UNT078 IN BECR 12.0
END DESCRIPTION:
XS GIS Cut Line= 4
      3801033.63     10557817.94      3800174.27     10557982.87
      3799922.54     10558069.68      3799184.69     10558694.68
#Sta/Elev= 30
  3968.6  450.72  4122.8  447.16  4490.3  437.14  4675.3  432.43    4768  425.76
  4797.5  424.16  4802.7  421.92  4838.2  421.97  4843.5  418.08  4851.3  418.33
  4940.6  413.63  4945.9  416.55  4964.9  412.74  4971.8  415.99  4977.1  412.44
  4996.7  412.89  5005.3     410  5008.1   409.5  5011.3     410    5021  410.56
  5102.4  421.09  5162.2  428.15  5190.8  428.42  5211.7  432.67  5339.1  445.09
  5381.9  447.21  5552.2  448.33  5765.4  443.59  5927.9  449.98  6076.9  461.31
#Mann= 8 ,-1 , 0
  3968.6     .05       0  4122.8     .16       0  4490.3     .05       0
    4768     .16       0  4851.3     .05       0  5005.3     .03       0
  5011.3     .05       0    5021     .16       0
Bank Sta=4971.8,5102.4
XS Rating Curve= 0 ,0
Exp/Cntr=0.3,0.1

Type RM Length L Ch R = 1 ,5242    ,478,478,478
BEGIN DESCRIPTION:
UNT078 IN BECR 11.0
END DESCRIPTION:
XS GIS Cut Line= 3
      3800540.25     10557434.36       3799724.3     10557660.05
      3799021.15     10558232.99
#Sta/Elev= 30
  4304.4  446.06  4472.7  440.69  4648.9  442.05  4730.5  439.52  4796.5  435.86
  4883.6  426.48  4909.9  424.39    4938  415.97  4944.2  411.45  4986.8  409.14
  4989.6  408.64  4992.8  409.14    5018  410.65  5041.7  409.51  5057.5  410.82
    5104  410.96  5114.4   412.8  5210.8  418.76  5282.7  419.71  5289.1  422.05
  5360.9  423.66  5389.2  425.69  5402.6  425.11  5453.6  429.52  5466.6   427.8
  5488.8  428.25  5608.7  435.57  5801.9  444.69  5886.6  450.93    6058  459.92
#Mann= 5 ,-1 , 0
  4304.4     .16       0  4472.7     .05       0  4883.6     .16       0
  4986.8     .07       0  4992.8     .16       0
Bank Sta=4909.9,5018
XS Rating Curve= 0 ,0
Exp/Cntr=0.3,0.1

Type RM Length L Ch R = 1 ,4764    ,522,522,522
BEGIN DESCRIPTION:
UNT078 IN BECR 10.0
END DESCRIPTION:
XS GIS Cut Line= 5
      3800262.48     10556809.37      3799715.62     10557260.75
      3799333.67     10557451.72      3798882.28     10557364.91
      3798363.05     10557382.22
#Sta/Elev= 30
  4113.7  437.93  4415.2  428.55  4493.4  422.32  4619.6  419.63  4641.9  419.39
  4677.1  412.75  4705.7  410.97  4885.4  406.27  4917.8   407.6  5054.5  405.05
  5057.3  404.55  5060.5  405.05  5086.7  409.82  5132.8   413.2  5198.5   419.1
  5220.8  418.96  5236.4  414.39    5366  419.03  5416.9  416.33  5430.8  412.96
  5437.2  409.58  5447.9  409.51  5457.6  416.35  5467.8  418.82    5577  429.44
  5762.2  437.41  5832.2  436.47  5872.2  430.92  5902.3  437.54    6229  447.96
#Mann= 7 ,-1 , 0
  4113.7     .05       0  4619.6     .16       0  5054.5     .07       0
  5060.5     .16       0  5132.8     .05       0  5430.8     .16       0
    5577     .05       0
Bank Sta=4917.8,5086.7
XS Rating Curve= 0 ,0
Exp/Cntr=0.3,0.1

Type RM Length L Ch R = 1 ,4242    ,386,386,386
BEGIN DESCRIPTION:
UNT078 IN BECR 9.0
END DESCRIPTION:
XS GIS Cut Line= 3
      3799767.66     10556687.85      3798934.37     10557165.26
       3798544.2     10557191.27
#Sta/Elev= 30
  4357.7  443.88  4517.9  443.28  4630.1  439.05  4676.4  435.01  4775.4  427.38
  4840.2  419.18  4885.6  415.87  4893.4  413.71    4915  410.76  4920.8  411.22
  4929.1  409.16  4963.3  402.79    4966  402.29  4969.3  402.79  4983.3  402.79
  5045.6  402.79  5076.1  403.07  5081.9  405.26    5092  406.23  5104.6  410.21
  5113.5  411.56  5162.2  417.85    5243  427.07    5302  431.03  5573.4  441.64
  5603.5  441.66  5663.6  443.89  5693.7  443.43  5703.7  443.75  5709.1  445.12
#Mann= 8 ,-1 , 0
  4357.7     .05       0  4676.4     .16       0  4929.1     .05       0
  4963.3     .07       0  4969.3     .05       0  4983.3     .12       0
  5045.6     .16       0  5162.2     .05       0
Bank Sta=4920.8,5113.5
XS Rating Curve= 0 ,0
Exp/Cntr=0.3,0.1

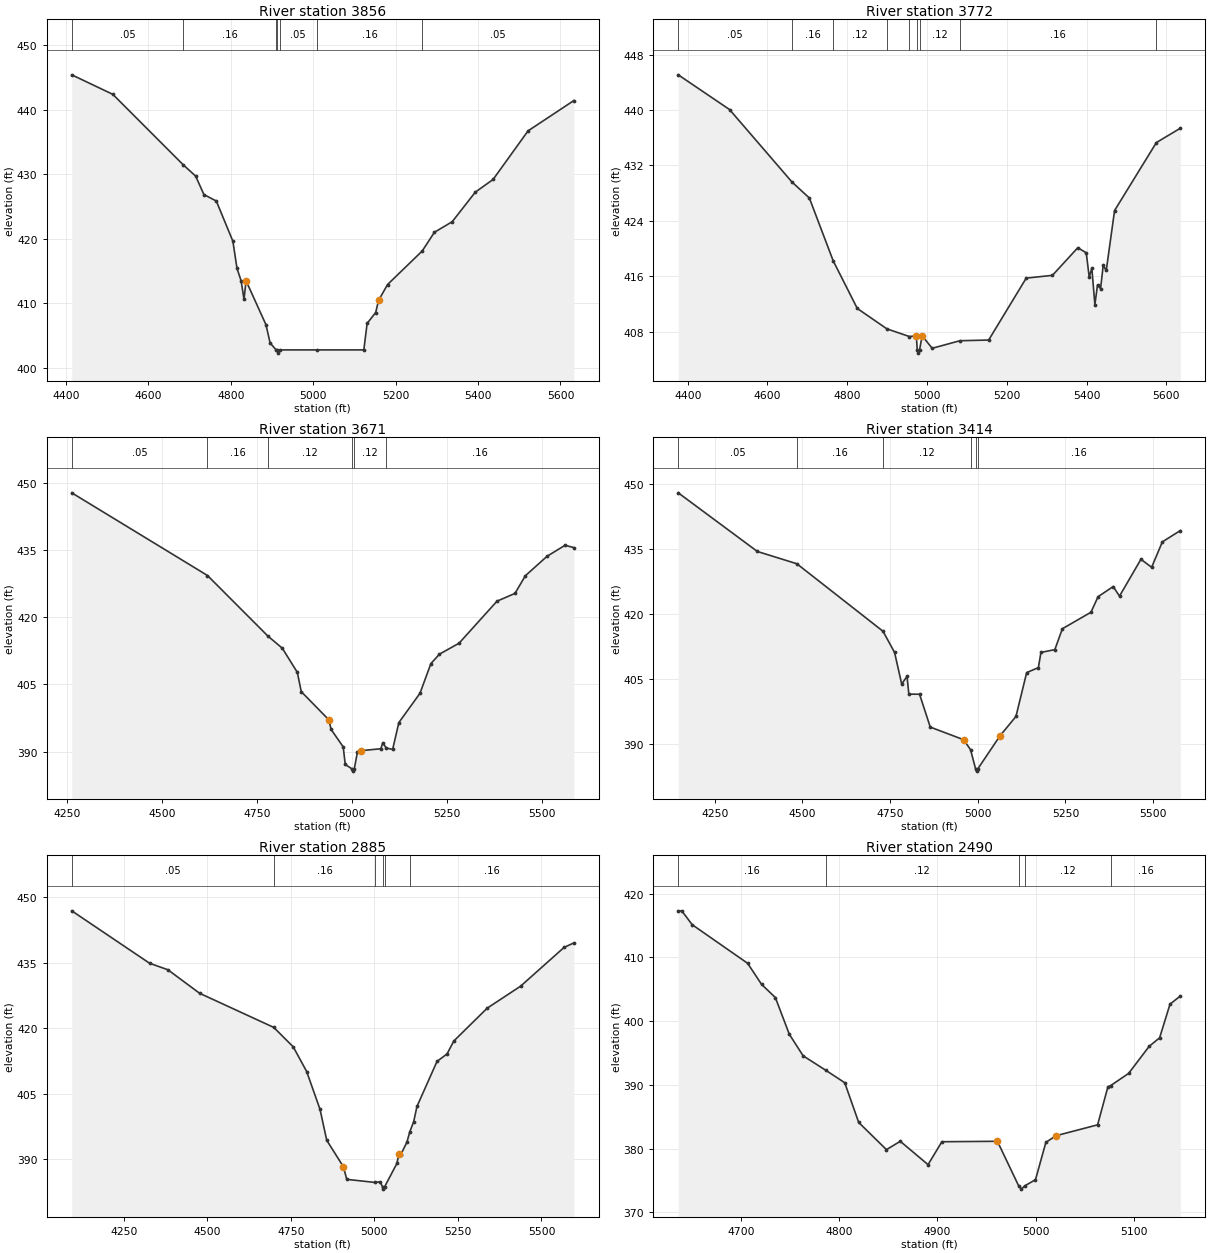
Type RM Length L Ch R = 1 ,3856    ,84,84,84
BEGIN DESCRIPTION:
UNT078 IN BECR 8.0
END DESCRIPTION:
XS GIS Cut Line= 3
      3799678.91     10556586.55      3799039.98     10556645.59
      3798589.53     10557005.94
#Sta/Elev= 30
    4414  445.45  4513.7  442.42  4684.9  431.47  4714.6  429.75  4734.7  426.88
  4764.8  425.88    4805  419.65    4815  415.43    4825  413.51    4832  410.63
    4837  413.51  4885.3   406.7  4895.3  403.88  4909.1  402.85  4912.4  402.79
  4915.2  402.29  4918.4  402.79  5008.7  402.79  5122.8  402.79  5130.8   406.9
  5151.6  408.59  5158.6  410.47  5180.4  412.93  5264.4  418.12  5294.1  421.03
  5337.3  422.67  5393.3  427.25  5436.6  429.23  5521.4  436.76  5632.5  441.46
#Mann= 7 ,-1 , 0
    4414     .05       0  4684.9     .16       0  4909.1     .05       0
  4912.4    .033       0  4918.4     .05       0  5008.7     .16       0
  5264.4     .05       0
Bank Sta=4837,5158.6
XS Rating Curve= 0 ,0
Exp/Cntr=0.3,0.1

Type RM Length L Ch R = 1 ,3772    ,101,101,101
BEGIN DESCRIPTION:
Mapping XS 09eced3c
END DESCRIPTION:
XS GIS Cut Line= 6
      3799688.14     10556533.22      3799262.82     10556550.58
      3799141.29      10556541.9       3799045.8     10556567.94
      3798802.75     10556706.83      3798551.01     10556923.84
#Sta/Elev= 30
  4376.3  445.09  4504.9  440.08  4661.4  429.62  4705.1   427.3  4764.8  418.24
  4825.2  411.36  4899.6  408.41  4955.7  407.31  4973.3  407.39  4975.5  405.41
  4978.2  404.91  4981.5  405.41  4987.8  407.41    5013  405.61  5082.6   406.7
  5154.6   406.8  5248.8  415.74  5314.5  416.14  5378.1  420.13  5399.3  419.39
  5406.7  415.88  5413.3  417.17  5420.9  411.91  5427.5  414.75  5435.2  414.22
  5441.8  417.58  5449.4  416.84  5470.3   425.5  5575.1  435.31  5635.1  437.38
#Mann= 9 ,-1 , 0
  4376.3     .05       0  4661.4     .16       0  4764.8     .12       0
  4899.6     .05       0  4955.7     .12       0  4975.5     .07       0
  4981.5     .12       0  5082.6     .16       0  5575.1     .05       0
Bank Sta=4973.3,4987.8
XS Rating Curve= 0 ,0
Exp/Cntr=0.3,0.1

Type RM Length L Ch R = 1 ,3671    ,257,257,257
BEGIN DESCRIPTION:
Mapping XS 3e3975ff
END DESCRIPTION:
XS GIS Cut Line= 4
      3799748.96     10556455.09      3799210.73     10556411.69
      3798967.68     10556489.81      3798455.48     10556611.35
#Sta/Elev= 30
  4261.6  447.71  4618.9  429.28  4778.3  415.75  4815.8  413.08  4855.3  407.71
  4865.8  403.39  4938.9  397.07  4944.1     395  4976.2  391.08  4981.5  387.17
  4999.3  386.18  5002.1  385.68  5005.3  386.18  5013.6  389.93  5023.3  390.24
  5075.2  390.67  5080.4  392.02  5089.4  390.83  5106.3  390.52  5122.6   396.5
  5178.2  403.02    5207  409.65  5229.6  411.76    5281  414.18    5381  423.56
  5428.3  425.29  5455.7  429.23  5512.8  433.57  5560.1  436.02  5583.3   435.5
#Mann= 6 ,-1 , 0
  4261.6     .05       0  4618.9     .16       0  4778.3     .12       0
  4999.3     .07       0  5005.3     .12       0  5089.4     .16       0
Bank Sta=4938.9,5023.3
XS Rating Curve= 0 ,0
Exp/Cntr=0.3,0.1

Type RM Length L Ch R = 1 ,3414    ,529,529,529
BEGIN DESCRIPTION:
UNT078 IN BECR 7.0
END DESCRIPTION:
XS GIS Cut Line= 2
      3799705.49      10556142.6       3798299.3     10556411.68
#Sta/Elev= 30
    4146  448.05  4371.7  434.52  4484.2  431.69    4730  416.11  4762.9  411.23
  4783.2  403.94  4798.4  405.71  4803.6  401.61  4834.1  401.59  4864.7  394.01
  4959.6   391.1  4979.5  388.81    4994  384.35  4996.8  383.85    5000  384.35
  5063.8  392.02    5109  396.46  5139.6  406.58    5173  407.73  5180.3  411.23
  5219.9  411.88  5241.4   416.7  5322.9   420.5  5343.2  424.09  5386.3  426.43
  5404.3  424.22  5465.4  432.72  5495.9  430.87  5526.5  436.74  5577.7  439.34
#Mann= 6 ,-1 , 0
    4146     .05       0  4484.2     .16       0    4730     .12       0
  4979.5     .16       0    4994     .07       0    5000     .16       0
Bank Sta=4959.6,5063.8
XS Rating Curve= 0 ,0
Exp/Cntr=0.3,0.1

Type RM Length L Ch R = 1 ,2885    ,395,395,395
BEGIN DESCRIPTION:
UNT078 IN BECR 6.0
END DESCRIPTION:
XS GIS Cut Line= 2
      3799662.17      10555873.5      3798160.39     10555830.09
#Sta/Elev= 30
  4094.4  446.92  4327.1   434.9    4382   433.4  4477.1     428  4698.8  420.18
  4757.2  415.71  4797.3  410.06  4837.3  401.37  4857.3   394.3  4907.3   388.2
  4917.3  385.32  5002.4  384.61  5017.3  384.77  5024.3  383.58  5027.1  383.08
  5030.3  383.58  5067.4  388.98  5073.3  391.15  5078.3  390.91  5097.4  393.88
  5106.1  396.28  5117.4  398.51  5127.4  402.05  5187.4  412.39  5217.4  414.09
  5237.4  417.04  5337.5  424.59  5437.5  429.64  5567.6  438.53  5596.8  439.56
#Mann= 6 ,-1 , 0
  4094.4     .05       0  4698.8     .16       0  5002.4     .12       0
  5024.3     .07       0  5030.3     .12       0  5106.1     .16       0
Bank Sta=4907.3,5073.3
XS Rating Curve= 0 ,0
Exp/Cntr=0.3,0.1

Type RM Length L Ch R = 1 ,2490    ,459,459,459
BEGIN DESCRIPTION:
UNT078 IN BECR 5.0
END DESCRIPTION:
XS GIS Cut Line= 3
      3798949.63     10555210.17      3798699.61     10555460.19
       3798549.6     10555510.19
#Sta/Elev= 30
  4635.8  417.29  4639.4  417.29    4650  415.12  4706.5  409.07  4720.7  405.77
  4734.8  403.69    4749  397.94  4763.1  394.56  4785.9  392.32  4805.5  390.34
  4819.7  384.12    4848  379.85  4862.1  381.16  4890.4   377.5  4904.5  381.09
  4961.1  381.16  4982.8  374.16  4985.6  373.66  4988.8  374.16  4999.9  375.14
  5010.5     381    5021  382.04  5063.2  383.74  5073.7  389.69  5076.5  389.89
  5094.8   391.8  5115.9  396.07  5126.4  397.38    5137  402.66  5147.5  403.93
#Mann= 5 ,-1 , 0
  4635.8     .16       0  4785.9     .12       0  4982.8     .07       0
  4988.8     .12       0  5076.5     .16       0
Bank Sta=4961.1,5021
XS Rating Curve= 0 ,0
Exp/Cntr=0.3,0.1

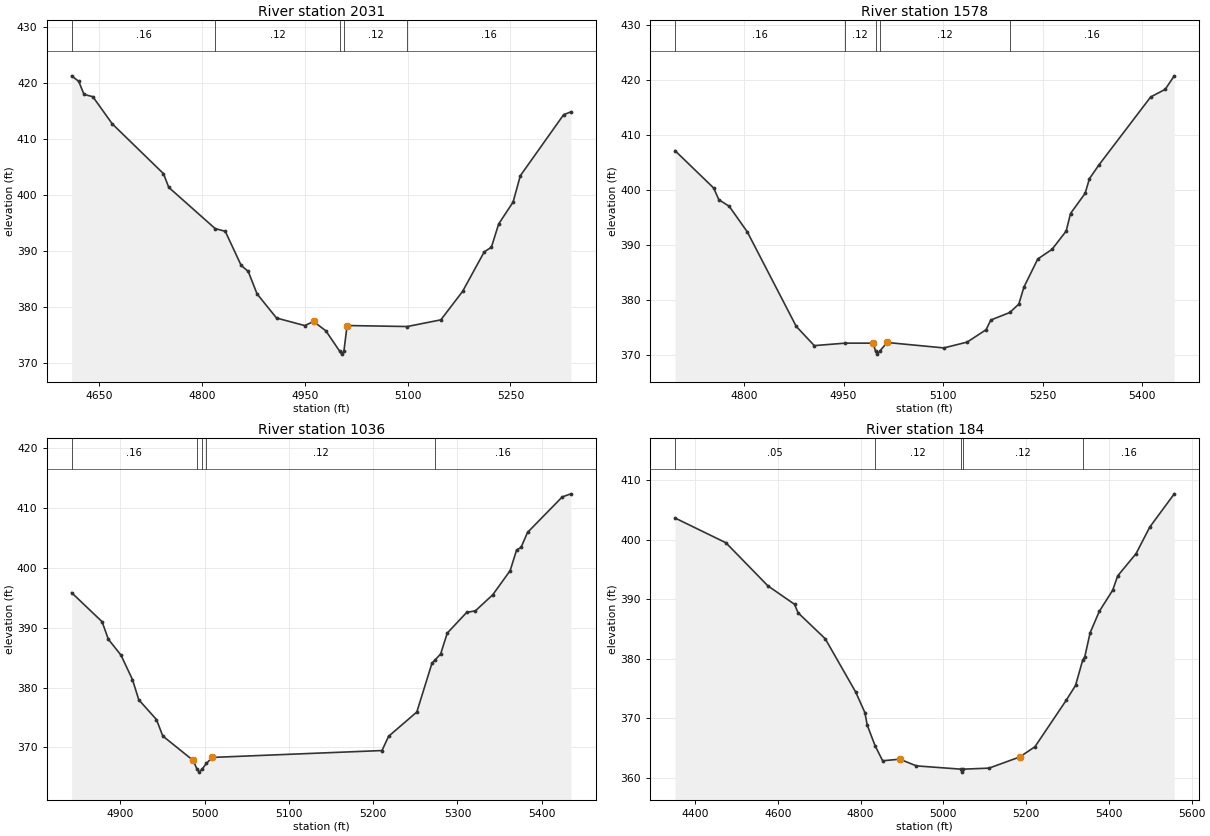
Type RM Length L Ch R = 1 ,2031    ,453,453,453
BEGIN DESCRIPTION:
UNT078 IN BECR 4.0
END DESCRIPTION:
XS GIS Cut Line= 3
      3798849.64     10555010.18      3798449.61     10555110.19
       3798349.6     10555410.21
#Sta/Elev= 30
  4609.7  421.22    4620  420.24  4627.8   417.9  4640.7  417.49    4669  412.64
  4743.7  403.75  4751.5  401.29  4819.2  393.93  4833.9  393.45  4857.1  387.36
  4867.4  386.29  4880.3  382.27  4908.7  377.96  4949.9  376.61  4962.8  377.34
  4980.8  375.66    5001  372.01  5003.8  371.51    5007  372.01  5011.7  376.62
  5099.4  376.44  5148.5  377.63  5180.2  382.71  5211.8  389.77  5222.3  390.61
  5232.9  394.77  5253.9  398.66  5264.5  403.38  5327.7  414.28  5338.3  414.78
#Mann= 5 ,-1 , 0
  4609.7     .16       0  4819.2     .12       0    5001     .07       0
    5007     .12       0  5099.4     .16       0
Bank Sta=4962.8,5011.7
XS Rating Curve= 0 ,0
Exp/Cntr=0.3,0.1

Type RM Length L Ch R = 1 ,1578    ,542,542,542
BEGIN DESCRIPTION:
UNT078 IN BECR 3.0
END DESCRIPTION:
XS GIS Cut Line= 3
      3798249.62     10554660.17      3798099.61     10554910.19
      3797749.64     10555210.16
#Sta/Elev= 30
  4695.9  407.17  4754.2  400.36    4762  398.23  4777.6  397.04  4804.8  392.39
  4878.6  375.18  4905.8  371.67  4952.2  372.12  4994.6  372.12  4998.2  370.62
  5000.9  370.12  5004.2  370.62  5015.5  372.24  5101.1  371.25  5136.2  372.31
  5164.7  374.56  5171.9  376.33  5200.5   377.7  5214.1  379.23  5221.8  382.33
  5242.7  387.45  5264.1  389.19  5285.5  392.53    5292  395.72    5314  399.39
  5320.6  402.08  5334.8  404.56  5412.8  416.94  5434.7  418.33  5448.4  420.79
#Mann= 5 ,-1 , 0
  4695.9     .16       0  4952.2     .12       0  4998.2     .07       0
  5004.2     .12       0  5200.5     .16       0
Bank Sta=4994.6,5015.5
XS Rating Curve= 0 ,0
Exp/Cntr=0.3,0.1

Type RM Length L Ch R = 1 ,1036    ,852,852,852
BEGIN DESCRIPTION:
UNT078 IN BECR 2.0
END DESCRIPTION:
XS GIS Cut Line= 3
      3797849.64     10554510.15      3797749.61     10554660.19
      3797649.62     10555060.15
#Sta/Elev= 30
    4842  395.88  4878.1  391.03  4885.6  388.09  4900.6  385.43  4914.2  381.35
  4921.7  377.97  4942.7  374.66  4950.2  371.91  4986.3  367.82  4990.8  366.37
  4993.5  365.87  4996.8  366.37    5002  367.33  5008.8  368.33  5210.4  369.48
  5218.2  371.86  5251.7  375.92  5269.7  384.08  5272.9  384.56    5280  385.63
  5287.8  389.11  5310.9  392.58  5321.3  392.85  5341.9  395.54  5362.5  399.57
  5370.2  403.04  5375.4  403.44  5383.1  405.95  5424.3  411.89  5434.6  412.41
#Mann= 5 ,-1 , 0
    4842     .16       0  4990.8     .07       0  4996.8     .16       0
    5002     .12       0  5272.9     .16       0
Bank Sta=4986.3,5008.8
XS Rating Curve= 0 ,0
Exp/Cntr=0.3,0.1

Type RM Length L Ch R = 1 ,184     ,0,0,0
BEGIN DESCRIPTION:
UNT078 IN BECR 1.0
END DESCRIPTION:
XS GIS Cut Line= 4
      3797465.92     10554120.03      3797023.23     10554380.44
      3797040.59     10554614.81      3797248.92     10555022.78
#Sta/Elev= 30
  4351.3  403.63  4474.3  399.47  4575.8  392.23  4640.2  389.13  4648.7  387.71
  4714.5  383.33  4787.9   374.4  4810.2  370.94    4816  368.81  4834.7   365.4
  4853.1  362.84  4894.7   363.1  4934.8  361.98  5042.1  361.43  5044.9  360.93
  5048.1  361.43  5110.2   361.6  5184.6  363.48  5221.3   365.2  5296.8     373
  5319.3  375.49  5336.5  379.71  5341.7  380.31  5354.6  384.34  5376.8  387.95
  5409.1  391.49  5421.3  393.91  5465.7  397.65  5498.9  402.12    5558  407.69
#Mann= 5 ,-1 , 0
  4351.3     .05       0  4834.7     .12       0  5042.1     .07       0
  5048.1     .12       0  5336.5     .16       0
Bank Sta=4894.7,5184.6
XS Rating Curve= 0 ,0
Exp/Cntr=0.3,0.1

Chan Stop Cuts=-1
Use User Specified Reach Order=0
Composite Channel Slope=5