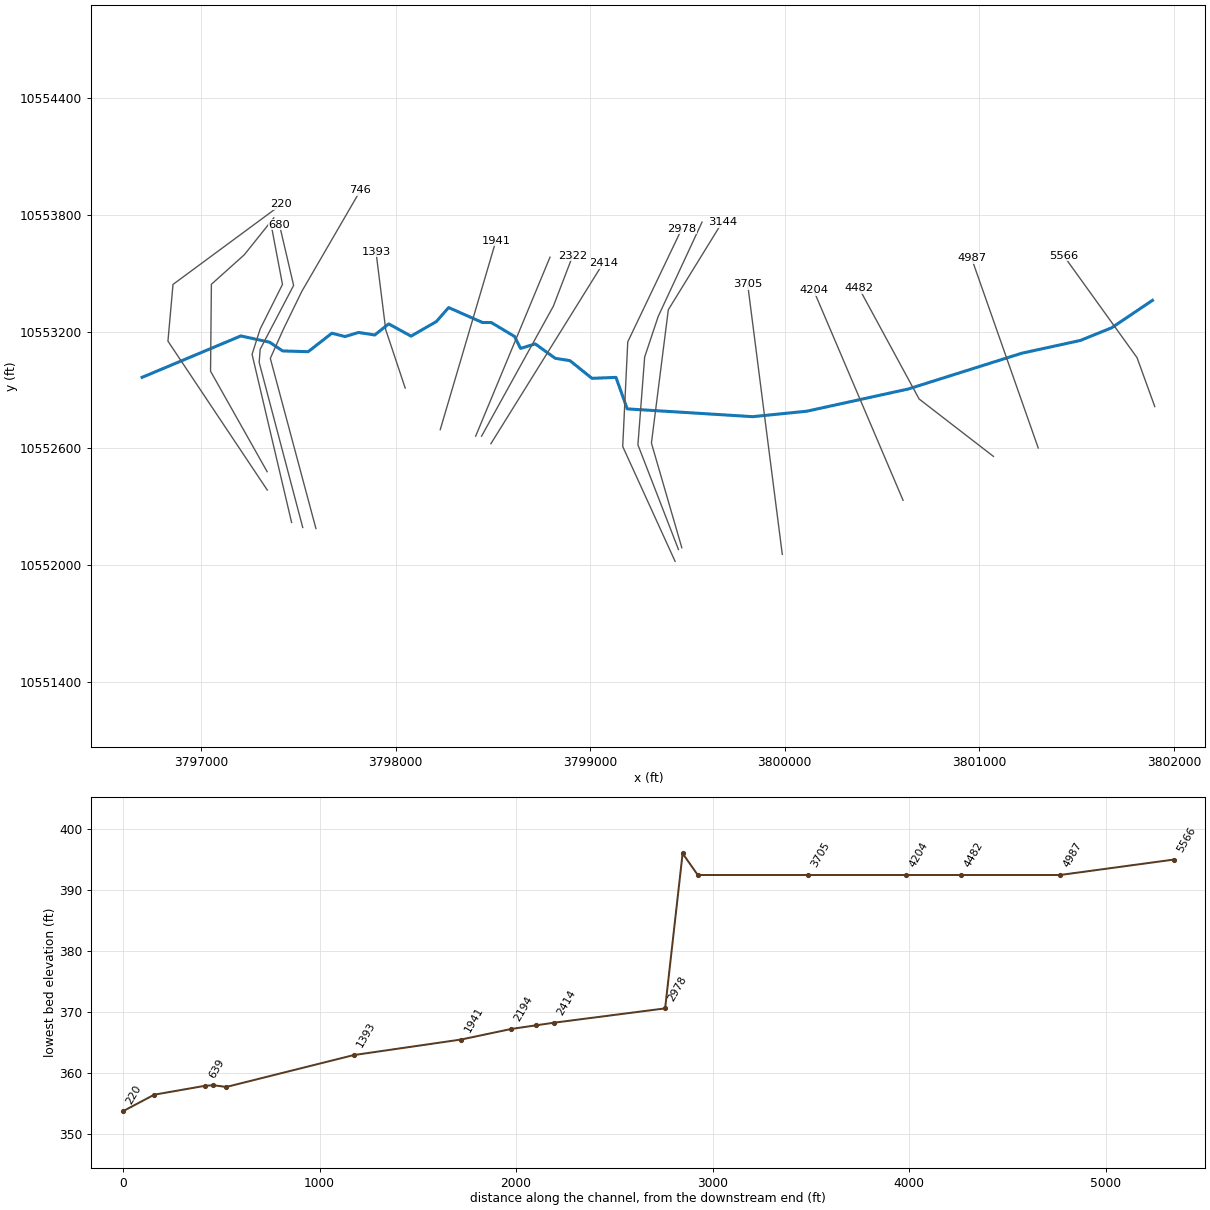
--- UNT079 IN BECR.prj (project) ---

Proj Title=UNT079 IN BECR Base Level Engineering
Current Plan=p01
Default Exp/Contr=0.3,0.1
English Units
Geom File=g01
Flow File=f01
Plan File=p01
Y Axis Title=Elevation
X Axis Title(PF)=Main Channel Distance
X Axis Title(XS)=Station
BEGIN DESCRIPTION:
UNT079 IN BECR
END DESCRIPTION:
DSS Export Rating Curves= 0
DSS Export Rating Curve Sorted= 0
DSS Export Volume Flow Curves= 0
DXF OffsetX= 0
DXF OffsetY= 0
DXF ScaleX= 1
DXF ScaleY= 10

--- UNT079 IN BECR.p01 (plan) ---

Plan Title=Multiple Run
Short Identifier=Multiple
Geom File=g01
Flow File=f01
Subcritical Flow
K Sum by GR= 0
Std Step Tol= 0.01
Critical Tol= 0.01
Num of Std Step Trials= 20
Max Error Tol= 0.3
Flow Tol Ratio= 0.001
Split Flow NTrial= 30
Split Flow Tol= 0.02
Split Flow Ratio= 0.02
Log Output Level= 0
Friction Slope Method= 1
Unsteady Friction Slope Method= 2
Unsteady Bridges Friction Slope Method= 1
Parabolic Critical Depth
Global Vel Dist=  1 , 1 , 1
Global Log Level= 0
CheckData=True
Encroach Param= -1, 0, 0, 0
BEGIN DESCRIPTION:
Multiple Run
END DESCRIPTION:

--- UNT079 IN BECR.f01 (steady flow) ---

Flow Title=Multiple
Program Version=4.10
Number of Profiles= 7
Profile Names=10-year,25-year,50-year,1pct_min,100-year,1pct_plu,500-year
River Rch & RM=UNT079 IN BECR,Reach-1         ,5566
     677     923    1129    1014    1371    1855    2031
River Rch & RM=UNT079 IN BECR,Reach-1         ,2978
     836    1155    1423    1289    1743    2358    2624
Boundary for River Rch & Prof#=UNT079 IN BECR,Reach-1         , 1
Up Type= 0
Dn Type= 3
Dn Slope=0.0068
Boundary for River Rch & Prof#=UNT079 IN BECR,Reach-1         , 2
Up Type= 0
Dn Type= 3
Dn Slope=0.0068
Boundary for River Rch & Prof#=UNT079 IN BECR,Reach-1         , 3
Up Type= 0
Dn Type= 3
Dn Slope=0.0068
Boundary for River Rch & Prof#=UNT079 IN BECR,Reach-1         , 4
Up Type= 0
Dn Type= 3
Dn Slope=0.0068
Boundary for River Rch & Prof#=UNT079 IN BECR,Reach-1         , 5
Up Type= 0
Dn Type= 3
Dn Slope=0.0068
Boundary for River Rch & Prof#=UNT079 IN BECR,Reach-1         , 6
Up Type= 0
Dn Type= 3
Dn Slope=0.0068
Boundary for River Rch & Prof#=UNT079 IN BECR,Reach-1         , 7
Up Type= 0
Dn Type= 3
Dn Slope=0.0068
DSS Import GetInterval= 0
DSS Import GetPeak= 0
DSS Import FillOption= 0

--- UNT079 IN BECR.g01 (geometry) ---

Geom Title=Existing Conditions
Program Version=4.10

River Reach=UNT079 IN BECR  ,Reach-1
Reach XY= 30
       3801889.5       10553361.      3801679.75       10553220.
       3801519.5       10553155.      3801217.25       10553089.
        3800634.       10552905.      3800113.25       10552791.
       3799835.5       10552763.       3799190.5       10552803.
      3799132.75       10552965.       3799009.5       10552960.
      3798896.25       10553051.        3798821.       10553063.
      3798717.75       10553137.      3798642.25       10553114.
        3798612.       10553175.        3798492.       10553247.
        3798447.       10553247.      3798272.75       10553324.
      3798209.75       10553252.      3798079.75       10553177.
        3797965.       10553240.        3797893.       10553183.
      3797810.25       10553196.      3797740.75       10553175.
      3797672.75       10553192.        3797551.       10553097.
       3797419.5       10553101.       3797352.5       10553146.
        3797205.       10553178.       3796697.5       10552965.

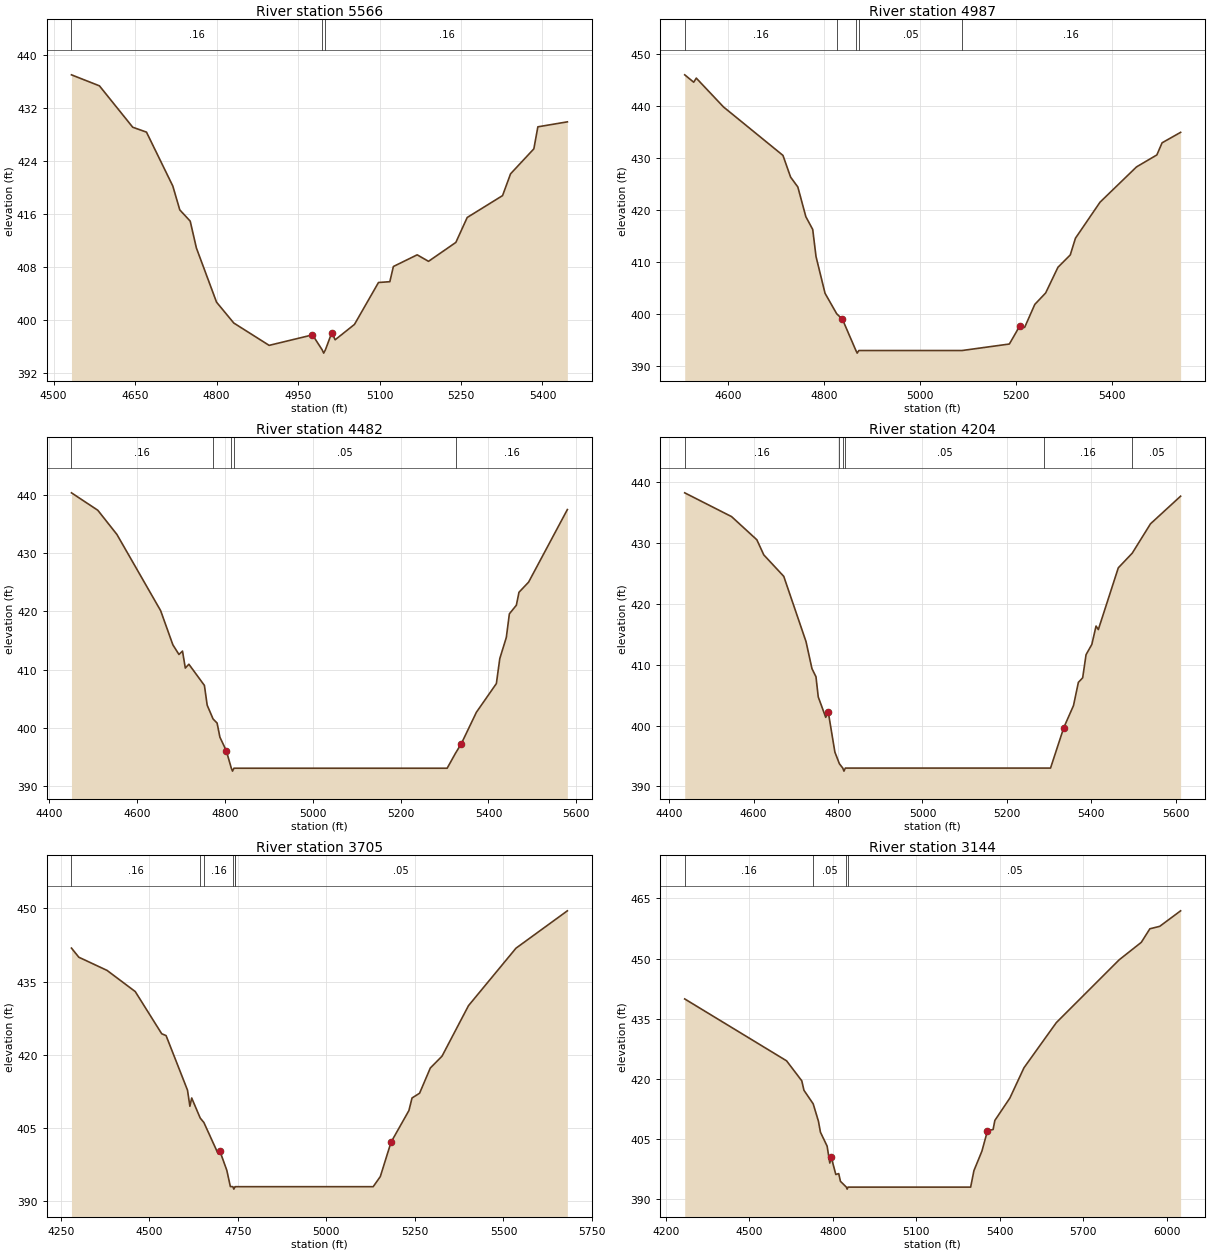
Type RM Length L Ch R = 1 ,5566    ,579,579,579
BEGIN DESCRIPTION:
Mapping XS 1db2b4e6
END DESCRIPTION:
XS GIS Cut Line= 3
      3801901.39     10552814.69      3801810.23     10553066.45
      3801433.61     10553590.25
#Sta/Elev= 30
  4532.9     437  4584.4  435.34  4645.7   429.1    4671  428.36  4719.5  420.23
  4732.3  416.64  4751.5  414.94  4762.9  410.89    4800  402.72  4831.7  399.58
  4896.8  396.21  4976.6  397.79  4994.4  395.54  4997.2  395.04  5000.4  395.54
  5012.2  398.13  5018.3  397.05  5053.9  399.37  5098.1  405.69    5119  405.81
  5125.5   408.1  5169.3  409.86  5190.2  408.88  5240.5  411.73  5261.4  415.49
  5326.5  418.79  5341.2  422.07  5384.1  425.84  5391.5  429.16  5445.8  429.91
#Mann= 3 ,-1 , 0
  4532.9     .16       0  4994.4     .07       0  5000.4     .16       0
Bank Sta=4976.6,5012.2
XS Rating Curve= 0 ,0
Exp/Cntr=0.3,0.1

Type RM Length L Ch R = 1 ,4987    ,505,505,505
BEGIN DESCRIPTION:
UNT079 IN BECR 11.0
END DESCRIPTION:
XS GIS Cut Line= 2
      3801302.43     10552602.02      3800960.15     10553576.87
#Sta/Elev= 30
  4509.7  445.98  4528.5  444.56  4533.8  445.35  4590.5  439.81  4714.4   430.5
  4730.3  426.33  4745.4  424.43  4762.1  418.72  4776.4  416.27  4783.3  411.06
  4802.1     404  4826.3  400.08  4838.4     399  4866.4  393.01  4869.1  392.51
  4872.4  393.01  5087.5  393.01  5186.1  394.26  5207.3  397.65  5217.9  397.45
  5239.1  401.87  5261.7  404.07  5287.3     409    5313  411.38  5323.8  414.59
    5375  421.51    5451  428.29  5493.4  430.59  5504.3  432.92  5542.9  434.93
#Mann= 5 ,-1 , 0
  4509.7     .16       0  4826.3     .05       0  4866.4    .033       0
  4872.4     .05       0  5087.5     .16       0
Bank Sta=4838.4,5207.3
XS Rating Curve= 0 ,0
Exp/Cntr=0.3,0.1

Type RM Length L Ch R = 1 ,4482    ,278,278,278
BEGIN DESCRIPTION:
UNT079 IN BECR 10.0
END DESCRIPTION:
XS GIS Cut Line= 3
      3801072.35     10552558.66      3800690.44     10552853.77
      3800382.27     10553422.38
#Sta/Elev= 30
  4450.3  440.41  4510.3  437.41  4553.8  433.25  4653.4  420.13  4681.2  414.26
  4695.1  412.59  4703.2  413.17  4709.6  410.25  4717.7  410.91  4753.1  407.26
  4759.4  403.86  4772.8  401.49    4782  400.78  4788.4  398.35  4802.9  396.03
  4814.4  393.01  4817.1  392.51  4820.4  393.01  5305.9  393.01    5325   395.6
  5338.3  397.25  5372.5  402.64    5418  407.58  5425.8  411.88  5440.7  415.53
  5447.6  419.58  5463.5  421.06  5469.5  423.29  5491.4  425.04  5579.7  437.53
#Mann= 5 ,-1 , 0
  4450.3     .16       0  4772.8     .05       0  4814.4    .033       0
  4820.4     .05       0    5325     .16       0
Bank Sta=4802.9,5338.3
XS Rating Curve= 0 ,0
Exp/Cntr=0.3,0.1

Type RM Length L Ch R = 1 ,4204    ,499,499,499
BEGIN DESCRIPTION:
UNT079 IN BECR 9.0
END DESCRIPTION:
XS GIS Cut Line= 2
      3800607.99     10552332.91      3800147.91     10553413.66
#Sta/Elev= 30
  4436.9  438.26  4547.9  434.35  4607.8  430.54  4624.2  428.06  4671.5  424.53
  4724.2  413.81  4738.3  409.36  4747.8  408.02  4753.2  404.71  4770.9  401.35
  4776.9  402.24  4792.6  395.64  4803.3  393.72  4811.3  393.01  4814.1  392.51
  4817.3  393.01  5287.1  393.01  5303.4  393.01  5334.8  399.67  5357.8  403.29
  5369.3   407.1  5379.5  407.85  5387.5  411.65  5401.2  413.34  5411.2  416.36
  5416.6  415.78  5463.9  425.93  5496.9  428.34  5540.2  433.17  5611.5  437.71
#Mann= 6 ,-1 , 0
  4436.9     .16       0  4803.3     .05       0  4811.3    .033       0
  4817.3     .05       0  5287.1     .16       0  5496.9     .05       0
Bank Sta=4776.9,5334.8
XS Rating Curve= 0 ,0
Exp/Cntr=0.3,0.1

Type RM Length L Ch R = 1 ,3705    ,561,561,561
BEGIN DESCRIPTION:
UNT079 IN BECR 8.0
END DESCRIPTION:
XS GIS Cut Line= 2
      3799987.32     10552055.12      3799809.36     10553444.07
#Sta/Elev= 30
  4280.2  441.87    4301     440  4380.7   437.3  4460.3  432.97    4535  424.33
  4547.4  423.95  4607.9  412.77  4614.6  409.48  4619.7  411.17  4643.8  407.06
  4654.1  406.16  4694.3  399.76  4699.3   400.3  4718.8  396.38  4728.9  393.04
    4736  393.01  4738.7  392.51    4742  393.01  4742.2  393.01  5132.2  393.01
  5152.3  395.08  5182.6  402.12    5233  408.59  5241.9  411.18  5263.2  412.15
  5293.5  417.31  5326.6  419.74  5401.3  430.08  5535.4  441.85  5680.5   449.5
#Mann= 6 ,-1 , 0
  4280.2     .16       0  4643.8     .07       0  4654.1     .16       0
    4736    .033       0    4742     .16       0  4742.2     .05       0
Bank Sta=4699.3,5182.6
XS Rating Curve= 0 ,0
Exp/Cntr=0.3,0.1

Type RM Length L Ch R = 1 ,3144    ,77,77,77
BEGIN DESCRIPTION:
UNT079 IN BECR 7.0
END DESCRIPTION:
XS GIS Cut Line= 4
      3799471.15     10552088.77       3799314.9     10552626.97
      3799401.71     10553312.73       3799679.5     10553764.15
#Sta/Elev= 30
    4268  439.94  4633.9  424.51  4688.6  419.53  4696.4  417.16  4729.6  413.78
  4748.5  409.43  4755.7   406.7  4779.7  403.22  4789.3  399.01  4794.5  400.47
  4810.9  396.16  4821.4  396.38  4827.5  394.46  4848.8  393.01  4851.6  392.51
  4854.8  393.01  5295.3  393.01  5307.2  397.14  5335.7  401.96  5355.8  407.05
    5376  407.38  5382.3  409.64  5436.4  415.24  5486.8  422.76  5603.1  434.03
  5829.2  449.71  5908.4  454.05  5939.2  457.43  5974.6  458.04  6049.7  461.91
#Mann= 4 ,-1 , 0
    4268     .16       0  4729.6     .05       0  4848.8     .03       0
  4854.8     .05       0
Bank Sta=4794.5,5355.8
XS Rating Curve= 0 ,0
Exp/Cntr=0.3,0.1

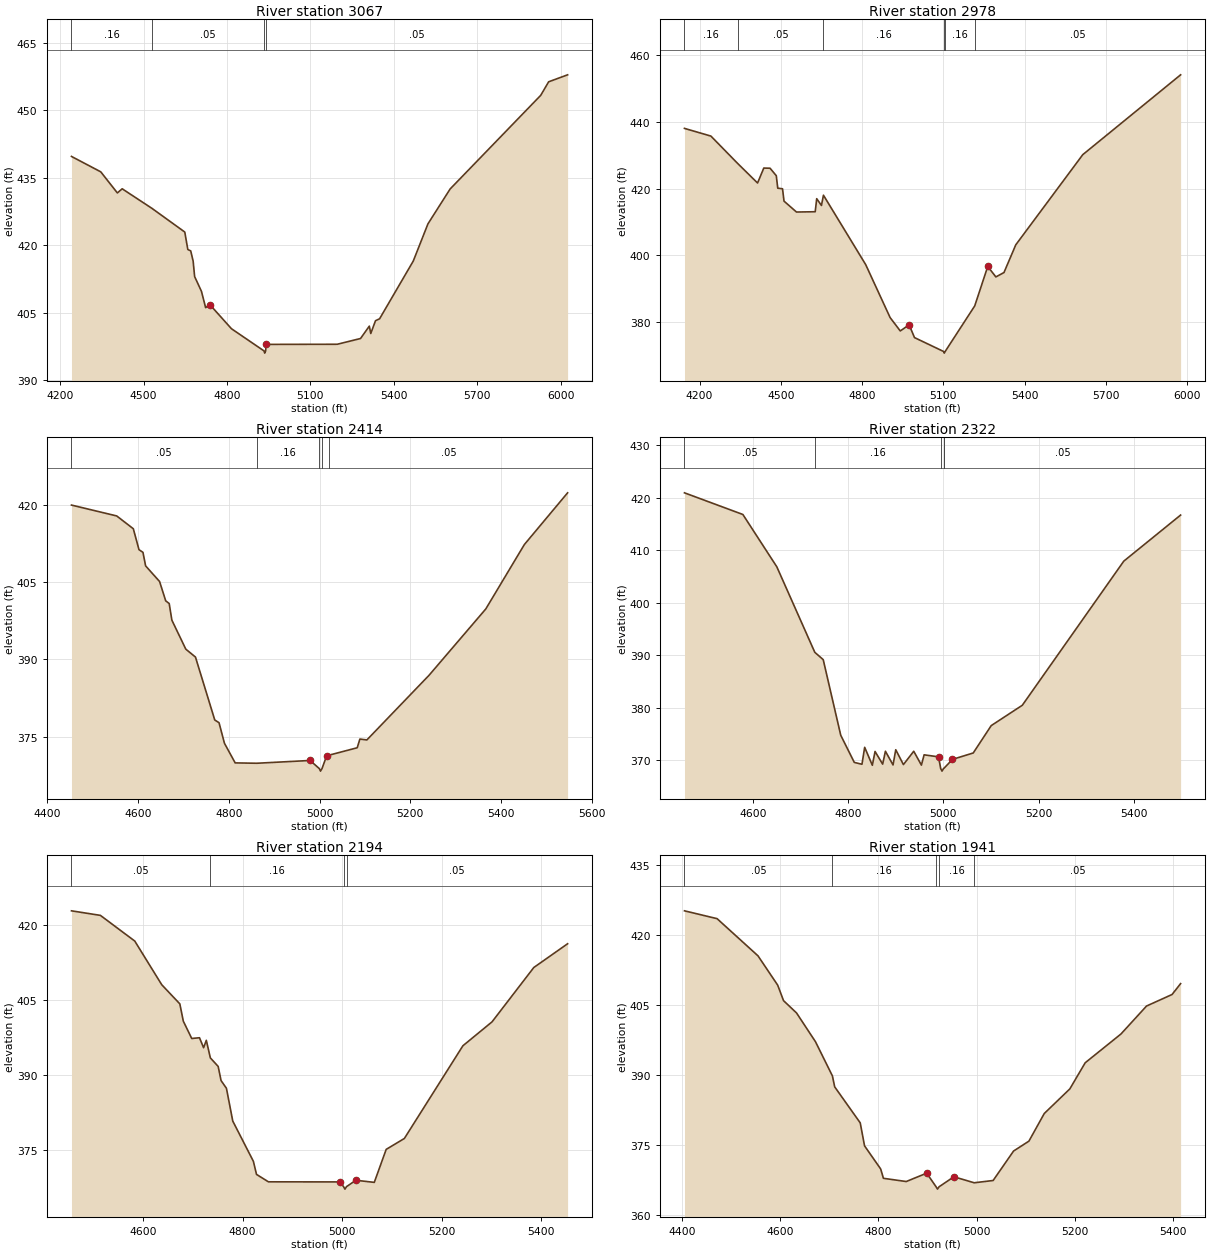
Type RM Length L Ch R = 1 ,3067    ,89,89,89
BEGIN DESCRIPTION:
Mapping XS e292b571
END DESCRIPTION:
XS GIS Cut Line= 5
      3799453.79     10552080.09      3799245.46     10552618.29
      3799280.18     10553069.68      3799349.62     10553278.01
      3799574.98      10553763.4
#Sta/Elev= 30
  4240.8  439.75  4346.1  436.33  4405.9  431.64  4423.2  432.56  4529.9  428.23
  4648.4  422.95  4659.3  419.07  4669.8  418.76  4678.5  416.48  4683.8  413.06
  4708.4  409.77  4723.4  406.15  4738.3  406.84  4816.3  401.47  4933.2  396.55
    4936  396.05  4939.2  396.55  4941.2  397.99    5197  398.02  5280.6   399.3
  5312.2  402.05  5317.4  400.41  5334.4  403.25  5349.1  403.68  5470.3  416.51
    5523  424.76  5602.9  432.52  5928.8  453.33  5957.2  456.33  6025.4  457.88
#Mann= 4 ,-1 , 0
  4240.8     .16       0  4529.9     .05       0  4933.2     .03       0
  4939.2     .05       0
Bank Sta=4738.3,4941.2
XS Rating Curve= 0 ,0
Exp/Cntr=0.3,0.1

Type RM Length L Ch R = 1 ,2978    ,564,564,564
BEGIN DESCRIPTION:
UNT079 IN BECR 6.0
END DESCRIPTION:
XS GIS Cut Line= 4
      3799436.43     10552019.32      3799167.33     10552609.61
      3799193.37      10553147.8      3799471.16     10553729.41
#Sta/Elev= 30
  4144.1  438.11  4241.7   435.8  4339.9  427.63    4414  421.71    4437   426.2
  4460.1  426.15  4483.1  423.91  4488.6  420.16  4506.2  419.98  4511.7  416.27
  4557.7     413  4626.9  413.09  4632.4  417.01  4649.9  414.97  4657.3  418.05
  4813.4   397.2  4903.5  381.31    4941   377.3  4973.6  379.13  4993.6   375.3
  5100.8  371.14  5103.5  370.64  5106.8  371.14    5216  384.83    5264  396.65
    5294  393.52    5324  394.84  5367.5  403.15  5614.9  430.22  5976.2  454.19
#Mann= 6 ,-1 , 0
  4144.1     .16       0  4339.9     .05       0  4657.3     .16       0
  5100.8     .07       0  5106.8     .16       0    5216     .05       0
Bank Sta=4973.6,5264
XS Rating Curve= 0 ,0
Exp/Cntr=0.3,0.1

Type RM Length L Ch R = 1 ,2414    ,92,92,92
BEGIN DESCRIPTION:
Mapping XS 472f0134
END DESCRIPTION:
XS GIS Cut Line= 2
      3798489.94     10552623.78      3799067.16     10553552.52
#Sta/Elev= 30
  4453.3  419.99    4553  417.88  4589.6  415.39  4602.1  411.33  4610.9   410.8
  4616.7  408.18  4647.5  405.14    4661  401.39  4668.7  400.86  4674.6  397.63
  4705.3     392  4726.6  390.46  4769.1  378.24  4778.5  377.71  4790.5  373.71
  4814.1   369.9  4861.8  369.83  4979.2  370.37  4999.5   368.8  5002.2   368.3
  5005.5   368.8  5015.8  371.29  5021.9  371.42  5083.1  372.84    5089  374.53
  5104.4  374.36  5241.3  386.91  5366.5  399.81  5451.5  412.32  5546.8  422.37
#Mann= 5 ,-1 , 0
  4453.3     .05       0  4861.8     .16       0  4999.5     .07       0
  5005.5     .16       0  5021.9     .05       0
Bank Sta=4979.2,5015.8
XS Rating Curve= 0 ,0
Exp/Cntr=0.3,0.1

Type RM Length L Ch R = 1 ,2322    ,128,128,128
BEGIN DESCRIPTION:
Mapping XS 02f94360
END DESCRIPTION:
XS GIS Cut Line= 3
      3798442.17     10552662.78       3798811.1      10553331.2
      3798910.94     10553591.64
#Sta/Elev= 30
  4456.1  420.94  4578.8  416.81  4650.2  406.82  4729.9  390.53  4747.6  389.13
  4784.4  374.72  4812.9  369.53    4829  369.18  4834.7  372.41  4850.8  368.99
  4856.5  371.62  4872.5   369.2  4878.3  371.66  4894.3  369.05    4900  371.95
  4916.1  369.12  4937.8  371.66  4953.9  369.02  4959.6  370.98    4990  370.59
  4994.4  368.37  4997.2  367.87  5000.4  368.37  5001.5  368.43  5019.2  370.11
  5062.8  371.33  5100.6  376.55  5165.9  380.43  5379.1  407.91  5498.5   416.7
#Mann= 5 ,-1 , 0
  4456.1     .05       0  4729.9     .16       0  4994.4     .07       0
  5000.4     .16       0  5001.5     .05       0
Bank Sta=4990,5019.2
XS Rating Curve= 0 ,0
Exp/Cntr=0.3,0.1

Type RM Length L Ch R = 1 ,2194    ,253,253,253
BEGIN DESCRIPTION:
UNT079 IN BECR 5.0
END DESCRIPTION:
XS GIS Cut Line= 2
      3798411.78     10552662.77      3798793.74     10553582.94
#Sta/Elev= 30
  4456.5  422.87  4514.6  421.96  4583.6  416.83  4637.8   408.1  4674.1  404.28
  4681.1  400.82    4698  397.36  4713.6  397.51  4721.8  395.52  4727.3  396.99
  4735.4  393.48  4751.1  391.78  4756.9  388.95  4767.7  387.41  4780.4  380.86
  4821.8  372.82  4828.1   370.2    4852  368.72  4995.1   368.7  5002.9  367.76
  5005.7  367.26  5008.9  367.76  5027.6  369.03  5064.6  368.61  5088.5   375.2
    5125  377.38  5242.5   395.9  5301.1  400.69  5384.9  411.54  5452.8  416.29
#Mann= 4 ,-1 , 0
  4456.5     .05       0  4735.4     .16       0  5002.9     .07       0
  5008.9     .05       0
Bank Sta=4995.1,5027.6
XS Rating Curve= 0 ,0
Exp/Cntr=0.3,0.1

Type RM Length L Ch R = 1 ,1941    ,548,548,548
BEGIN DESCRIPTION:
UNT079 IN BECR 4.0
END DESCRIPTION:
XS GIS Cut Line= 2
      3798229.83     10552696.42      3798515.77     10553666.87
#Sta/Elev= 30
  4404.5  425.22    4471  423.54  4554.4  415.57  4594.6  409.28  4606.5  405.96
  4633.1  403.31  4671.7  397.14  4706.2  389.81  4710.8  387.47  4762.9  379.75
  4771.7  374.82  4804.6  369.86  4810.2  367.86  4856.7  367.17  4898.4  368.96
  4917.6  366.04  4920.4  365.54  4923.6  366.04  4953.9  368.19  4995.3   366.9
  5033.9  367.39  5075.6  373.71  5106.9  375.83  5138.2  381.76  5190.3  387.03
  5221.6  392.63  5294.6  398.81  5346.7   404.8  5398.8  407.28  5416.2  409.61
#Mann= 5 ,-1 , 0
  4404.5     .05       0  4706.2     .16       0  4917.6     .03       0
  4923.6     .16       0  4995.3     .05       0
Bank Sta=4898.4,4953.9
XS Rating Curve= 0 ,0
Exp/Cntr=0.3,0.1

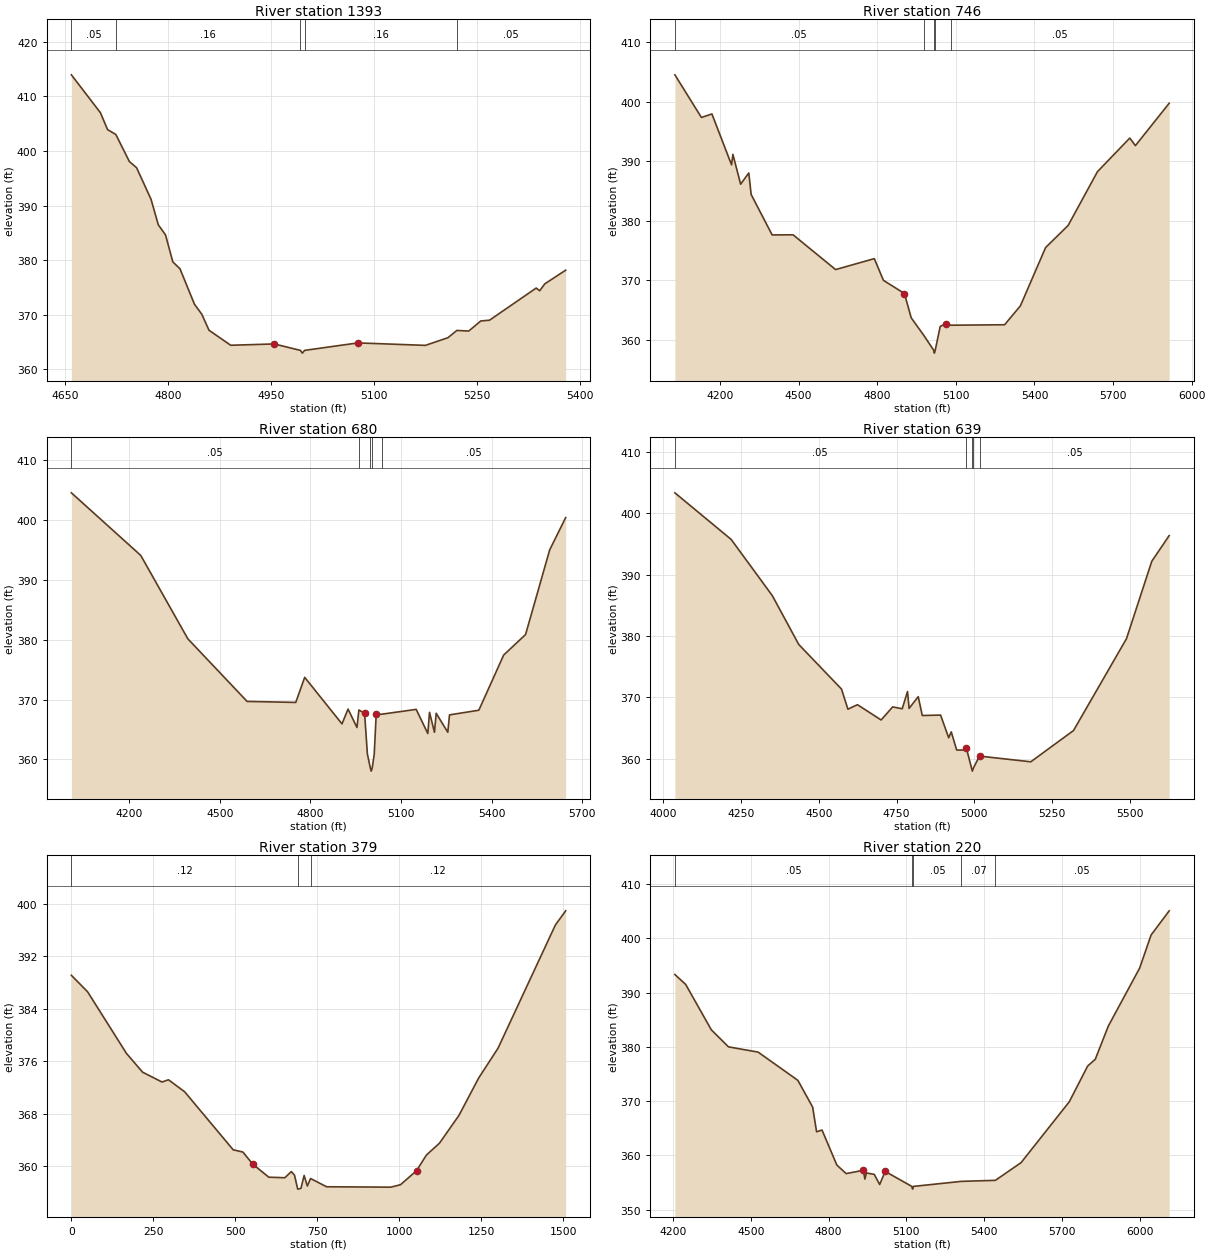
Type RM Length L Ch R = 1 ,1393    ,647,647,647
BEGIN DESCRIPTION:
UNT079 IN BECR 3.0
END DESCRIPTION:
XS GIS Cut Line= 3
      3798049.62     10552910.16      3797949.61     10553210.19
      3797899.61     10553610.22
#Sta/Elev= 30
  4659.2  413.92  4701.4     407  4711.9  403.89  4723.9     403  4743.6  398.05
  4754.1  396.92  4775.2  391.12  4785.7  386.47  4796.3   384.6  4806.8  379.69
  4817.3  378.41  4838.4  371.92    4849   370.1  4859.5  367.17  4891.1  364.42
  4954.4  364.66  4992.6  363.48  4995.4  362.98  4998.6  363.48  5076.2  364.85
  5174.5   364.4  5207.2   365.8  5220.2  367.13  5237.5  367.02  5255.1  368.87
  5267.7     369  5335.7  374.89  5340.8   374.4  5348.3  375.67  5378.6  378.16
#Mann= 5 ,-1 , 0
  4659.2     .05       0  4723.9     .16       0  4992.6     .07       0
  4998.6     .16       0  5220.2     .05       0
Bank Sta=4954.4,5076.2
XS Rating Curve= 0 ,0
Exp/Cntr=0.3,0.1

Type RM Length L Ch R = 1 ,746     ,66,66,66
BEGIN DESCRIPTION:
UNT079 IN BECR 2.0
END DESCRIPTION:
XS GIS Cut Line= 5
      3797590.94     10552187.72      3797356.57     10553062.73
      3797424.27     10553213.77      3797518.02     10553406.48
      3797819.52     10553926.29
#Sta/Elev= 30
  4027.6  404.53  4128.9  397.36    4169  397.95  4243.9   389.4    4249  391.16
  4278.6  386.15  4309.7  388.04  4318.7  384.42  4398.8  377.63  4478.9  377.64
    4641   371.8  4788.7  373.64  4823.6  369.99  4903.7  367.78  4929.6  363.69
  4976.8   360.8  5015.3  358.26  5018.1  357.76  5021.3  358.26  5040.3  362.25
  5062.2  362.71    5082  362.45  5286.1  362.53  5346.4  365.71  5442.5   375.5
  5528.6  379.22  5640.4  388.25  5763.8   393.9  5785.3  392.63  5914.2  399.75
#Mann= 5 ,-1 , 0
  4027.6     .05       0  4976.8     .12       0  5015.3     .07       0
  5021.3     .12       0    5082     .05       0
Bank Sta=4903.7,5062.2
XS Rating Curve= 0 ,0
Exp/Cntr=0.3,0.1

Type RM Length L Ch R = 1 ,680     ,41,41,41
BEGIN DESCRIPTION:
Mapping XS ace4923e
END DESCRIPTION:
XS GIS Cut Line= 5
      3797523.22     10552192.99      3797299.27      10553041.9
      3797304.48     10553109.61      3797476.36     10553437.73
      3797403.43     10553750.26
#Sta/Elev= 30
    4008  404.51  4237.8  394.06  4393.8  380.13    4590  369.68  4751.2  369.51
  4780.8   373.7  4904.3  365.93  4924.4   368.4  4953.9  365.33  4960.3  368.25
  4979.2  367.69  4988.4  360.92  4998.3  358.54    5001  358.04  5004.3  358.54
    5011   360.8  5017.7  367.56  5035.2  367.54  5150.1  368.35  5188.6  364.32
  5194.2  367.86  5210.6  364.53  5216.3   367.7  5254.8  364.53  5260.4  367.43
  5357.6  368.21  5439.8  377.42  5512.4  380.85  5592.3  394.99  5645.2  400.37
#Mann= 5 ,-1 , 0
    4008     .05       0  4960.3     .12       0  4998.3     .07       0
  5004.3     .12       0  5035.2     .05       0
Bank Sta=4979.2,5017.7
XS Rating Curve= 0 ,0
Exp/Cntr=0.3,0.1

Type RM Length L Ch R = 1 ,639     ,260,260,260
BEGIN DESCRIPTION:
Mapping XS b9dc7b44
END DESCRIPTION:
XS GIS Cut Line= 5
      3797465.95     10552218.95      3797262.82     10553083.56
      3797304.48     10553213.77      3797419.07     10553442.94
      3797361.78     10553744.98
#Sta/Elev= 30
  4037.7  403.34  4218.6  395.74  4350.9  386.57  4435.8  378.61  4573.2  371.34
  4593.7  368.06  4624.5  368.79  4700.5   366.3  4737.5  368.43  4768.3  368.13
  4785.3  370.94  4790.4  368.19  4819.7   370.1  4832.8  367.03  4891.6   367.1
  4917.6   363.4  4925.9  364.36  4943.3   361.4  4971.9  361.38  4974.8  361.66
    4991  358.46  4993.7  357.96    4997  358.46  5016.8  360.42  5016.9  360.41
  5181.5  359.48  5318.8  364.58    5489  379.56  5570.4  392.19  5626.2  396.36
#Mann= 5 ,-1 , 0
  4037.7     .05       0  4971.9     .12       0    4991     .07       0
    4997     .12       0  5016.9     .05       0
Bank Sta=4974.8,5016.8
XS Rating Curve= 0 ,0
Exp/Cntr=0.3,0.1

Type RM Length L Ch R = 1 ,379     ,159,159,159
XS GIS Cut Line= 5
     3797340.238     10552480.12     3797049.439    10552996.613
      3797053.78    10553443.662      3797223.05    10553595.572
     3797374.609    10553785.189
#Sta/Elev= 30
       0  389.13   49.33  386.62  167.73  377.22  217.06  374.34  276.25  372.84
  295.99  373.18  345.32  371.35  493.31  362.49  522.91  362.15  552.51  360.32
  601.84  358.31  650.79  358.23  670.37  359.17  680.16  358.62  689.95  356.49
  699.74   356.6  709.53  358.58  719.32  356.97  729.11  358.11  778.05  356.85
  973.85  356.79 1003.22  357.16 1052.34  359.31 1082.22  361.69 1122.05   363.5
 1181.81  367.77 1241.56  373.45 1300.59     378 1475.47  396.81 1506.79  398.97
#Mann= 3 ,-1 , 0
       0     .12       0  689.95     .07       0  729.11     .12       0
Bank Sta=552.51,1052.34
XS Rating Curve= 0 ,0
Exp/Cntr=0.3,0.1

Type RM Length L Ch R = 1 ,220     ,0,0,0
BEGIN DESCRIPTION:
UNT079 IN BECR 1.0
END DESCRIPTION:
XS GIS Cut Line= 4
      3797340.94     10552385.65      3796830.52     10553151.27
      3796856.57     10553442.94      3797413.85     10553854.39
#Sta/Elev= 30
  4207.3  393.33  4248.8  391.52  4347.9  383.13    4414     380  4528.2  379.03
  4681.4  373.83  4738.5  368.89  4753.6  364.35  4774.6  364.67  4831.7  358.22
  4867.7  356.64  4933.8  357.25  4939.8  355.63  4945.9  356.76  4975.9   356.5
  4996.9  354.63    5018  357.05  5120.8  354.28  5123.6  353.78  5126.8  354.28
  5311.7  355.21    5443   355.4    5542  358.66  5727.9  369.88  5798.8  376.47
  5828.1  377.71  5878.2  383.81  5999.3  394.53  6043.2  400.61    6113  405.07
#Mann= 5 ,-1 , 0
  4207.3     .05       0  5120.8     .03       0  5126.8     .05       0
  5311.7     .07       0    5443     .05       0
Bank Sta=4933.8,5018
XS Rating Curve= 0 ,0
Exp/Cntr=0.3,0.1

Chan Stop Cuts=-1
Use User Specified Reach Order=0
Composite Channel Slope=5