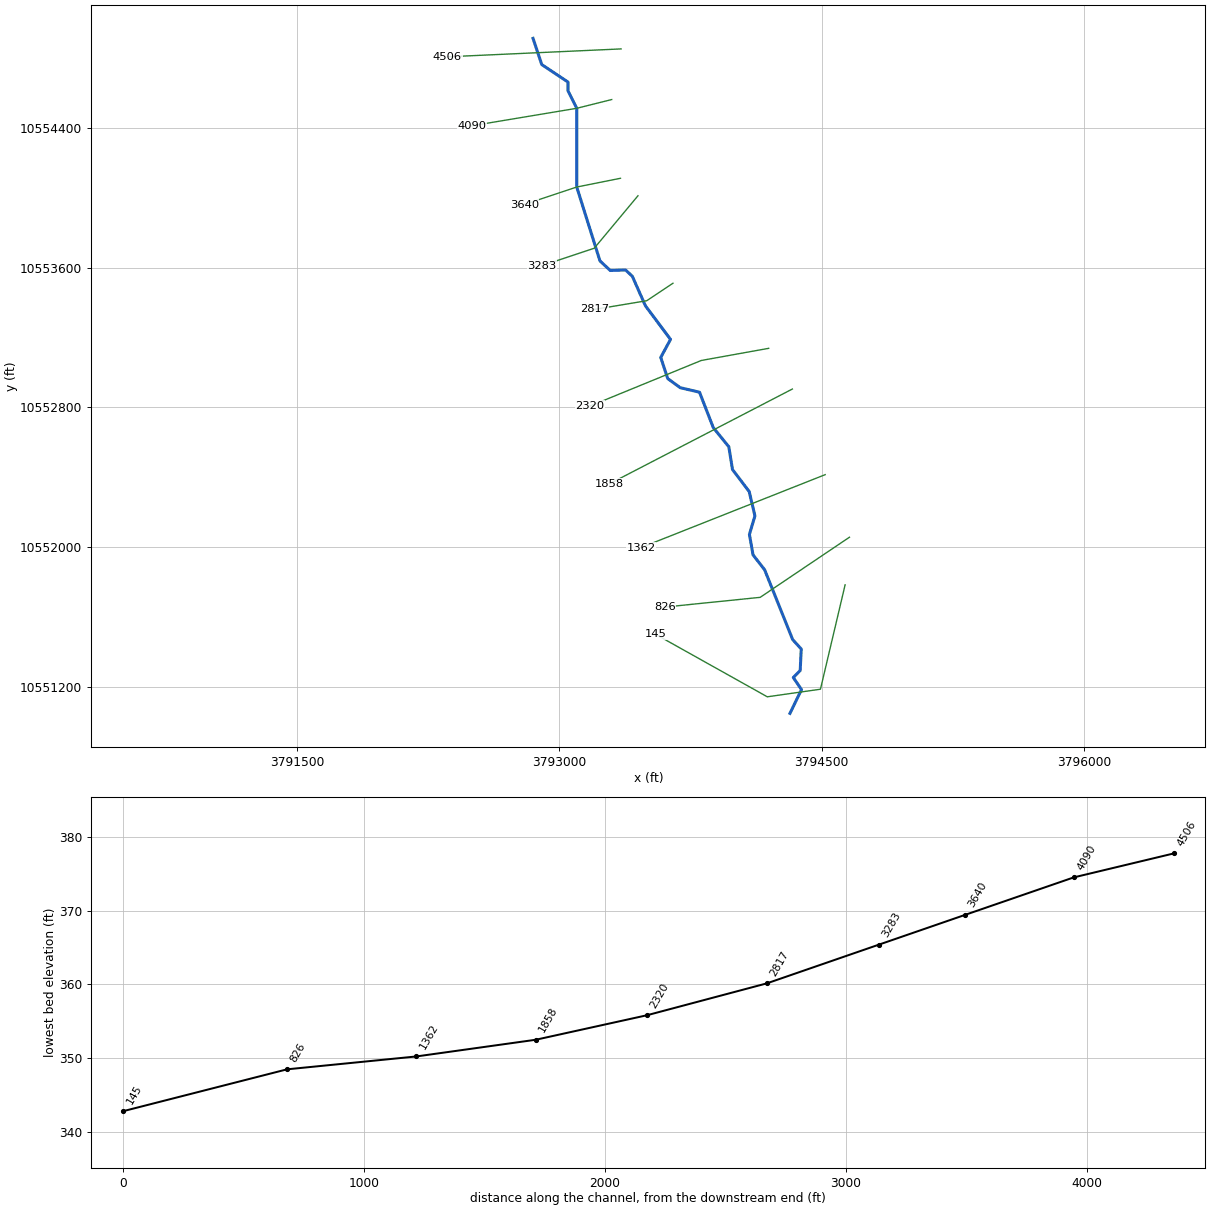
--- UNT080 IN BECR.prj (project) ---

Proj Title=UNT080 IN BECR Base Level Engineering
Current Plan=p01
Default Exp/Contr=0.3,0.1
English Units
Geom File=g01
Flow File=f01
Plan File=p01
BEGIN DESCRIPTION:
UNT080 IN BECR
END DESCRIPTION:

--- UNT080 IN BECR.p01 (plan) ---

Plan Title=Multiple Run
Short Identifier=Multiple
Geom File=g01
Flow File=f01
Subcritical Flow
K Sum by GR= 0
Std Step Tol= 0.01
Critical Tol= 0.01
Num of Std Step Trials= 20
Max Error Tol= 0.3
Flow Tol Ratio= 0.001
Split Flow NTrial= 30
Split Flow Tol= 0.02
Split Flow Ratio= 0.02
Log Output Level= 0
Friction Slope Method= 1
Unsteady Friction Slope Method= 2
Unsteady Bridges Friction Slope Method= 1
Parabolic Critical Depth
Global Vel Dist=  1 , 1 , 1
Global Log Level= 0
CheckData=True
Encroach Param= -1, 0, 0, 0
BEGIN DESCRIPTION:
Multiple Run
END DESCRIPTION:

--- UNT080 IN BECR.f01 (steady flow) ---

Flow Title=Multiple
Number of Profiles=7
Profile Names=10-year,25-year,50-year,1pct_min,100-year,1pct_plu,500-year
River Rch & RM= UNT080 IN BECR,Reach-1,4506
     595     805     979     876    1184    1601    1738
River Rch & RM= UNT080 IN BECR,Reach-1,1858
     636     863    1051     942    1273    1722    1873
Boundary for River Rch & Prof#=UNT080 IN BECR,Reach-1,1
Up Type=0
Dn Type=3
Dn Slope=0.005
Boundary for River Rch & Prof#=UNT080 IN BECR,Reach-1,2
Up Type=0
Dn Type=3
Dn Slope=0.005
Boundary for River Rch & Prof#=UNT080 IN BECR,Reach-1,3
Up Type=0
Dn Type=3
Dn Slope=0.005
Boundary for River Rch & Prof#=UNT080 IN BECR,Reach-1,4
Up Type=0
Dn Type=3
Dn Slope=0.005
Boundary for River Rch & Prof#=UNT080 IN BECR,Reach-1,5
Up Type=0
Dn Type=3
Dn Slope=0.005
Boundary for River Rch & Prof#=UNT080 IN BECR,Reach-1,6
Up Type=0
Dn Type=3
Dn Slope=0.005
Boundary for River Rch & Prof#=UNT080 IN BECR,Reach-1,7
Up Type=0
Dn Type=3
Dn Slope=0.005

--- UNT080 IN BECR.g01 (geometry) ---

Geom Title=Existing Conditions

River Reach=UNT080 IN BECR,Reach-1
Reach XY= 30
      3792849.61     10554910.19      3792899.61     10554760.19
      3793049.61     10554660.19      3793049.61     10554610.19
      3793099.61     10554510.19      3793099.61     10554060.19
      3793232.25     10553638.00      3793291.00     10553583.00
      3793378.50     10553586.00      3793417.25     10553550.00
      3793492.25     10553381.00      3793635.75     10553189.00
      3793579.75     10553086.00      3793619.75     10552965.00
      3793691.00     10552913.00      3793801.50     10552887.00
      3793880.00     10552685.00      3793969.00     10552575.00
      3793990.00     10552445.00      3794085.50     10552319.00
      3794118.25     10552180.00      3794086.75     10552074.00
      3794107.50     10551957.00      3794173.75     10551872.00
      3794334.00     10551473.00      3794383.00     10551419.00
      3794377.00     10551296.00      3794337.50     10551256.00
      3794384.50     10551187.00      3794318.50     10551051.00

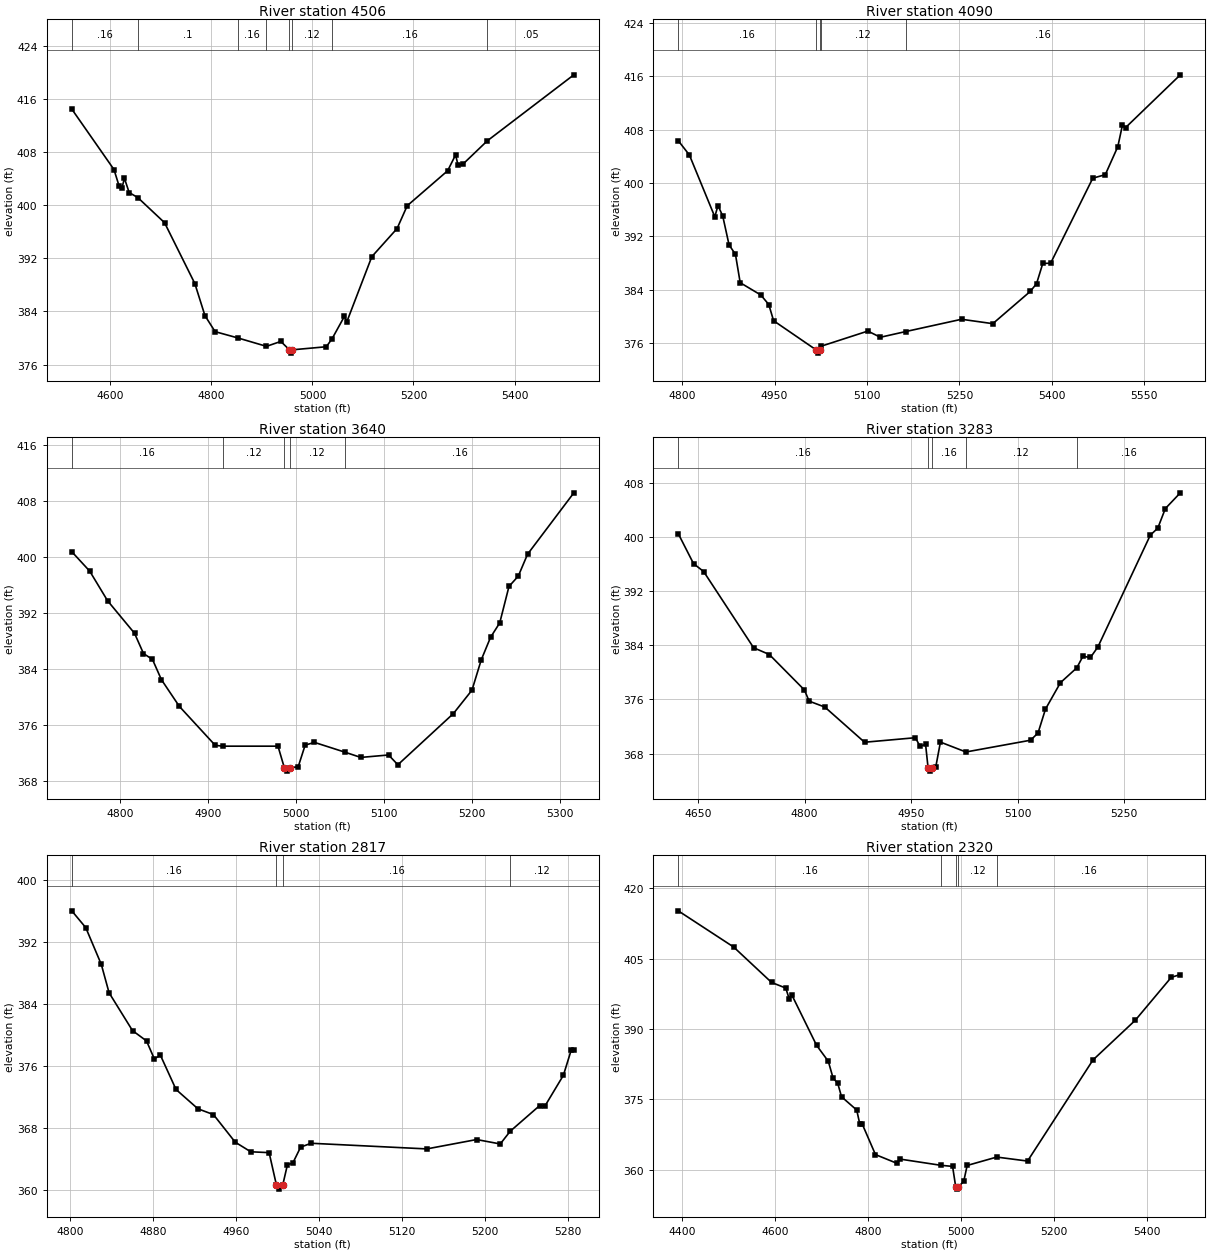
Type RM Length L Ch R = 1,4506,416,416,416
BEGIN DESCRIPTION:
UNT080 IN BECR 10.0
END DESCRIPTION:
XS GIS Cut Line= 2
      3793353.09     10554849.72      3792360.01     10554804.58
#Sta/Elev= 30
  4523.4  414.44  4607.0  405.34  4617.0  402.89  4622.6  402.50  4627.6  404.04
  4637.0  401.89  4654.4  401.11  4707.1  397.35  4767.1  388.19  4787.1  383.37
  4807.2  380.96  4852.0  380.02  4908.9  378.75  4937.3  379.49  4954.3  378.23
  4957.1  377.73  4960.3  378.23  5027.4  378.69  5038.7  379.88  5063.1  383.24
  5068.1  382.46  5117.5  392.24  5167.5  396.47  5187.6  399.90  5267.6  405.16
  5283.3  407.54  5288.3  406.00  5297.7  406.14  5346.1  409.66  5517.5  419.59
#Mann=8,-1,0
  4523.4    0.16       0  4654.4     0.1       0  4852.0    0.16       0
  4908.9    0.12       0  4954.3    0.07       0  4960.3    0.12       0
  5038.7    0.16       0  5346.1    0.05       0
Bank Sta=4954.3,4960.3
Exp/Cntr=0.3,0.1

Type RM Length L Ch R = 1,4090,450,450,450
BEGIN DESCRIPTION:
UNT080 IN BECR 9.0
END DESCRIPTION:
XS GIS Cut Line= 3
      3793299.65     10554560.20      3793099.61     10554510.19
      3792499.59     10554410.18
#Sta/Elev= 30
  4793.8  406.36  4811.9  404.21  4853.1  394.94  4858.3  396.63  4866.0  395.05
  4876.3  390.70  4886.6  389.32  4894.3  385.05  4927.8  383.20  4940.7  381.77
  4948.5  379.34  5017.3  374.98  5020.0  374.48  5023.3  374.98  5025.4  375.51
  5101.4  377.79  5121.7  376.86  5162.5  377.71  5253.4  379.56  5304.1  378.90
  5365.0  383.75  5375.1  384.91  5385.2  387.94  5397.9  387.97  5466.3  400.73
  5486.6  401.26  5506.9  405.46  5514.5  408.74  5519.6  408.33  5608.3  416.24
#Mann=5,-1,0
  4793.8    0.16       0  5017.3    0.07       0  5023.3    0.16       0
  5025.4    0.12       0  5162.5    0.16       0
Bank Sta=5017.3,5023.3
Exp/Cntr=0.3,0.1

Type RM Length L Ch R = 1,3640,357,357,357
BEGIN DESCRIPTION:
UNT080 IN BECR 8.0
END DESCRIPTION:
XS GIS Cut Line= 3
      3793349.66     10554110.20      3793099.61     10554060.19
      3792799.64     10553960.20
#Sta/Elev= 30
  4745.0  400.81  4765.4  398.03  4785.8  393.78  4816.4  389.14  4826.6  386.24
  4836.8  385.40  4847.0  382.50  4867.4  378.68  4908.2  373.11  4916.9  372.99
  4979.6  372.99  4986.8  369.92  4989.6  369.42  4992.8  369.92  5002.6  370.04
  5010.5  373.14  5021.1  373.53  5055.8  372.13  5073.8  371.38  5105.4  371.73
  5116.0  370.33  5179.2  377.66  5200.3  381.00  5210.8  385.32  5221.4  388.55
  5231.9  390.63  5242.4  395.84  5253.0  397.32  5263.5  400.44  5316.2  409.23
#Mann=5,-1,0
  4745.0    0.16       0  4916.9    0.12       0  4986.8    0.07       0
  4992.8    0.12       0  5055.8    0.16       0
Bank Sta=4986.8,4992.8
Exp/Cntr=0.3,0.1

Type RM Length L Ch R = 1,3283,466,466,466
BEGIN DESCRIPTION:
UNT080 IN BECR 7.0
END DESCRIPTION:
XS GIS Cut Line= 3
      3793449.63     10554010.21      3793199.61     10553710.19
      3792899.58     10553610.18
#Sta/Elev= 30
  4622.0  400.51  4643.5  396.08  4657.8  394.90  4728.1  383.64  4750.2  382.64
  4799.7  377.39  4806.2  375.75  4828.4  374.87  4884.3  369.67  4955.9  370.34
  4962.4  369.06  4970.2  369.36  4973.7  365.90  4976.5  365.40  4979.7  365.90
  4984.6  366.05  4991.1  369.69  5027.0  368.23  5118.0  369.97  5128.5  371.04
  5139.0  374.57  5160.1  378.48  5183.0  380.66  5191.7  382.37  5202.3  382.20
  5212.8  383.76  5286.6  400.29  5297.1  401.32  5307.7  404.21  5328.8  406.54
#Mann=5,-1,0
  4622.0    0.16       0  4973.7    0.07       0  4979.7    0.16       0
  5027.0    0.12       0  5183.0    0.16       0
Bank Sta=4973.7,4979.7
Exp/Cntr=0.3,0.1

Type RM Length L Ch R = 1,2817,497,497,497
BEGIN DESCRIPTION:
UNT080 IN BECR 6.0
END DESCRIPTION:
XS GIS Cut Line= 3
      3793649.59     10553510.18      3793499.61     10553410.19
      3793199.60     10553360.19
#Sta/Elev= 30
  4801.5  396.07  4815.0  393.90  4830.0  389.15  4837.5  385.49  4860.1  380.61
  4873.6  379.28  4881.1  376.98  4887.1  377.41  4902.1  373.01  4923.2  370.52
  4938.2  369.77  4959.2  366.21  4974.2  364.97  4991.9  364.86  4999.0  360.65
  5001.8  360.15  5005.0  360.65  5009.6  363.32  5014.7  363.50  5022.3  365.57
  5032.4  366.07  5144.0  365.34  5192.1  366.55  5214.9  365.98  5224.5  367.62
  5252.9  370.93  5258.0  370.87  5275.8  374.84  5283.4  378.11  5285.9  378.11
#Mann=4,-1,0
  4801.5    0.16       0  4999.0    0.07       0  5005.0    0.16       0
  5224.5    0.12       0
Bank Sta=4999,5005
Exp/Cntr=0.3,0.1

Type RM Length L Ch R = 1,2320,462,462,462
BEGIN DESCRIPTION:
UNT080 IN BECR 5.0
END DESCRIPTION:
XS GIS Cut Line= 3
      3794196.82     10553137.92      3793811.39     10553068.47
      3793176.01     10552808.07
#Sta/Elev= 30
  4392.5  415.23  4511.6  407.50  4592.9  399.95  4623.4  398.75  4631.0  396.39
  4636.0  397.37  4689.6  386.53  4714.8  383.12  4725.0  379.56  4735.1  378.41
  4743.2  375.55  4775.8  372.72  4782.5  369.70  4787.8  369.70  4816.1  363.21
  4861.7  361.37  4869.5  362.24  4956.1  360.93  4981.7  360.69  4988.4  356.34
  4991.1  355.84  4994.4  356.34  5005.7  357.52  5013.0  360.89  5076.5  362.68
  5142.7  361.83  5283.2  383.40  5374.0  391.87  5451.4  401.04  5470.8  401.63
#Mann=5,-1,0
  4392.5    0.16       0  4956.1    0.12       0  4988.4    0.07       0
  4994.4    0.12       0  5076.5    0.16       0
Bank Sta=4988.4,4994.4
Exp/Cntr=0.3,0.1

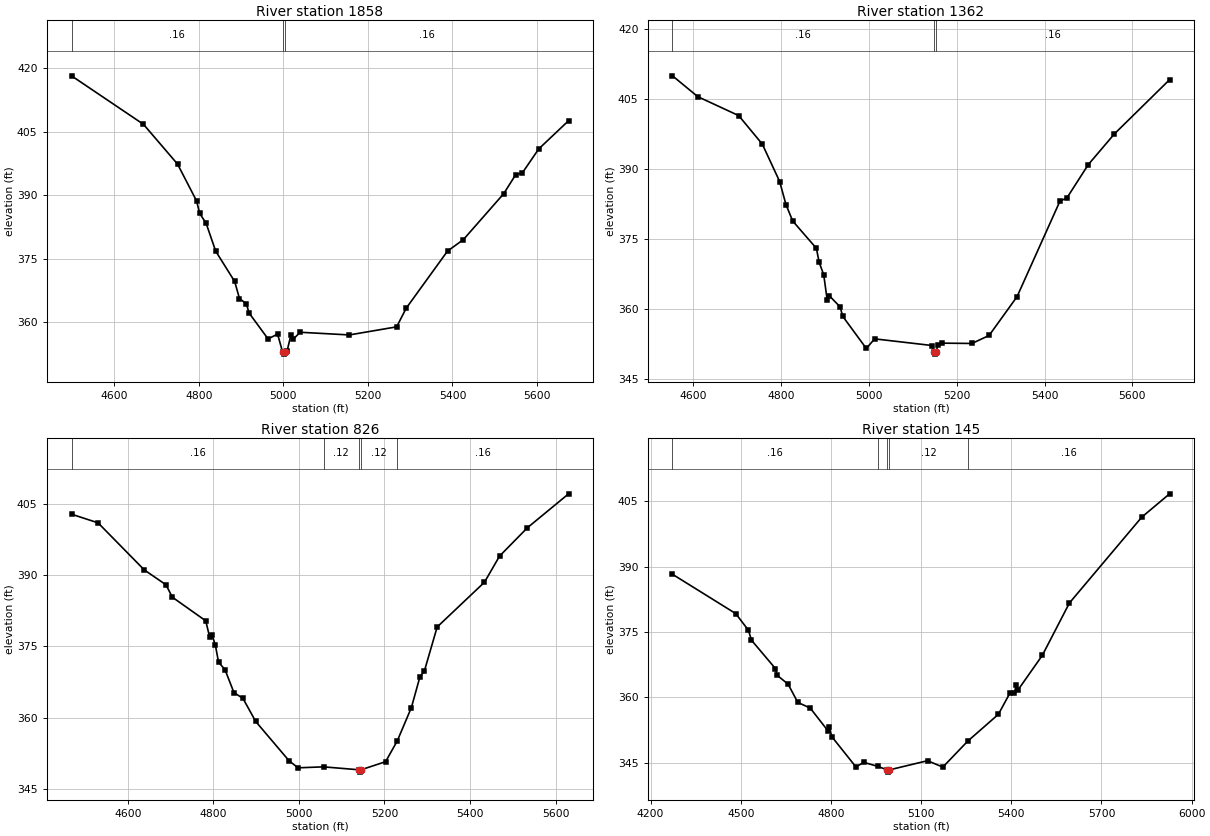
Type RM Length L Ch R = 1,1858,496,496,496
BEGIN DESCRIPTION:
UNT080 IN BECR 4.0
END DESCRIPTION:
XS GIS Cut Line= 2
      3794332.25     10552905.29      3793288.59     10552364.39
#Sta/Elev= 30
  4499.2  418.20  4669.4  406.75  4750.0  397.36  4795.0  388.66  4802.2  385.74
  4817.5  383.40  4840.1  376.83  4885.0  369.67  4896.4  365.64  4912.8  364.38
  4918.9  362.25  4964.0  356.11  4986.5  357.25  4998.3  353.02  5001.1  352.52
  5004.3  353.02  5009.0  353.27  5017.8  356.93  5023.5  356.06  5039.9  357.68
  5156.2  357.05  5268.1  358.96  5290.6  363.35  5388.4  376.84  5425.8  379.54
  5521.2  390.38  5549.7  394.89  5565.4  395.30  5604.1  400.95  5674.7  407.61
#Mann=3,-1,0
  4499.2    0.16       0  4998.3    0.07       0  5004.3    0.16       0
Bank Sta=4998.3,5004.3
Exp/Cntr=0.3,0.1

Type RM Length L Ch R = 1,1362,536,536,536
BEGIN DESCRIPTION:
UNT080 IN BECR 3.0
END DESCRIPTION:
XS GIS Cut Line= 2
      3794519.74     10552415.70      3793467.64     10551999.03
#Sta/Elev= 30
  4553.0  410.02  4610.5  405.55  4703.7  401.48  4757.5  395.35  4797.0  387.32
  4811.3  382.38  4826.7  378.84  4880.7  372.97  4886.6  370.05  4897.3  367.29
  4905.1  361.94  4910.4  362.76  4934.8  360.38  4940.3  358.41  4994.2  351.48
  5013.2  353.54  5144.7  352.10  5148.0  350.76  5150.7  350.26  5154.0  350.76
  5156.4  352.32  5166.2  352.62  5234.7  352.55  5273.8  354.27  5337.4  362.60
  5435.1  383.12  5450.9  383.80  5499.6  390.96  5559.0  397.55  5684.6  409.19
#Mann=3,-1,0
  4553.0    0.16       0  5148.0    0.07       0  5154.0    0.16       0
Bank Sta=5148,5154
Exp/Cntr=0.3,0.1

Type RM Length L Ch R = 1,826,681,681,681
BEGIN DESCRIPTION:
UNT080 IN BECR 2.0
END DESCRIPTION:
XS GIS Cut Line= 3
      3794658.64     10552058.08      3794148.20     10551714.31
      3793603.83     10551658.83
#Sta/Elev= 30
  4468.0  402.85  4530.0  401.03  4638.0  391.13  4688.9  387.98  4703.9  385.36
  4781.9  380.39  4790.9  377.04  4796.9  377.38  4804.4  375.27  4811.9  371.67
  4826.9  370.12  4847.9  365.27  4868.9  364.06  4898.8  359.19  4976.8  350.91
  4997.8  349.43  5057.4  349.63  5139.3  349.02  5142.1  348.52  5145.3  349.02
  5202.6  350.72  5230.1  355.14  5262.9  362.12  5283.0  368.63  5293.1  369.76
  5323.2  379.09  5433.8  388.52  5469.1  394.02  5534.3  400.00  5630.6  407.14
#Mann=5,-1,0
  4468.0    0.16       0  5057.4    0.12       0  5139.3    0.07       0
  5145.3    0.12       0  5230.1    0.16       0
Bank Sta=5139.3,5145.3
Exp/Cntr=0.3,0.1

Type RM Length L Ch R = 1,145,0,0,0
BEGIN DESCRIPTION:
UNT080 IN BECR 1.0
END DESCRIPTION:
XS GIS Cut Line= 4
      3794633.90     10551785.90      3794492.85     10551189.14
      3794189.03     10551145.74      3793548.87     10551503.80
#Sta/Elev= 30
  4272.9  388.22  4483.2  379.21  4525.4  375.40  4535.7  373.10  4615.2  366.61
  4620.3  365.10  4657.5  363.02  4689.8  358.83  4730.9  357.55  4789.5  352.38
  4794.6  353.09  4802.8  350.99  4883.0  344.05  4909.3  345.09  4957.0  344.15
  4987.4  343.35  4990.1  342.85  4993.4  343.35  5121.4  345.47  5172.2  344.00
  5255.0  349.95  5357.1  356.11  5394.8  360.91  5410.0  361.05  5416.5  362.80
  5422.2  361.68  5503.3  369.64  5593.4  381.64  5834.0  401.32  5926.5  406.67
#Mann=5,-1,0
  4272.9    0.16       0  4957.0    0.12       0  4987.4    0.07       0
  4993.4    0.12       0  5255.0    0.16       0
Bank Sta=4987.4,4993.4
Exp/Cntr=0.3,0.1

Chan Stop Cuts=-1