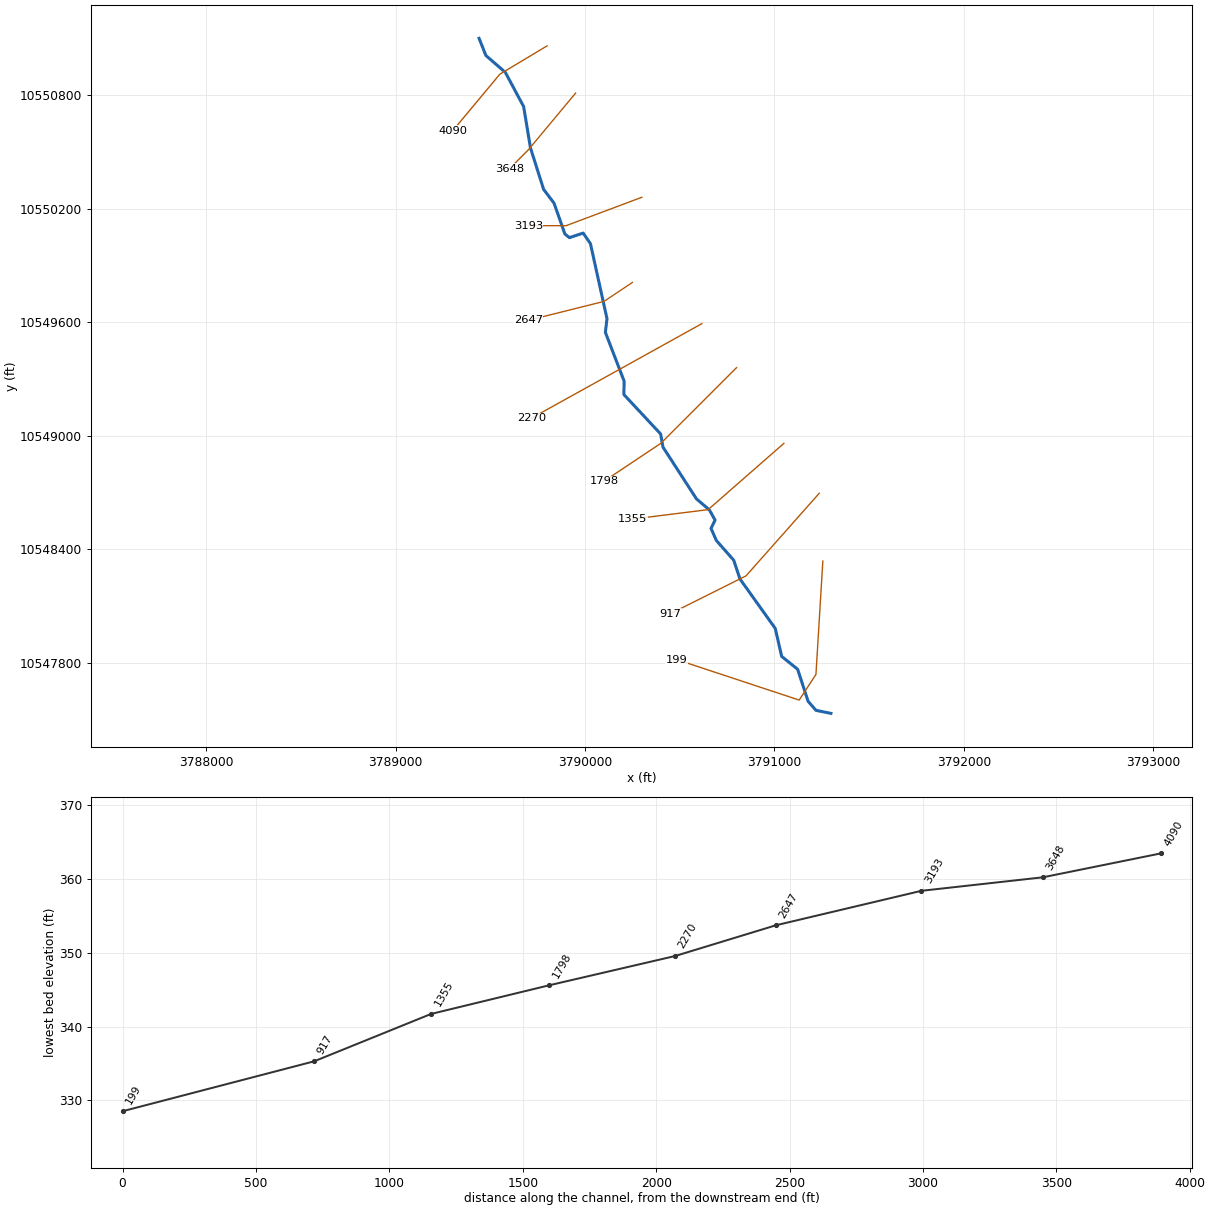
--- UNT082 IN BECR.prj (project) ---

Proj Title=UNT082 IN BECR Base Level Engineering
Current Plan=p01
Default Exp/Contr=0.3,0.1
English Units
Geom File=g01
Flow File=f01
Plan File=p01
BEGIN DESCRIPTION:
UNT082 IN BECR
END DESCRIPTION:

--- UNT082 IN BECR.p01 (plan) ---

Plan Title=Multiple Run
Short Identifier=Multiple
Geom File=g01
Flow File=f01
Subcritical Flow
K Sum by GR= 0
Std Step Tol= 0.01
Critical Tol= 0.01
Num of Std Step Trials= 20
Max Error Tol= 0.3
Flow Tol Ratio= 0.001
Split Flow NTrial= 30
Split Flow Tol= 0.02
Split Flow Ratio= 0.02
Log Output Level= 0
Friction Slope Method= 1
Unsteady Friction Slope Method= 2
Unsteady Bridges Friction Slope Method= 1
Parabolic Critical Depth
Global Vel Dist=  1 , 1 , 1
Global Log Level= 0
CheckData=True
Encroach Param= -1, 0, 0, 0
BEGIN DESCRIPTION:
Multiple Run
END DESCRIPTION:

--- UNT082 IN BECR.f01 (steady flow) ---

Flow Title=Multiple
Number of Profiles=7
Profile Names=10-year,25-year,50-year,1pct_min,100-year,1pct_plu,500-year
River Rch & RM= UNT082 IN BECR,Reach-1,4090
     568     765     928     828    1119    1514    1634
River Rch & RM= UNT082 IN BECR,Reach-1,3193
     717     979    1198    1077    1456    1969    2159
Boundary for River Rch & Prof#=UNT082 IN BECR,Reach-1,1
Up Type=0
Dn Type=3
Dn Slope=0.005
Boundary for River Rch & Prof#=UNT082 IN BECR,Reach-1,2
Up Type=0
Dn Type=3
Dn Slope=0.005
Boundary for River Rch & Prof#=UNT082 IN BECR,Reach-1,3
Up Type=0
Dn Type=3
Dn Slope=0.005
Boundary for River Rch & Prof#=UNT082 IN BECR,Reach-1,4
Up Type=0
Dn Type=3
Dn Slope=0.005
Boundary for River Rch & Prof#=UNT082 IN BECR,Reach-1,5
Up Type=0
Dn Type=3
Dn Slope=0.005
Boundary for River Rch & Prof#=UNT082 IN BECR,Reach-1,6
Up Type=0
Dn Type=3
Dn Slope=0.005
Boundary for River Rch & Prof#=UNT082 IN BECR,Reach-1,7
Up Type=0
Dn Type=3
Dn Slope=0.005

--- UNT082 IN BECR.g01 (geometry) ---

Geom Title=Existing Conditions

River Reach=UNT082 IN BECR,Reach-1
Reach XY= 30
      3789440.00     10551099.77      3789476.00     10551009.00
      3789578.75     10550920.00      3789675.50     10550739.00
      3789711.25     10550522.00      3789780.75     10550302.00
      3789836.00     10550229.00      3789893.25     10550066.00
      3789917.25     10550047.00      3789989.75     10550071.00
      3790028.25     10550015.00      3790115.50     10549619.00
      3790107.00     10549547.00      3790206.00     10549289.00
      3790204.75     10549218.00      3790398.75     10549010.00
      3790411.50     10548940.00      3790588.00     10548667.00
      3790656.00     10548609.00      3790686.25     10548555.00
      3790665.00     10548511.00      3790693.25     10548447.00
      3790784.75     10548343.00      3790817.75     10548244.00
      3791004.00     10547983.00      3791038.00     10547835.00
      3791122.25     10547767.00      3791177.50     10547598.00
      3791219.25     10547550.00      3791298.00     10547534.00

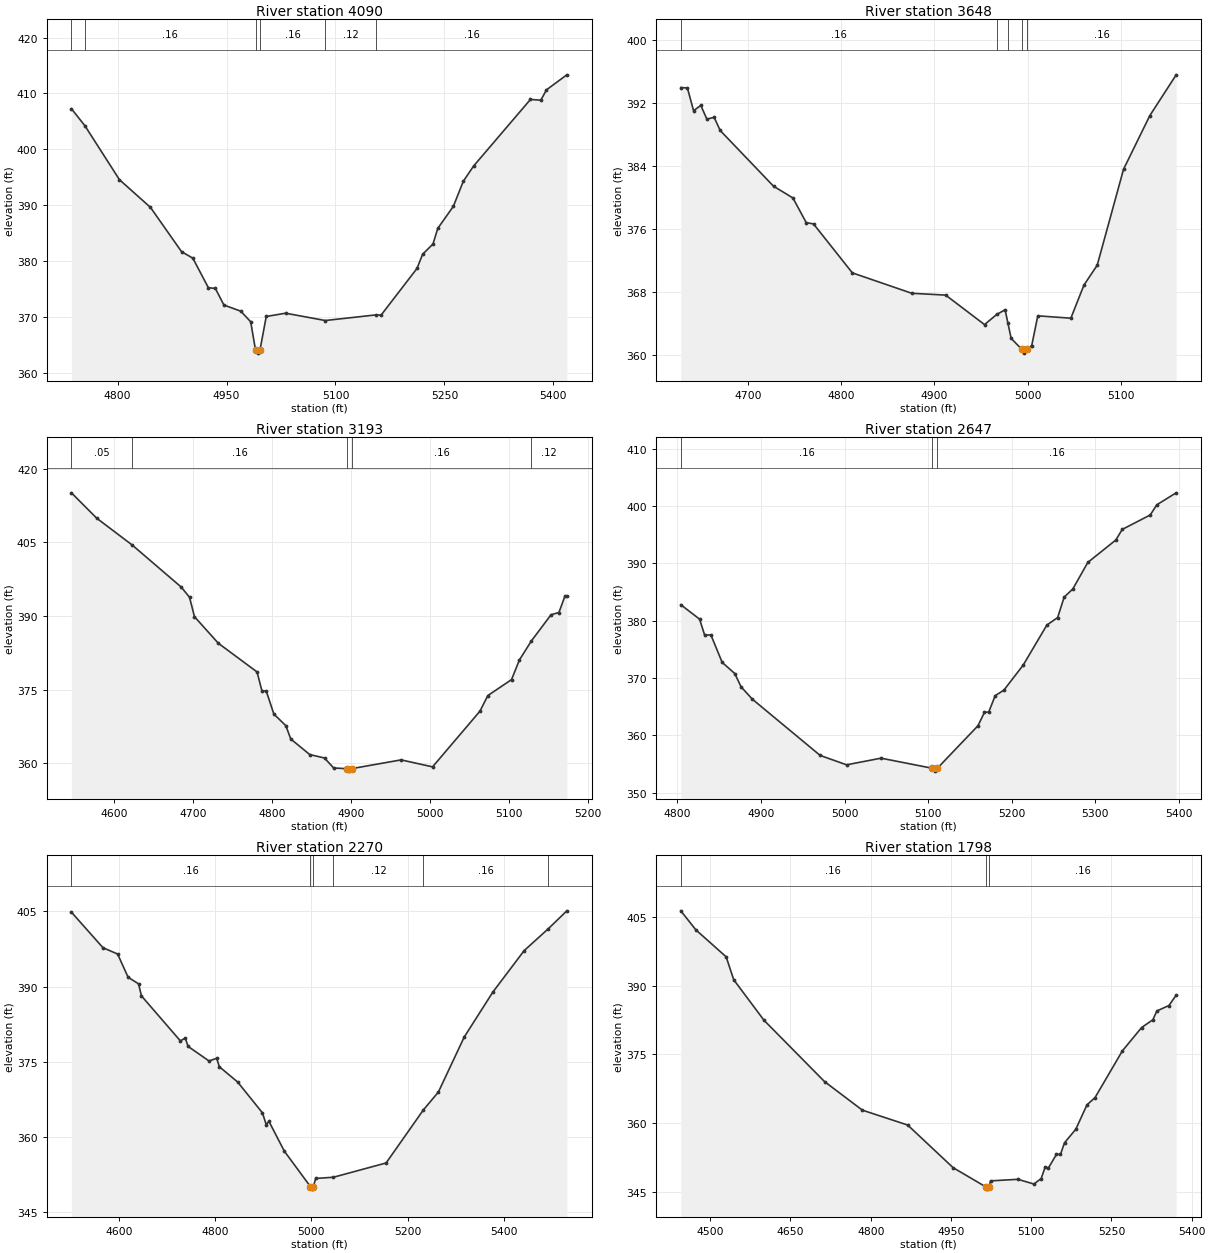
Type RM Length L Ch R = 1,4090,442,442,442
BEGIN DESCRIPTION:
UNT082 IN BECR 9.0
END DESCRIPTION:
XS GIS Cut Line= 3
      3789799.58     10551060.17      3789549.61     10550910.19
      3789299.63     10550610.21
#Sta/Elev= 30
  4736.5  407.27  4755.1  404.21  4802.6  394.56  4845.3  389.60  4888.1  381.67
  4903.6  380.51  4925.0  375.22  4934.7  375.08  4946.4  372.11  4969.7  371.01
  4983.3  369.11  4990.0  364.00  4992.8  363.50  4996.0  364.00  5004.7  370.06
  5031.3  370.65  5086.0  369.34  5155.9  370.35  5162.7  370.29  5212.2  378.66
  5220.0  381.21  5234.3  383.05  5240.8  385.83  5262.3  389.79  5276.0  394.28
  5290.3  397.03  5368.4  408.93  5382.7  408.80  5390.5  410.65  5418.5  413.34
#Mann=6,-1,0
  4736.5    0.05       0  4755.1    0.16       0  4990.0    0.07       0
  4996.0    0.16       0  5086.0    0.12       0  5155.9    0.16       0
Bank Sta=4990,4996
Exp/Cntr=0.3,0.1

Type RM Length L Ch R = 1,3648,455,455,455
BEGIN DESCRIPTION:
UNT082 IN BECR 8.0
END DESCRIPTION:
XS GIS Cut Line= 3
      3789949.60     10550810.18      3789699.61     10550510.19
      3789599.62     10550410.20
#Sta/Elev= 30
  4627.6  393.94  4634.7  393.90  4641.3  391.01  4649.1  391.68  4655.6  389.94
  4663.4  390.17  4669.9  388.50  4727.2  381.43  4748.0  379.94  4762.3  376.81
  4770.1  376.65  4811.8  370.44  4875.6  367.85  4912.0  367.62  4953.7  363.88
  4966.9  365.17  4975.8  365.76  4978.7  364.14  4982.3  362.13  4993.6  360.76
  4996.4  360.26  4999.6  360.76  5004.4  361.22  5010.9  364.99  5046.4  364.69
  5060.5  368.90  5074.7  371.41  5103.0  383.59  5131.2  390.39  5159.5  395.56
#Mann=5,-1,0
  4627.6    0.16       0  4966.9    0.12       0  4978.7    0.16       0
  4993.6    0.07       0  4999.6    0.16       0
Bank Sta=4993.6,4999.6
Exp/Cntr=0.3,0.1

Type RM Length L Ch R = 1,3193,546,546,546
BEGIN DESCRIPTION:
UNT082 IN BECR 7.0
END DESCRIPTION:
XS GIS Cut Line= 3
      3790299.63     10550260.20      3789899.61     10550110.19
      3789699.63     10550110.19
#Sta/Elev= 30
  4545.8  415.11  4577.9  409.93  4622.8  404.47  4684.7  395.93  4695.3  393.84
  4701.6  389.88  4731.8  384.47  4780.8  378.63  4787.0  374.76  4792.4  374.76
  4802.1  370.05  4817.3  367.68  4823.5  364.97  4847.5  361.81  4866.2  361.10
  4877.8  359.07  4894.4  358.93  4897.1  358.43  4900.4  358.93  4963.2  360.72
  5003.0  359.30  5063.0  370.64  5073.0  373.82  5103.0  377.07  5113.0  381.08
  5128.2  384.96  5153.0  390.28  5163.0  390.73  5170.5  394.02  5173.0  394.02
#Mann=5,-1,0
  4545.8    0.05       0  4622.8    0.16       0  4894.4    0.07       0
  4900.4    0.16       0  5128.2    0.12       0
Bank Sta=4894.4,4900.4
Exp/Cntr=0.3,0.1

Type RM Length L Ch R = 1,2647,377,377,377
BEGIN DESCRIPTION:
UNT082 IN BECR 6.0
END DESCRIPTION:
XS GIS Cut Line= 3
      3790249.58     10549810.17      3790099.61     10549710.19
      3789699.57     10549610.18
#Sta/Elev= 30
  4804.1  382.78  4826.6  380.26  4832.6  377.49  4840.1  377.51  4853.6  372.72
  4868.7  370.77  4876.2  368.46  4889.7  366.30  4970.8  356.49  5002.4  354.85
  5043.6  356.01  5105.0  354.25  5107.8  353.75  5111.0  354.25  5159.6  361.67
  5167.3  364.00  5172.5  364.07  5180.2  366.92  5190.5  367.86  5213.7  372.25
  5242.0  379.23  5254.9  380.54  5262.7  384.11  5273.0  385.52  5291.0  390.16
  5324.5  394.07  5332.2  395.92  5365.7  398.44  5373.5  400.21  5396.7  402.30
#Mann=3,-1,0
  4804.1    0.16       0  5105.0    0.07       0  5111.0    0.16       0
Bank Sta=5105,5111
Exp/Cntr=0.3,0.1

Type RM Length L Ch R = 1,2270,472,472,472
BEGIN DESCRIPTION:
UNT082 IN BECR 5.0
END DESCRIPTION:
XS GIS Cut Line= 2
      3790616.97     10549592.79      3789715.90     10549092.78
#Sta/Elev= 30
  4500.8  404.83  4566.4  397.74  4596.9  396.48  4618.7  391.85  4640.4  390.54
  4646.5  388.13  4727.4  379.16  4737.7  379.72  4743.4  378.06  4786.9  375.16
  4802.9  375.68  4808.6  373.99  4846.4  370.97  4898.1  364.81  4905.9  362.48
  4911.6  363.11  4943.7  357.16  4998.0  350.09  5000.7  349.59  5004.0  350.09
  5008.9  351.72  5045.7  351.96  5155.4  354.81  5233.0  365.40  5264.1  368.95
  5317.9  379.93  5377.4  388.89  5442.6  397.17  5492.6  401.51  5531.3  405.10
#Mann=6,-1,0
  4500.8    0.16       0  4998.0    0.07       0  5004.0    0.16       0
  5045.7    0.12       0  5233.0    0.16       0  5492.6    0.05       0
Bank Sta=4998,5004
Exp/Cntr=0.3,0.1

Type RM Length L Ch R = 1,1798,443,443,443
BEGIN DESCRIPTION:
UNT082 IN BECR 4.0
END DESCRIPTION:
XS GIS Cut Line= 3
      3790799.58     10549360.16      3790399.61     10548960.19
      3790099.61     10548760.19
#Sta/Elev= 30
  4444.9  406.29  4473.1  402.14  4529.7  396.26  4543.9  391.26  4600.4  382.44
  4713.6  369.07  4784.3  362.84  4869.1  359.59  4954.0  350.30  5015.1  346.12
  5017.8  345.62  5021.1  346.12  5024.1  347.42  5075.1  347.76  5105.2  346.73
  5118.7  347.93  5126.2  350.45  5132.2  350.23  5147.3  353.21  5154.8  353.19
  5162.3  355.73  5183.3  358.65  5204.3  363.99  5219.4  365.58  5270.5  375.76
  5306.5  380.85  5327.5  382.54  5335.0  384.46  5357.6  385.65  5371.1  387.91
#Mann=3,-1,0
  4444.9    0.16       0  5015.1    0.07       0  5021.1    0.16       0
Bank Sta=5015.1,5021.1
Exp/Cntr=0.3,0.1

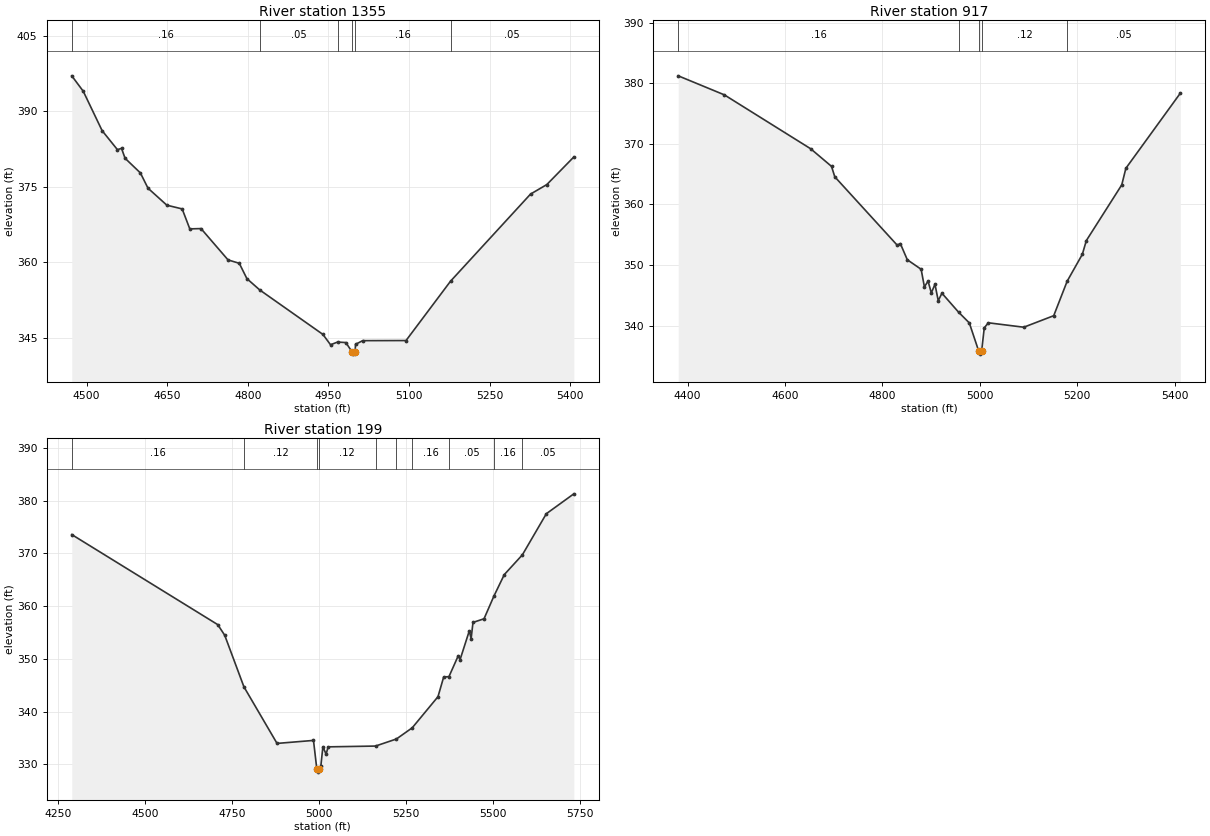
Type RM Length L Ch R = 1,1355,438,438,438
BEGIN DESCRIPTION:
UNT082 IN BECR 3.0
END DESCRIPTION:
XS GIS Cut Line= 3
      3791049.63     10548960.21      3790649.61     10548610.19
      3790249.66     10548560.19
#Sta/Elev= 30
  4472.4  397.06  4493.8  393.99  4528.9  386.16  4557.4  382.38  4565.0  382.64
  4571.6  380.67  4600.1  377.76  4614.3  374.72  4649.4  371.34  4677.9  370.60
  4692.1  366.63  4713.0  366.69  4763.3  360.46  4784.2  359.79  4798.4  356.74
  4822.3  354.49  4939.9  345.65  4954.1  343.59  4967.1  344.13  4982.6  344.03
  4993.8  342.23  4996.6  341.73  4999.8  342.23  5000.6  343.68  5014.0  344.41
  5094.6  344.43  5177.4  356.22  5326.4  373.55  5356.7  375.44  5407.0  380.93
#Mann=6,-1,0
  4472.4    0.16       0  4822.3    0.05       0  4967.1    0.16       0
  4993.8    0.07       0  4999.8    0.16       0  5177.4    0.05       0
Bank Sta=4993.8,4999.8
Exp/Cntr=0.3,0.1

Type RM Length L Ch R = 1,917,718,718,718
BEGIN DESCRIPTION:
UNT082 IN BECR 2.0
END DESCRIPTION:
XS GIS Cut Line= 3
      3791236.71     10548696.91      3790849.61     10548260.19
      3790449.61     10548060.19
#Sta/Elev= 30
  4380.7  381.23  4475.4  378.09  4652.7  369.19  4695.4  366.29  4702.1  364.57
  4830.1  353.30  4836.7  353.55  4851.0  350.88  4879.4  349.31  4886.1  346.41
  4893.6  347.36  4900.3  345.41  4907.8  346.84  4914.5  344.12  4922.1  345.36
  4956.4  342.22  4978.3  340.46  4997.6  335.81  5000.4  335.31  5003.6  335.81
  5009.0  339.65  5017.4  340.48  5090.1  339.75  5151.6  341.65  5179.3  347.36
  5210.3  351.77  5218.6  354.05  5291.3  363.24  5299.7  365.97  5411.5  378.36
#Mann=5,-1,0
  4380.7    0.16       0  4956.4    0.12       0  4997.6    0.07       0
  5003.6    0.12       0  5179.3    0.05       0
Bank Sta=4997.6,5003.6
Exp/Cntr=0.3,0.1

Type RM Length L Ch R = 1,199,0,0,0
BEGIN DESCRIPTION:
UNT082 IN BECR 1.0
END DESCRIPTION:
XS GIS Cut Line= 4
      3791255.44     10548338.68      3791218.98     10547739.71
      3791130.44     10547604.29      3790484.60     10547817.83
#Sta/Elev= 30
  4289.5  373.56  4708.8  356.49  4728.8  354.48  4784.0  344.70  4879.1  333.98
  4983.8  334.55  4993.5  329.04  4996.3  328.54  4999.5  329.04  5004.9  329.68
  5010.8  333.35  5020.0  331.94  5025.9  333.33  5161.9  333.48  5222.0  334.82
  5267.4  336.94  5341.4  342.84  5357.7  346.56  5372.9  346.64  5399.6  350.60
  5404.9  349.87  5431.3  355.31  5436.6  353.85  5441.9  356.91  5473.6  357.60
  5502.1  361.91  5531.8  365.97  5583.8  369.72  5652.6  377.51  5731.6  381.28
#Mann=10,-1,0
  4289.5    0.16       0  4784.0    0.12       0  4993.5    0.07       0
  4999.5    0.12       0  5161.9    0.16       0  5222.0    0.12       0
  5267.4    0.16       0  5372.9    0.05       0  5502.1    0.16       0
  5583.8    0.05       0
Bank Sta=4993.5,4999.5
Exp/Cntr=0.3,0.1

Chan Stop Cuts=-1