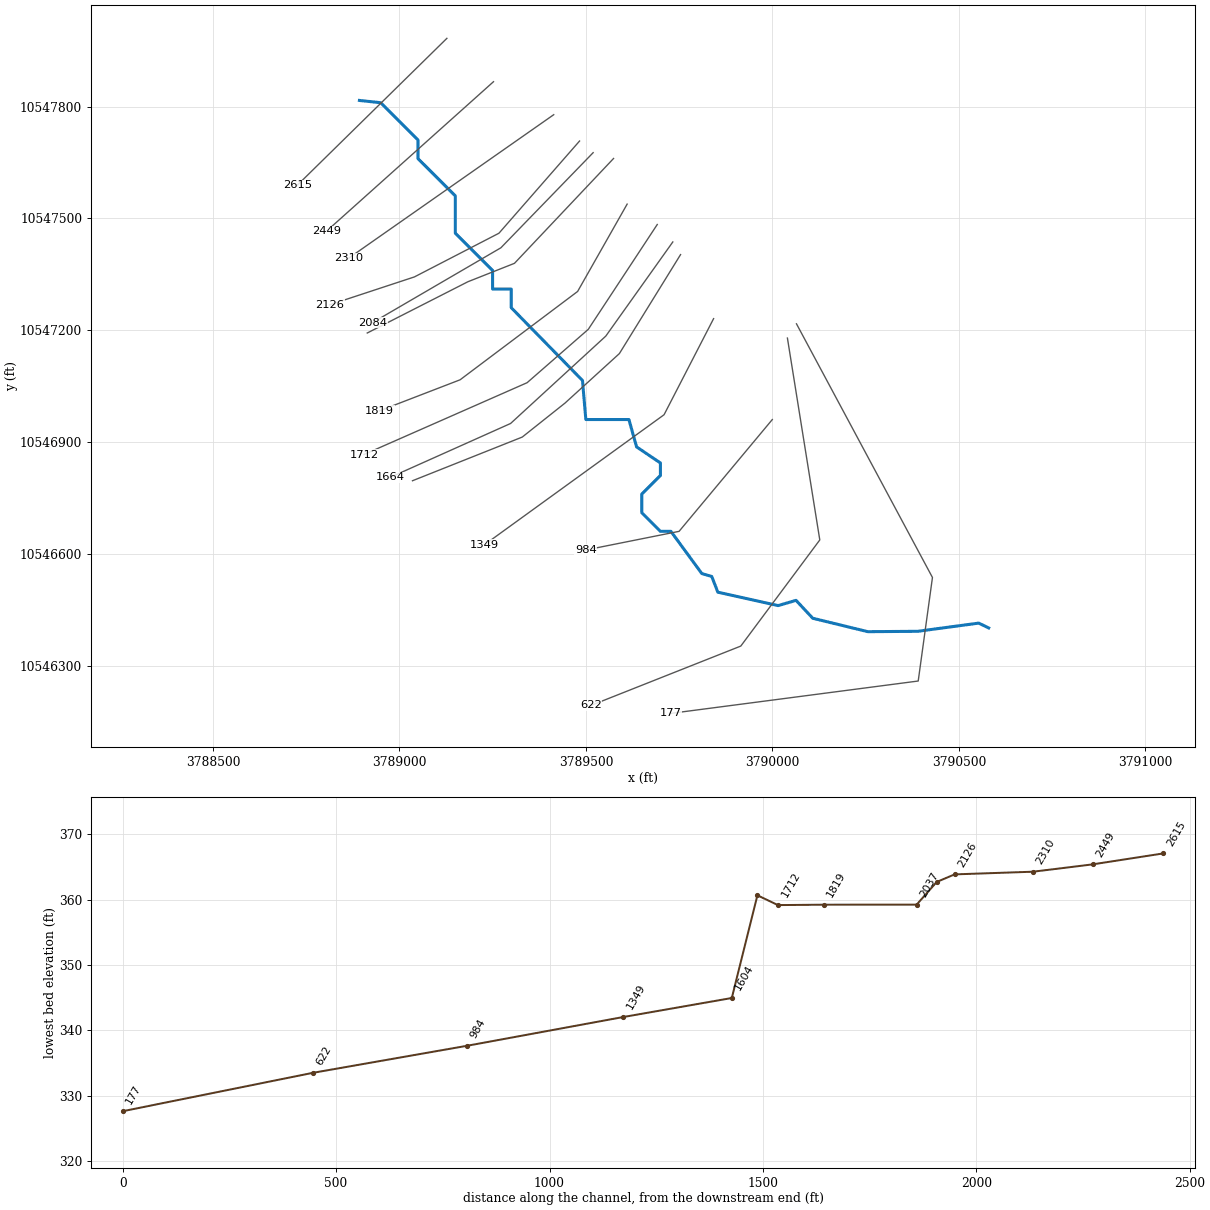
--- UNT083 IN BECR.prj (project) ---

Proj Title=UNT083 IN BECR Base Level Engineering
Current Plan=p01
Default Exp/Contr=0.3,0.1
English Units
Geom File=g01
Flow File=f01
Plan File=p01
Y Axis Title=Elevation
X Axis Title(PF)=Main Channel Distance
X Axis Title(XS)=Station
BEGIN DESCRIPTION:
UNT083 IN BECR
END DESCRIPTION:
DSS Export Rating Curves= 0
DSS Export Rating Curve Sorted= 0
DSS Export Volume Flow Curves= 0
DXF OffsetX= 0
DXF OffsetY= 0
DXF ScaleX= 1
DXF ScaleY= 10

--- UNT083 IN BECR.p01 (plan) ---

Plan Title=Multiple Run
Short Identifier=Multiple
Geom File=g01
Flow File=f01
Subcritical Flow
K Sum by GR= 0
Std Step Tol= 0.01
Critical Tol= 0.01
Num of Std Step Trials= 20
Max Error Tol= 0.3
Flow Tol Ratio= 0.001
Split Flow NTrial= 30
Split Flow Tol= 0.02
Split Flow Ratio= 0.02
Log Output Level= 0
Friction Slope Method= 1
Unsteady Friction Slope Method= 2
Unsteady Bridges Friction Slope Method= 1
Parabolic Critical Depth
Global Vel Dist=  1 , 1 , 1
Global Log Level= 0
CheckData=True
Encroach Param= -1, 0, 0, 0
BEGIN DESCRIPTION:
Multiple Run
END DESCRIPTION:

--- UNT083 IN BECR.f01 (steady flow) ---

Flow Title=Multiple
Program Version=4.10
Number of Profiles= 7
Profile Names=10-year,25-year,50-year,1pct_min,100-year,1pct_plu,500-year
River Rch & RM=UNT083 IN BECR,Reach-1         ,2615
     308     402     477     418     565     765     795
Boundary for River Rch & Prof#=UNT083 IN BECR,Reach-1         , 1
Up Type= 0
Dn Type= 3
Dn Slope=0.005
Boundary for River Rch & Prof#=UNT083 IN BECR,Reach-1         , 2
Up Type= 0
Dn Type= 3
Dn Slope=0.005
Boundary for River Rch & Prof#=UNT083 IN BECR,Reach-1         , 3
Up Type= 0
Dn Type= 3
Dn Slope=0.005
Boundary for River Rch & Prof#=UNT083 IN BECR,Reach-1         , 4
Up Type= 0
Dn Type= 3
Dn Slope=0.005
Boundary for River Rch & Prof#=UNT083 IN BECR,Reach-1         , 5
Up Type= 0
Dn Type= 3
Dn Slope=0.005
Boundary for River Rch & Prof#=UNT083 IN BECR,Reach-1         , 6
Up Type= 0
Dn Type= 3
Dn Slope=0.005
Boundary for River Rch & Prof#=UNT083 IN BECR,Reach-1         , 7
Up Type= 0
Dn Type= 3
Dn Slope=0.005
DSS Import GetInterval= 0
DSS Import GetPeak= 0
DSS Import FillOption= 0

--- UNT083 IN BECR.g01 (geometry) ---

Geom Title=Existing Conditions
Program Version=4.10

River Reach=UNT083 IN BECR  ,Reach-1
Reach XY= 30
      3788892.55     10547816.27      3788949.61     10547810.19
      3789049.61     10547710.19      3789049.61     10547660.19
      3789149.61     10547560.19      3789149.61     10547460.19
      3789249.61     10547360.19      3789249.61     10547310.19
      3789299.61     10547310.19      3789299.61     10547260.19
      3789490.62     10547064.98      3789499.61     10546960.19
      3789615.15     10546960.19      3789635.63     10546886.71
      3789699.61     10546843.66      3789699.61     10546810.19
      3789649.61     10546760.19      3789649.61     10546710.19
      3789699.61     10546660.19      3789727.68     10546660.19
       3789810.5       10546547.      3789837.25       10546539.
       3789853.5       10546497.        3790015.       10546461.
      3790063.25       10546475.        3790108.       10546427.
      3790255.75       10546391.      3790389.75       10546392.
        3790553.       10546414.      3790579.75       10546401.

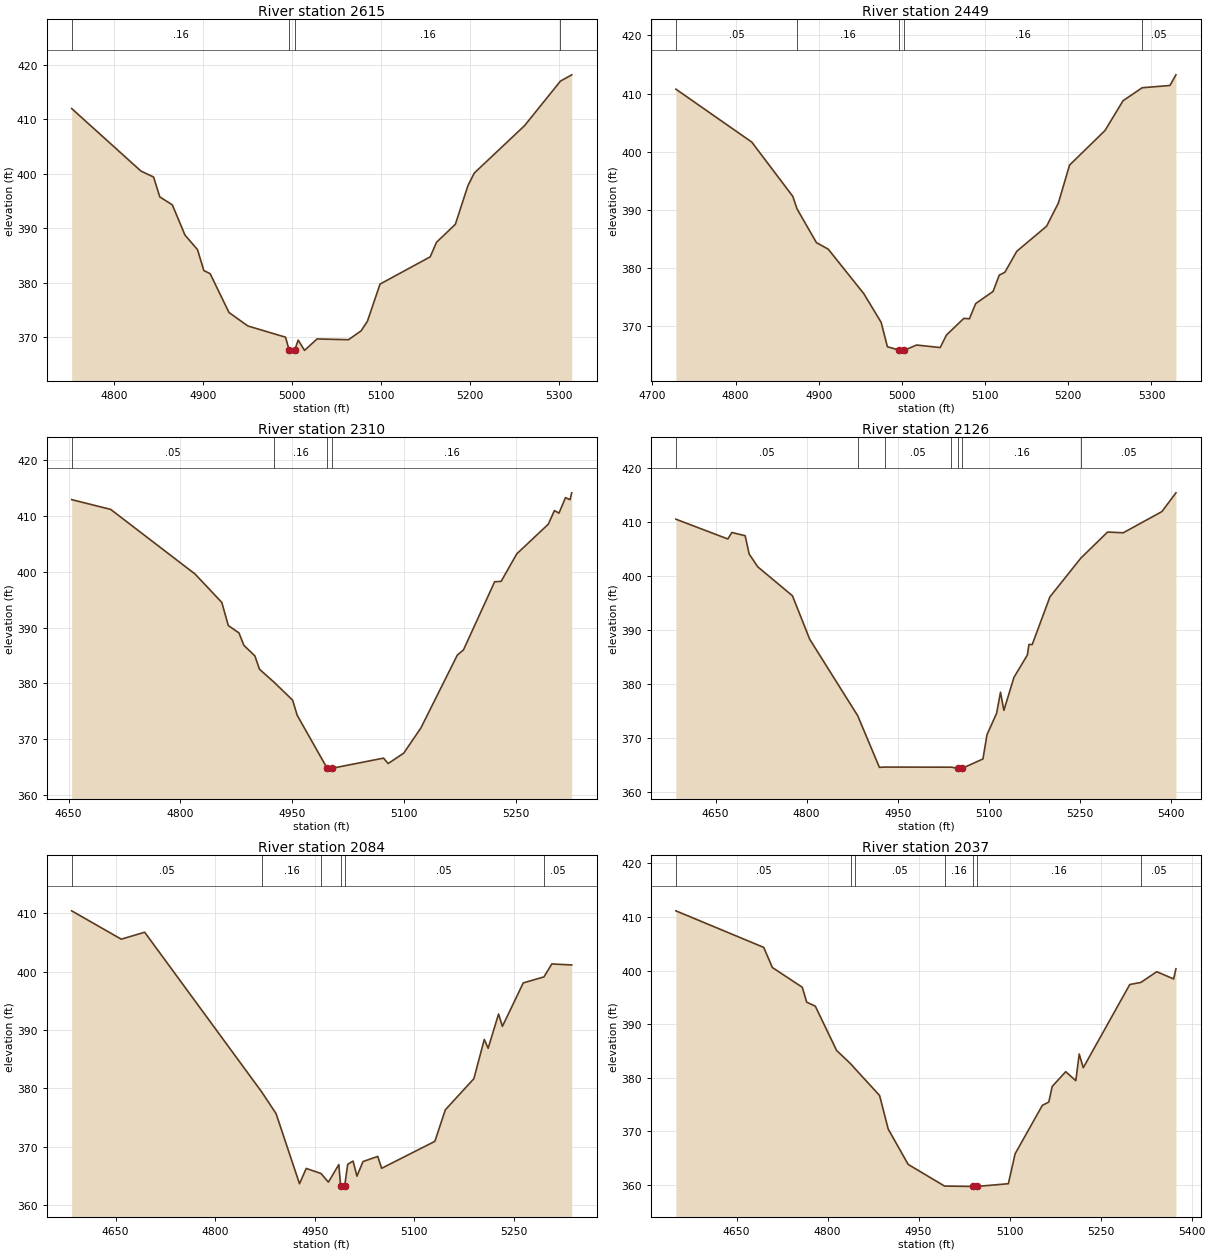
Type RM Length L Ch R = 1 ,2615    ,166,166,166
BEGIN DESCRIPTION:
UNT083 IN BECR 5.0
END DESCRIPTION:
XS GIS Cut Line= 2
      3789127.06     10547982.89      3788726.06     10547588.84
#Sta/Elev= 30
  4752.4  411.94  4830.3  400.47  4844.5  399.38  4851.5  395.73  4865.6  394.27
  4879.8  388.73  4893.9  386.06    4901  382.23  4908.1  381.65  4929.3  374.53
  4950.5  372.06  4992.9     370    4997  367.58  4999.8  367.08    5003  367.58
  5007.1  369.47  5014.2  367.58  5028.3  369.68  5063.6  369.54  5077.8  371.16
  5084.9  372.92  5099.1  379.74  5155.5  384.74  5162.6  387.41  5183.8  390.71
  5197.9  397.79  5205.1  400.11  5261.6   408.8  5301.9  416.96  5314.6  418.12
#Mann= 4 ,-1 , 0
  4752.4     .16       0    4997     .07       0    5003     .16       0
  5301.9     .05       0
Bank Sta=4997,5003
XS Rating Curve= 0 ,0
Exp/Cntr=0.3,0.1

Type RM Length L Ch R = 1 ,2449    ,139,139,139
BEGIN DESCRIPTION:
Mapping XS df8981c7
END DESCRIPTION:
XS GIS Cut Line= 2
      3789252.06     10547866.58      3788804.25     10547465.45
#Sta/Elev= 30
  4728.2  410.75  4819.5  401.65  4868.8  392.32  4873.9  390.17  4897.2  384.38
  4911.4  383.26  4954.1  375.62    4975  370.69  4982.5   366.5    4997   365.9
  4999.8   365.4    5003   365.9  5017.6  366.79    5046  366.36  5053.5  368.51
  5074.4  371.37  5081.1   371.3  5088.6  373.91  5109.5  375.99    5117   378.8
  5123.8   379.3    5138  382.89  5173.9   387.2    5188  391.17  5201.5   397.7
  5244.1  403.64  5265.8  408.76  5288.8  410.99  5322.2  411.38  5329.4  413.21
#Mann= 5 ,-1 , 0
  4728.2     .05       0  4873.9     .16       0    4997     .07       0
    5003     .16       0  5288.8     .05       0
Bank Sta=4997,5003
XS Rating Curve= 0 ,0
Exp/Cntr=0.3,0.1

Type RM Length L Ch R = 1 ,2310    ,184,184,184
BEGIN DESCRIPTION:
Mapping XS 346b24e9
END DESCRIPTION:
XS GIS Cut Line= 2
      3789413.51     10547778.03      3788863.89     10547393.12
#Sta/Elev= 30
  4654.1  412.92  4706.5  411.17  4819.8  399.58  4855.6   394.5  4864.3  390.36
  4878.6  389.04  4885.2  386.82    4900  384.92  4906.1  382.54  4925.7  380.21
  4950.6     377  4956.7   374.3    4997  364.78  4999.8  364.28    5003  364.78
  5072.6  366.61  5078.8  365.64  5099.7   367.5  5122.8  372.03  5171.6  385.06
  5179.9  386.01  5221.7  398.21  5230.4  398.28  5251.4  403.21  5293.7  408.52
  5301.9  410.96    5308   410.5  5316.8  413.28  5322.9  412.91  5325.1  414.14
#Mann= 4 ,-1 , 0
  4654.1     .05       0  4925.7     .16       0    4997     .07       0
    5003     .16       0
Bank Sta=4997,5003
XS Rating Curve= 0 ,0
Exp/Cntr=0.3,0.1

Type RM Length L Ch R = 1 ,2126    ,42,42,42
BEGIN DESCRIPTION:
Mapping XS 6c2a269c
END DESCRIPTION:
XS GIS Cut Line= 4
      3789482.76     10547707.39      3789266.64     10547460.02
      3789040.07     10547342.83      3788812.76     10547267.92
#Sta/Elev= 30
  4584.8  410.49  4670.3  406.83  4676.9  408.03  4698.8  407.43  4705.4  404.04
  4719.6  401.67  4776.6  396.32  4805.1  388.26    4884  374.13  4919.7  364.57
  4928.9  364.62  5038.1   364.6  5049.5  364.37  5052.3  363.87  5055.5  364.37
  5090.1  366.12  5096.8  370.62  5112.6  374.58    5119  378.47  5124.6  375.12
  5141.1  381.21  5163.2  385.36  5165.8   387.3  5171.2   387.3  5200.4  396.13
  5251.3   403.3  5295.2  408.11  5321.1  407.98  5384.6   411.9  5407.7  415.37
#Mann= 7 ,-1 , 0
  4584.8     .05       0    4884     .16       0  4928.9     .05       0
  5038.1     .16       0  5049.5    .033       0  5055.5     .16       0
  5251.3     .05       0
Bank Sta=5049.5,5055.5
XS Rating Curve= 0 ,0
Exp/Cntr=0.3,0.1

Type RM Length L Ch R = 1 ,2084    ,47,47,47
BEGIN DESCRIPTION:
UNT083 IN BECR 4.0
END DESCRIPTION:
XS GIS Cut Line= 3
      3789519.22     10547676.14      3789271.84     10547420.96
      3788928.07     10547220.42
#Sta/Elev= 30
  4583.9  410.43  4658.6  405.57  4693.9  406.76  4870.4  379.35  4891.9  375.65
  4927.2  363.63  4937.3  366.26  4959.6  365.39  4970.7  363.91  4986.4  366.92
  4989.2  363.21    4992  362.71  4995.2  363.21  4999.8  366.98  5007.9  367.52
  5013.7  364.93  5022.9  367.44  5045.1  368.32  5050.9  366.28  5131.1   370.9
  5146.9  376.31  5189.9  381.65  5205.6  388.38  5211.4  386.86  5227.1  392.74
  5232.9  390.62  5264.3  398.07  5295.5   399.1  5307.3  401.32  5337.3  401.15
#Mann= 6 ,-1 , 0
  4583.9     .05       0  4870.4     .16       0  4959.6     .05       0
  4989.2     .07       0  4995.2     .05       0  5295.5     .05       0
Bank Sta=4989.2,4995.2
XS Rating Curve= 0 ,0
Exp/Cntr=0.3,0.1

Type RM Length L Ch R = 1 ,2037    ,218,218,218
BEGIN DESCRIPTION:
Mapping XS 97626081
END DESCRIPTION:
XS GIS Cut Line= 4
      3789573.94     10547660.55       3789308.3     10547379.29
       3789183.3     10547329.81      3788913.53     10547192.33
#Sta/Elev= 30
    4550  411.13  4694.8  404.31    4709  400.56  4758.3  396.88  4765.6   394.1
  4779.8  393.35  4814.9  385.09  4838.2  382.59  4844.4   381.8  4885.7   376.7
  4899.9  370.45  4932.8  363.85  4992.8  359.81    5040  359.74  5042.8  359.24
    5046  359.74  5097.9  360.25  5109.1  365.84    5154  374.87  5164.6  375.47
  5170.2  378.39  5192.5  381.14  5209.1  379.46  5214.7  384.43  5221.4  381.88
    5298  397.39  5316.3  397.78  5342.5  399.78  5370.3  398.43  5374.1  400.32
#Mann= 7 ,-1 , 0
    4550     .05       0  4838.2     .16       0  4844.4     .05       0
  4992.8     .16       0    5040     .07       0    5046     .16       0
  5316.3     .05       0
Bank Sta=5040,5046
XS Rating Curve= 0 ,0
Exp/Cntr=0.3,0.1

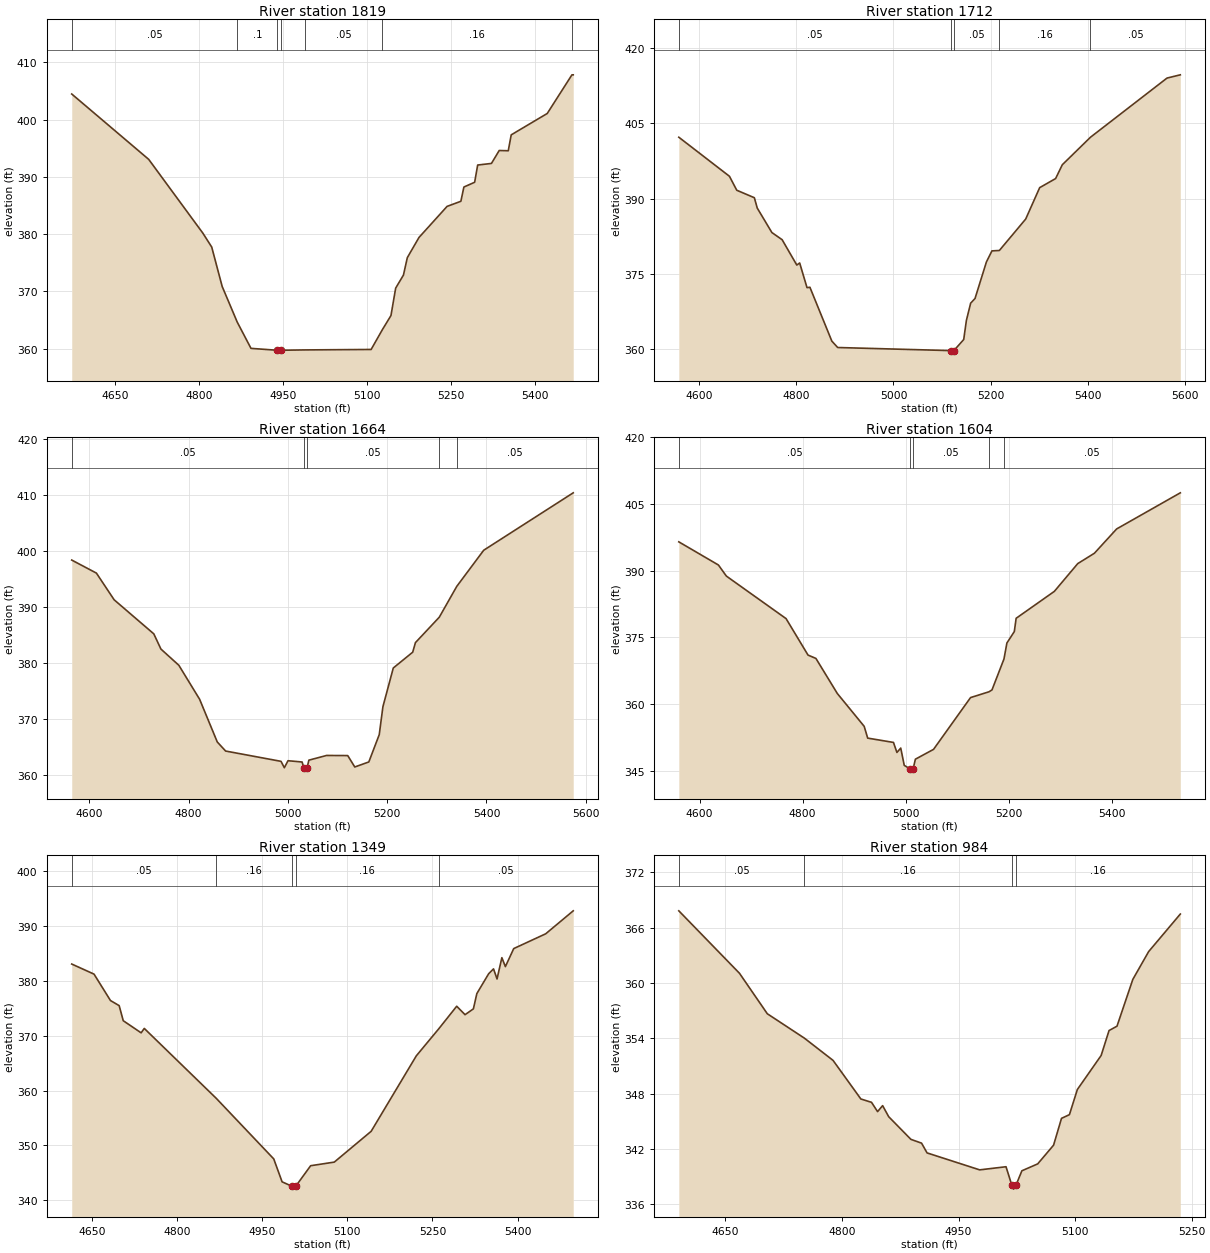
Type RM Length L Ch R = 1 ,1819    ,107,107,107
BEGIN DESCRIPTION:
Mapping XS b29d184c
END DESCRIPTION:
XS GIS Cut Line= 4
      3789610.38     10547538.14      3789477.57     10547303.77
      3789162.47     10547066.79      3788946.33     10546983.46
#Sta/Elev= 30
  4572.4  404.47  4709.8  393.06  4806.4  380.19  4822.3  377.75    4841  370.86
  4867.8  364.66  4892.4  360.06  4939.4  359.73  4942.2  359.23  4945.4  359.73
    4988  359.79  5106.9  359.87  5127.1  363.35  5142.3  365.79  5150.7  370.58
  5164.6  372.86  5171.5   375.9  5192.3  379.42  5242.5  384.85  5267.1  385.74
  5272.5  388.23  5291.7  389.06  5297.1  392.07  5321.7  392.35  5335.6  394.61
  5351.7  394.56    5357  397.34  5421.3  401.07  5465.4  407.82  5467.7  407.82
#Mann= 7 ,-1 , 0
  4572.4     .05       0  4867.8      .1       0  4939.4    .033       0
  4945.4      .1       0    4988     .05       0  5127.1     .16       0
  5465.4     .05       0
Bank Sta=4939.4,4945.4
XS Rating Curve= 0 ,0
Exp/Cntr=0.3,0.1

Type RM Length L Ch R = 1 ,1712    ,48,48,48
BEGIN DESCRIPTION:
Mapping XS c9f10719
END DESCRIPTION:
XS GIS Cut Line= 4
       3789691.1     10547483.44      3789506.22     10547202.21
      3789342.16     10547058.98      3788904.67     10546866.27
#Sta/Elev= 30
  4558.1  402.25  4662.3  394.46  4677.4  391.67  4713.6  390.18  4719.6  388.11
  4749.7  383.23  4770.8   381.8    4801  376.74  4806.9  377.16    4822  372.24
    4828  372.31  4873.1  361.57  4885.2  360.29  5118.3  359.67    5121  359.17
  5124.3  359.67  5144.6  361.88  5150.1  365.69  5158.9  369.14  5167.9  370.07
  5191.3  377.35  5202.7  379.57    5218  379.65  5272.2  385.92    5301  392.19
  5333.8     394  5347.6  396.76  5405.6  402.25  5563.1  414.05  5590.5   414.7
#Mann= 5 ,-1 , 0
  4558.1     .05       0  5118.3    .033       0  5124.3     .05       0
    5218     .16       0  5405.6     .05       0
Bank Sta=5118.3,5124.3
XS Rating Curve= 0 ,0
Exp/Cntr=0.3,0.1

Type RM Length L Ch R = 1 ,1664    ,60,60,60
BEGIN DESCRIPTION:
Mapping XS 4950556c
END DESCRIPTION:
XS GIS Cut Line= 4
      3789732.81     10547436.61      3789553.09     10547183.98
      3789297.89      10546949.6      3788975.04     10546804.97
#Sta/Elev= 30
  4564.5   398.4  4614.2  396.07  4649.9   391.3  4729.8  385.21  4744.2  382.49
  4780.3  379.59  4822.1  373.52  4857.7  365.88  4874.5  364.26  4986.1  362.42
  4992.8  361.28  5000.2  362.53  5028.6   362.3  5032.4  361.17  5035.1  360.67
  5038.4  361.17  5042.2  362.63  5077.9  363.47  5120.5  363.45  5134.7  361.41
    5163  362.31    5184  367.19  5191.4  372.19  5212.3  379.11  5251.4  381.93
  5256.9  383.64  5304.9  388.18  5340.2   393.7  5394.5  400.16  5574.8  410.42
#Mann= 5 ,-1 , 0
  4564.5     .05       0  5032.4     .03       0  5038.4     .05       0
  5304.9     .16       0  5340.2     .05       0
Bank Sta=5032.4,5038.4
XS Rating Curve= 0 ,0
Exp/Cntr=0.3,0.1

Type RM Length L Ch R = 1 ,1604    ,255,255,255
BEGIN DESCRIPTION:
Mapping XS 5c2ff57c
END DESCRIPTION:
XS GIS Cut Line= 5
      3789753.59     10547402.69      3789589.55      10547137.1
      3789443.72     10547004.29      3789329.14     10546913.14
      3789034.84     10546795.95
#Sta/Elev= 30
  4559.8  396.48  4636.6  391.28    4652  388.79  4767.8  379.23  4810.4  371.03
  4825.7  370.28  4867.2   362.4  4919.3  355.02  4926.1  352.37  4976.1   351.4
  4982.8  349.15  4990.2  350.13    4997  346.25  5008.2  345.45  5010.9  344.95
  5014.2  345.45  5018.6  347.63  5053.8  349.84  5125.6  361.48  5161.3  362.78
  5167.2  363.21  5190.4  370.15  5196.1  373.75  5210.5  376.32    5214   379.3
  5288.1  385.35  5333.5  391.59  5365.8  393.92  5408.9  399.38  5532.4   407.5
#Mann= 5 ,-1 , 0
  4559.8     .05       0  5008.2     .03       0  5014.2     .05       0
  5161.3     .16       0  5190.4     .05       0
Bank Sta=5008.2,5014.2
XS Rating Curve= 0 ,0
Exp/Cntr=0.3,0.1

Type RM Length L Ch R = 1 ,1349    ,365,365,365
BEGIN DESCRIPTION:
UNT083 IN BECR 3.0
END DESCRIPTION:
XS GIS Cut Line= 3
      3789842.18     10547230.89      3789709.34     10546973.04
      3789228.33     10546624.63
#Sta/Elev= 30
  4614.2   383.1  4653.5  381.26  4682.5  376.44  4697.8  375.51    4705  372.76
  4736.5  370.55  4742.1  371.35  4868.9   358.6  4970.3  347.54    4985  343.36
  5002.9  342.53  5005.6  342.03  5008.9  342.53  5035.3   346.3    5077  346.96
    5142  352.58  5221.6  366.35  5261.2  371.29  5292.8   375.4  5307.5  373.86
  5322.2  374.92  5328.3  377.71  5349.2  381.34  5357.7  382.22  5363.9  380.38
  5372.4  384.26  5378.6  382.63  5393.3  385.92  5449.7  388.62  5498.2  392.81
#Mann= 5 ,-1 , 0
  4614.2     .05       0  4868.9     .16       0  5002.9     .07       0
  5008.9     .16       0  5261.2     .05       0
Bank Sta=5002.9,5008.9
XS Rating Curve= 0 ,0
Exp/Cntr=0.3,0.1

Type RM Length L Ch R = 1 ,984     ,362,362,362
BEGIN DESCRIPTION:
UNT083 IN BECR 2.0
END DESCRIPTION:
XS GIS Cut Line= 3
      3789999.59     10546960.17      3789749.61     10546660.19
      3789499.65      10546610.2
#Sta/Elev= 30
    4590  367.84  4668.1  361.06  4703.9  356.67  4751.5  354.03  4788.5  351.61
  4824.3  347.42    4838  347.06  4845.8  346.05  4852.3   346.7  4860.1   345.5
  4888.7  343.04  4902.4  342.63  4909.5  341.57  4977.2  339.73  5011.1  340.07
  5018.3  338.14    5021  337.64  5024.3  338.14  5031.5  339.63  5051.9  340.38
  5072.3  342.41  5082.5  345.32  5092.7  345.72  5102.9  348.45  5133.5  352.14
  5143.7  354.85  5153.9  355.32  5174.3   360.4  5194.6  363.41  5235.4  367.49
#Mann= 4 ,-1 , 0
    4590     .05       0  4751.5     .16       0  5018.3     .07       0
  5024.3     .16       0
Bank Sta=5018.3,5024.3
XS Rating Curve= 0 ,0
Exp/Cntr=0.3,0.1

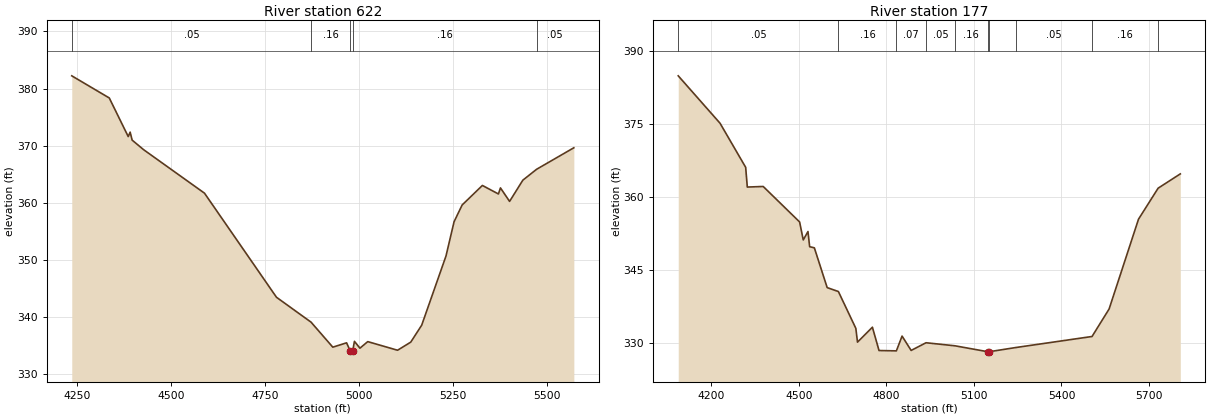
Type RM Length L Ch R = 1 ,622     ,445,445,445
BEGIN DESCRIPTION:
Mapping XS b6342b36
END DESCRIPTION:
XS GIS Cut Line= 4
      3790040.08     10547178.75      3790126.88      10546637.1
      3789915.07     10546352.38      3789513.43     10546193.11
#Sta/Elev= 30
  4236.5  382.23  4336.3  378.35  4386.7  371.59  4391.8  372.37  4397.1  370.97
  4427.5   369.3  4589.5  361.68    4781  343.45    4873  339.09  4930.8  334.71
  4967.5  335.47  4977.6  333.99  4980.4  333.49  4983.6  333.99  4988.4  335.73
    5003  334.53  5023.8  335.68  5103.1  334.17  5138.2  335.59  5167.3  338.56
  5231.9  350.67  5253.4  356.67  5274.9  359.61  5328.7  363.03  5371.4  361.54
  5376.8   362.6  5401.1  360.24  5436.3  363.95  5472.9  365.86    5572  369.63
#Mann= 5 ,-1 , 0
  4236.5     .05       0    4873     .16       0  4977.6     .07       0
  4983.6     .16       0  5472.9     .05       0
Bank Sta=4977.6,4983.6
XS Rating Curve= 0 ,0
Exp/Cntr=0.3,0.1

Type RM Length L Ch R = 1 ,177     ,0,0,0
BEGIN DESCRIPTION:
UNT083 IN BECR 1.0
END DESCRIPTION:
XS GIS Cut Line= 4
      3790064.38     10547216.96      3790428.96     10546536.41
      3790390.77     10546258.63      3789727.57     10546171.82
#Sta/Elev= 30
  4086.2  384.89  4229.6  375.13  4317.4  366.06    4323     362  4377.5  362.12
  4502.3  354.82  4514.8  351.12    4531  352.85  4536.7  349.73  4552.9  349.49
  4596.8  341.31  4635.3   340.5  4695.1  332.92  4700.8  330.09  4751.9  333.16
  4774.6  328.36  4834.1  328.29  4853.6  331.33  4884.7  328.38  4935.8  329.96
  5035.3  329.33  5146.9  328.12  5149.6  327.62  5152.9  328.12  5242.6  328.97
  5504.9  331.25  5563.4  336.91  5664.2  355.39  5731.5  361.77  5807.5  364.71
#Mann= 10 ,-1 , 0
  4086.2     .05       0  4635.3     .16       0  4834.1     .07       0
  4935.8     .05       0  5035.3     .16       0  5146.9     .03       0
  5152.9     .16       0  5242.6     .05       0  5504.9     .16       0
  5731.5     .05       0
Bank Sta=5146.9,5152.9
XS Rating Curve= 0 ,0
Exp/Cntr=0.3,0.1

Chan Stop Cuts=-1
Use User Specified Reach Order=0
Composite Channel Slope=5