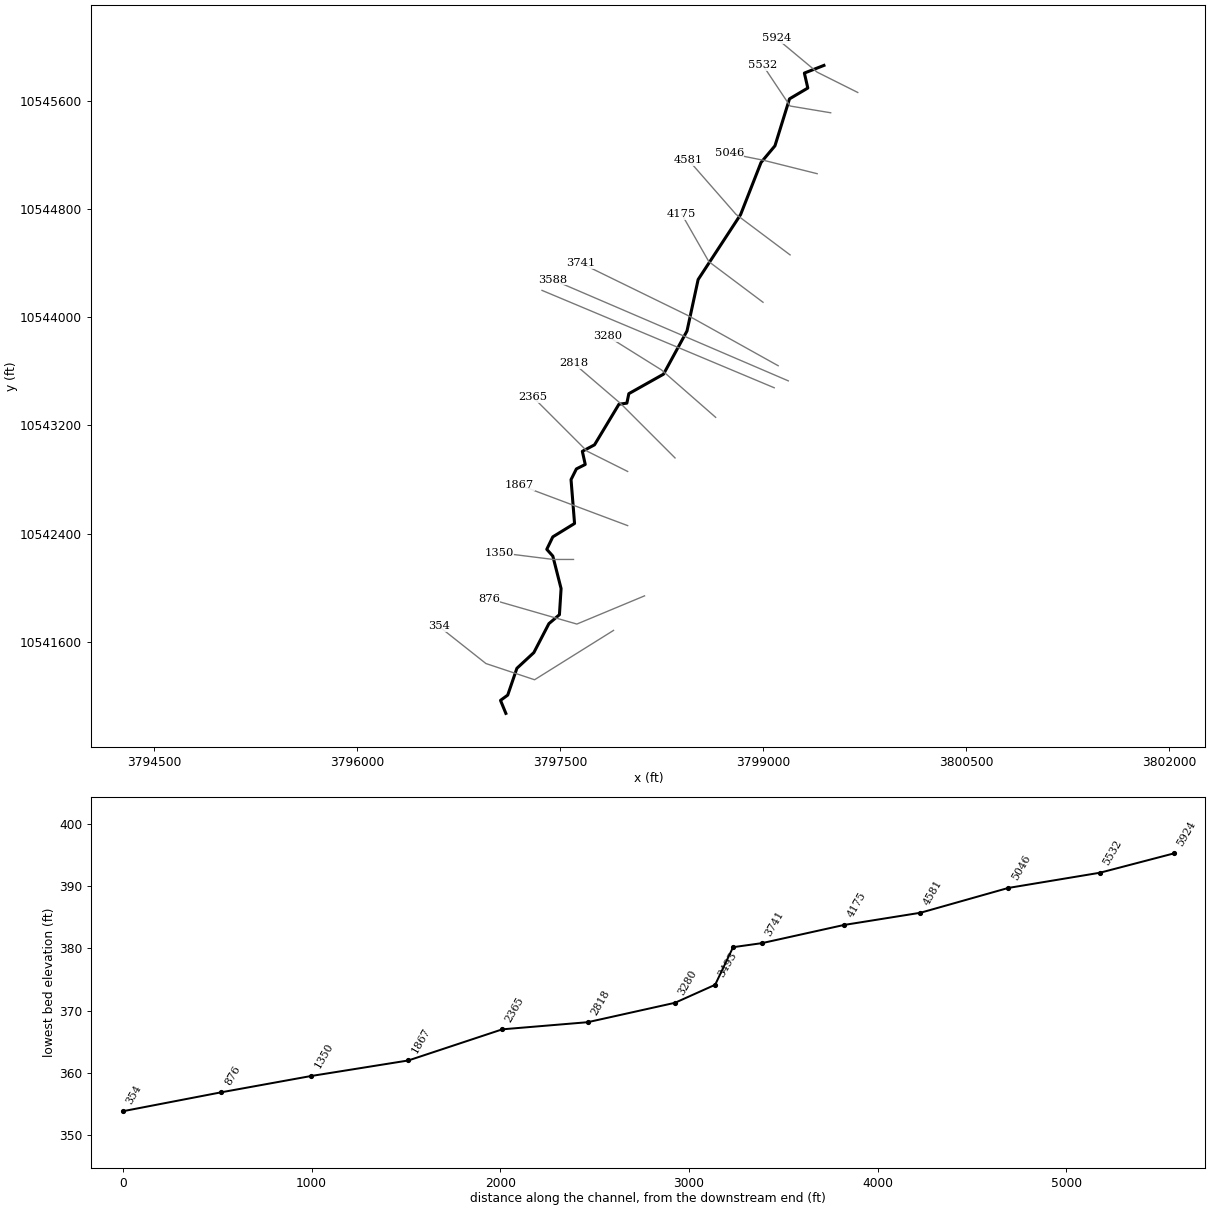
--- UNT085 IN BECR.prj (project) ---

Proj Title=UNT085 IN BECR Base Level Engineering
Current Plan=p01
Default Exp/Contr=0.3,0.1
English Units
Geom File=g01
Flow File=f01
Plan File=p01
Y Axis Title=Elevation
X Axis Title(PF)=Main Channel Distance
X Axis Title(XS)=Station
BEGIN DESCRIPTION:
UNT085 IN BECR
END DESCRIPTION:
DSS Export Rating Curves= 0
DSS Export Rating Curve Sorted= 0
DSS Export Volume Flow Curves= 0
DXF OffsetX= 0
DXF OffsetY= 0
DXF ScaleX= 1
DXF ScaleY= 10

--- UNT085 IN BECR.p01 (plan) ---

Plan Title=Multiple Run
Short Identifier=Multiple
Geom File=g01
Flow File=f01
Subcritical Flow
K Sum by GR= 0
Std Step Tol= 0.01
Critical Tol= 0.01
Num of Std Step Trials= 20
Max Error Tol= 0.3
Flow Tol Ratio= 0.001
Split Flow NTrial= 30
Split Flow Tol= 0.02
Split Flow Ratio= 0.02
Log Output Level= 0
Friction Slope Method= 1
Unsteady Friction Slope Method= 2
Unsteady Bridges Friction Slope Method= 1
Parabolic Critical Depth
Global Vel Dist=  1 , 1 , 1
Global Log Level= 0
CheckData=True
Encroach Param= -1, 0, 0, 0
BEGIN DESCRIPTION:
Multiple Run
END DESCRIPTION:

--- UNT085 IN BECR.f01 (steady flow) ---

Flow Title=Multiple
Program Version=4.10
Number of Profiles= 7
Profile Names=10-year,25-year,50-year,1pct_min,100-year,1pct_plu,500-year
River Rch & RM=UNT085 IN BECR,Reach-1         ,5924
     601     814     991     887    1199    1621    1761
River Rch & RM=UNT085 IN BECR,Reach-1         ,5046
     814    1118    1374    1240    1677    2268    2507
Boundary for River Rch & Prof#=UNT085 IN BECR,Reach-1         , 1
Up Type= 0
Dn Type= 3
Dn Slope=0.0066
Boundary for River Rch & Prof#=UNT085 IN BECR,Reach-1         , 2
Up Type= 0
Dn Type= 3
Dn Slope=0.0066
Boundary for River Rch & Prof#=UNT085 IN BECR,Reach-1         , 3
Up Type= 0
Dn Type= 3
Dn Slope=0.0066
Boundary for River Rch & Prof#=UNT085 IN BECR,Reach-1         , 4
Up Type= 0
Dn Type= 3
Dn Slope=0.0066
Boundary for River Rch & Prof#=UNT085 IN BECR,Reach-1         , 5
Up Type= 0
Dn Type= 3
Dn Slope=0.0066
Boundary for River Rch & Prof#=UNT085 IN BECR,Reach-1         , 6
Up Type= 0
Dn Type= 3
Dn Slope=0.0066
Boundary for River Rch & Prof#=UNT085 IN BECR,Reach-1         , 7
Up Type= 0
Dn Type= 3
Dn Slope=0.0066
DSS Import GetInterval= 0
DSS Import GetPeak= 0
DSS Import FillOption= 0

--- UNT085 IN BECR.g01 (geometry) ---

Geom Title=Existing Conditions
Program Version=4.10

River Reach=UNT085 IN BECR  ,Reach-1
Reach XY= 30
      3799449.61     10545860.19      3799305.09     10545803.54
       3799330.5       10545693.      3799195.25       10545613.
      3799087.75       10545266.        3798985.       10545143.
        3798834.       10544758.      3798520.25       10544278.
        3798438.       10543898.       3798264.5       10543579.
      3798008.25       10543435.      3797993.75       10543365.
      3797935.25       10543357.      3797754.75       10543057.
      3797664.75       10543009.      3797686.25       10542912.
      3797620.75       10542879.      3797581.25       10542800.
      3797607.25       10542476.       3797446.5       10542377.
        3797402.       10542285.      3797446.75       10542235.
      3797507.75       10541995.       3797495.5       10541802.
      3797417.75       10541736.       3797306.5       10541522.
      3797181.25       10541406.       3797113.5       10541208.
      3797060.25       10541169.      3797099.75       10541073.

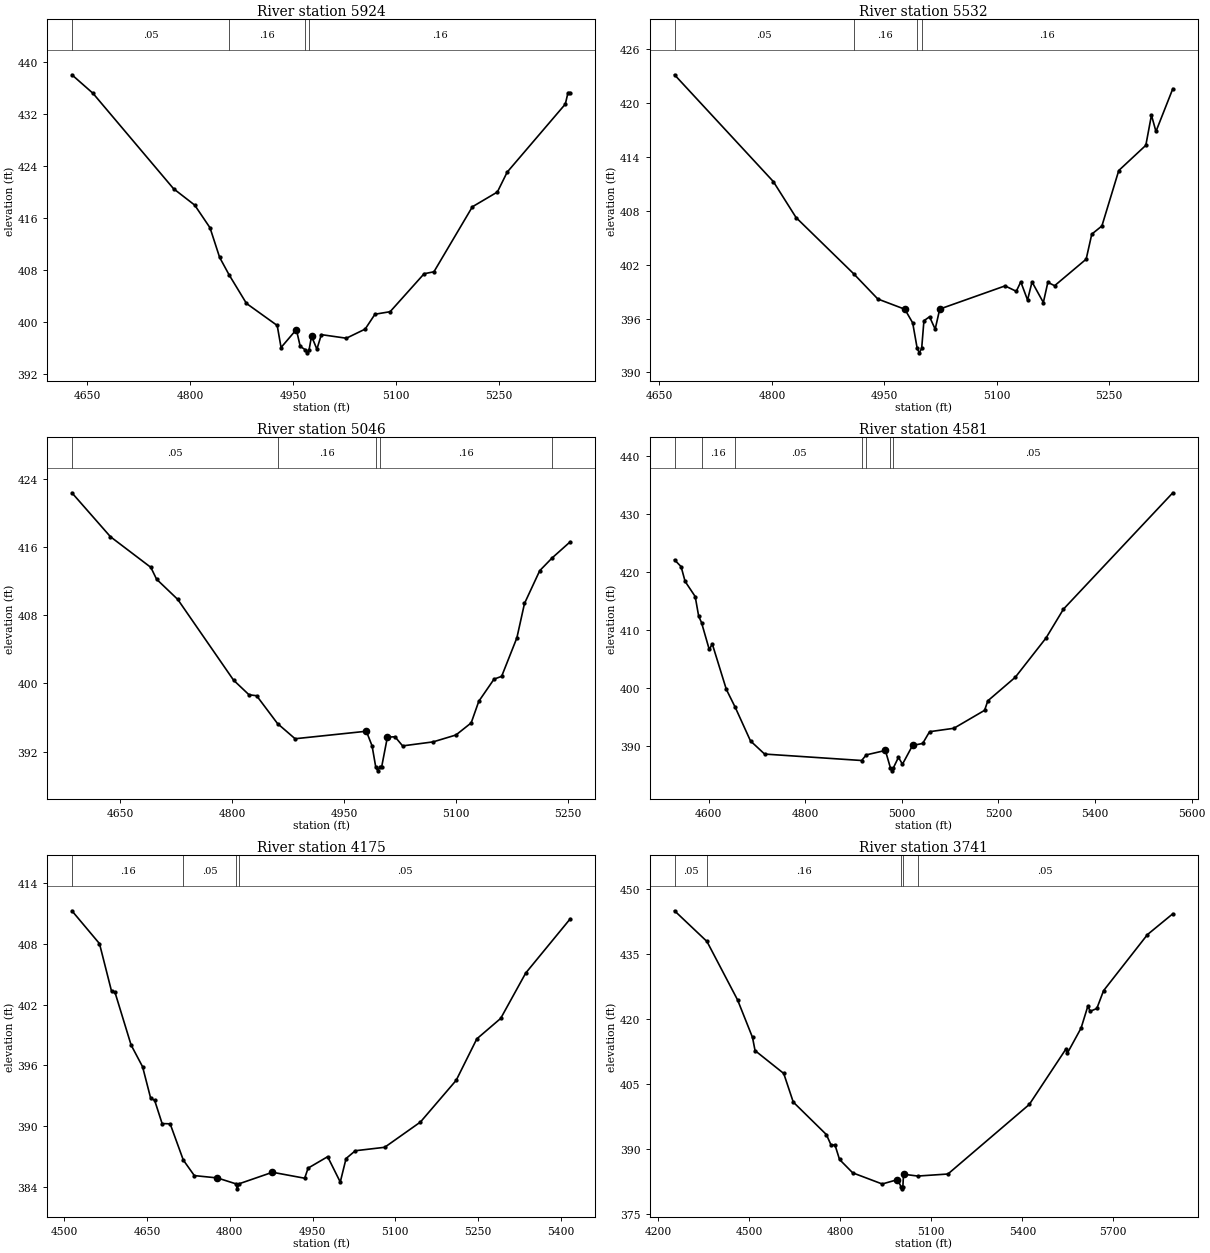
Type RM Length L Ch R = 1 ,5924    ,392,392,392
BEGIN DESCRIPTION:
UNT085 IN BECR 12.0
END DESCRIPTION:
XS GIS Cut Line= 3
      3799699.61     10545660.19      3799399.61     10545810.19
      3799099.62     10546060.18
#Sta/Elev= 30
  4627.5  438.08  4658.2  435.23  4775.6  420.55  4806.4  418.03  4828.7  414.54
  4842.7  409.99  4856.4  407.32  4881.8   402.9  4926.6  399.51  4932.2  396.12
  4954.5  398.88  4960.1   396.3  4967.1   395.8  4969.8   395.3  4973.1   395.8
  4976.6  397.87  4984.4  395.86  4990.9   398.1  5027.3  397.55  5054.7  398.95
    5069  401.24  5091.1  401.63  5140.6  407.47  5154.9  407.77  5210.9  417.77
  5247.3  420.04  5261.6   423.1  5346.3  433.57  5350.2  435.33  5353.4  435.33
#Mann= 4 ,-1 , 0
  4627.5     .05       0  4856.4     .16       0  4967.1     .07       0
  4973.1     .16       0
Bank Sta=4954.5,4976.6
XS Rating Curve= 0 ,0
Exp/Cntr=0.3,0.1

Type RM Length L Ch R = 1 ,5532    ,486,486,486
BEGIN DESCRIPTION:
UNT085 IN BECR 11.0
END DESCRIPTION:
XS GIS Cut Line= 3
      3799499.64     10545510.18      3799199.61     10545560.19
      3798999.63     10545860.16
#Sta/Elev= 30
  4670.1  423.18  4801.9  411.28  4832.3  407.26    4909  401.01  4941.3  398.19
  4977.3  397.05  4987.8  395.53  4993.8  392.69  4996.6  392.19  4999.8  392.69
  5002.8  395.77  5010.3  396.21  5017.8  394.83  5023.9  397.07    5111  399.65
    5126  399.05    5132   400.1    5141  398.08    5147  400.09  5162.1   397.8
  5168.1  400.05  5177.1  399.67  5219.2  402.63  5226.7  405.42  5240.2  406.33
  5262.7  412.51  5298.8  415.32  5306.3  418.68  5312.3  416.86  5334.8  421.63
#Mann= 4 ,-1 , 0
  4670.1     .05       0    4909     .16       0  4993.8     .07       0
  4999.8     .16       0
Bank Sta=4977.3,5023.9
XS Rating Curve= 0 ,0
Exp/Cntr=0.3,0.1

Type RM Length L Ch R = 1 ,5046    ,465,465,465
BEGIN DESCRIPTION:
UNT085 IN BECR 10.0
END DESCRIPTION:
XS GIS Cut Line= 3
      3799399.63     10545060.18      3798999.61     10545160.19
      3798749.59     10545210.19
#Sta/Elev= 30
  4585.7   422.4  4637.3  417.24  4691.4  413.64  4699.1  412.25  4727.5  409.87
  4802.2  400.39  4822.8  398.68  4833.1  398.56  4861.1  395.29  4884.6  393.51
    4980  394.39  4987.7  392.67  4992.5  390.24  4995.2  389.74  4998.5  390.24
  5000.6  390.24  5008.2   393.7  5018.4  393.74  5028.6  392.67  5069.4  393.14
    5100  393.95  5120.4  395.37  5130.6  397.91    5151  400.51  5161.2  400.84
  5181.6  405.36  5191.8   409.4  5212.2  413.25  5228.7  414.74    5253  416.64
#Mann= 5 ,-1 , 0
  4585.7     .05       0  4861.1     .16       0  4992.5     .07       0
  4998.5     .16       0  5228.7     .05       0
Bank Sta=4980,5008.2
XS Rating Curve= 0 ,0
Exp/Cntr=0.3,0.1

Type RM Length L Ch R = 1 ,4581    ,406,406,406
BEGIN DESCRIPTION:
UNT085 IN BECR 9.0
END DESCRIPTION:
XS GIS Cut Line= 3
      3799199.65     10544460.16      3798799.61     10544760.19
      3798449.58     10545160.22
#Sta/Elev= 30
  4529.4  422.09    4543  420.92  4551.3  418.38  4572.2  415.77  4579.4  412.39
  4585.3  411.29  4601.3  406.65  4607.6   407.6  4636.7  399.77  4655.2  396.67
  4686.7   390.9  4715.9  388.64  4916.8  387.53  4926.4   388.5  4965.9  389.26
  4976.4  386.25  4979.2  385.75  4982.4  386.25    4993  388.08  5001.3  386.89
  5022.2  390.12  5043.2  390.47  5057.4  392.49  5107.7  393.08  5171.3  396.17
    5178  397.81  5234.9  401.87  5298.5  408.63  5334.6   413.6    5561  433.64
#Mann= 7 ,-1 , 0
  4529.4     .05       0  4585.3     .16       0  4655.2     .05       0
  4916.8     .16       0  4926.4     .05       0  4976.4     .03       0
  4982.4     .05       0
Bank Sta=4965.9,5022.2
XS Rating Curve= 0 ,0
Exp/Cntr=0.3,0.1

Type RM Length L Ch R = 1 ,4175    ,434,434,434
BEGIN DESCRIPTION:
UNT085 IN BECR 8.0
END DESCRIPTION:
XS GIS Cut Line= 3
      3798999.59      10544110.2      3798599.61     10544410.19
      3798399.61     10544760.19
#Sta/Elev= 30
  4513.9  411.29  4563.9  408.04  4585.8  403.32    4592  403.22  4621.2  398.01
    4642  395.86  4656.6  392.76  4663.9  392.53  4677.4  390.24    4692  390.21
  4715.8  386.63  4735.8  385.09  4777.4  384.86  4810.9  384.28  4813.6  383.78
  4816.9  384.28  4877.4  385.42  4935.8  384.83    4942  385.83  4977.4  386.96
  5000.3  384.45  5010.8  386.78  5027.6  387.55  5080.8  387.89  5145.6  390.39
  5210.4  394.52  5247.8  398.62    5291  400.64  5336.4  405.13    5417  410.49
#Mann= 4 ,-1 , 0
  4513.9     .16       0  4715.8     .05       0  4810.9     .03       0
  4816.9     .05       0
Bank Sta=4777.4,4877.4
XS Rating Curve= 0 ,0
Exp/Cntr=0.3,0.1

Type RM Length L Ch R = 1 ,3741    ,153,153,153
BEGIN DESCRIPTION:
UNT085 IN BECR 7.0
END DESCRIPTION:
XS GIS Cut Line= 3
      3799111.56      10543641.4      3798449.61     10544010.19
       3797654.5     10544398.69
#Sta/Elev= 30
  4253.3  445.01  4360.2  437.93  4461.2  424.44  4510.4  415.79  4518.8  412.75
  4613.3  407.48  4644.7  400.88  4753.9  393.38  4769.8  390.89  4782.1  391.02
  4797.3  387.63  4840.7  384.55  4937.9  381.98  4988.2  382.98  5000.1  381.36
  5002.8  380.86  5006.1  381.36  5008.2  384.23  5055.3  383.81  5154.6  384.28
  5422.9  400.33    5543  413.05  5548.6  412.19  5593.6  417.95  5616.2  423.08
  5623.2  421.81  5645.5  422.47  5667.7  426.58  5812.4  439.52    5896  444.32
#Mann= 5 ,-1 , 0
  4253.3     .05       0  4360.2     .16       0  5000.1     .07       0
  5006.1     .16       0  5055.3     .05       0
Bank Sta=4988.2,5008.2
XS Rating Curve= 0 ,0
Exp/Cntr=0.3,0.1

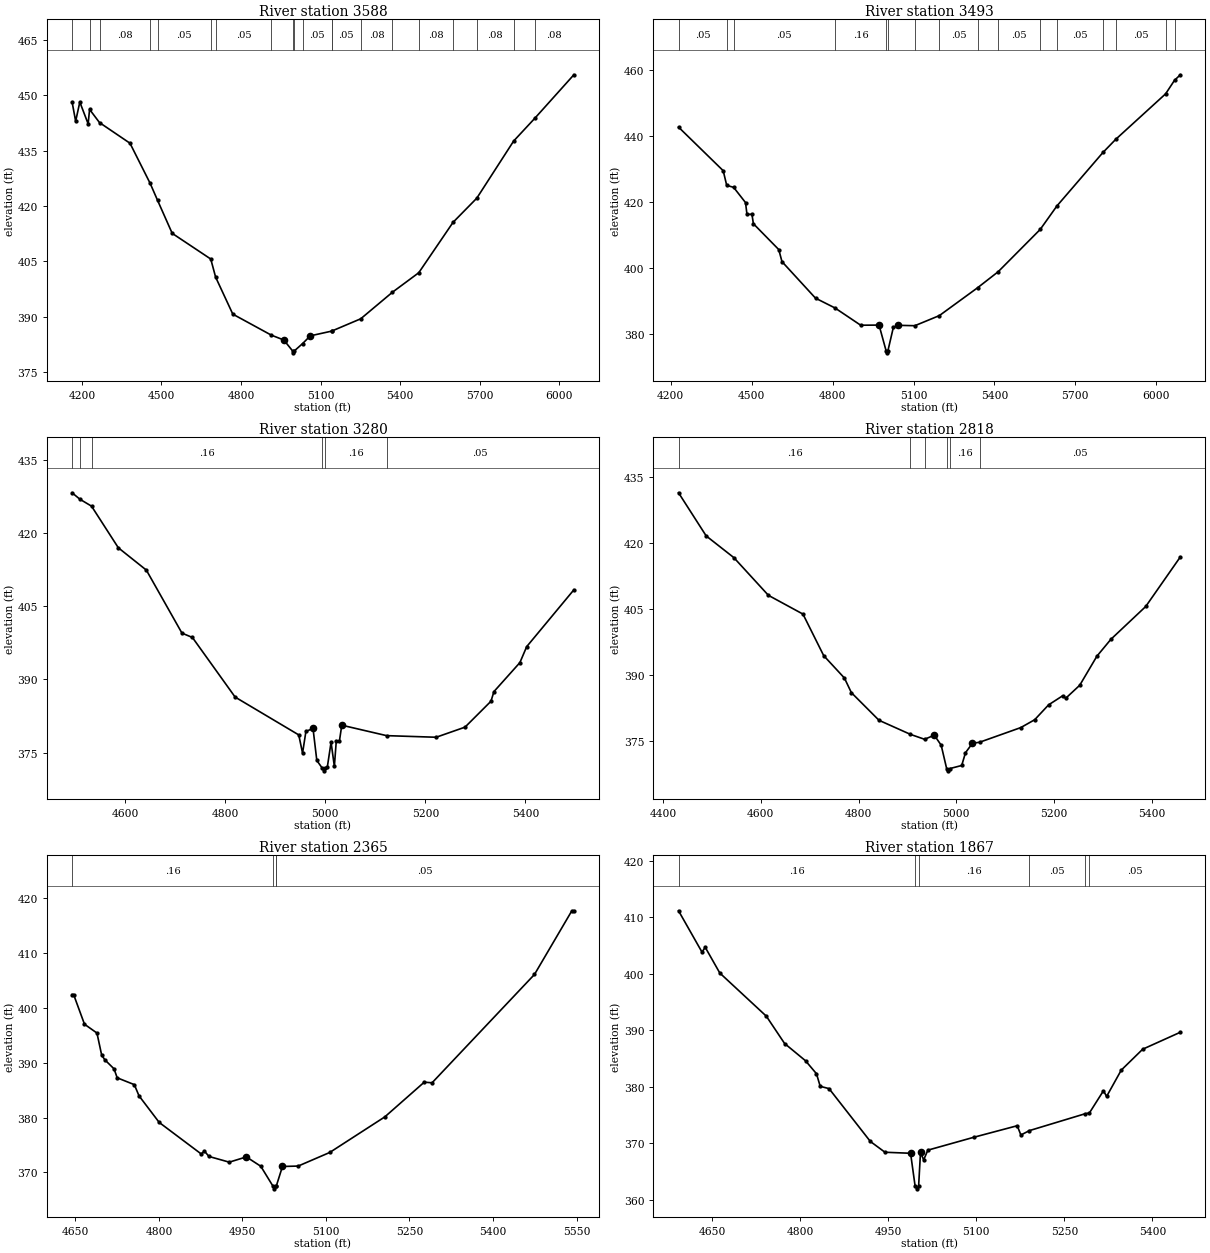
Type RM Length L Ch R = 1 ,3588    ,95,95,95
BEGIN DESCRIPTION:
Mapping XS 95beb2bf
END DESCRIPTION:
XS GIS Cut Line= 2
      3799186.47     10543529.62      3797448.21     10544275.67
#Sta/Elev= 30
  4162.9  448.27  4176.4  443.01  4192.1  448.21  4223.5   442.3  4228.9  446.22
  4266.4  442.64  4381.2  437.05  4457.3  426.16  4485.2  421.56  4540.4  412.61
  4685.7  405.65    4704  400.75  4768.9   390.7    4914  385.01  4961.2  383.69
  4994.4  380.71  4997.2  380.21  5000.4  380.71  5032.2  382.74  5060.9  384.82
  5141.6   386.1  5142.4  386.13    5251  389.44  5370.8  396.66  5469.8  401.93
  5599.1   415.6  5688.6  422.15  5827.5  437.64  5907.4  443.82  6054.5  455.61
#Mann= 20 ,-1 , 0
  4162.9     .08       0  4228.9     .05       0  4266.4     .08       0
  4457.3     .16       0  4485.2     .05       0  4685.7     .16       0
    4704     .05       0    4914     .16       0  4994.4     .07       0
  5000.4     .16       0  5032.2     .05       0  5141.6     .08       0
  5142.4     .05       0    5251     .08       0  5370.8     .05       0
  5469.8     .08       0  5599.1     .05       0  5688.6     .08       0
  5827.5      .1       0  5907.4     .08       0
Bank Sta=4961.2,5060.9
XS Rating Curve= 0 ,0
Exp/Cntr=0.3,0.1

Type RM Length L Ch R = 1 ,3493    ,213,213,213
BEGIN DESCRIPTION:
Mapping XS 82fc5f4d
END DESCRIPTION:
XS GIS Cut Line= 2
      3799082.34      10543478.6      3797366.78     10544198.03
#Sta/Elev= 30
  4228.8  442.56  4394.4  429.35  4407.4  424.91    4433  424.31  4477.1   419.7
  4482.6   416.1  4500.9  416.16  4506.3  413.29  4600.4  405.45  4612.3   401.8
  4736.6  390.73  4808.6  387.77  4904.1  382.53  4972.2  382.57  4998.7  374.66
  5001.4  374.16  5004.7  374.66  5025.2  381.88  5043.5   382.5  5104.8  382.38
  5195.7  385.44  5337.3  393.87  5413.7  398.73  5569.7  411.56  5631.6  418.67
  5802.2  434.87  5849.5  438.85  6034.6  452.65  6067.5  456.74  6089.1  458.42
#Mann= 16 ,-1 , 0
  4228.8     .05       0  4407.4     .08       0    4433     .05       0
  4808.6     .16       0  4998.7     .07       0  5004.7     .16       0
  5104.8     .08       0  5195.7     .05       0  5337.3     .08       0
  5413.7     .05       0  5569.7     .08       0  5631.6     .05       0
  5802.2     .08       0  5849.5     .05       0  6034.6     .08       0
  6067.5     .05       0
Bank Sta=4972.2,5043.5
XS Rating Curve= 0 ,0
Exp/Cntr=0.3,0.1

Type RM Length L Ch R = 1 ,3280    ,462,462,462
BEGIN DESCRIPTION:
UNT085 IN BECR 6.0
END DESCRIPTION:
XS GIS Cut Line= 3
      3798649.62     10543260.18      3798249.61     10543610.19
      3797849.62     10543860.18
#Sta/Elev= 30
  4493.6  428.22  4509.4  426.89  4532.5  425.48  4586.1  416.95  4642.1  412.38
  4713.3  399.47  4734.2  398.58  4819.6  386.37  4946.8  378.62  4954.4  374.89
  4961.1  379.32  4975.3  379.96  4982.9  373.39  4994.1  371.76  4996.9  371.26
  5000.1  371.76  5003.8  371.95  5011.4  377.12    5018  372.17  5021.8  377.36
  5028.1  377.36  5032.8  380.61  5122.4  378.47  5221.5  378.14  5279.2  380.21
  5331.1  385.52    5337  387.49  5388.9  393.43  5402.5   396.7  5496.8  408.34
#Mann= 6 ,-1 , 0
  4493.6     .16       0  4509.4     .05       0  4532.5     .16       0
  4994.1     .07       0  5000.1     .16       0  5122.4     .05       0
Bank Sta=4975.3,5032.8
XS Rating Curve= 0 ,0
Exp/Cntr=0.3,0.1

Type RM Length L Ch R = 1 ,2818    ,453,453,453
BEGIN DESCRIPTION:
UNT085 IN BECR 5.0
END DESCRIPTION:
XS GIS Cut Line= 3
      3798349.64     10542960.16      3797949.61     10543360.19
      3797599.61     10543660.19
#Sta/Elev= 30
  4431.6  431.42  4488.2   421.6  4544.8  416.66  4615.5  408.08  4686.2  403.81
  4728.6  394.36    4771  389.26  4785.2  385.94  4841.8  379.64  4906.1  376.44
    4935  375.32  4954.9  376.25    4969  373.97  4980.2  368.64  4982.9  368.14
  4986.2  368.64    5011  369.36  5018.7  372.26    5033  374.42  5047.4  374.64
  5131.8  377.98  5160.3  379.77  5188.8  383.16  5217.4  385.21    5224  384.67
  5252.5  387.62  5287.6  394.23  5316.2  398.07  5387.5  405.54  5458.3  416.82
#Mann= 6 ,-1 , 0
  4431.6     .16       0  4906.1     .05       0    4935     .16       0
  4980.2     .07       0  4986.2     .16       0  5047.4     .05       0
Bank Sta=4954.9,5033
XS Rating Curve= 0 ,0
Exp/Cntr=0.3,0.1

Type RM Length L Ch R = 1 ,2365    ,498,498,498
BEGIN DESCRIPTION:
UNT085 IN BECR 4.0
END DESCRIPTION:
XS GIS Cut Line= 3
      3797999.59      10542860.2      3797699.61     10543010.19
      3797299.59      10543410.2
#Sta/Elev= 30
  4644.1  402.45  4646.9  402.45  4666.4  397.04  4688.8  395.43  4697.2  391.43
  4702.8  390.56  4719.5  388.89  4725.1  387.26  4755.9  386.01  4764.3  383.97
  4800.6  379.11  4876.1  373.35  4881.7  373.89    4890   372.9  4926.4  371.86
  4957.1  372.82    4983  371.11  5004.8  367.49  5007.5  366.99  5010.8  367.49
  5010.9  367.52  5021.9  371.07  5050.2  371.15  5106.8  373.63  5205.8  380.13
  5276.5  386.46  5290.6  386.35  5474.5  406.13  5541.6  417.75  5545.2  417.75
#Mann= 4 ,-1 , 0
  4644.1     .16       0  5004.8     .07       0  5010.8     .16       0
  5010.9     .05       0
Bank Sta=4957.1,5021.9
XS Rating Curve= 0 ,0
Exp/Cntr=0.3,0.1

Type RM Length L Ch R = 1 ,1867    ,517,517,517
BEGIN DESCRIPTION:
UNT085 IN BECR 3.0
END DESCRIPTION:
XS GIS Cut Line= 3
      3797999.59      10542460.2      3797599.61     10542610.19
      3797199.59      10542760.2
#Sta/Elev= 30
    4593  411.15    4633  403.83  4638.4   404.7  4663.3  400.14  4742.5  392.51
  4773.6  387.68  4809.2  384.63  4827.9  382.33  4834.2  380.11  4849.3   379.7
  4919.6  370.36  4944.5  368.45  4988.1  368.27  4995.8  362.48  4998.6  361.98
  5001.8  362.48    5005  368.43  5010.4   367.1  5017.5  368.82  5095.8   371.1
  5169.7  373.14  5175.9   371.5  5190.5  372.28  5284.4  375.23  5292.6   375.4
  5316.5  379.32  5321.9  378.32  5346.8  382.97  5383.3  386.67  5447.4  389.67
#Mann= 6 ,-1 , 0
    4593     .16       0  4995.8     .07       0  5001.8     .16       0
  5190.5     .05       0  5284.4     .16       0  5292.6     .05       0
Bank Sta=4988.1,5005
XS Rating Curve= 0 ,0
Exp/Cntr=0.3,0.1

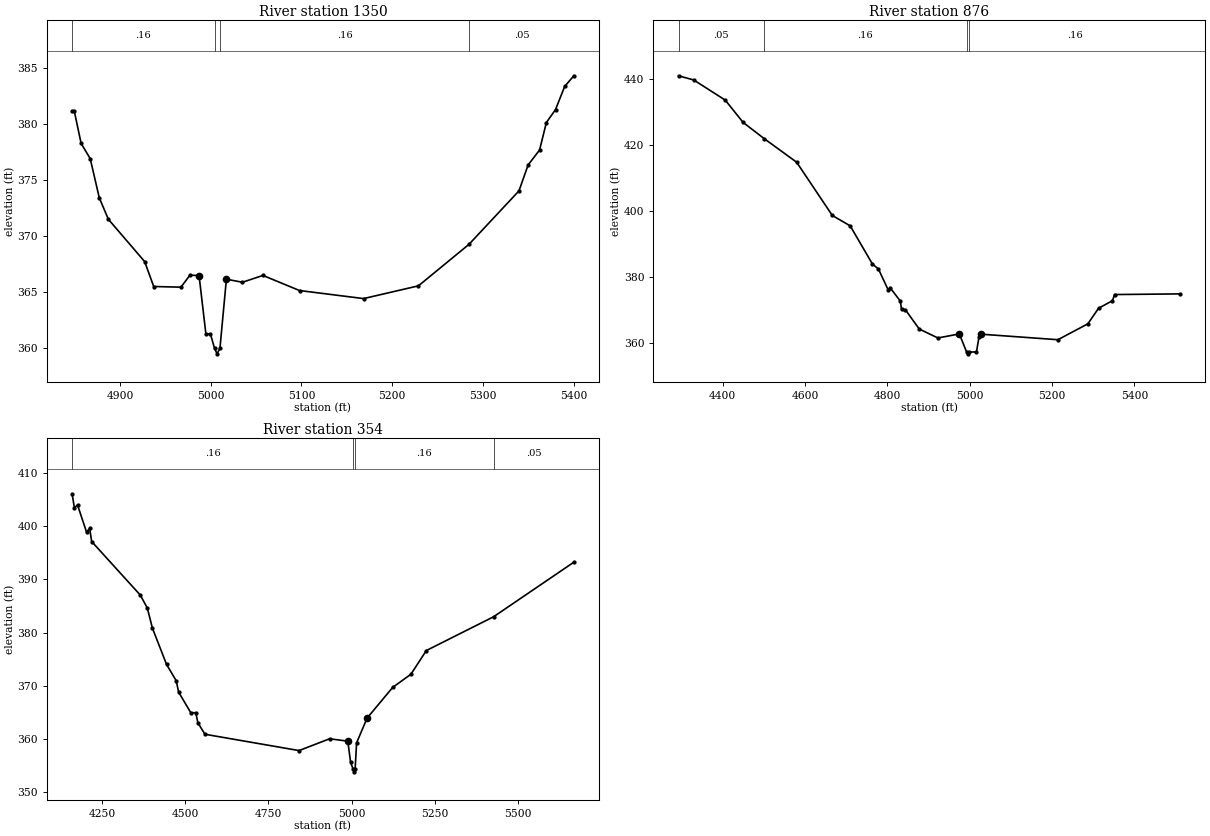
Type RM Length L Ch R = 1 ,1350    ,474,474,474
BEGIN DESCRIPTION:
UNT085 IN BECR 2.0
END DESCRIPTION:
XS GIS Cut Line= 3
      3797599.58     10542210.19      3797449.61     10542210.19
      3797049.59     10542260.19
#Sta/Elev= 30
  4847.2  381.15  4849.7  381.15  4857.2  378.28  4867.2  376.92  4877.2  373.42
  4887.2   371.5  4927.2  367.72  4937.2  365.49  4967.2  365.43  4977.2  366.51
  4987.2  366.46  4994.7  361.25  4999.7  361.25  5004.2  359.97    5007  359.47
  5010.2  359.97  5017.3  366.14    5035  365.87  5057.6  366.48  5097.9  365.13
  5168.5  364.41    5229  365.55  5284.7  369.26  5339.8  374.04  5349.9  376.36
  5362.5  377.69    5370  380.15  5380.1  381.31  5390.2  383.38  5400.3  384.33
#Mann= 4 ,-1 , 0
  4847.2     .16       0  5004.2     .07       0  5010.2     .16       0
  5284.7     .05       0
Bank Sta=4987.2,5017.3
XS Rating Curve= 0 ,0
Exp/Cntr=0.3,0.1

Type RM Length L Ch R = 1 ,876     ,522,522,522
BEGIN DESCRIPTION:
Mapping XS 6de18fec
END DESCRIPTION:
XS GIS Cut Line= 3
      3798124.32      10541941.2      3797624.35     10541732.88
      3796973.92      10541920.2
#Sta/Elev= 30
  4292.9  440.95  4329.8  439.68  4406.3  433.59  4449.7  426.85  4500.9  421.94
  4579.7  414.81  4666.3  398.71  4709.7  395.57  4763.8  384.01  4778.3  382.53
  4802.1  376.15  4807.6   376.7  4831.4  372.83  4834.4  370.36  4843.8  370.18
  4877.5  364.36  4922.7  361.66  4974.8  362.88  4992.6  357.36  4995.3  356.86
  4998.6  357.36  5016.4  357.47  5022.6  362.02  5027.8   362.8  5214.1  361.13
  5286.9  365.94  5312.8  370.64  5346.5  372.93  5351.7  374.79  5511.4  374.99
#Mann= 4 ,-1 , 0
  4292.9     .05       0  4500.9     .16       0  4992.6     .07       0
  4998.6     .16       0
Bank Sta=4974.8,5027.8
XS Rating Curve= 0 ,0
Exp/Cntr=0.3,0.1

Type RM Length L Ch R = 1 ,354     ,0,0,0
BEGIN DESCRIPTION:
UNT085 IN BECR 1.0
END DESCRIPTION:
XS GIS Cut Line= 4
      3797895.17       10541686.      3797311.85     10541321.42
      3796952.47     10541441.21      3796605.35      10541715.8
#Sta/Elev= 30
  4159.4  406.12  4166.4  403.48  4175.8  404.02  4202.9  398.92  4212.4  399.61
  4218.3  397.14  4364.5  387.07  4385.7  384.63  4401.1  380.84  4443.5  374.03
  4472.6  370.95  4480.1  368.78  4516.6  364.93  4531.5  364.93  4537.9  363.02
  4559.1  360.88  4842.1  357.81    4934  360.03  4988.8  359.58  4997.2   355.6
  5004.8  354.31  5007.5  353.81  5010.8  354.31  5015.2  359.27  5046.8  363.92
  5123.7  369.69  5178.6  372.17    5225  376.63  5427.2  382.98  5668.7  393.25
#Mann= 4 ,-1 , 0
  4159.4     .16       0  5004.8     .07       0  5010.8     .16       0
  5427.2     .05       0
Bank Sta=4988.8,5046.8
XS Rating Curve= 0 ,0
Exp/Cntr=0.3,0.1

Chan Stop Cuts=-1
Use User Specified Reach Order=0
Composite Channel Slope=5