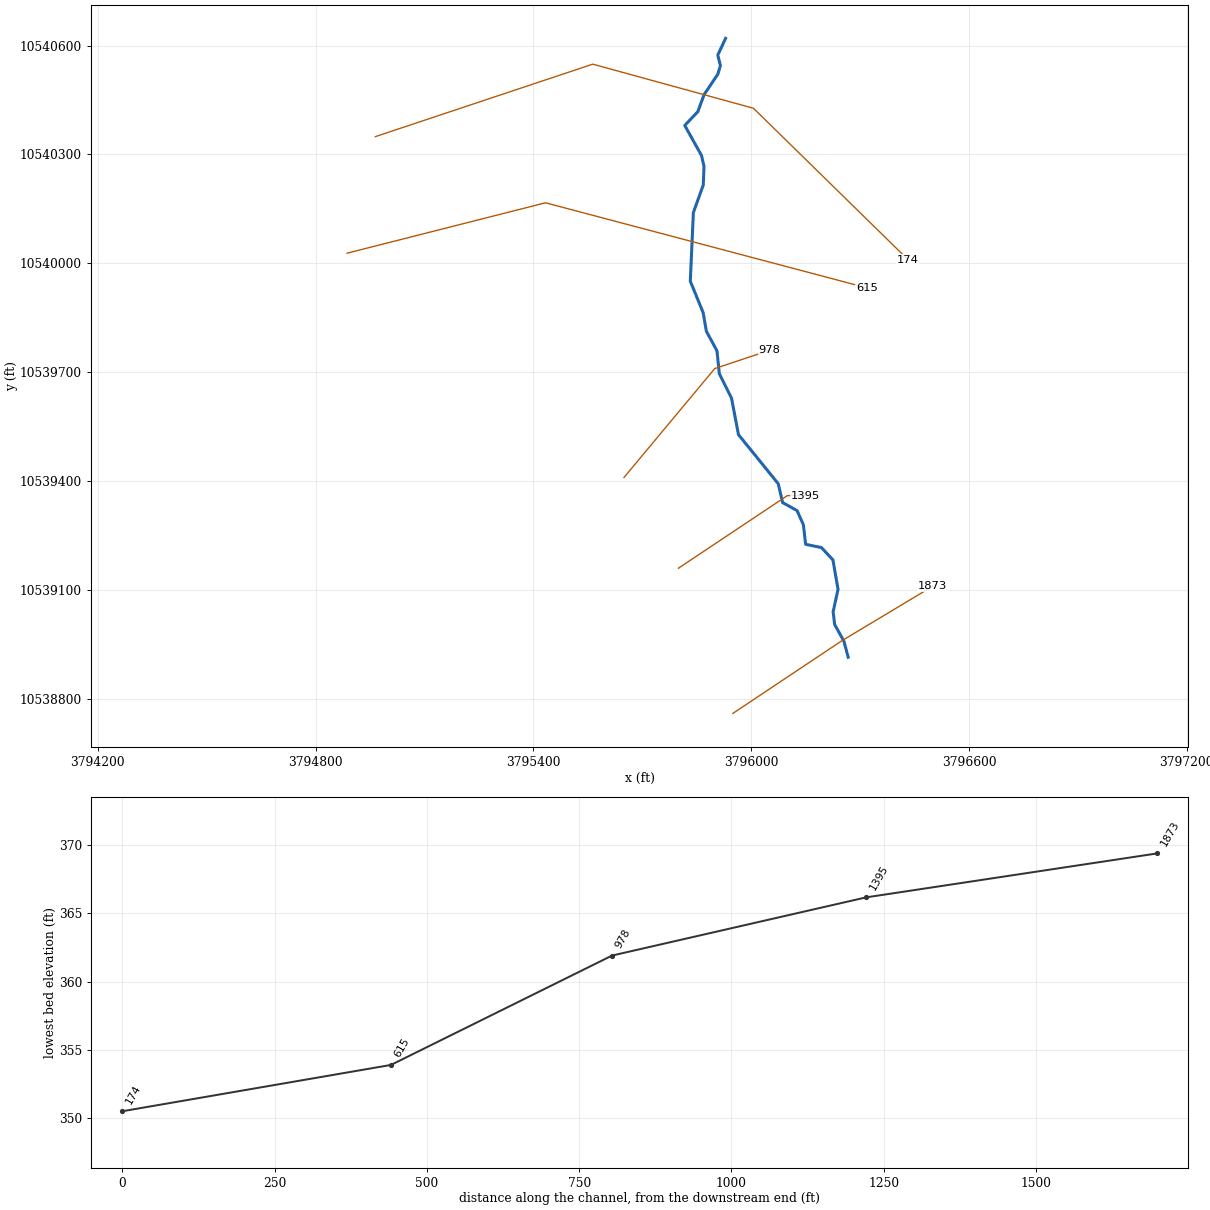
--- UNT086 IN BECR.prj (project) ---

Proj Title=UNT086 IN BECR Base Level Engineering
Current Plan=p01
Default Exp/Contr=0.3,0.1
English Units
Geom File=g01
Flow File=f01
Plan File=p01
BEGIN DESCRIPTION:
UNT086 IN BECR
END DESCRIPTION:

--- UNT086 IN BECR.p01 (plan) ---

Plan Title=Multiple Run
Short Identifier=Multiple
Geom File=g01
Flow File=f01
Subcritical Flow
K Sum by GR= 0
Std Step Tol= 0.01
Critical Tol= 0.01
Num of Std Step Trials= 20
Max Error Tol= 0.3
Flow Tol Ratio= 0.001
Split Flow NTrial= 30
Split Flow Tol= 0.02
Split Flow Ratio= 0.02
Log Output Level= 0
Friction Slope Method= 1
Unsteady Friction Slope Method= 2
Unsteady Bridges Friction Slope Method= 1
Parabolic Critical Depth
Global Vel Dist=  1 , 1 , 1
Global Log Level= 0
CheckData=True
Encroach Param= -1, 0, 0, 0
BEGIN DESCRIPTION:
Multiple Run
END DESCRIPTION:

--- UNT086 IN BECR.f01 (steady flow) ---

Flow Title=Multiple
Number of Profiles=7
Profile Names=10-year,25-year,50-year,1pct_min,100-year,1pct_plu,500-year
River Rch & RM= UNT086 IN BECR,Reach-1,1873
     581     790     963     866    1171    1583    1733
Boundary for River Rch & Prof#=UNT086 IN BECR,Reach-1,1
Up Type=0
Dn Type=3
Dn Slope=0.005
Boundary for River Rch & Prof#=UNT086 IN BECR,Reach-1,2
Up Type=0
Dn Type=3
Dn Slope=0.005
Boundary for River Rch & Prof#=UNT086 IN BECR,Reach-1,3
Up Type=0
Dn Type=3
Dn Slope=0.005
Boundary for River Rch & Prof#=UNT086 IN BECR,Reach-1,4
Up Type=0
Dn Type=3
Dn Slope=0.005
Boundary for River Rch & Prof#=UNT086 IN BECR,Reach-1,5
Up Type=0
Dn Type=3
Dn Slope=0.005
Boundary for River Rch & Prof#=UNT086 IN BECR,Reach-1,6
Up Type=0
Dn Type=3
Dn Slope=0.005
Boundary for River Rch & Prof#=UNT086 IN BECR,Reach-1,7
Up Type=0
Dn Type=3
Dn Slope=0.005

--- UNT086 IN BECR.g01 (geometry) ---

Geom Title=Existing Conditions

River Reach=UNT086 IN BECR,Reach-1
Reach XY= 30
      3796267.20     10538914.85      3796255.50     10538959.00
      3796230.00     10539005.00      3796225.75     10539040.00
      3796239.25     10539102.00      3796225.25     10539183.00
      3796193.50     10539217.00      3796150.00     10539226.00
      3796143.75     10539280.00      3796126.25     10539319.00
      3796086.50     10539341.00      3796074.50     10539393.00
      3795965.00     10539528.00      3795945.75     10539629.00
      3795912.25     10539696.00      3795905.75     10539759.00
      3795876.50     10539813.00      3795867.75     10539864.00
      3795832.25     10539951.00      3795840.75     10540140.00
      3795868.00     10540216.00      3795870.00     10540267.00
      3795863.25     10540297.00      3795817.00     10540380.00
      3795853.00     10540418.00      3795870.25     10540465.00
      3795908.00     10540521.00      3795915.25     10540545.00
      3795908.00     10540574.00      3795929.50     10540620.00

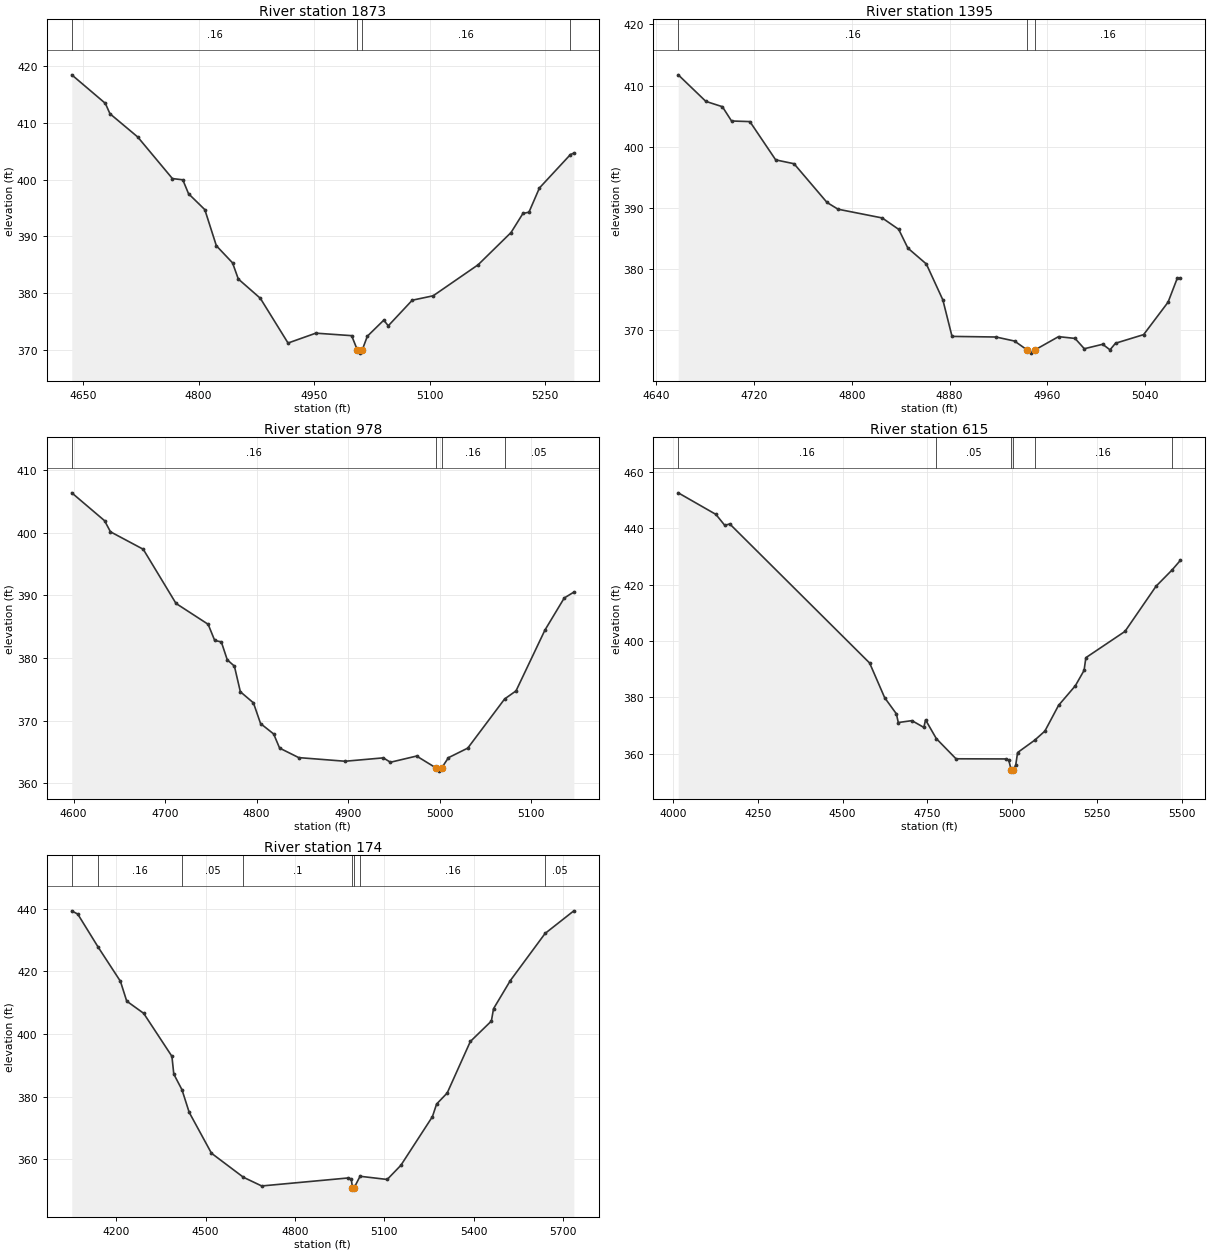
Type RM Length L Ch R = 1,1873,478,478,478
BEGIN DESCRIPTION:
UNT086 IN BECR 4.0
END DESCRIPTION:
XS GIS Cut Line= 3
      3795949.62     10538760.20      3796249.61     10538960.19
      3796499.62     10539110.19
#Sta/Elev= 30
  4635.3  418.46  4678.9  413.43  4684.9  411.60  4720.9  407.51  4766.0  400.17
  4779.5  399.95  4787.0  397.49  4808.1  394.69  4823.1  388.32  4844.1  385.31
  4851.6  382.46  4880.2  379.06  4916.2  371.17  4952.3  372.91  4998.8  372.47
  5006.4  369.89  5009.2  369.39  5012.4  369.89  5019.2  372.37  5040.5  375.20
  5046.4  374.21  5077.5  378.72  5104.7  379.50  5163.0  384.96  5205.8  390.65
  5221.3  394.02  5229.1  394.24  5242.7  398.51  5283.0  404.41  5287.4  404.65
#Mann=4,-1,0
  4635.3    0.16       0  5006.4    0.07       0  5012.4    0.16       0
  5283.0    0.05       0
Bank Sta=5006.4,5012.4
Exp/Cntr=0.3,0.1

Type RM Length L Ch R = 1,1395,417,417,417
BEGIN DESCRIPTION:
UNT086 IN BECR 3.0
END DESCRIPTION:
XS GIS Cut Line= 3
      3795799.57     10539160.16      3796099.61     10539360.19
      3796149.61     10539360.19
#Sta/Elev= 30
  4658.1  411.75  4680.7  407.40  4694.2  406.53  4701.7  404.19  4716.7  404.09
  4737.8  397.82  4752.8  397.19  4779.8  390.84  4788.8  389.74  4824.9  388.31
  4838.4  386.44  4845.9  383.37  4861.0  380.77  4874.5  374.89  4882.0  368.91
  4918.0  368.81  4933.1  368.15  4943.6  366.67  4946.3  366.17  4949.6  366.67
  4969.1  368.87  4982.6  368.58  4990.2  366.89  5005.2  367.62  5011.2  366.71
  5015.7  367.79  5038.7  369.20  5058.7  374.52  5066.2  378.43  5068.7  378.43
#Mann=3,-1,0
  4658.1    0.16       0  4943.6    0.07       0  4949.6    0.16       0
Bank Sta=4943.6,4949.6
Exp/Cntr=0.3,0.1

Type RM Length L Ch R = 1,978,363,363,363
BEGIN DESCRIPTION:
UNT086 IN BECR 2.0
END DESCRIPTION:
XS GIS Cut Line= 3
      3795649.61     10539410.19      3795899.61     10539710.19
      3796049.59     10539760.18
#Sta/Elev= 30
  4598.1  406.39  4633.9  401.94  4640.4  400.16  4676.2  397.37  4712.0  388.71
  4747.1  385.38  4754.3  382.79  4761.5  382.57  4768.0  379.70  4775.8  378.69
  4782.3  374.60  4796.6  372.82  4804.4  369.51  4818.7  367.85  4825.2  365.59
  4846.1  364.07  4896.8  363.49  4938.5  364.03  4946.3  363.33  4974.9  364.32
  4996.2  362.41  4998.9  361.91  5002.2  362.41  5009.7  364.06  5030.8  365.59
  5071.1  373.45  5083.5  374.73  5115.1  384.45  5136.2  389.58  5146.7  390.52
#Mann=4,-1,0
  4598.1    0.16       0  4996.2    0.07       0  5002.2    0.16       0
  5071.1    0.05       0
Bank Sta=4996.2,5002.2
Exp/Cntr=0.3,0.1

Type RM Length L Ch R = 1,615,441,441,441
BEGIN DESCRIPTION:
Mapping XS ef476fa0
END DESCRIPTION:
XS GIS Cut Line= 3
      3794886.50     10540028.02      3795433.37     10540166.90
      3796318.75     10539932.54
#Sta/Elev= 30
  4015.3  452.51  4126.3  444.87  4152.6  440.97  4167.2  441.49  4579.5  392.21
  4623.8  379.93  4658.4  374.20  4664.0  371.12  4704.2  371.79  4739.3  369.39
  4744.4  372.06  4776.1  365.43  4834.2  358.27  4980.6  358.22  4989.4  357.88
  4996.8  354.40  4999.5  353.90  5002.8  354.40  5010.1  355.95  5015.7  360.48
  5066.0  364.85  5096.1  368.08  5136.4  377.19  5186.0  384.16  5211.7  389.60
  5217.0  394.10  5332.3  403.41  5423.9  419.42  5470.9  425.15  5495.4  428.56
#Mann=6,-1,0
  4015.3    0.16       0  4776.1    0.05       0  4996.8   0.035       0
  5002.8    0.05       0  5066.0    0.16       0  5470.9    0.05       0
Bank Sta=4996.8,5002.8
Exp/Cntr=0.3,0.1

Type RM Length L Ch R = 1,174,0,0,0
BEGIN DESCRIPTION:
UNT086 IN BECR 1.0
END DESCRIPTION:
XS GIS Cut Line= 4
      3794964.58     10540349.18      3795563.58     10540548.85
      3796006.29     10540427.32      3796431.63     10540010.67
#Sta/Elev= 30
  4050.7  439.26  4070.8  438.24  4139.5  427.67  4214.1  416.80  4235.2  410.48
  4292.1  406.59  4387.0  392.87  4393.3  387.20  4420.8  382.20  4445.0  375.00
  4519.8  361.96  4627.1  354.29  4688.4  351.52  4978.7  354.07  4989.1  353.75
  4993.2  351.01  4996.0  350.51  4999.2  351.01  5018.7  354.61  5109.9  353.59
  5155.7  358.10  5261.7  373.62  5275.8  377.66  5311.3  381.17  5389.0  397.60
  5459.7  404.12  5466.9  408.06  5523.4  417.04  5640.0  432.06  5736.6  439.28
#Mann=8,-1,0
  4050.7    0.05       0  4139.5    0.16       0  4420.8    0.05       0
  4627.1     0.1       0  4993.2    0.07       0  4999.2     0.1       0
  5018.7    0.16       0  5640.0    0.05       0
Bank Sta=4993.2,4999.2
Exp/Cntr=0.3,0.1

Chan Stop Cuts=-1