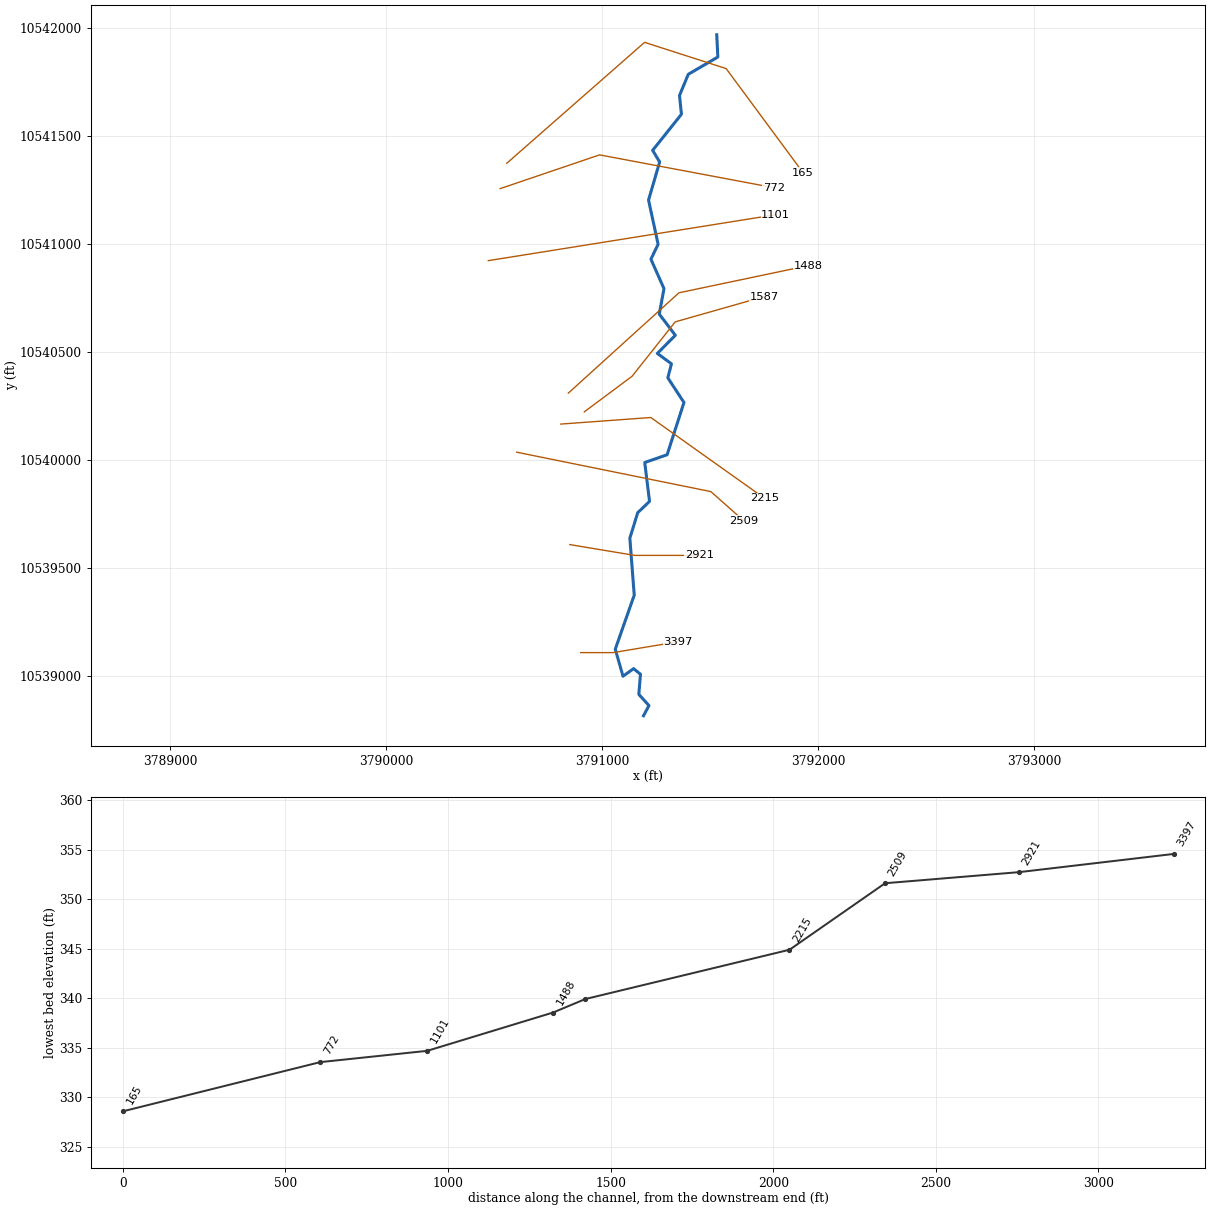
--- UNT087 IN BECR.prj (project) ---

Proj Title=UNT087 IN BECR Base Level Engineering
Current Plan=p01
Default Exp/Contr=0.3,0.1
English Units
Geom File=g01
Flow File=f01
Plan File=p01
BEGIN DESCRIPTION:
UNT087 IN BECR
END DESCRIPTION:

--- UNT087 IN BECR.p01 (plan) ---

Plan Title=Multiple Run
Short Identifier=Multiple
Geom File=g01
Flow File=f01
Subcritical Flow
K Sum by GR= 0
Std Step Tol= 0.01
Critical Tol= 0.01
Num of Std Step Trials= 20
Max Error Tol= 0.3
Flow Tol Ratio= 0.001
Split Flow NTrial= 30
Split Flow Tol= 0.02
Split Flow Ratio= 0.02
Log Output Level= 0
Friction Slope Method= 1
Unsteady Friction Slope Method= 2
Unsteady Bridges Friction Slope Method= 1
Parabolic Critical Depth
Global Vel Dist=  1 , 1 , 1
Global Log Level= 0
CheckData=True
Encroach Param= -1, 0, 0, 0
BEGIN DESCRIPTION:
Multiple Run
END DESCRIPTION:

--- UNT087 IN BECR.f01 (steady flow) ---

Flow Title=Multiple
Number of Profiles=7
Profile Names=10-year,25-year,50-year,1pct_min,100-year,1pct_plu,500-year
River Rch & RM= UNT087 IN BECR,Reach-1,3397
     590     798     971     868    1174    1588    1724
Boundary for River Rch & Prof#=UNT087 IN BECR,Reach-1,1
Up Type=0
Dn Type=3
Dn Slope=0.005
Boundary for River Rch & Prof#=UNT087 IN BECR,Reach-1,2
Up Type=0
Dn Type=3
Dn Slope=0.005
Boundary for River Rch & Prof#=UNT087 IN BECR,Reach-1,3
Up Type=0
Dn Type=3
Dn Slope=0.005
Boundary for River Rch & Prof#=UNT087 IN BECR,Reach-1,4
Up Type=0
Dn Type=3
Dn Slope=0.005
Boundary for River Rch & Prof#=UNT087 IN BECR,Reach-1,5
Up Type=0
Dn Type=3
Dn Slope=0.005
Boundary for River Rch & Prof#=UNT087 IN BECR,Reach-1,6
Up Type=0
Dn Type=3
Dn Slope=0.005
Boundary for River Rch & Prof#=UNT087 IN BECR,Reach-1,7
Up Type=0
Dn Type=3
Dn Slope=0.005

--- UNT087 IN BECR.g01 (geometry) ---

Geom Title=Existing Conditions

River Reach=UNT087 IN BECR,Reach-1
Reach XY= 30
      3791190.50     10538818.00      3791215.75     10538865.00
      3791168.75     10538917.00      3791176.50     10539010.00
      3791144.75     10539036.00      3791095.50     10539001.00
      3791059.75     10539126.00      3791147.50     10539376.00
      3791127.25     10539640.00      3791163.75     10539758.00
      3791218.25     10539810.00      3791196.25     10539990.00
      3791299.75     10540026.00      3791377.75     10540268.00
      3791303.00     10540382.00      3791319.75     10540447.00
      3791254.50     10540495.00      3791337.75     10540579.00
      3791263.50     10540677.00      3791285.25     10540795.00
      3791224.75     10540931.00      3791258.00     10541000.00
      3791213.75     10541205.00      3791265.25     10541381.00
      3791232.75     10541435.00      3791366.00     10541602.00
      3791357.00     10541689.00      3791397.75     10541787.00
      3791534.50     10541867.00      3791529.50     10541970.00

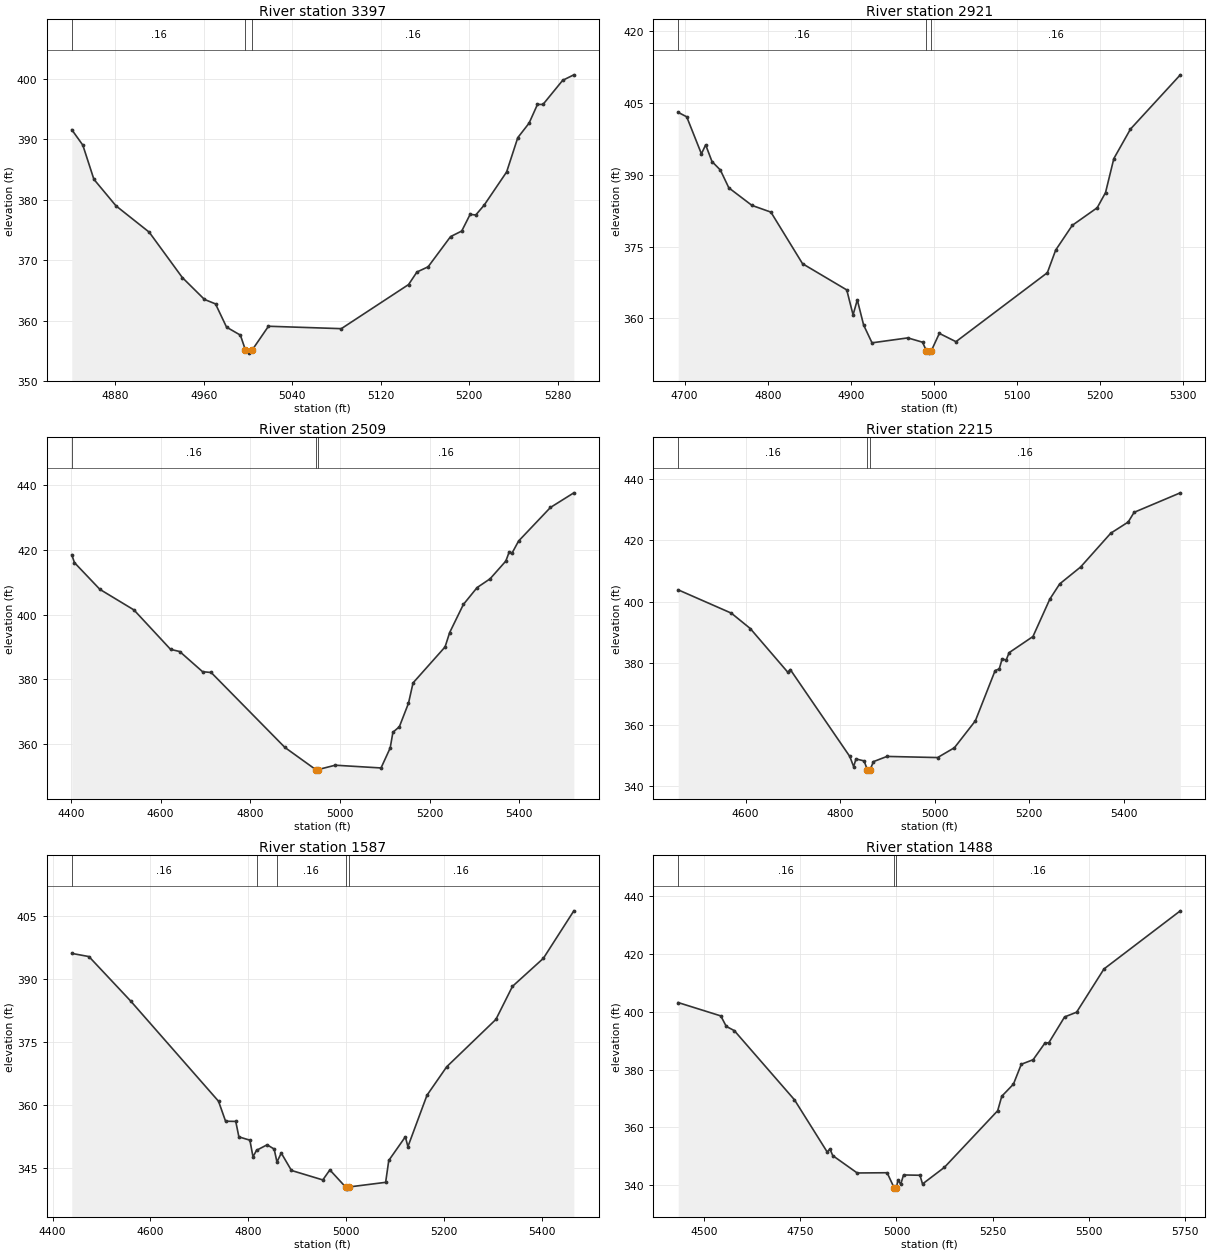
Type RM Length L Ch R = 1,3397,476,476,476
BEGIN DESCRIPTION:
UNT087 IN BECR 7.0
END DESCRIPTION:
XS GIS Cut Line= 3
      3790899.63     10539110.19      3791049.61     10539110.19
      3791349.59     10539160.19
#Sta/Elev= 30
  4840.5  391.59  4850.5  389.03  4860.5  383.38  4880.5  378.98  4910.5  374.63
  4940.5  367.11  4960.5  363.49  4970.5  362.75  4980.5  358.90  4993.0  357.58
  4997.6  355.10  5000.4  354.60  5003.6  355.10  5018.4  359.05  5084.3  358.65
  5145.1  365.95  5152.7  368.03  5162.8  368.89  5183.1  373.89  5193.2  374.81
  5200.8  377.57  5205.9  377.47  5213.5  379.10  5233.8  384.59  5243.9  390.27
  5254.1  392.67  5261.7  395.77  5266.7  395.77  5284.5  399.76  5294.6  400.67
#Mann=3,-1,0
  4840.5    0.16       0  4997.6    0.07       0  5003.6    0.16       0
Bank Sta=4997.6,5003.6
Exp/Cntr=0.3,0.1

Type RM Length L Ch R = 1,2921,412,412,412
BEGIN DESCRIPTION:
UNT087 IN BECR 6.0
END DESCRIPTION:
XS GIS Cut Line= 3
      3790849.58     10539610.19      3791149.61     10539560.19
      3791449.65     10539560.19
#Sta/Elev= 30
  4692.3  403.00  4702.5  402.08  4720.2  394.35  4725.3  396.23  4732.9  392.75
  4743.0  390.97  4753.2  387.25  4781.0  383.59  4803.8  382.19  4841.9  371.42
  4895.1  365.95  4902.7  360.74  4907.8  363.88  4915.4  358.62  4925.5  354.91
  4968.6  355.94  4986.3  355.04  4990.9  353.26  4993.7  352.76  4996.9  353.26
  5006.5  356.88  5026.5  355.15  5136.5  369.54  5146.5  374.26  5166.5  379.43
  5196.5  383.10  5206.5  386.26  5216.5  393.36  5236.5  399.51  5296.5  410.84
#Mann=3,-1,0
  4692.3    0.16       0  4990.9    0.07       0  4996.9    0.16       0
Bank Sta=4990.9,4996.9
Exp/Cntr=0.3,0.1

Type RM Length L Ch R = 1,2509,294,294,294
BEGIN DESCRIPTION:
UNT087 IN BECR 5.0
END DESCRIPTION:
XS GIS Cut Line= 3
      3790603.71     10540037.79      3791502.17     10539855.49
      3791654.08     10539720.94
#Sta/Elev= 30
  4402.0  418.58  4408.0  416.13  4464.7  407.87  4540.7  401.50  4622.3  389.31
  4642.7  388.64  4693.7  382.40  4712.9  382.15  4877.4  358.96  4945.8  352.14
  4948.6  351.64  4951.8  352.14  4989.6  353.47  5091.7  352.62  5112.1  358.80
  5118.2  363.67  5132.5  365.35  5152.9  372.63  5163.1  378.93  5234.5  390.06
  5244.7  394.49  5275.3  403.19  5306.0  408.43  5334.8  411.12  5370.0  416.62
  5377.5  419.42  5384.2  419.16  5398.4  422.81  5469.5  433.20  5521.7  437.73
#Mann=3,-1,0
  4402.0    0.16       0  4945.8    0.07       0  4951.8    0.16       0
Bank Sta=4945.8,4951.8
Exp/Cntr=0.3,0.1

Type RM Length L Ch R = 1,2215,628,628,628
BEGIN DESCRIPTION:
UNT087 IN BECR 4.0
END DESCRIPTION:
XS GIS Cut Line= 3
      3790807.70     10540167.99      3791224.39     10540198.37
      3791749.48     10539825.17
#Sta/Elev= 30
  4457.5  403.84  4569.7  396.28  4609.8  391.28  4689.5  377.02  4694.5  377.94
  4820.4  349.68  4828.5  346.38  4833.5  348.88  4850.5  348.25  4857.5  345.42
  4860.2  344.92  4863.5  345.42  4870.4  348.01  4899.1  349.70  5006.1  349.33
  5041.7  352.53  5086.0  361.27  5127.8  377.61  5136.5  378.14  5142.6  381.39
  5151.2  381.04  5157.4  383.43  5207.8  388.67  5243.5  400.83  5264.4  405.78
  5308.6  411.27  5372.4  422.26  5409.2  425.88  5421.8  429.04  5519.5  435.38
#Mann=3,-1,0
  4457.5    0.16       0  4857.5    0.07       0  4863.5    0.16       0
Bank Sta=4857.5,4863.5
Exp/Cntr=0.3,0.1

Type RM Length L Ch R = 1,1587,99,99,99
BEGIN DESCRIPTION:
Mapping XS f41a771b
END DESCRIPTION:
XS GIS Cut Line= 4
      3790916.22     10540224.41      3791137.58     10540389.34
      3791337.24     10540641.08      3791749.55     10540758.26
#Sta/Elev= 30
  4439.3  396.10  4474.4  395.34  4559.9  384.72  4739.2  360.88  4753.6  356.12
  4774.4  356.07  4780.8  352.39  4803.3  351.60  4809.6  347.64  4816.9  349.19
  4838.5  350.50  4852.9  349.49  4858.6  346.40  4867.4  348.53  4888.2  344.39
  4952.3  342.13  4966.7  344.52  4998.9  340.44  5001.7  339.94  5004.9  340.44
  5080.7  341.56  5087.1  346.77  5121.0  352.41  5126.2  350.05  5165.2  362.31
  5205.5  369.09  5306.0  380.37  5339.9  388.25  5403.0  394.92  5465.3  406.24
#Mann=5,-1,0
  4439.3    0.16       0  4816.9    0.12       0  4858.6    0.16       0
  4998.9    0.07       0  5004.9    0.16       0
Bank Sta=4998.9,5004.9
Exp/Cntr=0.3,0.1

Type RM Length L Ch R = 1,1488,387,387,387
BEGIN DESCRIPTION:
UNT087 IN BECR 3.0
END DESCRIPTION:
XS GIS Cut Line= 3
      3790842.46     10540311.23      3791354.60     10540775.63
      3791953.57     10540901.50
#Sta/Elev= 30
  4433.4  403.23  4543.9  398.61  4558.1  394.98  4579.0  393.51  4735.2  369.53
  4820.3  351.41  4827.1  352.54  4834.5  350.20  4898.0  344.18  4975.7  344.26
  4993.7  339.08  4996.4  338.58  4999.7  339.08  5004.1  341.81  5010.9  340.25
  5018.3  343.49  5060.9  343.39  5067.6  340.37  5124.4  346.13  5262.7  365.76
  5273.3  370.77  5303.6  374.97  5324.0  381.86  5354.7  383.43  5385.3  389.19
  5395.5  389.32  5436.4  398.26  5467.6  399.90  5538.6  414.88  5736.8  435.03
#Mann=3,-1,0
  4433.4    0.16       0  4993.7    0.07       0  4999.7    0.16       0
Bank Sta=4993.7,4999.7
Exp/Cntr=0.3,0.1

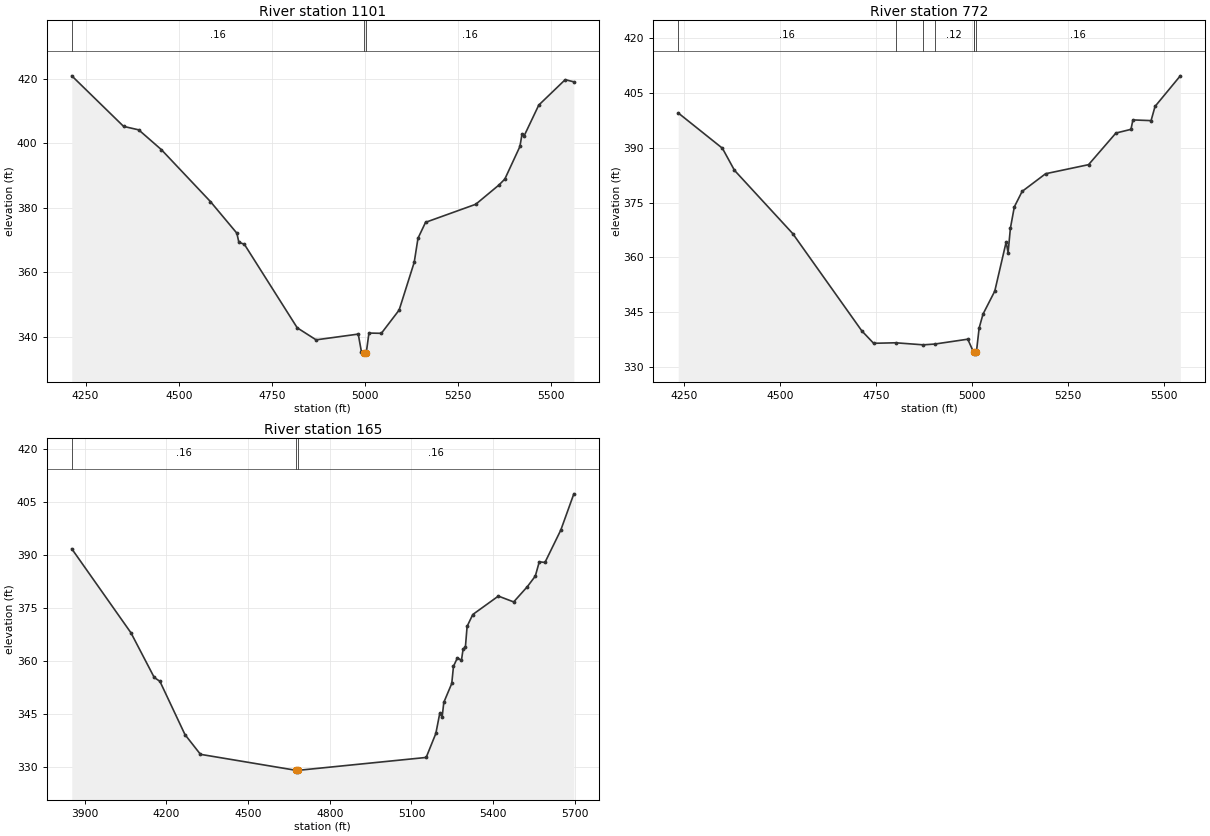
Type RM Length L Ch R = 1,1101,329,329,329
BEGIN DESCRIPTION:
UNT087 IN BECR 2.0
END DESCRIPTION:
XS GIS Cut Line= 2
      3790472.21     10540924.38      3791802.52     10541137.05
#Sta/Elev= 30
  4213.0  420.84  4352.1  405.19  4392.6  404.12  4453.4  398.00  4585.1  381.92
  4656.0  372.14  4661.3  369.35  4676.2  368.69  4818.0  342.85  4868.6  339.13
  4981.7  340.91  4990.1  335.49  4997.3  335.21  5000.0  334.71  5003.3  335.21
  5010.4  341.23  5043.7  341.15  5091.4  348.35  5131.9  363.14  5142.0  370.57
  5162.3  375.50  5297.0  381.09  5359.1  387.04  5375.0  388.89  5415.5  398.97
  5421.1  402.78  5426.2  402.11  5466.1  411.79  5537.0  419.65  5560.2  418.98
#Mann=3,-1,0
  4213.0    0.16       0  4997.3    0.07       0  5003.3    0.16       0
Bank Sta=4997.3,5003.3
Exp/Cntr=0.3,0.1

Type RM Length L Ch R = 1,772,607,607,607
BEGIN DESCRIPTION:
Mapping XS 9e3033c4
END DESCRIPTION:
XS GIS Cut Line= 3
      3790527.08     10541257.77      3790987.12     10541414.01
      3791794.40     10541262.10
#Sta/Elev= 30
  4235.6  399.48  4350.6  389.84  4382.0  383.81  4533.6  366.53  4713.5  339.94
  4744.3  336.53  4802.0  336.67  4873.5  336.11  4903.3  336.32  4989.5  337.65
  5004.6  334.09  5005.9  334.07  5008.6  333.57  5011.9  334.07  5019.1  340.71
  5029.2  344.51  5059.8  350.79  5089.4  364.19  5094.5  361.33  5100.5  367.99
  5110.7  373.81  5131.0  378.04  5192.1  382.87  5304.0  385.35  5375.2  393.99
  5414.4  395.00  5419.5  397.58  5466.8  397.39  5477.1  401.27  5542.9  409.63
#Mann=7,-1,0
  4235.6    0.16       0  4802.0    0.12       0  4873.5    0.16       0
  4903.3    0.12       0  5004.6    0.16       0  5005.9    0.07       0
  5011.9    0.16       0
Bank Sta=5005.9,5011.9
Exp/Cntr=0.3,0.1

Type RM Length L Ch R = 1,165,0,0,0
BEGIN DESCRIPTION:
UNT087 IN BECR 1.0
END DESCRIPTION:
XS GIS Cut Line= 4
      3790557.41     10541374.93      3791195.46     10541934.84
      3791573.06     10541813.32      3791928.94     10541331.58
#Sta/Elev= 30
  3852.0  391.74  4069.5  367.98  4154.9  355.37  4175.8  354.27  4267.9  339.21
  4324.8  333.63  4676.7  329.10  4679.4  328.60  4682.7  329.10  5154.0  332.75
  5189.5  339.53  5204.1  345.30  5212.6  344.16  5218.8  348.32  5248.0  353.67
  5254.3  358.52  5268.9  360.93  5283.5  360.19  5289.7  363.39  5298.1  363.94
  5304.4  369.82  5325.2  373.16  5419.2  378.37  5475.5  376.72  5525.6  381.03
  5554.9  384.02  5569.5  388.06  5590.4  387.88  5648.5  397.02  5696.5  407.28
#Mann=3,-1,0
  3852.0    0.16       0  4676.7    0.07       0  4682.7    0.16       0
Bank Sta=4676.7,4682.7
Exp/Cntr=0.3,0.1

Chan Stop Cuts=-1