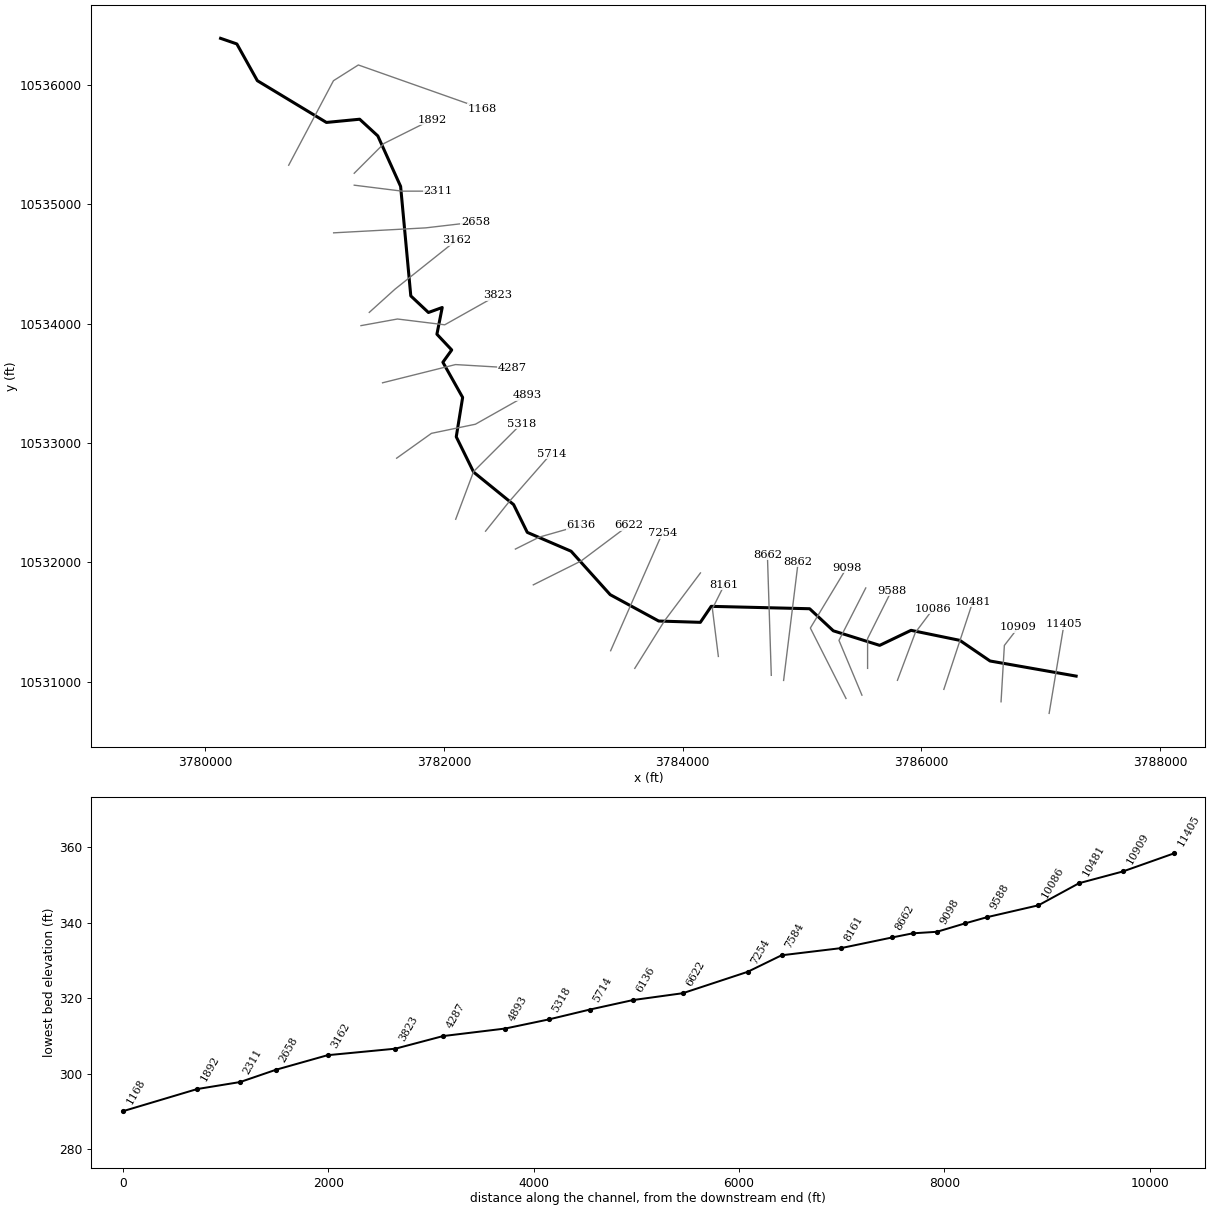
--- UNT089 IN BECR.prj (project) ---

Proj Title=UNT089 IN BECR Base Level Engineering
Current Plan=p01
Default Exp/Contr=0.3,0.1
English Units
Geom File=g01
Flow File=f01
Plan File=p01
BEGIN DESCRIPTION:
UNT089 IN BECR
END DESCRIPTION:

--- UNT089 IN BECR.p01 (plan) ---

Plan Title=Multiple Run
Short Identifier=Multiple
Geom File=g01
Flow File=f01
Subcritical Flow
K Sum by GR= 0
Std Step Tol= 0.01
Critical Tol= 0.01
Num of Std Step Trials= 20
Max Error Tol= 0.3
Flow Tol Ratio= 0.001
Split Flow NTrial= 30
Split Flow Tol= 0.02
Split Flow Ratio= 0.02
Log Output Level= 0
Friction Slope Method= 1
Unsteady Friction Slope Method= 2
Unsteady Bridges Friction Slope Method= 1
Parabolic Critical Depth
Global Vel Dist=  1 , 1 , 1
Global Log Level= 0
CheckData=True
Encroach Param= -1, 0, 0, 0
BEGIN DESCRIPTION:
Multiple Run
END DESCRIPTION:

--- UNT089 IN BECR.f01 (steady flow) ---

Flow Title=Multiple
Number of Profiles=7
Profile Names=10-year,25-year,50-year,1pct_min,100-year,1pct_plu,500-year
River Rch & RM= UNT089 IN BECR,Reach-1,11405
     623     848    1035     929    1257    1700    1859
River Rch & RM= UNT089 IN BECR,Reach-1,10481
     865    1195    1474    1334    1805    2440    2716
River Rch & RM= UNT089 IN BECR,Reach-1,4893
    1053    1466    1817    1652    2235    3022    3393
Boundary for River Rch & Prof#=UNT089 IN BECR,Reach-1,1
Up Type=0
Dn Type=3
Dn Slope=0.005
Boundary for River Rch & Prof#=UNT089 IN BECR,Reach-1,2
Up Type=0
Dn Type=3
Dn Slope=0.005
Boundary for River Rch & Prof#=UNT089 IN BECR,Reach-1,3
Up Type=0
Dn Type=3
Dn Slope=0.005
Boundary for River Rch & Prof#=UNT089 IN BECR,Reach-1,4
Up Type=0
Dn Type=3
Dn Slope=0.005
Boundary for River Rch & Prof#=UNT089 IN BECR,Reach-1,5
Up Type=0
Dn Type=3
Dn Slope=0.005
Boundary for River Rch & Prof#=UNT089 IN BECR,Reach-1,6
Up Type=0
Dn Type=3
Dn Slope=0.005
Boundary for River Rch & Prof#=UNT089 IN BECR,Reach-1,7
Up Type=0
Dn Type=3
Dn Slope=0.005

--- UNT089 IN BECR.g01 (geometry) ---

Geom Title=Existing Conditions

River Reach=UNT089 IN BECR,Reach-1
Reach XY= 30
      3787296.28     10531045.30      3786575.25     10531172.00
      3786322.00     10531345.00      3785913.50     10531429.00
      3785650.75     10531303.00      3785262.50     10531425.00
      3785064.25     10531610.00      3784239.75     10531630.00
      3784148.75     10531496.00      3783799.75     10531507.00
      3783393.50     10531728.00      3783066.25     10532092.00
      3782699.25     10532250.00      3782584.50     10532483.00
      3782249.75     10532755.00      3782104.25     10533051.00
      3782157.75     10533381.00      3781992.25     10533676.00
      3782066.25     10533779.00      3781942.25     10533911.00
      3781986.75     10534135.00      3781871.25     10534093.00
      3781723.50     10534232.00      3781638.25     10535150.00
      3781447.25     10535573.00      3781295.25     10535713.00
      3781016.75     10535686.00      3780438.25     10536036.00
      3780266.50     10536344.00      3780130.25     10536391.00

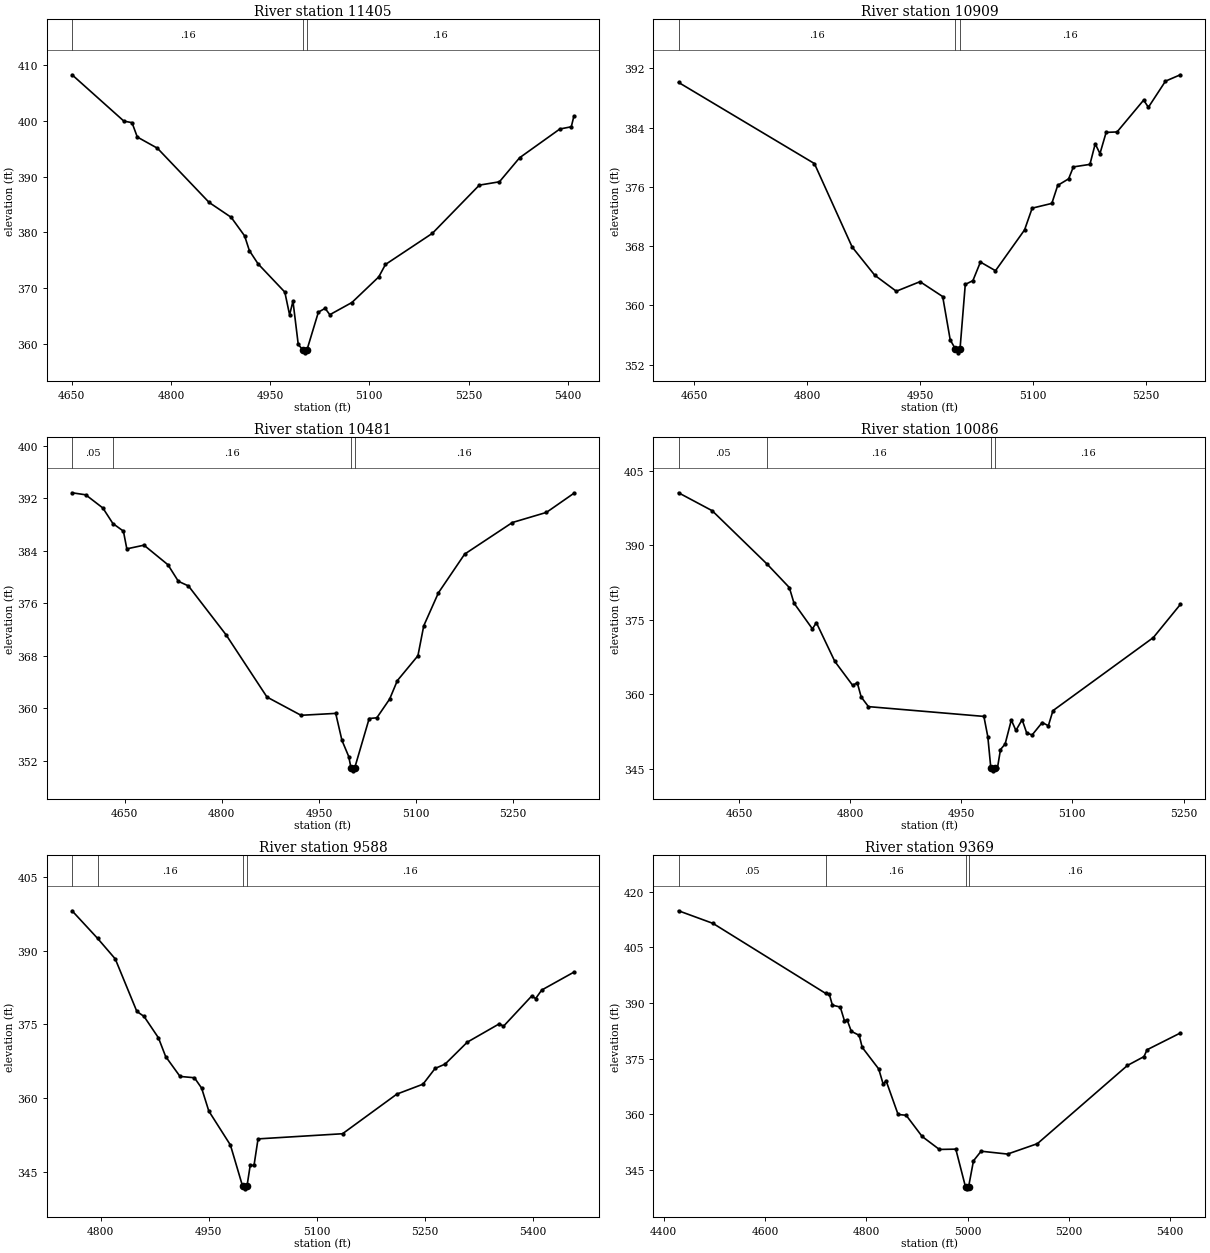
Type RM Length L Ch R = 1,11405,496,496,496
BEGIN DESCRIPTION:
UNT089 IN BECR 22.0
END DESCRIPTION:
XS GIS Cut Line= 2
      3787070.21     10530732.94      3787194.90     10531481.12
#Sta/Elev= 30
  4650.6  408.31  4728.9  399.99  4741.2  399.71  4749.2  397.13  4779.6  395.12
  4857.8  385.38  4891.1  382.71  4911.4  379.38  4918.6  376.73  4931.7  374.36
  4972.2  369.28  4979.4  365.19  4984.5  367.65  4992.5  359.87  4999.6  358.87
  5002.4  358.37  5005.6  358.87  5022.9  365.67  5033.1  366.37  5040.2  365.22
  5073.6  367.41  5114.2  372.01  5124.3  374.24  5195.3  379.84  5266.2  388.49
  5296.6  389.09  5327.1  393.41  5387.9  398.57  5405.2  398.97  5409.1  400.85
#Mann=3,-1,0
  4650.6    0.16       0  4999.6    0.07       0  5005.6    0.16       0
Bank Sta=4999.6,5005.6
Exp/Cntr=0.3,0.1

Type RM Length L Ch R = 1,10909,428,428,428
BEGIN DESCRIPTION:
UNT089 IN BECR 21.0
END DESCRIPTION:
XS GIS Cut Line= 3
      3786667.42     10530830.10      3786695.20     10531302.37
      3786813.28     10531455.18
#Sta/Elev= 30
  4629.5  390.11  4809.9  379.15  4860.0  367.88  4890.0  364.07  4918.6  361.91
  4950.1  363.20  4980.2  361.19  4990.2  355.34  4997.2  354.09  5000.0  353.59
  5003.2  354.09  5010.2  362.83  5020.3  363.34  5030.3  365.85  5050.3  364.68
  5088.9  370.19  5099.0  373.13  5125.1  373.77  5132.9  376.20  5147.4  377.09
  5153.7  378.70  5175.7  379.04  5182.7  381.82  5189.0  380.49  5197.2  383.36
  5211.7  383.42  5247.0  387.72  5253.3  386.75  5276.0  390.28  5295.7  391.14
#Mann=3,-1,0
  4629.5    0.16       0  4997.2    0.07       0  5003.2    0.16       0
Bank Sta=4997.2,5003.2
Exp/Cntr=0.3,0.1

Type RM Length L Ch R = 1,10481,395,395,395
BEGIN DESCRIPTION:
UNT089 IN BECR 20.0
END DESCRIPTION:
XS GIS Cut Line= 2
      3786188.26     10530934.31      3786431.31     10531670.42
#Sta/Elev= 30
  4568.7  392.82  4589.8  392.51  4616.3  390.50  4631.8  388.13  4648.0  386.98
  4653.3  384.28  4679.8  384.84  4716.8  381.86  4732.9  379.34  4748.5  378.63
  4806.6  371.19  4869.8  361.71  4922.4  358.93  4976.0  359.22  4985.6  355.12
  4996.1  352.65  4999.5  350.97  5002.2  350.47  5005.5  350.97  5027.7  358.44
  5039.5  358.55  5059.3  361.40  5071.2  364.21  5103.0  368.00  5112.0  372.56
  5134.7  377.59  5175.2  383.48  5248.9  388.29  5301.5  389.83  5343.9  392.74
#Mann=4,-1,0
  4568.7    0.05       0  4631.8    0.16       0  4999.5    0.07       0
  5005.5    0.16       0
Bank Sta=4999.5,5005.5
Exp/Cntr=0.3,0.1

Type RM Length L Ch R = 1,10086,498,498,498
BEGIN DESCRIPTION:
UNT089 IN BECR 19.0
END DESCRIPTION:
XS GIS Cut Line= 3
      3785799.60     10531010.17      3785949.61     10531410.19
      3786099.60     10531610.17
#Sta/Elev= 30
  4568.5  400.61  4613.9  397.00  4688.0  386.25  4718.0  381.53  4724.3  378.40
  4749.2  373.20  4754.5  374.46  4779.4  366.66  4803.5  361.83  4809.7  362.37
  4815.0  359.49  4824.8  357.55  4980.6  355.58  4985.9  351.48  4990.0  345.12
  4992.8  344.62  4996.0  345.12  4998.8  345.12  5003.0  348.90  5009.3  350.04
  5017.6  354.85  5023.8  352.75  5032.2  354.92  5038.4  352.23  5045.7  351.85
  5059.3  354.35  5067.6  353.70  5073.8  356.74  5209.3  371.46  5245.7  378.12
#Mann=4,-1,0
  4568.5    0.05       0  4688.0    0.16       0  4990.0    0.07       0
  4996.0    0.16       0
Bank Sta=4990,4996
Exp/Cntr=0.3,0.1

Type RM Length L Ch R = 1,9588,219,219,219
BEGIN DESCRIPTION:
UNT089 IN BECR 18.0
END DESCRIPTION:
XS GIS Cut Line= 3
      3785549.61     10531110.17      3785549.61     10531360.19
      3785749.60     10531760.16
#Sta/Elev= 30
  4760.1  398.16  4795.6  392.53  4820.1  388.35  4850.1  377.65  4860.1  376.63
  4880.1  372.27  4890.1  368.46  4910.1  364.40  4930.1  364.13  4940.1  362.02
  4950.1  357.34  4980.1  350.42  4997.1  341.99  4999.9  341.49  5003.1  341.99
  5007.6  346.27  5012.9  346.27  5018.5  351.67  5135.9  352.72  5211.4  360.80
  5247.7  362.82  5264.5  366.03  5278.4  366.91  5309.2  371.38  5353.9  375.14
  5359.5  374.62  5398.6  380.77  5404.2  380.27  5412.6  382.00  5457.3  385.65
#Mann=4,-1,0
  4760.1    0.05       0  4795.6    0.16       0  4997.1    0.07       0
  5003.1    0.16       0
Bank Sta=4997.1,5003.1
Exp/Cntr=0.3,0.1

Type RM Length L Ch R = 1,9369,271,271,271
BEGIN DESCRIPTION:
Mapping XS f062d31f
END DESCRIPTION:
XS GIS Cut Line= 3
      3785502.20     10530885.50      3785309.95     10531344.74
      3785534.24     10531784.15
#Sta/Elev= 30
  4429.1  414.90  4497.2  411.49  4719.8  392.58  4726.9  392.37  4733.0  389.42
  4748.6  388.90  4756.8  385.20  4762.2  385.42  4770.3  382.36  4786.0  381.26
  4791.9  378.02  4824.5  372.19  4833.5  368.01  4839.0  369.04  4862.8  359.89
  4878.7  359.68  4910.3  353.95  4944.3  350.45  4976.8  350.53  4996.0  340.31
  4998.8  339.81  5002.0  340.31  5011.7  347.38  5026.8  349.97  5079.0  349.20
  5138.0  352.01  5315.8  373.13  5348.5  375.52  5354.6  377.37  5420.3  381.89
#Mann=4,-1,0
  4429.1    0.05       0  4719.8    0.16       0  4996.0    0.07       0
  5002.0    0.16       0
Bank Sta=4996,5002
Exp/Cntr=0.3,0.1

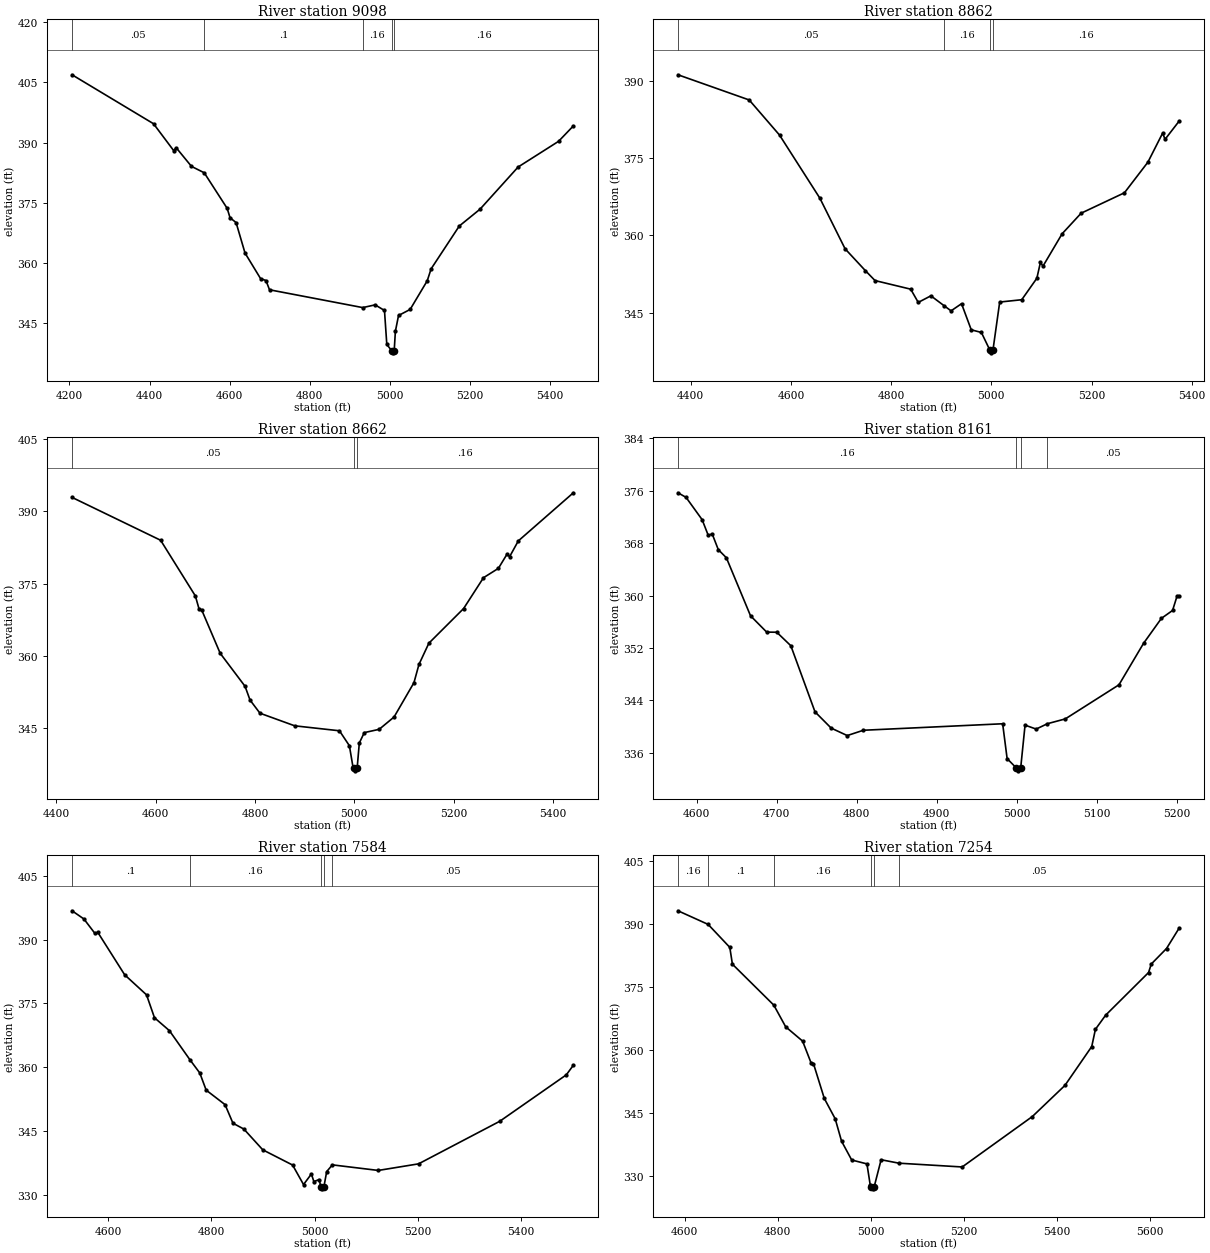
Type RM Length L Ch R = 1,9098,236,236,236
BEGIN DESCRIPTION:
UNT089 IN BECR 17.0
END DESCRIPTION:
XS GIS Cut Line= 3
      3785368.80     10530857.95      3785070.20     10531448.20
      3785375.20     10531954.22
#Sta/Elev= 30
  4206.4  406.92  4410.0  394.71  4460.2  388.03  4466.7  388.72  4504.8  384.08
  4536.6  382.49  4593.9  373.62  4601.1  371.28  4616.2  370.07  4638.5  362.48
  4677.4  356.10  4690.8  355.63  4699.7  353.32  4932.5  348.88  4963.6  349.56
  4986.9  348.16  4992.7  339.69  5005.2  338.10  5008.0  337.60  5011.2  338.10
  5014.1  342.95  5022.0  346.91  5051.0  348.42  5093.7  355.56  5103.4  358.54
  5173.8  369.22  5225.7  373.42  5320.8  383.93  5421.8  390.33  5458.7  394.17
#Mann=5,-1,0
  4206.4    0.05       0  4536.6     0.1       0  4932.5    0.16       0
  5005.2    0.07       0  5011.2    0.16       0
Bank Sta=5005.2,5011.2
Exp/Cntr=0.3,0.1

Type RM Length L Ch R = 1,8862,200,200,200
BEGIN DESCRIPTION:
Mapping XS 8ed70212
END DESCRIPTION:
XS GIS Cut Line= 2
      3784846.09     10531009.04      3784968.16     10532002.36
#Sta/Elev= 30
  4374.4  391.17  4516.6  386.28  4577.1  379.47  4657.7  367.21  4708.0  357.39
  4748.3  353.17  4767.8  351.22  4839.0  349.55  4854.1  346.98  4879.3  348.26
  4905.8  346.33  4919.6  345.34  4940.5  346.73  4959.9  341.66  4980.1  341.15
  4997.2  337.69  5000.0  337.19  5003.2  337.69  5016.7  347.05  5060.7  347.50
  5090.9  351.67  5098.0  354.76  5103.1  354.02  5141.3  360.30  5179.3  364.30
  5265.7  368.26  5312.6  374.21  5341.9  379.83  5346.9  378.65  5375.2  382.21
#Mann=4,-1,0
  4374.4    0.05       0  4905.8    0.16       0  4997.2    0.07       0
  5003.2    0.16       0
Bank Sta=4997.2,5003.2
Exp/Cntr=0.3,0.1

Type RM Length L Ch R = 1,8662,501,501,501
BEGIN DESCRIPTION:
UNT089 IN BECR 16.0
END DESCRIPTION:
XS GIS Cut Line= 2
      3784742.95     10531051.90      3784710.39     10532061.07
#Sta/Elev= 30
  4431.6  392.89  4610.0  383.99  4680.0  372.42  4687.6  369.65  4692.6  369.55
  4730.0  360.51  4780.1  353.65  4790.1  350.80  4810.1  348.07  4880.1  345.45
  4970.2  344.42  4990.2  341.32  4997.8  336.68  4999.8  336.60  5002.5  336.10
  5005.8  336.60  5010.2  341.88  5020.2  344.04  5050.2  344.72  5080.2  347.28
  5120.3  354.42  5130.3  358.19  5150.3  362.61  5220.3  369.81  5260.3  376.21
  5290.3  378.15  5307.9  381.13  5312.9  380.57  5330.4  383.85  5441.3  393.85
#Mann=3,-1,0
  4431.6    0.05       0  4999.8   0.035       0  5005.8    0.16       0
Bank Sta=4999.8,5005.8
Exp/Cntr=0.3,0.1

Type RM Length L Ch R = 1,8161,577,577,577
BEGIN DESCRIPTION:
UNT089 IN BECR 15.0
END DESCRIPTION:
XS GIS Cut Line= 3
      3784299.61     10531210.17      3784249.61     10531610.19
      3784349.59     10531810.16
#Sta/Elev= 30
  4576.4  375.67  4586.5  374.97  4606.6  371.57  4614.2  369.19  4619.2  369.39
  4626.8  367.00  4636.9  365.76  4667.1  356.91  4687.3  354.42  4699.9  354.40
  4717.5  352.34  4747.7  342.26  4767.9  339.78  4788.0  338.64  4808.2  339.45
  4982.3  340.44  4987.9  335.12  4998.9  333.76  5001.6  333.26  5004.9  333.76
  5010.3  340.23  5024.2  339.63  5038.3  340.45  5060.6  341.18  5127.7  346.38
  5158.4  352.70  5180.8  356.52  5194.7  357.72  5200.3  359.90  5203.1  359.90
#Mann=4,-1,0
  4576.4    0.16       0  4998.9    0.07       0  5004.9    0.16       0
  5038.3    0.05       0
Bank Sta=4998.9,5004.9
Exp/Cntr=0.3,0.1

Type RM Length L Ch R = 1,7584,330,330,330
BEGIN DESCRIPTION:
UNT089 IN BECR 14.0
END DESCRIPTION:
XS GIS Cut Line= 3
      3783599.62     10531110.21      3783849.61     10531510.19
      3784149.62     10531910.21
#Sta/Elev= 30
  4530.0  396.79  4553.0  394.86  4574.2  391.49  4580.1  391.68  4632.0  381.73
  4674.4  377.01  4689.8  371.62  4718.7  368.59  4758.5  361.74  4777.6  358.63
  4790.0  354.59  4826.6  351.18  4841.9  346.81  4863.1  345.43  4899.7  340.55
  4957.5  336.97  4978.7  332.38  4994.0  334.87  4998.7  333.08  5009.0  333.56
  5012.2  331.87  5015.0  331.37  5018.2  331.87  5023.6  335.43  5034.6  337.01
  5123.6  335.70  5201.7  337.25  5359.0  347.26  5488.1  358.19  5501.7  360.45
#Mann=5,-1,0
  4530.0     0.1       0  4758.5    0.16       0  5012.2    0.07       0
  5018.2    0.16       0  5034.6    0.05       0
Bank Sta=5012.2,5018.2
Exp/Cntr=0.3,0.1

Type RM Length L Ch R = 1,7254,632,632,632
BEGIN DESCRIPTION:
UNT089 IN BECR 13.0
END DESCRIPTION:
XS GIS Cut Line= 2
      3783397.45     10531258.08      3783831.40     10532245.31
#Sta/Elev= 30
  4585.6  393.11  4650.5  389.87  4697.1  384.41  4702.7  380.41  4791.8  370.67
  4817.3  365.52  4853.7  362.12  4871.6  357.03  4877.1  356.76  4900.4  348.48
  4923.8  343.65  4937.5  338.32  4959.3  333.85  4992.1  332.92  4999.3  327.82
  5001.7  327.49  5004.5  326.99  5007.7  327.49  5022.6  333.91  5060.9  333.09
  5197.0  332.19  5348.0  344.19  5418.0  351.58  5475.7  360.83  5483.6  364.92
  5505.5  368.27  5597.9  378.42  5603.8  380.45  5636.6  384.14  5664.0  389.04
#Mann=6,-1,0
  4585.6    0.16       0  4650.5     0.1       0  4791.8    0.16       0
  5001.7    0.07       0  5007.7    0.16       0  5060.9    0.05       0
Bank Sta=5001.7,5007.7
Exp/Cntr=0.3,0.1

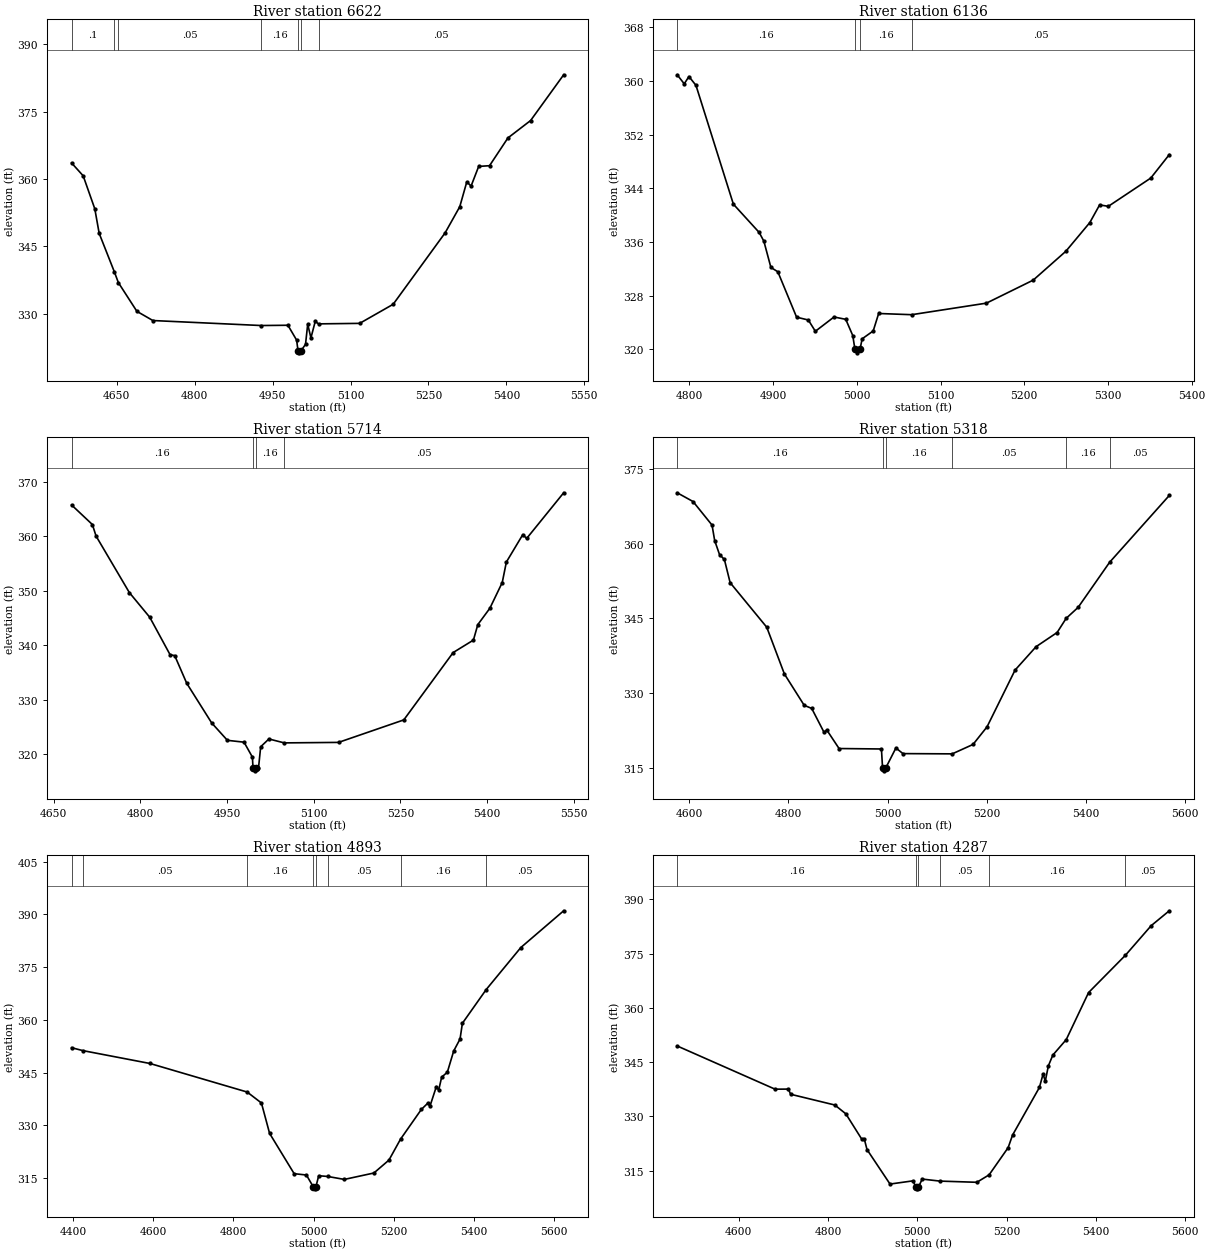
Type RM Length L Ch R = 1,6622,486,486,486
BEGIN DESCRIPTION:
UNT089 IN BECR 12.0
END DESCRIPTION:
XS GIS Cut Line= 3
      3782749.65     10531810.21      3783149.61     10532010.19
      3783549.63     10532310.21
#Sta/Elev= 30
  4563.0  363.59  4585.3  360.73  4607.7  353.38  4616.1  347.92  4645.4  339.33
  4653.0  336.96  4688.7  330.56  4719.5  328.51  4928.1  327.40  4979.4  327.46
  4996.2  324.15  4998.8  321.82  5001.5  321.32  5004.8  321.82  5013.3  323.21
  5017.5  327.69  5023.7  324.65  5032.0  328.31  5038.4  327.77  5117.5  327.88
  5182.0  332.13  5282.0  348.03  5310.2  353.85  5323.7  359.37  5332.0  358.45
  5346.6  362.82  5367.5  362.98  5402.9  369.16  5446.6  373.04  5510.2  383.22
#Mann=7,-1,0
  4563.0     0.1       0  4645.4    0.16       0  4653.0    0.05       0
  4928.1    0.16       0  4998.8    0.07       0  5004.8    0.16       0
  5038.4    0.05       0
Bank Sta=4998.8,5004.8
Exp/Cntr=0.3,0.1

Type RM Length L Ch R = 1,6136,422,422,422
BEGIN DESCRIPTION:
UNT089 IN BECR 11.0
END DESCRIPTION:
XS GIS Cut Line= 3
      3782599.57     10532110.17      3782799.61     10532210.19
      3783149.65     10532310.20
#Sta/Elev= 30
  4785.5  360.91  4793.9  359.56  4799.5  360.65  4807.9  359.34  4852.6  341.64
  4883.4  337.43  4889.0  336.13  4897.4  332.22  4905.7  331.57  4928.1  324.81
  4942.1  324.39  4950.5  322.71  4972.8  324.84  4986.8  324.49  4995.2  322.07
  4997.8  320.00  5000.5  319.50  5003.8  320.00  5006.4  321.59  5019.6  322.76
  5026.1  325.36  5065.5  325.18  5154.8  326.90  5210.7  330.33  5249.7  334.63
  5278.3  338.90  5290.0  341.53  5300.4  341.32  5351.1  345.53  5373.2  349.02
#Mann=4,-1,0
  4785.5    0.16       0  4997.8    0.07       0  5003.8    0.16       0
  5065.5    0.05       0
Bank Sta=4997.8,5003.8
Exp/Cntr=0.3,0.1

Type RM Length L Ch R = 1,5714,396,396,396
BEGIN DESCRIPTION:
UNT089 IN BECR 10.0
END DESCRIPTION:
XS GIS Cut Line= 3
      3782349.61     10532260.19      3782549.61     10532510.19
      3782899.63     10532910.22
#Sta/Elev= 30
  4681.0  365.77  4717.0  362.18  4723.4  360.06  4781.0  349.69  4816.3  345.16
  4851.5  338.28  4859.5  338.12  4880.3  333.04  4923.5  325.76  4950.7  322.57
  4979.5  322.23  4994.0  319.48  4995.0  317.47  4997.7  316.97  5001.0  317.47
  5004.5  317.47  5008.3  321.39  5022.5  322.82  5049.1  322.10  5143.0  322.19
  5256.0  326.32  5341.4  338.68  5376.5  340.97  5384.1  343.81  5405.0  346.82
  5426.4  351.54  5433.5  355.29  5462.0  360.34  5468.6  359.62  5532.7  368.01
#Mann=4,-1,0
  4681.0    0.16       0  4995.0    0.07       0  5001.0    0.16       0
  5049.1    0.05       0
Bank Sta=4995,5001
Exp/Cntr=0.3,0.1

Type RM Length L Ch R = 1,5318,425,425,425
BEGIN DESCRIPTION:
UNT089 IN BECR 9.0
END DESCRIPTION:
XS GIS Cut Line= 3
      3782099.61     10532360.20      3782249.61     10532760.19
      3782649.63     10533160.21
#Sta/Elev= 30
  4575.5  370.22  4607.5  368.46  4645.8  363.73  4651.1  360.63  4660.9  357.81
  4670.7  356.83  4682.3  352.17  4756.2  343.22  4791.8  333.83  4831.8  327.53
  4846.9  326.92  4871.9  322.09  4877.2  322.60  4902.1  318.86  4987.6  318.77
  4989.9  314.88  4992.6  314.38  4995.9  314.88  5016.8  318.97  5031.0  317.84
  5130.4  317.79  5172.4  319.68  5200.7  323.22  5257.2  334.61  5299.7  339.32
  5342.1  342.16  5360.3  345.00  5384.5  347.21  5447.9  356.25  5568.4  369.68
#Mann=6,-1,0
  4575.5    0.16       0  4989.9    0.07       0  4995.9    0.16       0
  5130.4    0.05       0  5360.3    0.16       0  5447.9    0.05       0
Bank Sta=4989.9,4995.9
Exp/Cntr=0.3,0.1

Type RM Length L Ch R = 1,4893,606,606,606
BEGIN DESCRIPTION:
UNT089 IN BECR 8.0
END DESCRIPTION:
XS GIS Cut Line= 4
      3781604.90     10532871.80      3781896.59     10533080.15
      3782264.65     10533156.54      3782694.87     10533399.40
#Sta/Elev= 30
  4395.9  352.10  4424.1  351.27  4591.6  347.61  4834.2  339.49  4869.8  336.38
  4890.2  327.73  4951.5  316.27  4982.1  315.89  4999.6  312.46  5002.3  311.96
  5005.6  312.46  5012.8  315.69  5035.3  315.48  5076.8  314.64  5150.5  316.46
  5188.1  320.13  5217.0  326.08  5269.0  334.54  5284.9  336.30  5290.6  335.49
  5306.5  341.05  5312.3  340.03  5319.7  343.72  5333.9  345.13  5349.8  351.17
  5365.6  354.57  5371.5  359.05  5431.0  368.65  5517.3  380.58  5624.3  391.04
#Mann=8,-1,0
  4395.9    0.16       0  4424.1    0.05       0  4834.2    0.16       0
  4999.6    0.07       0  5005.6    0.16       0  5035.3    0.05       0
  5217.0    0.16       0  5431.0    0.05       0
Bank Sta=4999.6,5005.6
Exp/Cntr=0.3,0.1

Type RM Length L Ch R = 1,4287,464,464,464
BEGIN DESCRIPTION:
UNT089 IN BECR 7.0
END DESCRIPTION:
XS GIS Cut Line= 3
      3781486.89     10533503.76      3782097.98     10533656.54
      3782570.17     10533628.76
#Sta/Elev= 30
  4461.8  349.45  4681.1  337.51  4710.9  337.53  4716.1  336.10  4815.1  333.13
  4839.8  330.69  4875.9  323.60  4881.0  323.81  4887.2  320.82  4938.8  311.28
  4990.3  312.17  4996.6  310.46  4999.3  309.96  5002.6  310.46  5010.9  312.66
  5050.5  312.10  5133.4  311.77  5160.9  313.83  5203.5  321.34  5213.5  324.84
  5273.6  337.98  5281.8  341.68  5286.8  339.73  5293.7  343.96  5303.7  346.93
  5333.7  351.20  5383.8  364.21  5466.5  374.54  5524.1  382.70  5564.7  386.82
#Mann=6,-1,0
  4461.8    0.16       0  4996.6    0.07       0  5002.6    0.16       0
  5050.5    0.05       0  5160.9    0.16       0  5466.5    0.05       0
Bank Sta=4996.6,5002.6
Exp/Cntr=0.3,0.1

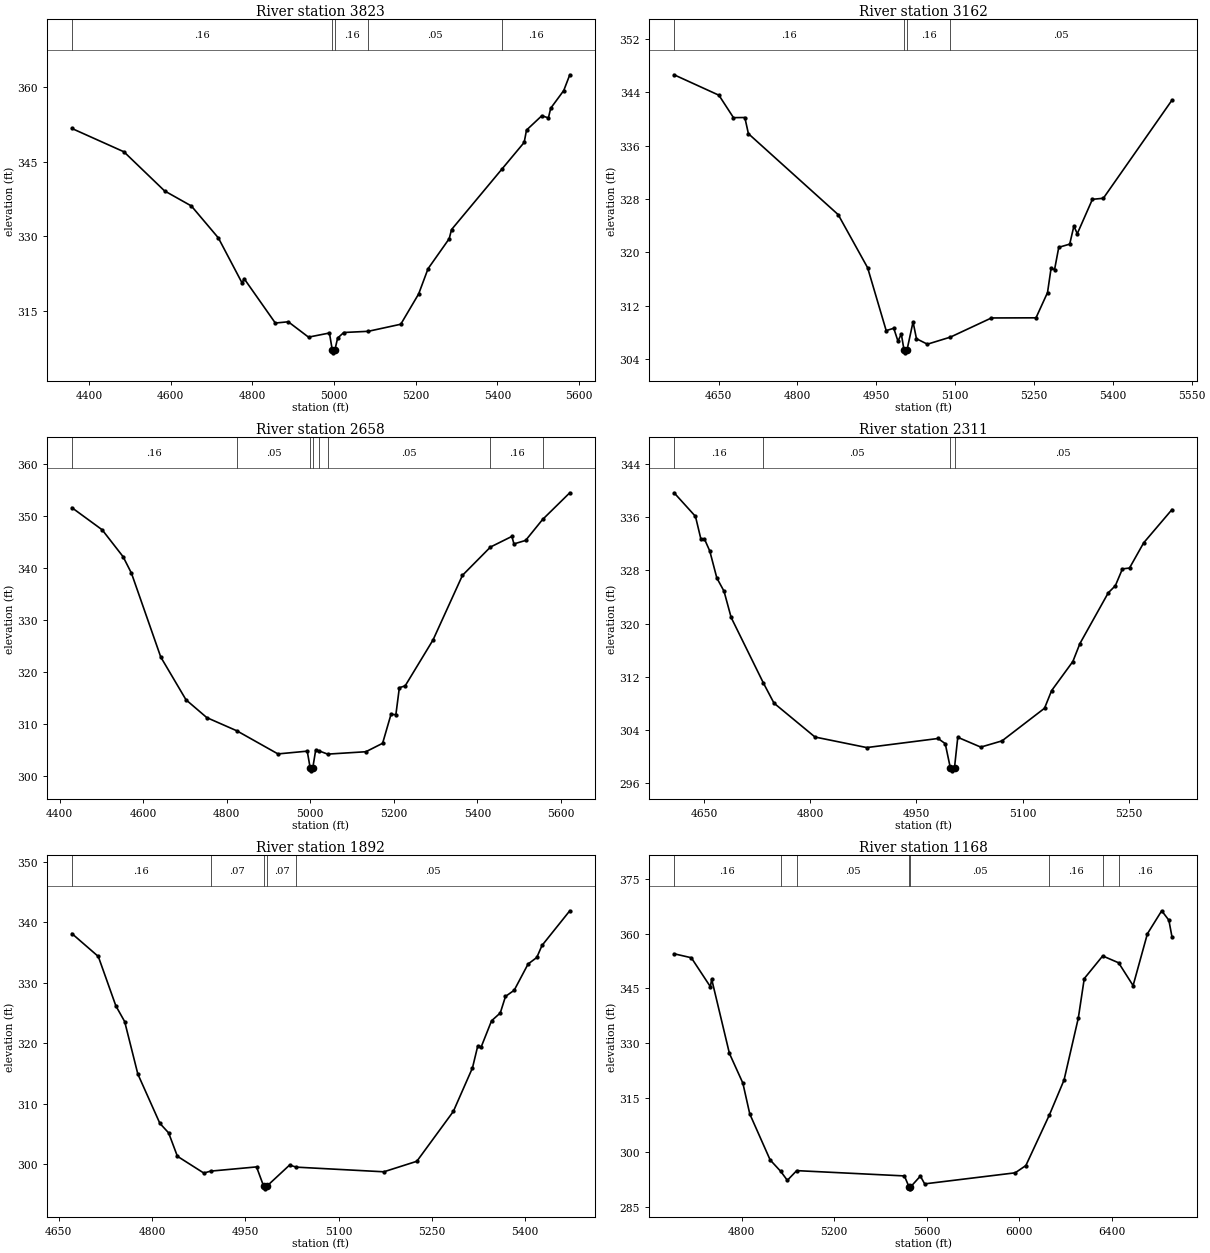
Type RM Length L Ch R = 1,3823,661,661,661
BEGIN DESCRIPTION:
UNT089 IN BECR 6.0
END DESCRIPTION:
XS GIS Cut Line= 4
      3781306.32     10533982.93      3781611.87     10534038.48
      3782007.70     10533989.87      3782452.15     10534239.87
#Sta/Elev= 30
  4357.9  351.64  4485.3  346.96  4584.9  339.11  4650.5  336.09  4716.6  329.68
  4774.7  320.64  4779.8  321.50  4856.1  312.60  4887.8  312.85  4937.4  309.77
  4988.6  310.60  4995.7  307.12  4998.4  306.62  5001.7  307.12  5008.7  309.58
  5023.7  310.70  5083.7  310.94  5163.3  312.36  5207.1  318.44  5230.1  323.50
  5281.9  329.52  5287.6  331.35  5410.5  343.44  5465.5  348.84  5471.2  351.31
  5508.8  354.20  5524.8  353.75  5530.5  355.70  5562.4  359.25  5577.2  362.41
#Mann=5,-1,0
  4357.9    0.16       0  4995.7    0.07       0  5001.7    0.16       0
  5083.7    0.05       0  5410.5    0.16       0
Bank Sta=4995.7,5001.7
Exp/Cntr=0.3,0.1

Type RM Length L Ch R = 1,3162,504,504,504
BEGIN DESCRIPTION:
UNT089 IN BECR 5.0
END DESCRIPTION:
XS GIS Cut Line= 3
      3781375.73     10534094.01      3781591.04     10534288.48
      3782104.80     10534698.11
#Sta/Elev= 30
  4565.4  346.66  4650.7  343.59  4678.4  340.22  4700.0  340.24  4706.8  337.81
  4877.6  325.65  4933.6  317.67  4968.9  308.23  4983.3  308.58  4991.3  306.65
  4997.7  307.71  5002.7  305.39  5005.5  304.89  5008.7  305.39  5020.0  309.54
  5026.5  307.01  5047.3  306.19  5091.0  307.25  5169.1  310.13  5253.9  310.15
  5275.8  313.94  5282.7  317.67  5289.1  317.35  5297.2  320.74  5318.0  321.22
  5326.0  323.94  5332.4  322.78  5361.2  327.95  5382.0  328.11  5512.6  342.85
#Mann=4,-1,0
  4565.4    0.16       0  5002.7    0.07       0  5008.7    0.16       0
  5091.0    0.05       0
Bank Sta=5002.7,5008.7
Exp/Cntr=0.3,0.1

Type RM Length L Ch R = 1,2658,347,347,347
BEGIN DESCRIPTION:
UNT089 IN BECR 4.0
END DESCRIPTION:
XS GIS Cut Line= 3
      3781077.18     10534760.71      3781847.98     10534802.37
      3782264.63     10534850.98
#Sta/Elev= 30
  4429.6  351.56  4502.1  347.31  4552.2  342.14  4572.2  338.97  4642.3  322.87
  4702.7  314.66  4752.5  311.24  4824.3  308.71  4922.7  304.27  4992.8  304.80
  4999.9  301.52  5002.6  301.02  5005.9  301.52  5012.9  304.96  5020.1  304.88
  5041.6  304.23  5133.1  304.69  5173.1  306.31  5193.1  311.84  5204.9  311.83
  5213.2  316.99  5227.1  317.34  5293.8  326.16  5364.2  338.57  5431.2  344.00
  5482.4  346.04  5487.4  344.60  5515.3  345.27  5555.9  349.29  5621.0  354.42
#Mann=8,-1,0
  4429.6    0.16       0  4824.3    0.05       0  4999.9    0.03       0
  5005.9    0.05       0  5020.1    0.16       0  5041.6    0.05       0
  5431.2    0.16       0  5555.9    0.05       0
Bank Sta=4999.9,5005.9
Exp/Cntr=0.3,0.1

Type RM Length L Ch R = 1,2311,419,419,419
BEGIN DESCRIPTION:
UNT089 IN BECR 3.0
END DESCRIPTION:
XS GIS Cut Line= 3
      3781249.64     10535160.18      3781649.61     10535110.19
      3781949.63     10535110.19
#Sta/Elev= 30
  4607.9  339.72  4638.1  336.16  4645.7  332.77  4650.7  332.77  4658.3  330.94
  4668.3  326.86  4678.4  324.88  4688.5  320.91  4734.0  311.03  4749.0  307.99
  4806.9  302.88  4880.0  301.29  4980.7  302.66  4990.8  301.88  4997.9  298.28
  5000.7  297.78  5003.9  298.28  5008.5  302.84  5041.0  301.36  5071.0  302.30
  5131.0  307.22  5141.0  309.88  5171.0  314.27  5181.0  316.98  5221.0  324.63
  5231.0  325.70  5241.0  328.24  5251.0  328.37  5271.0  332.17  5311.0  337.19
#Mann=4,-1,0
  4607.9    0.16       0  4734.0    0.05       0  4997.9    0.03       0
  5003.9    0.05       0
Bank Sta=4997.9,5003.9
Exp/Cntr=0.3,0.1

Type RM Length L Ch R = 1,1892,724,724,724
BEGIN DESCRIPTION:
UNT089 IN BECR 2.0
END DESCRIPTION:
XS GIS Cut Line= 3
      3781249.58     10535260.16      3781499.61     10535510.19
      3781899.60     10535710.18
#Sta/Elev= 30
  4671.0  338.16  4713.5  334.37  4741.8  326.18  4755.9  323.60  4777.1  314.91
  4812.5  306.76  4826.6  305.18  4840.7  301.31  4883.2  298.53  4894.1  298.85
  4968.0  299.55  4979.2  296.42  4981.9  295.92  4985.2  296.42  5021.1  299.85
  5032.0  299.51  5172.7  298.74  5225.8  300.48  5284.5  308.73  5315.3  315.94
  5323.7  319.53  5329.3  319.40  5346.0  323.73  5360.0  325.02  5368.4  327.76
  5382.4  328.78  5404.7  333.12  5418.7  334.20  5427.1  336.19  5471.8  341.93
#Mann=5,-1,0
  4671.0    0.16       0  4894.1    0.07       0  4979.2    0.07       0
  4985.2    0.07       0  5032.0    0.05       0
Bank Sta=4979.2,4985.2
Exp/Cntr=0.3,0.1

Type RM Length L Ch R = 1,1168,0,0,0
BEGIN DESCRIPTION:
UNT089 IN BECR 1.0
END DESCRIPTION:
XS GIS Cut Line= 4
      3780700.73     10535327.48      3781075.74     10536035.83
      3781284.07     10536167.77      3782325.20     10535799.91
#Sta/Elev= 30
  4508.1  354.45  4582.6  353.36  4665.0  345.43  4670.6  347.50  4747.3  327.15
  4805.4  319.01  4835.3  310.56  4923.3  297.97  4969.0  294.83  4997.7  292.37
  5038.2  295.03  5503.6  293.58  5524.0  290.54  5526.7  290.04  5530.0  290.54
  5572.7  293.53  5591.3  291.40  5982.6  294.43  6028.7  296.42  6130.9  310.36
  6193.7  319.84  6255.5  336.85  6281.2  347.66  6360.8  353.85  6429.7  351.98
  6492.3  345.73  6554.1  359.93  6615.9  366.23  6646.9  363.65  6660.4  359.07
#Mann=8,-1,0
  4508.1    0.16       0  4969.0    0.12       0  5038.2    0.05       0
  5524.0    0.07       0  5530.0    0.05       0  6130.9    0.16       0
  6360.8    0.05       0  6429.7    0.16       0
Bank Sta=5524,5530
Exp/Cntr=0.3,0.1

Chan Stop Cuts=-1