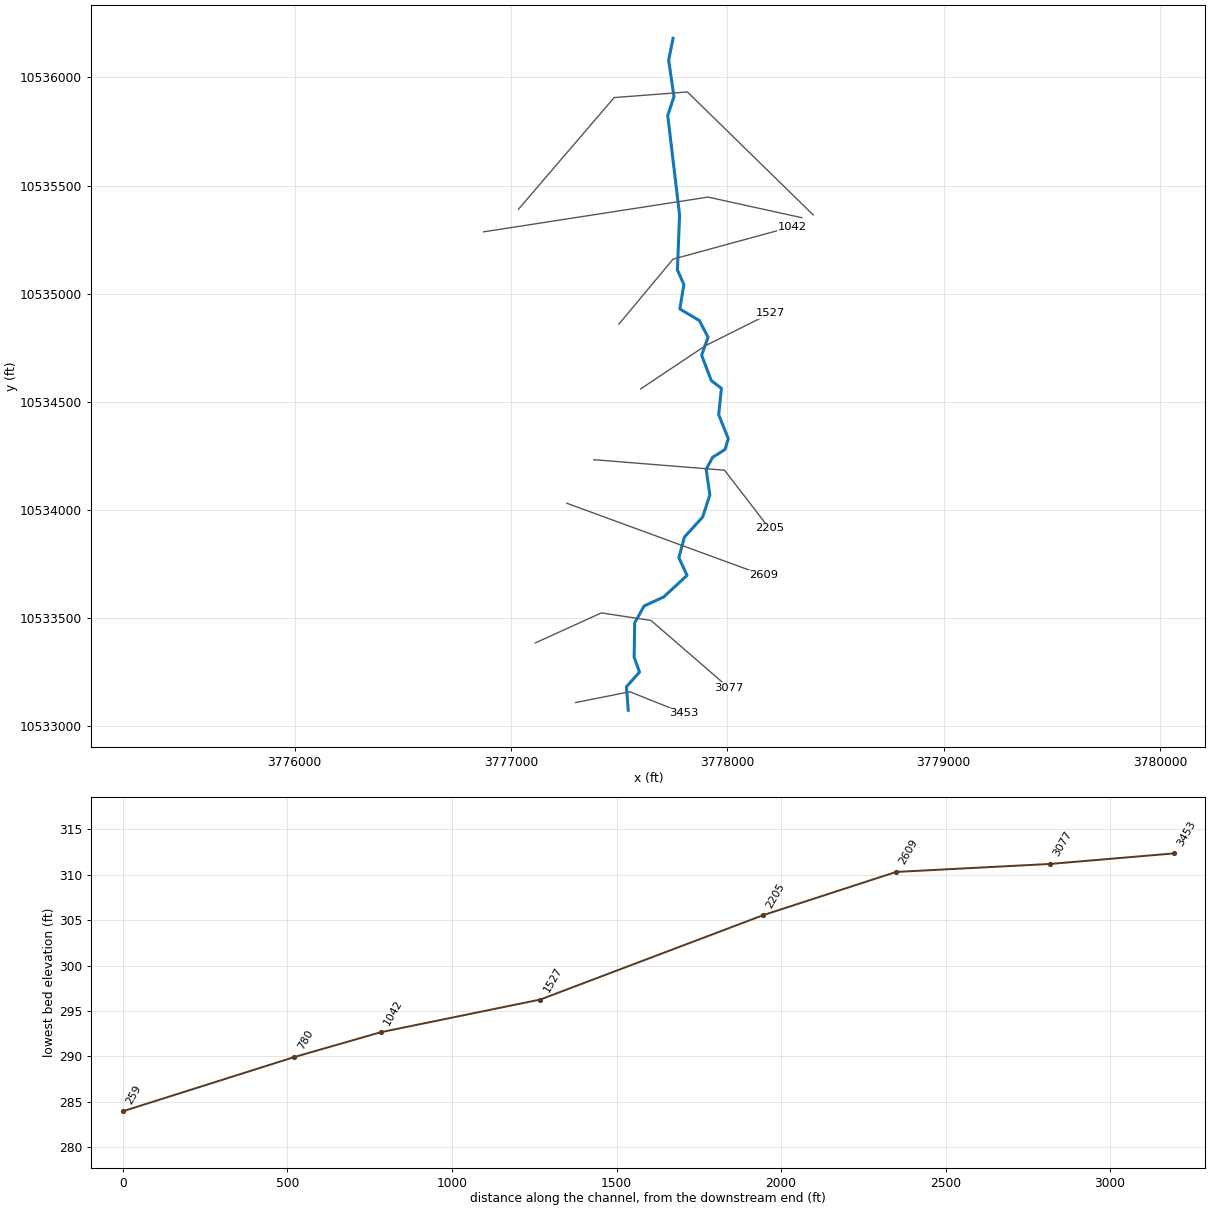
--- UNT090 IN BECR.prj (project) ---

Proj Title=UNT090 IN BECR Base Level Engineering
Current Plan=p01
Default Exp/Contr=0.3,0.1
English Units
Geom File=g01
Flow File=f01
Plan File=p01
Y Axis Title=Elevation
X Axis Title(PF)=Main Channel Distance
X Axis Title(XS)=Station
BEGIN DESCRIPTION:
UNT090 IN BECR
END DESCRIPTION:
DSS Export Rating Curves= 0
DSS Export Rating Curve Sorted= 0
DSS Export Volume Flow Curves= 0
DXF OffsetX= 0
DXF OffsetY= 0
DXF ScaleX= 1
DXF ScaleY= 10

--- UNT090 IN BECR.p01 (plan) ---

Plan Title=Multiple Run
Short Identifier=Multiple
Geom File=g01
Flow File=f01
Subcritical Flow
K Sum by GR= 0
Std Step Tol= 0.01
Critical Tol= 0.01
Num of Std Step Trials= 20
Max Error Tol= 0.3
Flow Tol Ratio= 0.001
Split Flow NTrial= 30
Split Flow Tol= 0.02
Split Flow Ratio= 0.02
Log Output Level= 0
Friction Slope Method= 1
Unsteady Friction Slope Method= 2
Unsteady Bridges Friction Slope Method= 1
Parabolic Critical Depth
Global Vel Dist=  1 , 1 , 1
Global Log Level= 0
CheckData=True
Encroach Param= -1, 0, 0, 0
BEGIN DESCRIPTION:
Multiple Run
END DESCRIPTION:

--- UNT090 IN BECR.f01 (steady flow) ---

Flow Title=Multiple
Number of Profiles=7
Profile Names=10-year,25-year,50-year,1pct_min,100-year,1pct_plu,500-year
River Rch & RM= UNT090 IN BECR,Reach-1,3453
     609     831    1018     917    1240    1677    1846
Boundary for River Rch & Prof#=UNT090 IN BECR,Reach-1,1
Up Type=0
Dn Type=3
Dn Slope=0.005
Boundary for River Rch & Prof#=UNT090 IN BECR,Reach-1,2
Up Type=0
Dn Type=3
Dn Slope=0.005
Boundary for River Rch & Prof#=UNT090 IN BECR,Reach-1,3
Up Type=0
Dn Type=3
Dn Slope=0.005
Boundary for River Rch & Prof#=UNT090 IN BECR,Reach-1,4
Up Type=0
Dn Type=3
Dn Slope=0.005
Boundary for River Rch & Prof#=UNT090 IN BECR,Reach-1,5
Up Type=0
Dn Type=3
Dn Slope=0.005
Boundary for River Rch & Prof#=UNT090 IN BECR,Reach-1,6
Up Type=0
Dn Type=3
Dn Slope=0.005
Boundary for River Rch & Prof#=UNT090 IN BECR,Reach-1,7
Up Type=0
Dn Type=3
Dn Slope=0.005

--- UNT090 IN BECR.g01 (geometry) ---

Geom Title=Existing Conditions
Program Version=4.10

River Reach=UNT090 IN BECR  ,Reach-1
Reach XY= 30
      3777542.45     10533074.84        3777534.       10533183.
       3777594.5       10533251.      3777569.75       10533320.
      3777572.25       10533479.      3777616.25       10533557.
      3777705.75       10533598.      3777814.25       10533698.
       3777776.5       10533780.        3777802.       10533875.
       3777886.5       10533968.      3777919.75       10534070.
      3777902.75       10534189.       3777932.5       10534244.
      3777989.75       10534280.        3778005.       10534330.
       3777960.5       10534441.      3777973.25       10534563.
      3777926.25       10534599.      3777881.75       10534716.
      3777911.25       10534799.       3777871.5       10534876.
        3777781.       10534930.      3777799.75       10535043.
      3777769.75       10535110.      3777779.75       10535364.
        3777725.       10535824.      3777753.75       10535912.
      3777729.25       10536080.       3777749.5       10536181.

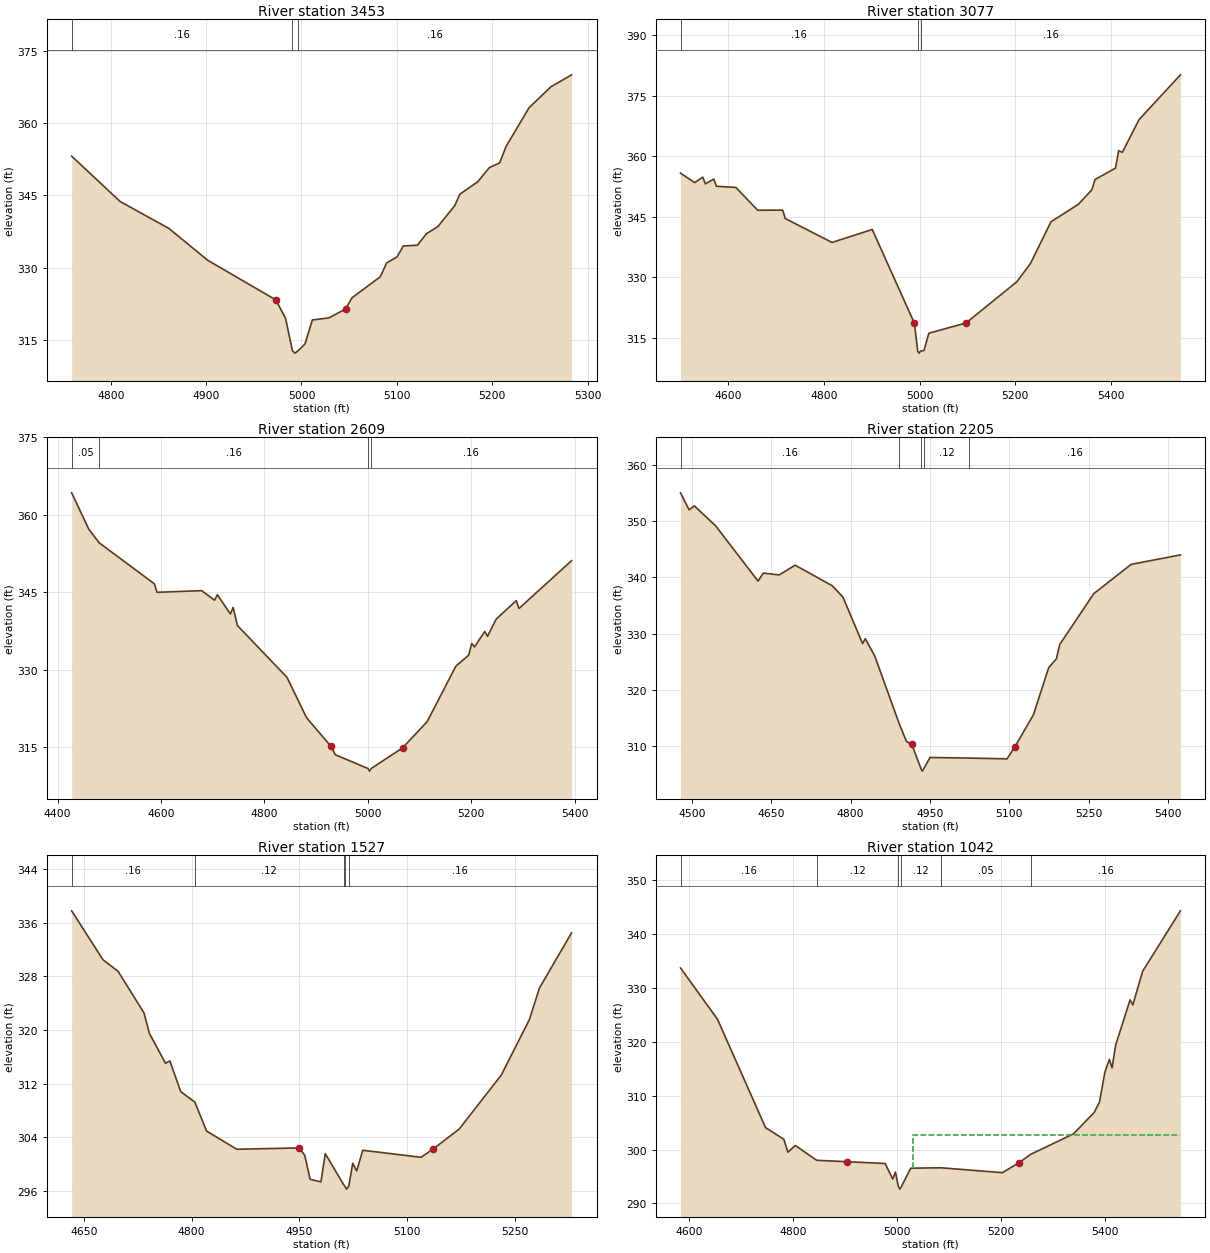
Type RM Length L Ch R = 1 ,3453    ,376,376,376
BEGIN DESCRIPTION:
UNT090 IN BECR 7.0
END DESCRIPTION:
XS GIS Cut Line= 3
      3777299.65      10533110.2      3777549.61     10533160.19
      3777799.64     10533060.18
#Sta/Elev= 30
    4759  353.14  4809.9  343.74  4860.9  338.18  4901.7  331.58  4973.1  323.38
  4983.3  319.56  4990.5  312.86  4993.3  312.36  4996.5  312.86  5003.7  314.27
  5011.4  319.23  5028.7  319.65  5046.2  321.49  5052.9  323.81  5082.6  328.16
  5089.3  331.03  5100.1  332.27  5106.8  334.54  5121.6   334.7    5131  337.08
  5143.1  338.57  5160.7  342.89    5166  345.25  5184.9  347.85    5197  350.76
  5207.8  351.74  5214.5  355.14  5238.7  363.18  5261.6   367.5  5283.2  369.97
#Mann= 3 ,-1 , 0
    4759     .16       0  4990.5     .07       0  4996.5     .16       0
Bank Sta=4973.1,5046.2
XS Rating Curve= 0 ,0
Exp/Cntr=0.3,0.1

Type RM Length L Ch R = 1 ,3077    ,468,468,468
BEGIN DESCRIPTION:
UNT090 IN BECR 6.0
END DESCRIPTION:
XS GIS Cut Line= 4
      3777112.63     10533385.77      3777418.19     10533524.66
      3777647.36     10533489.94      3778008.49     10533177.42
#Sta/Elev= 30
  4500.4  355.82    4530  353.48  4546.9  354.83  4552.4  353.17    4570  354.35
  4575.5  352.57  4616.1  352.28  4661.8  346.63  4713.9  346.66  4719.4  344.57
  4817.1  338.64  4901.2  341.85  4989.2  318.65  4996.3   311.7  4999.1   311.2
  5002.3   311.7  5009.4  311.87  5019.5  316.13  5097.2  318.68  5203.5   328.9
    5232  333.43  5274.8  343.77  5331.8  348.07  5360.3   351.7  5366.9  354.24
  5409.7  357.07  5416.3  361.38  5423.9  360.97    5459  369.11  5545.4   380.2
#Mann= 3 ,-1 , 0
  4500.4     .16       0  4996.3     .07       0  5002.3     .16       0
Bank Sta=4989.2,5097.2
XS Rating Curve= 0 ,0
Exp/Cntr=0.3,0.1

Type RM Length L Ch R = 1 ,2609    ,404,404,404
BEGIN DESCRIPTION:
UNT090 IN BECR 5.0
END DESCRIPTION:
XS GIS Cut Line= 2
      3777258.45     10534031.61      3778166.41     10533698.92
#Sta/Elev= 30
  4427.1  364.23  4460.3  357.18  4480.3  354.55  4586.9  346.62  4592.3  344.96
  4678.5  345.28  4703.6  343.43    4709  344.49  4734.1  340.76  4739.5  342.03
  4747.8  338.52  4843.7  328.48  4881.4  320.68  4928.9  315.11  4937.1   313.5
  5000.4  310.82  5003.2  310.32  5006.4  310.82  5067.3  314.83  5114.8  319.91
  5170.5  330.68  5195.1  332.77    5201  335.06  5206.3  334.38  5226.2  337.37
  5231.5  336.43  5248.4  339.78  5287.2  343.35  5292.5  341.83  5394.1  351.09
#Mann= 4 ,-1 , 0
  4427.1     .05       0  4480.3     .16       0  5000.4     .07       0
  5006.4     .16       0
Bank Sta=4928.9,5067.3
XS Rating Curve= 0 ,0
Exp/Cntr=0.3,0.1

Type RM Length L Ch R = 1 ,2205    ,678,678,678
BEGIN DESCRIPTION:
UNT090 IN BECR 4.0
END DESCRIPTION:
XS GIS Cut Line= 3
      3777383.49     10534232.99      3777987.64     10534184.38
      3778194.63     10533915.29
#Sta/Elev= 30
  4478.2  354.99  4494.4  351.97  4504.4  352.67  4544.5  349.14  4624.8  339.32
  4634.8  340.73  4664.9  340.41    4695  342.14  4765.2  338.49  4785.3  336.49
  4822.6  328.21  4827.7  329.09  4845.5  326.03  4891.7  314.03  4905.7  310.81
  4915.7  310.31  4932.8  306.06  4935.5  305.56  4938.8  306.06  4950.2  307.98
  5024.7  307.88  5095.8  307.74  5110.3  309.81  5145.7  315.56  5174.7  323.95
  5189.2  325.52  5195.5  328.05  5259.8  337.07  5330.5  342.28  5423.8  343.97
#Mann= 5 ,-1 , 0
  4478.2     .16       0  4891.7     .12       0  4932.8     .07       0
  4938.8     .12       0  5024.7     .16       0
Bank Sta=4915.7,5110.3
XS Rating Curve= 0 ,0
Exp/Cntr=0.3,0.1

Type RM Length L Ch R = 1 ,1527    ,485,485,485
BEGIN DESCRIPTION:
UNT090 IN BECR 3.0
END DESCRIPTION:
XS GIS Cut Line= 3
      3777599.58     10534560.17      3777899.61     10534760.19
      3778199.61     10534910.19
#Sta/Elev= 30
  4633.1  337.79  4676.7  330.49  4697.7  328.77  4733.8  322.56  4741.3  319.51
  4763.8  315.03  4769.8   315.4  4784.9  310.82  4804.7  309.23  4820.9  304.93
    4863  302.21  4950.1  302.41  4957.6  301.31  4965.1  297.73  4980.2  297.34
  4986.2  301.56    5012  296.88  5013.1  296.76  5015.8  296.26  5019.1  296.76
  5024.4  300.12    5030  298.98  5038.4  302.06  5119.5  301.01  5136.2  302.23
  5172.6  305.22  5231.3  313.29  5270.4  321.56  5284.4  326.27  5329.1   334.5
#Mann= 5 ,-1 , 0
  4633.1     .16       0  4804.7     .12       0    5012     .16       0
  5013.1     .07       0  5019.1     .16       0
Bank Sta=4950.1,5136.2
XS Rating Curve= 0 ,0
Exp/Cntr=0.3,0.1

Type RM Length L Ch R = 1 ,1042    ,262,262,262
BEGIN DESCRIPTION:
UNT090 IN BECR 2.0
END DESCRIPTION:
XS GIS Cut Line= 3
       3777499.6     10534860.18      3777749.61     10535160.19
       3778299.6     10535310.19
#Sta/Elev= 30
  4583.8  333.63  4654.8  324.13  4747.2  304.05  4782.3   301.9  4790.1   299.5
  4804.5  300.74  4845.5     298  4903.4  297.74  4976.9  297.41  4991.6  294.53
  4996.8  295.81  5002.4  293.16  5005.2  292.66  5008.4  293.16  5026.1  296.54
  5084.5  296.61  5202.4  295.71  5233.5  297.51  5256.8  299.11  5338.8  302.89
  5378.6  306.85  5388.9  308.79  5399.3  314.33  5407.9  316.69  5413.1  315.14
    5420  319.35  5447.7  327.72  5452.9  326.77  5471.9  333.03  5544.4  344.21
#Mann= 6 ,-1 , 0
  4583.8     .16       0  4845.5     .12       0  5002.4     .07       0
  5008.4     .12       0  5084.5     .05       0  5256.8     .16       0
#XS Ineff= 2 , 0
                            5030          302.69
Permanent Ineff=
       F       F
Bank Sta=4903.4,5233.5
XS Rating Curve= 0 ,0
Exp/Cntr=0.3,0.1

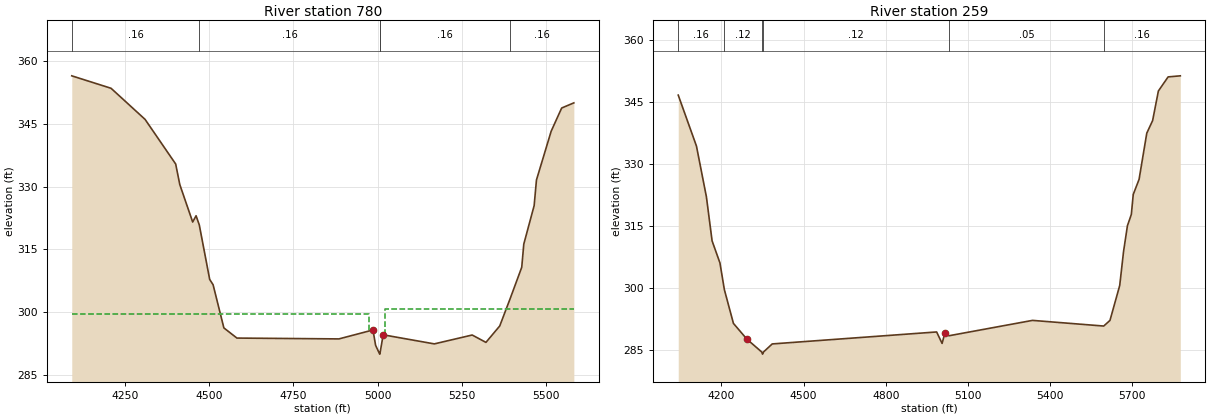
Type RM Length L Ch R = 1 ,780     ,521,521,521
BEGIN DESCRIPTION:
Mapping XS 9e0f086a
END DESCRIPTION:
XS GIS Cut Line= 3
      3776874.12     10535286.47      3777911.44     10535447.06
      3778344.99     10535351.67
#Sta/Elev= 30
  4090.4   356.5  4207.3  353.52  4308.5  346.08  4399.5  335.41  4411.8  330.48
  4450.1  321.53  4460.2  323.03  4469.8  320.82  4500.7   307.8  4510.8  306.53
  4542.9   296.2  4581.7  293.77  4885.2  293.57  4986.4  295.71  4994.3  292.04
  5006.4  289.93  5006.9  289.93  5016.8  294.55  5168.9  292.38  5281.6   294.5
  5322.5  292.74  5363.5  296.66  5394.2  303.13    5429  310.71  5435.1  316.25
  5465.9  325.46  5472.8  331.59  5516.5  343.24  5547.8   348.8    5584  350.03
#Mann= 5 ,-1 , 0
  4090.4     .16       0  4469.8     .16       0  5006.4     .07       0
  5006.9     .16       0  5394.2     .16       0
#XS Ineff= 2 , 0
         4975.45  299.52 5020.91          300.73
Permanent Ineff=
       F       F
Bank Sta=4986.4,5016.8
XS Rating Curve= 0 ,0
Exp/Cntr=0.3,0.1

Type RM Length L Ch R = 1 ,259     ,0,0,0
BEGIN DESCRIPTION:
UNT090 IN BECR 1.0
END DESCRIPTION:
XS GIS Cut Line= 4
      3777034.73     10535390.66      3777477.41     10535907.12
      3777815.96     10535933.17      3778397.26     10535364.88
#Sta/Elev= 30
  4042.7  346.69  4109.2  334.35  4145.5  322.07  4166.3  311.39  4194.9  306.06
  4211.2  299.55  4244.2   291.4  4293.6  287.57  4347.7  284.46  4350.5  283.96
  4353.7  284.46  4385.8  286.43  4985.9  289.33  5005.9  286.55    5016  289.09
  5030.9  288.41  5335.8  292.13  5595.9  290.76  5618.7  292.13  5654.2  300.58
  5668.3  308.85  5682.4  315.06  5696.6  317.79  5703.6  322.63  5724.9  326.29
    5753  337.47  5774.3  340.52  5795.4  347.69  5830.9   351.1  5875.4  351.36
#Mann= 6 ,-1 , 0
  4042.7     .16       0  4211.2     .12       0  4347.7     .07       0
  4353.7     .12       0  5030.9     .05       0  5595.9     .16       0
Bank Sta=4293.6,5016
XS Rating Curve= 0 ,0
Exp/Cntr=0.3,0.1

Chan Stop Cuts=-1
Use User Specified Reach Order=0
Composite Channel Slope=5