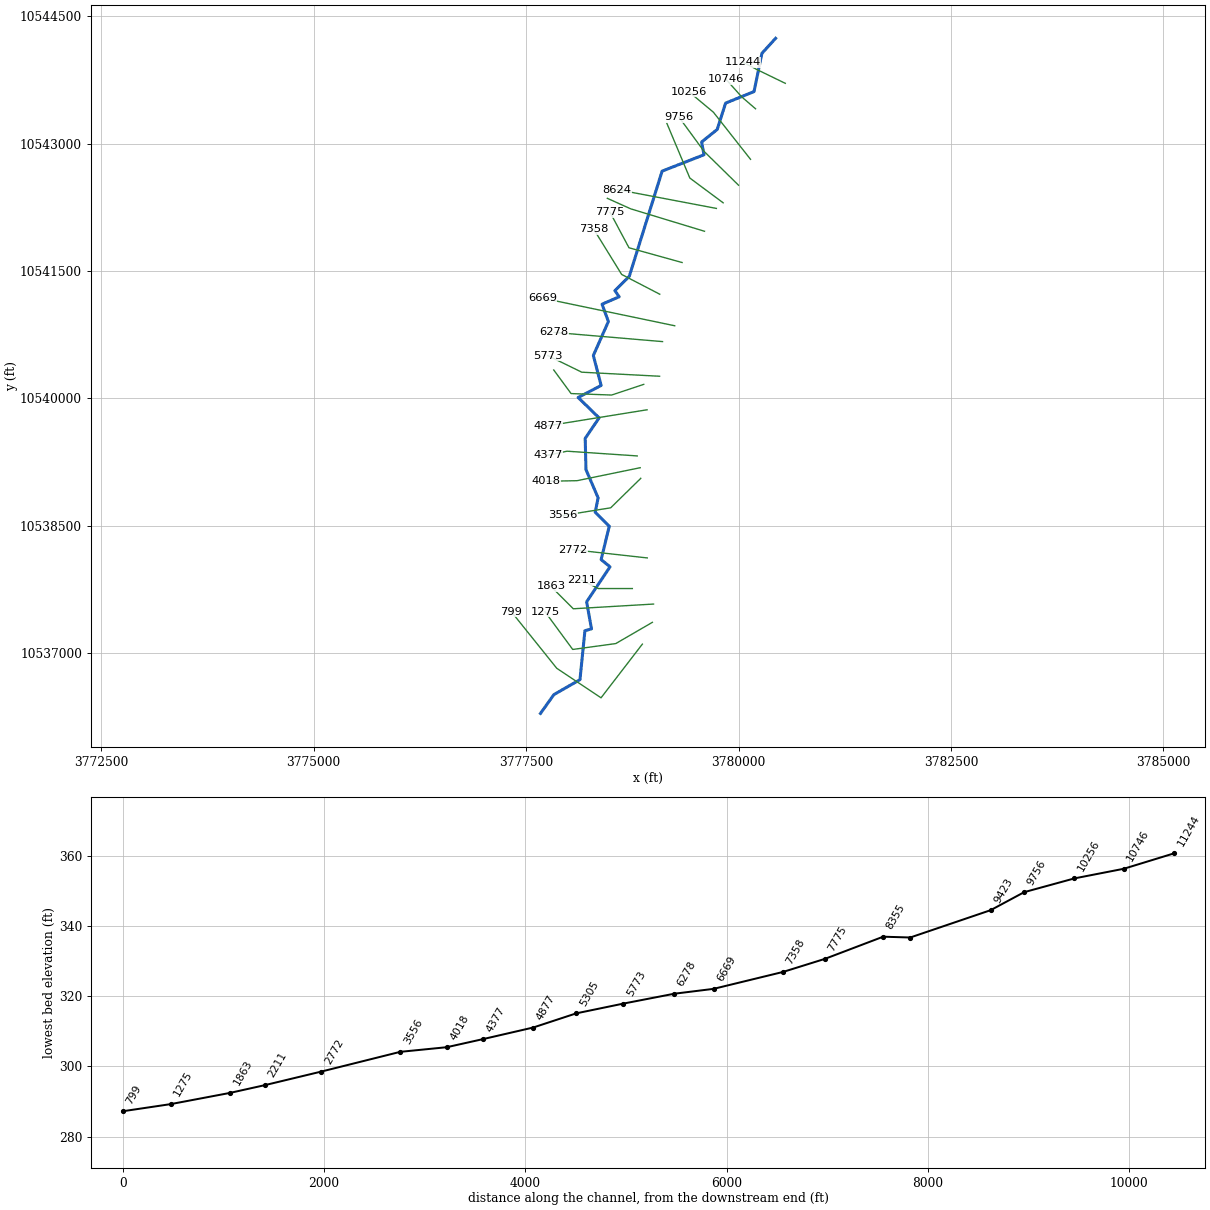
--- UNT092 IN BECR.prj (project) ---

Proj Title=UNT092 IN BECR Base Level Engineering
Current Plan=p01
Default Exp/Contr=0.3,0.1
English Units
Geom File=g01
Flow File=f01
Plan File=p01
BEGIN DESCRIPTION:
UNT092 IN BECR
END DESCRIPTION:

--- UNT092 IN BECR.p01 (plan) ---

Plan Title=Multiple Run
Short Identifier=Multiple
Geom File=g01
Flow File=f01
Subcritical Flow
K Sum by GR= 0
Std Step Tol= 0.01
Critical Tol= 0.01
Num of Std Step Trials= 20
Max Error Tol= 0.3
Flow Tol Ratio= 0.001
Split Flow NTrial= 30
Split Flow Tol= 0.02
Split Flow Ratio= 0.02
Log Output Level= 0
Friction Slope Method= 1
Unsteady Friction Slope Method= 2
Unsteady Bridges Friction Slope Method= 1
Parabolic Critical Depth
Global Vel Dist=  1 , 1 , 1
Global Log Level= 0
CheckData=True
Encroach Param= -1, 0, 0, 0
BEGIN DESCRIPTION:
Multiple Run
END DESCRIPTION:

--- UNT092 IN BECR.f01 (steady flow) ---

Flow Title=Multiple
Number of Profiles=7
Profile Names=10-year,25-year,50-year,1pct_min,100-year,1pct_plu,500-year
River Rch & RM= UNT092 IN BECR,Reach-1,11244
     594     804     978     875    1183    1599    1736
River Rch & RM= UNT092 IN BECR,Reach-1,10256
     954    1326    1642    1492    2018    2730    3062
River Rch & RM= UNT092 IN BECR,Reach-1,6669
    1056    1473    1828    1665    2252    3045    3429
River Rch & RM= UNT092 IN BECR,Reach-1,4877
    1125    1573    1955    1782    2411    3260    3681
Boundary for River Rch & Prof#=UNT092 IN BECR,Reach-1,1
Up Type=0
Dn Type=3
Dn Slope=0.005
Boundary for River Rch & Prof#=UNT092 IN BECR,Reach-1,2
Up Type=0
Dn Type=3
Dn Slope=0.005
Boundary for River Rch & Prof#=UNT092 IN BECR,Reach-1,3
Up Type=0
Dn Type=3
Dn Slope=0.005
Boundary for River Rch & Prof#=UNT092 IN BECR,Reach-1,4
Up Type=0
Dn Type=3
Dn Slope=0.005
Boundary for River Rch & Prof#=UNT092 IN BECR,Reach-1,5
Up Type=0
Dn Type=3
Dn Slope=0.005
Boundary for River Rch & Prof#=UNT092 IN BECR,Reach-1,6
Up Type=0
Dn Type=3
Dn Slope=0.005
Boundary for River Rch & Prof#=UNT092 IN BECR,Reach-1,7
Up Type=0
Dn Type=3
Dn Slope=0.005

--- UNT092 IN BECR.g01 (geometry) ---

Geom Title=Existing Conditions

River Reach=UNT092 IN BECR,Reach-1
Reach XY= 30
      3780435.75     10544240.00      3780274.50     10544063.00
      3780181.75     10543613.00      3779847.00     10543477.00
      3779748.50     10543167.00      3779564.75     10543019.00
      3779593.25     10542869.00      3779100.00     10542676.00
      3778713.50     10541437.00      3778544.50     10541269.00
      3778594.50     10541196.00      3778393.00     10541109.00
      3778467.75     10540905.00      3778290.75     10540505.00
      3778382.25     10540152.00      3778111.75     10540010.00
      3778358.75     10539770.00      3778194.75     10539529.00
      3778204.00     10539161.00      3778346.75     10538829.00
      3778312.50     10538658.00      3778478.00     10538494.00
      3778382.50     10538101.00      3778487.00     10538016.00
      3778211.75     10537604.00      3778268.75     10537285.00
      3778191.50     10537264.00      3778133.25     10536687.00
      3777826.25     10536511.00      3777668.75     10536290.00

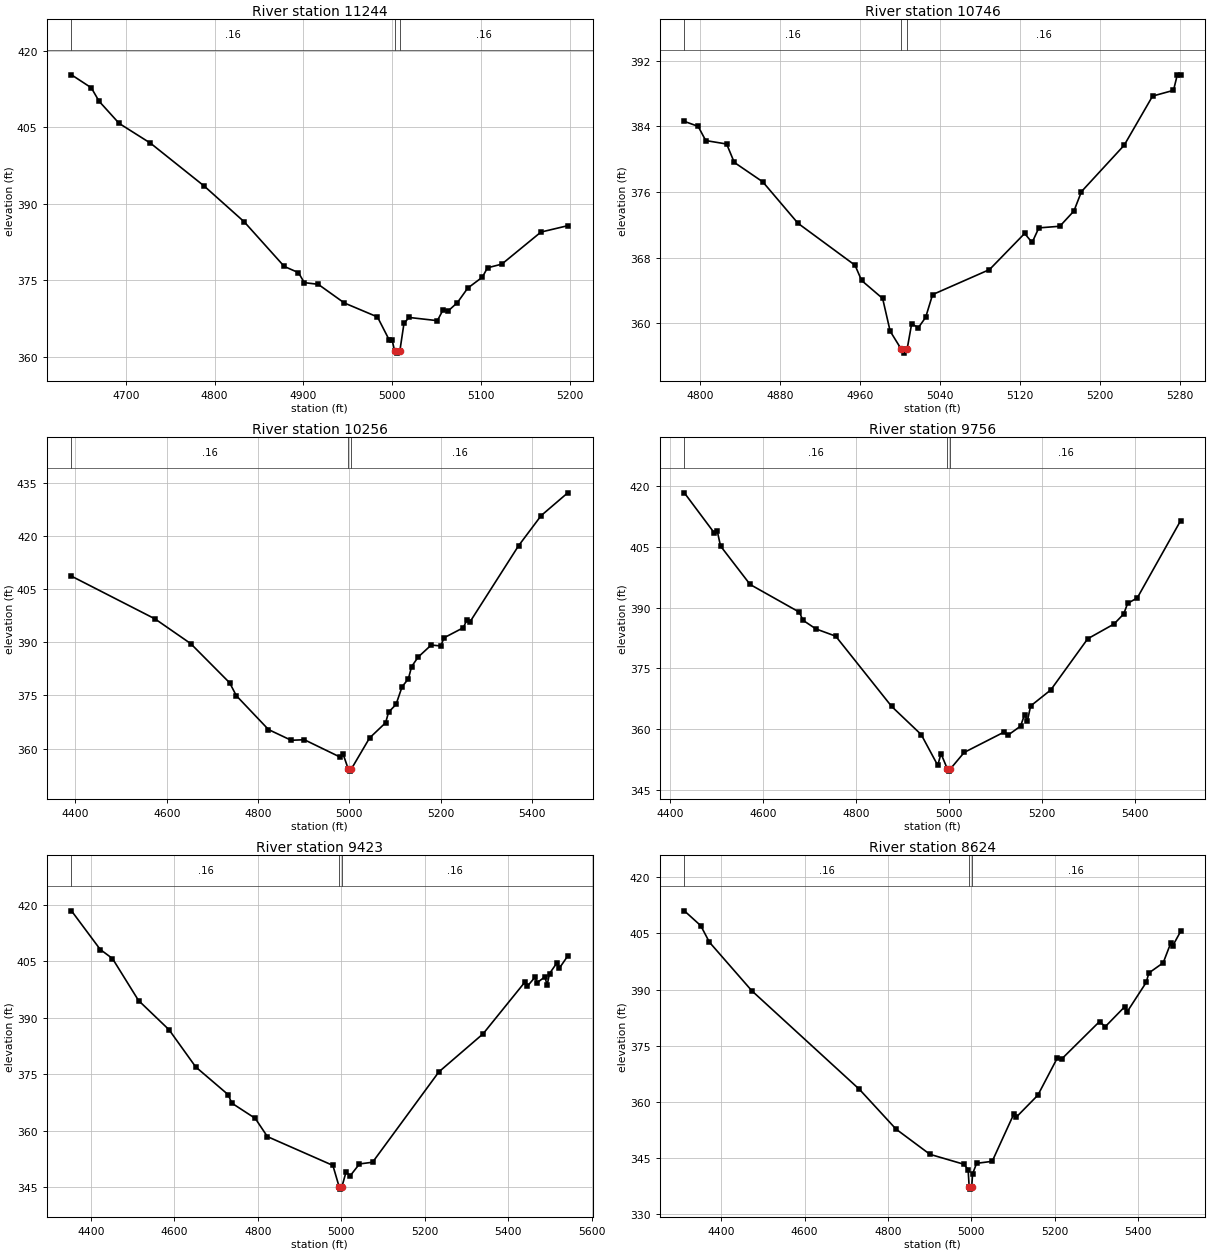
Type RM Length L Ch R = 1,11244,498,498,498
BEGIN DESCRIPTION:
UNT092 IN BECR 21.0
END DESCRIPTION:
XS GIS Cut Line= 3
      3780549.64     10543710.17      3780224.75     10543868.00
      3780049.63     10543960.18
#Sta/Elev= 30
  4638.8  415.33  4661.1  412.79  4669.9  410.15  4692.5  405.80  4727.8  401.92
  4788.3  393.51  4833.4  386.49  4878.5  377.74  4894.5  376.52  4901.1  374.56
  4916.8  374.23  4946.2  370.57  4983.5  367.83  4996.8  363.30  5000.0  363.30
  5002.8  361.23  5005.6  360.73  5008.8  361.23  5013.4  366.58  5019.1  367.73
  5051.0  367.10  5057.5  369.24  5063.2  369.01  5073.6  370.65  5085.2  373.48
  5101.6  375.62  5107.5  377.47  5123.6  378.19  5167.7  384.48  5197.9  385.73
#Mann=3,-1,0
  4638.8    0.16       0  5002.8    0.07       0  5008.8    0.16       0
Bank Sta=5002.8,5008.8
Exp/Cntr=0.3,0.1

Type RM Length L Ch R = 1,10746,490,490,490
BEGIN DESCRIPTION:
UNT092 IN BECR 20.0
END DESCRIPTION:
XS GIS Cut Line= 3
      3780199.62     10543410.18      3780036.50     10543551.00
      3779849.62     10543760.18
#Sta/Elev= 30
  4784.5  384.59  4798.3  383.98  4805.9  382.25  4826.8  381.83  4834.4  379.59
  4862.9  377.22  4898.1  372.17  4955.1  367.06  4961.7  365.20  4982.7  363.01
  4990.2  359.03  5001.2  356.85  5004.0  356.35  5007.2  356.85  5011.7  359.93
  5018.4  359.45  5025.7  360.71  5032.6  363.48  5089.5  366.53  5124.6  370.93
  5132.1  369.83  5138.8  371.61  5159.8  371.81  5173.9  373.67  5181.4  376.03
  5224.1  381.68  5252.5  387.67  5273.4  388.37  5277.2  390.26  5280.5  390.26
#Mann=3,-1,0
  4784.5    0.16       0  5001.2    0.07       0  5007.2    0.16       0
Bank Sta=5001.2,5007.2
Exp/Cntr=0.3,0.1

Type RM Length L Ch R = 1,10256,500,500,500
BEGIN DESCRIPTION:
UNT092 IN BECR 19.0
END DESCRIPTION:
XS GIS Cut Line= 3
      3780140.64     10542815.12      3779703.13     10543370.69
      3779411.48     10543613.73
#Sta/Elev= 30
  4391.3  408.70  4574.2  396.63  4652.3  389.65  4737.8  378.55  4752.2  374.94
  4822.7  365.36  4872.4  362.33  4901.3  362.48  4979.9  357.56  4986.3  358.35
  4997.7  354.11  5000.5  353.61  5003.7  354.11  5044.1  362.98  5079.3  367.29
  5085.7  370.28  5102.0  372.44  5115.3  377.45  5129.1  379.70  5136.2  383.16
  5150.5  385.84  5179.1  389.24  5199.9  388.98  5207.2  391.29  5249.4  394.13
  5257.2  396.36  5263.7  395.72  5370.5  417.32  5419.9  425.82  5478.1  432.25
#Mann=3,-1,0
  4391.3    0.16       0  4997.7    0.07       0  5003.7    0.16       0
Bank Sta=4997.7,5003.7
Exp/Cntr=0.3,0.1

Type RM Length L Ch R = 1,9756,333,333,333
BEGIN DESCRIPTION:
UNT092 IN BECR 18.0
END DESCRIPTION:
XS GIS Cut Line= 3
      3779999.62     10542510.18      3779593.50     10542909.00
      3779299.62     10543310.17
#Sta/Elev= 30
  4430.8  418.33  4494.5  408.54  4501.5  408.93  4508.6  405.21  4572.2  395.72
  4678.3  388.87  4685.3  386.93  4713.6  384.76  4756.1  382.97  4876.3  365.64
  4939.9  358.69  4975.4  351.11  4982.4  354.00  4996.2  350.18  4999.0  349.68
  5002.2  350.18  5032.2  354.29  5117.9  359.31  5125.4  358.47  5153.4  360.78
  5161.9  363.61  5168.1  362.12  5175.0  365.75  5218.3  369.71  5297.7  382.33
  5354.1  385.96  5375.0  388.44  5383.4  391.04  5404.3  392.43  5497.3  411.45
#Mann=3,-1,0
  4430.8    0.16       0  4996.2    0.07       0  5002.2    0.16       0
Bank Sta=4996.2,5002.2
Exp/Cntr=0.3,0.1

Type RM Length L Ch R = 1,9423,799,799,799
BEGIN DESCRIPTION:
UNT092 IN BECR 17.0
END DESCRIPTION:
XS GIS Cut Line= 3
      3779818.55     10542302.96      3779426.20     10542594.62
      3779155.37     10543240.45
#Sta/Elev= 30
  4353.7  418.36  4422.7  408.10  4451.9  405.71  4514.4  394.57  4587.5  386.82
  4651.4  376.96  4729.3  369.59  4737.7  367.37  4794.0  363.32  4823.2  358.48
  4980.1  350.84  4995.4  345.05  4998.2  344.55  5001.4  345.05  5011.3  348.97
  5022.1  348.16  5043.8  351.23  5075.2  351.68  5234.1  375.65  5340.0  385.74
  5440.5  399.50  5445.9  398.33  5464.3  400.74  5469.7  399.33  5488.1  400.84
  5493.5  398.65  5499.2  401.72  5517.3  404.61  5522.7  403.14  5542.9  406.38
#Mann=3,-1,0
  4353.7    0.16       0  4995.4    0.07       0  5001.4    0.16       0
Bank Sta=4995.4,5001.4
Exp/Cntr=0.3,0.1

Type RM Length L Ch R = 1,8624,269,269,269
BEGIN DESCRIPTION:
UNT092 IN BECR 16.0
END DESCRIPTION:
XS GIS Cut Line= 2
      3779738.75     10542236.98      3778568.56     10542459.21
#Sta/Elev= 30
  4311.5  411.05  4350.9  407.09  4371.7  402.68  4473.5  389.71  4731.9  363.38
  4819.6  352.78  4901.0  346.05  4982.4  343.40  4992.6  341.98  4995.2  337.26
  4997.9  336.76  5001.2  337.26  5003.3  340.82  5013.0  343.65  5050.4  344.18
  5102.7  356.91  5107.8  355.93  5160.0  361.84  5206.4  371.70  5217.3  371.51
  5308.1  381.50  5321.8  380.13  5369.0  385.51  5374.1  384.06  5420.1  391.95
  5426.3  394.45  5460.8  397.17  5478.6  402.34  5483.7  401.72  5502.6  405.54
#Mann=3,-1,0
  4311.5    0.16       0  4995.2    0.07       0  5001.2    0.16       0
Bank Sta=4995.2,5001.2
Exp/Cntr=0.3,0.1

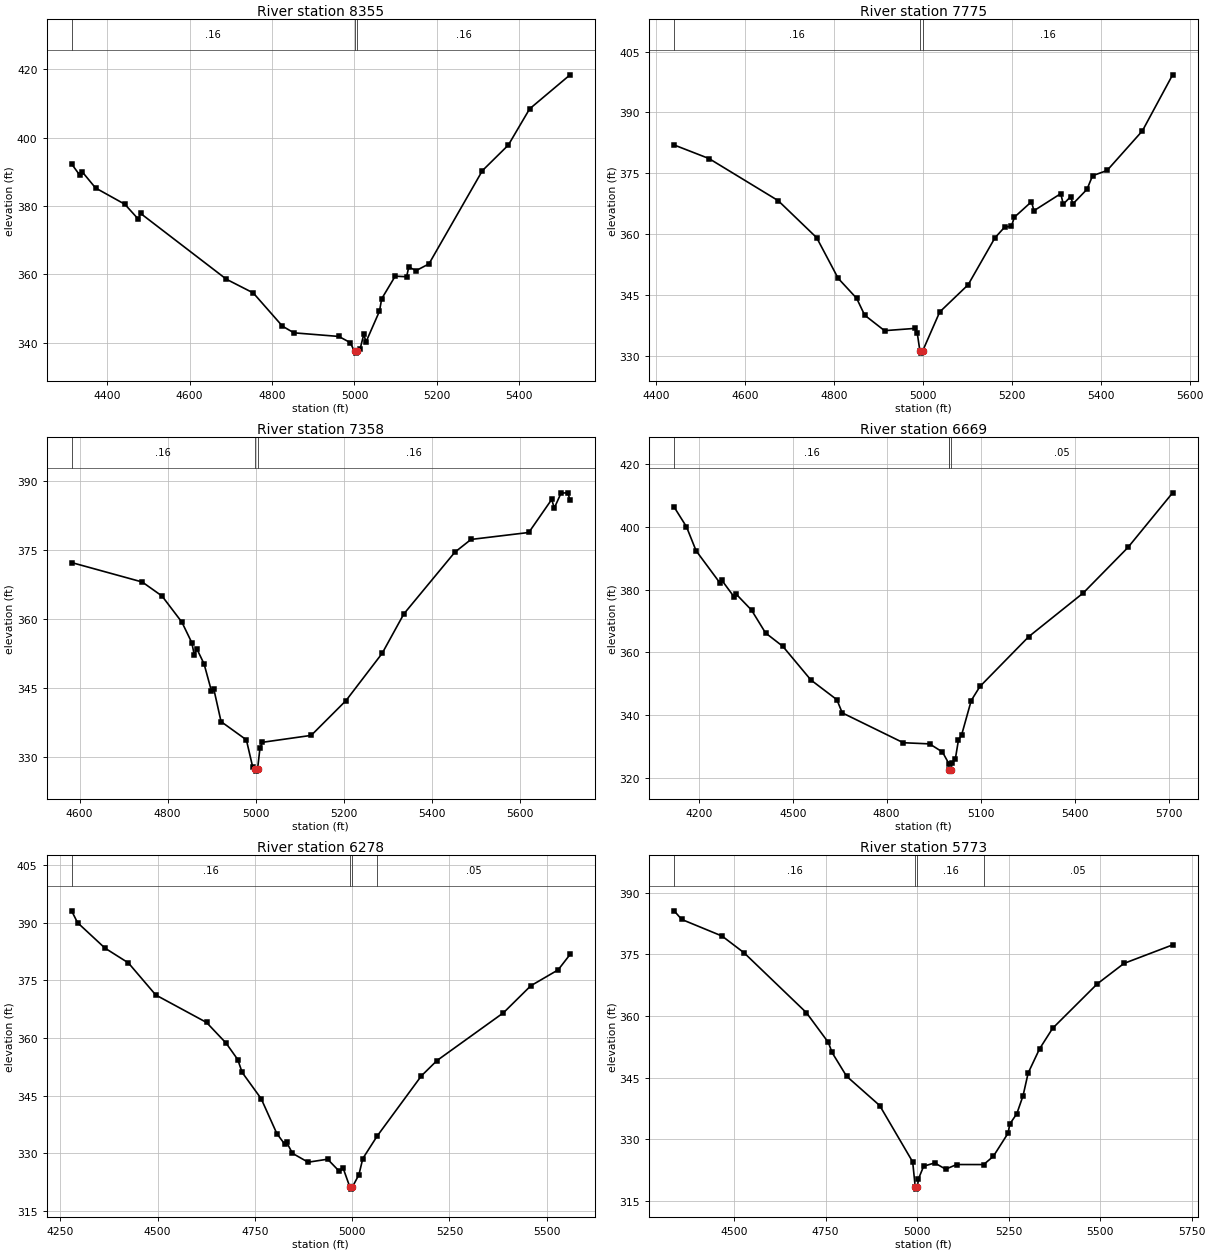
Type RM Length L Ch R = 1,8355,580,580,580
BEGIN DESCRIPTION:
UNT092 IN BECR 15.0
END DESCRIPTION:
XS GIS Cut Line= 3
      3779598.98     10541967.91      3778730.91     10542231.80
      3778455.68     10542355.65
#Sta/Elev= 30
  4313.9  392.35  4333.9  389.02  4339.2  390.10  4372.0  385.31  4443.0  380.55
  4475.9  376.17  4481.1  377.88  4689.5  358.60  4754.5  354.60  4825.4  344.87
  4853.1  342.93  4962.1  341.87  4989.8  340.06  5000.1  337.49  5002.8  336.99
  5006.1  337.49  5013.5  338.09  5022.7  342.55  5027.9  340.24  5060.7  349.27
  5066.0  352.89  5098.8  359.50  5126.5  359.34  5131.7  362.19  5149.4  361.12
  5180.7  363.10  5310.3  390.38  5373.2  397.86  5424.9  408.46  5523.0  418.41
#Mann=3,-1,0
  4313.9    0.16       0  5000.1    0.07       0  5006.1    0.16       0
Bank Sta=5000.1,5006.1
Exp/Cntr=0.3,0.1

Type RM Length L Ch R = 1,7775,417,417,417
BEGIN DESCRIPTION:
UNT092 IN BECR 14.0
END DESCRIPTION:
XS GIS Cut Line= 3
      3779335.06     10541599.86      3778710.08     10541773.46
      3778487.84     10542190.15
#Sta/Elev= 30
  4440.5  381.99  4518.8  378.65  4674.5  368.26  4761.0  359.13  4809.4  349.10
  4850.9  344.18  4869.0  340.02  4913.6  336.20  4982.1  336.76  4987.3  335.54
  4993.2  331.16  4996.0  330.66  4999.2  331.16  5037.7  340.81  5101.6  347.52
  5161.8  359.08  5183.8  361.75  5198.8  361.94  5205.7  364.19  5244.0  367.99
  5249.6  365.78  5309.9  369.99  5315.5  367.38  5331.8  369.21  5337.5  367.50
  5368.8  371.05  5381.4  374.41  5414.0  375.70  5493.4  385.47  5561.4  399.29
#Mann=3,-1,0
  4440.5    0.16       0  4993.2    0.07       0  4999.2    0.16       0
Bank Sta=4993.2,4999.2
Exp/Cntr=0.3,0.1

Type RM Length L Ch R = 1,7358,689,689,689
BEGIN DESCRIPTION:
UNT092 IN BECR 13.0
END DESCRIPTION:
XS GIS Cut Line= 3
      3779072.01     10541226.58      3778624.12     10541459.21
      3778294.46     10541993.60
#Sta/Elev= 30
  4581.8  372.21  4742.3  367.99  4787.3  364.94  4832.4  359.27  4854.9  354.82
  4860.7  352.08  4866.3  353.48  4882.8  350.21  4899.3  344.42  4904.9  344.75
  4921.4  337.68  4978.9  333.72  4993.4  327.77  4998.4  327.43  5001.2  326.93
  5004.4  327.43  5009.9  332.02  5015.5  333.19  5126.2  334.69  5205.4  342.26
  5287.4  352.50  5336.7  361.06  5452.6  374.46  5489.3  377.23  5620.6  378.74
  5672.6  385.91  5678.5  384.04  5693.9  387.30  5709.3  387.35  5714.4  385.70
#Mann=3,-1,0
  4581.8    0.16       0  4998.4    0.07       0  5004.4    0.16       0
Bank Sta=4998.4,5004.4
Exp/Cntr=0.3,0.1

Type RM Length L Ch R = 1,6669,391,391,391
BEGIN DESCRIPTION:
UNT092 IN BECR 12.0
END DESCRIPTION:
XS GIS Cut Line= 2
      3779248.29     10540855.03      3777690.13     10541180.55
#Sta/Elev= 30
  4121.3  406.37  4160.8  400.06  4191.5  392.41  4268.4  382.04  4273.5  383.02
  4313.3  377.63  4318.4  378.69  4368.4  373.50  4413.3  366.19  4468.4  361.93
  4558.1  351.19  4641.0  344.91  4658.1  340.71  4853.0  331.18  4937.2  330.81
  4978.1  328.22  4998.5  324.54  4999.9  322.62  5002.7  322.12  5005.9  322.62
  5008.7  324.81  5019.0  325.83  5029.2  332.03  5039.4  333.68  5070.0  344.64
  5097.8  349.12  5253.9  365.04  5427.6  378.94  5570.6  393.49  5713.1  410.90
#Mann=4,-1,0
  4121.3    0.16       0  4998.5    0.05       0  4999.9    0.03       0
  5005.9    0.05       0
Bank Sta=4999.9,5005.9
Exp/Cntr=0.3,0.1

Type RM Length L Ch R = 1,6278,505,505,505
BEGIN DESCRIPTION:
UNT092 IN BECR 11.0
END DESCRIPTION:
XS GIS Cut Line= 2
      3779104.99     10540668.41      3777828.99     10540776.91
#Sta/Elev= 30
  4279.3  393.09  4294.7  390.00  4365.0  383.40  4425.2  379.55  4495.5  371.21
  4625.9  364.07  4676.1  358.70  4706.2  354.41  4717.3  351.10  4766.4  344.23
  4806.6  335.17  4826.5  332.45  4831.5  332.95  4846.7  330.04  4886.9  327.73
  4937.0  328.51  4967.2  325.35  4977.2  326.10  4994.3  321.23  4997.0  320.73
  5000.3  321.23  5017.3  324.44  5027.4  328.69  5064.6  334.57  5177.9  350.18
  5218.1  354.17  5388.7  366.58  5458.9  373.60  5529.2  377.74  5559.9  381.75
#Mann=4,-1,0
  4279.3    0.16       0  4994.3    0.07       0  5000.3    0.16       0
  5064.6    0.05       0
Bank Sta=4994.3,5000.3
Exp/Cntr=0.3,0.1

Type RM Length L Ch R = 1,5773,468,468,468
BEGIN DESCRIPTION:
UNT092 IN BECR 10.0
END DESCRIPTION:
XS GIS Cut Line= 3
      3779070.33     10540260.42      3778154.50     10540308.17
      3777755.18     10540503.49
#Sta/Elev= 30
  4336.4  385.57  4357.1  383.48  4467.3  379.44  4527.4  375.37  4697.6  360.82
  4757.7  353.57  4767.7  351.14  4807.4  345.37  4897.9  338.24  4988.0  324.54
  4995.0  318.42  4997.8  317.92  5001.0  318.42  5003.6  320.38  5018.0  323.49
  5048.1  324.29  5078.1  322.77  5108.2  323.90  5181.8  323.89  5208.3  325.89
  5248.4  331.50  5253.4  333.76  5272.5  336.27  5289.5  340.64  5303.4  346.14
  5334.5  352.01  5370.2  357.01  5492.1  367.81  5565.2  372.79  5698.0  377.29
#Mann=4,-1,0
  4336.4    0.16       0  4995.0    0.07       0  5001.0    0.16       0
  5181.8    0.05       0
Bank Sta=4995,5001
Exp/Cntr=0.3,0.1

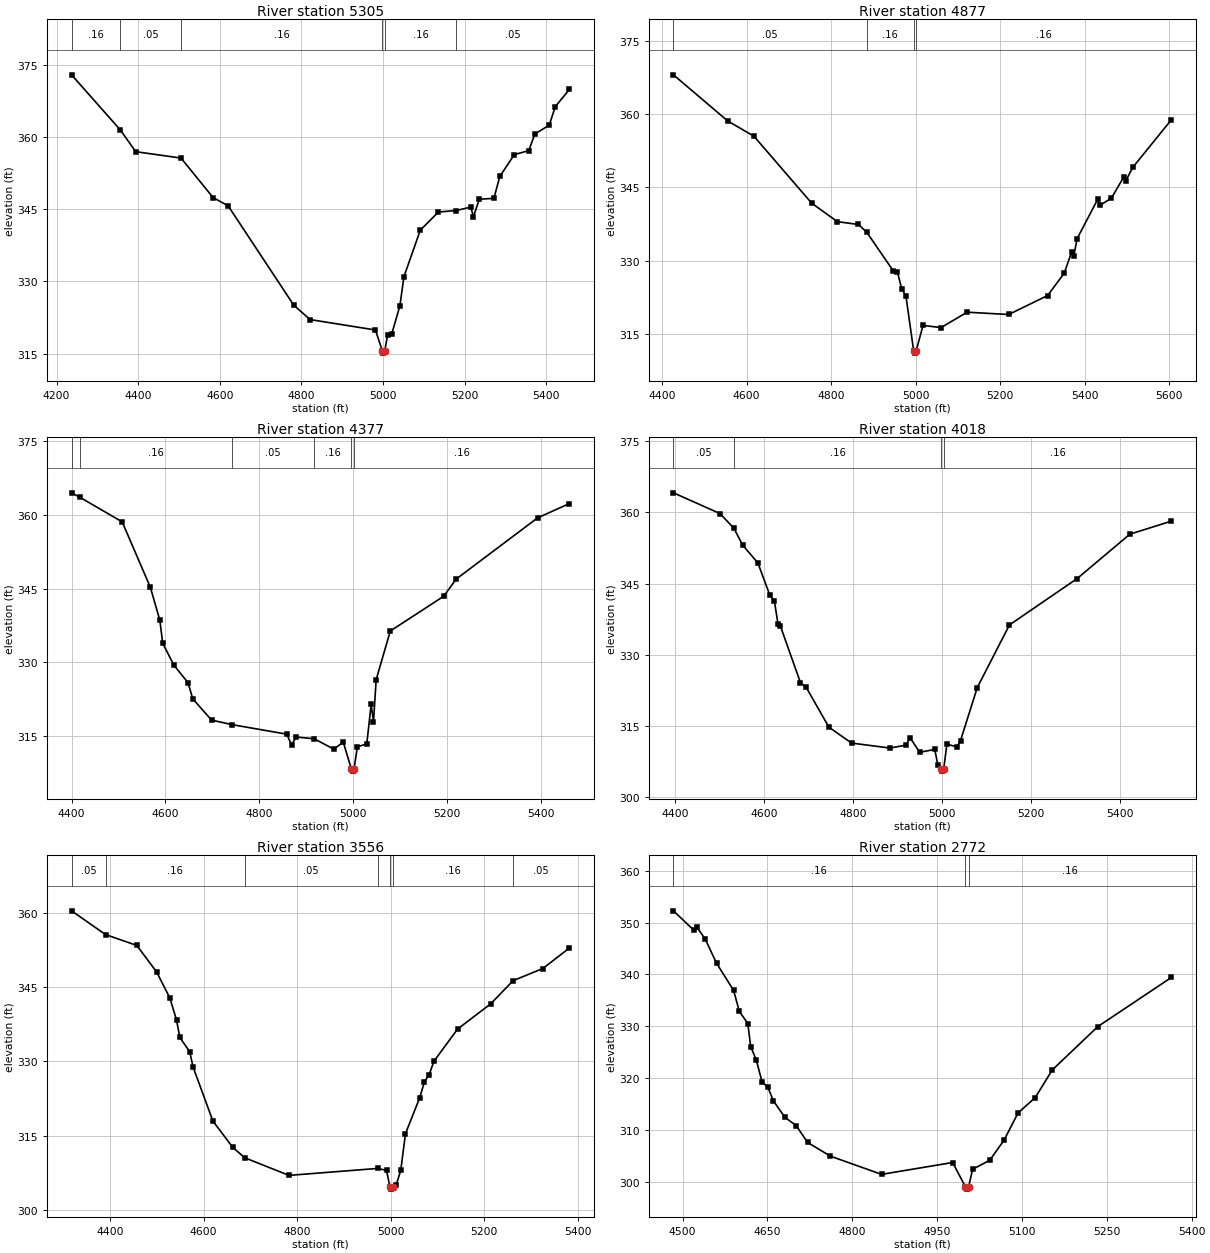
Type RM Length L Ch R = 1,5305,428,428,428
BEGIN DESCRIPTION:
UNT092 IN BECR 9.0
END DESCRIPTION:
XS GIS Cut Line= 4
      3778883.64     10540164.93      3778506.06     10540039.07
      3778028.63     10540056.43      3777824.63     10540334.22
#Sta/Elev= 30
  4236.7  372.87  4356.4  361.42  4393.9  356.93  4505.0  355.60  4583.6  347.41
  4620.5  345.69  4781.3  325.09  4821.3  322.10  4981.4  319.94  4998.4  315.64
  5001.2  315.14  5004.4  315.64  5011.4  318.93  5021.4  319.10  5041.4  324.94
  5051.4  331.00  5091.5  340.65  5135.9  344.41  5179.6  344.72  5215.4  345.44
  5221.6  343.42  5236.2  347.07  5271.8  347.24  5286.4  351.79  5321.9  356.32
  5357.4  357.15  5372.1  360.57  5407.6  362.44  5422.2  366.25  5457.1  369.86
#Mann=6,-1,0
  4236.7    0.16       0  4356.4    0.05       0  4505.0    0.16       0
  4998.4    0.07       0  5004.4    0.16       0  5179.6    0.05       0
Bank Sta=4998.4,5004.4
Exp/Cntr=0.3,0.1

Type RM Length L Ch R = 1,4877,500,500,500
BEGIN DESCRIPTION:
UNT092 IN BECR 8.0
END DESCRIPTION:
XS GIS Cut Line= 2
      3778922.77     10539865.46      3777759.49     10539677.95
#Sta/Elev= 30
  4427.1  368.01  4555.7  358.56  4617.5  355.46  4754.4  341.75  4815.2  337.98
  4864.7  337.41  4884.4  335.84  4946.9  327.97  4957.0  327.72  4967.1  324.31
  4977.3  322.77  4995.5  311.60  4998.2  311.10  5001.5  311.60  5017.8  316.77
  5060.3  316.32  5122.1  319.47  5220.4  319.00  5312.6  322.88  5352.0  327.46
  5369.3  331.77  5374.4  330.94  5382.4  334.51  5431.1  342.56  5436.2  341.30
  5463.5  342.79  5492.9  347.14  5498.0  346.40  5514.1  349.08  5605.4  358.82
#Mann=4,-1,0
  4427.1    0.05       0  4884.4    0.16       0  4995.5    0.07       0
  5001.5    0.16       0
Bank Sta=4995.5,5001.5
Exp/Cntr=0.3,0.1

Type RM Length L Ch R = 1,4377,359,359,359
BEGIN DESCRIPTION:
UNT092 IN BECR 7.0
END DESCRIPTION:
XS GIS Cut Line= 3
      3778807.26     10539322.08      3777980.91     10539377.63
      3777753.19     10539329.33
#Sta/Elev= 30
  4400.1  364.50  4417.1  363.63  4508.0  358.58  4568.1  345.22  4588.2  338.54
  4594.4  333.82  4618.2  329.38  4648.3  325.81  4658.3  322.53  4698.4  318.19
  4742.8  317.25  4858.8  315.32  4868.8  313.12  4878.8  314.74  4917.2  314.38
  4959.0  312.27  4979.1  313.70  4996.1  308.29  4998.8  307.79  5002.1  308.29
  5009.1  312.74  5029.2  313.34  5038.5  321.39  5043.5  317.82  5049.2  326.44
  5079.3  336.34  5193.2  343.43  5219.6  346.92  5393.2  359.40  5461.1  362.32
#Mann=6,-1,0
  4400.1    0.05       0  4417.1    0.16       0  4742.8    0.05       0
  4917.2    0.16       0  4996.1    0.07       0  5002.1    0.16       0
Bank Sta=4996.1,5002.1
Exp/Cntr=0.3,0.1

Type RM Length L Ch R = 1,4018,462,462,462
BEGIN DESCRIPTION:
UNT092 IN BECR 6.0
END DESCRIPTION:
XS GIS Cut Line= 3
      3778842.00     10539183.18      3778098.96     10539030.41
      3777737.81     10539023.46
#Sta/Elev= 30
  4395.4  364.10  4499.9  359.74  4531.1  356.68  4551.0  353.10  4585.4  349.32
  4612.2  342.53  4622.4  341.30  4630.6  336.45  4635.7  336.10  4681.0  324.14
  4693.9  323.14  4745.0  314.75  4796.0  311.40  4882.4  310.35  4918.5  310.97
  4927.6  312.53  4949.1  309.45  4983.1  310.06  4990.0  306.81  4997.2  305.99
  4999.9  305.49  5003.2  305.99  5010.4  311.14  5033.4  310.61  5041.0  311.91
  5078.7  323.09  5151.1  336.28  5303.4  346.05  5421.9  355.39  5515.2  358.14
#Mann=4,-1,0
  4395.4    0.05       0  4531.1    0.16       0  4997.2    0.07       0
  5003.2    0.16       0
Bank Sta=4997.2,5003.2
Exp/Cntr=0.3,0.1

Type RM Length L Ch R = 1,3556,784,784,784
BEGIN DESCRIPTION:
UNT092 IN BECR 5.0
END DESCRIPTION:
XS GIS Cut Line= 3
      3778848.96     10539058.18      3778494.80     10538710.96
      3777933.46     10538620.87
#Sta/Elev= 30
  4317.6  360.48  4390.3  355.67  4457.1  353.48  4499.5  348.11  4527.8  342.83
  4542.0  338.40  4549.1  334.85  4570.2  331.97  4577.4  328.87  4619.8  317.94
  4662.2  312.63  4687.7  310.52  4782.4  306.95  4972.3  308.36  4991.0  307.95
  4998.1  304.67  5000.9  304.17  5004.1  304.67  5011.3  304.93  5021.4  307.97
  5031.5  315.40  5061.9  322.65  5072.0  325.88  5082.2  327.35  5092.3  330.04
  5142.9  336.56  5213.8  341.67  5261.6  346.35  5325.2  348.81  5382.1  352.97
#Mann=7,-1,0
  4317.6    0.05       0  4390.3    0.16       0  4687.7    0.05       0
  4972.3    0.16       0  4998.1    0.07       0  5004.1    0.16       0
  5261.6    0.05       0
Bank Sta=4998.1,5004.1
Exp/Cntr=0.3,0.1

Type RM Length L Ch R = 1,2772,561,561,561
BEGIN DESCRIPTION:
UNT092 IN BECR 4.0
END DESCRIPTION:
XS GIS Cut Line= 2
      3778925.40     10538120.68      3778050.38     10538217.91
#Sta/Elev= 30
  4483.7  352.29  4519.6  348.56  4524.6  349.21  4539.8  346.85  4560.0  342.16
  4590.1  336.92  4600.2  332.87  4615.2  330.53  4620.3  326.09  4630.4  323.41
  4640.4  319.23  4650.5  318.25  4660.6  315.57  4680.7  312.42  4700.7  310.82
  4720.9  307.56  4761.2  304.92  4851.7  301.40  4977.4  303.69  4999.7  299.05
  5002.4  298.55  5005.7  299.05  5012.7  302.39  5042.9  304.11  5067.9  307.95
  5093.2  313.28  5123.4  316.23  5153.5  321.56  5234.1  329.94  5364.1  339.42
#Mann=3,-1,0
  4483.7    0.16       0  4999.7    0.07       0  5005.7    0.16       0
Bank Sta=4999.7,5005.7
Exp/Cntr=0.3,0.1

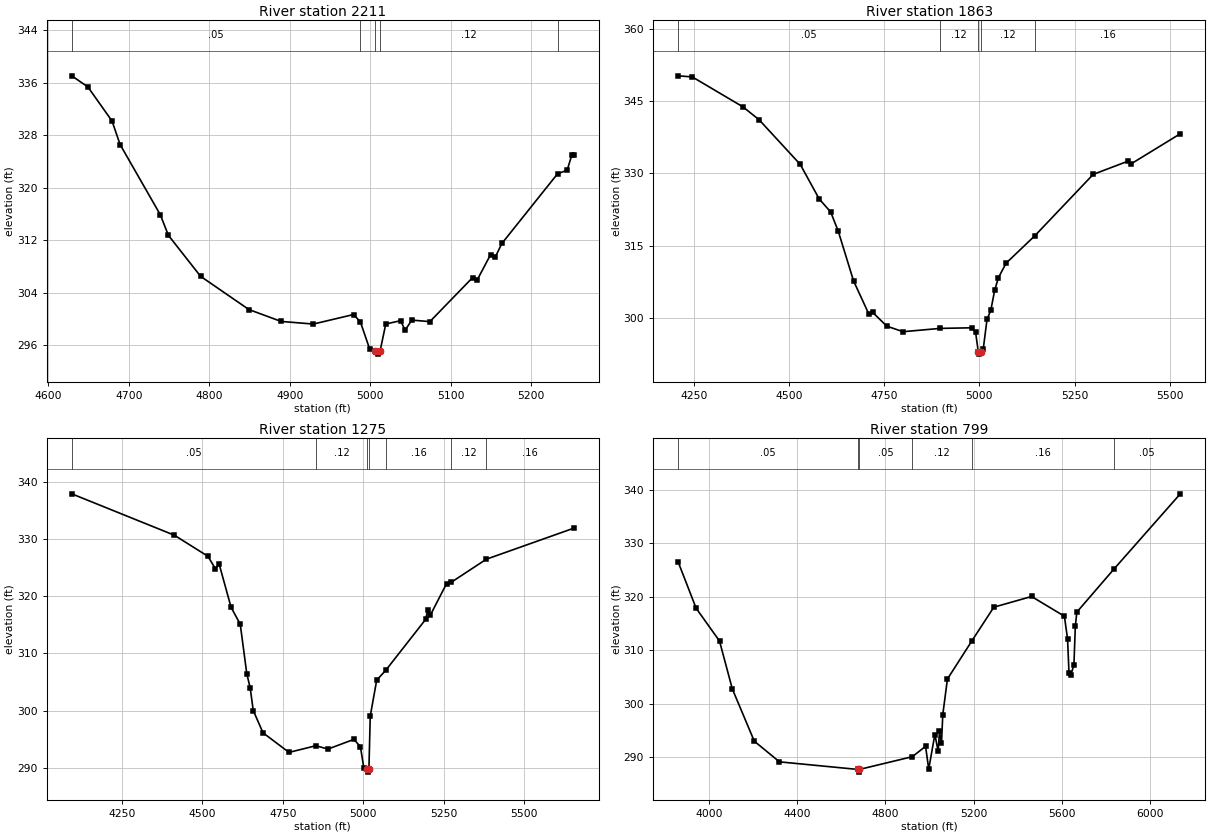
Type RM Length L Ch R = 1,2211,348,348,348
BEGIN DESCRIPTION:
UNT092 IN BECR 3.0
END DESCRIPTION:
XS GIS Cut Line= 3
      3778749.65     10537760.19      3778349.61     10537760.19
      3778149.65     10537860.17
#Sta/Elev= 30
  4629.3  337.06  4649.3  335.37  4679.3  330.18  4689.3  326.60  4739.3  315.90
  4749.3  312.77  4789.3  306.53  4849.3  301.47  4889.3  299.66  4929.3  299.26
  4979.3  300.71  4987.8  299.58  4999.3  295.46  5006.3  295.18  5009.1  294.68
  5012.3  295.18  5019.3  299.27  5037.7  299.77  5043.3  298.33  5051.7  299.86
  5074.1  299.63  5127.2  306.34  5132.8  305.96  5149.5  309.84  5155.1  309.41
  5163.5  311.53  5232.7  322.15  5244.6  322.68  5250.2  324.94  5252.9  324.94
#Mann=5,-1,0
  4629.3    0.05       0  4987.8    0.12       0  5006.3    0.07       0
  5012.3    0.12       0  5232.7    0.16       0
Bank Sta=5006.3,5012.3
Exp/Cntr=0.3,0.1

Type RM Length L Ch R = 1,1863,588,588,588
BEGIN DESCRIPTION:
UNT092 IN BECR 2.0
END DESCRIPTION:
XS GIS Cut Line= 3
      3778999.32     10537577.49      3778054.90     10537521.94
      3777791.33     10537785.51
#Sta/Elev= 30
  4209.1  350.29  4246.1  350.06  4379.1  343.84  4421.4  341.17  4529.4  331.90
  4579.5  324.69  4609.5  322.00  4629.5  317.99  4669.6  307.68  4709.7  300.80
  4719.7  301.14  4757.0  298.27  4799.8  297.12  4897.2  297.81  4980.1  297.93
  4990.2  297.00  4997.2  292.96  4999.9  292.46  5003.2  292.96  5010.2  293.48
  5020.2  299.68  5030.2  301.59  5040.2  305.71  5050.3  308.37  5070.3  311.36
  5146.2  317.09  5299.1  329.81  5391.0  332.57  5398.1  331.97  5527.9  338.26
#Mann=5,-1,0
  4209.1    0.05       0  4897.2    0.12       0  4997.2    0.07       0
  5003.2    0.12       0  5146.2    0.16       0
Bank Sta=4997.2,5003.2
Exp/Cntr=0.3,0.1

Type RM Length L Ch R = 1,1275,476,476,476
BEGIN DESCRIPTION:
Mapping XS 6bf0b3c1
END DESCRIPTION:
XS GIS Cut Line= 4
      3778985.48     10537362.23      3778554.90     10537112.22
      3778047.96     10537042.77      3777722.33     10537486.18
#Sta/Elev= 30
  4094.3  337.90  4413.3  330.66  4517.4  326.98  4540.5  324.80  4552.1  325.63
  4589.2  318.07  4617.7  315.11  4637.9  306.50  4648.5  303.99  4658.1  300.03
  4688.4  296.14  4769.1  292.72  4852.5  293.88  4890.2  293.30  4971.0  295.00
  4991.2  293.67  5001.3  290.07  5011.4  289.77  5014.2  289.27  5017.4  289.77
  5021.5  299.06  5041.6  305.34  5069.5  307.05  5193.9  315.98  5200.1  317.60
  5208.5  316.74  5258.7  322.22  5273.0  322.44  5382.0  326.47  5654.0  331.90
#Mann=7,-1,0
  4094.3    0.05       0  4852.5    0.12       0  5011.4    0.07       0
  5017.4    0.12       0  5069.5    0.16       0  5273.0    0.12       0
  5382.0    0.16       0
Bank Sta=5011.4,5017.4
Exp/Cntr=0.3,0.1

Type RM Length L Ch R = 1,799,0,0,0
BEGIN DESCRIPTION:
UNT092 IN BECR 1.0
END DESCRIPTION:
XS GIS Cut Line= 4
      3778867.41     10537105.28      3778381.29     10536473.33
      3777860.46     10536820.55      3777326.53     10537486.22
#Sta/Elev= 30
  3860.2  326.49  3941.4  317.87  4047.4  311.74  4105.4  302.80  4205.1  293.02
  4319.3  289.16  4675.2  287.74  4678.0  287.24  4681.2  287.74  4922.0  290.13
  4981.7  292.07  4996.0  287.80  5023.7  294.27  5038.8  291.16  5044.8  294.86
  5053.8  292.62  5059.8  298.00  5080.8  304.64  5190.2  311.68  5291.1  318.07
  5462.3  320.07  5611.2  316.38  5625.6  312.12  5632.0  305.80  5640.0  305.32
  5654.4  307.31  5660.8  314.53  5667.6  317.15  5834.3  325.12  6136.8  339.26
#Mann=6,-1,0
  3860.2    0.05       0  4675.2    0.07       0  4681.2    0.05       0
  4922.0    0.12       0  5190.2    0.16       0  5834.3    0.05       0
Bank Sta=4675.2,4681.2
Exp/Cntr=0.3,0.1

Chan Stop Cuts=-1