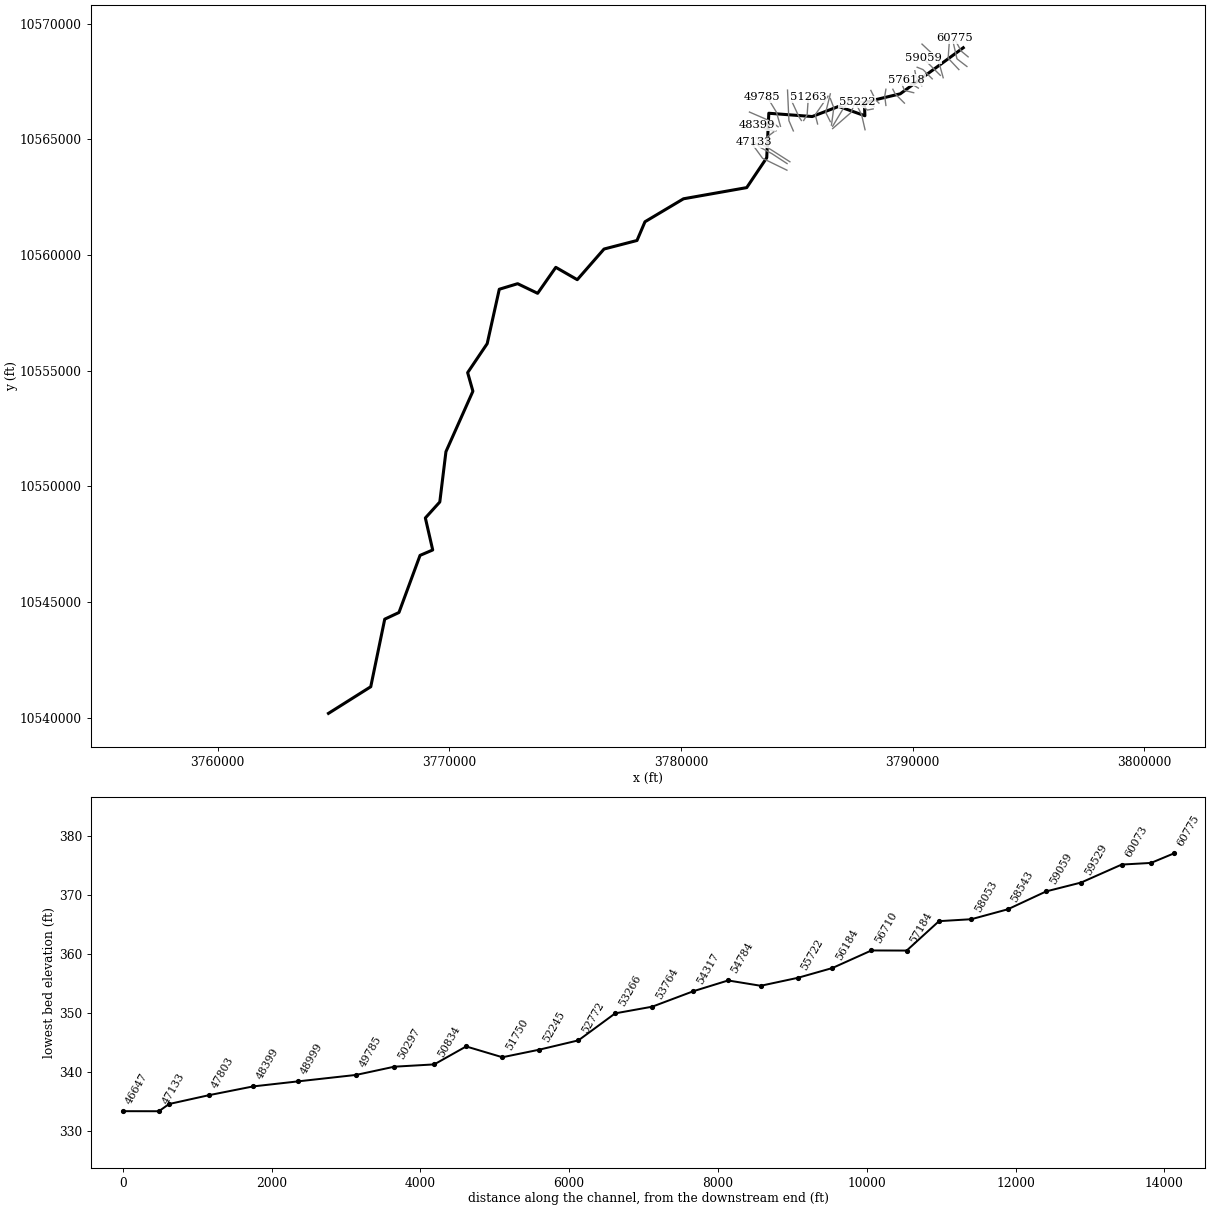
--- UNT094 IN BECR.prj (project) ---

Proj Title=UNT094 IN BECR Base Level Engineering
Current Plan=p01
Default Exp/Contr=0.3,0.1
English Units
Geom File=g01
Flow File=f01
Plan File=p01
Y Axis Title=Elevation
X Axis Title(PF)=Main Channel Distance
X Axis Title(XS)=Station
BEGIN DESCRIPTION:
UNT094 IN BECR
END DESCRIPTION:
DSS Export Rating Curves= 0
DSS Export Rating Curve Sorted= 0
DSS Export Volume Flow Curves= 0
DXF OffsetX= 0
DXF OffsetY= 0
DXF ScaleX= 1
DXF ScaleY= 10

--- UNT094 IN BECR.p01 (plan) ---

Plan Title=Multiple Run
Short Identifier=Multiple
Geom File=g01
Flow File=f01
Subcritical Flow
K Sum by GR= 0
Std Step Tol= 0.01
Critical Tol= 0.01
Num of Std Step Trials= 20
Max Error Tol= 0.3
Flow Tol Ratio= 0.001
Split Flow NTrial= 30
Split Flow Tol= 0.02
Split Flow Ratio= 0.02
Log Output Level= 0
Friction Slope Method= 1
Unsteady Friction Slope Method= 2
Unsteady Bridges Friction Slope Method= 1
Parabolic Critical Depth
Global Vel Dist=  1 , 1 , 1
Global Log Level= 0
CheckData=True
Encroach Param= -1, 0, 0, 0
BEGIN DESCRIPTION:
Multiple Run
END DESCRIPTION:

--- UNT094 IN BECR.f01 (steady flow) ---

Flow Title=Multiple
Program Version=4.10
Number of Profiles= 7
Profile Names=10-year,25-year,50-year,1pct_min,100-year,1pct_plu,500-year
River Rch & RM=UNT094 IN BECR,Reach-1         ,60775
     715     978    1197    1078    1458    1972    2169
River Rch & RM=UNT094 IN BECR,Reach-1         ,59059
     901    1244    1532    1386    1874    2535    2816
River Rch & RM=UNT094 IN BECR,Reach-1         ,54317
    1158    1617    2008    1828    2472    3343    3762
River Rch & RM=UNT094 IN BECR,Reach-1         ,51750
    1510    2129    2661    2436    3294    4455    5071
River Rch & RM=UNT094 IN BECR,Reach-1         ,47270
    1689    2388    2989    2740    3706    5012    5719
River Rch & RM=UNT094 IN BECR,Reach-1         ,43615
    2080    2967    3736    3443    4656    6297    7263
River Rch & RM=UNT094 IN BECR,Reach-1         ,43064
    2080    2967    3736    3443    4656    6297    7263
River Rch & RM=UNT094 IN BECR,Reach-1         ,41848
    2114    3013    3791    3491    4721    6385    7352
River Rch & RM=UNT094 IN BECR,Reach-1         ,38486
    2238    3192    4017    3699    5003    6766    7791
River Rch & RM=UNT094 IN BECR,Reach-1         ,34238
    2288    3263    4107    3781    5113    6915    7960
River Rch & RM=UNT094 IN BECR,Reach-1         ,31674
    2647    3790    4784    4415    5971    8076    9341
River Rch & RM=UNT094 IN BECR,Reach-1         ,28275
    2791    4005    5062    4677    6325    8553    9918
River Rch & RM=UNT094 IN BECR,Reach-1         ,27715
    2913    4183    5291    4890    6614    8944   10379
River Rch & RM=UNT094 IN BECR,Reach-1         ,25055
    3025    4348    5501    5086    6878    9302   10800
River Rch & RM=UNT094 IN BECR,Reach-1         ,22929
    3036    4360    5513    5094    6889    9316   10802
River Rch & RM=UNT094 IN BECR,Reach-1         ,22179
    3070    4407    5571    5146    6960    9412   10907
River Rch & RM=UNT094 IN BECR,Reach-1         ,17815
    3274    4701    5944    5490    7425   10042   11634
River Rch & RM=UNT094 IN BECR,Reach-1         ,12052
    3394    4878    6170    5701    7710   10426   12087
River Rch & RM=UNT094 IN BECR,Reach-1         ,11165
    3394    4878    6170    5701    7710   10426   12087
River Rch & RM=UNT094 IN BECR,Reach-1         ,9541
    3576    5145    6513    6022    8144   11014   12786
River Rch & RM=UNT094 IN BECR,Reach-1         ,8229
    3576    5145    6513    6022    8144   11014   12786
River Rch & RM=UNT094 IN BECR,Reach-1         ,1829
    3707    5334    6754    6245    8445   11421   13259
Boundary for River Rch & Prof#=UNT094 IN BECR,Reach-1         , 1
Up Type= 0
Dn Type= 3
Dn Slope=0.002
Boundary for River Rch & Prof#=UNT094 IN BECR,Reach-1         , 2
Up Type= 0
Dn Type= 3
Dn Slope=0.002
Boundary for River Rch & Prof#=UNT094 IN BECR,Reach-1         , 3
Up Type= 0
Dn Type= 3
Dn Slope=0.002
Boundary for River Rch & Prof#=UNT094 IN BECR,Reach-1         , 4
Up Type= 0
Dn Type= 3
Dn Slope=0.002
Boundary for River Rch & Prof#=UNT094 IN BECR,Reach-1         , 5
Up Type= 0
Dn Type= 3
Dn Slope=0.002
Boundary for River Rch & Prof#=UNT094 IN BECR,Reach-1         , 6
Up Type= 0
Dn Type= 3
Dn Slope=0.002
Boundary for River Rch & Prof#=UNT094 IN BECR,Reach-1         , 7
Up Type= 0
Dn Type= 3
Dn Slope=0.002
DSS Import GetInterval= 0
DSS Import GetPeak= 0
DSS Import FillOption= 0

--- UNT094 IN BECR.g01 (geometry) ---

Geom Title=Existing Conditions
Program Version=4.10

River Reach=UNT094 IN BECR  ,Reach-1
Reach XY= 30
      3792189.18     10568953.02       3789468.5       10566962.
      3787918.25       10566594.        3787942.       10566015.
       3786810.5       10566419.      3785668.75       10565981.
       3783793.5       10566123.      3783703.75       10564199.
      3782839.75       10562910.       3780110.5       10562427.
        3778447.       10561435.        3778102.       10560625.
        3776679.       10560256.        3775523.       10558931.
        3774596.       10559465.      3773811.75       10558342.
      3772948.25       10558758.        3772156.       10558518.
      3771634.25       10556168.        3770790.       10554915.
      3771016.75       10554111.       3769852.5       10551499.
      3769587.25       10549326.      3768963.75       10548635.
      3769281.25       10547252.      3768734.25       10547018.
      3767824.25       10544550.      3767209.75       10544262.
        3766606.       10541342.        3764780.       10540191.

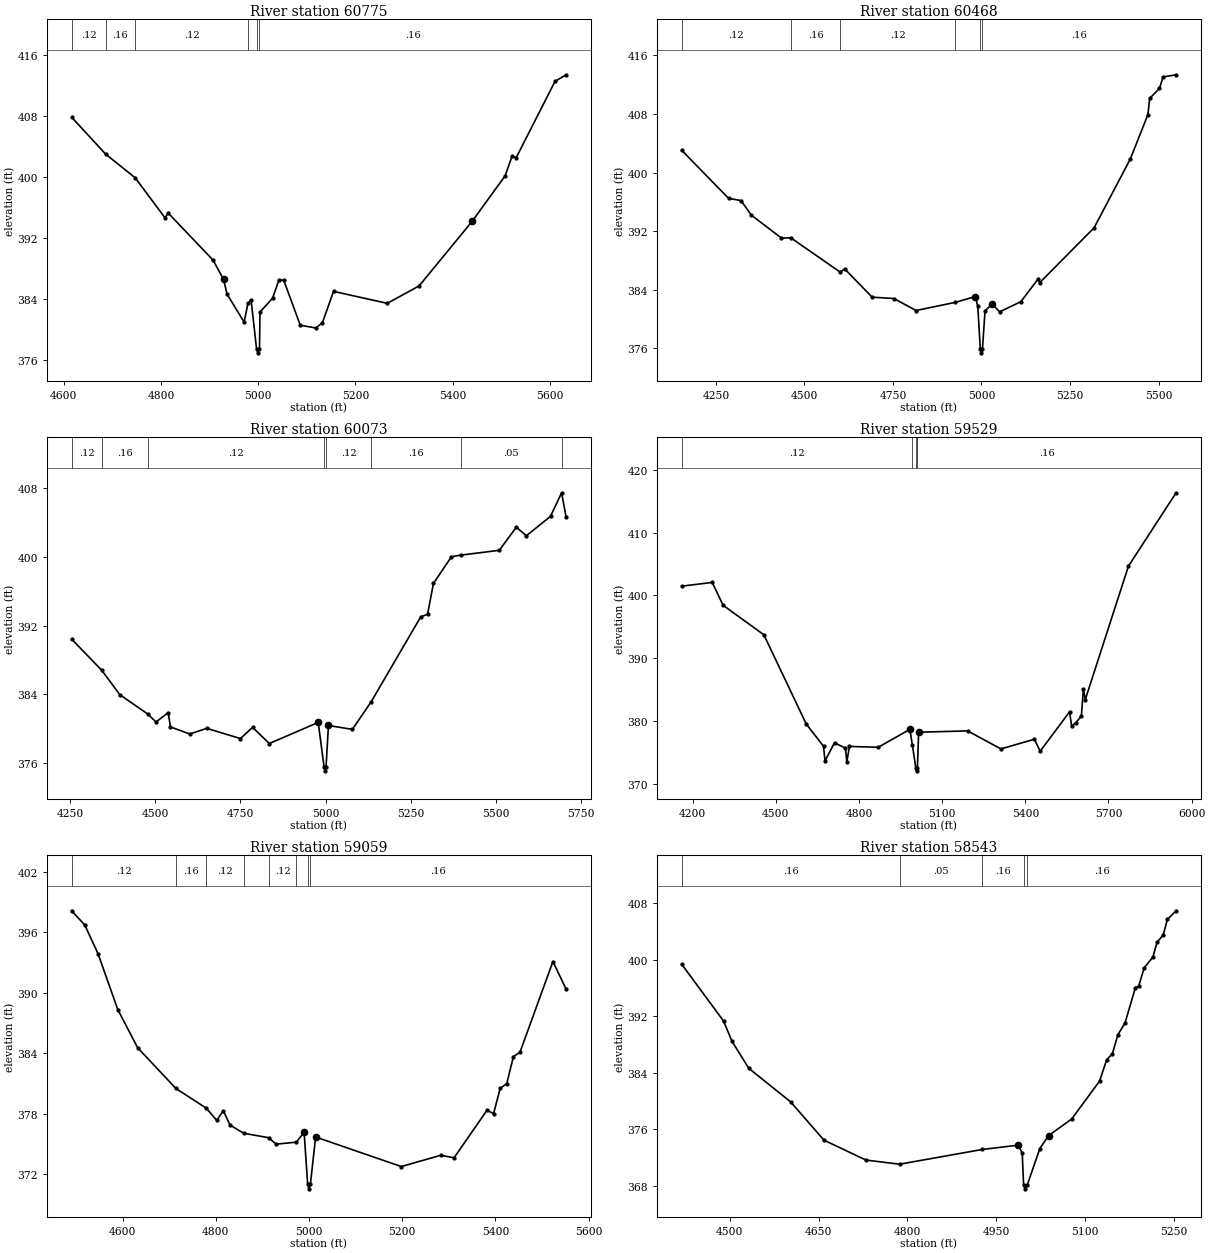
Type RM Length L Ch R = 1 ,60775   ,307,307,307
BEGIN DESCRIPTION:
UNT094 IN BECR 101.0
END DESCRIPTION:
XS GIS Cut Line= 3
      3792399.61     10568560.19      3792099.61     10568810.19
      3791799.61     10569360.18
#Sta/Elev= 30
  4616.3  407.88  4685.9  403.06  4746.8  399.95  4808.3  394.69  4814.8  395.32
  4907.2  389.14  4928.7  386.61  4935.9  384.69    4971  381.01  4978.9   383.5
  4985.3  383.94  4996.6  377.49  4999.4  376.99  5002.6  377.49  5003.6  382.33
  5029.6  384.16  5042.4  386.53  5052.4  386.52  5086.5  380.61  5118.3  380.25
  5132.1  380.95  5154.9  385.05  5265.5  383.48    5331  385.77  5440.1  394.24
    5508  400.21  5521.8  402.74  5530.8   402.6  5610.5  412.59  5633.3  413.45
#Mann= 6 ,-1 , 0
  4616.3     .12       0  4685.9     .16       0  4746.8     .12       0
  4978.9     .16       0  4996.6     .07       0  5002.6     .16       0
Bank Sta=4928.7,5440.1
XS Rating Curve= 0 ,0
Exp/Cntr=0.3,0.1

Type RM Length L Ch R = 1 ,60468   ,395,395,395
BEGIN DESCRIPTION:
UNT094 IN BECR 100.0
END DESCRIPTION:
XS GIS Cut Line= 3
      3792348.07     10568143.49      3791918.36     10568473.37
      3791727.56     10569305.95
#Sta/Elev= 30
  4153.6  403.04  4285.9  396.48  4321.2  396.17  4350.3  394.18  4435.4  391.05
  4461.7  391.09  4601.2   386.4    4614  386.83  4691.4  382.98  4752.7   382.8
  4815.2  381.16    4926  382.27  4982.6  383.07  4989.6  381.72  4996.8  375.88
  4999.6  375.38  5002.8  375.88  5010.1  381.12  5030.6  382.07  5051.1  380.97
  5111.3  382.37  5159.3  385.43  5164.5  384.97  5317.9  392.45  5420.5  401.87
  5469.9  407.91    5475  410.12  5502.6   411.5  5512.8  413.05  5549.5  413.35
#Mann= 6 ,-1 , 0
  4153.6     .12       0  4461.7     .16       0  4601.2     .12       0
    4926     .16       0  4996.8     .07       0  5002.8     .16       0
Bank Sta=4982.6,5030.6
XS Rating Curve= 0 ,0
Exp/Cntr=0.3,0.1

Type RM Length L Ch R = 1 ,60073   ,544,544,544
BEGIN DESCRIPTION:
UNT094 IN BECR 99.0
END DESCRIPTION:
XS GIS Cut Line= 3
      3791999.63     10568010.16      3791536.41     10568503.75
       3791592.8     10569275.79
#Sta/Elev= 30
  4254.7  390.43  4342.9  386.81  4396.1  383.96  4478.4   381.7  4502.1  380.78
  4537.8  381.88  4544.6  380.21  4601.3  379.39  4651.1  380.05  4749.8  378.86
  4785.4  380.16  4834.8  378.28  4978.2  380.74  4995.2   375.6    4998   375.1
  5001.2   375.6  5008.2  380.38  5078.4  379.93  5133.1  383.11    5279  393.03
    5299  393.33  5316.4  396.93  5369.2  400.03  5396.5  400.22  5509.6  400.78
  5559.7  403.48    5589  402.47    5660  404.74  5692.4  407.48  5705.7  404.65
#Mann= 8 ,-1 , 0
  4254.7     .12       0  4342.9     .16       0  4478.4     .12       0
  4995.2     .07       0  5001.2     .12       0  5133.1     .16       0
  5396.5     .05       0  5692.4     .16       0
Bank Sta=4978.2,5008.2
XS Rating Curve= 0 ,0
Exp/Cntr=0.3,0.1

Type RM Length L Ch R = 1 ,59529   ,470,470,470
BEGIN DESCRIPTION:
UNT094 IN BECR 98.0
END DESCRIPTION:
XS GIS Cut Line= 3
      3791323.74     10567657.41      3791099.61     10568460.19
      3790407.91     10569111.42
#Sta/Elev= 30
  4160.4  401.46  4270.5  402.06  4309.9  398.41  4456.9  393.72  4609.7  379.52
    4672  375.97  4677.5  373.65  4711.7  376.53    4751  375.68  4756.2  373.51
  4765.5  375.95  4869.3  375.81  4983.5  378.66  4992.6  376.19  5004.8  372.56
  5007.6  372.06  5010.8  372.56  5015.1  378.21  5191.9  378.42  5312.1  375.55
  5432.7  377.09  5453.7  375.19  5559.7  381.46    5567  379.21  5581.1  379.68
  5602.2  380.76  5609.5   385.1  5616.3   383.4  5772.1  404.66  5943.9  416.33
#Mann= 4 ,-1 , 0
  4160.4     .12       0  4992.6     .16       0  5004.8     .07       0
  5010.8     .16       0
Bank Sta=4983.5,5015.1
XS Rating Curve= 0 ,0
Exp/Cntr=0.3,0.1

Type RM Length L Ch R = 1 ,59059   ,516,516,516
BEGIN DESCRIPTION:
UNT094 IN BECR 97.0
END DESCRIPTION:
XS GIS Cut Line= 3
      3791199.64     10567760.16      3790849.61     10568110.19
      3790449.61     10568510.19
#Sta/Elev= 30
  4490.8  398.13  4519.1   396.7  4547.4  393.86  4589.8  388.32  4632.3  384.55
  4714.4  380.51  4779.8  378.55    4802  377.34  4816.1  378.31  4830.3  376.89
  4859.8  376.07  4913.4  375.63  4929.2  374.99  4972.9  375.19  4989.4  376.17
    4997  371.06  4999.7  370.56    5003  371.06  5014.1   375.7  5197.9  372.77
  5282.8  373.89  5311.1  373.64  5381.8  378.35  5395.9  378.02  5410.1  380.52
  5424.2     381  5438.4  383.67  5452.5   384.1  5523.2   393.1  5551.5  390.36
#Mann= 8 ,-1 , 0
  4490.8     .12       0  4714.4     .16       0  4779.8     .12       0
  4859.8     .16       0  4913.4     .12       0  4972.9     .16       0
    4997     .07       0    5003     .16       0
Bank Sta=4989.4,5014.1
XS Rating Curve= 0 ,0
Exp/Cntr=0.3,0.1

Type RM Length L Ch R = 1 ,58543   ,490,490,490
BEGIN DESCRIPTION:
UNT094 IN BECR 96.0
END DESCRIPTION:
XS GIS Cut Line= 3
      3790849.63     10567610.17      3790449.61     10568010.19
      3790199.59      10568110.2
#Sta/Elev= 30
  4418.9  399.36  4489.6  391.31  4503.8  388.45  4532.1  384.62  4602.8  379.86
  4659.3  374.42  4730.1  371.61  4786.8  371.02  4926.7  373.11  4987.3  373.72
    4994  372.62  4996.4  368.03  4999.2  367.53  5002.4  368.03  5023.7  373.23
  5038.5  375.07  5077.5  377.42  5124.6  382.79  5136.7  385.83  5146.2  386.65
  5155.6  389.36  5167.7  391.04  5185.2  396.05  5190.6  396.21    5200  398.85
  5214.8  400.37  5221.6  402.45  5232.3  403.53  5239.1   405.7  5253.9  406.93
#Mann= 5 ,-1 , 0
  4418.9     .16       0  4786.8     .05       0  4926.7     .16       0
  4996.4     .07       0  5002.4     .16       0
Bank Sta=4987.3,5038.5
XS Rating Curve= 0 ,0
Exp/Cntr=0.3,0.1

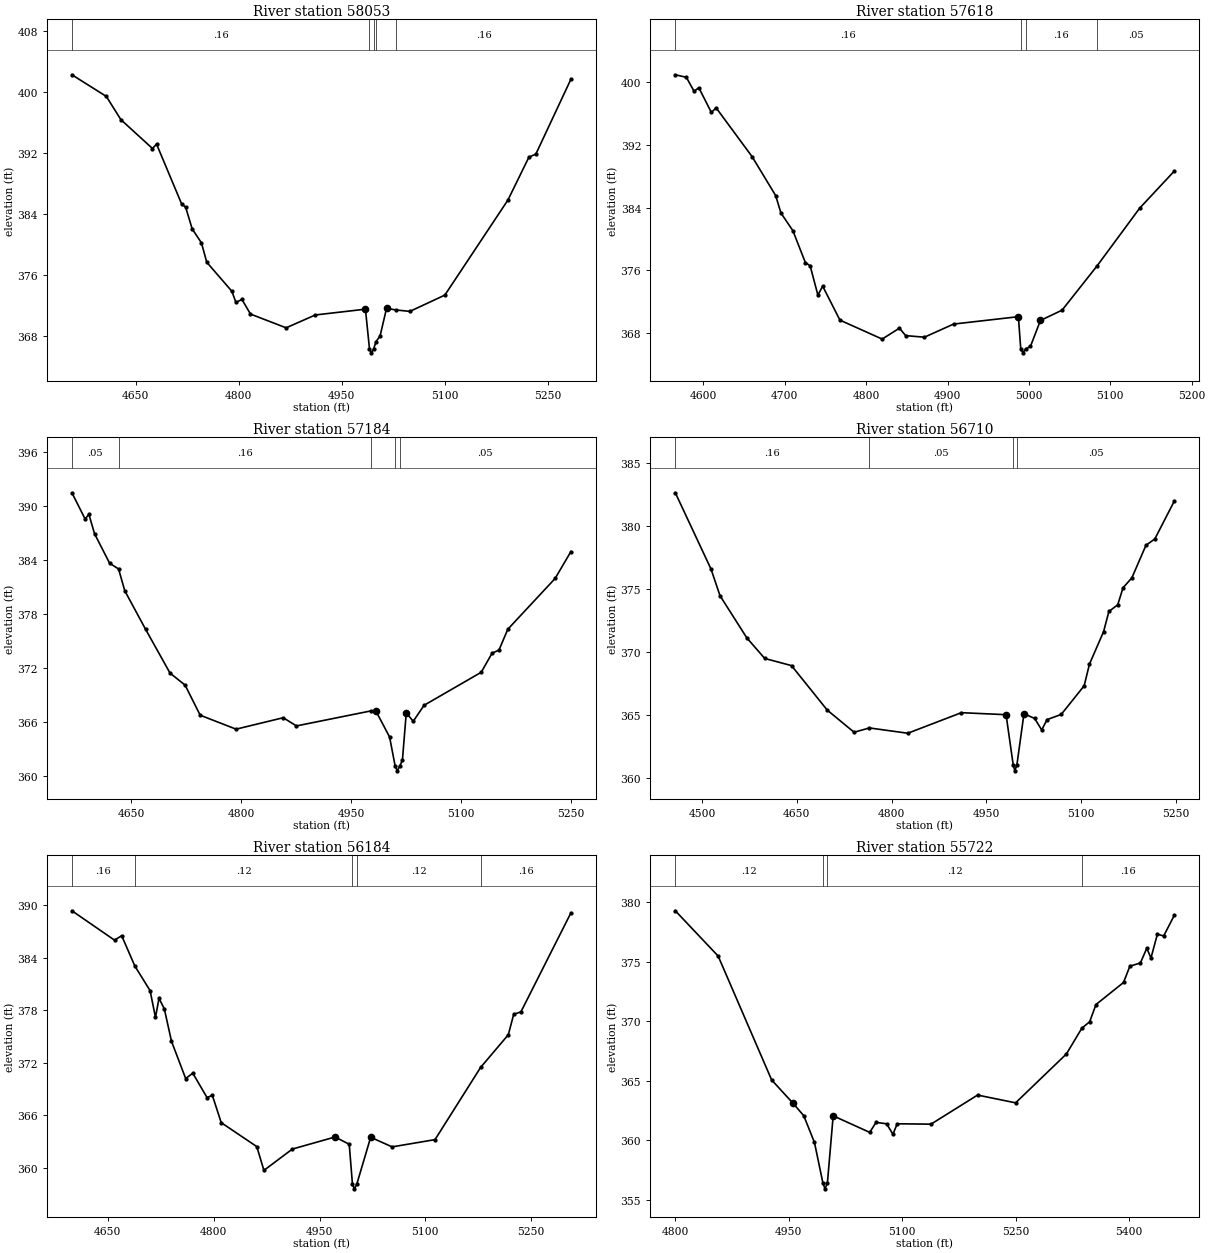
Type RM Length L Ch R = 1 ,58053   ,435,435,435
BEGIN DESCRIPTION:
UNT094 IN BECR 95.0
END DESCRIPTION:
XS GIS Cut Line= 3
      3790399.59     10567310.22      3790149.61     10567710.19
      3790099.61     10567960.18
#Sta/Elev= 30
  4557.4  402.21  4607.5  399.38  4628.7  396.34  4674.7  392.57  4680.6  393.15
  4717.1  385.33    4723  384.89  4732.5  382.06    4746  380.23  4753.7   377.7
  4790.3   373.9  4796.2  372.45    4805  372.83  4817.4  370.92  4869.3  369.12
  4911.7   370.8  4984.8  371.56  4990.7  366.35  4993.4  365.85  4996.7  366.35
  5000.3  367.33  5006.1  368.05  5015.5  371.66    5030  371.45  5049.5  371.27
  5100.4   373.4  5192.2  385.82  5222.8  391.43    5233  391.85    5284  401.63
#Mann= 5 ,-1 , 0
  4557.4     .16       0  4990.7     .07       0  4996.7     .16       0
  5000.3     .12       0    5030     .16       0
Bank Sta=4984.8,5015.5
XS Rating Curve= 0 ,0
Exp/Cntr=0.3,0.1

Type RM Length L Ch R = 1 ,57618   ,434,434,434
BEGIN DESCRIPTION:
UNT094 IN BECR 94.0
END DESCRIPTION:
XS GIS Cut Line= 3
      3790249.64     10567210.17      3789849.61     10567460.19
      3789749.58     10567560.21
#Sta/Elev= 30
  4565.4  400.89    4579  400.57  4588.4   398.8  4594.3  399.24  4609.7   396.1
  4615.6  396.68  4659.8  390.47  4688.7  385.53  4695.2  383.31  4709.9  381.05
  4725.2  377.01  4731.1  376.59  4740.6  372.87  4746.5     374  4767.7  369.68
  4819.6  367.27  4840.8  368.66  4848.5  367.71  4871.5  367.51  4907.4  369.18
    4987  370.12  4989.9  366.02  4992.7  365.52  4995.9  366.02  5001.8  366.33
  5014.1  369.64  5040.7  370.95  5083.7  376.58  5136.1  383.93  5178.6  388.64
#Mann= 4 ,-1 , 0
  4565.4     .16       0  4989.9     .07       0  4995.9     .16       0
  5083.7     .05       0
Bank Sta=4987,5014.1
XS Rating Curve= 0 ,0
Exp/Cntr=0.3,0.1

Type RM Length L Ch R = 1 ,57184   ,474,474,474
BEGIN DESCRIPTION:
UNT094 IN BECR 93.0
END DESCRIPTION:
XS GIS Cut Line= 3
      3790049.62     10567010.19      3789649.61     10567110.19
       3789549.6     10567360.21
#Sta/Elev= 30
  4568.7  391.43  4586.7  388.52  4591.9  389.03  4599.6  386.88  4620.2   383.6
  4632.4  382.97  4640.9  380.54  4669.2  376.28  4702.7   371.4  4723.3  370.06
  4743.9  366.72  4792.9  365.17  4857.3  366.44  4875.4  365.53  4977.2   367.2
  4983.7  367.22  5002.6   364.3  5010.3  361.04  5013.1  360.54  5016.3  361.04
  5020.1   361.7  5025.4  366.99  5034.9  366.04  5049.7  367.82  5127.8  371.49
  5142.6  373.61    5152  373.95  5164.1  376.27  5228.7  381.91  5250.3   384.9
#Mann= 5 ,-1 , 0
  4568.7     .05       0  4632.4     .16       0  4977.2     .05       0
  5010.3     .03       0  5016.3     .05       0
Bank Sta=4983.7,5025.4
XS Rating Curve= 0 ,0
Exp/Cntr=0.3,0.1

Type RM Length L Ch R = 1 ,56710   ,526,526,526
BEGIN DESCRIPTION:
UNT094 IN BECR 92.0
END DESCRIPTION:
XS GIS Cut Line= 3
      3789649.58     10566560.21      3789249.61     10566960.19
      3789149.59     10567160.23
#Sta/Elev= 30
  4457.9   382.6  4514.4  376.55  4528.6  374.44    4571   371.1  4599.3  369.47
  4641.7   368.9  4698.3  365.37  4740.7  363.62    4765  363.96  4825.6  363.54
  4910.4  365.17  4981.1  365.01  4992.3  361.06    4995  360.56  4998.3  361.06
  5009.4  365.09  5026.3  364.71  5037.5   363.8  5045.9  364.62  5068.3  365.03
  5104.6   367.3    5113  369.02  5135.4   371.6  5143.7  373.19  5157.7  373.72
  5166.1  375.07  5180.1  375.86  5202.4  378.44  5216.4  378.94  5247.2  381.94
#Mann= 4 ,-1 , 0
  4457.9     .16       0    4765     .05       0  4992.3     .03       0
  4998.3     .05       0
Bank Sta=4981.1,5009.4
XS Rating Curve= 0 ,0
Exp/Cntr=0.3,0.1

Type RM Length L Ch R = 1 ,56184   ,462,462,462
BEGIN DESCRIPTION:
UNT094 IN BECR 91.0
END DESCRIPTION:
XS GIS Cut Line= 3
      3788849.61     10566460.21      3788799.61     10566860.19
       3788849.6     10567160.16
#Sta/Elev= 30
  4599.1  389.39  4659.5  386.03  4669.6  386.54  4688.2  383.08  4709.9  380.25
  4717.5  377.19  4722.5  379.38  4730.1  378.15  4740.2  374.46  4760.3   370.2
  4770.4  370.81  4790.6  368.02  4798.1  368.28  4810.7  365.15  4861.1  362.41
  4871.2  359.69  4911.5  362.13    4972  363.51  4992.1  362.68  4996.7  358.08
  4999.4  357.58  5002.7  358.08  5022.5  363.48  5052.9  362.38  5113.7  363.21
  5178.4  371.48  5217.6  375.21  5225.2  377.55  5235.4  377.82  5306.3  389.15
#Mann= 5 ,-1 , 0
  4599.1     .16       0  4688.2     .12       0  4996.7     .07       0
  5002.7     .12       0  5178.4     .16       0
Bank Sta=4972,5022.5
XS Rating Curve= 0 ,0
Exp/Cntr=0.3,0.1

Type RM Length L Ch R = 1 ,55722   ,500,500,500
BEGIN DESCRIPTION:
UNT094 IN BECR 90.0
END DESCRIPTION:
XS GIS Cut Line= 3
      3788549.62     10566560.18      3788399.61     10566710.19
      3788199.59     10567110.23
#Sta/Elev= 30
  4800.3  379.27  4856.9  375.47  4927.6  365.07  4955.9  363.11    4970  362.07
  4984.2  359.82  4995.3  356.43  4998.1  355.93  5001.3  356.43  5008.9  362.06
  5057.2  360.67  5065.6  361.51  5079.5  361.39  5087.9  360.51  5093.5  361.39
  5138.2  361.36  5199.7   363.8    5250  363.15  5317.1  367.25  5337.5  369.41
  5347.9  369.96  5356.2   371.4  5392.6  373.25    5401  374.62  5414.9  374.89
  5423.3  376.12  5428.9  375.31  5437.3   377.3  5445.7  377.16  5459.7  378.89
#Mann= 4 ,-1 , 0
  4800.3     .12       0  4995.3     .07       0  5001.3     .12       0
  5337.5     .16       0
Bank Sta=4955.9,5008.9
XS Rating Curve= 0 ,0
Exp/Cntr=0.3,0.1

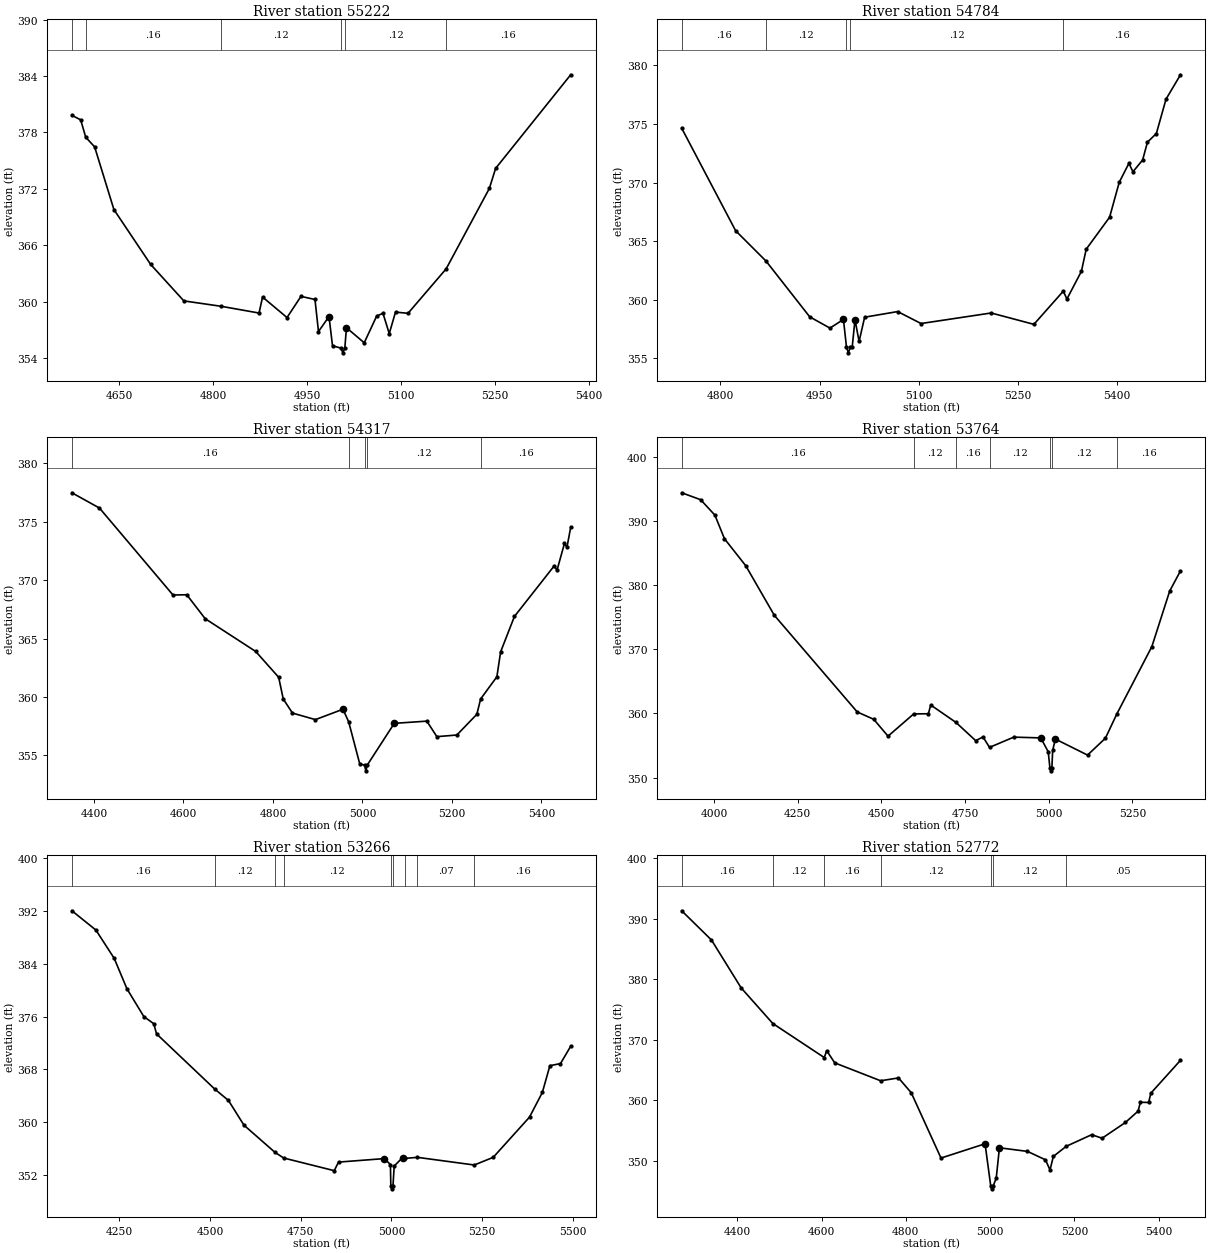
Type RM Length L Ch R = 1 ,55222   ,438,438,438
BEGIN DESCRIPTION:
UNT094 IN BECR 89.0
END DESCRIPTION:
XS GIS Cut Line= 3
       3788349.6     10566410.19      3787949.61     10566610.19
      3787599.61     10566610.19
#Sta/Elev= 30
  4574.2  379.82  4588.2  379.34  4596.3  377.49  4610.5  376.47  4641.3  369.81
    4700  363.98  4753.1   360.1  4812.4  359.53  4873.3  358.81  4878.9  360.51
    4918  358.33  4940.3  360.58  4962.7  360.25  4968.3  356.84  4985.1  358.44
  4990.7  355.33  5004.4  355.08  5007.2  354.58  5010.4  355.08    5013  357.25
  5041.4  355.65  5061.4   358.5  5071.4  358.78  5081.4  356.62  5091.4  358.91
  5111.4  358.78  5172.3   363.5  5241.4  372.05  5251.4  374.18  5371.4  384.13
#Mann= 6 ,-1 , 0
  4574.2     .12       0  4596.3     .16       0  4812.4     .12       0
  5004.4     .07       0  5010.4     .12       0  5172.3     .16       0
Bank Sta=4985.1,5013
XS Rating Curve= 0 ,0
Exp/Cntr=0.3,0.1

Type RM Length L Ch R = 1 ,54784   ,467,467,467
BEGIN DESCRIPTION:
UNT094 IN BECR 88.0
END DESCRIPTION:
XS GIS Cut Line= 3
      3788299.65      10566310.2      3788049.61     10566260.19
       3787649.6     10566560.19
#Sta/Elev= 30
  4741.3  374.64  4822.9   365.9  4868.9  363.31  4935.1  358.55  4965.7  357.59
  4986.1  358.33  4990.7  355.98  4993.5  355.48  4996.7  355.98  4999.4  355.98
  5003.6  358.31  5009.8  356.45  5018.2  358.52  5068.2     359  5103.6  357.98
  5209.8  358.88  5274.4  357.91  5318.9  360.74  5324.4  360.07  5346.3  362.43
  5353.6  364.32    5389  367.05  5403.6  370.03  5418.2  371.64  5424.4  370.93
    5439  371.93  5446.3  373.45  5459.8  374.19  5474.4  377.12  5496.3   379.2
#Mann= 5 ,-1 , 0
  4741.3     .16       0  4868.9     .12       0  4990.7     .07       0
  4996.7     .12       0  5318.9     .16       0
Bank Sta=4986.1,5003.6
XS Rating Curve= 0 ,0
Exp/Cntr=0.3,0.1

Type RM Length L Ch R = 1 ,54317   ,553,553,553
BEGIN DESCRIPTION:
UNT094 IN BECR 87.0
END DESCRIPTION:
XS GIS Cut Line= 3
      3787949.62     10565410.14      3787799.61     10566060.19
      3787599.63     10566460.15
#Sta/Elev= 30
    4351  377.49  4412.6  376.18  4576.8  368.73  4607.6  368.75  4648.7   366.7
  4761.6  363.89  4812.9  361.68  4823.1  359.82  4843.7  358.61    4895  358.05
  4956.6  358.94  4969.4  357.85  4994.2  354.23  5004.9  354.16  5007.6  353.66
  5010.9  354.16  5071.2  357.73  5143.9  357.92  5166.3  356.59    5211  356.73
  5255.7  358.51  5264.1  359.82  5300.4  361.72  5308.8  363.86  5339.6  366.89
    5429  371.25  5434.6  370.83  5451.4  373.15    5457  372.82  5465.3  374.53
#Mann= 5 ,-1 , 0
    4351     .16       0  4969.4     .12       0  5004.9     .07       0
  5010.9     .12       0  5264.1     .16       0
Bank Sta=4956.6,5071.2
XS Rating Curve= 0 ,0
Exp/Cntr=0.3,0.1

Type RM Length L Ch R = 1 ,53764   ,498,498,498
BEGIN DESCRIPTION:
UNT094 IN BECR 86.0
END DESCRIPTION:
XS GIS Cut Line= 3
      3786549.58     10565460.16      3787349.61     10566160.19
      3787499.63     10566560.23
#Sta/Elev= 30
  3903.6  394.43  3960.1  393.35  4002.8  390.94  4031.3  387.26  4094.9  383.05
  4180.3  375.31    4428  360.23  4477.4  359.08  4520.1  356.45  4596.7  359.92
  4640.6  359.95  4647.7  361.31  4722.9   358.6    4782  355.75  4803.9  356.33
  4823.3   354.7  4895.9   356.3  4976.4  356.18  4998.7  354.02  5003.7  351.54
  5006.5  351.04  5009.7  351.54    5012  354.22  5020.1     356  5116.2   353.5
  5169.6  356.13  5203.8  359.92  5308.4  370.43  5361.8  379.11  5393.9  382.24
#Mann= 7 ,-1 , 0
  3903.6     .16       0  4596.7     .12       0  4722.9     .16       0
  4823.3     .12       0  5003.7     .07       0  5009.7     .12       0
  5203.8     .16       0
Bank Sta=4976.4,5020.1
XS Rating Curve= 0 ,0
Exp/Cntr=0.3,0.1

Type RM Length L Ch R = 1 ,53266   ,494,494,494
BEGIN DESCRIPTION:
UNT094 IN BECR 85.0
END DESCRIPTION:
XS GIS Cut Line= 3
      3786549.61     10565560.19      3786999.61     10566310.19
      3787299.59     10566710.16
#Sta/Elev= 30
  4119.4  392.02  4185.5   389.1    4236  384.81    4271  380.21  4317.6     376
  4344.9  374.92  4352.6  373.38  4512.4  365.05  4550.9  363.29  4593.6  359.55
  4678.5  355.46  4702.9  354.58  4842.4  352.66  4854.1  353.96  4980.4  354.49
  4997.2  353.59  4998.3  350.41  5001.1  349.91  5004.3  350.41  5007.6  353.36
  5030.5  354.64  5037.9  354.52  5071.5  354.68  5228.3  353.52  5280.5  354.68
  5380.5  360.77  5415.9  364.51  5436.7  368.56  5465.9  368.88    5494   371.5
#Mann= 9 ,-1 , 0
  4119.4     .16       0  4512.4     .12       0  4678.5     .16       0
  4702.9     .12       0  4998.3     .07       0  5004.3     .12       0
  5037.9     .05       0  5071.5     .07       0  5228.3     .16       0
Bank Sta=4980.4,5030.5
XS Rating Curve= 0 ,0
Exp/Cntr=0.3,0.1

Type RM Length L Ch R = 1 ,52772   ,527,527,527
BEGIN DESCRIPTION:
UNT094 IN BECR 84.0
END DESCRIPTION:
XS GIS Cut Line= 3
      3786499.61     10565610.22      3786599.61     10566360.19
      3786449.61     10566760.18
#Sta/Elev= 30
    4268  391.32  4338.6  386.49  4409.2  378.56  4484.2  372.68  4606.3  367.05
  4612.2  368.18  4631.2  366.17  4740.1  363.21  4782.5  363.68  4812.7  361.24
  4883.4  350.43    4988  352.79  5001.4  345.84  5004.2  345.34  5007.4  345.84
  5014.5   347.1  5022.1  352.13  5088.7  351.53  5131.4  350.14  5142.1  348.46
  5150.1   350.7  5180.6  352.37  5240.9  354.29  5265.8  353.71    5321  356.31
  5351.2  358.19  5356.6  359.66  5376.2  359.62  5381.5  361.16  5451.8  366.59
#Mann= 7 ,-1 , 0
    4268     .16       0  4484.2     .12       0  4606.3     .16       0
  4740.1     .12       0  5001.4     .07       0  5007.4     .12       0
  5180.6     .05       0
Bank Sta=4988,5022.1
XS Rating Curve= 0 ,0
Exp/Cntr=0.3,0.1

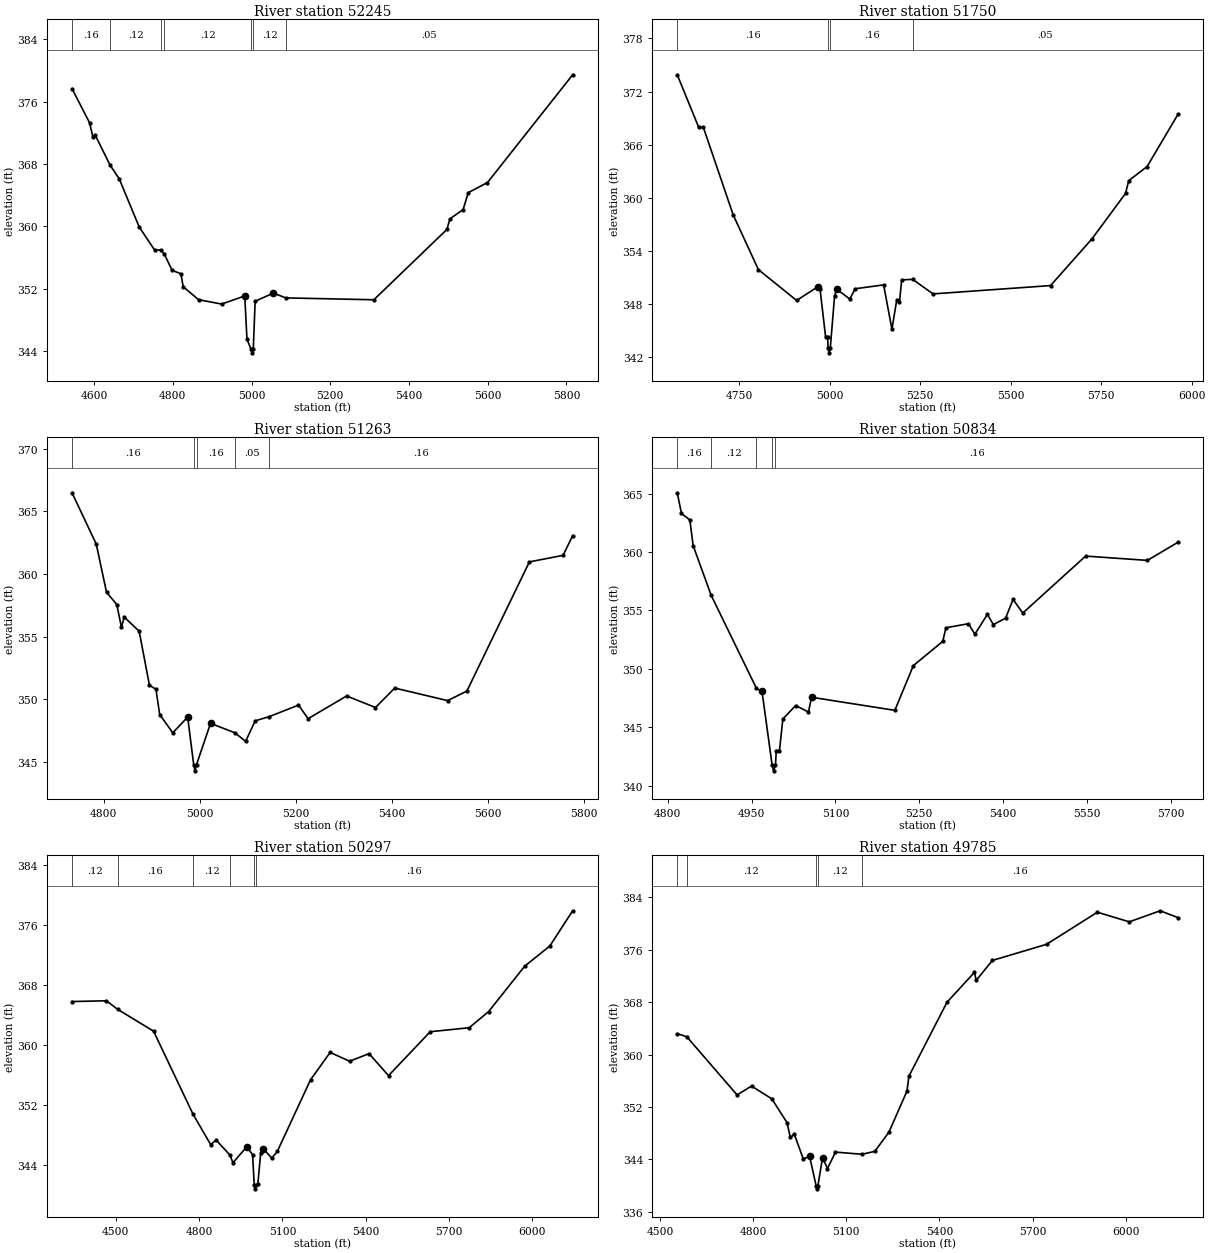
Type RM Length L Ch R = 1 ,52245   ,495,495,495
BEGIN DESCRIPTION:
UNT094 IN BECR 83.0
END DESCRIPTION:
XS GIS Cut Line= 3
      3786449.59     10565760.23      3786249.61     10566160.19
      3786449.61      10566960.2
#Sta/Elev= 30
    4544  377.66  4588.7  373.27  4597.1  371.43  4602.6  371.73  4640.7  367.85
  4664.1  366.07  4714.5  359.93  4753.6  356.96  4770.1  356.96  4778.8   356.4
  4798.3  354.34  4820.7  353.91  4826.3  352.25  4865.4  350.58  4924.1  350.02
  4982.8  351.06  4988.4  345.51  4998.5  344.26  5001.2  343.76  5004.5  344.26
  5009.2  350.38  5055.6  351.43  5086.7  350.81  5310.7  350.57  5496.2  359.59
    5504  360.95  5537.5  362.15  5550.4  364.31  5599.3  365.61  5815.8  379.44
#Mann= 7 ,-1 , 0
    4544     .16       0  4640.7     .12       0  4770.1     .16       0
  4778.8     .12       0  4998.5     .07       0  5004.5     .12       0
  5086.7     .05       0
Bank Sta=4982.8,5055.6
XS Rating Curve= 0 ,0
Exp/Cntr=0.3,0.1

Type RM Length L Ch R = 1 ,51750   ,487,487,487
BEGIN DESCRIPTION:
UNT094 IN BECR 82.0
END DESCRIPTION:
XS GIS Cut Line= 3
      3785899.61      10565660.2      3785799.61     10566060.19
      3786349.59     10566860.17
#Sta/Elev= 30
  4579.1   373.9  4638.4  367.96  4651.2  367.96  4733.7  358.06  4803.3  351.88
  4908.9   348.4  4968.2  349.97  4973.4  349.74  4988.8  344.32  4994.4  344.32
  4995.8  342.98  4998.6  342.48  5001.8  342.98  5013.7  348.92  5019.8  349.67
  5055.7  348.56  5070.6  349.72  5149.2  350.16  5172.1  345.15  5185.6   348.5
    5193  348.22  5199.1  350.73  5229.5  350.78  5285.7  349.14  5610.3  350.08
  5724.8  355.36  5817.4  360.49  5826.3  361.94    5877  363.53  5962.2  369.42
#Mann= 4 ,-1 , 0
  4579.1     .16       0  4995.8     .07       0  5001.8     .16       0
  5229.5     .05       0
Bank Sta=4968.2,5019.8
XS Rating Curve= 0 ,0
Exp/Cntr=0.3,0.1

Type RM Length L Ch R = 1 ,51263   ,429,429,429
BEGIN DESCRIPTION:
UNT094 IN BECR 81.0
END DESCRIPTION:
XS GIS Cut Line= 3
      3785299.62     10565810.21      3785449.61     10566060.19
      3785499.61      10566810.2
#Sta/Elev= 30
  4734.2  366.48  4784.7  362.39  4806.1  358.55  4827.5  357.57  4837.2  355.75
    4843  356.57  4874.1  355.44  4895.5  351.14  4909.1  350.81  4916.9   348.8
  4944.1  347.34  4975.2   348.6  4987.7  344.81  4990.5  344.31  4993.7  344.81
  5022.8   348.1  5073.7  347.34  5095.9  346.66  5115.9   348.3  5144.9  348.63
  5206.1  349.55  5226.2  348.47  5306.3  350.28  5366.5  349.36  5406.6  350.91
  5516.8  349.91  5556.9  350.67  5687.2  360.97  5757.3  361.49  5777.4  363.06
#Mann= 5 ,-1 , 0
  4734.2     .16       0  4987.7     .07       0  4993.7     .16       0
  5073.7     .05       0  5144.9     .16       0
Bank Sta=4975.2,5022.8
XS Rating Curve= 0 ,0
Exp/Cntr=0.3,0.1

Type RM Length L Ch R = 1 ,50834   ,537,537,537
BEGIN DESCRIPTION:
UNT094 IN BECR 80.0
END DESCRIPTION:
XS GIS Cut Line= 3
      3785199.61     10565810.19      3785099.61     10565960.19
      3784799.59     10566610.22
#Sta/Elev= 30
  4816.9  365.08  4824.4  363.31  4839.4  362.76  4845.4  360.55  4877.6   356.3
  4958.7  348.33  4968.6  348.08  4986.7  341.77  4989.4  341.27  4992.7  341.77
  4994.2  343.01  4999.9  343.01  5005.9  345.71  5028.8  346.86  5051.8  346.31
  5057.3  347.57  5206.4  346.45  5239.5  350.28  5292.2  352.36  5297.8  353.52
  5338.1  353.87  5349.6  352.97  5372.1  354.67  5382.7  353.79  5404.7  354.35
    5418  355.95  5435.4  354.78  5547.9  359.66  5658.5  359.29  5713.1  360.84
#Mann= 5 ,-1 , 0
  4816.9     .16       0  4877.6     .12       0  4958.7     .16       0
  4986.7     .07       0  4992.7     .16       0
Bank Sta=4968.6,5057.3
XS Rating Curve= 0 ,0
Exp/Cntr=0.3,0.1

Type RM Length L Ch R = 1 ,50297   ,512,512,512
BEGIN DESCRIPTION:
UNT094 IN BECR 79.0
END DESCRIPTION:
XS GIS Cut Line= 3
      3784853.11     10565360.47      3784662.15     10565803.16
      3784601.39     10567122.64
#Sta/Elev= 30
  4342.2  365.83  4465.9  365.93  4506.3   364.8  4635.9  361.88  4778.1  350.82
  4841.4  346.78  4861.4  347.37  4911.9  345.34  4921.5  344.35  4971.5  346.48
  4992.4  345.44  4998.5  341.38  5001.3  340.88  5004.5  341.38  5011.5  341.55
  5021.6  345.61  5031.6  346.19  5061.6  344.97  5081.6  345.87  5201.2  355.41
  5271.8  359.05  5341.9  357.88    5412  358.89    5482  355.96  5632.2  361.81
  5772.4  362.34  5842.4  364.49  5972.6  370.55  6062.7  373.22  6145.2  377.92
#Mann= 6 ,-1 , 0
  4342.2     .12       0  4506.3     .16       0  4778.1     .12       0
  4911.9     .16       0  4998.5     .07       0  5004.5     .16       0
Bank Sta=4971.5,5031.6
XS Rating Curve= 0 ,0
Exp/Cntr=0.3,0.1

Type RM Length L Ch R = 1 ,49785   ,786,786,786
BEGIN DESCRIPTION:
UNT094 IN BECR 78.0
END DESCRIPTION:
XS GIS Cut Line= 4
      3784297.57     10565560.08      3784123.96     10566167.74
      3783759.37      10566766.7       3783483.1     10566809.87
#Sta/Elev= 30
  4555.3  363.19  4586.1  362.71    4748  353.83  4794.6  355.18  4859.8  353.24
    4909  349.59  4919.4  347.35  4932.6  347.81    4961  344.08  4981.8  344.43
  5002.4  339.99  5005.1  339.49  5008.4  339.99  5023.4  344.26  5039.2  342.59
    5065   345.1  5150.3  344.77  5191.6  345.21    5237  348.13  5295.5  354.44
  5301.4  356.68  5424.3  367.99  5512.5  372.54  5518.4  371.33  5570.6  374.37
    5745  376.83  5908.5  381.73  6011.5  380.26  6110.9  381.95  6168.1  380.91
#Mann= 5 ,-1 , 0
  4555.3     .16       0  4586.1     .12       0  5002.4     .07       0
  5008.4     .12       0  5150.3     .16       0
Bank Sta=4981.8,5023.4
XS Rating Curve= 0 ,0
Exp/Cntr=0.3,0.1

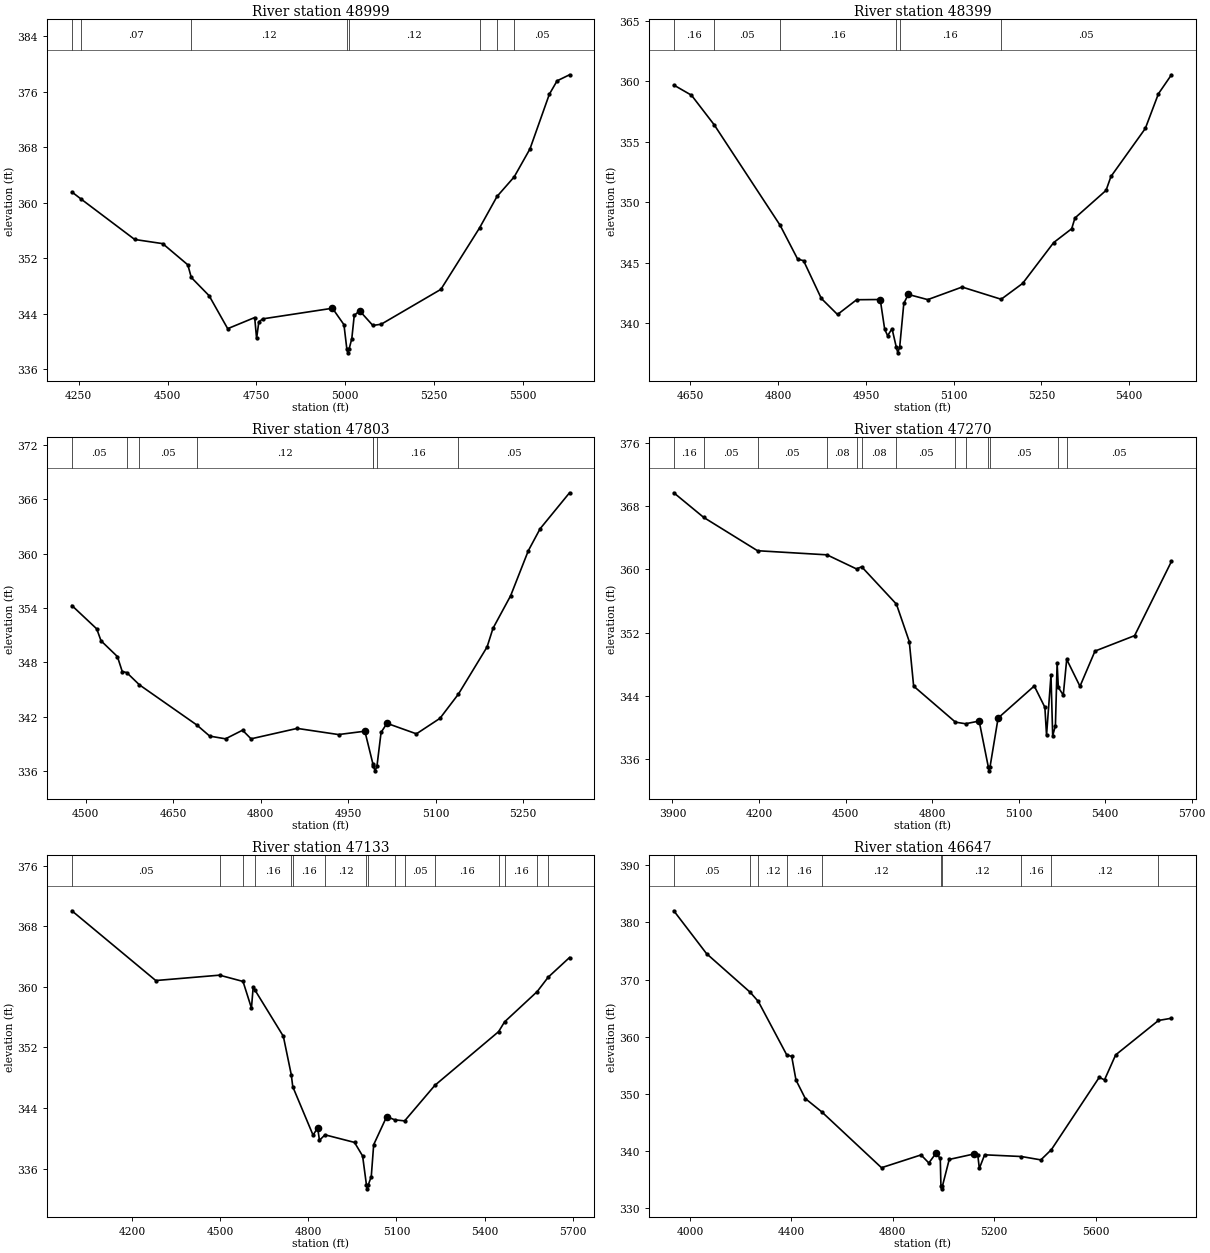
Type RM Length L Ch R = 1 ,48999   ,600,600,600
BEGIN DESCRIPTION:
UNT094 IN BECR 77.0
END DESCRIPTION:
XS GIS Cut Line= 3
      3784193.55     10565536.35      3783887.98     10565772.47
      3782957.47     10566175.23
#Sta/Elev= 30
  4230.6  361.55    4257  360.51  4407.4  354.71  4486.2  354.11  4556.8  351.06
  4566.6  349.24  4616.8  346.61    4669  341.87  4744.9  343.47  4750.3  340.46
  4756.6  342.84  4767.5  343.28  4963.7  344.81  4996.1  342.44  5004.3  338.89
    5007  338.39  5010.3  338.89  5018.2  340.45    5025  343.77    5040  344.45
  5077.4  342.33  5100.9  342.51  5268.8  347.53  5377.5  356.37  5426.8  360.91
    5475  363.72  5519.4  367.75  5573.9  375.62  5595.7  377.55  5630.7  378.42
#Mann= 8 ,-1 , 0
  4230.6     .16       0    4257     .07       0  4566.6     .12       0
  5004.3     .07       0  5010.3     .12       0  5377.5     .05       0
  5426.8     .16       0    5475     .05       0
Bank Sta=4963.7,5040
XS Rating Curve= 0 ,0
Exp/Cntr=0.3,0.1

Type RM Length L Ch R = 1 ,48399   ,596,596,596
BEGIN DESCRIPTION:
UNT094 IN BECR 76.0
END DESCRIPTION:
XS GIS Cut Line= 3
      3784099.62     10565360.19      3783699.61     10565410.19
      3783299.64     10565610.17
#Sta/Elev= 30
  4621.8  359.68    4652  358.84  4690.9  356.39  4803.4  348.09  4833.4  345.29
  4843.5  345.16  4873.8  342.04  4901.5  340.71  4934.2  341.93  4974.5  341.95
  4982.1  339.49  4987.1  338.96  4994.7  339.53  5001.8  338.04  5004.5  337.54
  5007.8  338.04  5014.8  341.63  5022.4  342.37  5055.7  341.94  5114.4  342.98
  5181.1  341.97  5217.8  343.28  5270.9  346.66  5301.6   347.8  5307.2  348.69
  5360.3  350.97  5368.7  352.12  5427.4  356.09  5449.8  358.96  5472.1  360.53
#Mann= 6 ,-1 , 0
  4621.8     .16       0  4690.9     .05       0  4803.4     .16       0
  5001.8     .07       0  5007.8     .16       0  5181.1     .05       0
Bank Sta=4974.5,5022.4
XS Rating Curve= 0 ,0
Exp/Cntr=0.3,0.1

Type RM Length L Ch R = 1 ,47803   ,533,533,533
BEGIN DESCRIPTION:
UNT094 IN BECR 75.0
END DESCRIPTION:
XS GIS Cut Line= 3
      3783999.58     10565310.17      3783599.61     10565010.19
      3783249.63     10565060.19
#Sta/Elev= 30
  4476.3  354.28    4519   351.7  4526.3  350.39  4554.4  348.65  4562.7     347
  4570.3  346.89  4592.2  345.53  4690.5  341.11  4712.7  339.88  4739.8  339.58
    4769  340.53  4783.6  339.58  4862.7  340.73  4933.6  340.05  4978.8  340.42
  4992.6  336.81  4993.5  336.55  4996.2  336.05  4999.5  336.55  5006.6  340.29
  5016.7  341.29  5067.2  340.13  5107.6  341.84  5139.2  344.51  5188.4  349.71
  5198.5  351.76  5228.8  355.36  5259.1  360.32  5279.3  362.74  5329.8  366.71
#Mann= 8 ,-1 , 0
  4476.3     .05       0  4570.3     .16       0  4592.2     .05       0
  4690.5     .12       0  4992.6     .16       0  4993.5     .07       0
  4999.5     .16       0  5139.2     .05       0
Bank Sta=4978.8,5016.7
XS Rating Curve= 0 ,0
Exp/Cntr=0.3,0.1

Type RM Length L Ch R = 1 ,47270   ,137,137,137
BEGIN DESCRIPTION:
UNT094 IN BECR 74.0
END DESCRIPTION:
XS GIS Cut Line= 5
      3784704.15     10564026.26      3783870.83      10564560.1
      3783645.14     10564681.63      3783441.14      10564807.5
      3783307.24      10565006.2
#Sta/Elev= 30
  3904.7  369.69  4008.3  366.58  4194.9  362.37  4435.7  361.85  4538.1  360.07
  4556.1  360.34  4676.5  355.62    4721   350.9  4736.2  345.26  4881.2  340.71
  4916.2  340.51  4963.3  340.85    4995  335.06  4997.7  334.56    5001  335.06
    5029  341.23  5154.4  345.28  5191.1  342.59  5196.9  339.06  5212.3  346.63
  5218.2  338.99  5227.7  340.27  5233.6  348.15  5237.8   345.1  5254.9  344.13
  5266.8  348.64  5312.8  345.24  5364.9  349.69  5502.2  351.64    5630  361.02
#Mann= 13 ,-1 , 0
  3904.7     .16       0  4008.3     .05       0  4194.9     .05       0
  4435.7     .08       0  4538.1     .16       0  4556.1     .08       0
  4676.5     .05       0  4881.2     .16       0  4916.2     .05       0
    4995     .04       0    5001     .05       0  5237.8     .16       0
  5266.8     .05       0
Bank Sta=4963.3,5029
XS Rating Curve= 0 ,0
Exp/Cntr=0.3,0.1

Type RM Length L Ch R = 1 ,47133   ,486,486,486
BEGIN DESCRIPTION:
Mapping XS eb0e2c66
END DESCRIPTION:
XS GIS Cut Line= 5
       3784582.6     10563948.15       3783931.6     10564373.47
      3783710.24       10564495.      3783462.85     10564625.21
        3783164.     10564867.75
#Sta/Elev= 30
  3994.6  370.05  4280.3  360.84  4497.5  361.55  4577.4  360.72  4606.1  357.21
  4612.1  360.01  4618.7  359.54  4714.7  353.48  4741.7  348.41  4746.8  346.82
  4815.9  340.43  4831.5  341.39  4837.7  339.75  4856.7  340.47    4957  339.47
  4984.6  337.68  4997.7  333.84  5000.4  333.34  5003.7  333.84  5014.1  334.96
  5022.3  339.17  5066.6  342.88  5094.1  342.45  5127.7  342.31  5230.8  347.01
  5447.6  354.09  5467.9  355.38    5579  359.38  5616.5  361.28  5689.2  363.88
#Mann= 16 ,-1 , 0
  3994.6     .05       0  4497.5     .16       0  4577.4     .05       0
  4618.7     .16       0  4741.7     .12       0  4746.8     .16       0
  4856.7     .12       0  4997.7     .07       0  5003.7     .12       0
  5094.1     .16       0  5127.7     .05       0  5230.8     .16       0
  5447.6     .12       0  5467.9     .16       0    5579     .12       0
  5616.5     .16       0
Bank Sta=4831.5,5066.6
XS Rating Curve= 0 ,0
Exp/Cntr=0.3,0.1

Type RM Length L Ch R = 1 ,46647   ,777,777,777
BEGIN DESCRIPTION:
UNT094 IN BECR 72.0
END DESCRIPTION:
XS GIS Cut Line= 3
      3784575.77     10563663.11      3783525.42     10564175.27
      3783057.54     10564816.44
#Sta/Elev= 30
  3936.5  382.05  4065.7  374.54  4238.1  367.76  4269.7  366.17  4381.8  356.81
  4401.3  356.55  4418.3   352.4  4455.1  349.16  4519.9  346.83  4755.5  337.05
  4911.3  339.29  4942.1  337.88  4970.2  339.58  4987.2  338.67  4989.8  333.85
  4992.5  333.35  4995.8  333.85  5022.5   338.5  5120.4  339.46    5135  339.31
  5141.2  336.92  5162.1  339.31  5307.3  339.01  5383.8  338.42  5425.4  340.22
  5613.9  352.87  5634.8  352.44  5678.8  356.81  5847.6  362.84  5898.8  363.23
#Mann= 10 ,-1 , 0
  3936.5     .05       0  4238.1     .16       0  4269.7     .12       0
  4381.8     .16       0  4519.9     .12       0  4989.8     .07       0
  4995.8     .12       0  5307.3     .16       0  5425.4     .12       0
  5847.6     .16       0
Bank Sta=4970.2,5120.4
XS Rating Curve= 0 ,0
Exp/Cntr=0.3,0.1