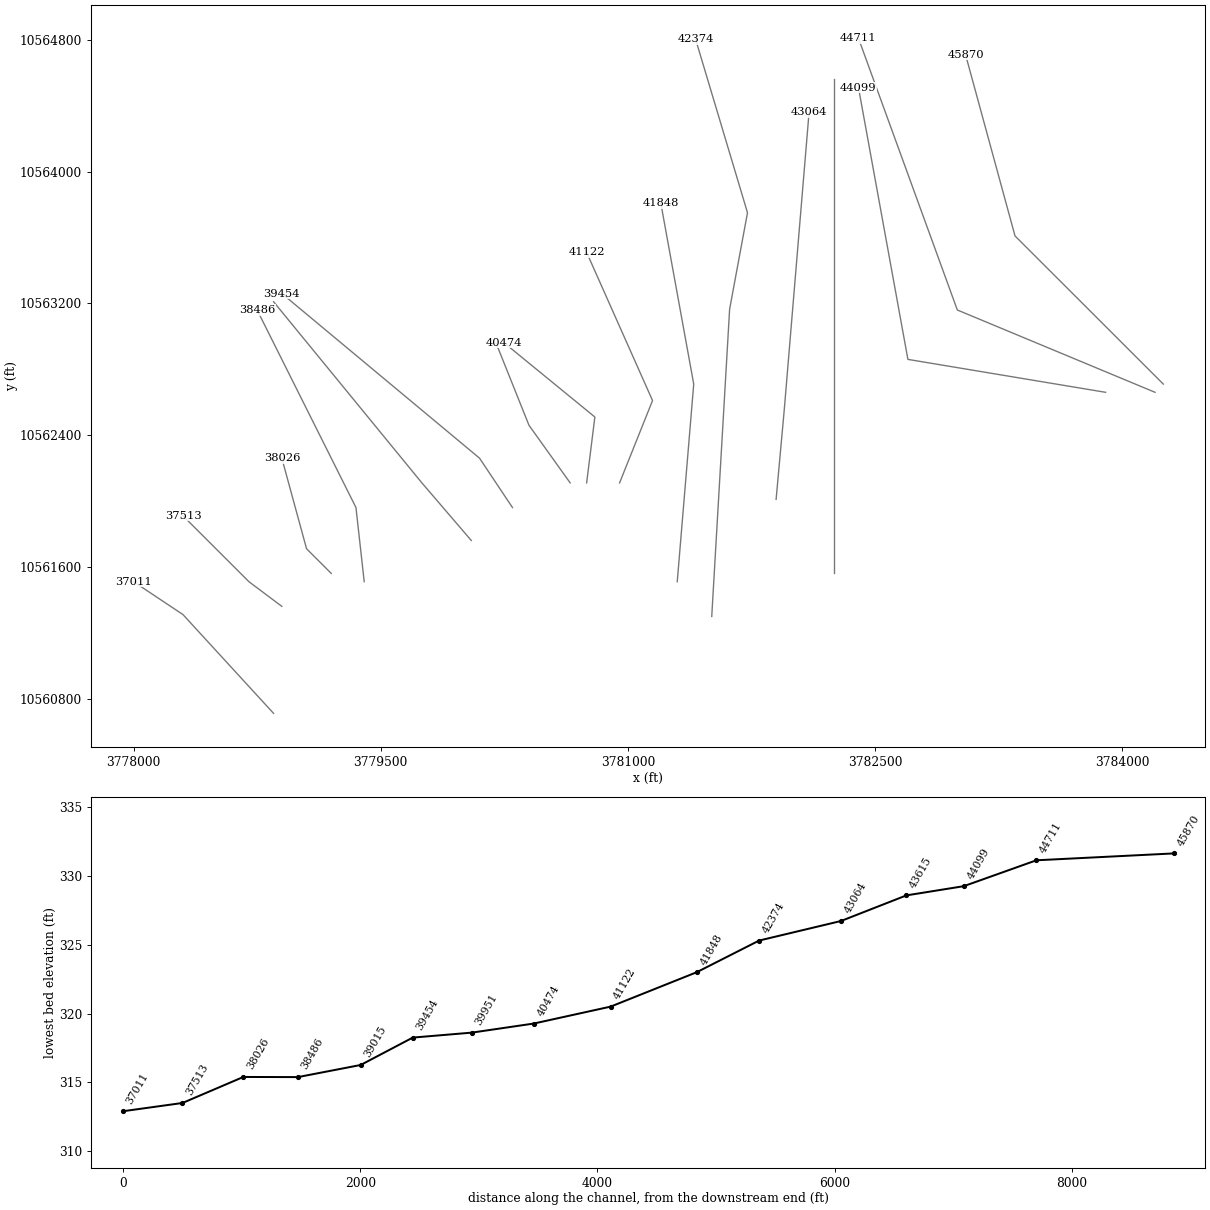
HEC-RAS study UNT094 IN BECR.prj: UNT094 IN BECR Base Level Engineering

--- UNT094 IN BECR.g01 (geometry) --- (continued)

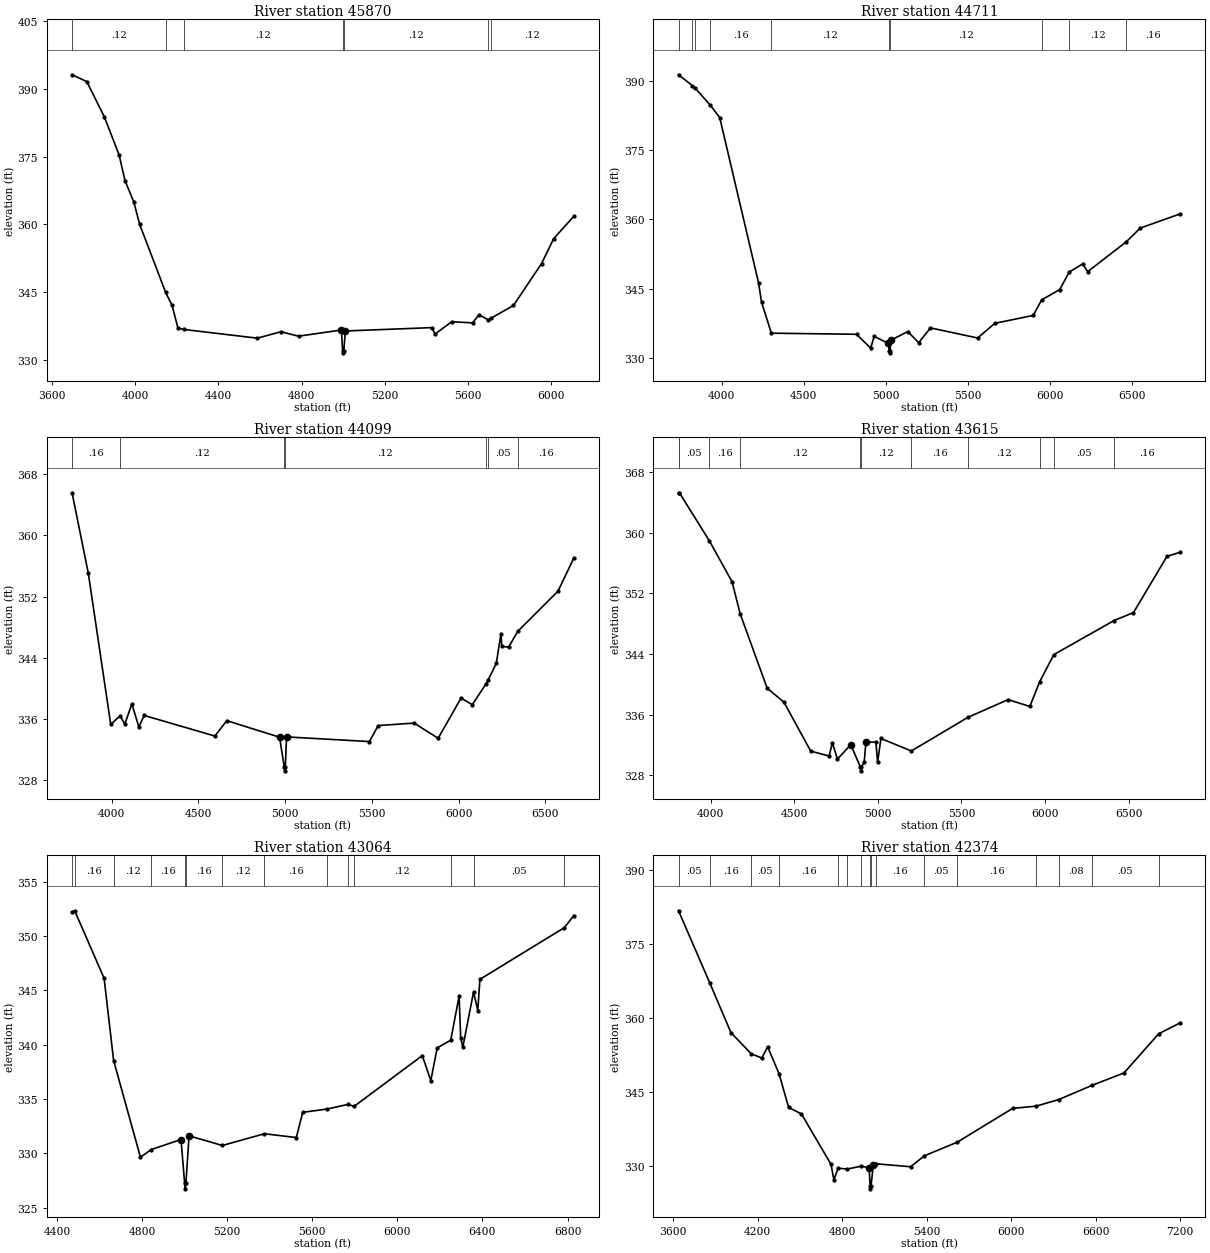
Type RM Length L Ch R = 1 ,45870   ,1159,1159,1159
BEGIN DESCRIPTION:
UNT094 IN BECR 71.0
END DESCRIPTION:
XS GIS Cut Line= 3
       3784249.6     10562710.19      3783349.61     10563610.19
       3783049.6     10564710.23
#Sta/Elev= 30
  3696.1  393.07  3766.8  391.57  3851.7  383.73  3922.4  375.34  3950.6  369.69
  3993.1  364.94  4021.4  359.99  4145.6  345.04  4176.9  342.12  4205.2   337.1
  4234.5  336.79    4587  334.87  4700.2  336.29    4785  335.31  4991.3  336.67
    4997  332.13  4999.7  331.63    5003  332.13  5010.3  336.46    5425   337.2
  5442.2   335.8  5521.7  338.51  5621.9  338.25    5653  340.05  5696.8  338.94
  5710.2  339.27  5818.8   342.1  5953.6  351.35  6012.3  356.88  6109.1  361.81
#Mann= 7 ,-1 , 0
  3696.1     .12       0  4145.6     .16       0  4234.5     .12       0
    4997     .07       0    5003     .12       0  5696.8     .16       0
  5710.2     .12       0
Bank Sta=4991.3,5010.3
XS Rating Curve= 0 ,0
Exp/Cntr=0.3,0.1

Type RM Length L Ch R = 1 ,44711   ,612,612,612
BEGIN DESCRIPTION:
UNT094 IN BECR 70.0
END DESCRIPTION:
XS GIS Cut Line= 3
      3784199.62     10562660.18      3782999.61     10563160.19
      3782399.62     10564810.17
#Sta/Elev= 30
  3736.9  391.24  3821.9  388.88  3835.2  388.47  3930.7  384.65  3987.7  381.98
  4224.4  346.23  4242.3  342.06  4302.3  335.38  4820.8  335.14  4906.9  332.15
  4928.6  334.71  5015.2  333.16  5019.3  331.63    5022  331.13  5025.3  331.63
  5027.7  333.83  5132.7  335.72  5199.8  333.33    5271  336.52  5558.3  334.34
  5662.7  337.51  5896.8  339.22  5948.4  342.58  6058.4  344.81  6116.3  348.59
  6197.4  350.36  6228.7  348.69  6463.1  355.12  6548.5   358.1  6792.6  361.18
#Mann= 10 ,-1 , 0
  3736.9     .12       0  3821.9     .16       0  3835.2     .12       0
  3930.7     .16       0  4302.3     .12       0  5019.3     .07       0
  5025.3     .12       0  5948.4     .16       0  6116.3     .12       0
  6463.1     .16       0
Bank Sta=5015.2,5027.7
XS Rating Curve= 0 ,0
Exp/Cntr=0.3,0.1

Type RM Length L Ch R = 1 ,44099   ,484,484,484
BEGIN DESCRIPTION:
UNT094 IN BECR 69.0
END DESCRIPTION:
XS GIS Cut Line= 3
       3783899.6     10562660.19      3782699.61     10562860.19
      3782399.61     10564510.19
#Sta/Elev= 30
    3771  365.54  3864.8  355.01    3994   335.3  4048.1  336.44  4075.1  335.34
  4115.7  337.99  4156.2  334.97  4186.6  336.48  4594.7  333.79  4663.1   335.8
  4967.3  333.64  4994.7  329.75  4997.5  329.25  5000.7  329.75  5007.9  333.68
  5485.6  333.07  5536.4  335.16  5743.5  335.48    5882   333.5  6014.1  338.75
  6078.9  337.88  6155.4  340.52  6170.2   341.1  6217.4  343.29  6244.1  347.11
  6249.1  345.49  6288.5   345.4  6341.4  347.46  6573.1   352.7  6664.6  357.03
#Mann= 7 ,-1 , 0
    3771     .16       0  4048.1     .12       0  4994.7     .07       0
  5000.7     .12       0  6155.4     .16       0  6170.2     .05       0
  6341.4     .16       0
Bank Sta=4967.3,5007.9
XS Rating Curve= 0 ,0
Exp/Cntr=0.3,0.1

Type RM Length L Ch R = 1 ,43615   ,551,551,551
BEGIN DESCRIPTION:
UNT094 IN BECR 68.0
END DESCRIPTION:
XS GIS Cut Line= 3
      3782249.61     10561560.16      3782249.61     10562760.19
      3782249.61     10564560.16
#Sta/Elev= 30
  3808.3  365.22  3813.5  365.28    3992  358.96  4128.3  353.54  4176.3  349.34
  4338.3  339.48  4438.3  337.65  4598.3  331.19  4708.3  330.53  4728.3  332.28
  4758.3  330.14  4838.3  332.03  4895.3  329.08  4898.1  328.58  4901.3  329.08
  4918.3  329.69  4928.3  332.34  4988.3  332.39  4998.3  329.69  5018.3  332.85
  5200.2   331.2  5537.7  335.63  5778.3  337.98  5908.3  337.08  5967.8  340.35
    6052  343.92  6412.4  348.42  6528.3  349.47  6728.3  356.88  6808.3  357.44
#Mann= 11 ,-1 , 0
  3808.3     .16       0  3813.5     .05       0    3992     .16       0
  4176.3     .12       0  4895.3     .07       0  4901.3     .12       0
  5200.2     .16       0  5537.7     .12       0  5967.8     .16       0
    6052     .05       0  6412.4     .16       0
Bank Sta=4838.3,4928.3
XS Rating Curve= 0 ,0
Exp/Cntr=0.3,0.1

Type RM Length L Ch R = 1 ,43064   ,690,690,690
BEGIN DESCRIPTION:
UNT094 IN BECR 67.0
END DESCRIPTION:
XS GIS Cut Line= 3
      3781899.61     10562010.15      3781949.61     10562560.19
      3782099.61     10564360.24
#Sta/Elev= 30
  4471.2  352.21  4483.5  352.31  4621.9  346.09  4666.6  338.52  4792.6  329.63
  4843.8  330.34  4983.3  331.26  5000.4  327.22  5003.2  326.72  5006.4  327.22
    5021   331.6  5177.6  330.71  5375.1  331.79  5525.2  331.44  5555.3  333.76
  5671.4  334.07  5770.1   334.5  5796.1   334.3  6117.3  338.98  6157.4  336.69
  6187.5  339.69    6251   340.4  6290.4  344.44  6297.9  340.63  6307.9  339.75
  6358.2  344.83  6378.2  343.13  6388.2     346  6784.6  350.75  6829.8  351.87
#Mann= 14 ,-1 , 0
  4471.2     .12       0  4483.5     .16       0  4666.6     .12       0
  4843.8     .16       0  5000.4     .07       0  5006.4     .16       0
  5177.6     .12       0  5375.1     .16       0  5671.4     .12       0
  5770.1     .16       0  5796.1     .12       0    6251     .16       0
  6358.2     .05       0  6784.6     .16       0
Bank Sta=4983.3,5021
XS Rating Curve= 0 ,0
Exp/Cntr=0.3,0.1

Type RM Length L Ch R = 1 ,42374   ,526,526,526
BEGIN DESCRIPTION:
UNT094 IN BECR 66.0
END DESCRIPTION:
XS GIS Cut Line= 4
      3781508.96     10561298.82      3781617.47      10563165.1
      3781725.98     10563751.04       3781411.3     10564803.57
#Sta/Elev= 30
  3637.8   381.7  3859.1   367.1  4009.8     357  4154.6  352.67  4230.2  351.84
  4270.2  354.13  4351.5  348.66  4419.9   341.8  4510.6   340.5    4721  330.26
    4741  327.14  4771.6  329.48  4836.3  329.32    4935  329.89  4991.5  329.59
  4998.5   325.8  5001.2   325.3  5004.5   325.8  5021.5  330.15  5040.9  330.38
  5286.3  329.78  5384.1     332  5617.2  334.76  6010.7  341.62  6177.6  342.07
  6339.3  343.42  6573.5  346.28  6801.2   348.8  7047.9  356.75  7201.7  358.98
#Mann= 16 ,-1 , 0
  3637.8     .05       0  3859.1     .16       0  4154.6     .05       0
  4351.5     .16       0  4771.6     .12       0  4836.3     .16       0
    4935     .12       0  4998.5     .07       0  5004.5     .12       0
  5040.9     .16       0  5384.1     .05       0  5617.2     .16       0
  6177.6     .05       0  6339.3     .08       0  6573.5     .05       0
  7047.9     .16       0
Bank Sta=4991.5,5021.5
XS Rating Curve= 0 ,0
Exp/Cntr=0.3,0.1

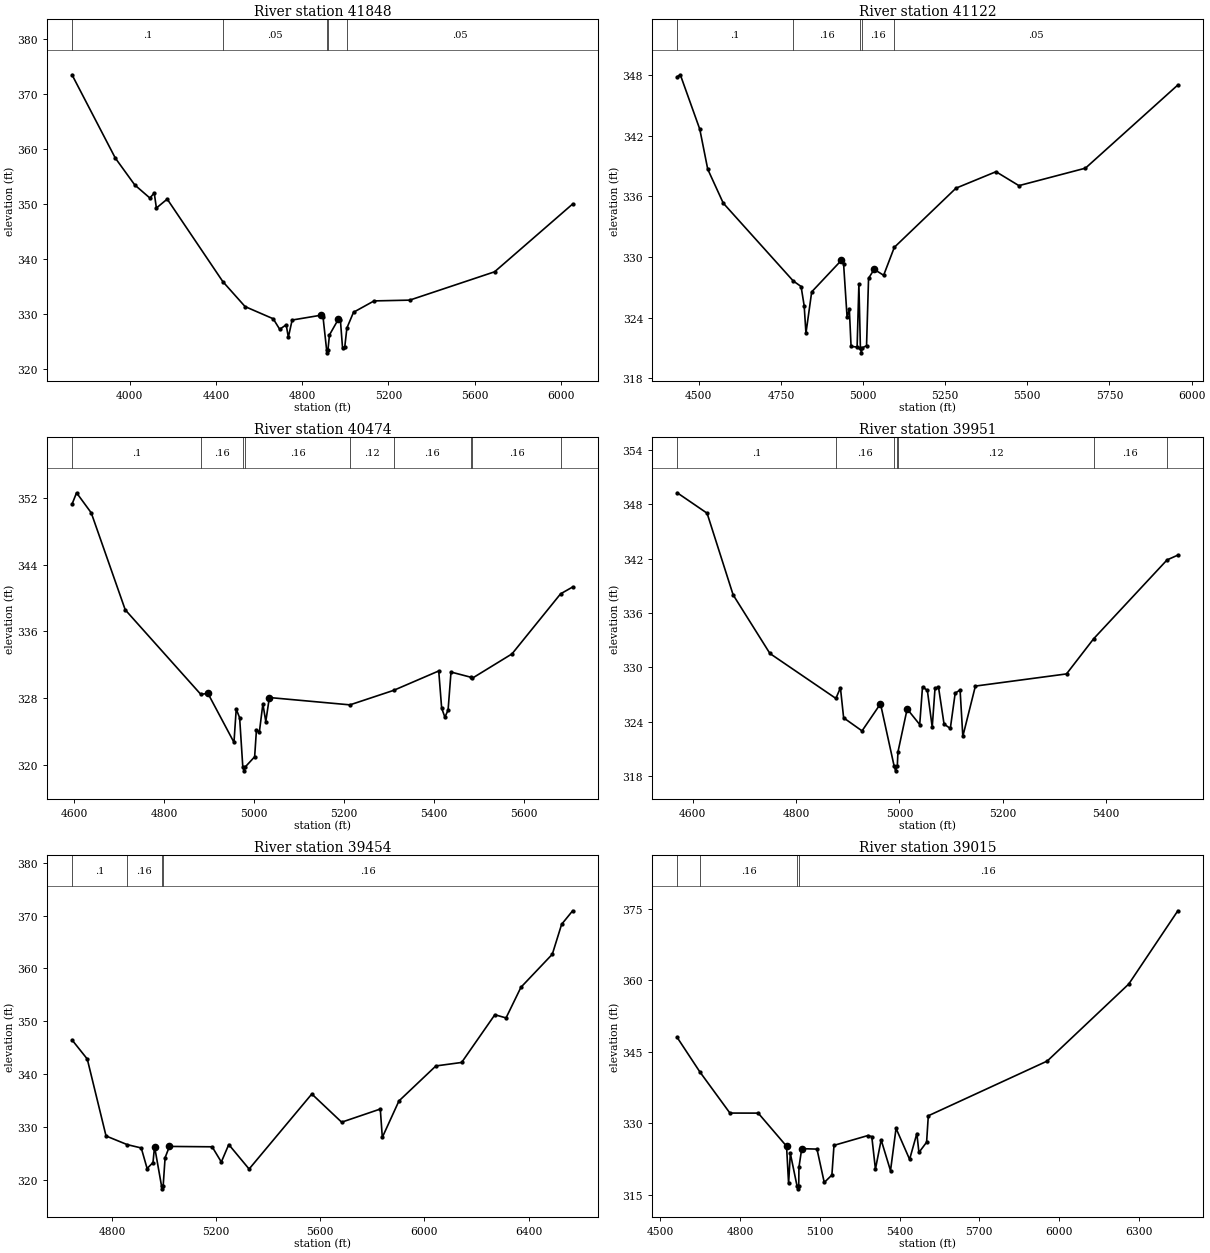
Type RM Length L Ch R = 1 ,41848   ,726,726,726
BEGIN DESCRIPTION:
UNT094 IN BECR 65.0
END DESCRIPTION:
XS GIS Cut Line= 3
      3781299.61     10561510.15      3781399.61     10562710.19
      3781199.61     10563810.16
#Sta/Elev= 30
  3732.3  373.44    3933  358.34  4023.3  353.46  4093.6  351.08  4113.7     352
  4123.7  349.27  4173.9  350.89  4431.9  335.92  4535.1  331.39  4665.6  329.18
  4695.7  327.27  4725.8  328.09  4735.8  325.82  4753.4  328.95  4886.3  329.82
  4896.4  329.59  4913.4   323.5  4916.2     323  4919.4   323.5  4926.5  326.25
  4968.3  329.13  4977.2  328.97  4987.3  323.82  4997.5  324.08  5007.3   327.5
  5038.1  330.36  5133.4  332.42  5298.6  332.56  5692.4   337.7  6054.5     350
#Mann= 5 ,-1 , 0
  3732.3      .1       0  4431.9     .05       0  4913.4     .07       0
  4919.4     .05       0  5007.3     .05       0
Bank Sta=4886.3,4968.3
XS Rating Curve= 0 ,0
Exp/Cntr=0.3,0.1

Type RM Length L Ch R = 1 ,41122   ,648,648,648
BEGIN DESCRIPTION:
UNT094 IN BECR 64.0
END DESCRIPTION:
XS GIS Cut Line= 3
      3780949.59     10562110.14      3781149.61     10562610.19
      3780749.59     10563510.23
#Sta/Elev= 30
  4434.5  347.85    4444  348.04  4503.2  342.65  4527.4  338.69  4574.6  335.33
  4787.6  327.62  4811.5  327.07  4820.9  325.16  4826.3  322.45  4843.8  326.54
    4934  329.66  4940.8  329.33  4951.5  324.02  4958.3  324.83  4963.6  321.14
    4982  321.07  4987.4   327.3    4992     321  4994.7   320.5    4998     321
  5010.7  321.21  5016.8  327.88  5033.9  328.77  5062.7  328.18  5095.2  330.95
  5282.9  336.81  5404.6  338.44  5474.4  337.06  5676.8  338.79    5958  347.03
#Mann= 5 ,-1 , 0
  4434.5      .1       0  4787.6     .16       0    4992     .07       0
    4998     .16       0  5095.2     .05       0
Bank Sta=4934,5033.9
XS Rating Curve= 0 ,0
Exp/Cntr=0.3,0.1

Type RM Length L Ch R = 1 ,40474   ,523,523,523
BEGIN DESCRIPTION:
UNT094 IN BECR 63.0
END DESCRIPTION:
XS GIS Cut Line= 3
      3780749.61     10562110.21      3780799.61     10562510.19
      3780249.62     10562960.18
#Sta/Elev= 30
  4594.7  351.27  4604.8  352.65  4637.5  350.24  4713.1   338.6  4881.2  328.45
    4897  328.57    4955  322.69    4960  326.68  4967.6  325.64  4974.6  319.77
  4977.4  319.27  4980.6  319.77    5001  320.96    5005   324.2  5011.4  323.89
  5019.3   327.3  5025.8  325.19  5033.7  328.07    5213  327.19  5310.1  328.93
  5410.5  331.26    5417   326.8  5424.2  325.71  5431.3  326.56  5437.8  331.13
  5481.7  330.51  5485.5   330.4  5573.5  333.31  5681.6  340.52  5708.4  341.34
#Mann= 9 ,-1 , 0
  4594.7      .1       0  4881.2     .16       0  4974.6     .07       0
  4980.6     .16       0    5213     .12       0  5310.1     .16       0
  5481.7     .12       0  5485.5     .16       0  5681.6     .05       0
Bank Sta=4897,5033.7
XS Rating Curve= 0 ,0
Exp/Cntr=0.3,0.1

Type RM Length L Ch R = 1 ,39951   ,497,497,497
BEGIN DESCRIPTION:
UNT094 IN BECR 62.0
END DESCRIPTION:
XS GIS Cut Line= 3
      3780649.61     10562110.18      3780399.61     10562460.19
      3780199.62     10562960.15
#Sta/Elev= 30
  4570.1  349.25  4627.9     347  4678.3     338  4749.5  331.54  4877.1  326.59
  4885.9  327.76  4892.1  324.45  4927.7  323.01  4963.4     326  4989.9  319.11
  4992.6  318.61  4995.9  319.11  4997.2  320.69    5015  325.43  5039.3  323.71
  5044.7  327.87  5054.1  327.47  5063.5  323.42  5068.9   327.7  5075.6  327.85
  5086.4  323.76  5098.5  323.28  5107.9  327.16  5117.4  327.53  5122.7  322.41
    5147  327.95  5323.3  329.29  5375.9  333.17  5517.8  341.85  5538.7  342.38
#Mann= 7 ,-1 , 0
  4570.1      .1       0  4877.1     .16       0  4989.9     .07       0
  4995.9     .16       0  4997.2     .12       0  5375.9     .16       0
  5517.8     .05       0
Bank Sta=4963.4,5015
XS Rating Curve= 0 ,0
Exp/Cntr=0.3,0.1

Type RM Length L Ch R = 1 ,39454   ,439,439,439
BEGIN DESCRIPTION:
UNT094 IN BECR 61.0
END DESCRIPTION:
XS GIS Cut Line= 3
      3780299.61     10561960.19      3780099.61     10562260.19
      3778899.61     10563260.19
#Sta/Elev= 30
  4646.7  346.45  4705.3  342.83  4777.4  328.26  4858.8  326.62  4912.6  325.99
  4935.1   322.1  4957.7  323.23  4963.7  326.26  4990.7  318.75  4993.5  318.25
  4996.7  318.75  5004.2  324.15  5020.9  326.28  5184.9  326.21  5220.1  323.33
  5248.7  326.64  5326.8     322  5567.6  336.21  5682.2  330.87  5830.6  333.36
  5838.4     328  5902.2  334.89  6044.1  341.52    6143  342.18  6270.6  351.22
  6313.5  350.61  6370.8  356.42  6491.2  362.67    6527  368.34  6569.3   370.9
#Mann= 4 ,-1 , 0
  4646.7      .1       0  4858.8     .16       0  4990.7     .07       0
  4996.7     .16       0
Bank Sta=4963.7,5020.9
XS Rating Curve= 0 ,0
Exp/Cntr=0.3,0.1

Type RM Length L Ch R = 1 ,39015   ,529,529,529
BEGIN DESCRIPTION:
UNT094 IN BECR 60.0
END DESCRIPTION:
XS GIS Cut Line= 3
      3780049.64     10561760.15      3779749.61     10562110.19
       3778849.6     10563210.19
#Sta/Elev= 30
  4564.1     348  4649.2  340.79  4762.3  332.15  4868.7  332.14  4975.2   325.2
  4982.9  317.38  4989.5  323.68    5015  316.76  5017.7  316.26    5021  316.76
  5021.8  320.78  5032.3  324.69  5089.7  324.59    5117  317.59  5145.7  319.16
  5153.6  325.38  5281.4  327.44  5295.7   327.2  5309.4  320.39  5330.9  326.52
  5366.1  320.06  5386.9  328.95  5437.9  322.44  5465.1  327.86    5473  323.89
  5501.8  326.04  5508.2  331.58  5955.4  343.06  6261.9  359.21  6446.4  374.57
#Mann= 4 ,-1 , 0
  4564.1      .1       0  4649.2     .16       0    5015     .07       0
    5021     .16       0
Bank Sta=4975.2,5032.3
XS Rating Curve= 0 ,0
Exp/Cntr=0.3,0.1

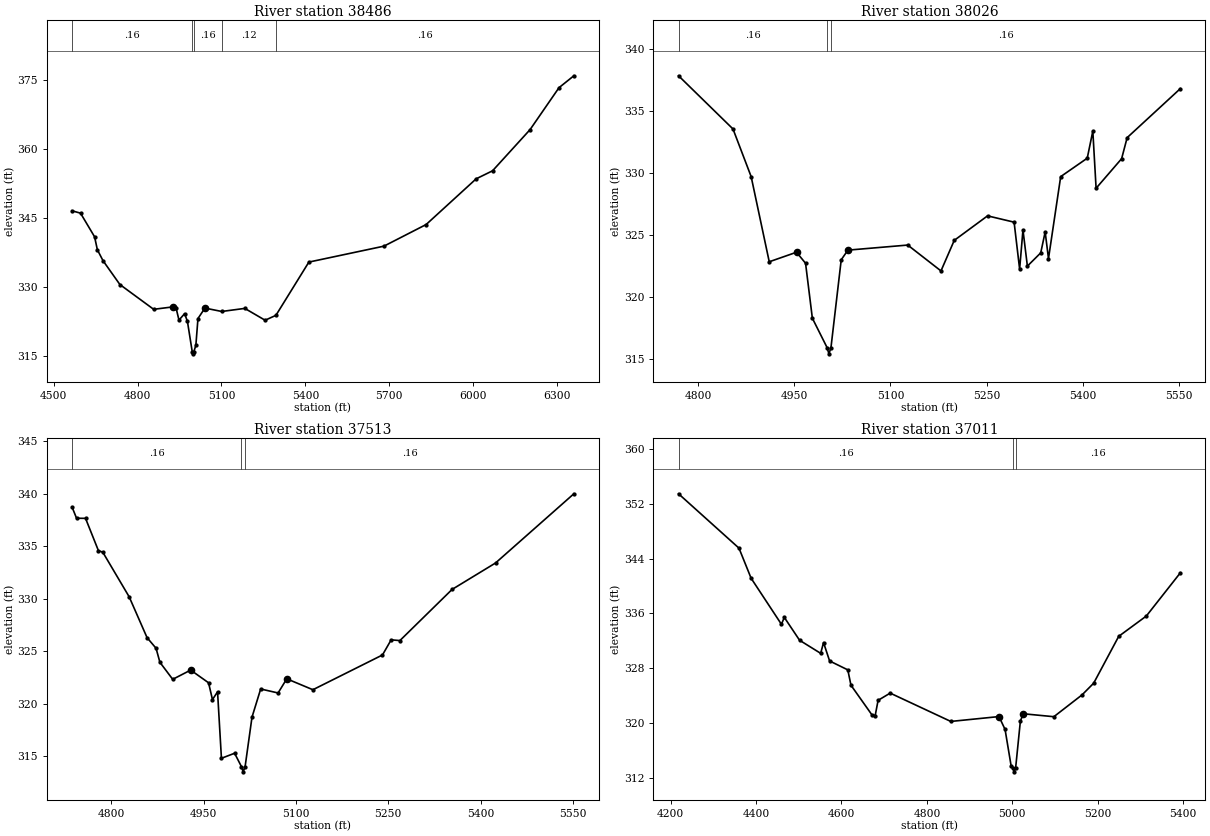
Type RM Length L Ch R = 1 ,38486   ,460,460,460
BEGIN DESCRIPTION:
UNT094 IN BECR 59.0
END DESCRIPTION:
XS GIS Cut Line= 3
      3779399.61     10561510.22      3779349.61     10561960.19
       3778749.6      10563160.2
#Sta/Elev= 30
  4565.9  346.54  4596.1  346.03  4646.4  340.88  4656.4  338.05  4676.5  335.68
  4736.9  330.48  4857.7  325.08  4928.1  325.62  4938.1  325.29  4948.2  322.73
  4968.3  324.13  4978.4  322.46  4995.5  315.88  4998.3  315.38  5001.5  315.88
  5008.6  317.23  5016.1  323.07    5041  325.35    5101  324.61  5183.6  325.28
  5256.2   322.7  5294.9  323.77  5412.7  335.37  5681.1  338.84    5832  343.55
  6010.9  353.51  6069.6  355.26  6203.8  364.24  6307.2  373.37  6360.3  375.96
#Mann= 5 ,-1 , 0
  4565.9     .16       0  4995.5     .07       0  5001.5     .16       0
    5101     .12       0  5294.9     .16       0
Bank Sta=4928.1,5041
XS Rating Curve= 0 ,0
Exp/Cntr=0.3,0.1

Type RM Length L Ch R = 1 ,38026   ,513,513,513
BEGIN DESCRIPTION:
UNT094 IN BECR 58.0
END DESCRIPTION:
XS GIS Cut Line= 3
      3779199.63     10561560.17      3779049.61     10561710.19
      3778899.62     10562260.15
#Sta/Elev= 30
  4769.7  337.86  4854.6  333.56  4882.9  329.71  4911.1  322.83  4953.6   323.6
  4967.7  322.71  4978.3  318.27  5001.3  315.89  5004.1  315.39  5007.3  315.89
  5023.3  322.99  5033.7  323.77    5127  324.18  5178.8  322.09  5199.5  324.56
  5251.4  326.54  5292.8  326.03  5301.4  322.24  5306.6   325.4  5313.5  322.48
  5334.3  323.55  5341.2  325.24  5346.4  323.09  5365.4  329.71  5406.8   331.2
  5415.5  333.39  5420.6  328.77  5460.4  331.16    5469  332.86  5551.9  336.82
#Mann= 3 ,-1 , 0
  4769.7     .16       0  5001.3     .07       0  5007.3     .16       0
Bank Sta=4953.6,5033.7
XS Rating Curve= 0 ,0
Exp/Cntr=0.3,0.1

Type RM Length L Ch R = 1 ,37513   ,502,502,502
BEGIN DESCRIPTION:
UNT094 IN BECR 57.0
END DESCRIPTION:
XS GIS Cut Line= 3
      3778899.64     10561360.16      3778699.61     10561510.19
      3778299.63     10561910.17
#Sta/Elev= 30
    4736  338.71  4743.3  337.65  4757.9  337.64  4778.8  334.57    4786  334.41
  4828.8  330.17  4857.9  326.28  4872.5  325.27  4878.8  323.93  4899.6  322.31
  4928.8  323.19  4957.9  321.98  4964.2  320.38  4972.5  321.12  4978.8  314.79
  5000.2  315.27  5011.3     314  5014.1   313.5  5017.3     314  5028.5  318.71
  5042.6  321.39  5070.9  321.01    5085  322.36  5127.5  321.32  5240.6  324.63
  5254.7  326.07  5268.9     326  5353.7  330.87  5424.4  333.39  5551.7  339.98
#Mann= 3 ,-1 , 0
    4736     .16       0  5011.3     .07       0  5017.3     .16       0
Bank Sta=4928.8,5085
XS Rating Curve= 0 ,0
Exp/Cntr=0.3,0.1

Type RM Length L Ch R = 1 ,37011   ,430,430,430
BEGIN DESCRIPTION:
UNT094 IN BECR 56.0
END DESCRIPTION:
XS GIS Cut Line= 3
       3778849.6     10560710.19      3778299.61     10561310.19
       3777999.6     10561510.19
#Sta/Elev= 30
  4218.7  353.45  4360.2  345.52  4388.6  341.13  4459.5  334.42  4466.3  335.42
    4502  332.09  4551.4  330.18  4558.1  331.75  4572.3  329.07  4614.9  327.77
  4622.3  325.53  4671.6  321.19    4679  321.11  4685.8  323.33  4714.1  324.38
    4856  320.25  4968.8  320.96    4983  319.08  4997.2  313.76  5001.6   313.4
  5004.3   312.9  5007.6   313.4  5018.8  320.29  5025.5  321.37  5097.2  320.94
  5163.3  324.13  5190.4  325.83    5249  332.66  5313.6  335.62  5393.2  341.92
#Mann= 3 ,-1 , 0
  4218.7     .16       0  5001.6     .07       0  5007.6     .16       0
Bank Sta=4968.8,5025.5
XS Rating Curve= 0 ,0
Exp/Cntr=0.3,0.1