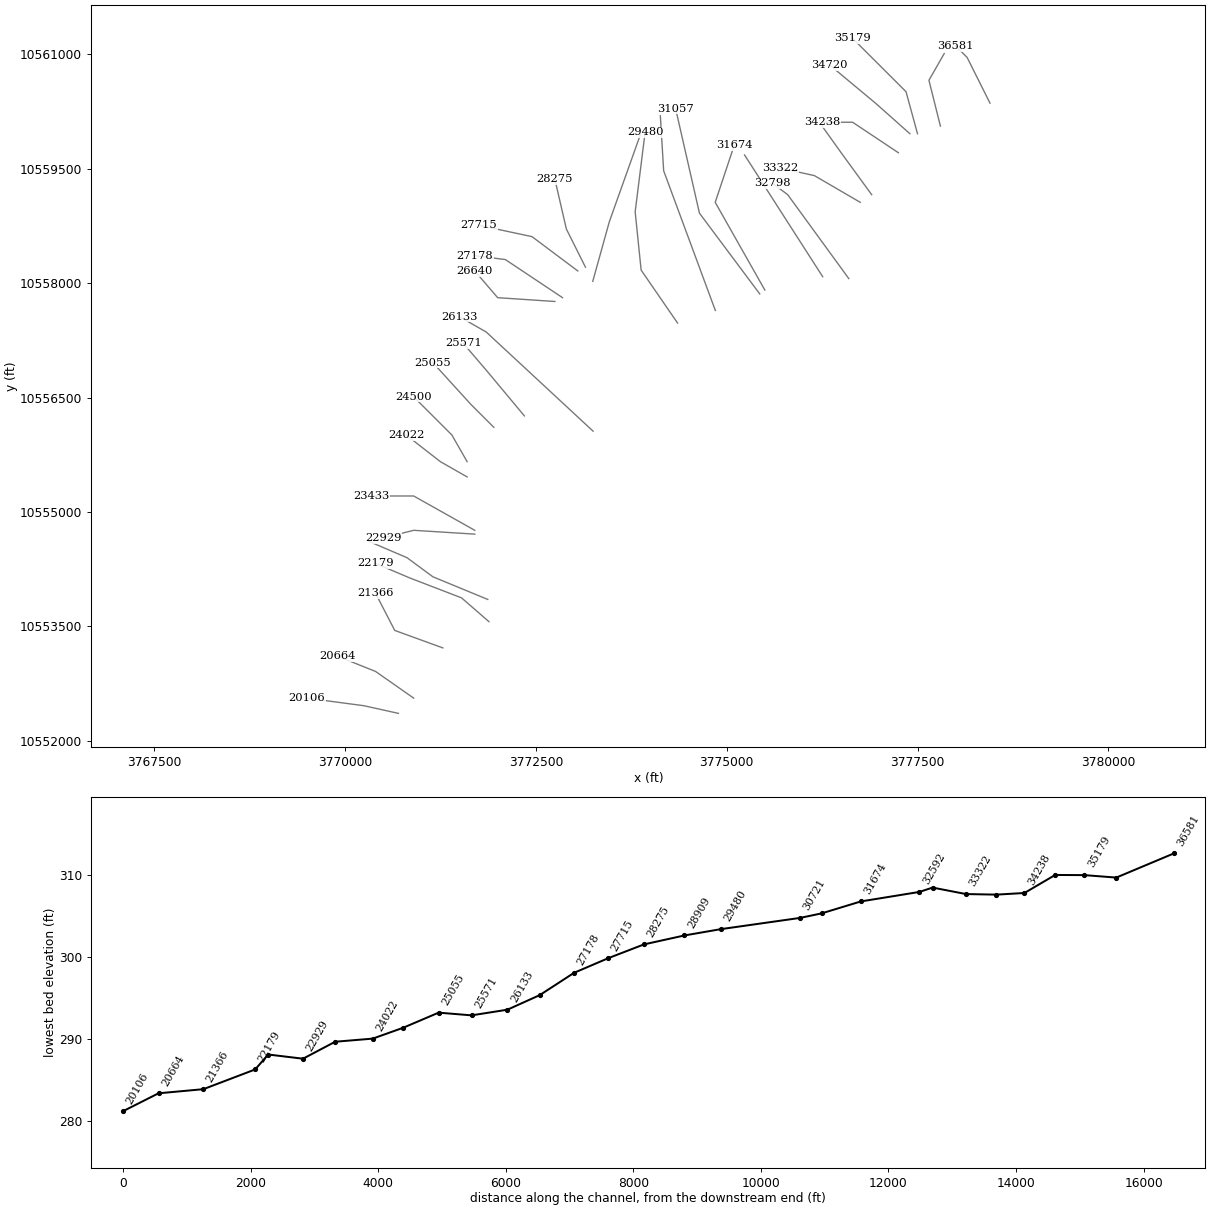
HEC-RAS study UNT094 IN BECR.prj: UNT094 IN BECR Base Level Engineering

--- UNT094 IN BECR.g01 (geometry) --- (continued)

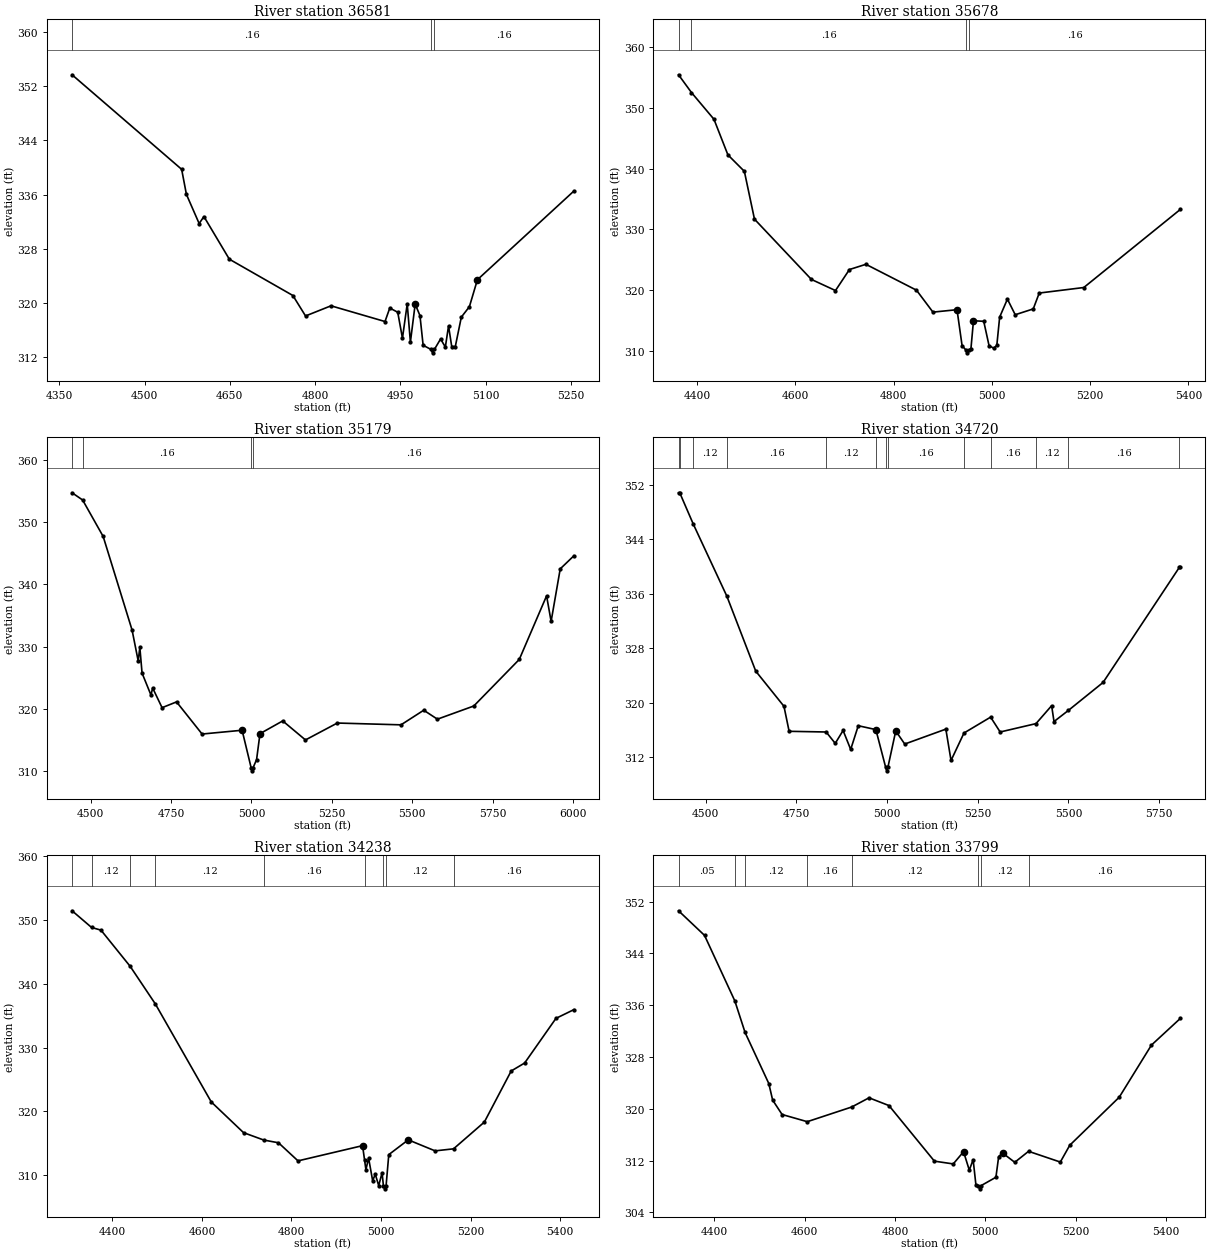
Type RM Length L Ch R = 1 ,36581   ,903,903,903
BEGIN DESCRIPTION:
UNT094 IN BECR 55.0
END DESCRIPTION:
XS GIS Cut Line= 3
      3778449.59     10560360.22      3778149.61     10560960.19
      3777999.62     10561110.18
#Sta/Elev= 30
  4372.4  353.68  4565.2  339.73  4573.6  336.03    4596  331.73  4604.4  332.76
  4649.1  326.47  4760.9  321.11  4783.2  318.09    4828  319.59    4923  317.27
  4931.4  319.26  4945.4  318.64  4953.7  314.81  4962.1  319.87  4967.7  314.24
  4976.1  319.84  4984.5  318.15  4990.1  313.77  5003.9  313.15  5006.6  312.65
  5009.9  313.15  5020.8   314.7  5029.2   313.5  5034.8  316.62  5040.4  313.58
  5046.7  313.58  5057.3  317.92  5071.5  319.46  5085.6  323.44  5255.3  336.52
#Mann= 3 ,-1 , 0
  4372.4     .16       0  5003.9     .07       0  5009.9     .16       0
Bank Sta=4976.1,5085.6
XS Rating Curve= 0 ,0
Exp/Cntr=0.3,0.1

Type RM Length L Ch R = 1 ,35678   ,499,499,499
BEGIN DESCRIPTION:
UNT094 IN BECR 54.0
END DESCRIPTION:
XS GIS Cut Line= 3
       3777799.6     10560060.22      3777649.61     10560660.19
      3777849.59     10561010.15
#Sta/Elev= 30
    4362  355.46  4388.3  352.54  4434.1  348.14  4462.5  342.28    4496  339.57
  4516.6   331.7  4632.5  321.78  4681.5  319.95  4709.9  323.41  4743.4  324.27
  4846.4  320.01  4879.9   316.4  4928.9   316.8  4939.2   310.9  4946.5   310.2
  4949.3   309.7  4952.5   310.2  4957.2  310.34  4962.4  314.98  4983.3  314.89
  4994.1  310.89  5003.5  310.47  5009.9  310.91  5015.7  315.58  5031.5  318.54
  5047.4  315.97  5084.1  316.93  5096.3  319.54    5187  320.45  5383.5   333.3
#Mann= 4 ,-1 , 0
    4362     .05       0  4388.3     .16       0  4946.5     .07       0
  4952.5     .16       0
Bank Sta=4928.9,4962.4
XS Rating Curve= 0 ,0
Exp/Cntr=0.3,0.1

Type RM Length L Ch R = 1 ,35179   ,459,459,459
BEGIN DESCRIPTION:
UNT094 IN BECR 53.0
END DESCRIPTION:
XS GIS Cut Line= 3
       3777499.6     10559960.21      3777349.61     10560510.19
      3776649.62     10561210.18
#Sta/Elev= 30
  4442.4  354.73  4475.2  353.57  4539.1   347.7    4629  332.64    4648  327.68
  4653.1  329.86    4660  325.72  4687.7  322.19  4692.9  323.33  4722.2  320.16
  4767.2  321.09  4846.6  315.92    4971  316.53  4999.1   310.5  5001.9     310
  5005.1   310.5    5016   311.8  5026.6  315.98  5097.3  318.03    5168  314.97
    5267  317.69    5465   317.4  5535.7  319.75  5578.2  318.31  5691.3  320.43
  5832.7  327.92  5917.6  338.15  5931.7  334.04    5960  342.49  6002.4  344.59
#Mann= 4 ,-1 , 0
  4442.4     .05       0  4475.2     .16       0  4999.1     .07       0
  5005.1     .16       0
Bank Sta=4971,5026.6
XS Rating Curve= 0 ,0
Exp/Cntr=0.3,0.1

Type RM Length L Ch R = 1 ,34720   ,482,482,482
BEGIN DESCRIPTION:
UNT094 IN BECR 52.0
END DESCRIPTION:
XS GIS Cut Line= 3
      3777399.58     10559960.21      3776949.61     10560360.19
      3776349.58     10560860.21
#Sta/Elev= 30
  4425.4  350.82  4428.7  350.82    4466  346.23  4558.4  335.67  4638.2  324.65
    4716  319.49  4730.2  315.82  4832.3  315.72  4857.3  314.05    4879  315.94
  4899.9  313.16  4920.8  316.64  4969.3  316.07  4996.4  310.52  4999.2  310.02
  5002.4  310.52  5024.1  315.87  5048.9  313.95  5162.2  316.14  5176.5  311.54
  5212.2  315.57  5285.6   317.9  5311.9  315.72  5410.7  316.95  5453.8  319.58
  5460.3  317.25  5499.8  318.88  5595.6  322.99  5806.1   339.9  5808.5   339.9
#Mann= 13 ,-1 , 0
  4425.4     .05       0  4428.7     .16       0    4466     .12       0
  4558.4     .16       0  4832.3     .12       0  4969.3     .16       0
  4996.4     .07       0  5002.4     .16       0  5212.2     .12       0
  5285.6     .16       0  5410.7     .12       0  5499.8     .16       0
  5806.1     .05       0
Bank Sta=4969.3,5024.1
XS Rating Curve= 0 ,0
Exp/Cntr=0.3,0.1

Type RM Length L Ch R = 1 ,34238   ,439,439,439
BEGIN DESCRIPTION:
UNT094 IN BECR 51.0
END DESCRIPTION:
XS GIS Cut Line= 3
      3777249.61     10559710.19      3776649.61     10560110.19
      3776249.62     10560110.19
#Sta/Elev= 30
  4309.8  351.47  4353.4  348.85  4374.4  348.43  4439.8  342.73  4495.8  336.85
  4620.8  321.46  4692.9  316.64  4738.1  315.48    4771  315.05  4814.6  312.21
  4958.8   314.6  4963.2  312.39  4966.3  310.83  4972.3  312.65  4981.3  309.12
  4987.3  310.09  4994.9  308.33  5002.4  310.34  5005.4  308.32  5008.1  307.82
  5011.4  308.32  5017.4  313.19  5060.9  315.51  5120.9  313.78  5162.1   314.1
  5230.9   318.3  5290.9  326.32  5320.9  327.57  5390.9  334.58  5430.9  335.95
#Mann= 9 ,-1 , 0
  4309.8     .16       0  4353.4     .12       0  4439.8     .16       0
  4495.8     .12       0  4738.1     .16       0  4963.2     .12       0
  5005.4     .07       0  5011.4     .12       0  5162.1     .16       0
Bank Sta=4958.8,5060.9
XS Rating Curve= 0 ,0
Exp/Cntr=0.3,0.1

Type RM Length L Ch R = 1 ,33799   ,477,477,477
BEGIN DESCRIPTION:
UNT094 IN BECR 50.0
END DESCRIPTION:
XS GIS Cut Line= 3
      3776899.59     10559160.21      3776499.61     10559710.19
      3776249.59     10560060.22
#Sta/Elev= 30
  4321.2   350.6  4378.7   346.8  4445.8  336.66  4468.4  331.79  4520.9   323.9
  4529.4  321.34  4550.3  319.11    4606     318  4704.4  320.27  4742.7  321.69
  4786.8  320.49  4887.3   311.9    4929  311.47  4951.8  313.36  4964.5  310.51
    4973  312.13  4979.2   308.2  4984.7  308.12  4987.5  307.62  4990.7  308.12
  5023.4  309.41  5029.5  312.61  5038.1  313.16  5065.1  311.72  5095.6  313.42
  5165.9  311.76  5186.8  314.36  5296.2  321.78  5367.5  329.84  5431.4  333.96
#Mann= 8 ,-1 , 0
  4321.2     .05       0  4445.8     .16       0  4468.4     .12       0
    4606     .16       0  4704.4     .12       0  4984.7     .07       0
  4990.7     .12       0  5095.6     .16       0
Bank Sta=4951.8,5038.1
XS Rating Curve= 0 ,0
Exp/Cntr=0.3,0.1

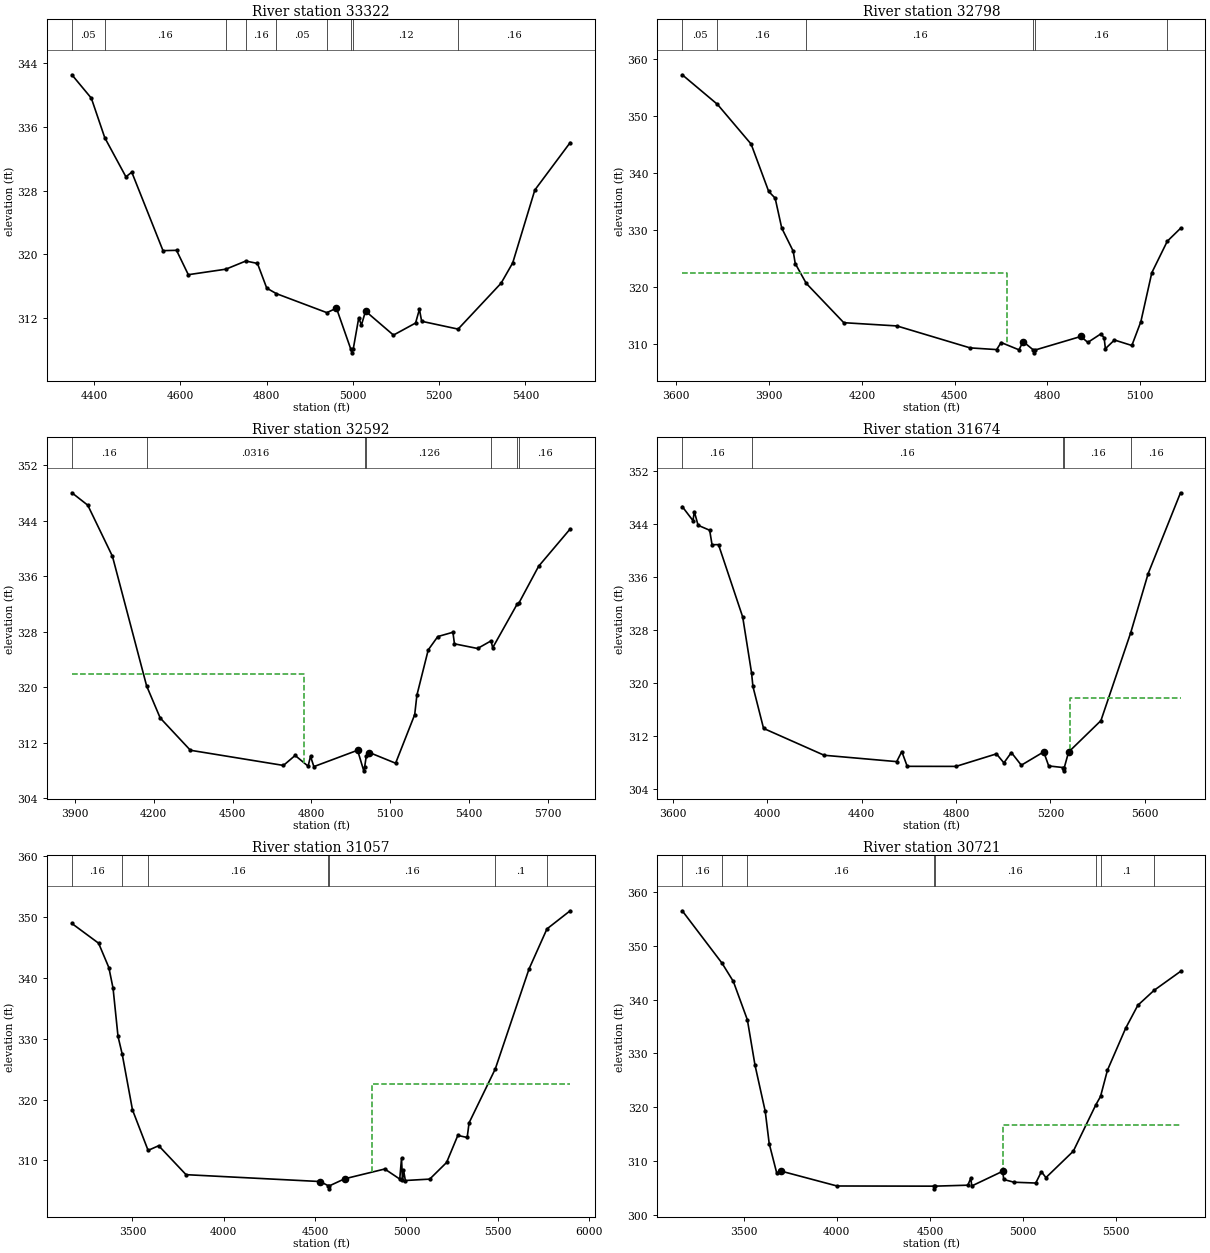
Type RM Length L Ch R = 1 ,33322   ,524,524,524
BEGIN DESCRIPTION:
UNT094 IN BECR 49.0
END DESCRIPTION:
XS GIS Cut Line= 3
      3776749.62     10559060.18      3776149.61     10559410.19
      3775699.62     10559510.19
#Sta/Elev= 30
  4348.2  342.49  4393.3  339.56  4424.4  334.62  4473.5  329.72  4487.1   330.3
  4559.5  320.48  4590.9  320.52  4618.2  317.47  4705.3  318.16  4751.5  319.18
  4778.6  318.88  4800.1  315.79  4822.4   315.1  4939.5  312.72  4961.8  313.28
  4994.8  308.19  4997.5  307.69  5000.8  308.19  5013.5  312.07  5019.7  311.16
  5029.2  312.91    5094  309.91  5145.3  311.42  5154.2  313.14  5159.4  311.64
  5243.9  310.66  5343.7  316.41  5370.6  318.95  5421.9  328.07  5503.8     334
#Mann= 9 ,-1 , 0
  4348.2     .05       0  4424.4     .16       0  4705.3     .05       0
  4751.5     .16       0  4822.4     .05       0  4939.5     .12       0
  4994.8     .07       0  5000.8     .12       0  5243.9     .16       0
Bank Sta=4961.8,5029.2
XS Rating Curve= 0 ,0
Exp/Cntr=0.3,0.1

Type RM Length L Ch R = 1 ,32798   ,206,206,206
BEGIN DESCRIPTION:
UNT094 IN BECR 48.0
END DESCRIPTION:
XS GIS Cut Line= 3
      3776599.61     10558060.19      3775799.61     10559160.19
      3775599.64     10559310.16
#Sta/Elev= 30
  3619.7  357.26  3733.5  352.07  3842.3   345.1  3899.1  336.79  3919.9  335.62
  3941.2  330.37  3978.3  326.31  3984.8  324.15  4020.4  320.67  4141.7  313.77
  4313.3   313.2  4549.8  309.35  4635.6  309.05  4650.2  310.29  4707.8  309.01
  4721.3  310.46  4754.3  308.98    4757  308.48  4760.3  308.98  4907.6  311.35
  4930.4  310.31  4972.5  311.81    4983  311.12  4987.1  309.21  5016.3  310.73
  5072.6  309.77  5101.7  313.95  5137.1  322.54  5187.1  328.06  5229.8  330.32
#Mann= 6 ,-1 , 0
  3619.7     .05       0  3733.5     .16       0  4020.4     .16       0
  4754.3     .07       0  4760.3     .16       0  5187.1     .16       0
#XS Ineff= 2 , 0
         4667.73  322.53
Permanent Ineff=
       F       F
Bank Sta=4721.3,4907.6
XS Rating Curve= 0 ,0
Exp/Cntr=0.3,0.1

Type RM Length L Ch R = 1 ,32592   ,918,918,918
BEGIN DESCRIPTION:
UNT094 IN BECR 47.0
END DESCRIPTION:
XS GIS Cut Line= 2
      3776257.64     10558084.96      3775233.96     10559681.21
#Sta/Elev= 30
  3888.7  348.06  3949.1  346.27    4043   338.9  4173.1   320.2  4224.7  315.58
  4339.6  310.92  4693.8  308.73  4738.4  310.17  4787.7  308.62  4796.9  310.05
  4809.6  308.56    4976  310.92  4999.5  307.95  5002.7  308.45    5009  310.05
  5020.9  310.59  5120.7  309.05  5193.4  316.06  5201.7  318.86  5244.9   325.4
  5281.3  327.32  5338.8  327.94  5344.7  326.27  5432.6   325.6  5484.1   326.7
  5490.1   325.7    5583  331.98  5589.9  332.15    5665  337.46    5785  342.84
#Mann= 7 ,-1 , 0
  3888.7     .16       0  4173.1   .0316       0  5002.7     .05       0
    5009    .126       0  5484.1     .16       0    5583      .1       0
  5589.9     .16       0
#XS Ineff= 2 , 0
         4772.73   321.9
Permanent Ineff=
       F       F
Bank Sta=4976,5020.9
XS Rating Curve= 0 ,0
Exp/Cntr=0.3,0.1

Type RM Length L Ch R = 1 ,31674   ,617,617,617
BEGIN DESCRIPTION:
UNT094 IN BECR 46.0
END DESCRIPTION:
XS GIS Cut Line= 3
       3775499.6     10557910.21      3774849.61     10559060.19
       3775099.6     10559810.16
#Sta/Elev= 30
  3639.5  346.64    3685  344.52  3690.7  345.88  3706.6  343.82  3755.7  343.07
  3765.8  340.89  3793.2   340.9  3895.7  329.99  3933.3  321.55    3939  319.52
  3984.1  313.19  4240.8  309.14  4548.3  308.18  4569.9   309.7  4592.9  307.47
  4799.6  307.46    4971  309.35  5002.6  307.99  5034.2  309.55  5076.4  307.64
  5171.3  309.65  5192.4  307.53  5252.6  307.29  5255.4  306.79  5258.6  307.29
  5276.7  309.62  5413.7  314.36  5540.2  327.64    5614  336.54    5751  348.72
#Mann= 5 ,-1 , 0
  3639.5     .16       0  3933.3     .16       0  5252.6     .07       0
  5258.6     .16       0  5540.2     .16       0
#XS Ineff= 2 , 0
                         5284.09          317.71
Permanent Ineff=
       F       F
Bank Sta=5171.3,5276.7
XS Rating Curve= 0 ,0
Exp/Cntr=0.3,0.1

Type RM Length L Ch R = 1 ,31057   ,336,336,336
BEGIN DESCRIPTION:
UNT094 IN BECR 45.0
END DESCRIPTION:
XS GIS Cut Line= 3
      3775432.96     10557859.31      3774643.04     10558918.32
      3774330.55      10560289.8
#Sta/Elev= 30
  3168.6  348.95  3314.8  345.71    3371   341.7    3394   338.3  3421.1  330.39
    3444  327.48  3500.3  318.31  3585.8  311.65  3643.8  312.42  3793.5  307.66
  4527.6  306.53  4572.8  305.83  4575.5  305.33  4578.8  305.83  4661.8  306.98
  4881.4  308.59  4963.5  306.94  4973.2  310.34  4978.4  306.85    4984  308.46
  4994.2   306.7  5127.6  306.93  5219.9  309.66  5281.4  314.11  5332.7  313.77
    5343  316.18  5486.5  325.04  5671.2  341.47  5769.4  348.06  5896.4  351.04
#Mann= 7 ,-1 , 0
  3168.6     .16       0    3444     .07       0  3585.8     .16       0
  4572.8    .035       0  4578.8     .16       0  5486.5      .1       0
  5769.4     .05       0
#XS Ineff= 2 , 0
                         4811.93           322.6
Permanent Ineff=
       F       F
Bank Sta=4527.6,4661.8
XS Rating Curve= 0 ,0
Exp/Cntr=0.3,0.1

Type RM Length L Ch R = 1 ,30721   ,1241,1241,1241
BEGIN DESCRIPTION:
UNT094 IN BECR 44.0
END DESCRIPTION:
XS GIS Cut Line= 3
      3774851.36     10557642.32      3774174.29     10559473.88
      3774130.89     10560194.37
#Sta/Elev= 30
  3170.7  356.56  3384.5  346.79    3445   343.4  3520.3  336.25  3561.3   327.8
  3616.2  319.21  3637.5   313.2  3677.7  307.74  3701.5  308.08  4001.5  305.31
  4519.4  305.28  4522.2  304.78  4525.4  305.28  4703.7  305.46  4719.2  306.75
    4725  305.32    4891  308.06  4896.3  306.52  4951.8  306.01  5068.1  305.86
  5098.6  307.97  5122.9  306.87    5270   311.8  5390.2  320.39  5415.9  321.98
    5453  326.87  5550.5  334.67  5616.3  338.97  5703.2  341.74  5845.2  345.27
#Mann= 8 ,-1 , 0
  3170.7     .16       0  3384.5     .12       0  3520.3     .16       0
  4519.4    .033       0  4525.4     .16       0  5390.2     .16       0
  5415.9      .1       0  5703.2     .16       0
#XS Ineff= 2 , 0
                         4892.05           316.6
Permanent Ineff=
       F       F
Bank Sta=3701.5,4891
XS Rating Curve= 0 ,0
Exp/Cntr=0.3,0.1

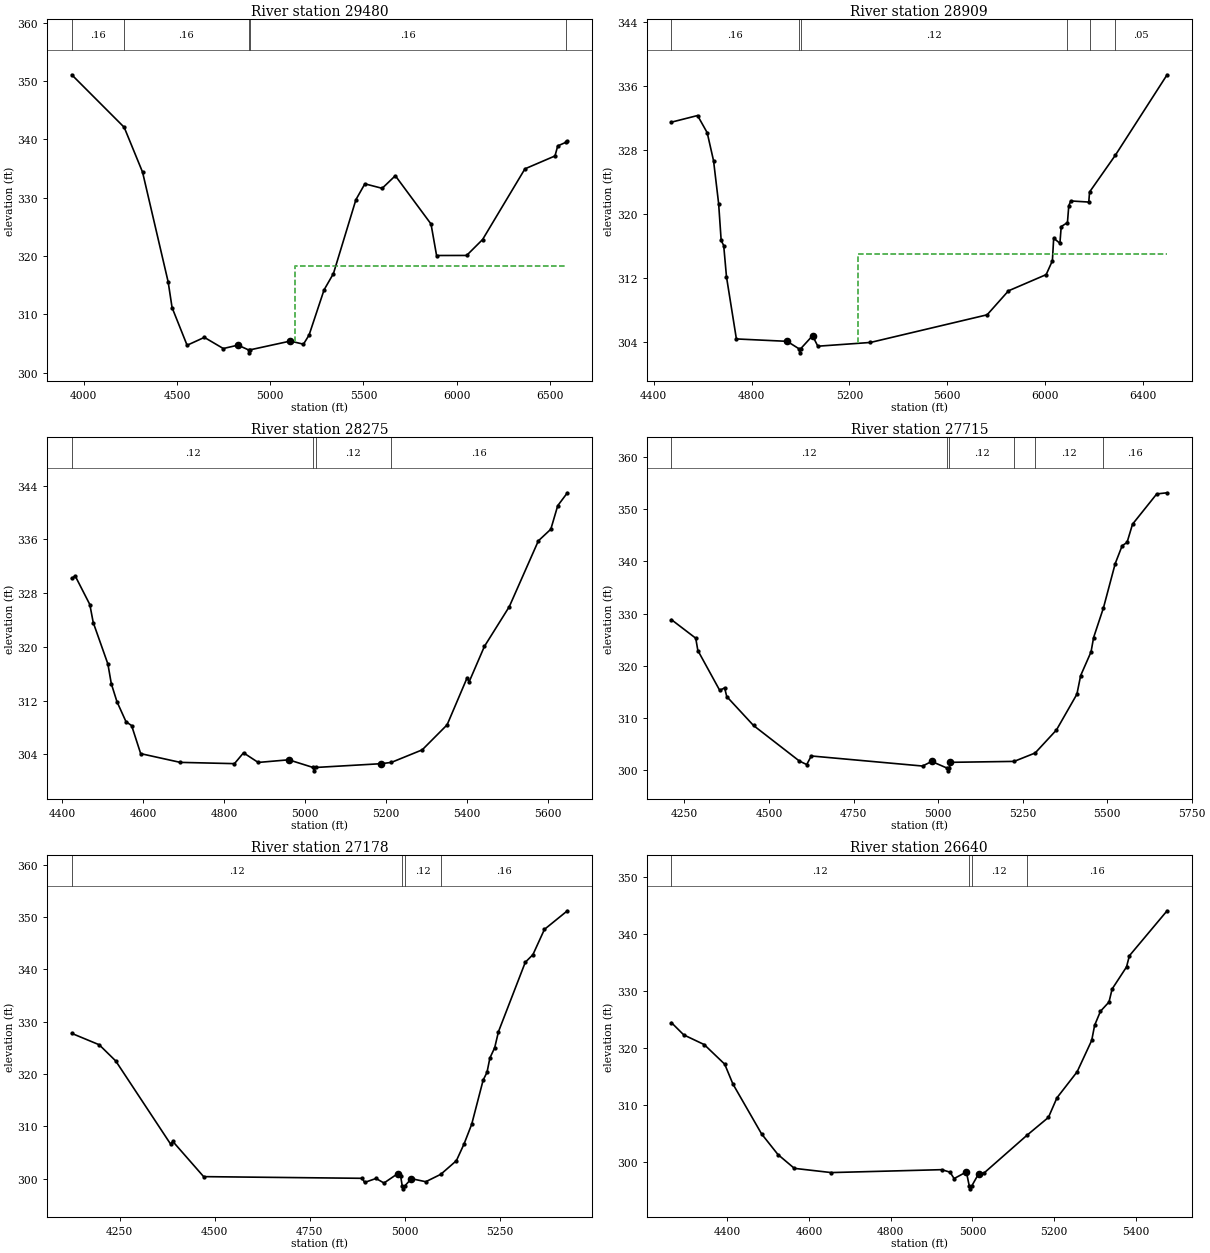
Type RM Length L Ch R = 1 ,29480   ,571,571,571
BEGIN DESCRIPTION:
UNT094 IN BECR 43.0
END DESCRIPTION:
XS GIS Cut Line= 4
      3774356.59     10557477.34      3773879.15     10558171.79
      3773801.03     10558935.68       3773931.1     10559976.27
#Sta/Elev= 30
  3935.2  351.09  4216.4  342.09  4315.1  334.39  4452.5  315.56  4473.5  311.16
    4554  304.71  4646.7  306.06  4748.2  304.15  4827.1  304.73  4883.9  303.91
  4886.7  303.41  4889.9  303.91  5108.1  305.43  5178.4  304.89  5208.6  306.47
    5289  314.21  5339.3  317.01  5459.9  329.68  5507.9  332.39  5600.7  331.62
  5671.3  333.78  5862.8   325.5  5892.6   320.1  6053.8  320.11  6139.5  322.84
  6366.7  334.96  6527.9  337.17  6542.6  338.89  6588.4  339.54  6594.5  339.68
#Mann= 5 ,-1 , 0
  3935.2     .16       0  4216.4     .16       0  4883.9     .07       0
  4889.9     .16       0  6588.4     .05       0
#XS Ineff= 2 , 0
                         5134.66          318.32
Permanent Ineff=
       F       F
Bank Sta=4827.1,5108.1
XS Rating Curve= 0 ,0
Exp/Cntr=0.3,0.1

Type RM Length L Ch R = 1 ,28909   ,634,634,634
BEGIN DESCRIPTION:
UNT094 IN BECR 42.0
END DESCRIPTION:
XS GIS Cut Line= 3
      3773245.48     10558024.26      3773462.48     10558805.48
      3773870.47     10559951.32
#Sta/Elev= 30
  4472.2  331.51    4579  332.34  4618.4  330.19  4644.4  326.68  4665.2  321.31
  4675.5  316.71  4685.9  316.07  4697.3  312.15  4737.8  304.38  4945.4  304.08
  4994.3  303.14    4997  302.64  5000.3  303.14  5049.2  304.78  5070.9  303.47
  5286.2  303.94  5763.3   307.4  5850.5   310.4  6004.7  312.43  6030.2  314.16
  6035.5  316.99    6061  316.35  6066.3  318.44  6091.8  318.94  6097.2  321.04
  6105.3  321.65    6179  321.51  6182.3  322.77  6287.9  327.38  6499.3  337.44
#Mann= 6 ,-1 , 0
  4472.2     .16       0  4994.3     .07       0  5000.3     .12       0
  6091.8     .16       0  6182.3      .1       0  6287.9     .05       0
#XS Ineff= 2 , 0
                          5235.8          314.97
Permanent Ineff=
       F       F
Bank Sta=4945.4,5049.2
XS Rating Curve= 0 ,0
Exp/Cntr=0.3,0.1

Type RM Length L Ch R = 1 ,28275   ,560,560,560
BEGIN DESCRIPTION:
UNT094 IN BECR 41.0
END DESCRIPTION:
XS GIS Cut Line= 3
      3773149.61     10558210.18      3772899.61     10558710.19
      3772749.61     10559360.18
#Sta/Elev= 30
  4423.1  330.18  4431.5  330.56  4467.8  326.29  4476.2  323.62  4512.5  317.44
  4520.9  314.52  4534.9  311.84  4557.3  308.86  4571.2  308.28  4593.6  304.11
  4691.4  302.81  4825.6  302.62    4848  304.23  4884.3   302.8  4959.8  303.19
  5020.2  302.05  5022.9  301.55  5026.2  302.05  5187.4  302.61  5213.5   302.8
    5290  304.67  5351.6  308.39  5401.2   315.4  5406.3  314.82  5443.9  320.06
  5505.5  325.98  5577.4  335.77  5608.2   337.5  5625.3     341  5649.2  342.92
#Mann= 4 ,-1 , 0
  4423.1     .12       0  5020.2     .07       0  5026.2     .12       0
  5213.5     .16       0
Bank Sta=4959.8,5187.4
XS Rating Curve= 0 ,0
Exp/Cntr=0.3,0.1

Type RM Length L Ch R = 1 ,27715   ,537,537,537
BEGIN DESCRIPTION:
UNT094 IN BECR 40.0
END DESCRIPTION:
XS GIS Cut Line= 3
      3773049.58     10558160.21      3772449.61     10558610.19
      3771749.66     10558760.18
#Sta/Elev= 30
  4211.5  328.84  4283.3  325.29  4289.6  322.93  4354.2   315.3  4368.8  315.77
    4375  314.11  4454.2  308.56  4589.6  301.76  4611.5  301.07    4625  302.72
  4954.2  300.79  4981.1  301.67  5027.5  300.37  5030.2  299.87  5033.5  300.37
  5035.6   301.5  5224.9  301.68  5287.1  303.29  5350.1   307.7  5410.6  314.56
  5421.7  318.13  5452.4  322.66    5460  325.42  5489.1   331.1  5523.9  339.59
  5544.4  343.01  5558.9  343.65  5575.1  347.14  5646.7  352.94  5677.3  353.16
#Mann= 6 ,-1 , 0
  4211.5     .12       0  5027.5     .07       0  5033.5     .12       0
  5224.9     .16       0  5287.1     .12       0  5489.1     .16       0
Bank Sta=4981.1,5035.6
XS Rating Curve= 0 ,0
Exp/Cntr=0.3,0.1

Type RM Length L Ch R = 1 ,27178   ,538,538,538
BEGIN DESCRIPTION:
UNT094 IN BECR 39.0
END DESCRIPTION:
XS GIS Cut Line= 3
      3772849.65     10557810.16      3772099.61     10558310.19
      3771699.65     10558360.18
#Sta/Elev= 30
  4123.9  327.76  4196.1  325.59  4239.6   322.5  4383.8  306.65  4389.9  307.13
    4471  300.41  4888.6  300.09  4894.6   299.3  4924.7  300.06  4945.7  299.19
  4981.8  300.98  4989.3  300.62  4993.8  298.58  4996.5  298.08  4999.8  298.58
  5017.8  300.02  5055.6  299.44  5095.1  300.85  5136.2  303.45  5156.3  306.63
  5176.5   310.4  5206.7  318.85  5216.8  320.32  5224.4  323.06    5237  325.01
    5247  328.09  5317.6  341.34  5337.7   342.8    5368  347.62  5428.4  351.17
#Mann= 4 ,-1 , 0
  4123.9     .12       0  4993.8     .07       0  4999.8     .12       0
  5095.1     .16       0
Bank Sta=4981.8,5017.8
XS Rating Curve= 0 ,0
Exp/Cntr=0.3,0.1

Type RM Length L Ch R = 1 ,26640   ,507,507,507
BEGIN DESCRIPTION:
UNT094 IN BECR 38.0
END DESCRIPTION:
XS GIS Cut Line= 3
      3772749.65     10557760.19      3771999.61     10557810.19
       3771699.6      10558160.2
#Sta/Elev= 30
  4263.5  324.48  4293.6  322.34  4343.7  320.64  4393.8  317.21  4413.9  313.73
    4484  304.99  4524.1  301.37  4564.2  298.95  4654.4  298.21    4925  298.72
  4945.1  298.28  4955.1  297.16  4985.1  298.32  4992.2  295.86  4994.9  295.36
  4998.2  295.86  5015.2  298.01  5028.9  298.17  5133.7  304.77  5185.9  307.88
  5206.7  311.31  5256.1  315.87  5291.8  321.38  5298.9  324.02  5313.2  326.48
  5334.1   328.1  5341.7  330.38  5376.9  334.24    5384  336.21  5476.2  344.09
#Mann= 4 ,-1 , 0
  4263.5     .12       0  4992.2     .07       0  4998.2     .12       0
  5133.7     .16       0
Bank Sta=4985.1,5015.2
XS Rating Curve= 0 ,0
Exp/Cntr=0.3,0.1

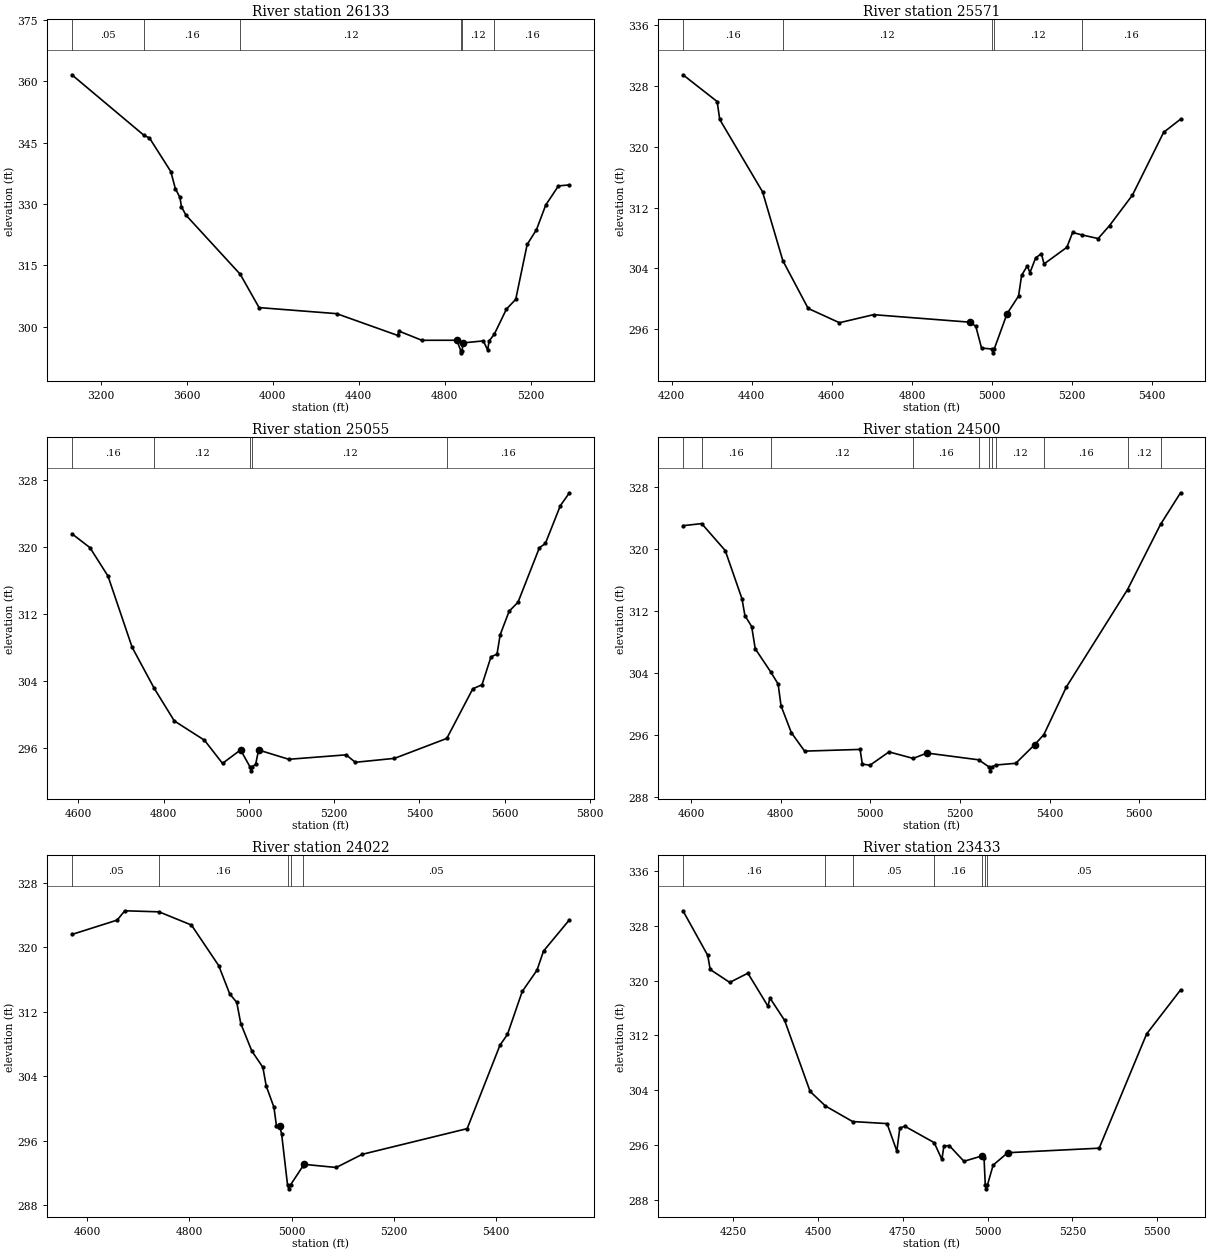
Type RM Length L Ch R = 1 ,26133   ,562,562,562
BEGIN DESCRIPTION:
UNT094 IN BECR 37.0
END DESCRIPTION:
XS GIS Cut Line= 3
      3773249.63     10556060.16      3771849.61     10557360.19
      3771499.65     10557560.17
#Sta/Elev= 30
    3066  361.62  3401.7  346.79  3426.9  346.15  3526.1  337.94  3547.1  333.78
  3568.6   331.6  3575.4  329.34  3596.9  327.25    3849   312.8  3936.5  304.65
  4297.1  303.17  4580.5  297.85  4587.3  298.89  4693.4  296.65  4856.1  296.66
  4874.6  294.08  4877.3  293.58  4880.6  294.08  4884.4  296.01  4979.4   296.5
  4999.6  294.25    5006  296.48  5030.5  298.16  5086.7  304.28  5129.9  306.67
  5183.1   320.1  5226.3   323.7  5269.5  329.75  5328.5  334.43  5379.6  334.67
#Mann= 6 ,-1 , 0
    3066     .05       0  3401.7     .16       0    3849     .12       0
  4874.6     .07       0  4880.6     .12       0  5030.5     .16       0
Bank Sta=4856.1,4884.4
XS Rating Curve= 0 ,0
Exp/Cntr=0.3,0.1

Type RM Length L Ch R = 1 ,25571   ,516,516,516
BEGIN DESCRIPTION:
UNT094 IN BECR 36.0
END DESCRIPTION:
XS GIS Cut Line= 3
      3772349.64     10556260.15      3771849.61     10556860.19
      3771549.64     10557210.15
#Sta/Elev= 30
  4228.5  329.46  4313.8  325.94  4320.3  323.58  4427.1  314.07  4477.8  305.01
    4541  298.73  4619.1  296.85  4704.3  297.91  4945.1  296.92  4959.5  296.37
  4973.8  293.52  4999.4  293.39  5002.2  292.89  5005.4  293.39  5037.6  298.05
  5066.1  300.35  5073.8  303.08    5088  304.33  5094.6  303.43  5108.9  305.39
  5123.2  305.92  5129.8  304.58  5186.8  306.77  5201.1  308.72  5224.5   308.4
  5264.8  307.92  5293.3  309.63  5350.4  313.63  5428.3  321.89  5470.5  323.62
#Mann= 5 ,-1 , 0
  4228.5     .16       0  4477.8     .12       0  4999.4     .07       0
  5005.4     .12       0  5224.5     .16       0
Bank Sta=4945.1,5037.6
XS Rating Curve= 0 ,0
Exp/Cntr=0.3,0.1

Type RM Length L Ch R = 1 ,25055   ,555,555,555
BEGIN DESCRIPTION:
UNT094 IN BECR 35.0
END DESCRIPTION:
XS GIS Cut Line= 3
      3771949.58     10556110.22      3771649.61     10556410.19
      3771149.62     10556960.17
#Sta/Elev= 30
  4584.6  321.54    4627  319.88  4669.4  316.48    4726  307.98    4778  303.06
    4825  299.18  4895.7  296.88  4938.1  294.11  4980.5  295.72  5002.3  293.72
    5005  293.22  5008.3  293.72  5015.9     294  5022.7  295.71  5093.6   294.6
  5228.1  295.13  5249.7  294.24  5341.6  294.71  5464.3  297.09  5525.4  303.02
    5547   303.5    5568  306.83  5582.2  307.16  5589.6  309.47  5610.6  312.28
  5631.5  313.36  5681.5  319.85  5695.7  320.38  5730.8  324.89  5752.1  326.43
#Mann= 5 ,-1 , 0
  4584.6     .16       0    4778     .12       0  5002.3     .07       0
  5008.3     .12       0  5464.3     .16       0
Bank Sta=4980.5,5022.7
XS Rating Curve= 0 ,0
Exp/Cntr=0.3,0.1

Type RM Length L Ch R = 1 ,24500   ,478,478,478
BEGIN DESCRIPTION:
UNT094 IN BECR 34.0
END DESCRIPTION:
XS GIS Cut Line= 3
       3771599.6     10555660.21      3771399.61     10556010.19
      3770899.61     10556510.19
#Sta/Elev= 30
  4581.9  322.96  4623.6  323.23  4676.2  319.76  4713.6  313.54  4720.1  311.38
  4735.2  309.97  4743.1  307.11  4778.1  304.09  4794.2  302.56  4800.7  299.76
  4823.7   296.3  4853.3  293.92  4977.1  294.14  4982.1  292.25  4999.1   292.1
  5041.6  293.82  5095.5  292.98  5126.4  293.67  5241.8   292.8  5264.8  291.88
  5267.6  291.38  5270.8  291.88  5279.9  292.13  5324.4  292.35  5366.8  294.76
  5387.2  296.05  5437.5   302.2  5573.9  314.74  5647.4  323.12  5692.1   327.2
#Mann= 11 ,-1 , 0
  4581.9     .05       0  4623.6     .16       0  4778.1     .12       0
  5095.5     .16       0  5241.8     .05       0  5264.8     .07       0
  5270.8     .05       0  5279.9     .12       0  5387.2     .16       0
  5573.9     .12       0  5647.4     .16       0
Bank Sta=5126.4,5366.8
XS Rating Curve= 0 ,0
Exp/Cntr=0.3,0.1

Type RM Length L Ch R = 1 ,24022   ,589,589,589
BEGIN DESCRIPTION:
UNT094 IN BECR 33.0
END DESCRIPTION:
XS GIS Cut Line= 3
      3771599.59      10555460.2      3771249.61     10555660.19
      3770799.59      10556010.2
#Sta/Elev= 30
  4570.3  321.61  4658.8  323.39  4673.9  324.55  4740.7  324.42  4804.2  322.78
  4857.5  317.75  4879.1  314.23  4892.8  313.19  4900.7  310.56  4922.3  307.15
  4943.9  305.13  4950.4  302.82  4965.5  300.18  4970.5  297.86  4976.6  297.86
  4980.6  296.86  4992.1  290.55  4994.9  290.05  4998.1  290.55  5021.9  292.84
  5024.1  293.09  5087.4   292.7  5138.1  294.33  5343.5  297.52  5407.7  307.88
  5422.2   309.2  5451.2  314.54  5480.1  317.18  5492.8  319.55  5543.5  323.43
#Mann= 5 ,-1 , 0
  4570.3     .05       0  4740.7     .16       0  4992.1     .07       0
  4998.1     .16       0  5021.9     .05       0
Bank Sta=4976.6,5024.1
XS Rating Curve= 0 ,0
Exp/Cntr=0.3,0.1

Type RM Length L Ch R = 1 ,23433   ,504,504,504
BEGIN DESCRIPTION:
UNT094 IN BECR 32.0
END DESCRIPTION:
XS GIS Cut Line= 3
       3771699.6      10554760.2      3770899.61     10555210.19
      3770349.57     10555210.19
#Sta/Elev= 30
  4101.3  330.16  4174.3  323.67  4181.6  321.61  4239.3  319.73  4292.8  321.07
  4352.1  316.26  4357.8  317.46  4401.2   314.2  4476.4  303.85  4521.7  301.73
  4601.7  299.47  4703.3  299.17  4732.3  295.17  4740.9  298.49  4755.3   298.8
  4842.4   296.4  4865.2  293.95    4871   295.9  4886.9  295.97  4930.2  293.68
  4983.8  294.47  4989.5  294.17  4993.2  290.17    4996  289.67  4999.2  290.17
  5016.3  293.12  5059.2  294.93  5329.2  295.59  5469.2  312.23  5569.2  318.63
#Mann= 7 ,-1 , 0
  4101.3     .16       0  4521.7     .12       0  4601.7     .05       0
  4842.4     .16       0  4983.8     .05       0  4993.2     .03       0
  4999.2     .05       0
Bank Sta=4983.8,5059.2
XS Rating Curve= 0 ,0
Exp/Cntr=0.3,0.1

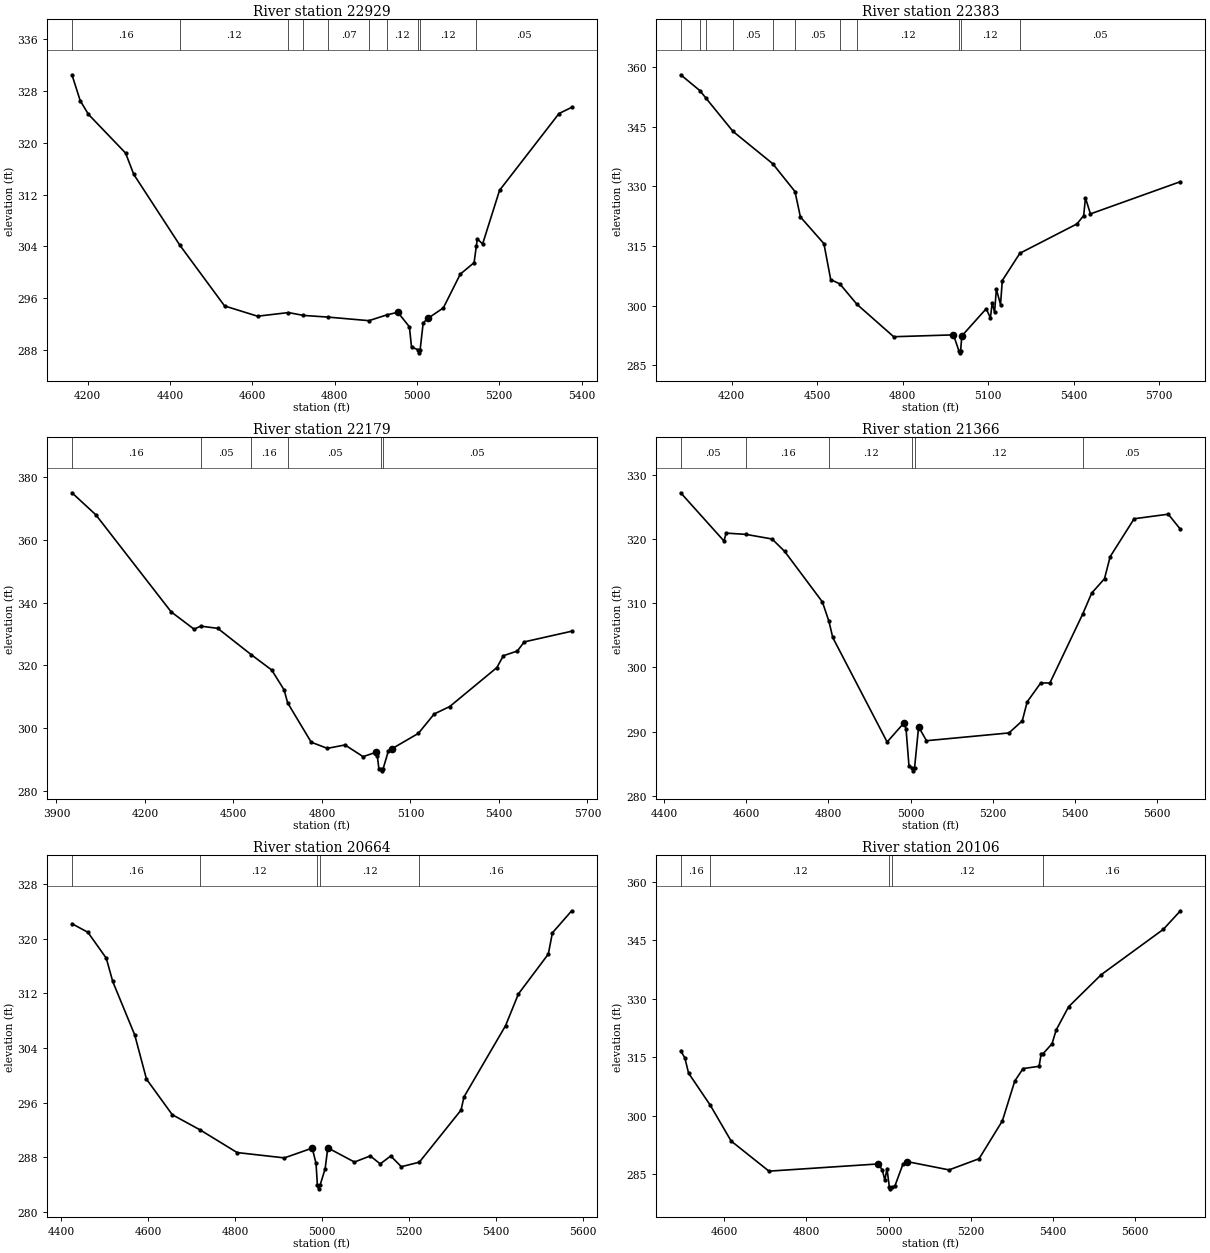
Type RM Length L Ch R = 1 ,22929   ,546,546,546
BEGIN DESCRIPTION:
UNT094 IN BECR 31.0
END DESCRIPTION:
XS GIS Cut Line= 3
      3771699.57     10554710.19      3770899.61     10554760.19
      3770499.64      10554660.2
#Sta/Elev= 30
  4162.1  330.48  4182.1  326.49  4202.1  324.38  4292.3  318.41  4312.3  315.11
    4424  304.21  4532.8  294.83  4612.9  293.25    4688  293.81  4724.3  293.37
  4784.3  293.11  4883.4  292.56  4927.6  293.47  4953.6  293.85  4981.7  291.61
  4986.8  288.49  5001.8   288.1  5004.6   287.6  5007.8   288.1  5015.2  292.24
    5028  292.97  5064.1  294.53  5105.3  299.74  5138.8  301.51  5144.3  304.09
  5146.6  305.17  5159.5  304.39  5200.7  312.67    5345   324.5  5375.9  325.46
#Mann= 10 ,-1 , 0
  4162.1     .16       0    4424     .12       0    4688     .07       0
  4724.3     .05       0  4784.3     .07       0  4883.4     .05       0
  4927.6     .12       0  5001.8     .07       0  5007.8     .12       0
  5144.3     .05       0
Bank Sta=4953.6,5028
XS Rating Curve= 0 ,0
Exp/Cntr=0.3,0.1

Type RM Length L Ch R = 1 ,22383   ,204,204,204
BEGIN DESCRIPTION:
UNT094 IN BECR 30.0
END DESCRIPTION:
XS GIS Cut Line= 4
      3771870.07      10553853.9      3771151.32     10554150.78
      3770812.78     10554400.78      3770303.48     10554619.05
#Sta/Elev= 30
  4021.3  358.02  4088.5  354.05    4109  352.23  4204.8  343.78  4344.1  335.66
  4422.2  328.66  4441.1  322.28  4523.6  315.57  4547.5  306.51  4579.2  305.46
  4639.6   300.3  4768.3  292.16    4978  292.63    4997  288.61  4999.7  288.11
    5003  288.61  5007.3  292.36  5092.9  299.21  5107.5  296.87  5113.7  300.69
  5122.1  298.34  5128.4   304.1    5143  300.25  5149.2  306.29  5210.9  313.15
  5411.2  320.53  5434.7  322.63  5440.8  327.08  5458.3  323.04  5773.9  331.15
#Mann= 11 ,-1 , 0
  4021.3     .16       0  4088.5     .05       0    4109     .16       0
  4204.8     .05       0  4344.1     .16       0  4422.2     .05       0
  4579.2     .16       0  4639.6     .12       0    4997     .07       0
    5003     .12       0  5210.9     .05       0
Bank Sta=4978,5007.3
XS Rating Curve= 0 ,0
Exp/Cntr=0.3,0.1

Type RM Length L Ch R = 1 ,22179   ,813,813,813
BEGIN DESCRIPTION:
UNT094 IN BECR 29.0
END DESCRIPTION:
XS GIS Cut Line= 4
       3771885.7     10553562.23      3771526.32     10553874.74
      3770849.24     10554135.15       3770396.1     10554327.87
#Sta/Elev= 30
  3952.6  375.11  4033.4  368.09  4288.9  337.07  4366.7  331.53  4388.8  332.51
  4446.8  331.81    4560  323.42  4629.7   318.5  4671.8  312.14  4683.8  307.98
  4763.6  295.44  4818.2  293.47  4878.2  294.56  4939.6  290.82  4982.2   292.2
  4987.5  291.17  4993.2  286.85  5000.9  286.79  5003.6  286.29  5006.9  286.79
  5025.3  292.67    5036  293.28  5126.8  298.25  5180.5  304.45  5233.2  306.83
    5393  319.27    5415  323.06  5462.3  324.56  5485.9  327.48  5646.7  330.89
#Mann= 6 ,-1 , 0
  3952.6     .16       0  4388.8     .05       0    4560     .16       0
  4683.8     .05       0  5000.9     .04       0  5006.9     .05       0
Bank Sta=4982.2,5036
XS Rating Curve= 0 ,0
Exp/Cntr=0.3,0.1

Type RM Length L Ch R = 1 ,21366   ,702,702,702
BEGIN DESCRIPTION:
UNT094 IN BECR 28.0
END DESCRIPTION:
XS GIS Cut Line= 3
      3771281.53     10553218.49      3770651.32     10553447.65
      3770401.31     10553932.06
#Sta/Elev= 30
  4440.7  327.25    4546  319.73  4551.3  320.96  4599.7  320.76    4663  320.04
  4693.6  318.11  4785.4  310.23  4801.4  307.18  4810.6  304.68  4942.9  288.38
  4983.6  291.33  4988.9  290.44  4996.1   284.6  5003.7  284.38  5006.5  283.88
  5009.7  284.38  5019.5  290.74  5038.6  288.58  5239.2  289.79  5271.7  291.68
  5283.6  294.64  5316.6  297.59  5338.8  297.58  5418.5  308.31  5440.5   311.6
  5471.7  313.85  5485.5  317.29  5543.8   323.2  5626.8  323.91  5656.4  321.55
#Mann= 6 ,-1 , 0
  4440.7     .05       0  4599.7     .16       0  4801.4     .12       0
  5003.7     .07       0  5009.7     .12       0  5418.5     .05       0
Bank Sta=4983.6,5019.5
XS Rating Curve= 0 ,0
Exp/Cntr=0.3,0.1

Type RM Length L Ch R = 1 ,20664   ,558,558,558
BEGIN DESCRIPTION:
UNT094 IN BECR 27.0
END DESCRIPTION:
XS GIS Cut Line= 3
       3770899.6     10552560.19      3770399.61     10552910.19
      3769899.64     10553110.18
#Sta/Elev= 30
  4425.5  322.19  4462.1  320.93  4504.4  317.14  4519.2  313.73  4569.8   305.9
  4596.8  299.44  4656.1  294.23  4719.7  292.02  4805.2  288.69  4913.8  287.91
  4977.8  289.34  4986.6  287.09  4989.7  283.88  4992.4  283.38  4995.7  283.88
  5007.5  286.32  5013.6  289.38  5074.9   287.3  5111.2   288.2  5134.1  287.03
  5158.3  288.19  5182.6  286.62    5224  287.28  5319.9  294.91  5326.6  296.83
  5422.2  307.26  5451.8  311.91  5520.5  317.74  5529.9  320.85  5574.3  324.08
#Mann= 5 ,-1 , 0
  4425.5     .16       0  4719.7     .12       0  4989.7     .07       0
  4995.7     .12       0    5224     .16       0
Bank Sta=4977.8,5013.6
XS Rating Curve= 0 ,0
Exp/Cntr=0.3,0.1

Type RM Length L Ch R = 1 ,20106   ,638,638,638
BEGIN DESCRIPTION:
UNT094 IN BECR 26.0
END DESCRIPTION:
XS GIS Cut Line= 3
      3770699.58     10552360.19      3770249.61     10552460.19
       3769499.6     10552560.19
#Sta/Elev= 30
  4493.6  316.65  4503.8  314.77  4512.8  310.89  4565.8  302.63  4616.5  293.46
  4708.7  285.73  4974.7  287.58  4984.8  286.06  4991.1  283.39  4996.2   286.4
    5002  281.69  5004.7  281.19    5008  281.69  5015.1  281.81  5035.3  287.57
  5045.3  288.18  5147.5  286.05  5220.6  288.92  5277.4  298.64  5307.6  308.86
  5327.8  312.05  5366.9  312.64    5372  315.92  5375.5  315.76  5398.4  318.43
  5408.5  321.97  5438.8  327.93  5518.2  336.15  5669.6  347.79  5711.2  352.55
#Mann= 5 ,-1 , 0
  4493.6     .16       0  4565.8     .12       0    5002     .07       0
    5008     .12       0  5375.5     .16       0
Bank Sta=4974.7,5045.3
XS Rating Curve= 0 ,0
Exp/Cntr=0.3,0.1