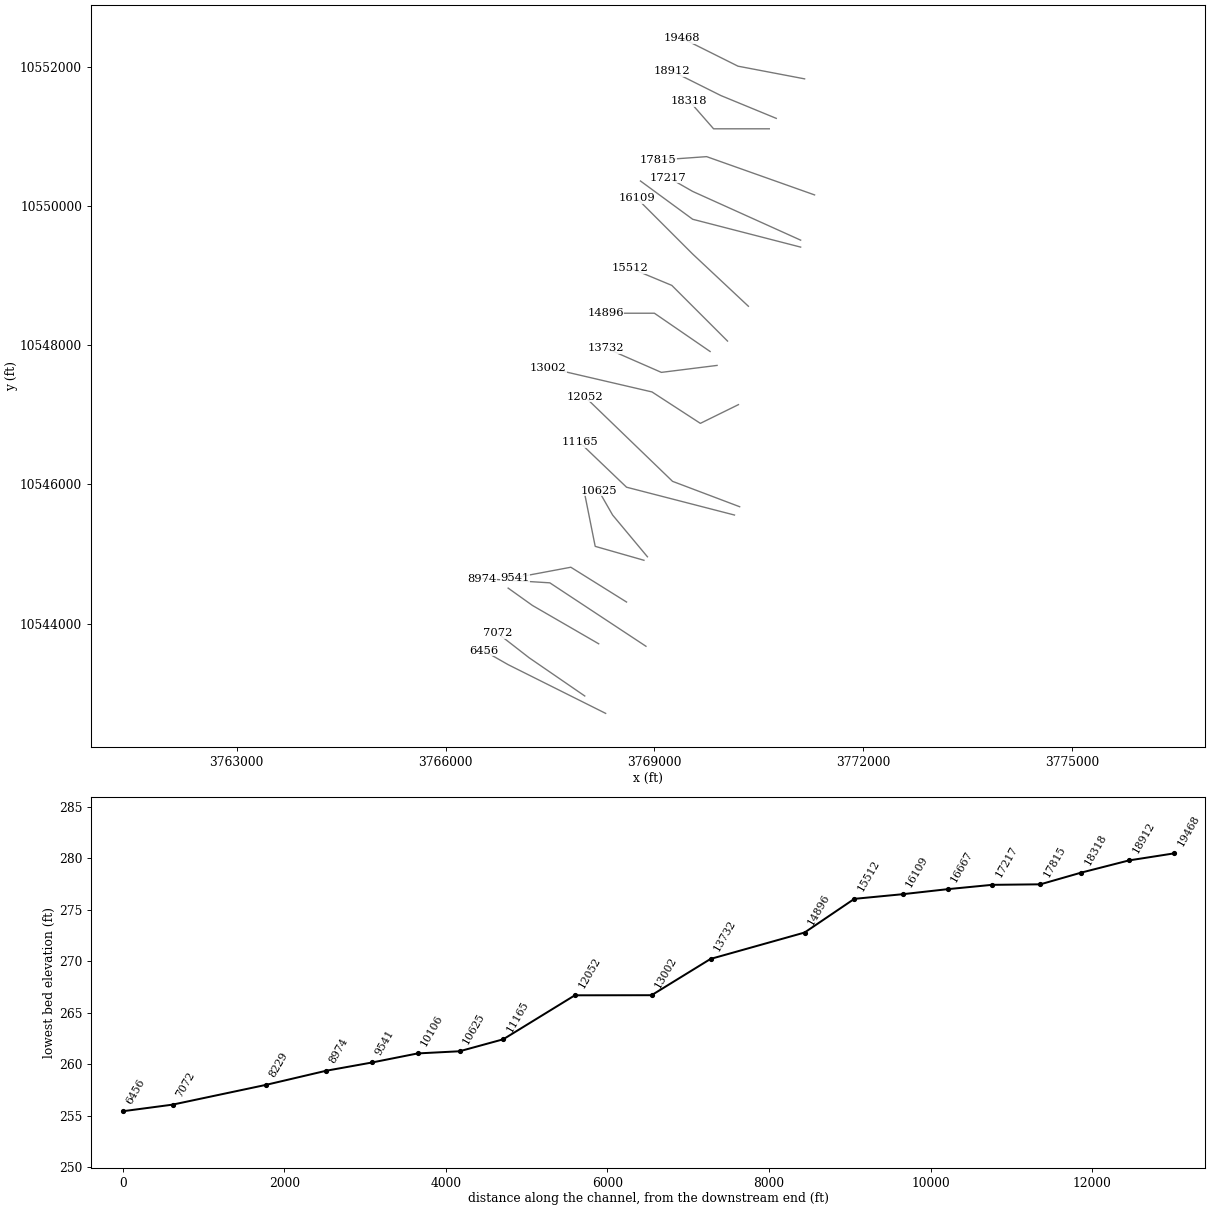
HEC-RAS study UNT094 IN BECR.prj: UNT094 IN BECR Base Level Engineering

--- UNT094 IN BECR.g01 (geometry) --- (continued)

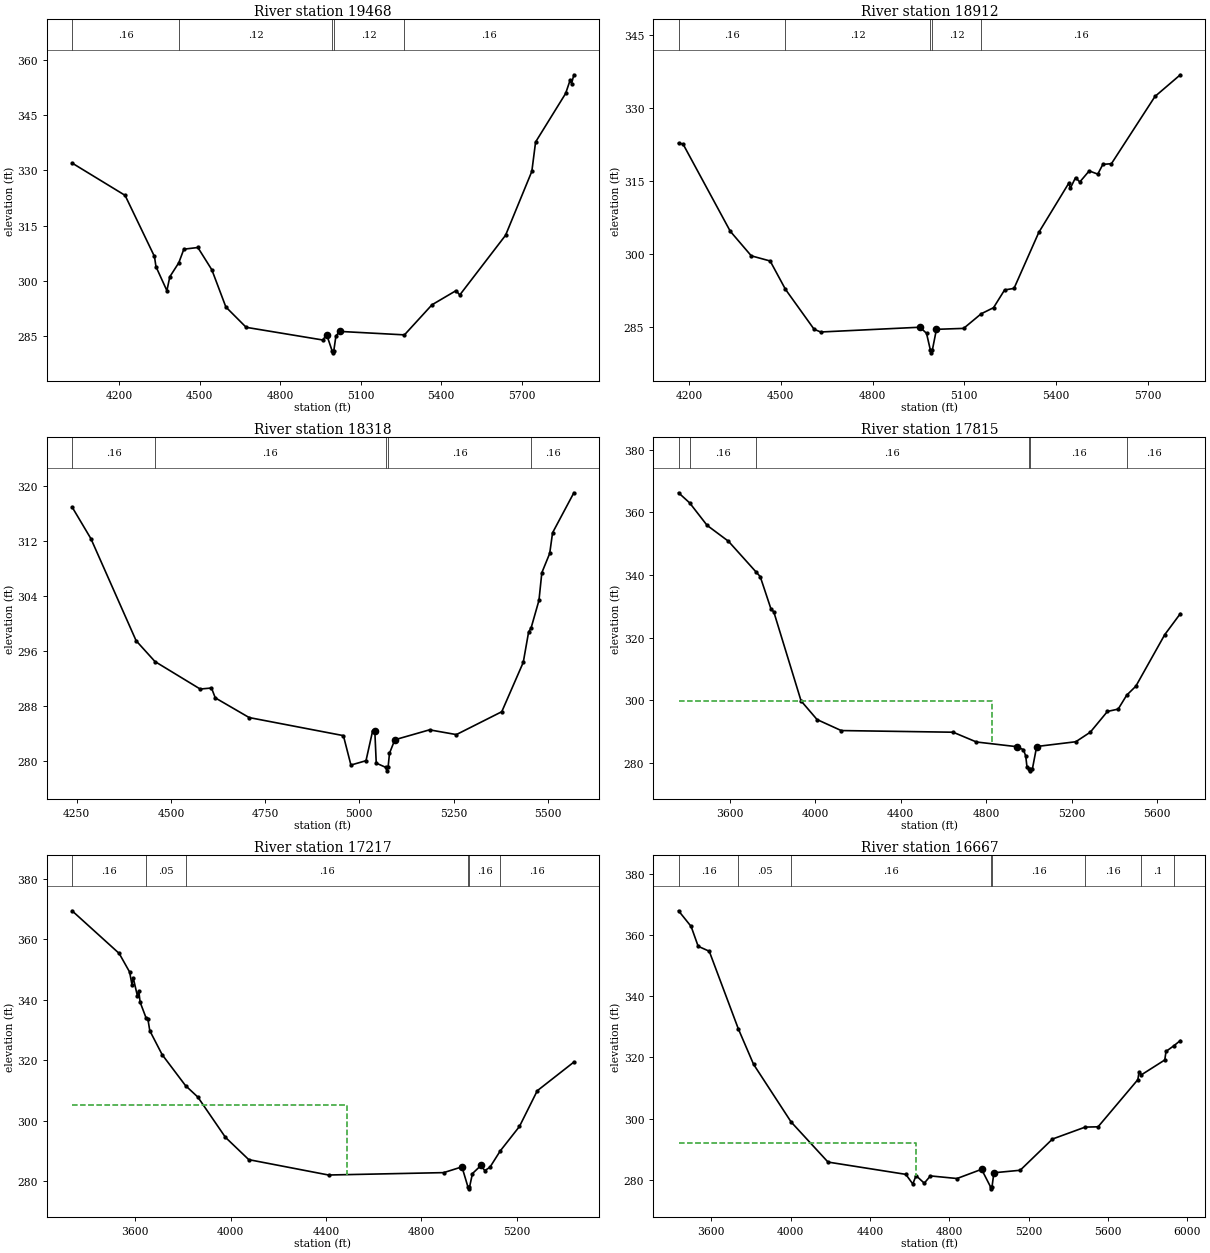
Type RM Length L Ch R = 1 ,19468   ,556,556,556
BEGIN DESCRIPTION:
UNT094 IN BECR 25.0
END DESCRIPTION:
XS GIS Cut Line= 3
      3771156.49     10551827.87      3770199.61     10552010.19
      3769399.63     10552410.18
#Sta/Elev= 30
  4025.3  332.02  4222.7  323.24  4332.1  306.64  4337.7  303.88  4378.4  297.36
  4389.3  301.13  4422.9  304.96  4441.5  308.62  4493.7  309.08  4545.8  303.02
    4598  292.92  4673.6   287.4  4958.7  283.96  4973.3  285.41  4993.8  280.97
  4996.6  280.47  4999.8  280.97  5007.8  285.05  5021.8  286.29    5263  285.35
  5365.5  293.52    5455  297.36    5469  296.19  5639.5   312.4  5737.3  329.76
  5751.3  337.73  5863.1  350.91  5879.8  354.51  5885.4  353.62  5893.8  355.99
#Mann= 5 ,-1 , 0
  4025.3     .16       0  4422.9     .12       0  4993.8     .07       0
  4999.8     .12       0    5263     .16       0
Bank Sta=4973.3,5021.8
XS Rating Curve= 0 ,0
Exp/Cntr=0.3,0.1

Type RM Length L Ch R = 1 ,18912   ,594,594,594
BEGIN DESCRIPTION:
UNT094 IN BECR 24.0
END DESCRIPTION:
XS GIS Cut Line= 3
      3770749.65     10551260.17      3769953.41     10551588.28
      3769255.48     10551937.24
#Sta/Elev= 30
  4165.3  322.84    4180  322.67  4334.5  304.76  4403.3  299.71    4465  298.65
  4515.1  292.83  4608.8  284.63  4630.4  284.07  4954.9  285.05  4976.5  283.81
  4989.4  280.29  4992.2  279.79  4995.4  280.29    5009  284.62  5097.8  284.81
  5155.4  287.81  5195.7  289.06    5232  292.71  5262.7  293.02  5343.8  304.52
  5441.6   314.6  5447.2  313.62    5464  315.77    5478  314.88  5508.7  317.15
  5536.7  316.49  5553.4  318.49  5581.4  318.63  5723.9  332.44  5806.8  336.89
#Mann= 5 ,-1 , 0
  4165.3     .16       0  4515.1     .12       0  4989.4     .07       0
  4995.4     .12       0  5155.4     .16       0
Bank Sta=4954.9,5009
XS Rating Curve= 0 ,0
Exp/Cntr=0.3,0.1

Type RM Length L Ch R = 1 ,18318   ,503,503,503
BEGIN DESCRIPTION:
UNT094 IN BECR 23.0
END DESCRIPTION:
XS GIS Cut Line= 3
      3770649.66     10551110.19      3769849.61     10551110.19
      3769499.58     10551510.22
#Sta/Elev= 30
  4237.6  316.89  4287.6  312.29  4407.6  297.48  4457.6  294.46  4577.6  290.47
  4607.6  290.62  4617.6  289.19  4707.6  286.33  4957.6  283.71  4977.6  279.44
  5017.6  280.07  5035.1  284.37    5041  284.37  5044.8  279.72  5070.2   279.1
    5073   278.6  5076.2   279.1  5079.9  281.14  5094.1  283.11  5186.2  284.55
  5257.4  283.86  5377.9  287.18  5434.9  294.34  5449.1  298.74  5455.7  299.33
  5476.6  303.34  5484.2  307.35  5505.1  310.15  5512.7  313.15  5569.2  318.95
#Mann= 5 ,-1 , 0
  4237.6     .16       0  4457.6     .16       0  5070.2     .07       0
  5076.2     .16       0  5455.7     .16       0
Bank Sta=5041,5094.1
XS Rating Curve= 0 ,0
Exp/Cntr=0.3,0.1

Type RM Length L Ch R = 1 ,17815   ,598,598,598
BEGIN DESCRIPTION:
UNT094 IN BECR 22.0
END DESCRIPTION:
XS GIS Cut Line= 3
      3771299.65     10550160.17      3769749.61     10550710.19
      3769049.63     10550660.19
#Sta/Elev= 30
  3361.1  366.24    3413  363.02  3494.7  355.84  3594.6  350.76  3721.9  341.09
  3743.1  339.48  3792.8  329.27  3806.8  328.17  3934.1   299.8  4008.9  293.84
  4121.8  290.33  4645.1   289.8  4754.1  286.68  4942.2  285.19    4974  284.23
  4984.6   282.2  4990.4  278.81  5000.2  277.97  5002.9  277.47  5006.2  277.97
  5015.9   278.1  5035.9  285.24  5218.9  286.76  5286.6  289.81  5366.8  296.43
  5416.9  297.18    5457  301.64  5499.6  304.49  5634.9  320.96  5707.6  327.65
#Mann= 6 ,-1 , 0
  3361.1     .05       0    3413     .16       0  3721.9     .16       0
  5000.2     .07       0  5006.2     .16       0    5457     .16       0
#XS Ineff= 2 , 0
         4827.27   299.8
Permanent Ineff=
       F       F
Bank Sta=4942.2,5035.9
XS Rating Curve= 0 ,0
Exp/Cntr=0.3,0.1

Type RM Length L Ch R = 1 ,17217   ,550,550,550
BEGIN DESCRIPTION:
UNT094 IN BECR 21.0
END DESCRIPTION:
XS GIS Cut Line= 3
      3771099.62     10549510.18      3769549.61     10550210.19
      3769199.57     10550410.21
#Sta/Elev= 30
  3335.6  369.34  3533.1  355.24    3577  349.08  3586.6  344.95  3592.1  347.15
  3609.7  341.14  3615.2  342.89  3620.9  339.13  3646.2  333.86  3653.8   333.4
  3661.5  329.69  3713.2  321.79  3811.2  311.55  3862.9  307.76  3978.5  294.46
  4076.5  287.07  4410.9  281.99  4893.7  282.78  4970.3  284.68  4995.9  277.92
  4998.7  277.42  5001.9  277.92  5014.4  282.48    5050  285.15  5065.9  283.45
  5087.5  284.54  5130.6  289.93  5211.3  298.03  5286.1  309.85  5439.5  319.32
#Mann= 6 ,-1 , 0
  3335.6     .16       0  3646.2     .05       0  3811.2     .16       0
  4995.9     .07       0  5001.9     .16       0  5130.6     .16       0
#XS Ineff= 2 , 0
         4488.64  305.06
Permanent Ineff=
       F       F
Bank Sta=4970.3,5050
XS Rating Curve= 0 ,0
Exp/Cntr=0.3,0.1

Type RM Length L Ch R = 1 ,16667   ,558,558,558
BEGIN DESCRIPTION:
UNT094 IN BECR 20.0
END DESCRIPTION:
XS GIS Cut Line= 3
      3771099.57      10549410.2      3769549.61     10549810.19
       3768799.6     10550360.19
#Sta/Elev= 30
  3434.4  368.01  3497.9  362.88  3533.4  356.39  3589.3  354.77  3736.2  329.33
  3812.9  317.75  4002.4  298.87  4188.3  285.76  4580.7  281.74  4615.9  278.59
  4632.4  281.33  4673.7  278.85  4704.7  281.23  4838.9  280.38  4962.8  283.39
  5009.2   277.5    5012     277  5015.2   277.5  5024.8  282.26  5157.5  283.08
  5320.4   293.3  5485.5  297.21  5550.3   297.3    5751  312.74  5757.2  315.34
  5768.7  314.31  5886.8  319.18    5893  321.98  5931.5  323.78  5965.2  325.53
#Mann= 8 ,-1 , 0
  3434.4     .16       0  3736.2     .05       0  4002.4     .16       0
  5009.2     .07       0  5015.2     .16       0  5485.5     .16       0
  5768.7      .1       0  5931.5     .16       0
#XS Ineff= 2 , 0
         4632.95  292.14
Permanent Ineff=
       F       F
Bank Sta=4962.8,5024.8
XS Rating Curve= 0 ,0
Exp/Cntr=0.3,0.1

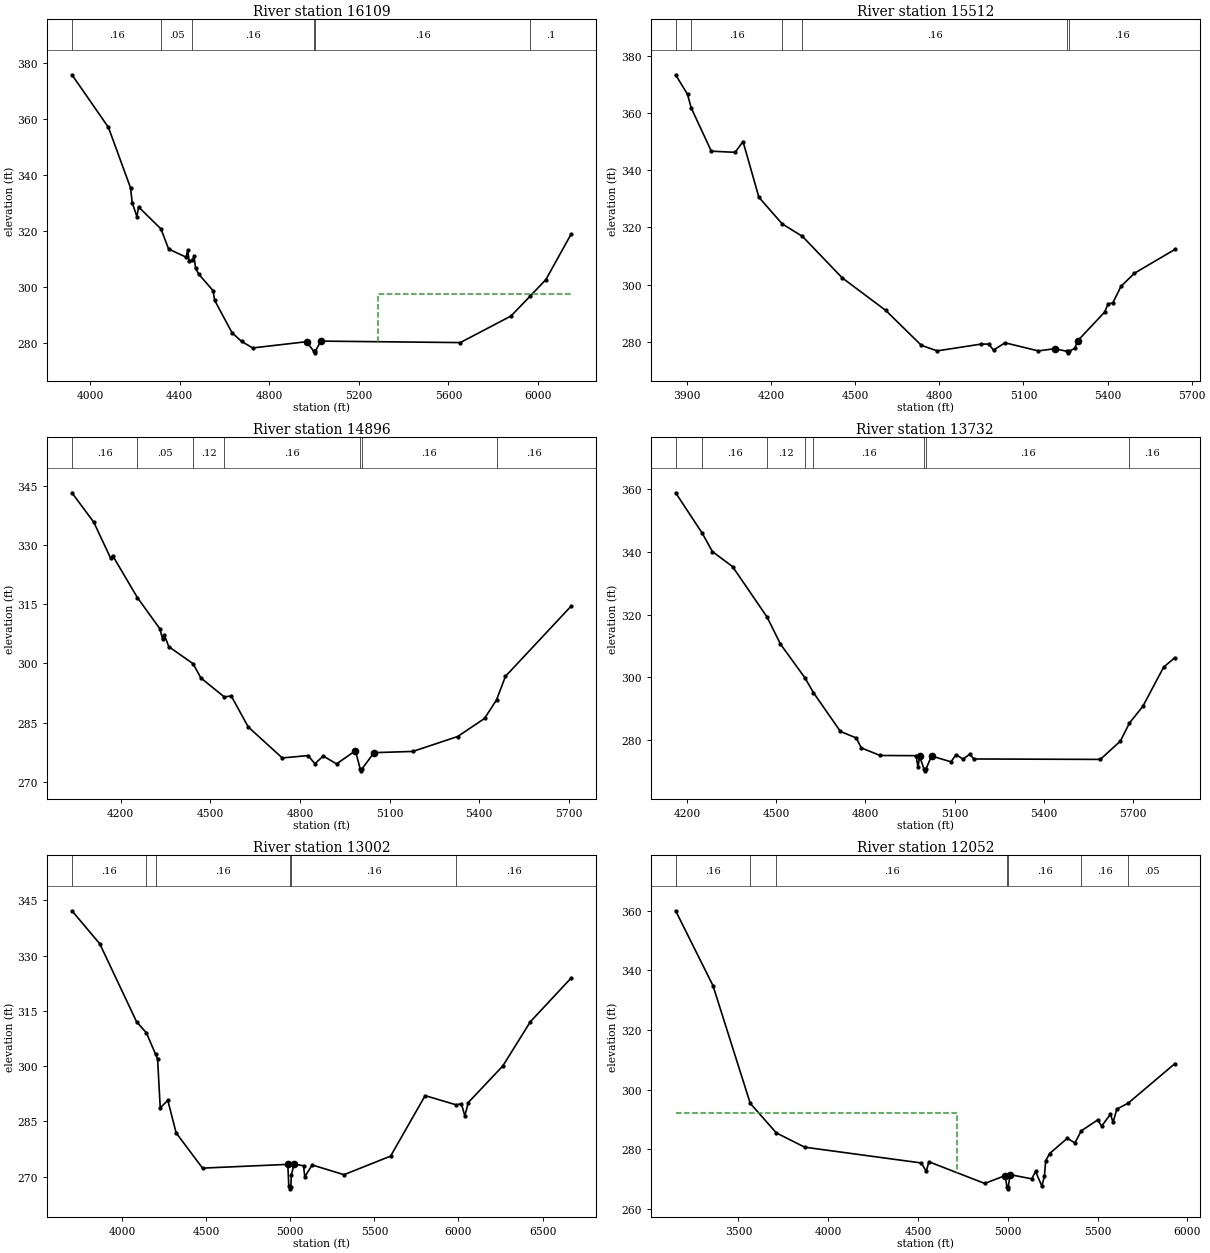
Type RM Length L Ch R = 1 ,16109   ,597,597,597
BEGIN DESCRIPTION:
UNT094 IN BECR 19.0
END DESCRIPTION:
XS GIS Cut Line= 3
      3770349.58     10548560.22      3769549.61     10549310.19
      3768749.62     10550110.18
#Sta/Elev= 30
  3919.9   375.8  4082.7  357.02  4181.4  335.42  4188.7  330.15  4209.8  325.15
  4217.1  328.62  4317.2  320.75  4351.4  313.57  4429.1  310.68  4436.4  313.09
  4443.2  309.24  4457.4  309.51  4464.7  310.97  4471.6  306.73  4485.7   304.6
  4549.7  298.71  4556.6  295.27  4634.2   283.7  4676.7   280.6  4726.5  278.26
  4966.9  280.49  4999.5  277.01  5002.3  276.51  5005.5  277.01  5030.6   280.7
  5652.8  280.17  5879.1  289.66    5964  296.71  6034.7  302.67  6147.8  318.96
#Mann= 6 ,-1 , 0
  3919.9     .16       0  4317.2     .05       0  4457.4     .16       0
  4999.5     .07       0  5005.5     .16       0    5964      .1       0
#XS Ineff= 2 , 0
                         5286.36           297.4
Permanent Ineff=
       F       F
Bank Sta=4966.9,5030.6
XS Rating Curve= 0 ,0
Exp/Cntr=0.3,0.1

Type RM Length L Ch R = 1 ,15512   ,616,616,616
BEGIN DESCRIPTION:
UNT094 IN BECR 18.0
END DESCRIPTION:
XS GIS Cut Line= 3
      3770049.62     10548060.18      3769249.61     10548860.19
      3768649.59      10549110.2
#Sta/Elev= 30
  3858.9  373.52  3901.3  366.65  3914.5  361.89  3986.2  346.74    4071  346.34
  4099.3  350.12  4155.9  330.59  4238.8  321.28  4311.5  316.86  4452.9  302.37
  4608.4  290.94  4735.7  278.68  4792.3  276.75  4947.9  279.11  4976.1  279.13
    4993  277.01  5034.2  279.58  5152.8  276.74  5211.8  277.51  5256.5  276.56
  5259.2  276.06  5262.5  276.56  5282.8  277.63  5294.2  280.37  5389.5  290.34
  5401.9   293.2  5418.7  293.56    5448  299.37  5495.7  303.95  5640.3  312.31
#Mann= 6 ,-1 , 0
  3858.9     .05       0  3914.5     .16       0  4238.8     .05       0
  4311.5     .16       0  5256.5     .07       0  5262.5     .16       0
Bank Sta=5211.8,5294.2
XS Rating Curve= 0 ,0
Exp/Cntr=0.3,0.1

Type RM Length L Ch R = 1 ,14896   ,1164,1164,1164
BEGIN DESCRIPTION:
UNT094 IN BECR 17.0
END DESCRIPTION:
XS GIS Cut Line= 3
      3769799.64     10547910.17      3768999.61     10548460.19
      3768299.57     10548460.19
#Sta/Elev= 30
  4036.8  343.27  4109.7  335.83  4166.7  326.63  4172.8  327.37  4255.8  316.71
  4331.1  308.79  4339.9  306.28    4346  307.27  4360.9  304.26  4442.1  299.95
  4468.5  296.32  4546.5  291.53    4570  291.77  4626.8  283.91  4740.7  276.06
    4827  276.66  4849.9   274.6  4877.8  276.54  4922.4  274.55  4985.3  277.87
  5001.6  273.29  5004.4  272.79  5007.6  273.29  5047.7   277.4  5177.7  277.71
  5327.7  281.49  5417.7  286.07  5457.7  290.77  5487.7  296.75  5707.7  314.56
#Mann= 7 ,-1 , 0
  4036.8     .16       0  4255.8     .05       0  4442.1     .12       0
  4546.5     .16       0  5001.6     .07       0  5007.6     .16       0
  5457.7     .16       0
Bank Sta=4985.3,5047.7
XS Rating Curve= 0 ,0
Exp/Cntr=0.3,0.1

Type RM Length L Ch R = 1 ,13732   ,730,730,730
BEGIN DESCRIPTION:
UNT094 IN BECR 16.0
END DESCRIPTION:
XS GIS Cut Line= 3
      3769899.61     10547710.19      3769099.61     10547610.19
      3768299.65     10547960.17
#Sta/Elev= 30
  4161.4  358.77  4251.2  345.85  4284.9  340.06  4352.9  335.26  4468.8  319.22
  4514.1  310.57  4595.7  299.93    4625  295.13  4715.7  282.77  4768.6  280.71
  4786.2  277.52  4849.2  275.12  4970.4  275.06  4976.6  271.36  4982.1  274.81
    4997  270.73  4999.7  270.23    5003  270.73  5022.2  274.94  5087.7   273.1
  5104.5   275.4  5127.8  273.97  5151.2  275.56  5164.1  274.01  5589.8  273.87
  5657.2  279.68    5688  285.47  5732.9  290.77    5803  303.27  5840.8  306.28
#Mann= 8 ,-1 , 0
  4161.4     .05       0  4251.2     .16       0  4468.8     .12       0
  4595.7     .05       0    4625     .16       0    4997     .07       0
    5003     .16       0    5688     .16       0
Bank Sta=4982.1,5022.2
XS Rating Curve= 0 ,0
Exp/Cntr=0.3,0.1

Type RM Length L Ch R = 1 ,13002   ,950,950,950
BEGIN DESCRIPTION:
Mapping XS 40d2e9ba
END DESCRIPTION:
XS GIS Cut Line= 4
      3770206.61     10547146.72      3769659.71     10546877.61
      3768965.26       10547329.      3767473.36     10547675.95
#Sta/Elev= 30
  3701.2  342.15  3866.9  333.18    4086     312  4143.7  309.06  4198.4  303.26
  4210.5  301.95  4226.4  288.67  4271.4  290.72  4320.7  281.91  4477.8  272.33
    4985  273.35  4990.9  267.56  4997.1  267.21  4999.8  266.71  5003.1  267.21
  5006.1  270.37  5021.2  273.37  5078.5  272.99  5086.1  269.97  5129.9  273.19
  5319.3  270.55  5596.5  275.59  5801.9     292  5986.7   289.5  6017.5  289.81
    6038  286.48  6058.5  290.13  6263.9  300.05  6428.1  312.07  6670.7  323.93
#Mann= 6 ,-1 , 0
  3701.2     .16       0  4143.7     .16       0  4198.4     .16       0
  4997.1     .07       0  5003.1     .16       0  5986.7     .16       0
Bank Sta=4985,5021.2
XS Rating Curve= 0 ,0
Exp/Cntr=0.3,0.1

Type RM Length L Ch R = 1 ,12052   ,887,887,887
BEGIN DESCRIPTION:
UNT094 IN BECR 15.0
END DESCRIPTION:
XS GIS Cut Line= 3
      3770223.96     10545679.69       3769260.4     10546044.28
      3768001.69     10547259.59
#Sta/Elev= 30
  3150.5  359.92  3358.3  334.84  3565.9  295.36  3711.1  285.45  3869.3  280.66
  4517.8  275.38  4546.1  272.57  4560.2  275.78  4871.5  268.51  4984.7  271.13
  4995.8   267.2  4998.6   266.7  5001.8   267.2    5013  271.46  5133.1  270.05
  5154.5  272.53  5189.7  267.61  5203.9     271  5210.8  276.09  5232.2   278.5
  5331.2  283.65  5373.7  282.09  5408.9  286.14    5501  289.83  5522.1   287.7
  5571.7  291.73  5585.8  288.97    5607  293.44  5669.7   295.4  5930.4  308.69
#Mann= 7 ,-1 , 0
  3150.5     .16       0  3565.9     .05       0  3711.1     .16       0
  4995.8     .07       0  5001.8     .16       0  5408.9     .16       0
  5669.7     .05       0
#XS Ineff= 2 , 0
         4716.48  292.17
Permanent Ineff=
       F       F
Bank Sta=4984.7,5013
XS Rating Curve= 0 ,0
Exp/Cntr=0.3,0.1

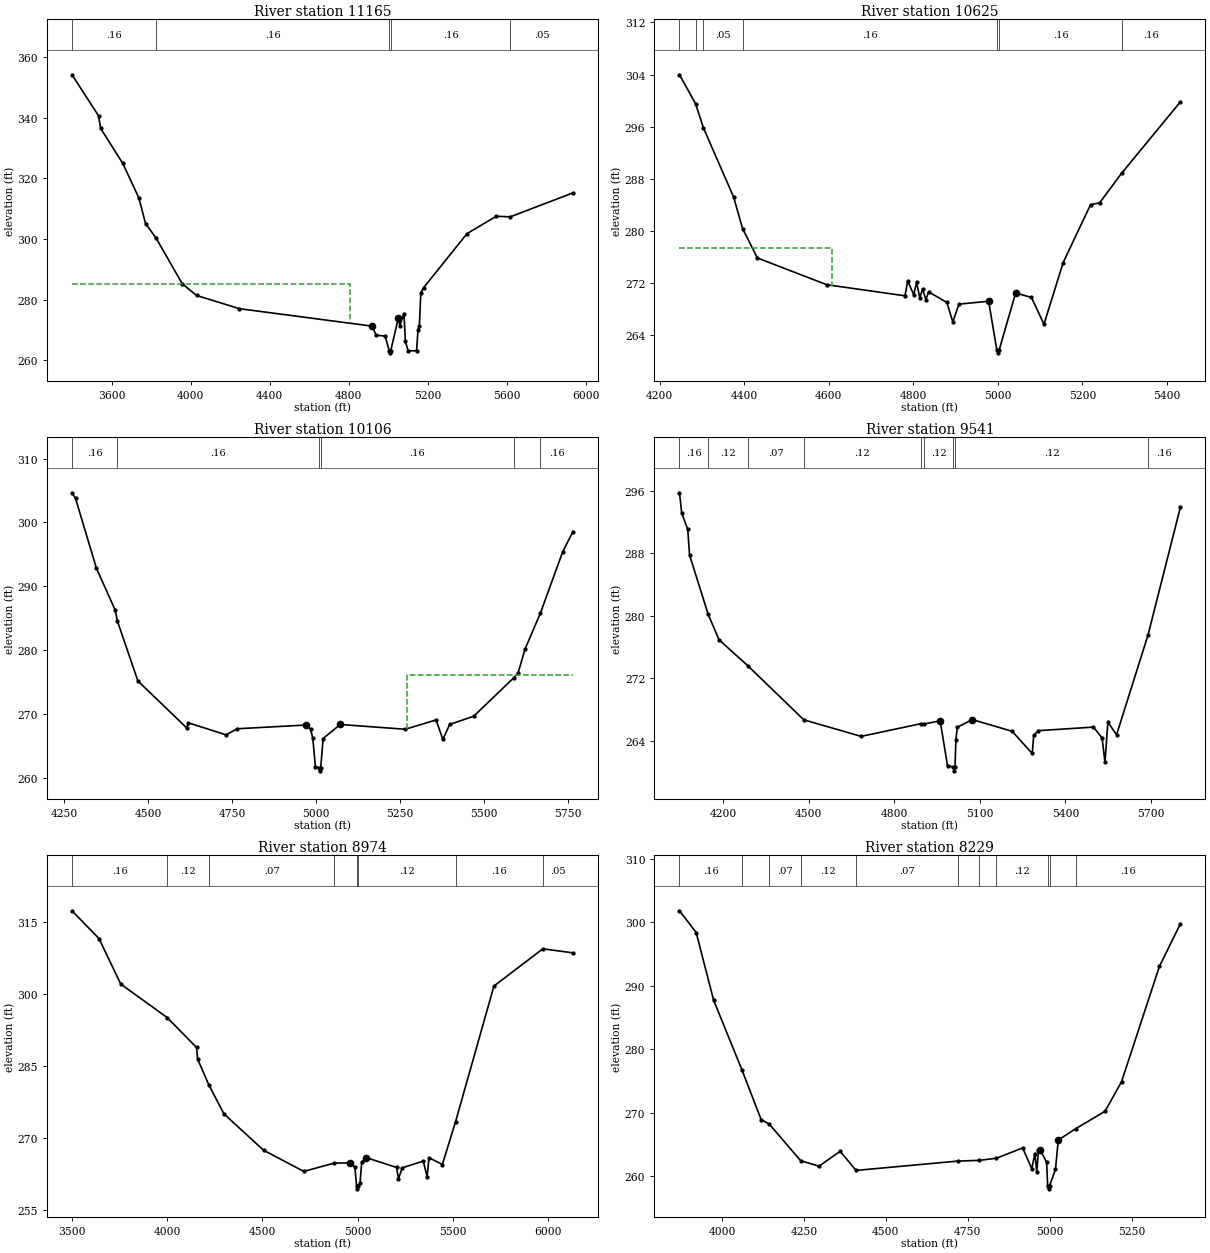
Type RM Length L Ch R = 1 ,11165   ,540,540,540
BEGIN DESCRIPTION:
UNT094 IN BECR 14.0
END DESCRIPTION:
XS GIS Cut Line= 3
      3770149.59     10545560.19      3768599.61     10545960.19
      3767926.25     10546604.33
#Sta/Elev= 30
  3400.3  354.14  3534.5  340.61  3545.2  336.44  3656.9  324.92  3738.2  313.53
  3772.1  305.08  3825.6  300.25    3958  285.18  4030.3  281.35  4247.1  276.99
  4918.4  271.23  4937.5  268.23  4983.3  267.97  5005.1  262.93  5007.9  262.43
  5011.1  262.93  5050.6  274.02  5057.5  271.42  5078.9  275.35  5085.8  266.19
    5100  263.12  5142.4  263.11  5149.7  269.97  5156.6  271.19  5163.8  282.19
    5178  283.91  5397.2  301.73  5545.6  307.48  5616.4  307.29  5932.9  315.18
#Mann= 5 ,-1 , 0
  3400.3     .16       0  3825.6     .16       0  5005.1     .07       0
  5011.1     .16       0  5616.4     .05       0
#XS Ineff= 2 , 0
         4805.11  285.03
Permanent Ineff=
       F       F
Bank Sta=4918.4,5050.6
XS Rating Curve= 0 ,0
Exp/Cntr=0.3,0.1

Type RM Length L Ch R = 1 ,10625   ,519,519,519
BEGIN DESCRIPTION:
UNT094 IN BECR 13.0
END DESCRIPTION:
XS GIS Cut Line= 3
      3768899.62     10544960.18      3768399.61     10545560.19
      3768199.58     10545910.23
#Sta/Elev= 30
  4247.2  303.97  4285.2  299.53  4303.7  295.83  4375.4  285.16  4396.3  280.35
  4431.4  275.84  4595.4  271.73  4780.3  270.03  4786.8  272.31  4801.1  270.19
  4807.6  272.09  4815.4  269.73  4821.9  271.08  4829.7  269.45  4836.2  270.63
  4879.2  269.02  4893.5  266.01  4907.8  268.75  4978.1  269.19  4997.3  261.77
    5000  261.27  5003.3  261.77  5041.9  270.46  5079.3  269.78  5108.9  265.65
  5154.2  275.12    5219  284.02  5240.6  284.31  5293.1   288.9  5431.4  299.81
#Mann= 7 ,-1 , 0
  4247.2     .05       0  4285.2     .16       0  4303.7     .05       0
  4396.3     .16       0  4997.3     .07       0  5003.3     .16       0
  5293.1     .16       0
#XS Ineff= 2 , 0
         4608.86  277.33
Permanent Ineff=
       F       F
Bank Sta=4978.1,5041.9
XS Rating Curve= 0 ,0
Exp/Cntr=0.3,0.1

Type RM Length L Ch R = 1 ,10106   ,565,565,565
BEGIN DESCRIPTION:
UNT094 IN BECR 12.0
END DESCRIPTION:
XS GIS Cut Line= 3
       3768849.6     10544910.19      3768149.61     10545110.19
      3767999.62     10545860.14
#Sta/Elev= 30
  4272.9  304.66  4283.3  303.78  4345.7  292.82  4401.6  286.25  4408.1  284.55
  4469.2  275.15  4614.8  267.79    4620  268.58  4731.8  266.71  4765.6  267.66
  4969.7  268.24    4984  267.59  4990.5  266.15  4998.3  261.69  5008.1  261.56
  5010.8  261.06  5014.1  261.56  5021.3  266.13  5072.3  268.33    5266  267.58
  5357.8  269.04  5378.2     266  5398.6  268.34    5470  269.62  5589.7  275.66
  5602.6  276.45    5623  280.15  5668.6  285.76  5735.2  295.39  5765.7  298.57
#Mann= 6 ,-1 , 0
  4272.9     .16       0  4408.1     .16       0  5008.1     .07       0
  5014.1     .16       0  5589.7     .05       0  5668.6     .16       0
#XS Ineff= 2 , 0
                         5271.82          276.08
Permanent Ineff=
       F       F
Bank Sta=4969.7,5072.3
XS Rating Curve= 0 ,0
Exp/Cntr=0.3,0.1

Type RM Length L Ch R = 1 ,9541    ,567,567,567
BEGIN DESCRIPTION:
UNT094 IN BECR 11.0
END DESCRIPTION:
XS GIS Cut Line= 3
      3768599.61     10544310.19      3767799.61     10544810.19
      3766999.65      10544660.2
#Sta/Elev= 30
  4046.2  295.77  4053.9  293.21  4075.1  291.08  4081.6   287.8  4146.6  280.23
  4184.8  276.96  4285.4  273.65  4482.3  266.71  4683.6  264.59  4892.7  266.21
  4904.9  266.17  4960.7  266.59  4986.7  260.81    5007  260.68  5009.7  260.18
    5013  260.68  5015.9  264.15    5021  265.76  5073.5  266.74  5213.4  265.24
  5283.8   262.4  5288.9  264.71    5305  265.32  5498.3  265.78  5528.8   264.4
    5539  261.27  5549.2  266.41  5579.7   264.8    5690  277.57  5803.5  293.91
#Mann= 9 ,-1 , 0
  4046.2     .16       0  4146.6     .12       0  4285.4     .07       0
  4482.3     .12       0  4892.7     .07       0  4904.9     .12       0
    5007     .07       0    5013     .12       0    5690     .16       0
Bank Sta=4960.7,5073.5
XS Rating Curve= 0 ,0
Exp/Cntr=0.3,0.1

Type RM Length L Ch R = 1 ,8974    ,745,745,745
BEGIN DESCRIPTION:
UNT094 IN BECR 10.0
END DESCRIPTION:
XS GIS Cut Line= 3
      3768878.47     10543674.47      3767498.25     10544585.94
      3766526.07      10544646.7
#Sta/Elev= 30
  3500.8  317.34  3642.3  311.55  3756.6  302.06  4000.4  295.07    4154  288.85
    4160  286.42  4218.4  281.06  4298.5  274.98  4506.1  267.42  4716.9  263.01
  4877.4  264.76  4961.5  264.77  4984.8  263.91  4994.4  259.88  4997.2  259.38
  5000.4  259.88  5011.8  260.52  5020.9  264.95    5042  265.91  5203.6  263.84
  5213.6  261.48  5233.6  263.76  5343.8  265.16  5363.9  261.87  5373.9  265.88
    5444  264.45    5513  273.35  5714.6  301.65  5971.3  309.41  6128.9  308.57
#Mann= 8 ,-1 , 0
  3500.8     .16       0  4000.4     .12       0  4218.4     .07       0
  4877.4     .12       0  4994.4     .07       0  5000.4     .12       0
    5513     .16       0  5971.3     .05       0
Bank Sta=4961.5,5042
XS Rating Curve= 0 ,0
Exp/Cntr=0.3,0.1

Type RM Length L Ch R = 1 ,8229    ,1157,1157,1157
BEGIN DESCRIPTION:
UNT094 IN BECR 9.0
END DESCRIPTION:
XS GIS Cut Line= 3
      3768199.65     10543710.16      3767249.61     10544260.19
       3766899.6     10544510.19
#Sta/Elev= 30
  3870.6  301.78  3921.6  298.36  3974.6  287.72  4061.8  276.65  4119.6  268.92
  4144.6   268.2    4240  262.45  4296.1  261.57  4360.7  263.92  4409.2  260.91
  4719.8  262.38  4783.7  262.49  4837.3  262.82  4917.4  264.45  4945.3  261.18
  4954.7  263.57  4960.5  260.63  4965.5  264.07  4971.4  264.07  4990.5  262.21
  4993.6  258.51  4996.4  258.01  4999.6  258.51  5017.5  261.07  5026.1   265.7
  5079.9   267.5  5168.7  270.22  5219.1  274.88  5334.6  293.03  5398.5  299.72
#Mann= 11 ,-1 , 0
  3870.6     .16       0  4061.8     .12       0  4144.6     .07       0
    4240     .12       0  4409.2     .07       0  4719.8     .12       0
  4783.7     .07       0  4837.3     .12       0  4993.6     .07       0
  4999.6     .12       0  5079.9     .16       0
Bank Sta=4971.4,5026.1
XS Rating Curve= 0 ,0
Exp/Cntr=0.3,0.1

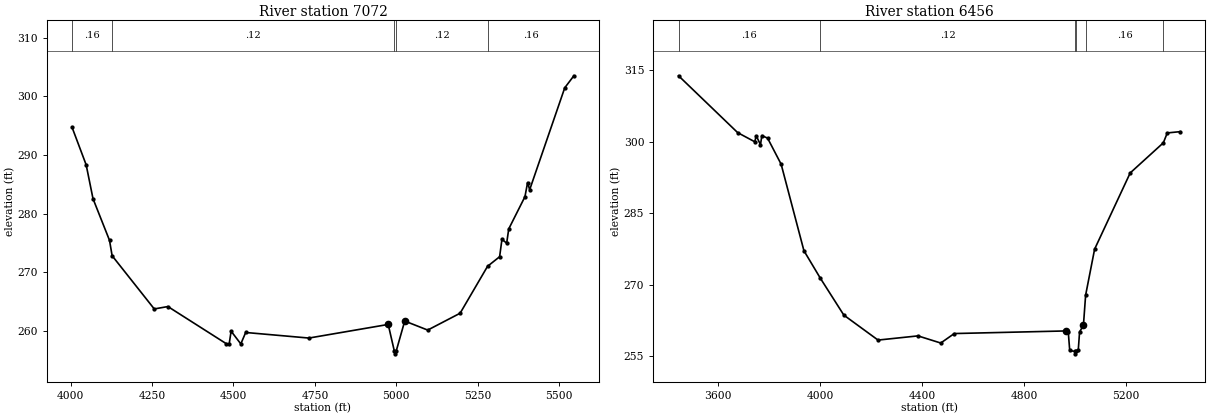
Type RM Length L Ch R = 1 ,7072    ,616,616,616
BEGIN DESCRIPTION:
UNT094 IN BECR 8.0
END DESCRIPTION:
XS GIS Cut Line= 3
       3767999.6     10542960.19      3767199.61     10543510.19
      3766749.61     10543860.18
#Sta/Elev= 30
  4004.3  294.69  4047.6   288.3  4068.6  282.53  4119.3  275.43  4127.3  272.81
  4256.7  263.74  4298.6  264.15  4477.8  257.82  4486.7  257.76  4492.7  259.95
  4522.5  257.78  4537.4  259.73  4731.6  258.78  4975.1   261.1  4993.8  256.59
  4996.6  256.09  4999.8  256.59  5025.8  261.68  5096.4  260.14  5195.9  263.01
  5280.2  271.01  5317.2  272.64  5324.4  275.61  5338.9  274.95  5345.2  277.38
    5395  282.87  5403.1  285.28  5409.5  284.06  5517.2  301.43  5545.2  303.48
#Mann= 5 ,-1 , 0
  4004.3     .16       0  4127.3     .12       0  4993.8     .07       0
  4999.8     .12       0  5280.2     .16       0
Bank Sta=4975.1,5025.8
XS Rating Curve= 0 ,0
Exp/Cntr=0.3,0.1

Type RM Length L Ch R = 1 ,6456    ,538,538,538
BEGIN DESCRIPTION:
UNT094 IN BECR 7.0
END DESCRIPTION:
XS GIS Cut Line= 3
      3768299.62     10542710.19      3766899.61     10543410.19
      3766549.58      10543610.2
#Sta/Elev= 30
  3445.2  313.84  3677.2   301.9  3744.3  299.98  3749.9  301.25  3766.6  299.37
  3772.2  301.28  3794.6  300.74  3847.7  295.27  3937.1   277.1    4001  271.37
  4093.7  263.58  4227.8  258.34  4384.4  259.22  4473.8  257.72  4526.9  259.71
  4965.7  260.26  4974.1     260  4979.7  256.17  4999.1  255.95  5001.8  255.45
  5005.1  255.95  5013.3  256.27  5018.4  260.05  5033.5  261.44  5042.1  267.77
  5077.4  277.44    5217  293.44  5346.9  299.76  5362.5  301.84  5413.6  302.11
#Mann= 6 ,-1 , 0
  3445.2     .16       0    4001     .12       0  4999.1     .07       0
  5005.1     .12       0  5042.1     .16       0  5346.9     .05       0
Bank Sta=4965.7,5033.5
XS Rating Curve= 0 ,0
Exp/Cntr=0.3,0.1