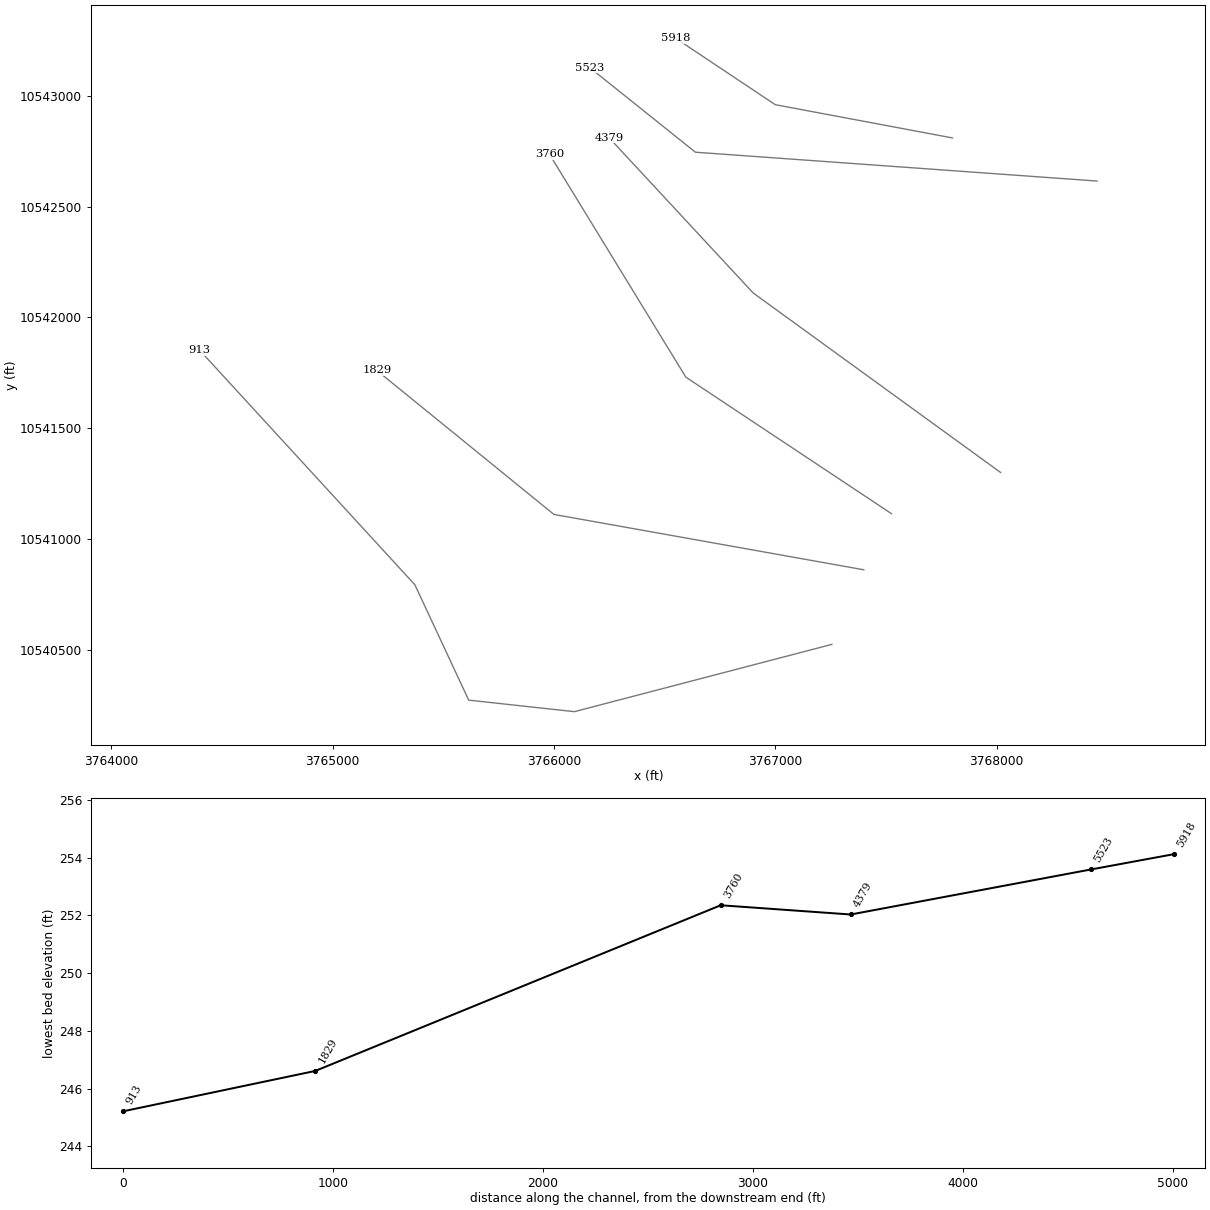
HEC-RAS study UNT094 IN BECR.prj: UNT094 IN BECR Base Level Engineering

--- UNT094 IN BECR.g01 (geometry) --- (continued)

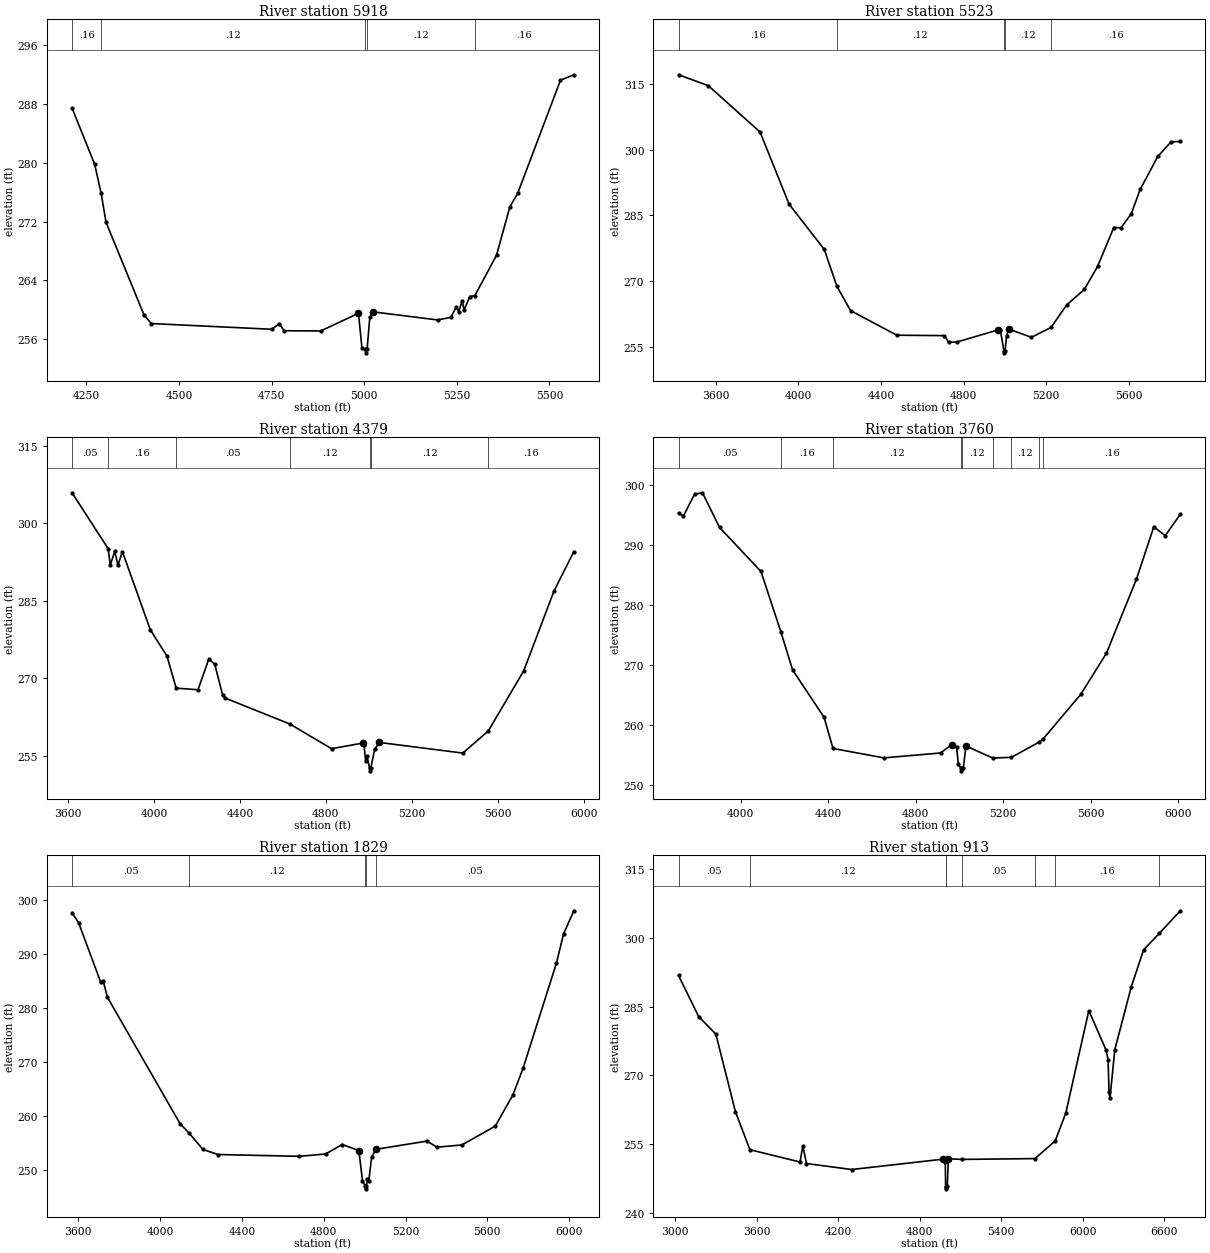
Type RM Length L Ch R = 1 ,5918    ,395,395,395
BEGIN DESCRIPTION:
UNT094 IN BECR 6.0
END DESCRIPTION:
XS GIS Cut Line= 3
      3767799.63     10542810.18      3766999.61     10542960.19
       3766549.6     10543260.19
#Sta/Elev= 30
  4211.2  287.45  4272.3  279.78  4289.7  275.85  4302.8  271.91  4405.4  259.29
  4424.9  258.11  4750.5  257.33  4770.8  258.09  4783.5  257.13  4882.7   257.1
  4984.5  259.51  4993.8   254.8  5001.8  254.62  5004.6  254.12  5007.8  254.62
    5015  258.94  5022.6  259.71  5197.9   258.6    5234  258.95    5249   260.4
    5255   259.7    5264  261.13    5270     260  5285.1  261.79  5298.7   261.9
  5357.2  267.42  5393.2     274  5414.3  275.84  5529.9  291.25    5566  291.99
#Mann= 5 ,-1 , 0
  4211.2     .16       0  4289.7     .12       0  5001.8     .07       0
  5007.8     .12       0  5298.7     .16       0
Bank Sta=4984.5,5022.6
XS Rating Curve= 0 ,0
Exp/Cntr=0.3,0.1

Type RM Length L Ch R = 1 ,5523    ,1144,1144,1144
BEGIN DESCRIPTION:
UNT094 IN BECR 5.0
END DESCRIPTION:
XS GIS Cut Line= 3
      3768453.08     10542615.46      3766638.87     10542745.67
      3766162.99     10543126.37
#Sta/Elev= 30
  3420.9  317.15  3564.7  314.67  3815.4  304.06  3955.7  287.59  4126.2  277.23
  4187.2  268.81  4253.4  263.24  4477.1  257.62  4707.7  257.52  4727.7  256.01
  4767.8  256.06  4968.3  258.85  4978.4   258.7  4995.4  254.09  4998.2  253.59
  5001.4  254.09  5008.4  257.46  5018.5  259.02  5128.8  257.14  5223.7   259.4
  5299.8  264.57  5384.6  268.07  5448.6  273.34  5527.1  282.23  5562.3  282.18
  5611.9  285.41  5655.1  290.95    5740  298.47    5804  301.81  5849.2  301.91
#Mann= 5 ,-1 , 0
  3420.9     .16       0  4187.2     .12       0  4995.4     .07       0
  5001.4     .12       0  5223.7     .16       0
Bank Sta=4968.3,5018.5
XS Rating Curve= 0 ,0
Exp/Cntr=0.3,0.1

Type RM Length L Ch R = 1 ,4379    ,619,619,619
BEGIN DESCRIPTION:
UNT094 IN BECR 4.0
END DESCRIPTION:
XS GIS Cut Line= 3
       3768017.2     10541299.68      3766899.61     10542110.19
      3766249.61     10542810.18
#Sta/Elev= 30
  3618.7   305.9  3786.6  295.07  3796.6  291.92  3817.5  294.56  3832.2  291.86
  3853.1  294.49    3983  279.35  4060.4  274.27  4103.3  268.05  4204.9  267.74
  4255.1  273.67  4282.8  272.71  4319.8  266.66  4332.4  266.11  4633.6  261.08
  4826.4  256.32    4971   257.4  4977.2  257.06  4985.7  253.88  4991.9  254.89
  5003.3  252.53  5006.1  252.03  5009.3  252.53  5027.3  256.22  5048.9  257.53
  5437.8  255.47  5556.6  259.78  5721.2  271.41  5862.4  286.91  5954.5   294.5
#Mann= 7 ,-1 , 0
  3618.7     .05       0  3786.6     .16       0  4103.3     .05       0
  4633.6     .12       0  5003.3     .07       0  5009.3     .12       0
  5556.6     .16       0
Bank Sta=4971,5048.9
XS Rating Curve= 0 ,0
Exp/Cntr=0.3,0.1

Type RM Length L Ch R = 1 ,3760    ,1931,1931,1931
BEGIN DESCRIPTION:
UNT094 IN BECR 3.0
END DESCRIPTION:
XS GIS Cut Line= 3
      3767524.26     10541113.74      3766595.47     10541730.04
       3765979.7     10542736.09
#Sta/Elev= 30
    3716   295.3  3738.1  294.81  3789.3  298.47  3825.4   298.7  3903.5  292.92
    4093  285.58  4183.8  275.53  4237.4  269.18  4381.6  261.26  4422.2  256.08
  4655.4  254.51  4913.8  255.33    4966  256.73  4987.3  256.34    4995  253.55
  5005.6  252.85  5008.4  252.35  5011.6  252.85  5018.2  252.86  5030.1   256.5
  5152.7  254.48  5238.3  254.61  5365.2  257.15  5380.9  257.58  5556.1  265.15
  5672.1  271.93  5809.5   284.3  5888.9  293.03  5941.1  291.55  6010.2  295.11
#Mann= 9 ,-1 , 0
    3716     .05       0  4183.8     .16       0  4422.2     .12       0
  5005.6     .07       0  5011.6     .12       0  5152.7     .07       0
  5238.3     .12       0  5365.2     .07       0  5380.9     .16       0
Bank Sta=4966,5030.1
XS Rating Curve= 0 ,0
Exp/Cntr=0.3,0.1

Type RM Length L Ch R = 1 ,1829    ,916,916,916
BEGIN DESCRIPTION:
UNT094 IN BECR 2.0
END DESCRIPTION:
XS GIS Cut Line= 3
      3767399.58     10540860.19      3765999.61     10541110.19
      3765199.61     10541760.19
#Sta/Elev= 30
    3570  297.63    3602  295.77  3709.6  284.83  3722.3     285  3742.7  282.02
  4098.2  258.63  4141.1  256.96  4209.9  253.88  4283.6  252.95  4680.8  252.62
  4809.3  253.05  4890.5   254.8  4971.8  253.69  4989.6  248.14  5002.7  247.11
  5005.5  246.61  5008.7  247.11  5013.7  248.47  5020.1  248.04  5034.5  252.53
  5056.2  253.92  5304.6  255.43  5354.1  254.31  5475.5  254.72  5638.6  258.19
  5724.8  263.96  5774.4  268.86  5937.4  288.28  5972.6  293.72  6022.9  297.99
#Mann= 5 ,-1 , 0
    3570     .05       0  4141.1     .12       0  5002.7     .07       0
  5008.7     .12       0  5056.2     .05       0
Bank Sta=4971.8,5056.2
XS Rating Curve= 0 ,0
Exp/Cntr=0.3,0.1

Type RM Length L Ch R = 1 ,913     ,0,0,0
BEGIN DESCRIPTION:
UNT094 IN BECR 1.0
END DESCRIPTION:
XS GIS Cut Line= 5
      3767255.19     10540523.44        3766092.     10540219.62
      3765614.57     10540271.71      3765371.51     10540792.54
      3764399.26      10541851.6
#Sta/Elev= 30
  3023.9  291.82  3172.2  282.84  3298.8     279  3443.1  262.05  3549.3  253.76
  3918.5  251.07  3939.2   254.6  3965.9  250.74  4298.9  249.43  4970.7  251.69
  4988.1  250.99  4990.6  245.71  4993.3  245.21  4996.6  245.71  5002.7  245.77
  5010.9  251.78  5112.1  251.64  5648.2  251.82    5797  255.65  5875.2  261.73
  6045.2  284.16  6172.8  275.46    6187   273.4  6193.8  266.27    6201   265.1
  6236.3  275.61  6356.6  289.24  6448.4  297.43  6564.1  301.03  6718.8  305.96
#Mann= 8 ,-1 , 0
  3023.9     .05       0  3549.3     .12       0  4990.6     .07       0
  4996.6     .12       0  5112.1     .05       0  5648.2     .12       0
    5797     .16       0  6564.1     .12       0
Bank Sta=4970.7,5010.9
XS Rating Curve= 0 ,0
Exp/Cntr=0.3,0.1

Chan Stop Cuts=-1
Use User Specified Reach Order=0
Composite Channel Slope=5