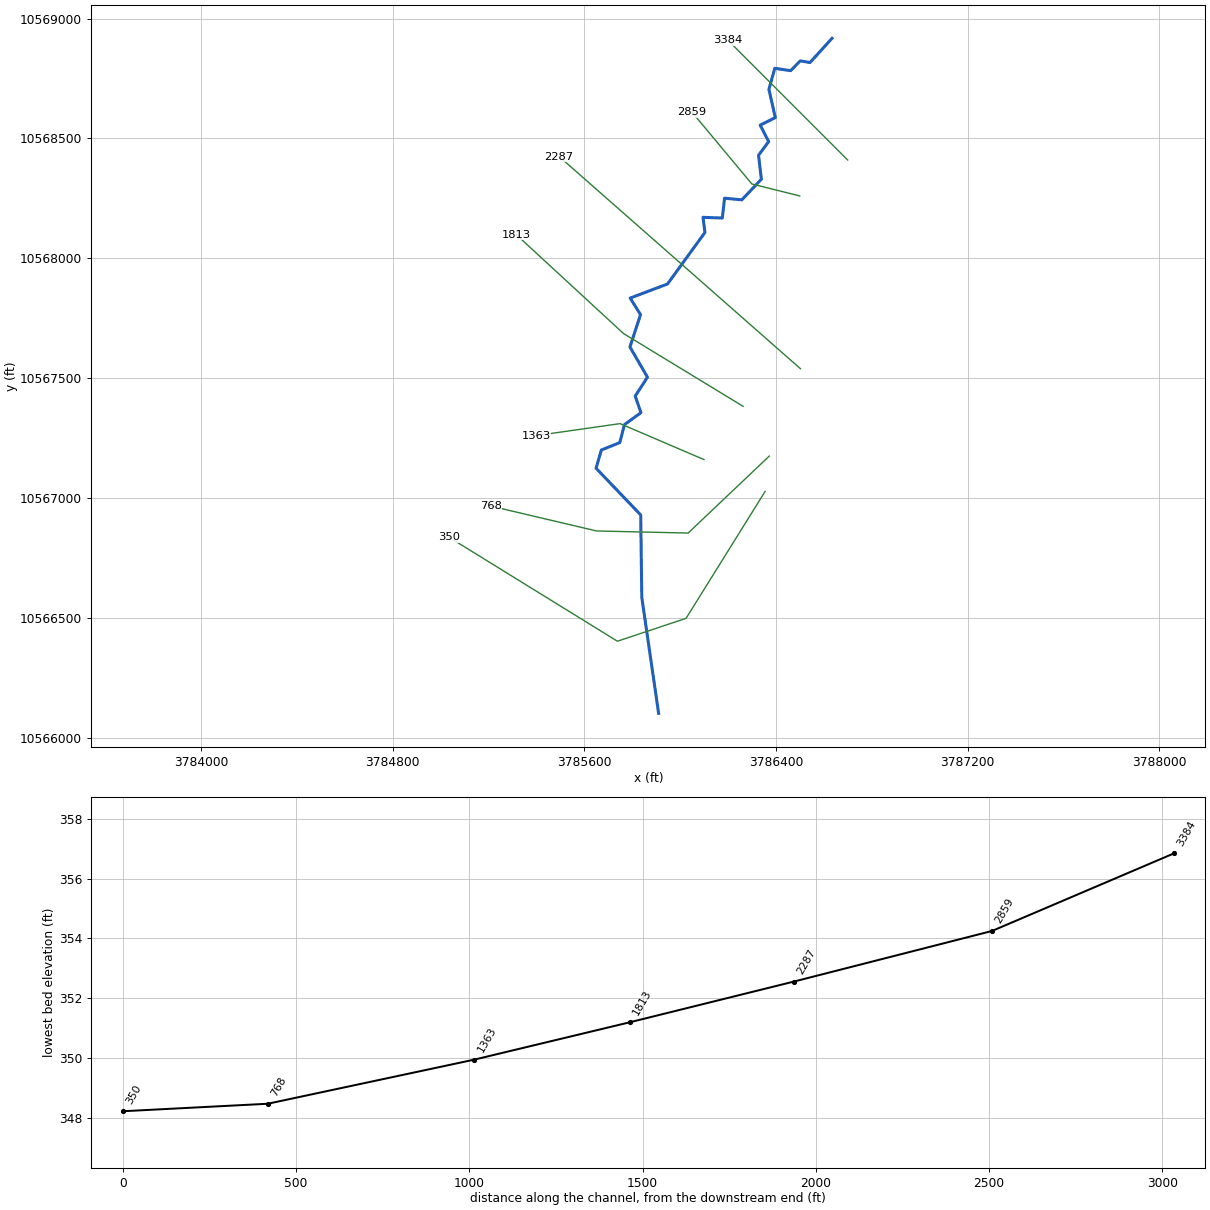
--- UNT095 IN BECR.prj (project) ---

Proj Title=UNT095 IN BECR Base Level Engineering
Current Plan=p01
Default Exp/Contr=0.3,0.1
English Units
Geom File=g01
Flow File=f01
Plan File=p01
BEGIN DESCRIPTION:
UNT095 IN BECR
END DESCRIPTION:

--- UNT095 IN BECR.p01 (plan) ---

Plan Title=Multiple Run
Short Identifier=Multiple
Geom File=g01
Flow File=f01
Subcritical Flow
K Sum by GR= 0
Std Step Tol= 0.01
Critical Tol= 0.01
Num of Std Step Trials= 20
Max Error Tol= 0.3
Flow Tol Ratio= 0.001
Split Flow NTrial= 30
Split Flow Tol= 0.02
Split Flow Ratio= 0.02
Log Output Level= 0
Friction Slope Method= 1
Unsteady Friction Slope Method= 2
Unsteady Bridges Friction Slope Method= 1
Parabolic Critical Depth
Global Vel Dist=  1 , 1 , 1
Global Log Level= 0
CheckData=True
Encroach Param= -1, 0, 0, 0
BEGIN DESCRIPTION:
Multiple Run
END DESCRIPTION:

--- UNT095 IN BECR.f01 (steady flow) ---

Flow Title=Multiple
Number of Profiles=7
Profile Names=10-year,25-year,50-year,1pct_min,100-year,1pct_plu,500-year
River Rch & RM= UNT095 IN BECR,Reach-1,3384
     616     833    1013     906    1225    1656    1795
Boundary for River Rch & Prof#=UNT095 IN BECR,Reach-1,1
Up Type=0
Dn Type=3
Dn Slope=0.005
Boundary for River Rch & Prof#=UNT095 IN BECR,Reach-1,2
Up Type=0
Dn Type=3
Dn Slope=0.005
Boundary for River Rch & Prof#=UNT095 IN BECR,Reach-1,3
Up Type=0
Dn Type=3
Dn Slope=0.005
Boundary for River Rch & Prof#=UNT095 IN BECR,Reach-1,4
Up Type=0
Dn Type=3
Dn Slope=0.005
Boundary for River Rch & Prof#=UNT095 IN BECR,Reach-1,5
Up Type=0
Dn Type=3
Dn Slope=0.005
Boundary for River Rch & Prof#=UNT095 IN BECR,Reach-1,6
Up Type=0
Dn Type=3
Dn Slope=0.005
Boundary for River Rch & Prof#=UNT095 IN BECR,Reach-1,7
Up Type=0
Dn Type=3
Dn Slope=0.005

--- UNT095 IN BECR.g01 (geometry) ---

Geom Title=Existing Conditions

River Reach=UNT095 IN BECR,Reach-1
Reach XY= 30
      3786634.00     10568917.99      3786542.25     10568817.00
      3786501.75     10568824.00      3786461.25     10568783.00
      3786395.25     10568793.00      3786370.75     10568705.00
      3786397.50     10568587.00      3786334.25     10568556.00
      3786369.75     10568487.00      3786327.50     10568430.00
      3786339.25     10568330.00      3786257.75     10568244.00
      3786185.75     10568251.00      3786176.25     10568168.00
      3786095.75     10568171.00      3786103.75     10568108.00
      3785947.75     10567893.00      3785791.75     10567834.00
      3785835.00     10567765.00      3785790.75     10567630.00
      3785864.00     10567504.00      3785812.75     10567425.00
      3785836.75     10567356.00      3785768.00     10567306.00
      3785748.50     10567231.00      3785671.50     10567200.00
      3785649.50     10567124.00      3785835.75     10566929.00
      3785840.25     10566585.00      3785910.50     10566101.00

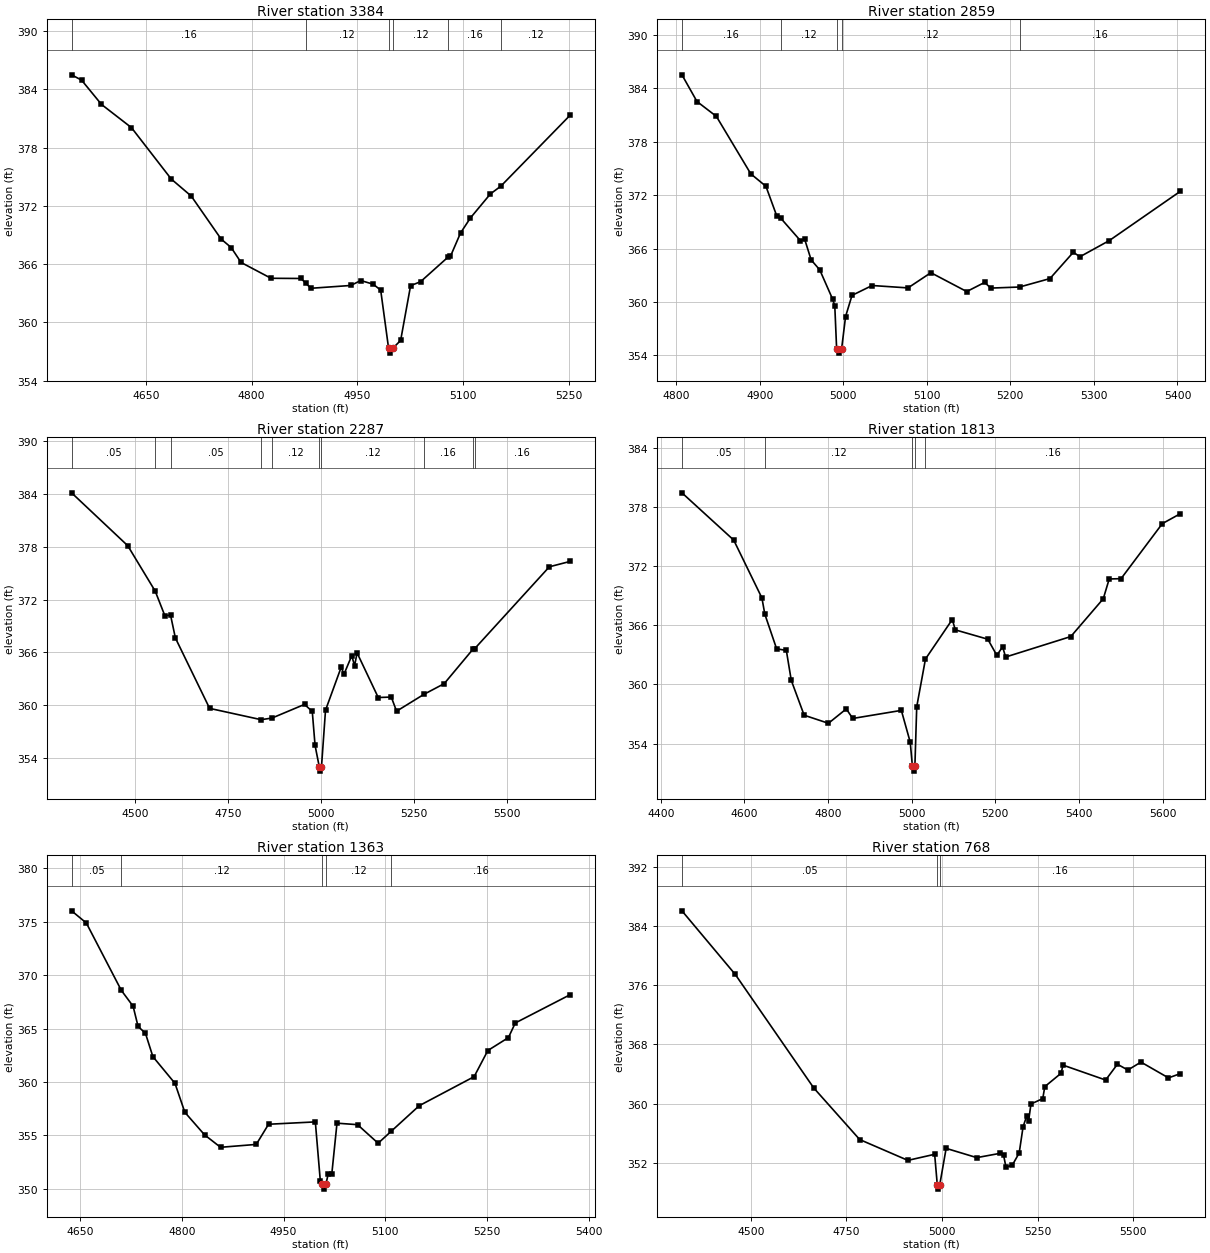
Type RM Length L Ch R = 1,3384,525,525,525
BEGIN DESCRIPTION:
UNT095 IN BECR 6.0
END DESCRIPTION:
XS GIS Cut Line= 3
      3786699.62     10568410.18      3786399.61     10568710.19
      3786199.62     10568910.18
#Sta/Elev= 30
  4544.7  385.51  4558.9  384.96  4587.1  382.46  4629.6  380.07  4686.1  374.77
  4714.4  373.02  4756.8  368.59  4771.0  367.72  4785.1  366.18  4827.6  364.55
  4870.0  364.53  4876.9  364.04  4884.1  363.52  4940.7  363.81  4954.8  364.32
  4972.5  363.94  4983.1  363.33  4994.3  357.34  4997.0  356.84  5000.3  357.34
  5011.4  358.15  5025.5  363.79  5039.7  364.20  5078.6  366.73  5082.1  366.82
  5096.3  369.21  5110.4  370.77  5138.7  373.24  5153.5  374.04  5251.8  381.35
#Mann=6,-1,0
  4544.7    0.16       0  4876.9    0.12       0  4994.3    0.07       0
  5000.3    0.12       0  5078.6    0.16       0  5153.5    0.12       0
Bank Sta=4994.3,5000.3
Exp/Cntr=0.3,0.1

Type RM Length L Ch R = 1,2859,572,572,572
BEGIN DESCRIPTION:
UNT095 IN BECR 5.0
END DESCRIPTION:
XS GIS Cut Line= 3
      3786499.57     10568260.20      3786299.61     10568310.19
      3786049.63     10568610.17
#Sta/Elev= 30
  4807.0  385.53  4825.0  382.53  4848.2  380.86  4889.4  374.40  4907.5  373.00
  4920.3  369.71  4925.3  369.41  4948.7  366.90  4953.8  367.07  4961.6  364.73
  4971.9  363.61  4987.3  360.32  4989.9  359.57  4992.1  354.75  4994.8  354.25
  4998.1  354.75  5002.8  358.36  5010.5  360.74  5034.6  361.85  5077.5  361.58
  5104.9  363.29  5147.8  361.17  5169.3  362.20  5176.5  361.56  5211.0  361.68
  5247.4  362.63  5275.4  365.59  5283.2  365.08  5318.4  366.90  5403.6  372.45
#Mann=5,-1,0
  4807.0    0.16       0  4925.3    0.12       0  4992.1    0.07       0
  4998.1    0.12       0  5211.0    0.16       0
Bank Sta=4992.1,4998.1
Exp/Cntr=0.3,0.1

Type RM Length L Ch R = 1,2287,474,474,474
BEGIN DESCRIPTION:
UNT095 IN BECR 4.0
END DESCRIPTION:
XS GIS Cut Line= 2
      3786502.41     10567539.29      3785495.51     10568424.67
#Sta/Elev= 30
  4329.9  384.09  4480.9  378.10  4554.8  372.95  4580.6  370.18  4596.1  370.23
  4609.0  367.65  4701.1  359.67  4839.5  358.39  4868.7  358.57  4956.3  360.12
  4977.2  359.32  4984.7  355.47  4996.0  353.06  4998.7  352.56  5002.0  353.06
  5012.8  359.46  5055.0  364.34  5062.5  363.54  5083.4  365.64  5091.0  364.49
  5097.7  365.96  5154.6  360.90  5189.7  360.95  5203.9  359.35  5277.5  361.26
  5332.0  362.47  5408.9  366.35  5413.7  366.42  5614.8  375.71  5670.7  376.32
#Mann=10,-1,0
  4329.9    0.05       0  4554.8    0.16       0  4596.1    0.05       0
  4839.5    0.16       0  4868.7    0.12       0  4996.0    0.07       0
  5002.0    0.12       0  5277.5    0.16       0  5408.9    0.12       0
  5413.7    0.16       0
Bank Sta=4996,5002
Exp/Cntr=0.3,0.1

Type RM Length L Ch R = 1,1813,450,450,450
BEGIN DESCRIPTION:
UNT095 IN BECR 3.0
END DESCRIPTION:
XS GIS Cut Line= 3
      3786263.00     10567382.41      3785763.84     10567686.24
      3785316.81     10568098.56
#Sta/Elev= 30
  4450.5  379.47  4574.3  374.67  4641.8  368.79  4648.7  367.15  4676.9  363.63
  4700.2  363.46  4712.0  360.42  4742.8  356.88  4800.9  356.06  4843.6  357.52
  4859.0  356.55  4975.3  357.37  4996.6  354.13  5001.7  351.70  5004.4  351.20
  5007.7  351.70  5012.1  357.74  5033.0  362.59  5097.1  366.60  5104.4  365.55
  5182.1  364.60  5203.7  362.96  5217.5  363.83  5224.7  362.79  5380.6  364.87
  5458.3  368.71  5472.5  370.72  5500.8  370.75  5599.5  376.34  5643.0  377.36
#Mann=5,-1,0
  4450.5    0.05       0  4648.7    0.12       0  5001.7    0.07       0
  5007.7    0.12       0  5033.0    0.16       0
Bank Sta=5001.7,5007.7
Exp/Cntr=0.3,0.1

Type RM Length L Ch R = 1,1363,595,595,595
BEGIN DESCRIPTION:
UNT095 IN BECR 2.0
END DESCRIPTION:
XS GIS Cut Line= 3
      3786099.59     10567160.19      3785749.61     10567310.19
      3785399.64     10567260.19
#Sta/Elev= 30
  4637.8  376.03  4659.5  374.89  4711.0  368.58  4728.4  367.09  4735.7  365.20
  4746.6  364.55  4757.5  362.37  4790.1  359.86  4804.6  357.15  4833.6  355.04
  4857.2  353.87  4909.8  354.14  4927.9  356.03  4996.8  356.25  5004.1  350.75
  5006.5  350.45  5009.3  349.95  5012.5  350.45  5015.9  351.40  5021.1  351.40
  5028.7  356.13  5059.0  355.99  5089.3  354.25  5108.7  355.38  5149.9  357.77
  5230.7  360.49  5250.9  362.94  5281.2  364.15  5291.3  365.52  5372.1  368.17
#Mann=5,-1,0
  4637.8    0.05       0  4711.0    0.12       0  5006.5    0.07       0
  5012.5    0.12       0  5108.7    0.16       0
Bank Sta=5006.5,5012.5
Exp/Cntr=0.3,0.1

Type RM Length L Ch R = 1,768,418,418,418
BEGIN DESCRIPTION:
Mapping XS 0e8a47a5
END DESCRIPTION:
XS GIS Cut Line= 4
      3786372.18     10567174.65      3786033.68     10566853.51
      3785651.73     10566862.19      3785209.07     10566966.34
#Sta/Elev= 30
  4320.0  386.03  4459.5  377.44  4664.6  362.13  4784.7  355.17  4910.7  352.36
  4980.7  353.18  4987.7  348.98  4990.5  348.48  4993.7  348.98  5010.7  353.98
  5090.8  352.73  5150.8  353.30  5160.8  353.09  5167.2  351.42  5184.0  351.74
  5201.7  353.36  5211.9  356.90  5221.2  358.32  5226.4  357.72  5232.5  359.97
  5263.3  360.69  5268.7  362.31  5311.1  364.11  5316.3  365.21  5427.7  363.20
  5458.5  365.33  5485.8  364.55  5520.1  365.62  5592.0  363.49  5623.4  364.07
#Mann=3,-1,0
  4320.0    0.05       0  4987.7    0.07       0  4993.7    0.16       0
Bank Sta=4987.7,4993.7
Exp/Cntr=0.3,0.1

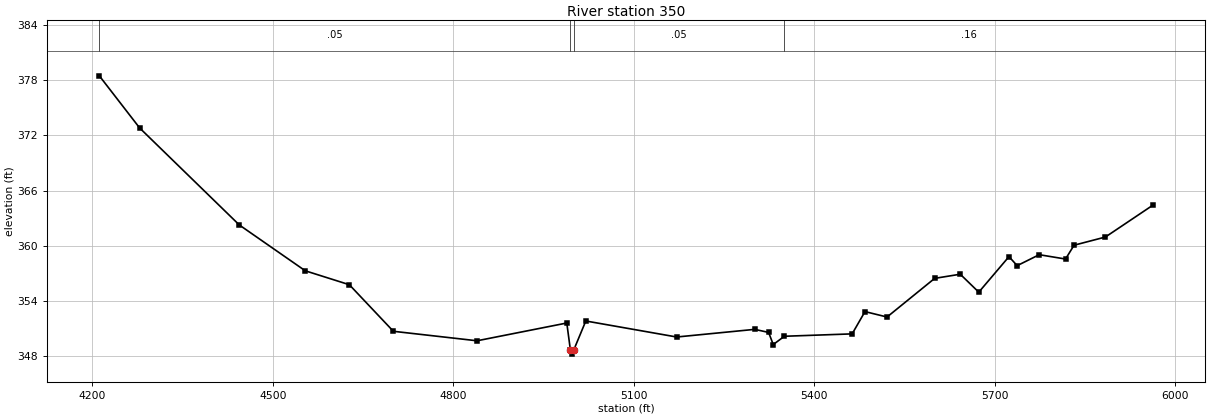
Type RM Length L Ch R = 1,350,0,0,0
BEGIN DESCRIPTION:
UNT095 IN BECR 1.0
END DESCRIPTION:
XS GIS Cut Line= 4
      3786354.87     10567027.13      3786025.00     10566497.60
      3785738.54     10566402.12      3785036.20     10566835.66
#Sta/Elev= 30
  4211.6  378.46  4278.7  372.79  4444.3  362.26  4554.0  357.28  4627.2  355.77
  4700.4  350.71  4839.5  349.68  4988.7  351.61  4994.6  348.73  4997.4  348.23
  5000.6  348.73  5020.3  351.83  5171.4  350.09  5301.1  350.92  5324.2  350.59
  5331.9  349.27  5350.4  350.17  5463.1  350.43  5484.4  352.85  5521.1  352.26
  5600.3  356.46  5642.8  356.91  5673.6  354.96  5723.8  358.82  5737.4  357.84
  5774.1  359.03  5817.8  358.56  5832.0  360.06  5884.1  360.95  5962.8  364.40
#Mann=4,-1,0
  4211.6    0.05       0  4994.6    0.03       0  5000.6    0.05       0
  5350.4    0.16       0
Bank Sta=4994.6,5000.6
Exp/Cntr=0.3,0.1

Chan Stop Cuts=-1