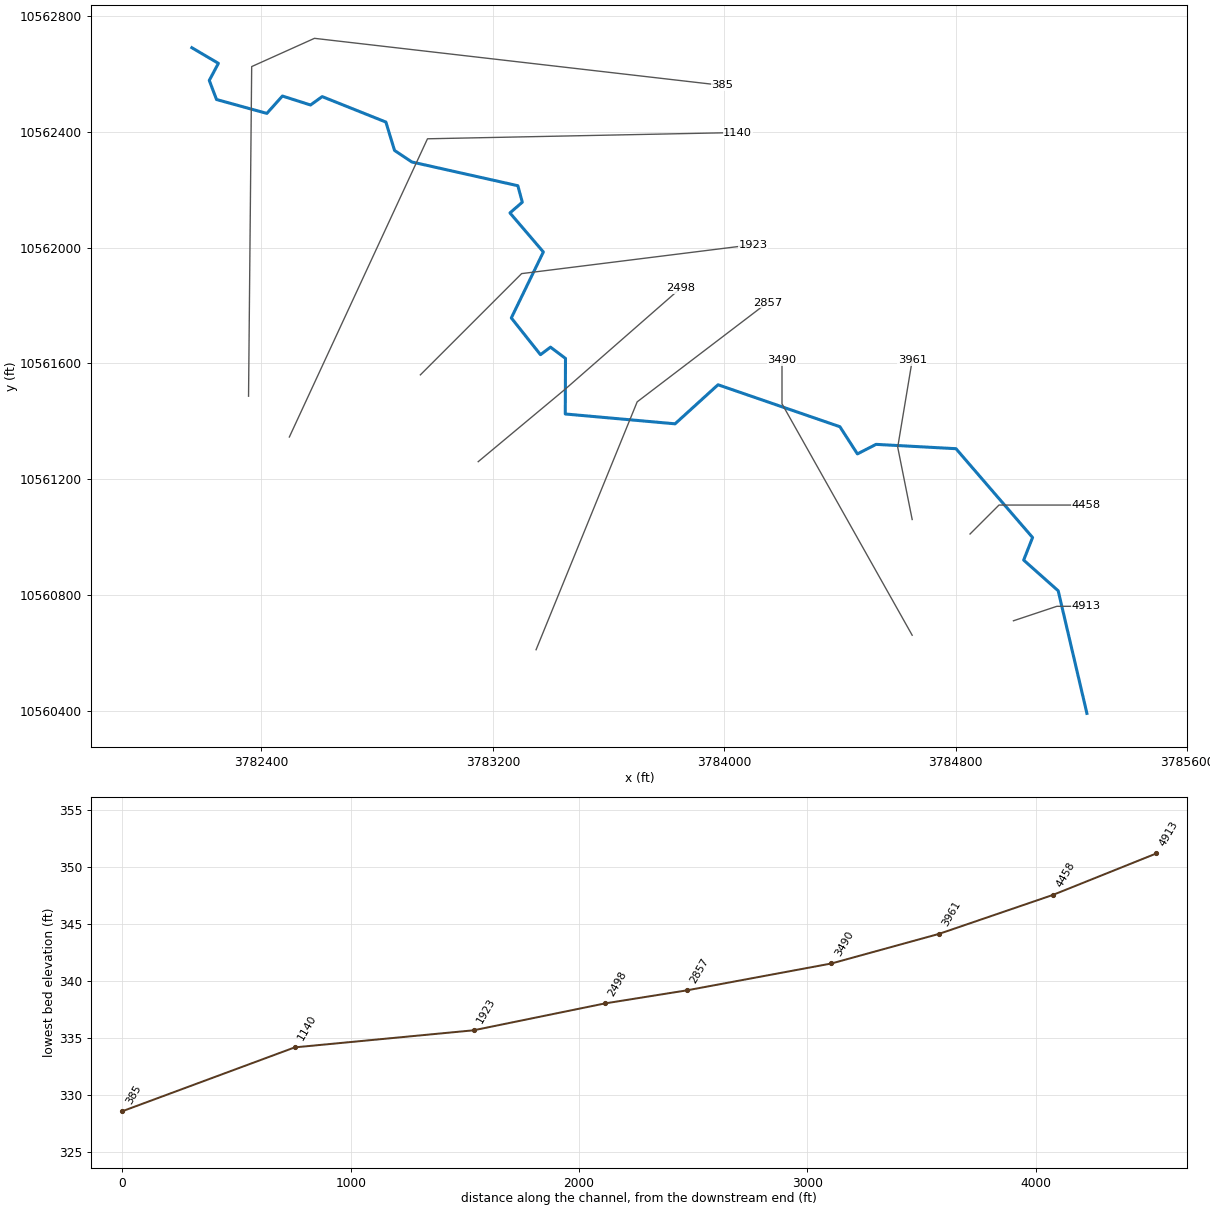
--- UNT096 IN BECR.prj (project) ---

Proj Title=UNT096 IN BECR Base Level Engineering
Current Plan=p01
Default Exp/Contr=0.3,0.1
English Units
Geom File=g01
Flow File=f01
Plan File=p01
BEGIN DESCRIPTION:
UNT096 IN BECR
END DESCRIPTION:

--- UNT096 IN BECR.p01 (plan) ---

Plan Title=Multiple Run
Short Identifier=Multiple
Geom File=g01
Flow File=f01
Subcritical Flow
K Sum by GR= 0
Std Step Tol= 0.01
Critical Tol= 0.01
Num of Std Step Trials= 20
Max Error Tol= 0.3
Flow Tol Ratio= 0.001
Split Flow NTrial= 30
Split Flow Tol= 0.02
Split Flow Ratio= 0.02
Log Output Level= 0
Friction Slope Method= 1
Unsteady Friction Slope Method= 2
Unsteady Bridges Friction Slope Method= 1
Parabolic Critical Depth
Global Vel Dist=  1 , 1 , 1
Global Log Level= 0
CheckData=True
Encroach Param= -1, 0, 0, 0
BEGIN DESCRIPTION:
Multiple Run
END DESCRIPTION:

--- UNT096 IN BECR.f01 (steady flow) ---

Flow Title=Multiple
Number of Profiles=7
Profile Names=10-year,25-year,50-year,1pct_min,100-year,1pct_plu,500-year
River Rch & RM= UNT096 IN BECR,Reach-1,4913
     620     843    1028     923    1248    1688    1845
River Rch & RM= UNT096 IN BECR,Reach-1,3490
     744    1019    1249    1125    1522    2058    2267
Boundary for River Rch & Prof#=UNT096 IN BECR,Reach-1,1
Up Type=0
Dn Type=3
Dn Slope=0.005
Boundary for River Rch & Prof#=UNT096 IN BECR,Reach-1,2
Up Type=0
Dn Type=3
Dn Slope=0.005
Boundary for River Rch & Prof#=UNT096 IN BECR,Reach-1,3
Up Type=0
Dn Type=3
Dn Slope=0.005
Boundary for River Rch & Prof#=UNT096 IN BECR,Reach-1,4
Up Type=0
Dn Type=3
Dn Slope=0.005
Boundary for River Rch & Prof#=UNT096 IN BECR,Reach-1,5
Up Type=0
Dn Type=3
Dn Slope=0.005
Boundary for River Rch & Prof#=UNT096 IN BECR,Reach-1,6
Up Type=0
Dn Type=3
Dn Slope=0.005
Boundary for River Rch & Prof#=UNT096 IN BECR,Reach-1,7
Up Type=0
Dn Type=3
Dn Slope=0.005

--- UNT096 IN BECR.g01 (geometry) ---

Geom Title=Existing Conditions

River Reach=UNT096 IN BECR,Reach-1
Reach XY= 30
      3785253.57     10560390.13      3785154.25     10560814.00
      3785035.00     10560920.00      3785065.75     10560998.00
      3784801.00     10561305.00      3784524.75     10561320.00
      3784460.25     10561287.00      3784399.75     10561381.00
      3783978.50     10561526.00      3783830.00     10561391.00
      3783450.50     10561425.00      3783451.25     10561617.00
      3783399.50     10561656.00      3783364.75     10561630.00
      3783264.00     10561757.00      3783374.75     10561985.00
      3783259.25     10562120.00      3783302.00     10562157.00
      3783286.50     10562214.00      3782920.25     10562296.00
      3782860.25     10562336.00      3782830.50     10562434.00
      3782610.25     10562522.00      3782570.00     10562493.00
      3782472.75     10562524.00      3782419.00     10562464.00
      3782245.00     10562512.00      3782220.00     10562578.00
      3782251.50     10562637.00      3782159.75     10562691.00

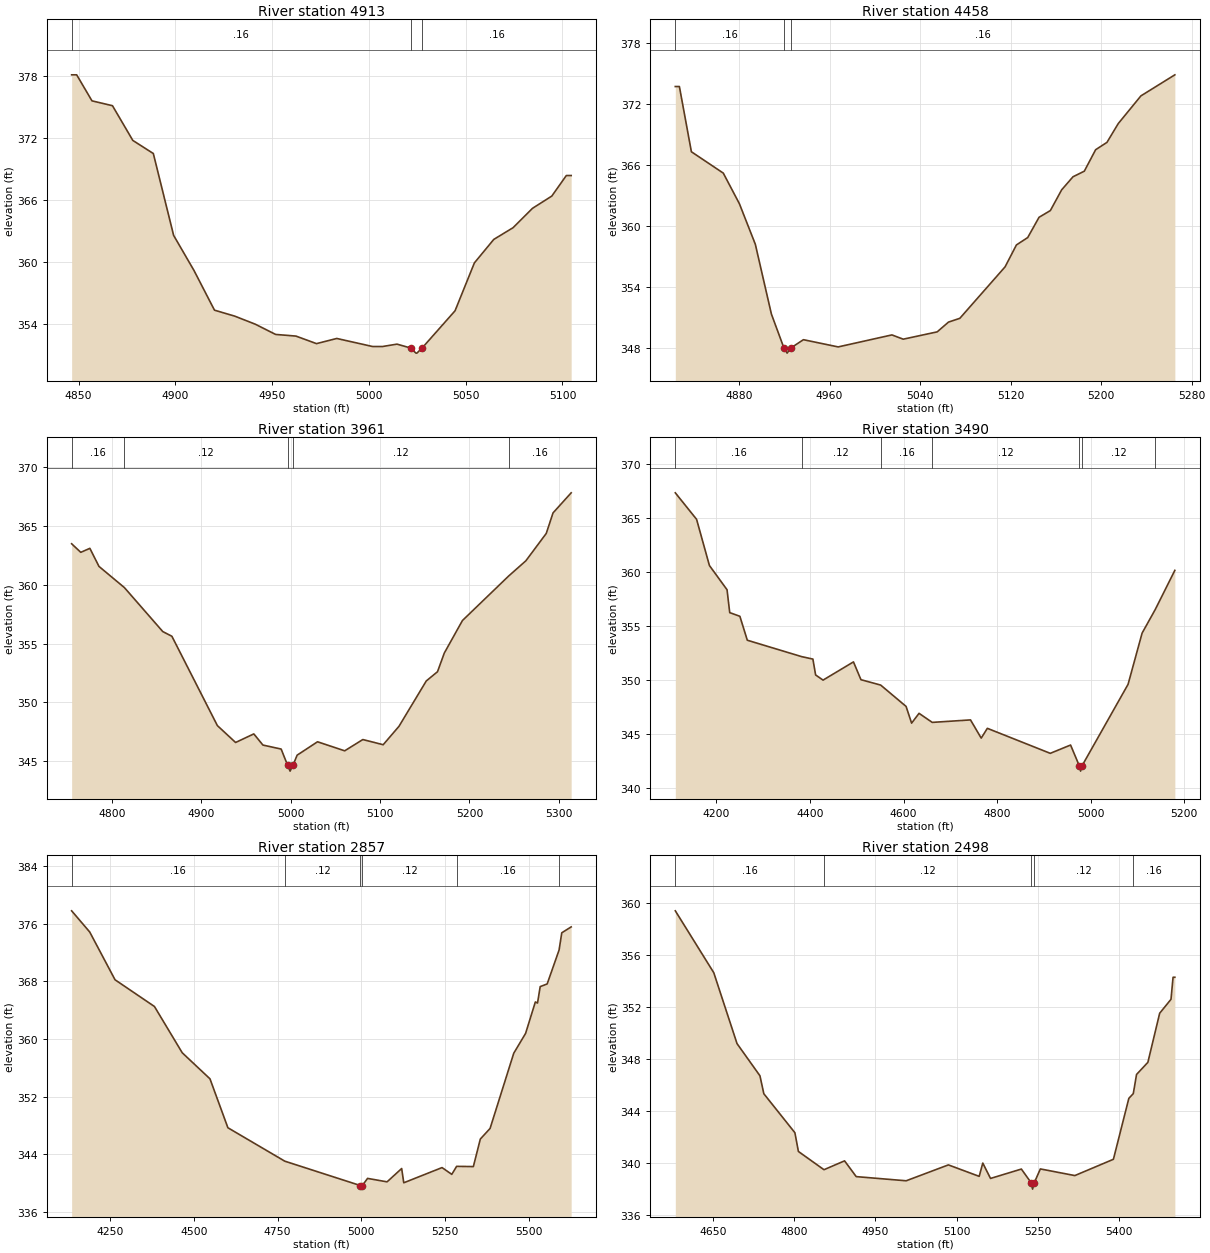
Type RM Length L Ch R = 1,4913,455,455,455
BEGIN DESCRIPTION:
UNT096 IN BECR 8.0
END DESCRIPTION:
XS GIS Cut Line= 3
      3784999.61     10560710.19      3785149.61     10560760.19
      3785249.60     10560760.19
#Sta/Elev= 30
  4846.4  378.15  4849.0  378.15  4856.9  375.63  4867.5  375.16  4878.0  371.80
  4888.6  370.53  4899.1  362.60  4909.6  359.21  4920.2  355.36  4930.7  354.78
  4941.3  354.00  4951.8  353.01  4962.3  352.85  4972.9  352.12  4983.4  352.62
  5001.9  351.84  5007.0  351.84  5014.5  352.07  5021.5  351.70  5024.3  351.20
  5024.8  351.20  5027.5  351.70  5044.5  355.30  5054.5  359.94  5064.5  362.21
  5074.5  363.35  5084.5  365.22  5094.5  366.41  5102.0  368.40  5104.5  368.40
#Mann=3,-1,0
  4846.4    0.16       0  5021.5    0.07       0  5027.5    0.16       0
Bank Sta=5021.5,5027.5
Exp/Cntr=0.3,0.1

Type RM Length L Ch R = 1,4458,497,497,497
BEGIN DESCRIPTION:
UNT096 IN BECR 7.0
END DESCRIPTION:
XS GIS Cut Line= 3
      3784849.59     10561010.17      3784949.61     10561110.19
      3785249.57     10561110.19
#Sta/Elev= 30
  4823.7  373.74  4827.3  373.74  4837.9  367.33  4866.1  365.23  4880.3  362.23
  4894.4  358.24  4908.6  351.38  4919.7  348.04  4922.5  347.54  4925.7  348.04
  4936.9  348.86  4967.6  348.15  5015.1  349.33  5025.1  348.91  5055.1  349.63
  5065.1  350.59  5075.1  350.96  5115.1  356.02  5125.1  358.17  5135.1  358.90
  5145.1  360.89  5155.1  361.55  5165.1  363.59  5175.1  364.87  5185.1  365.42
  5195.1  367.53  5205.1  368.25  5215.1  370.10  5235.1  372.82  5265.1  374.89
#Mann=3,-1,0
  4823.7    0.16       0  4919.7    0.07       0  4925.7    0.16       0
Bank Sta=4919.7,4925.7
Exp/Cntr=0.3,0.1

Type RM Length L Ch R = 1,3961,471,471,471
BEGIN DESCRIPTION:
UNT096 IN BECR 6.0
END DESCRIPTION:
XS GIS Cut Line= 3
      3784649.61     10561060.21      3784599.61     10561310.19
      3784649.61     10561610.22
#Sta/Elev= 30
  4754.8  363.50  4765.0  362.77  4775.2  363.11  4785.4  361.57  4813.8  359.77
  4856.8  356.02  4867.0  355.62  4917.9  348.01  4938.3  346.57  4958.7  347.30
  4968.9  346.35  4989.3  346.01  4996.5  344.63  4999.3  344.13  5002.5  344.63
  5007.2  345.49  5030.0  346.63  5060.4  345.86  5080.7  346.82  5103.5  346.38
  5121.2  347.95  5151.7  351.81  5164.3  352.60  5171.9  354.19  5192.2  356.96
  5243.9  360.75  5263.2  362.05  5286.0  364.38  5293.6  366.13  5313.9  367.84
#Mann=5,-1,0
  4754.8    0.16       0  4813.8    0.12       0  4996.5    0.07       0
  5002.5    0.12       0  5243.9    0.16       0
Bank Sta=4996.5,5002.5
Exp/Cntr=0.3,0.1

Type RM Length L Ch R = 1,3490,633,633,633
BEGIN DESCRIPTION:
UNT096 IN BECR 5.0
END DESCRIPTION:
XS GIS Cut Line= 3
      3784649.59     10560660.22      3784199.61     10561460.19
      3784199.61     10561610.15
#Sta/Elev= 30
  4112.1  367.34  4157.6  364.88  4185.0  360.60  4222.7  358.35  4228.4  356.23
  4250.1  355.89  4266.0  353.67  4382.0  352.15  4406.2  351.92  4412.0  350.45
  4427.9  349.97  4492.9  351.66  4508.9  350.01  4551.1  349.51  4605.4  347.53
  4617.2  345.98  4633.1  346.89  4661.3  346.05  4743.1  346.28  4766.0  344.59
  4779.1  345.50  4913.6  343.18  4957.0  343.95  4975.6  342.03  4978.4  341.53
  4981.6  342.03  5079.9  349.58  5109.9  354.33  5138.0  356.52  5179.9  360.15
#Mann=7,-1,0
  4112.1    0.16       0  4382.0    0.12       0  4551.1    0.16       0
  4661.3    0.12       0  4975.6    0.07       0  4981.6    0.12       0
  5138.0    0.16       0
Bank Sta=4975.6,4981.6
Exp/Cntr=0.3,0.1

Type RM Length L Ch R = 1,2857,359,359,359
BEGIN DESCRIPTION:
UNT096 IN BECR 4.0
END DESCRIPTION:
XS GIS Cut Line= 3
      3783349.60     10560610.16      3783699.03     10561466.93
      3784149.59     10561810.17
#Sta/Elev= 30
  4134.8  377.80  4188.8  374.86  4264.4  368.23  4382.1  364.52  4465.0  358.10
  4547.9  354.48  4601.4  347.69  4771.3  343.05  4996.8  339.67  4999.6  339.17
  5002.8  339.67  5018.5  340.66  5076.7  340.18  5120.3  342.03  5126.6  340.05
  5240.9  342.16  5270.0  341.22  5284.4  342.33  5334.4  342.30  5355.2  346.12
  5384.3  347.59  5455.0  358.03  5490.4  360.79  5519.5  365.15  5526.0  365.00
  5534.0  367.28  5554.8  367.65  5590.4  372.36  5598.4  374.75  5626.5  375.57
#Mann=6,-1,0
  4134.8    0.16       0  4771.3    0.12       0  4996.8    0.07       0
  5002.8    0.12       0  5284.4    0.16       0  5590.4    0.12       0
Bank Sta=4996.8,5002.8
Exp/Cntr=0.3,0.1

Type RM Length L Ch R = 1,2498,575,575,575
BEGIN DESCRIPTION:
UNT096 IN BECR 3.0
END DESCRIPTION:
XS GIS Cut Line= 3
      3783149.59     10561260.18      3783449.61     10561510.19
      3783849.58     10561860.16
#Sta/Elev= 30
  4580.6  359.38  4651.6  354.63  4694.5  349.19  4736.8  346.72  4744.0  345.34
  4801.3  342.35  4807.8  340.91  4855.0  339.51  4893.0  340.19  4914.5  338.98
  5006.7  338.66  5084.6  339.88  5141.5  339.00  5148.1  340.02  5162.4  338.84
  5219.3  339.56  5237.2  338.52  5240.0  338.02  5243.2  338.52  5254.4  339.57
  5318.0  339.06  5389.2  340.31  5417.7  344.99  5425.9  345.35  5431.9  346.82
  5452.8  347.75  5474.6  351.52  5495.5  352.59  5499.3  354.28  5502.6  354.28
#Mann=5,-1,0
  4580.6    0.16       0  4855.0    0.12       0  5237.2    0.07       0
  5243.2    0.12       0  5425.9    0.16       0
Bank Sta=5237.2,5243.2
Exp/Cntr=0.3,0.1

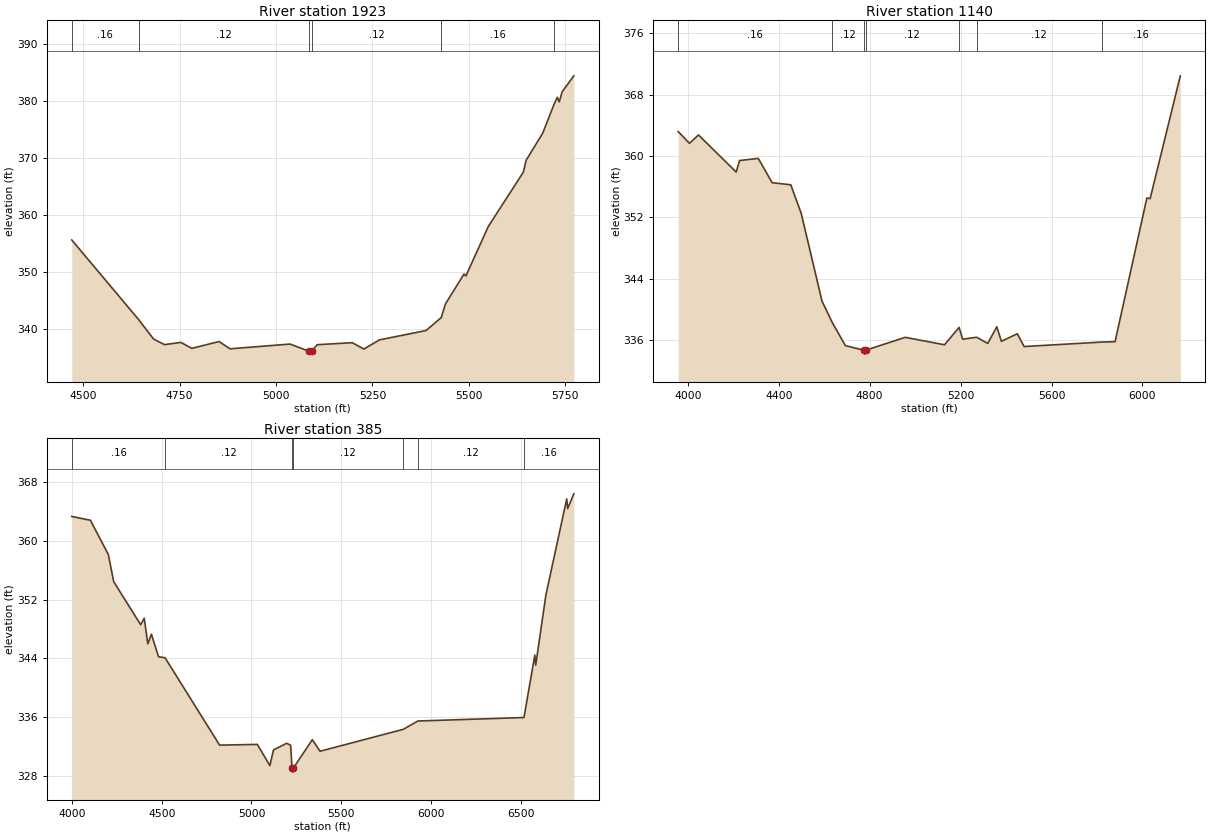
Type RM Length L Ch R = 1,1923,783,783,783
BEGIN DESCRIPTION:
UNT096 IN BECR 2.0
END DESCRIPTION:
XS GIS Cut Line= 3
      3782949.61     10561560.19      3783299.61     10561910.19
      3784099.62     10562010.19
#Sta/Elev= 30
  4470.8  355.63  4644.0  341.71  4682.9  338.29  4711.2  337.32  4753.6  337.71
  4781.9  336.67  4852.6  337.86  4880.9  336.59  5036.3  337.42  5086.2  336.16
  5089.0  335.66  5092.2  336.16  5106.9  337.31  5197.6  337.66  5227.8  336.55
  5268.1  338.15  5389.0  339.79  5428.3  342.05  5439.4  344.46  5487.3  349.67
  5492.3  349.33  5550.3  357.99  5641.0  367.48  5648.5  369.59  5691.4  374.33
  5720.7  379.36  5729.2  380.59  5734.2  379.79  5741.8  381.57  5772.0  384.35
#Mann=6,-1,0
  4470.8    0.16       0  4644.0    0.12       0  5086.2    0.07       0
  5092.2    0.12       0  5428.3    0.16       0  5720.7    0.12       0
Bank Sta=5086.2,5092.2
Exp/Cntr=0.3,0.1

Type RM Length L Ch R = 1,1140,755,755,755
BEGIN DESCRIPTION:
Mapping XS 5f0d106c
END DESCRIPTION:
XS GIS Cut Line= 3
      3782496.76     10561345.39      3782974.20     10562376.22
      3784046.55     10562397.89
#Sta/Elev= 30
  3957.9  363.19  4007.3  361.65  4046.9  362.75  4212.8  357.91  4227.7  359.41
  4310.0  359.69  4370.9  356.52  4453.0  356.25  4498.9  352.52  4590.5  341.06
  4635.7  338.27  4693.2  335.27  4775.7  334.66  4778.5  334.16  4781.7  334.66
  4956.3  336.35  5129.3  335.38  5193.1  337.64  5209.4  336.11  5270.5  336.36
  5319.4  335.56  5359.4  337.73  5379.4  335.83  5449.4  336.82  5479.4  335.15
  5820.4  335.73  5879.5  335.78  6019.5  354.53  6033.8  354.44  6166.5  370.46
#Mann=7,-1,0
  3957.9    0.16       0  4635.7    0.12       0  4775.7    0.07       0
  4781.7    0.12       0  5193.1    0.16       0  5270.5    0.12       0
  5820.4    0.16       0
Bank Sta=4775.7,4781.7
Exp/Cntr=0.3,0.1

Type RM Length L Ch R = 1,385,0,0,0
BEGIN DESCRIPTION:
UNT096 IN BECR 1.0
END DESCRIPTION:
XS GIS Cut Line= 4
      3782355.71     10561486.46      3782366.56     10562625.79
      3782583.58     10562723.44      3783994.16     10562560.68
#Sta/Elev= 30
  3998.8  363.31  4102.5  362.80  4202.5  358.14  4232.5  354.45  4382.5  348.59
  4402.5  349.48  4422.5  346.00  4442.5  347.30  4482.6  344.23  4518.4  344.10
  4822.6  332.22  5032.6  332.32  5102.6  329.44  5122.6  331.57  5196.3  332.47
  5218.3  332.21  5226.0  329.05  5228.7  328.55  5232.0  329.05  5338.9  332.96
  5382.2  331.39  5845.7  334.37  5927.4  335.50  6518.2  335.97  6578.7  344.46
  6583.7  343.10  6640.5  352.65  6756.5  365.70  6761.6  364.38  6796.1  366.39
#Mann=7,-1,0
  3998.8    0.16       0  4518.4    0.12       0  5226.0    0.07       0
  5232.0    0.12       0  5845.7    0.16       0  5927.4    0.12       0
  6518.2    0.16       0
Bank Sta=5226,5232
Exp/Cntr=0.3,0.1

Chan Stop Cuts=-1