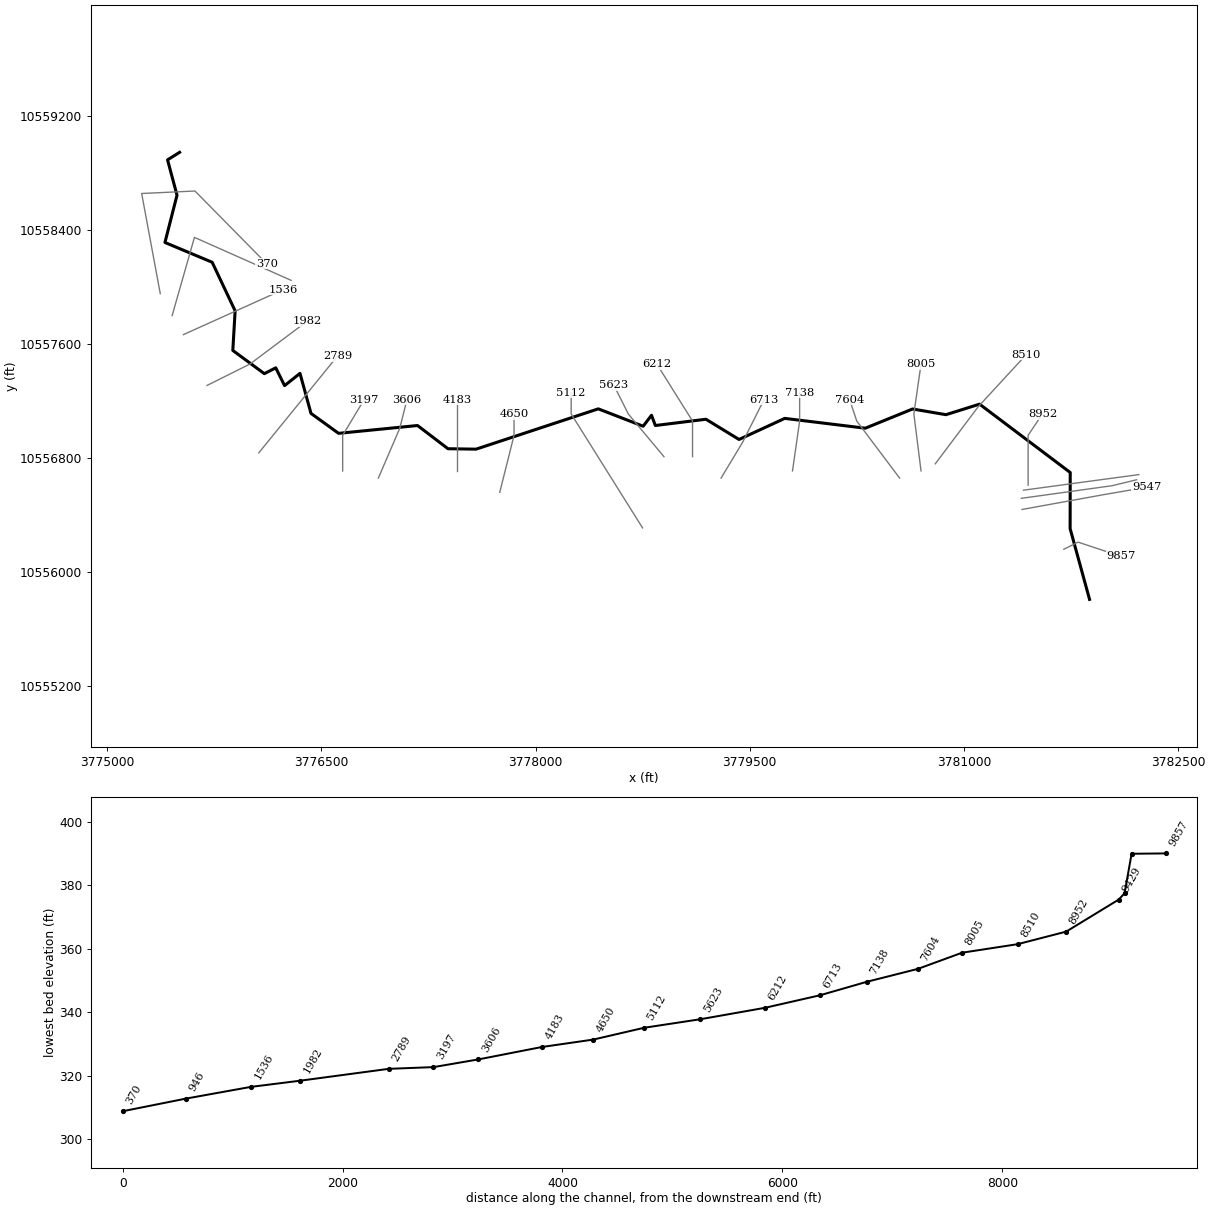
--- UNT097 IN BECR.prj (project) ---

Proj Title=UNT097 IN BECR Base Level Engineering
Current Plan=p01
Default Exp/Contr=0.3,0.1
English Units
Geom File=g01
Flow File=f01
Plan File=p01
BEGIN DESCRIPTION:
UNT097 IN BECR
END DESCRIPTION:

--- UNT097 IN BECR.p01 (plan) ---

Plan Title=Multiple Run
Short Identifier=Multiple
Geom File=g01
Flow File=f01
Subcritical Flow
K Sum by GR= 0
Std Step Tol= 0.01
Critical Tol= 0.01
Num of Std Step Trials= 20
Max Error Tol= 0.3
Flow Tol Ratio= 0.001
Split Flow NTrial= 30
Split Flow Tol= 0.02
Split Flow Ratio= 0.02
Log Output Level= 0
Friction Slope Method= 1
Unsteady Friction Slope Method= 2
Unsteady Bridges Friction Slope Method= 1
Parabolic Critical Depth
Global Vel Dist=  1 , 1 , 1
Global Log Level= 0
CheckData=True
Encroach Param= -1, 0, 0, 0
BEGIN DESCRIPTION:
Multiple Run
END DESCRIPTION:

--- UNT097 IN BECR.f01 (steady flow) ---

Flow Title=Multiple
Number of Profiles=7
Profile Names=10-year,25-year,50-year,1pct_min,100-year,1pct_plu,500-year
River Rch & RM= UNT097 IN BECR,Reach-1,9857
     542     727     878     780    1055    1427    1529
River Rch & RM= UNT097 IN BECR,Reach-1,8952
     925    1277    1573    1422    1923    2601    2886
Boundary for River Rch & Prof#=UNT097 IN BECR,Reach-1,1
Up Type=0
Dn Type=3
Dn Slope=0.005
Boundary for River Rch & Prof#=UNT097 IN BECR,Reach-1,2
Up Type=0
Dn Type=3
Dn Slope=0.005
Boundary for River Rch & Prof#=UNT097 IN BECR,Reach-1,3
Up Type=0
Dn Type=3
Dn Slope=0.005
Boundary for River Rch & Prof#=UNT097 IN BECR,Reach-1,4
Up Type=0
Dn Type=3
Dn Slope=0.005
Boundary for River Rch & Prof#=UNT097 IN BECR,Reach-1,5
Up Type=0
Dn Type=3
Dn Slope=0.005
Boundary for River Rch & Prof#=UNT097 IN BECR,Reach-1,6
Up Type=0
Dn Type=3
Dn Slope=0.005
Boundary for River Rch & Prof#=UNT097 IN BECR,Reach-1,7
Up Type=0
Dn Type=3
Dn Slope=0.005

--- UNT097 IN BECR.g01 (geometry) ---

Geom Title=Existing Conditions

River Reach=UNT097 IN BECR,Reach-1
Reach XY= 30
      3781879.83     10555808.21      3781743.75     10556305.00
      3781744.50     10556699.00      3781109.50     10557179.00
      3780874.25     10557105.00      3780640.50     10557145.00
      3780309.25     10557010.00      3779745.25     10557079.00
      3779425.25     10556931.00      3779193.50     10557073.00
      3778839.25     10557029.00      3778812.25     10557101.00
      3778754.00     10557024.00      3778439.50     10557146.00
      3777583.75     10556863.00      3777387.00     10556866.00
      3777173.75     10557029.00      3776621.00     10556974.00
      3776427.75     10557114.00      3776350.75     10557395.00
      3776242.75     10557309.00      3776181.00     10557434.00
      3776101.00     10557393.00      3775880.25     10557556.00
      3775896.50     10557834.00      3775735.75     10558175.00
      3775405.00     10558314.00      3775489.50     10558646.00
      3775423.25     10558894.00      3775507.75     10558947.00

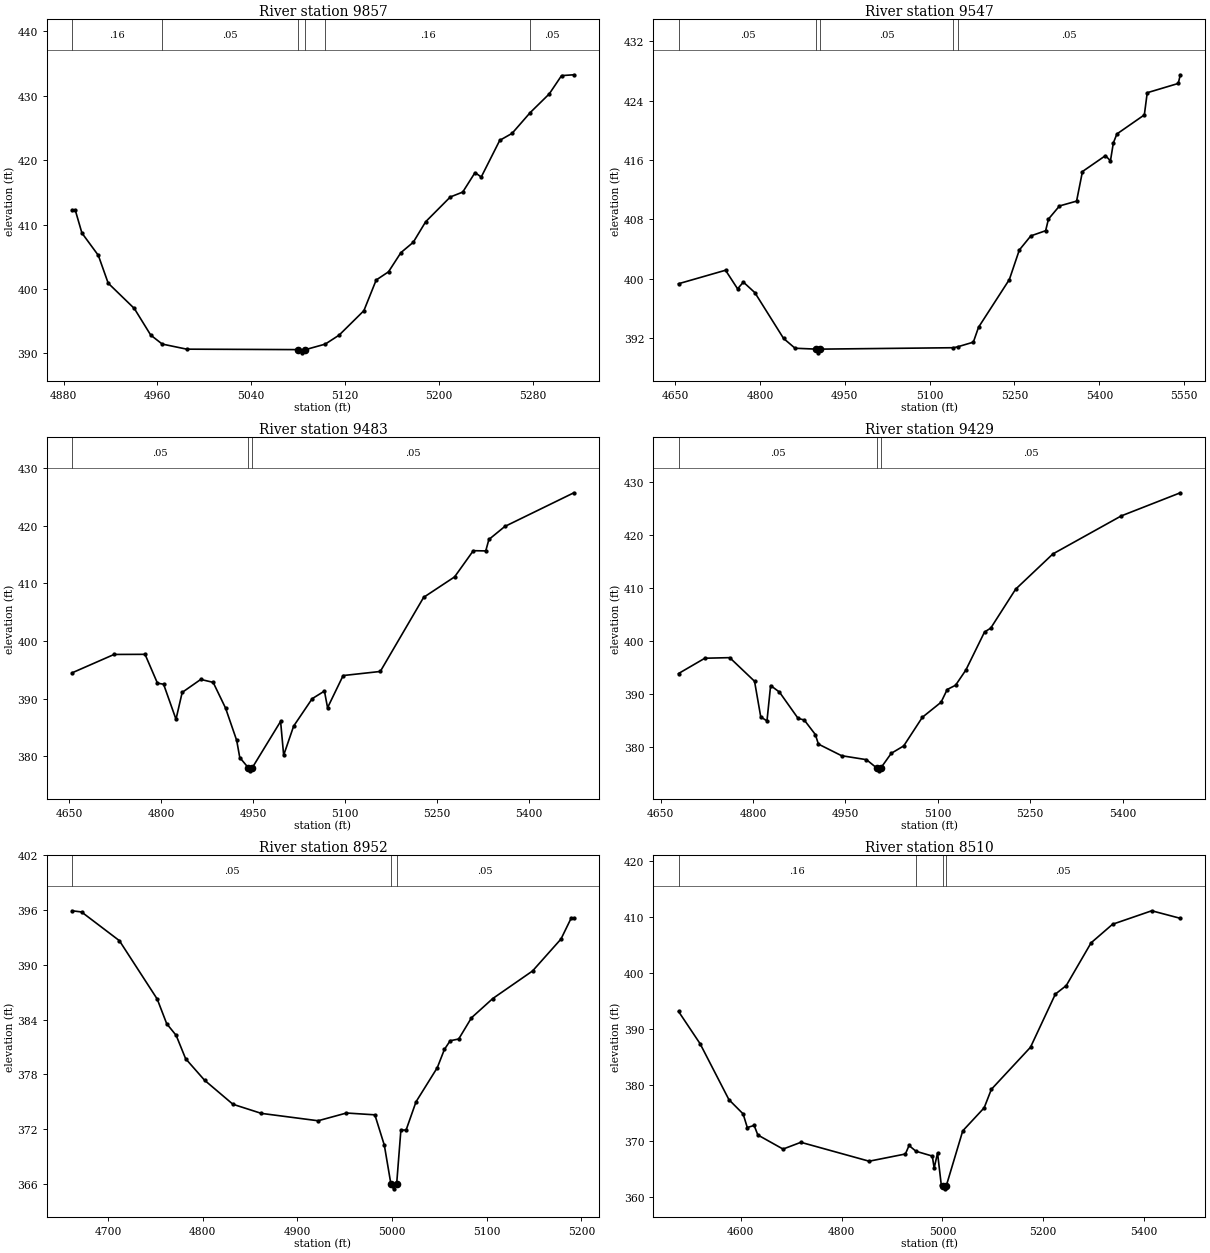
Type RM Length L Ch R = 1,9857,310,310,310
BEGIN DESCRIPTION:
UNT097 IN BECR 19.0
END DESCRIPTION:
XS GIS Cut Line= 3
      3781699.60     10556160.18      3781799.61     10556210.19
      3782099.57     10556110.20
#Sta/Elev= 30
  4887.2  412.18  4890.0  412.18  4895.6  408.68  4909.6  405.21  4918.0  400.90
  4940.3  396.97  4954.3  392.84  4964.1  391.45  4985.0  390.66  5080.3  390.59
  5083.1  390.09  5086.3  390.59  5103.1  391.44  5115.0  392.84  5136.1  396.63
  5146.6  401.39  5157.1  402.66  5167.7  405.64  5178.2  407.24  5188.8  410.43
  5209.8  414.27  5220.4  415.03  5230.9  418.05  5236.2  417.37  5252.0  423.06
  5262.5  424.14  5278.0  427.37  5294.2  430.26  5304.7  433.10  5315.2  433.23
#Mann=6,-1,0
  4887.2    0.16       0  4964.1    0.05       0  5080.3   0.033       0
  5086.3    0.05       0  5103.1    0.16       0  5278.0    0.05       0
Bank Sta=5080.3,5086.3
Exp/Cntr=0.3,0.1

Type RM Length L Ch R = 1,9547,64,64,64
BEGIN DESCRIPTION:
Mapping XS c7b0950d
END DESCRIPTION:
XS GIS Cut Line= 3
      3781406.89     10556439.58      3781979.84     10556543.76
      3782280.07     10556595.52
#Sta/Elev= 30
  4656.2  399.30  4739.3  401.12  4760.6  398.61  4770.8  399.52  4791.1  398.10
  4841.9  391.92  4862.2  390.60  4899.9  390.48  4902.6  389.98  4905.9  390.48
  5142.1  390.67  5149.9  390.80  5177.3  391.42  5186.5  393.43  5241.0  399.87
  5258.6  403.85  5278.9  405.75  5305.1  406.45  5310.1  408.02  5329.6  409.79
  5359.8  410.44  5370.2  414.43  5410.8  416.57  5419.7  415.88  5424.8  418.29
  5431.1  419.50  5479.6  422.07  5484.7  425.06  5539.5  426.31  5543.2  427.48
#Mann=5,-1,0
  4656.2    0.05       0  4899.9   0.033       0  4905.9    0.05       0
  5142.1    0.16       0  5149.9    0.05       0
Bank Sta=4899.9,4905.9
Exp/Cntr=0.3,0.1

Type RM Length L Ch R = 1,9483,54,54,54
BEGIN DESCRIPTION:
UNT097 IN BECR 18.0
END DESCRIPTION:
XS GIS Cut Line= 3
      3781401.72     10556517.71      3782037.14     10556606.26
      3782209.00     10556647.92
#Sta/Elev= 30
  4655.0  394.50  4723.5  397.69  4774.0  397.71  4794.2  392.72  4804.3  392.52
  4824.5  386.45  4834.6  391.11  4864.9  393.36  4885.1  392.85  4905.3  388.40
  4923.5  382.78  4928.5  379.82  4942.7  378.01  4945.4  377.51  4948.7  378.01
  4995.1  386.08  5000.1  380.22  5016.4  385.27  5046.6  390.02  5066.6  391.34
  5071.7  388.45  5097.1  394.03  5157.7  394.74  5228.4  407.59  5278.9  411.14
  5309.4  415.68  5329.7  415.64  5334.8  417.62  5360.8  419.88  5473.4  425.72
#Mann=3,-1,0
  4655.0    0.05       0  4942.7   0.033       0  4948.7    0.05       0
Bank Sta=4942.7,4948.7
Exp/Cntr=0.3,0.1

Type RM Length L Ch R = 1,9429,477,477,477
BEGIN DESCRIPTION:
Mapping XS 0e4d76d9
END DESCRIPTION:
XS GIS Cut Line= 2
      3781417.31     10556575.00      3782224.63     10556684.38
#Sta/Elev= 30
  4679.1  393.89  4721.8  396.78  4762.2  396.89  4802.5  392.43  4812.6  385.69
  4822.7  384.94  4828.6  391.62  4842.9  390.39  4873.2  385.42  4883.2  385.11
  4901.2  382.37  4906.2  380.56  4943.8  378.37  4984.2  377.62  5001.3  376.01
  5004.1  375.51  5007.3  376.01  5024.5  378.82  5044.7  380.22  5075.0  385.63
  5105.3  388.46  5115.3  390.87  5128.9  391.68  5145.6  394.55  5175.9  401.73
  5186.0  402.47  5226.4  409.82  5286.9  416.48  5397.9  423.66  5493.8  428.03
#Mann=3,-1,0
  4679.1    0.05       0  5001.3   0.033       0  5007.3    0.05       0
Bank Sta=5001.3,5007.3
Exp/Cntr=0.3,0.1

Type RM Length L Ch R = 1,8952,442,442,442
BEGIN DESCRIPTION:
UNT097 IN BECR 17.0
END DESCRIPTION:
XS GIS Cut Line= 3
      3781449.61     10556610.21      3781449.61     10556960.19
      3781549.63     10557110.22
#Sta/Elev= 30
  4661.8  395.93  4671.8  395.80  4711.8  392.65  4751.8  386.24  4761.8  383.54
  4771.8  382.26  4781.8  379.70  4801.8  377.34  4831.8  374.70  4861.8  373.70
  4921.8  372.89  4951.8  373.74  4981.8  373.54  4991.8  370.21  4998.8  365.92
  5001.5  365.42  5004.8  365.92  5009.3  371.87  5014.8  371.87  5025.3  374.97
  5047.8  378.72  5055.3  380.72  5061.4  381.67  5070.4  381.86  5083.9  384.19
  5106.4  386.30  5148.5  389.33  5178.5  392.83  5189.1  395.09  5192.1  395.09
#Mann=3,-1,0
  4661.8    0.05       0  4998.8    0.03       0  5004.8    0.05       0
Bank Sta=4998.8,5004.8
Exp/Cntr=0.3,0.1

Type RM Length L Ch R = 1,8510,505,505,505
BEGIN DESCRIPTION:
UNT097 IN BECR 16.0
END DESCRIPTION:
XS GIS Cut Line= 3
      3780799.63     10556760.22      3781099.61     10557160.19
      3781434.78     10557525.04
#Sta/Elev= 30
  4476.4  393.18  4519.1  387.42  4576.4  377.40  4604.5  374.86  4612.8  372.42
  4626.4  372.80  4633.7  371.09  4683.7  368.57  4719.1  369.78  4854.5  366.40
  4926.4  367.69  4933.7  369.21  4947.4  368.18  4979.8  367.32  4983.5  365.17
  4990.2  367.87  4997.6  362.16  5001.4  361.96  5004.2  361.46  5007.4  361.96
  5040.2  371.83  5082.7  375.95  5096.9  379.25  5174.6  386.78  5223.9  396.28
  5245.5  397.80  5294.8  405.45  5337.4  408.77  5415.1  411.18  5471.8  409.83
#Mann=4,-1,0
  4476.4    0.16       0  4947.4    0.05       0  5001.4    0.03       0
  5007.4    0.05       0
Bank Sta=5001.4,5007.4
Exp/Cntr=0.3,0.1

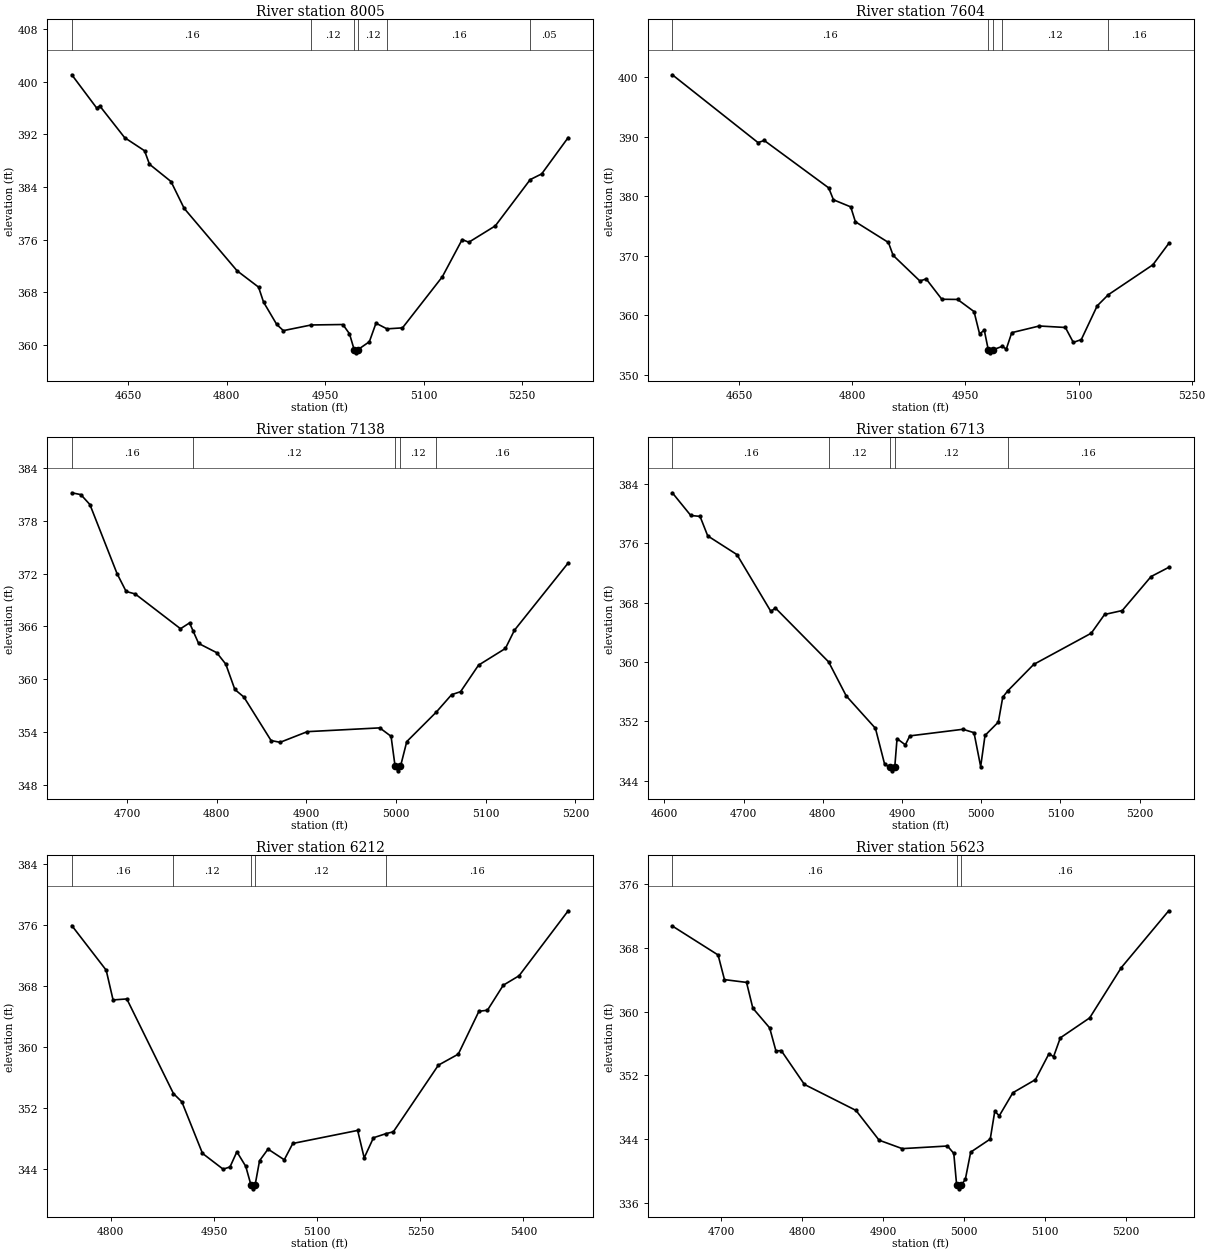
Type RM Length L Ch R = 1,8005,401,401,401
BEGIN DESCRIPTION:
UNT097 IN BECR 15.0
END DESCRIPTION:
XS GIS Cut Line= 3
      3780699.61     10556710.17      3780649.61     10557110.19
      3780699.61     10557460.21
#Sta/Elev= 30
  4563.8  401.08  4601.6  396.04  4606.6  396.32  4644.4  391.51  4674.7  389.52
  4682.2  387.47  4715.0  384.84  4735.1  380.75  4815.8  371.25  4848.5  368.77
  4856.1  366.49  4876.2  363.09  4886.3  362.15  4928.7  363.01  4977.0  363.08
  4987.1  361.67  4994.2  359.27  4997.0  358.77  5000.2  359.27  5017.4  360.46
  5027.5  363.28  5044.2  362.42  5067.9  362.57  5128.6  370.34  5158.9  376.01
  5169.0  375.60  5209.4  378.09  5262.6  385.13  5280.1  386.00  5320.5  391.53
#Mann=6,-1,0
  4563.8    0.16       0  4928.7    0.12       0  4994.2    0.07       0
  5000.2    0.12       0  5044.2    0.16       0  5262.6    0.05       0
Bank Sta=4994.2,5000.2
Exp/Cntr=0.3,0.1

Type RM Length L Ch R = 1,7604,466,466,466
BEGIN DESCRIPTION:
UNT097 IN BECR 14.0
END DESCRIPTION:
XS GIS Cut Line= 3
      3780549.62     10556660.17      3780249.61     10557060.19
      3780199.62     10557210.15
#Sta/Elev= 30
  4561.4  400.39  4675.0  389.00  4683.3  389.35  4768.7  381.39  4775.0  379.39
  4797.9  378.20  4804.1  375.70  4847.9  372.22  4854.1  370.06  4889.6  365.75
  4897.9  366.10  4918.7  362.68  4939.6  362.65  4961.4  360.61  4968.7  356.88
  4975.0  357.47  4980.3  354.18  4983.1  353.68  4986.3  354.18  4999.0  354.78
  5004.1  354.29  5011.4  357.07  5047.9  358.19  5082.5  357.94  5093.0  355.43
  5103.6  355.91  5124.7  361.58  5139.3  363.43  5198.5  368.47  5219.5  372.05
#Mann=5,-1,0
  4561.4    0.16       0  4980.3    0.07       0  4986.3    0.16       0
  4999.0    0.12       0  5139.3    0.16       0
Bank Sta=4980.3,4986.3
Exp/Cntr=0.3,0.1

Type RM Length L Ch R = 1,7138,425,425,425
BEGIN DESCRIPTION:
UNT097 IN BECR 13.0
END DESCRIPTION:
XS GIS Cut Line= 3
      3779799.61     10556710.21      3779849.61     10557060.19
      3779849.61     10557260.15
#Sta/Elev= 30
  4638.4  381.17  4648.5  380.96  4658.6  379.83  4688.9  371.98  4699.0  369.96
  4709.1  369.68  4759.6  365.73  4769.7  366.39  4773.6  365.49  4779.8  364.06
  4800.0  363.01  4810.1  361.71  4820.2  358.83  4830.3  357.97  4860.6  353.03
  4870.7  352.83  4901.0  354.04  4981.8  354.47  4994.4  353.51  4998.9  350.09
  5001.7  349.59  5004.9  350.09  5011.9  352.91  5044.8  356.26  5061.9  358.24
  5071.9  358.58  5091.9  361.59  5121.9  363.49  5131.9  365.55  5191.9  373.20
#Mann=5,-1,0
  4638.4    0.16       0  4773.6    0.12       0  4998.9    0.07       0
  5004.9    0.12       0  5044.8    0.16       0
Bank Sta=4998.9,5004.9
Exp/Cntr=0.3,0.1

Type RM Length L Ch R = 1,6713,501,501,501
BEGIN DESCRIPTION:
UNT097 IN BECR 12.0
END DESCRIPTION:
XS GIS Cut Line= 3
      3779299.62     10556660.21      3779449.61     10556910.19
      3779599.59     10557210.15
#Sta/Elev= 30
  4609.9  382.82  4633.2  379.76  4644.9  379.64  4654.6  377.01  4691.5  374.49
  4734.3  366.84  4740.1  367.29  4807.3  360.03  4829.5  355.45  4866.4  351.08
  4878.1  346.21  4884.8  345.85  4887.6  345.35  4890.8  345.85  4893.7  349.69
  4904.2  348.85  4909.8  350.06  4976.9  350.95  4990.9  350.49  4999.3  345.92
  5004.8  350.12  5021.6  351.92  5027.2  355.27  5033.5  356.13  5066.3  359.69
  5139.0  363.90  5155.8  366.42  5178.1  366.95  5214.5  371.53  5236.8  372.77
#Mann=5,-1,0
  4609.9    0.16       0  4807.3    0.12       0  4884.8    0.07       0
  4890.8    0.12       0  5033.5    0.16       0
Bank Sta=4884.8,4890.8
Exp/Cntr=0.3,0.1

Type RM Length L Ch R = 1,6212,589,589,589
BEGIN DESCRIPTION:
UNT097 IN BECR 11.0
END DESCRIPTION:
XS GIS Cut Line= 3
      3779099.61     10556810.23      3779099.61     10557060.19
      3778849.59     10557460.22
#Sta/Elev= 30
  4743.3  375.91  4793.3  370.06  4803.3  366.16  4823.3  366.29  4891.1  353.88
  4903.3  352.80  4933.3  346.04  4963.3  343.97  4973.3  344.26  4983.3  346.25
  4996.2  344.34  5003.8  341.89  5006.6  341.39  5009.8  341.89  5016.3  345.08
  5028.6  346.60  5052.2  345.20  5064.6  347.34  5158.9  349.05  5168.4  345.45
  5181.9  348.09  5199.9  348.62  5210.8  348.87  5276.3  357.61  5305.2  359.05
  5335.2  364.67  5347.6  364.81  5370.6  368.09  5393.6  369.33  5465.0  377.85
#Mann=5,-1,0
  4743.3    0.16       0  4891.1    0.12       0  5003.8    0.07       0
  5009.8    0.12       0  5199.9    0.16       0
Bank Sta=5003.8,5009.8
Exp/Cntr=0.3,0.1

Type RM Length L Ch R = 1,5623,511,511,511
BEGIN DESCRIPTION:
UNT097 IN BECR 10.0
END DESCRIPTION:
XS GIS Cut Line= 3
      3778899.62     10556810.17      3778649.61     10557110.19
      3778549.63     10557310.15
#Sta/Elev= 30
  4639.2  370.73  4695.8  367.10  4703.7  364.01  4731.0  363.66  4738.8  360.43
  4759.6  357.96  4767.4  355.06  4773.9  355.12  4802.6  350.87  4866.4  347.61
  4895.0  343.88  4923.6  342.82  4979.6  343.15  4987.4  342.22  4990.9  338.28
  4993.7  337.78  4996.9  338.28  5001.7  338.98  5008.3  342.38  5032.5  344.02
  5038.1  347.50  5043.7  346.94  5060.5  349.83  5088.4  351.47  5105.2  354.73
  5110.8  354.34  5119.2  356.71  5155.5  359.21  5194.6  365.51  5253.3  372.64
#Mann=3,-1,0
  4639.2    0.16       0  4990.9    0.07       0  4996.9    0.16       0
Bank Sta=4990.9,4996.9
Exp/Cntr=0.3,0.1

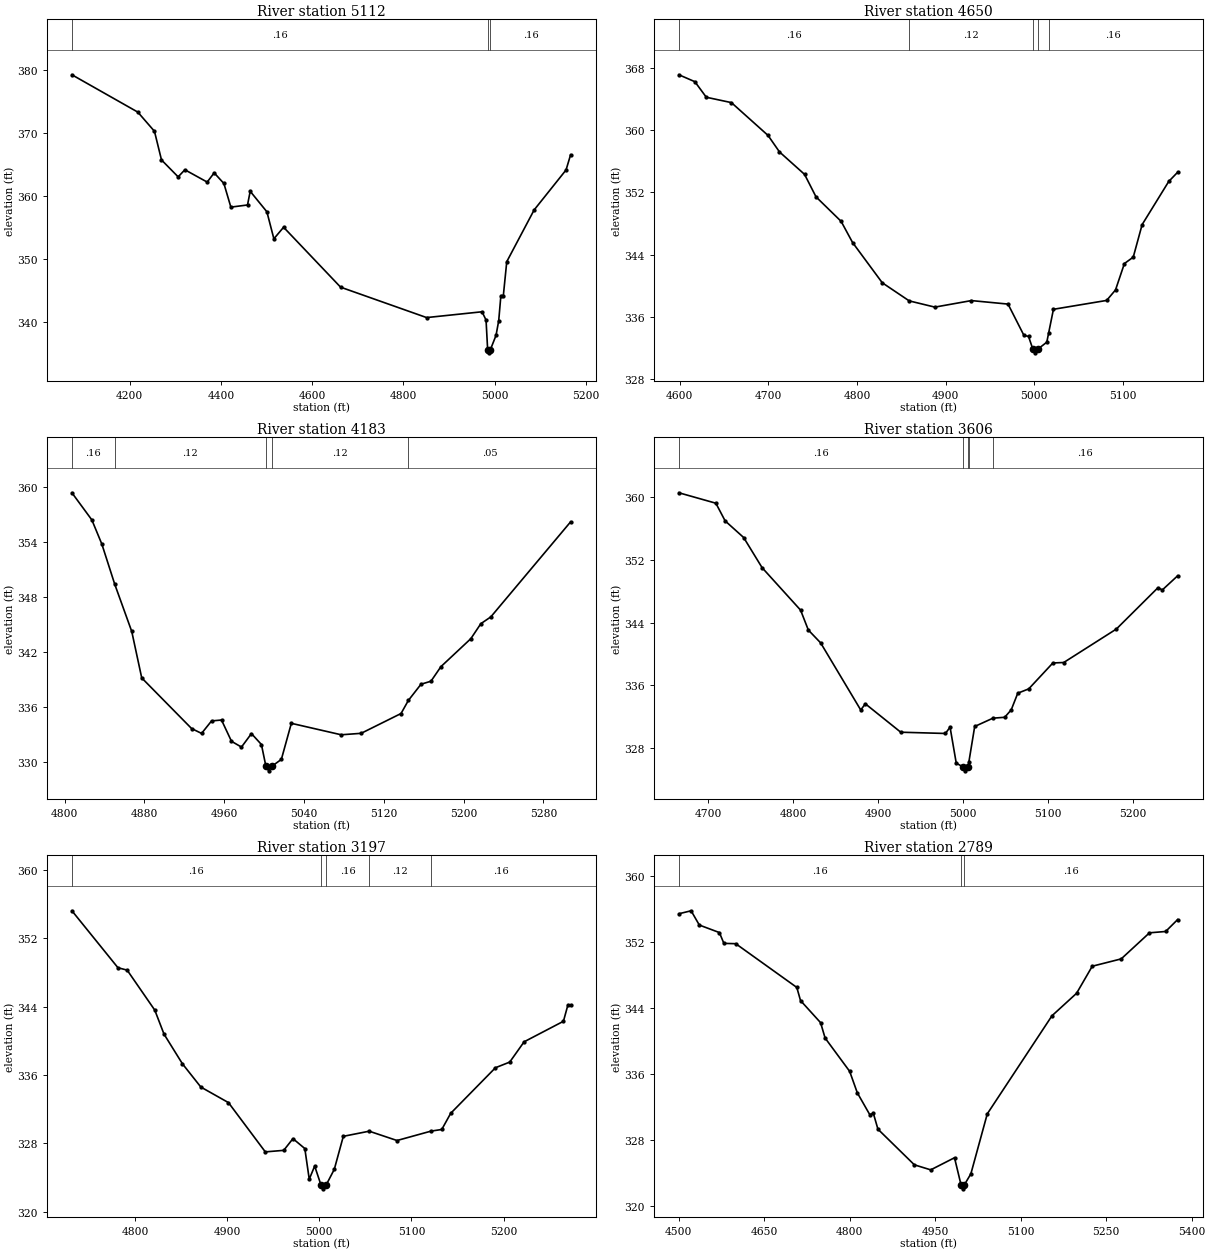
Type RM Length L Ch R = 1,5112,462,462,462
BEGIN DESCRIPTION:
UNT097 IN BECR 9.0
END DESCRIPTION:
XS GIS Cut Line= 3
      3778749.62     10556310.17      3778249.61     10557110.19
      3778249.61     10557260.17
#Sta/Elev= 30
  4073.4  379.17  4217.9  373.25  4254.4  370.21  4269.8  365.67  4306.3  362.99
  4321.1  364.11  4370.0  362.16  4385.3  363.62  4406.6  361.94  4421.9  358.19
  4458.4  358.53  4464.3  360.70  4500.9  357.45  4516.2  353.17  4537.5  355.00
  4662.5  345.50  4851.1  340.68  4972.6  341.60  4981.4  340.29  4984.9  335.59
  4987.7  335.09  4990.9  335.59  5003.3  337.86  5009.2  340.20  5013.9  344.15
  5019.3  344.15  5026.8  349.54  5086.8  357.74  5156.8  364.08  5166.8  366.49
#Mann=3,-1,0
  4073.4    0.16       0  4984.9    0.07       0  4990.9    0.16       0
Bank Sta=4984.9,4990.9
Exp/Cntr=0.3,0.1

Type RM Length L Ch R = 1,4650,467,467,467
BEGIN DESCRIPTION:
UNT097 IN BECR 8.0
END DESCRIPTION:
XS GIS Cut Line= 3
      3777749.61     10556560.21      3777849.61     10556960.19
      3777849.61     10557110.20
#Sta/Elev= 30
  4599.2  367.13  4617.2  366.24  4630.1  364.24  4658.4  363.55  4699.7  359.33
  4712.6  357.21  4740.9  354.32  4753.8  351.43  4782.1  348.28  4795.0  345.56
  4828.5  340.38  4858.9  338.05  4887.8  337.25  4929.0  338.09  4970.3  337.64
  4988.3  333.60  4993.4  333.49  4998.2  331.87  5000.9  331.37  5004.2  331.87
  5014.0  332.74  5016.0  333.87  5021.5  336.97  5081.5  338.11  5091.5  339.46
  5101.5  342.85  5111.5  343.68  5121.5  347.86  5151.5  353.41  5161.5  354.59
#Mann=5,-1,0
  4599.2    0.16       0  4858.9    0.12       0  4998.2    0.07       0
  5004.2    0.12       0  5016.0    0.16       0
Bank Sta=4998.2,5004.2
Exp/Cntr=0.3,0.1

Type RM Length L Ch R = 1,4183,577,577,577
BEGIN DESCRIPTION:
UNT097 IN BECR 7.0
END DESCRIPTION:
XS GIS Cut Line= 3
      3777449.61     10556710.18      3777449.61     10556910.19
      3777449.61     10557210.18
#Sta/Elev= 30
  4807.3  359.34  4827.3  356.38  4837.3  353.75  4850.3  349.35  4867.3  344.22
  4877.3  339.16  4927.3  333.64  4937.3  333.11  4947.3  334.47  4957.3  334.57
  4967.3  332.25  4977.3  331.62  4987.3  333.09  4997.3  331.90  5001.8  329.53
  5004.6  329.03  5007.8  329.53  5017.3  330.28  5027.3  334.21  5077.3  332.96
  5097.3  333.12  5137.3  335.28  5144.6  336.70  5157.3  338.47  5167.3  338.80
  5177.3  340.39  5207.3  343.44  5217.3  345.07  5227.3  345.81  5307.3  356.17
#Mann=5,-1,0
  4807.3    0.16       0  4850.3    0.12       0  5001.8    0.07       0
  5007.8    0.12       0  5144.6    0.05       0
Bank Sta=5001.8,5007.8
Exp/Cntr=0.3,0.1

Type RM Length L Ch R = 1,3606,409,409,409
BEGIN DESCRIPTION:
UNT097 IN BECR 6.0
END DESCRIPTION:
XS GIS Cut Line= 3
      3776899.61     10556660.19      3777049.61     10557010.19
      3777099.60     10557210.15
#Sta/Elev= 30
  4665.5  360.54  4709.0  359.21  4719.9  356.96  4741.7  354.84  4763.4  351.00
  4808.7  345.59  4817.8  343.06  4832.3  341.42  4879.5  332.87  4884.9  333.66
  4926.6  330.04  4979.2  329.88  4984.6  330.69  4991.9  326.10  4999.8  325.62
  5002.5  325.12  5005.8  325.62  5006.7  326.21  5013.6  330.77  5035.1  331.83
  5048.9  331.94  5056.6  332.89  5064.3  335.01  5077.2  335.56  5105.6  338.86
  5118.4  338.92  5180.3  343.18  5229.3  348.45  5234.4  348.16  5252.4  349.96
#Mann=5,-1,0
  4665.5    0.16       0  4999.8    0.07       0  5005.8    0.16       0
  5006.7    0.12       0  5035.1    0.16       0
Bank Sta=4999.8,5005.8
Exp/Cntr=0.3,0.1

Type RM Length L Ch R = 1,3197,408,408,408
BEGIN DESCRIPTION:
UNT097 IN BECR 5.0
END DESCRIPTION:
XS GIS Cut Line= 3
      3776649.61     10556710.22      3776649.61     10556960.19
      3776799.60     10557210.18
#Sta/Elev= 30
  4731.3  355.20  4781.3  348.54  4791.3  348.26  4821.3  343.58  4831.3  340.78
  4851.3  337.31  4871.3  334.59  4901.3  332.77  4941.3  327.01  4961.3  327.19
  4971.3  328.56  4984.2  327.40  4989.0  323.82  4994.9  325.35  5001.6  323.19
  5004.3  322.69  5007.6  323.19  5016.2  324.97  5026.0  328.83  5054.1  329.43
  5084.3  328.34  5121.3  329.44  5132.9  329.63  5142.6  331.52  5191.2  336.85
  5206.7  337.51  5222.3  339.88  5265.0  342.28  5269.9  344.20  5272.8  344.20
#Mann=5,-1,0
  4731.3    0.16       0  5001.6    0.07       0  5007.6    0.16       0
  5054.1    0.12       0  5121.3    0.16       0
Bank Sta=5001.6,5007.6
Exp/Cntr=0.3,0.1

Type RM Length L Ch R = 1,2789,807,807,807
BEGIN DESCRIPTION:
UNT097 IN BECR 4.0
END DESCRIPTION:
XS GIS Cut Line= 2
      3776062.22     10556837.17      3776613.28     10557516.46
#Sta/Elev= 30
  4500.6  355.48  4522.0  355.84  4536.4  354.11  4571.6  353.20  4579.5  351.89
  4600.3  351.85  4707.4  346.55  4713.9  344.96  4749.1  342.28  4757.0  340.42
  4800.1  336.38  4813.5  333.78  4835.3  331.14  4841.7  331.28  4849.7  329.37
  4913.6  325.05  4942.3  324.44  4984.0  325.91  4995.4  322.64  4998.1  322.14
  5001.4  322.64  5012.7  323.96  5041.5  331.23  5155.0  343.12  5198.1  345.84
  5225.6  349.12  5276.4  350.01  5326.0  353.17  5354.3  353.33  5375.3  354.77
#Mann=3,-1,0
  4500.6    0.16       0  4995.4    0.07       0  5001.4    0.16       0
Bank Sta=4995.4,5001.4
Exp/Cntr=0.3,0.1

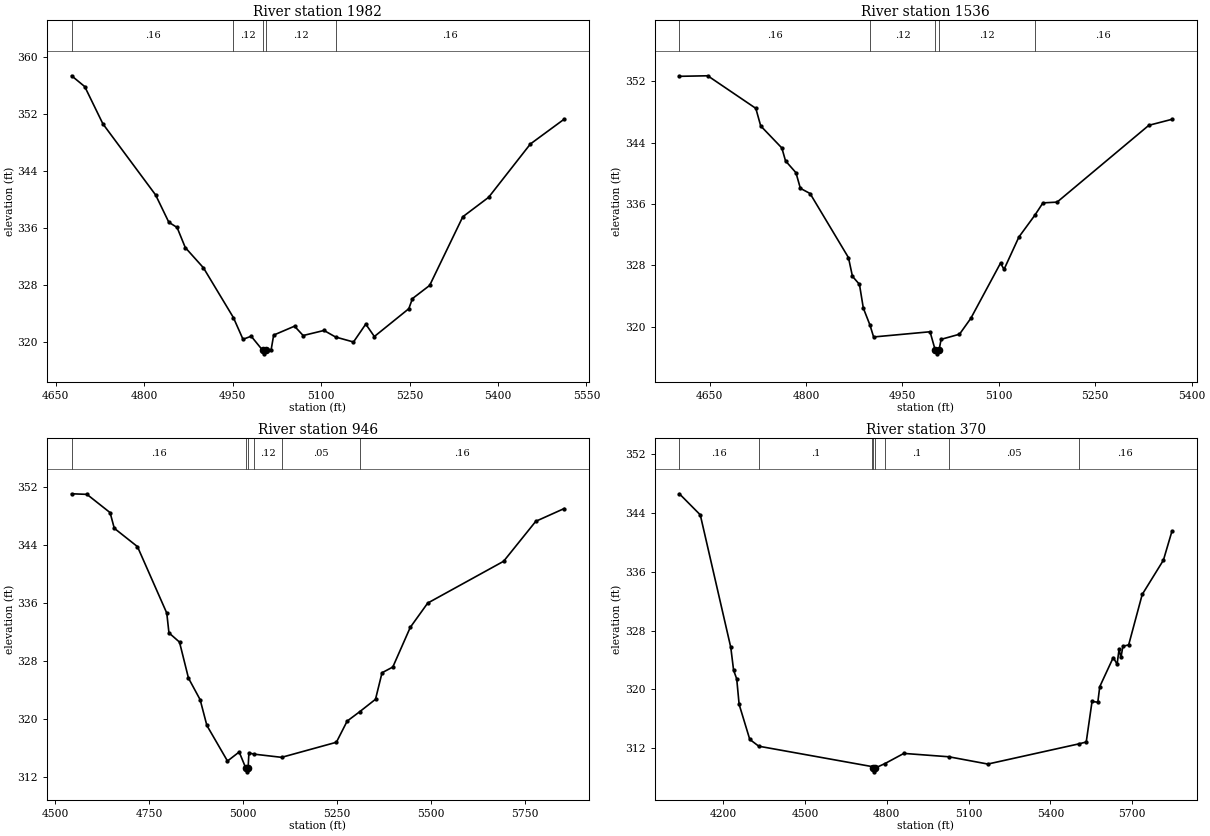
Type RM Length L Ch R = 1,1982,446,446,446
BEGIN DESCRIPTION:
UNT097 IN BECR 3.0
END DESCRIPTION:
XS GIS Cut Line= 3
      3775699.62     10557310.20      3775999.61     10557460.19
      3776399.61     10557760.19
#Sta/Elev= 30
  4676.7  357.40  4699.0  355.88  4729.8  350.65  4819.2  340.68  4841.6  336.85
  4855.6  336.12  4869.5  333.30  4900.3  330.46  4951.1  323.48  4967.4  320.43
  4981.3  320.86  5000.7  318.89  5003.5  318.39  5006.7  318.89  5015.2  318.99
  5019.4  321.02  5054.8  322.27  5069.4  320.96  5104.8  321.67  5124.4  320.75
  5154.8  320.05  5175.6  322.56  5190.2  320.82  5248.6  324.72  5254.8  326.14
  5284.0  327.99  5340.2  337.62  5384.0  340.35  5454.8  347.83  5512.1  351.31
#Mann=5,-1,0
  4676.7    0.16       0  4951.1    0.12       0  5000.7    0.07       0
  5006.7    0.12       0  5124.4    0.16       0
Bank Sta=5000.7,5006.7
Exp/Cntr=0.3,0.1

Type RM Length L Ch R = 1,1536,590,590,590
BEGIN DESCRIPTION:
UNT097 IN BECR 2.0
END DESCRIPTION:
XS GIS Cut Line= 2
      3775534.41     10557667.00      3776232.32     10557982.97
#Sta/Elev= 30
  4603.1  352.65  4647.2  352.72  4722.0  348.47  4729.6  346.18  4762.5  343.30
  4768.2  341.62  4784.4  340.08  4791.3  338.04  4806.4  337.36  4866.1  329.00
  4872.3  326.56  4883.2  325.51  4889.2  322.42  4899.6  320.19  4905.2  318.65
  4993.0  319.33  5001.0  316.95  5003.7  316.45  5007.0  316.95  5010.2  318.34
  5038.8  319.01  5056.4  321.08  5102.6  328.28  5108.1  327.47  5131.2  331.69
  5155.9  334.52  5168.6  336.14  5190.6  336.24  5333.3  346.26  5369.2  347.04
#Mann=5,-1,0
  4603.1    0.16       0  4899.6    0.12       0  5001.0    0.07       0
  5007.0    0.12       0  5155.9    0.16       0
Bank Sta=5001,5007
Exp/Cntr=0.3,0.1

Type RM Length L Ch R = 1,946,576,576,576
BEGIN DESCRIPTION:
Mapping XS 47972fec
END DESCRIPTION:
XS GIS Cut Line= 3
      3775455.38     10557800.82      3775611.62     10558349.83
      3776288.66     10558048.20
#Sta/Elev= 30
  4543.5  351.12  4584.4  351.04  4646.0  348.52  4657.2  346.36  4718.9  343.83
  4797.0  334.66  4802.8  331.93  4830.9  330.66  4854.8  325.69  4885.9  322.71
  4903.8  319.16  4958.7  314.25  4989.9  315.50  5007.6  313.26  5010.3  312.76
  5013.6  313.26  5015.8  315.37  5029.5  315.20  5102.9  314.76  5248.8  316.84
  5277.5  319.76  5311.3  321.07  5353.0  322.77  5370.4  326.43  5399.1  327.22
  5445.6  332.69  5492.0  336.04  5694.3  341.81  5779.9  347.32  5855.5  349.08
#Mann=6,-1,0
  4543.5    0.16       0  5007.6    0.07       0  5013.6    0.16       0
  5029.5    0.12       0  5102.9    0.05       0  5311.3    0.16       0
Bank Sta=5007.6,5013.6
Exp/Cntr=0.3,0.1

Type RM Length L Ch R = 1,370,0,0,0
BEGIN DESCRIPTION:
UNT097 IN BECR 1.0
END DESCRIPTION:
XS GIS Cut Line= 4
      3775372.20     10557954.83      3775242.00     10558657.91
      3775615.26     10558675.27      3776117.70     10558164.17
#Sta/Elev= 30
  4039.8  346.63  4116.4  343.76  4228.3  325.70  4238.5  322.61  4250.0  321.42
  4258.8  317.96  4297.8  313.19  4330.8  312.26  4746.8  309.48  4750.4  309.27
  4753.2  308.77  4756.4  309.27  4793.1  309.89  4862.6  311.28  5027.7  310.82
  5170.5  309.83  5503.2  312.57  5531.1  312.83  5552.4  318.35  5573.6  318.25
  5580.7  320.37  5630.1  324.33  5644.3  323.43  5651.4  325.45  5658.4  324.35
  5665.5  325.86  5686.7  326.06  5736.3  332.92  5814.0  337.59  5845.2  341.52
#Mann=8,-1,0
  4039.8    0.16       0  4330.8     0.1       0  4746.8    0.05       0
  4750.4    0.07       0  4756.4    0.05       0  4793.1     0.1       0
  5027.7    0.05       0  5503.2    0.16       0
Bank Sta=4750.4,4756.4
Exp/Cntr=0.3,0.1

Chan Stop Cuts=-1