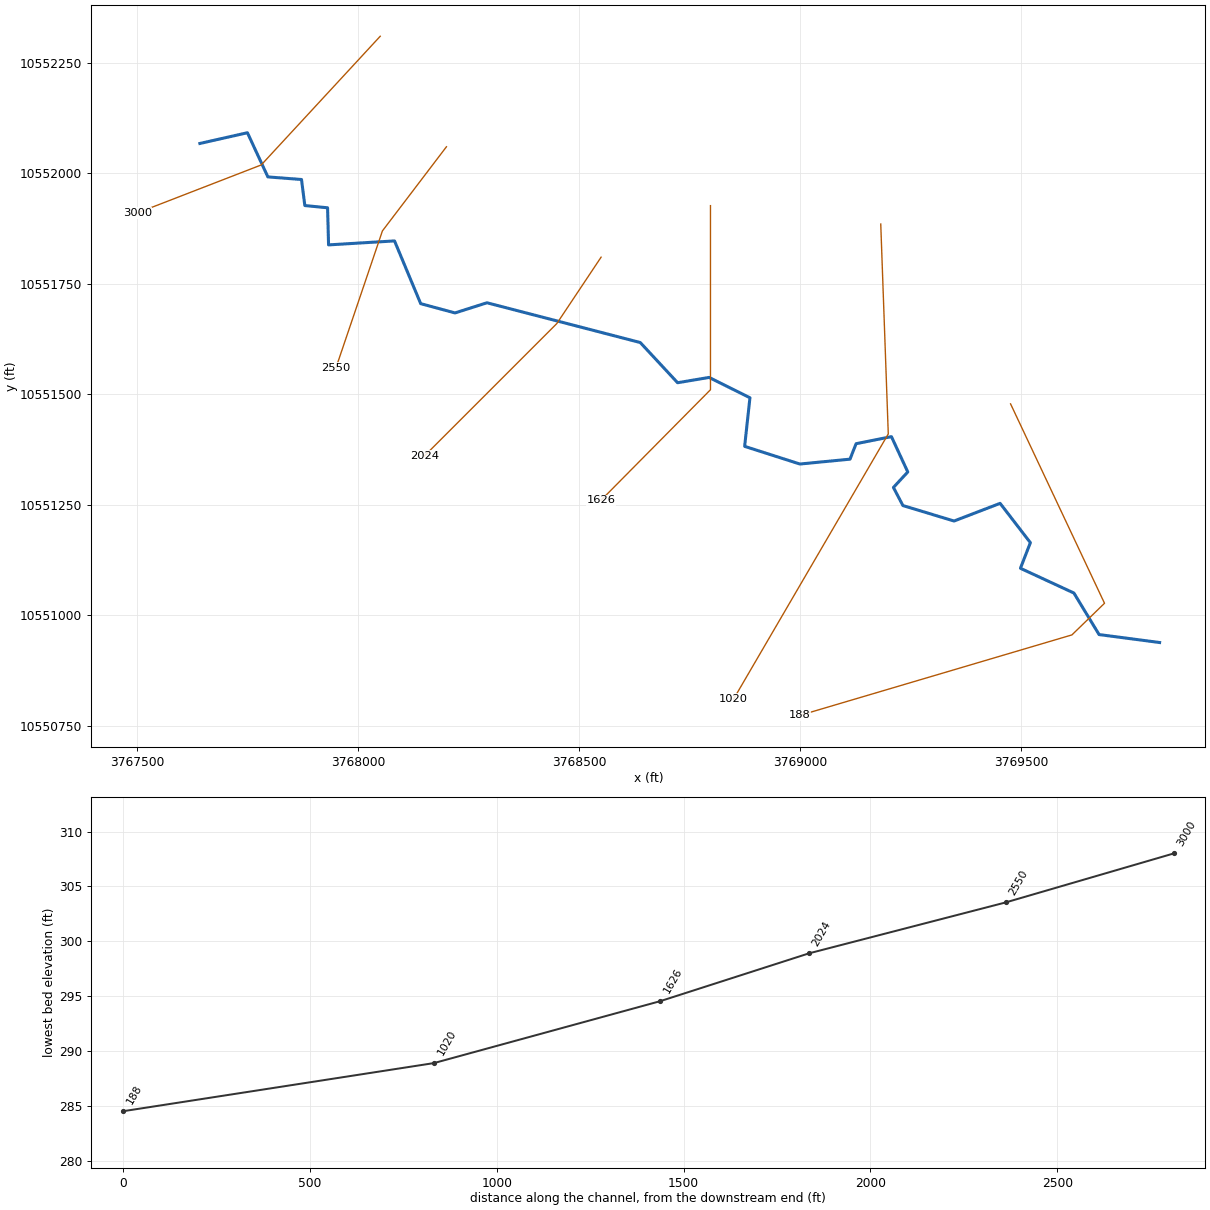
--- UNT099 IN BECR.prj (project) ---

Proj Title=UNT099 IN BECR Base Level Engineering
Current Plan=p01
Default Exp/Contr=0.3,0.1
English Units
Geom File=g01
Flow File=f01
Plan File=p01
BEGIN DESCRIPTION:
UNT099 IN BECR
END DESCRIPTION:

--- UNT099 IN BECR.p01 (plan) ---

Plan Title=Multiple Run
Short Identifier=Multiple
Geom File=g01
Flow File=f01
Subcritical Flow
K Sum by GR= 0
Std Step Tol= 0.01
Critical Tol= 0.01
Num of Std Step Trials= 20
Max Error Tol= 0.3
Flow Tol Ratio= 0.001
Split Flow NTrial= 30
Split Flow Tol= 0.02
Split Flow Ratio= 0.02
Log Output Level= 0
Friction Slope Method= 1
Unsteady Friction Slope Method= 2
Unsteady Bridges Friction Slope Method= 1
Parabolic Critical Depth
Global Vel Dist=  1 , 1 , 1
Global Log Level= 0
CheckData=True
Encroach Param= -1, 0, 0, 0
BEGIN DESCRIPTION:
Multiple Run
END DESCRIPTION:

--- UNT099 IN BECR.f01 (steady flow) ---

Flow Title=Multiple
Number of Profiles=7
Profile Names=10-year,25-year,50-year,1pct_min,100-year,1pct_plu,500-year
River Rch & RM= UNT099 IN BECR,Reach-1,3000
     475     644     786     706     955    1292    1415
Boundary for River Rch & Prof#=UNT099 IN BECR,Reach-1,1
Up Type=0
Dn Type=3
Dn Slope=0.005
Boundary for River Rch & Prof#=UNT099 IN BECR,Reach-1,2
Up Type=0
Dn Type=3
Dn Slope=0.005
Boundary for River Rch & Prof#=UNT099 IN BECR,Reach-1,3
Up Type=0
Dn Type=3
Dn Slope=0.005
Boundary for River Rch & Prof#=UNT099 IN BECR,Reach-1,4
Up Type=0
Dn Type=3
Dn Slope=0.005
Boundary for River Rch & Prof#=UNT099 IN BECR,Reach-1,5
Up Type=0
Dn Type=3
Dn Slope=0.005
Boundary for River Rch & Prof#=UNT099 IN BECR,Reach-1,6
Up Type=0
Dn Type=3
Dn Slope=0.005
Boundary for River Rch & Prof#=UNT099 IN BECR,Reach-1,7
Up Type=0
Dn Type=3
Dn Slope=0.005

--- UNT099 IN BECR.g01 (geometry) ---

Geom Title=Existing Conditions

River Reach=UNT099 IN BECR,Reach-1
Reach XY= 30
      3767641.44     10552067.55      3767749.08     10552091.86
      3767795.37     10551991.87      3767871.50     10551986.00
      3767879.00     10551927.00      3767930.50     10551922.00
      3767932.75     10551838.00      3768082.00     10551847.00
      3768141.25     10551705.00      3768219.00     10551684.00
      3768291.25     10551707.00      3768638.25     10551617.00
      3768722.75     10551526.00      3768794.00     10551538.00
      3768886.50     10551492.00      3768874.50     10551382.00
      3768999.50     10551342.00      3769113.00     10551353.00
      3769126.75     10551388.00      3769206.75     10551404.00
      3769243.75     10551324.00      3769211.25     10551289.00
      3769232.75     10551248.00      3769348.50     10551213.00
      3769452.75     10551253.00      3769521.25     10551164.00
      3769498.75     10551106.00      3769619.75     10551050.00
      3769676.75     10550956.00      3769813.75     10550938.00

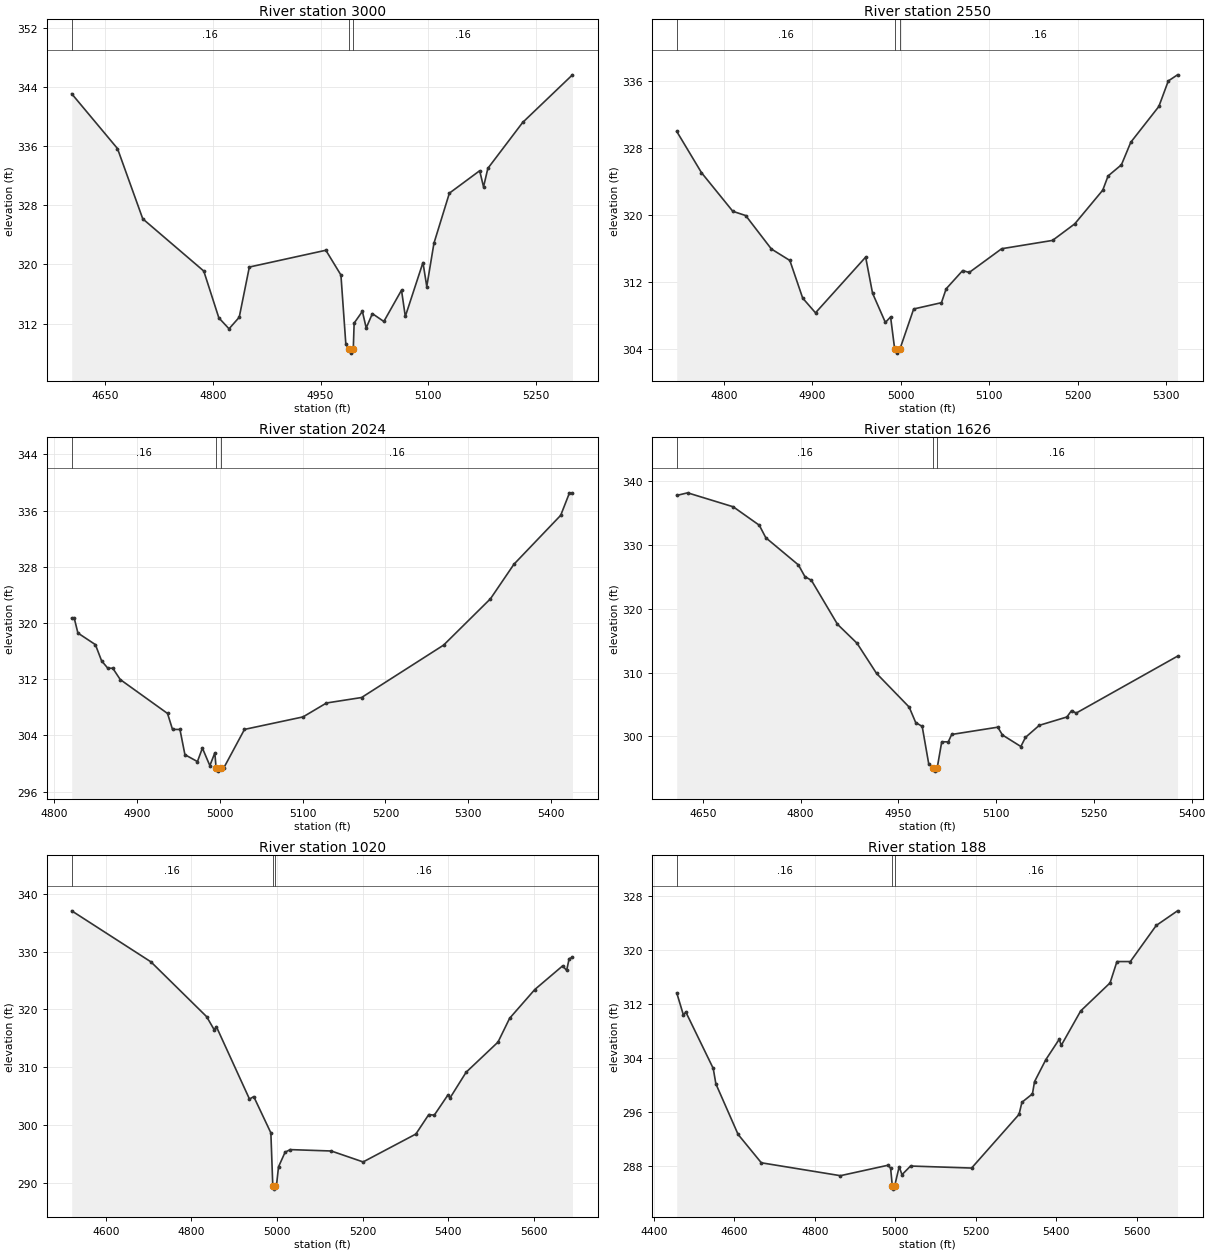
Type RM Length L Ch R = 1,3000,450,450,450
BEGIN DESCRIPTION:
UNT099 IN BECR 6.0
END DESCRIPTION:
XS GIS Cut Line= 3
      3768049.64     10552310.22      3767780.33     10552018.94
      3767499.65     10551910.21
#Sta/Elev= 30
  4603.3  343.08  4667.1  335.67  4702.3  326.17  4787.3  319.11  4808.3  312.78
  4822.5  311.30  4836.7  312.86  4850.8  319.65  4957.4  321.92  4978.4  318.57
  4985.2  309.27  4989.6  308.51  4992.3  308.01  4995.6  308.51  4996.8  312.07
  5008.3  313.66  5013.6  311.41  5022.2  313.35  5038.2  312.29  5062.8  316.52
  5068.1  312.97  5092.7  320.26  5098.0  317.01  5108.0  322.87  5129.5  329.64
  5171.7  332.67  5177.1  330.49  5183.1  332.99  5231.6  339.20  5301.0  345.64
#Mann=3,-1,0
  4603.3    0.16       0  4989.6    0.07       0  4995.6    0.16       0
Bank Sta=4989.6,4995.6
Exp/Cntr=0.3,0.1

Type RM Length L Ch R = 1,2550,526,526,526
BEGIN DESCRIPTION:
UNT099 IN BECR 5.0
END DESCRIPTION:
XS GIS Cut Line= 3
      3768199.58     10552060.15      3768054.63     10551869.64
      3767949.60     10551560.16
#Sta/Elev= 30
  4746.7  329.97  4774.7  325.05  4810.1  320.45  4824.7  319.94  4853.7  315.96
  4874.6  314.59  4889.1  310.11  4903.6  308.35  4960.3  314.99  4968.1  310.69
  4982.6  307.21  4988.5  307.86  4993.1  304.05  4995.8  303.55  4999.1  304.05
  5014.6  308.81  5046.0  309.56  5051.3  311.21  5070.0  313.39  5077.4  313.16
  5114.1  315.99  5171.6  316.98  5196.7  318.95  5228.4  322.97  5234.4  324.66
  5249.5  325.99  5260.1  328.68  5291.8  332.94  5302.5  335.98  5312.9  336.71
#Mann=3,-1,0
  4746.7    0.16       0  4993.1    0.07       0  4999.1    0.16       0
Bank Sta=4993.1,4999.1
Exp/Cntr=0.3,0.1

Type RM Length L Ch R = 1,2024,398,398,398
BEGIN DESCRIPTION:
UNT099 IN BECR 4.0
END DESCRIPTION:
XS GIS Cut Line= 3
      3768549.62     10551810.21      3768449.61     10551660.19
      3768149.59     10551360.17
#Sta/Elev= 30
  4821.2  320.72  4824.2  320.72  4828.7  318.58  4849.8  316.93  4857.3  314.62
  4864.8  313.57  4870.8  313.57  4879.8  311.96  4936.9  307.13  4942.9  304.86
  4951.9  304.85  4957.9  301.26  4973.0  300.28  4979.0  302.20  4988.0  299.70
  4994.0  301.52  4995.5  299.42  4998.2  298.92  5001.5  299.42  5005.0  299.42
  5029.8  304.86  5100.5  306.64  5128.8  308.62  5171.2  309.40  5270.2  316.86
  5326.8  323.46  5355.1  328.37  5411.6  335.34  5422.2  338.54  5425.8  338.54
#Mann=3,-1,0
  4821.2    0.16       0  4995.5    0.07       0  5001.5    0.16       0
Bank Sta=4995.5,5001.5
Exp/Cntr=0.3,0.1

Type RM Length L Ch R = 1,1626,606,606,606
BEGIN DESCRIPTION:
UNT099 IN BECR 3.0
END DESCRIPTION:
XS GIS Cut Line= 3
      3768797.16     10551926.86      3768797.16     10551510.15
      3768549.61     10551260.19
#Sta/Elev= 30
  4609.8  337.79  4626.5  338.20  4696.5  336.01  4736.5  333.12  4746.5  331.16
  4796.5  326.90  4806.5  325.07  4816.5  324.48  4856.5  317.59  4886.5  314.62
  4916.5  309.88  4966.5  304.61  4976.5  302.19  4986.5  301.58  4996.5  295.72
  5003.5  295.07  5006.2  294.57  5009.5  295.07  5016.5  299.17  5026.5  299.16
  5031.8  300.32  5102.5  301.46  5109.6  300.24  5137.9  298.43  5145.0  299.86
  5166.2  301.75  5208.6  303.06  5215.7  304.06  5222.8  303.67  5378.3  312.59
#Mann=3,-1,0
  4609.8    0.16       0  5003.5    0.07       0  5009.5    0.16       0
Bank Sta=5003.5,5009.5
Exp/Cntr=0.3,0.1

Type RM Length L Ch R = 1,1020,832,832,832
BEGIN DESCRIPTION:
UNT099 IN BECR 2.0
END DESCRIPTION:
XS GIS Cut Line= 3
      3769182.57     10551885.18      3769199.61     10551410.19
      3768849.62     10550810.21
#Sta/Elev= 30
  4520.3  337.03  4705.4  328.21  4835.5  318.74  4853.3  316.46  4858.3  317.01
  4935.6  304.50  4945.6  304.92  4985.6  298.65  4990.1  289.43  4992.8  288.93
  4996.1  289.43  4998.5  289.43  5003.5  292.79  5018.8  295.31  5030.7  295.76
  5126.7  295.52  5201.1  293.63  5324.3  298.45  5354.5  301.82  5367.3  301.71
  5398.7  305.15  5404.5  304.73  5441.7  309.13  5516.2  314.34  5543.4  318.46
  5602.2  323.43  5667.1  327.51  5676.6  326.74  5682.4  328.75  5690.2  329.00
#Mann=3,-1,0
  4520.3    0.16       0  4990.1    0.07       0  4996.1    0.16       0
Bank Sta=4990.1,4996.1
Exp/Cntr=0.3,0.1

Type RM Length L Ch R = 1,188,0,0,0
BEGIN DESCRIPTION:
UNT099 IN BECR 1.0
END DESCRIPTION:
XS GIS Cut Line= 4
      3769476.39     10551478.18      3769689.05     10551026.83
      3769615.26     10550955.21      3768998.92     10550772.92
#Sta/Elev= 30
  4457.1  313.61  4473.9  310.29  4479.5  310.79  4547.8  302.42  4554.4  300.13
  4609.6  292.65  4667.3  288.45  4863.9  286.54  4981.6  288.08  4988.6  287.68
  4992.8  285.05  4995.5  284.55  4998.8  285.05  5009.9  287.87  5016.9  286.69
  5038.2  287.97  5189.9  287.67  5307.8  295.62  5315.0  297.41  5341.1  298.65
  5346.3  300.46  5374.3  303.71  5407.6  306.73  5412.8  305.84  5461.0  310.93
  5534.0  315.08  5551.1  318.24  5584.4  318.24  5648.7  323.58  5701.6  325.75
#Mann=3,-1,0
  4457.1    0.16       0  4992.8    0.07       0  4998.8    0.16       0
Bank Sta=4992.8,4998.8
Exp/Cntr=0.3,0.1

Chan Stop Cuts=-1