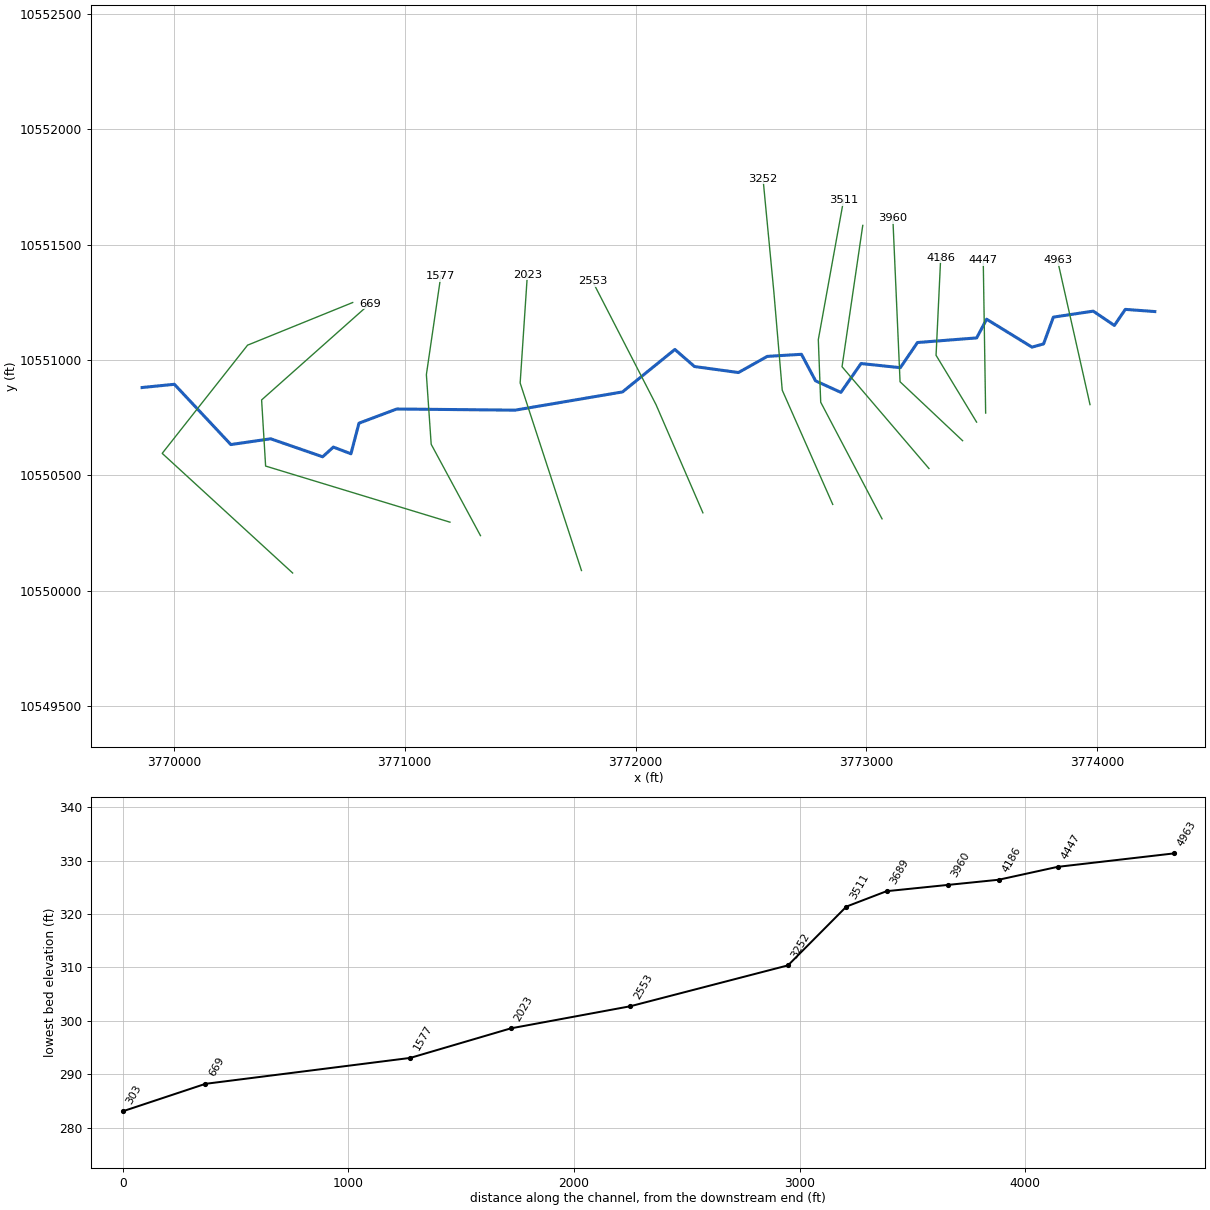
--- UNT100 IN BECR.prj (project) ---

Proj Title=UNT100 IN BECR Base Level Engineering
Current Plan=p01
Default Exp/Contr=0.3,0.1
English Units
Geom File=g01
Flow File=f01
Plan File=p01
BEGIN DESCRIPTION:
UNT100 IN BECR
END DESCRIPTION:

--- UNT100 IN BECR.p01 (plan) ---

Plan Title=Multiple Run
Short Identifier=Multiple
Geom File=g01
Flow File=f01
Subcritical Flow
K Sum by GR= 0
Std Step Tol= 0.01
Critical Tol= 0.01
Num of Std Step Trials= 20
Max Error Tol= 0.3
Flow Tol Ratio= 0.001
Split Flow NTrial= 30
Split Flow Tol= 0.02
Split Flow Ratio= 0.02
Log Output Level= 0
Friction Slope Method= 1
Unsteady Friction Slope Method= 2
Unsteady Bridges Friction Slope Method= 1
Parabolic Critical Depth
Global Vel Dist=  1 , 1 , 1
Global Log Level= 0
CheckData=True
Encroach Param= -1, 0, 0, 0
BEGIN DESCRIPTION:
Multiple Run
END DESCRIPTION:

--- UNT100 IN BECR.f01 (steady flow) ---

Flow Title=Multiple
Number of Profiles=7
Profile Names=10-year,25-year,50-year,1pct_min,100-year,1pct_plu,500-year
River Rch & RM= UNT100 IN BECR,Reach-1,4963
     522     711     869     783    1059    1432    1576
River Rch & RM= UNT100 IN BECR,Reach-1,3252
     603     826    1013     915    1238    1674    1852
Boundary for River Rch & Prof#=UNT100 IN BECR,Reach-1,1
Up Type=0
Dn Type=3
Dn Slope=0.005
Boundary for River Rch & Prof#=UNT100 IN BECR,Reach-1,2
Up Type=0
Dn Type=3
Dn Slope=0.005
Boundary for River Rch & Prof#=UNT100 IN BECR,Reach-1,3
Up Type=0
Dn Type=3
Dn Slope=0.005
Boundary for River Rch & Prof#=UNT100 IN BECR,Reach-1,4
Up Type=0
Dn Type=3
Dn Slope=0.005
Boundary for River Rch & Prof#=UNT100 IN BECR,Reach-1,5
Up Type=0
Dn Type=3
Dn Slope=0.005
Boundary for River Rch & Prof#=UNT100 IN BECR,Reach-1,6
Up Type=0
Dn Type=3
Dn Slope=0.005
Boundary for River Rch & Prof#=UNT100 IN BECR,Reach-1,7
Up Type=0
Dn Type=3
Dn Slope=0.005

--- UNT100 IN BECR.g01 (geometry) ---

Geom Title=Existing Conditions

River Reach=UNT100 IN BECR,Reach-1
Reach XY= 30
      3774249.61     10551210.19      3774121.84     10551219.59
      3774074.50     10551150.00      3773983.00     10551212.00
      3773810.25     10551186.00      3773767.75     10551070.00
      3773717.75     10551056.00      3773521.00     10551177.00
      3773478.00     10551096.00      3773221.50     10551076.00
      3773147.25     10550967.00      3772977.00     10550985.00
      3772889.75     10550860.00      3772780.00     10550910.00
      3772719.00     10551025.00      3772571.00     10551016.00
      3772446.00     10550946.00      3772255.50     10550972.00
      3772170.50     10551046.00      3771943.75     10550862.00
      3771478.50     10550783.00      3770965.50     10550788.00
      3770801.99     10550726.54      3770767.25     10550594.00
      3770691.00     10550623.00      3770644.75     10550581.00
      3770419.25     10550659.00      3770246.89     10550633.95
      3770002.25     10550895.00      3769862.25     10550881.00

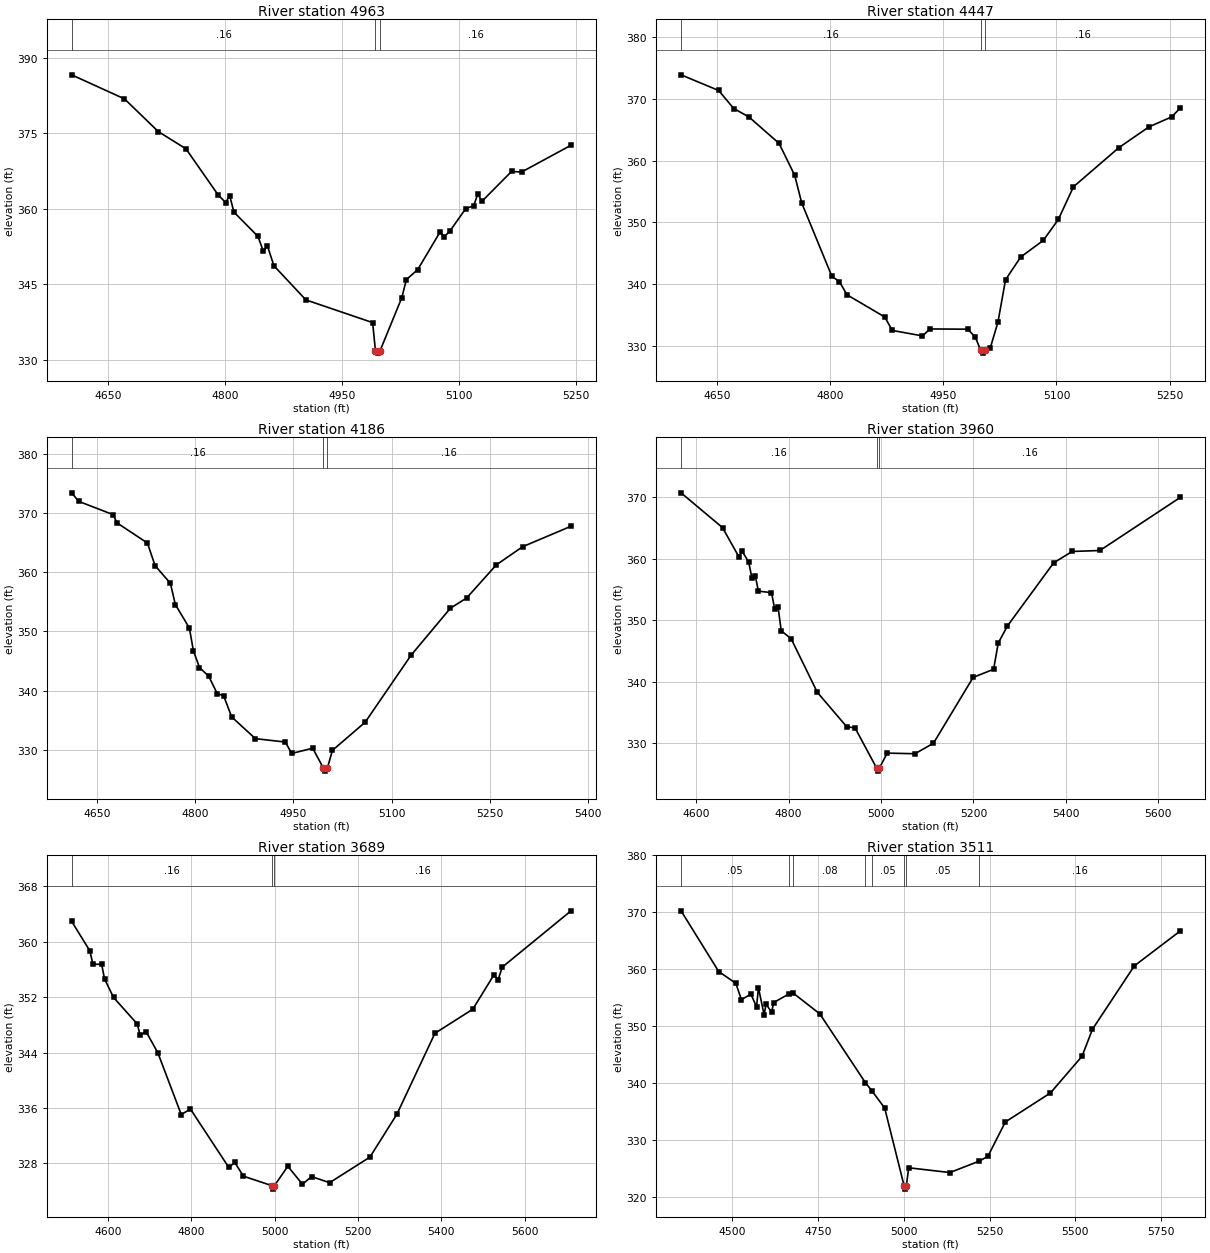
Type RM Length L Ch R = 1,4963,516,516,516
BEGIN DESCRIPTION:
UNT100 IN BECR 9.0
END DESCRIPTION:
XS GIS Cut Line= 2
      3773969.03     10550807.04      3773828.41     10551432.01
#Sta/Elev= 30
  4603.2  386.60  4671.0  381.82  4714.3  375.34  4749.9  371.90  4790.9  362.80
  4800.8  361.22  4805.9  362.63  4811.4  359.34  4842.2  354.52  4849.2  351.52
  4854.3  352.66  4862.7  348.68  4903.7  341.91  4989.3  337.40  4992.9  331.84
  4995.7  331.34  4998.9  331.84  5026.7  342.34  5032.6  345.94  5047.2  347.94
  5075.8  355.39  5081.0  354.43  5088.2  355.53  5108.7  360.03  5118.9  360.60
  5124.3  362.98  5129.4  361.47  5167.5  367.41  5180.4  367.30  5243.8  372.62
#Mann=3,-1,0
  4603.2    0.16       0  4992.9    0.07       0  4998.9    0.16       0
Bank Sta=4992.9,4998.9
Exp/Cntr=0.3,0.1

Type RM Length L Ch R = 1,4447,261,261,261
BEGIN DESCRIPTION:
UNT100 IN BECR 8.0
END DESCRIPTION:
XS GIS Cut Line= 2
      3773516.91     10550770.41      3773506.49     10551431.82
#Sta/Elev= 30
  4602.7  373.94  4652.5  371.40  4672.5  368.48  4692.5  367.12  4732.5  362.83
  4753.2  357.66  4762.5  353.18  4802.5  341.27  4812.5  340.41  4822.5  338.28
  4872.5  334.68  4882.5  332.50  4922.5  331.61  4932.5  332.74  4982.5  332.70
  4992.5  331.40  4999.5  329.32  5002.3  328.82  5005.5  329.32  5012.5  329.73
  5022.5  333.86  5032.5  340.71  5052.5  344.39  5082.5  347.09  5102.5  350.50
  5122.5  355.79  5182.6  362.13  5222.6  365.51  5252.6  367.12  5264.2  368.60
#Mann=3,-1,0
  4602.7    0.16       0  4999.5    0.07       0  5005.5    0.16       0
Bank Sta=4999.5,5005.5
Exp/Cntr=0.3,0.1

Type RM Length L Ch R = 1,4186,226,226,226
BEGIN DESCRIPTION:
Mapping XS c911ec6e
END DESCRIPTION:
XS GIS Cut Line= 3
      3773477.60     10550731.27      3773302.08     10551020.67
      3773322.19     10551444.13
#Sta/Elev= 30
  4611.5  373.37  4622.5  371.92  4674.8  369.69  4680.7  368.30  4727.2  364.90
  4738.9  361.08  4762.3  358.10  4769.8  354.52  4791.2  350.57  4797.4  346.71
  4806.7  343.89  4820.8  342.42  4833.8  339.47  4843.5  339.15  4855.8  335.56
  4892.0  331.89  4937.7  331.32  4947.5  329.39  4979.5  330.28  4995.9  326.91
  4998.6  326.41  5001.9  326.91  5009.6  329.91  5059.6  334.66  5129.7  345.97
  5189.8  353.91  5214.4  355.61  5259.8  361.21  5299.9  364.27  5373.9  367.73
#Mann=3,-1,0
  4611.5    0.16       0  4995.9    0.07       0  5001.9    0.16       0
Bank Sta=4995.9,5001.9
Exp/Cntr=0.3,0.1

Type RM Length L Ch R = 1,3960,271,271,271
BEGIN DESCRIPTION:
UNT100 IN BECR 7.0
END DESCRIPTION:
XS GIS Cut Line= 3
      3773416.98     10550650.75      3773146.11     10550905.99
      3773114.86     10551614.32
#Sta/Elev= 30
  4567.1  370.71  4656.9  365.05  4692.1  360.33  4699.4  361.21  4713.6  359.44
  4720.4  356.91  4727.7  357.24  4734.6  354.72  4762.9  354.47  4769.8  351.86
  4777.1  352.16  4784.0  348.27  4805.4  346.98  4862.1  338.26  4925.6  332.67
  4943.9  332.46  4990.5  325.94  4993.3  325.44  4996.5  325.94  5013.5  328.37
  5073.6  328.27  5113.6  329.98  5199.5  340.69  5243.8  342.01  5253.8  346.27
  5273.8  349.06  5373.9  359.33  5413.9  361.17  5474.0  361.33  5648.3  369.98
#Mann=3,-1,0
  4567.1    0.16       0  4990.5    0.07       0  4996.5    0.16       0
Bank Sta=4990.5,4996.5
Exp/Cntr=0.3,0.1

Type RM Length L Ch R = 1,3689,178,178,178
BEGIN DESCRIPTION:
Mapping XS 7388c8b7
END DESCRIPTION:
XS GIS Cut Line= 3
      3773271.29     10550530.22      3772894.74     10550971.09
      3772984.52     10551583.45
#Sta/Elev= 30
  4512.8  362.96  4556.3  358.71  4564.0  356.76  4584.9  356.74  4591.7  354.64
  4613.4  351.96  4670.5  348.11  4677.1  346.50  4691.4  347.03  4719.9  343.94
  4775.9  335.04  4797.9  335.84  4890.1  327.40  4904.4  328.12  4925.2  326.14
  4993.6  324.77  4996.3  324.27  4999.6  324.77  5031.7  327.57  5066.8  324.98
  5088.7  326.08  5132.1  325.20  5228.8  328.90  5293.6  335.10  5384.8  346.78
  5475.7  350.26  5526.3  355.21  5536.4  354.52  5546.5  356.34  5711.5  364.47
#Mann=3,-1,0
  4512.8    0.16       0  4993.6    0.07       0  4999.6    0.16       0
Bank Sta=4993.6,4999.6
Exp/Cntr=0.3,0.1

Type RM Length L Ch R = 1,3511,259,259,259
BEGIN DESCRIPTION:
UNT100 IN BECR 6.0
END DESCRIPTION:
XS GIS Cut Line= 4
      3773067.98     10550312.25      3772802.36     10550817.45
      3772791.95     10551088.28      3772901.32     10551692.45
#Sta/Elev= 30
  4350.4  370.24  4460.2  359.59  4510.0  357.52  4526.4  354.66  4554.1  355.60
  4570.5  353.40  4576.1  356.73  4592.5  351.98  4598.2  353.86  4614.5  352.44
  4620.2  354.14  4665.4  355.66  4678.1  355.76  4754.8  352.16  4887.6  340.10
  4907.2  338.61  4943.9  335.64  5001.0  321.89  5003.7  321.39  5007.0  321.89
  5014.0  325.14  5134.1  324.30  5220.2  326.32  5245.0  327.16  5295.8  333.18
  5427.2  338.27  5519.3  344.71  5549.8  349.46  5671.8  360.58  5806.2  366.73
#Mann=8,-1,0
  4350.4    0.05       0  4665.4    0.16       0  4678.1    0.08       0
  4887.6    0.16       0  4907.2    0.05       0  5001.0    0.04       0
  5007.0    0.05       0  5220.2    0.16       0
Bank Sta=5001,5007
Exp/Cntr=0.3,0.1

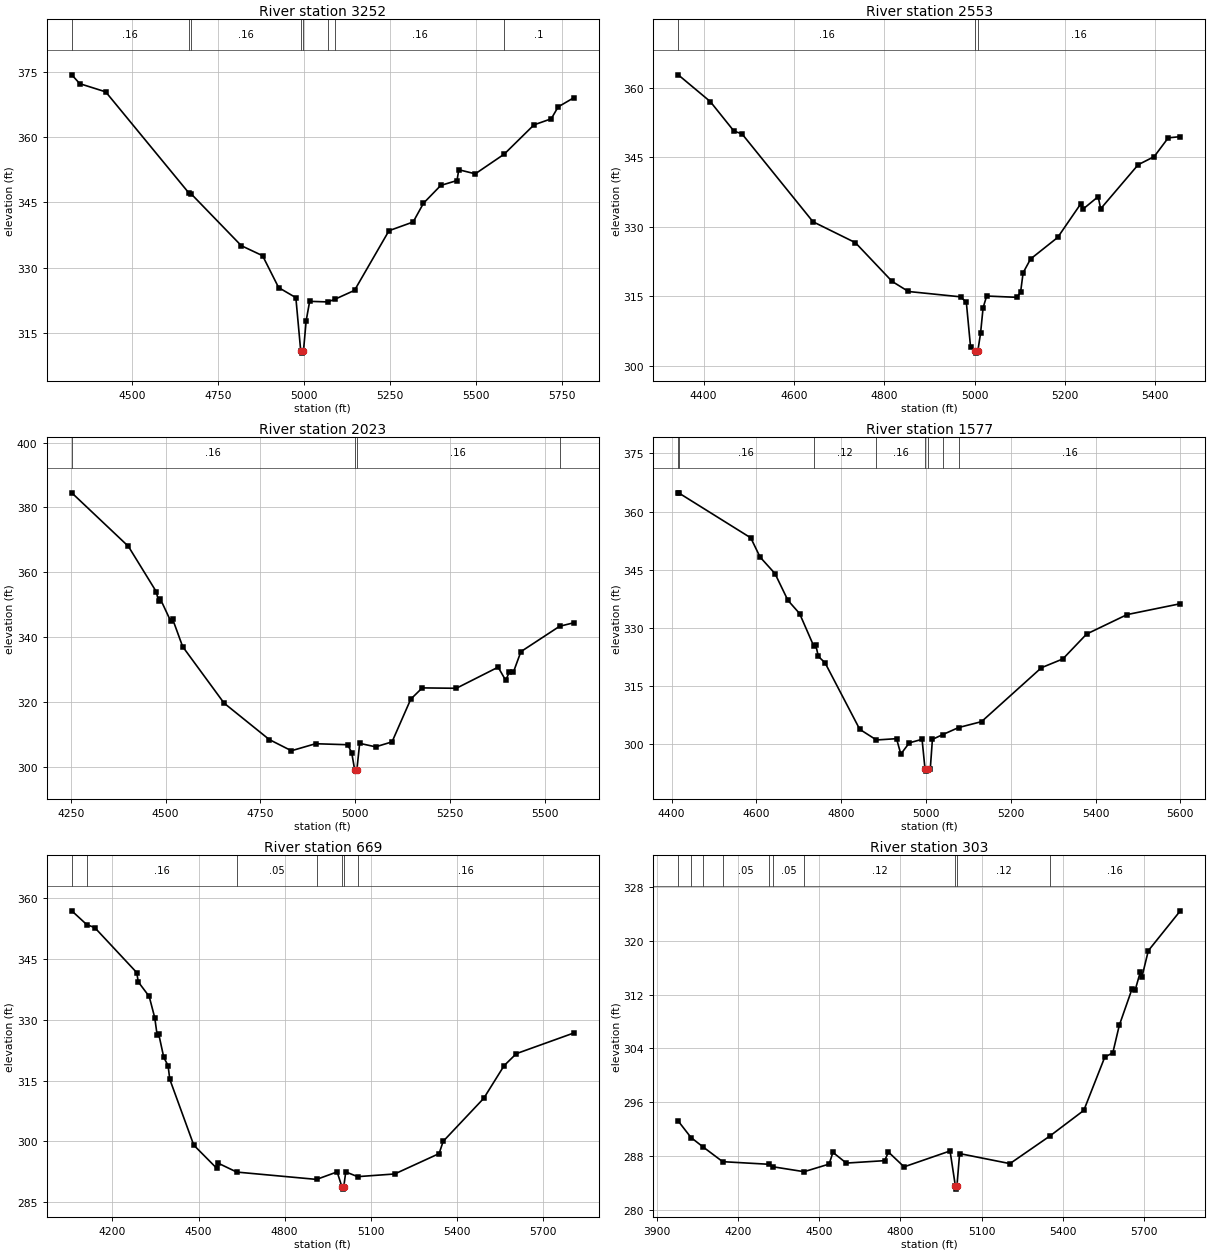
Type RM Length L Ch R = 1,3252,699,699,699
BEGIN DESCRIPTION:
UNT100 IN BECR 5.0
END DESCRIPTION:
XS GIS Cut Line= 4
      3772854.44     10550374.76      3772635.70     10550869.53
      3772599.24     10551296.61      3772552.41     10551785.67
#Sta/Elev= 30
  4324.2  374.29  4347.5  372.26  4422.9  370.38  4664.3  347.22  4670.8  347.02
  4817.5  335.06  4879.4  332.76  4926.1  325.44  4976.2  323.13  4990.4  310.89
  4993.2  310.39  4996.4  310.89  4998.4  310.91  5006.3  317.87  5016.4  322.28
  5068.9  322.15  5089.0  322.73  5146.9  324.80  5247.2  338.50  5317.5  340.50
  5347.6  344.81  5397.9  348.90  5445.2  350.02  5450.2  352.50  5498.3  351.56
  5582.5  356.08  5669.1  362.80  5719.3  364.19  5739.4  366.93  5785.1  369.03
#Mann=8,-1,0
  4324.2    0.16       0  4664.3    0.05       0  4670.8    0.16       0
  4990.4    0.07       0  4996.4    0.16       0  5068.9    0.05       0
  5089.0    0.16       0  5582.5     0.1       0
Bank Sta=4990.4,4996.4
Exp/Cntr=0.3,0.1

Type RM Length L Ch R = 1,2553,530,530,530
BEGIN DESCRIPTION:
UNT100 IN BECR 4.0
END DESCRIPTION:
XS GIS Cut Line= 3
      3772291.97     10550338.24      3772088.82     10550807.03
      3771813.71     10551341.68
#Sta/Elev= 30
  4343.7  362.75  4414.6  356.99  4467.0  350.63  4485.0  350.01  4642.2  331.07
  4736.1  326.56  4817.4  318.21  4853.6  316.03  4969.1  314.88  4981.9  313.70
  4991.2  304.10  5001.4  303.24  5004.1  302.74  5007.4  303.24  5013.4  307.02
  5019.0  312.51  5026.9  315.05  5094.3  314.77  5102.1  315.90  5107.7  320.08
  5124.3  323.05  5184.3  327.69  5235.1  334.90  5240.8  333.83  5273.9  336.48
  5279.5  333.87  5362.6  343.37  5398.0  345.11  5429.1  349.16  5455.9  349.42
#Mann=3,-1,0
  4343.7    0.16       0  5001.4    0.07       0  5007.4    0.16       0
Bank Sta=5001.4,5007.4
Exp/Cntr=0.3,0.1

Type RM Length L Ch R = 1,2023,446,446,446
BEGIN DESCRIPTION:
UNT100 IN BECR 3.0
END DESCRIPTION:
XS GIS Cut Line= 3
      3771765.92     10550088.24      3771500.28     10550900.78
      3771531.53     10551369.57
#Sta/Elev= 30
  4252.6  384.53  4401.9  368.01  4475.6  354.00  4481.5  351.00  4486.7  351.65
  4513.3  345.01  4518.6  345.58  4545.2  337.04  4654.4  319.60  4773.6  308.36
  4832.1  304.89  4895.8  307.06  4980.6  306.75  4991.1  304.34  4998.9  299.10
  5001.7  298.60  5004.9  299.10  5012.2  307.18  5054.2  306.10  5097.6  307.63
  5147.0  320.82  5177.3  324.30  5267.2  324.18  5377.5  330.70  5397.5  326.62
  5407.5  329.31  5417.6  329.09  5437.6  335.49  5539.8  343.33  5577.3  344.41
#Mann=4,-1,0
  4252.6    0.16       0  4998.9    0.07       0  5004.9    0.16       0
  5539.8    0.05       0
Bank Sta=4998.9,5004.9
Exp/Cntr=0.3,0.1

Type RM Length L Ch R = 1,1577,908,908,908
BEGIN DESCRIPTION:
UNT100 IN BECR 2.0
END DESCRIPTION:
XS GIS Cut Line= 4
      3771328.40     10550239.33      3771114.86     10550635.15
      3771094.03     10550937.24      3771156.53     10551364.34
#Sta/Elev= 30
  4415.6  364.82  4416.4  364.82  4586.7  353.21  4608.6  348.26  4643.8  344.00
  4674.3  337.10  4701.8  333.70  4735.2  325.32  4740.0  325.57  4746.1  322.63
  4761.8  321.01  4843.7  303.85  4883.1  301.10  4930.5  301.44  4940.6  297.46
  4960.6  300.36  4990.7  301.27  4997.7  293.57  5000.4  293.07  5003.7  293.57
  5010.1  293.69  5015.1  301.26  5039.5  302.49  5077.0  304.31  5131.0  305.83
  5272.2  319.73  5322.7  321.99  5378.8  328.41  5474.3  333.43  5599.8  336.23
#Mann=8,-1,0
  4415.6    0.05       0  4416.4    0.16       0  4735.2    0.12       0
  4883.1    0.16       0  4997.7    0.07       0  5003.7    0.16       0
  5039.5    0.12       0  5077.0    0.16       0
Bank Sta=4997.7,5003.7
Exp/Cntr=0.3,0.1

Type RM Length L Ch R = 1,669,366,366,366
BEGIN DESCRIPTION:
UNT100 IN BECR 1.0
END DESCRIPTION:
XS GIS Cut Line= 4
      3771196.21     10550297.74      3770397.55     10550540.81
      3770380.19     10550827.26      3770848.96     10551243.95
#Sta/Elev= 30
  4058.3  356.91  4110.1  353.53  4138.4  352.76  4284.7  341.66  4289.9  339.37
  4328.0  335.78  4347.4  330.51  4355.7  326.23  4360.9  326.61  4378.8  320.72
  4393.7  318.73  4399.7  315.34  4483.3  299.08  4563.2  293.37  4568.4  294.62
  4633.0  292.43  4911.0  290.62  4982.7  292.47  4999.7  288.72  5002.5  288.22
  5005.7  288.72  5012.7  292.47  5054.1  291.30  5183.1  291.96  5337.9  296.99
  5352.1  300.02  5493.4  310.63  5564.5  318.71  5607.1  321.66  5807.3  326.76
#Mann=7,-1,0
  4058.3    0.05       0  4110.1    0.16       0  4633.0    0.05       0
  4911.0    0.12       0  4999.7    0.07       0  5005.7    0.12       0
  5054.1    0.16       0
Bank Sta=4999.7,5005.7
Exp/Cntr=0.3,0.1

Type RM Length L Ch R = 1,303,0,0,0
BEGIN DESCRIPTION:
Mapping XS 39be7b92
END DESCRIPTION:
XS GIS Cut Line= 4
      3770514.61     10550077.56      3769949.51     10550595.79
      3770319.31     10551064.54      3770774.85     10551249.36
#Sta/Elev= 30
  3979.0  293.20  4026.1  290.76  4070.7  289.36  4143.2  287.17  4314.6  286.78
  4329.0  286.41  4444.1  285.68  4536.5  286.81  4550.7  288.55  4600.0  286.96
  4741.8  287.32  4755.8  288.60  4813.6  286.40  4983.5  288.76  5003.0  283.59
  5005.8  283.09  5009.0  283.59  5018.8  288.37  5204.8  286.88  5352.7  290.99
  5477.8  294.79  5555.4  302.72  5584.9  303.33  5609.0  307.44  5656.1  312.85
  5668.0  312.73  5686.7  315.37  5692.1  314.54  5716.2  318.52  5834.4  324.44
#Mann=10,-1,0
  3979.0    0.16       0  4026.1    0.05       0  4070.7    0.07       0
  4143.2    0.05       0  4314.6    0.12       0  4329.0    0.05       0
  4444.1    0.12       0  5003.0    0.07       0  5009.0    0.12       0
  5352.7    0.16       0
Bank Sta=5003,5009
Exp/Cntr=0.3,0.1

Chan Stop Cuts=-1