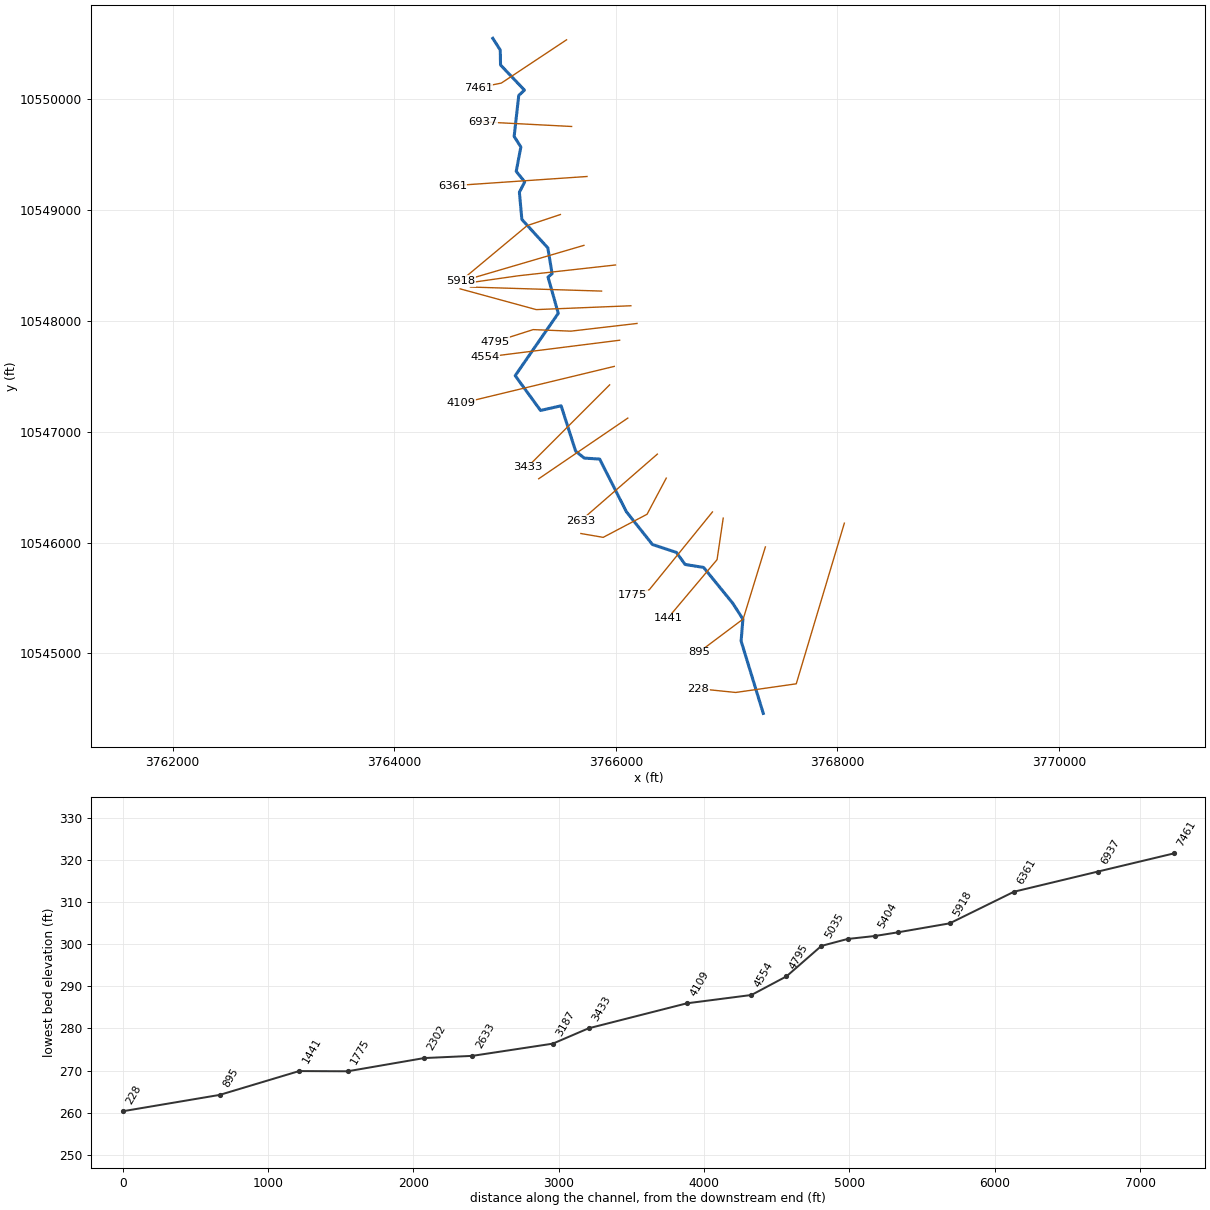
--- UNT101 IN BECR.prj (project) ---

Proj Title=UNT101 IN BECR Base Level Engineering
Current Plan=p01
Default Exp/Contr=0.3,0.1
English Units
Geom File=g01
Flow File=f01
Plan File=p01
Y Axis Title=Elevation
X Axis Title(PF)=Main Channel Distance
X Axis Title(XS)=Station
BEGIN DESCRIPTION:
UNT101 IN BECR
END DESCRIPTION:
DSS Export Rating Curves= 0
DSS Export Rating Curve Sorted= 0
DSS Export Volume Flow Curves= 0
DXF OffsetX= 0
DXF OffsetY= 0
DXF ScaleX= 1
DXF ScaleY= 10

--- UNT101 IN BECR.p01 (plan) ---

Plan Title=Multiple Run
Short Identifier=Multiple
Geom File=g01
Flow File=f01
Subcritical Flow
K Sum by GR= 0
Std Step Tol= 0.01
Critical Tol= 0.01
Num of Std Step Trials= 20
Max Error Tol= 0.3
Flow Tol Ratio= 0.001
Split Flow NTrial= 30
Split Flow Tol= 0.02
Split Flow Ratio= 0.02
Log Output Level= 0
Friction Slope Method= 1
Unsteady Friction Slope Method= 2
Unsteady Bridges Friction Slope Method= 1
Parabolic Critical Depth
Global Vel Dist=  1 , 1 , 1
Global Log Level= 0
CheckData=True
Encroach Param= -1, 0, 0, 0
BEGIN DESCRIPTION:
Multiple Run
END DESCRIPTION:

--- UNT101 IN BECR.f01 (steady flow) ---

Flow Title=Multiple
Program Version=4.10
Number of Profiles= 7
Profile Names=10-year,25-year,50-year,1pct_min,100-year,1pct_plu,500-year
River Rch & RM=UNT101 IN BECR,Reach-1         ,7461
     398     532     642     572     773    1046    1123
River Rch & RM=UNT101 IN BECR,Reach-1         ,4795
     677     934    1150    1043    1410    1907    2127
River Rch & RM=UNT101 IN BECR,Reach-1         ,1775
     725    1003    1237    1123    1518    2053    2294
Boundary for River Rch & Prof#=UNT101 IN BECR,Reach-1         , 1
Up Type= 0
Dn Type= 3
Dn Slope=0.006
Boundary for River Rch & Prof#=UNT101 IN BECR,Reach-1         , 2
Up Type= 0
Dn Type= 3
Dn Slope=0.006
Boundary for River Rch & Prof#=UNT101 IN BECR,Reach-1         , 3
Up Type= 0
Dn Type= 3
Dn Slope=0.006
Boundary for River Rch & Prof#=UNT101 IN BECR,Reach-1         , 4
Up Type= 0
Dn Type= 3
Dn Slope=0.006
Boundary for River Rch & Prof#=UNT101 IN BECR,Reach-1         , 5
Up Type= 0
Dn Type= 3
Dn Slope=0.006
Boundary for River Rch & Prof#=UNT101 IN BECR,Reach-1         , 6
Up Type= 0
Dn Type= 3
Dn Slope=0.006
Boundary for River Rch & Prof#=UNT101 IN BECR,Reach-1         , 7
Up Type= 0
Dn Type= 3
Dn Slope=0.006
DSS Import GetInterval= 0
DSS Import GetPeak= 0
DSS Import FillOption= 0

--- UNT101 IN BECR.g01 (geometry) ---

Geom Title=Existing Conditions
Program Version=4.10

River Reach=UNT101 IN BECR  ,Reach-1
Reach XY= 30
      3764889.68     10550550.46        3764957.       10550445.
       3764959.5       10550310.      3765175.25       10550083.
        3765124.       10550035.      3765082.25       10549665.
        3765143.       10549570.        3765101.       10549350.
       3765177.5       10549255.      3765129.75       10549161.
        3765152.       10548916.       3765386.5       10548659.
      3765424.75       10548426.        3765388.       10548396.
       3765480.5       10548069.      3765091.75       10547506.
       3765320.5       10547192.       3765506.5       10547234.
       3765637.5       10546824.       3765715.5       10546762.
        3765854.       10546753.      3766095.25       10546278.
       3766330.5       10545982.       3766546.5       10545911.
      3766625.25       10545802.      3766792.25       10545775.
       3767054.5       10545453.        3767147.       10545309.
      3767130.75       10545111.      3767330.75       10544458.

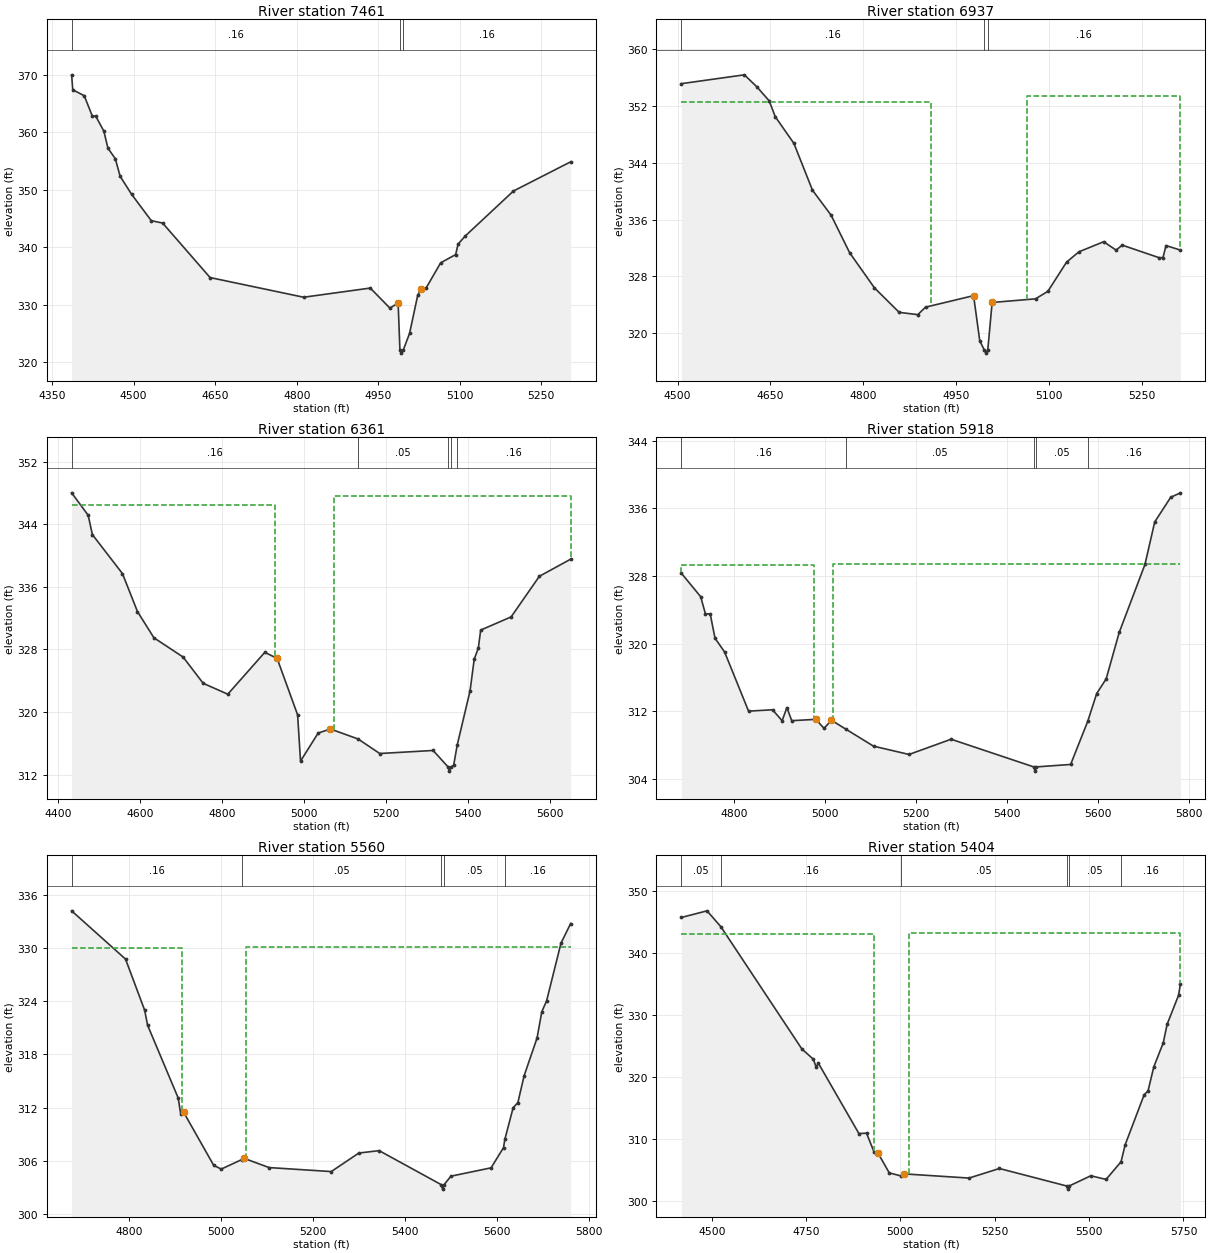
Type RM Length L Ch R = 1 ,7461    ,524,524,524
BEGIN DESCRIPTION:
UNT101 IN BECR 16.0
END DESCRIPTION:
XS GIS Cut Line= 3
      3765555.25     10550537.12      3764966.69     10550146.49
      3764759.29     10550105.01
#Sta/Elev= 30
    4386  370.04  4388.1  367.43  4409.2   366.4  4424.2  362.83  4430.2  362.87
  4445.3  360.22  4452.8  357.25  4466.3  355.43  4475.3  352.35  4496.4  349.21
  4532.5  344.63  4553.5   344.2  4640.7  334.71  4812.8  331.28  4935.4  332.88
  4971.5  329.38  4986.6  330.28  4989.9  322.04  4992.6  321.54  4995.9  322.04
  5007.6  324.97  5022.6  331.62  5028.9   332.7  5037.7  332.83  5064.9  337.29
  5092.4  338.71  5096.8  340.53  5109.8  341.93  5198.7  349.79  5303.9  354.88
#Mann= 3 ,-1 , 0
    4386     .16       0  4989.9     .07       0  4995.9     .16       0
Bank Sta=4986.6,5028.9
XS Rating Curve= 0 ,0
Exp/Cntr=0.3,0.1

Type RM Length L Ch R = 1 ,6937    ,576,576,576
BEGIN DESCRIPTION:
UNT101 IN BECR 15.0
END DESCRIPTION:
XS GIS Cut Line= 2
      3765601.15     10549754.95      3764795.63     10549796.61
#Sta/Elev= 30
  4506.1   355.1  4607.8  356.34  4627.8  354.67  4647.8   352.7  4657.8  350.45
  4687.9   346.7  4717.9  340.12    4748  336.61    4778  331.33  4818.1  326.39
  4858.1  322.95  4888.2  322.63  4900.6  323.68  4978.3   325.3  4988.3  318.95
  4995.3  317.72  4998.1  317.22  5001.3  317.72  5008.3  324.34  5078.4  324.85
  5098.4  325.91  5128.5     330  5148.5  331.46  5188.6  332.88  5208.6   331.7
  5218.6   332.4  5278.7  330.62  5284.4  330.66  5289.4  332.34  5312.7   331.7
#Mann= 3 ,-1 , 0
  4506.1     .16       0  4995.3     .07       0  5001.3     .16       0
#XS Ineff= 2 , 0
         4909.19  352.57 5064.04          353.41
Permanent Ineff=
       F       F
Bank Sta=4978.3,5008.3
XS Rating Curve= 0 ,0
Exp/Cntr=0.3,0.1

Type RM Length L Ch R = 1 ,6361    ,443,443,443
BEGIN DESCRIPTION:
UNT101 IN BECR 14.0
END DESCRIPTION:
XS GIS Cut Line= 2
      3765740.06     10549303.56      3764524.72     10549220.22
#Sta/Elev= 30
  4432.6  348.01  4473.1  345.14  4483.2  342.68  4556.7  337.69  4593.4  332.83
  4633.5  329.49  4704.9  327.02  4753.8  323.67  4813.9  322.28  4904.2  327.63
  4934.2  326.86  4984.3  319.64  4991.4  313.73  5034.5  317.32  5064.5  317.83
  5131.8  316.56  5184.8   314.7  5315.1  315.09  5352.2  312.95    5355  312.45
  5358.2  312.95  5365.2  313.19    5374   315.8  5405.3  322.72  5415.4  326.74
  5425.4  328.16  5431.2  330.47  5505.6  332.16  5574.5  337.35  5650.8  339.53
#Mann= 5 ,-1 , 0
  4432.6     .16       0  5131.8     .05       0  5352.2     .07       0
  5358.2     .05       0    5374     .16       0
#XS Ineff= 2 , 0
         4930.05  346.42 5072.44          347.64
Permanent Ineff=
       F       F
Bank Sta=4934.2,5064.5
XS Rating Curve= 0 ,0
Exp/Cntr=0.3,0.1

Type RM Length L Ch R = 1 ,5918    ,358,358,358
BEGIN DESCRIPTION:
UNT101 IN BECR 13.0
END DESCRIPTION:
XS GIS Cut Line= 3
      3765499.65      10548960.2      3765199.61     10548860.19
      3764599.61     10548360.19
#Sta/Elev= 30
  4684.8  328.32    4727  325.56  4737.5  323.54  4748.1  323.51  4758.6  320.65
  4779.7  319.02  4832.4  312.03  4885.1  312.19  4906.2   310.9  4916.7  312.45
  4927.3   310.9    4980  311.06  4998.4     310  5014.7  310.95  5045.7  309.92
  5107.2  307.89  5185.3  306.91  5277.7  308.71  5459.5  305.44  5462.3  304.94
  5465.5  305.44  5540.6  305.73  5578.3  310.84  5597.9  314.11  5618.7  315.84
  5647.4  321.33    5704  329.36  5725.5  334.39  5760.6   337.3  5782.1  337.83
#Mann= 5 ,-1 , 0
  4684.8     .16       0  5045.7     .05       0  5459.5     .07       0
  5465.5     .05       0  5578.3     .16       0
#XS Ineff= 2 , 0
         4975.59  329.26  5018.9          329.46
Permanent Ineff=
       F       F
Bank Sta=4980,5014.7
XS Rating Curve= 0 ,0
Exp/Cntr=0.3,0.1

Type RM Length L Ch R = 1 ,5560    ,156,156,156
BEGIN DESCRIPTION:
Mapping XS 5e5deadb
END DESCRIPTION:
XS GIS Cut Line= 2
      3765712.28      10548682.1      3764669.34     10548376.11
#Sta/Elev= 30
  4674.1  334.18  4791.5  328.74  4833.2  322.97  4839.6  321.28  4906.2  313.08
  4911.6  311.32 4918.11  311.47  4983.6  305.48    5000  305.06    5045  306.14
  5050.3  306.26  5104.2  305.23  5239.6  304.78  5299.7  306.87  5343.9  307.14
  5479.3   303.3  5482.1   302.8  5485.3   303.3  5500.2  304.26  5587.7   305.2
  5614.8  307.48  5617.7  308.41  5635.7  311.97  5646.1  312.56  5659.7  315.59
  5687.8  319.83  5698.3  322.82  5708.6  324.02  5739.9  330.52    5761  332.75
#Mann= 5 ,-1 , 0
  4674.1     .16       0    5045     .05       0  5479.3     .07       0
  5485.3     .05       0  5617.7     .16       0
#XS Ineff= 2 , 0
         4914.96  330.03 5054.33          330.15
Permanent Ineff=
       F       F
Bank Sta=4918.11,5050.3
XS Rating Curve= 0 ,0
Exp/Cntr=0.3,0.1

Type RM Length L Ch R = 1 ,5404    ,189,189,189
BEGIN DESCRIPTION:
Mapping XS 59f7ca59
END DESCRIPTION:
XS GIS Cut Line= 3
      3765996.99     10548504.95      3765121.98     10548407.72
      3764684.52     10548345.23
#Sta/Elev= 30
  4419.8  345.66  4487.6  346.73  4524.2  344.18  4739.1  324.48  4769.3  322.85
  4777.1  321.52  4782.1  322.26  4890.1  310.88  4910.2  310.95  4930.3   307.9
  4940.4  307.77  4970.5  304.55  5000.6  304.08  5010.8  304.39  5181.8  303.72
  5262.3  305.26    5441  302.44  5443.8  301.94    5447  302.44  5504.6  304.09
    5545   303.5  5584.7  306.35  5595.5  309.07    5646  317.15  5656.1  317.73
  5671.5  321.63  5696.5  325.48  5706.7  328.46    5737  333.13  5742.1     335
#Mann= 6 ,-1 , 0
  4419.8     .05       0  4524.2     .16       0  5000.6     .05       0
    5441     .07       0    5447     .05       0  5584.7     .16       0
#XS Ineff= 2 , 0
         4929.13  342.99 5021.92          343.16
Permanent Ineff=
       F       F
Bank Sta=4940.4,5010.8
XS Rating Curve= 0 ,0
Exp/Cntr=0.3,0.1

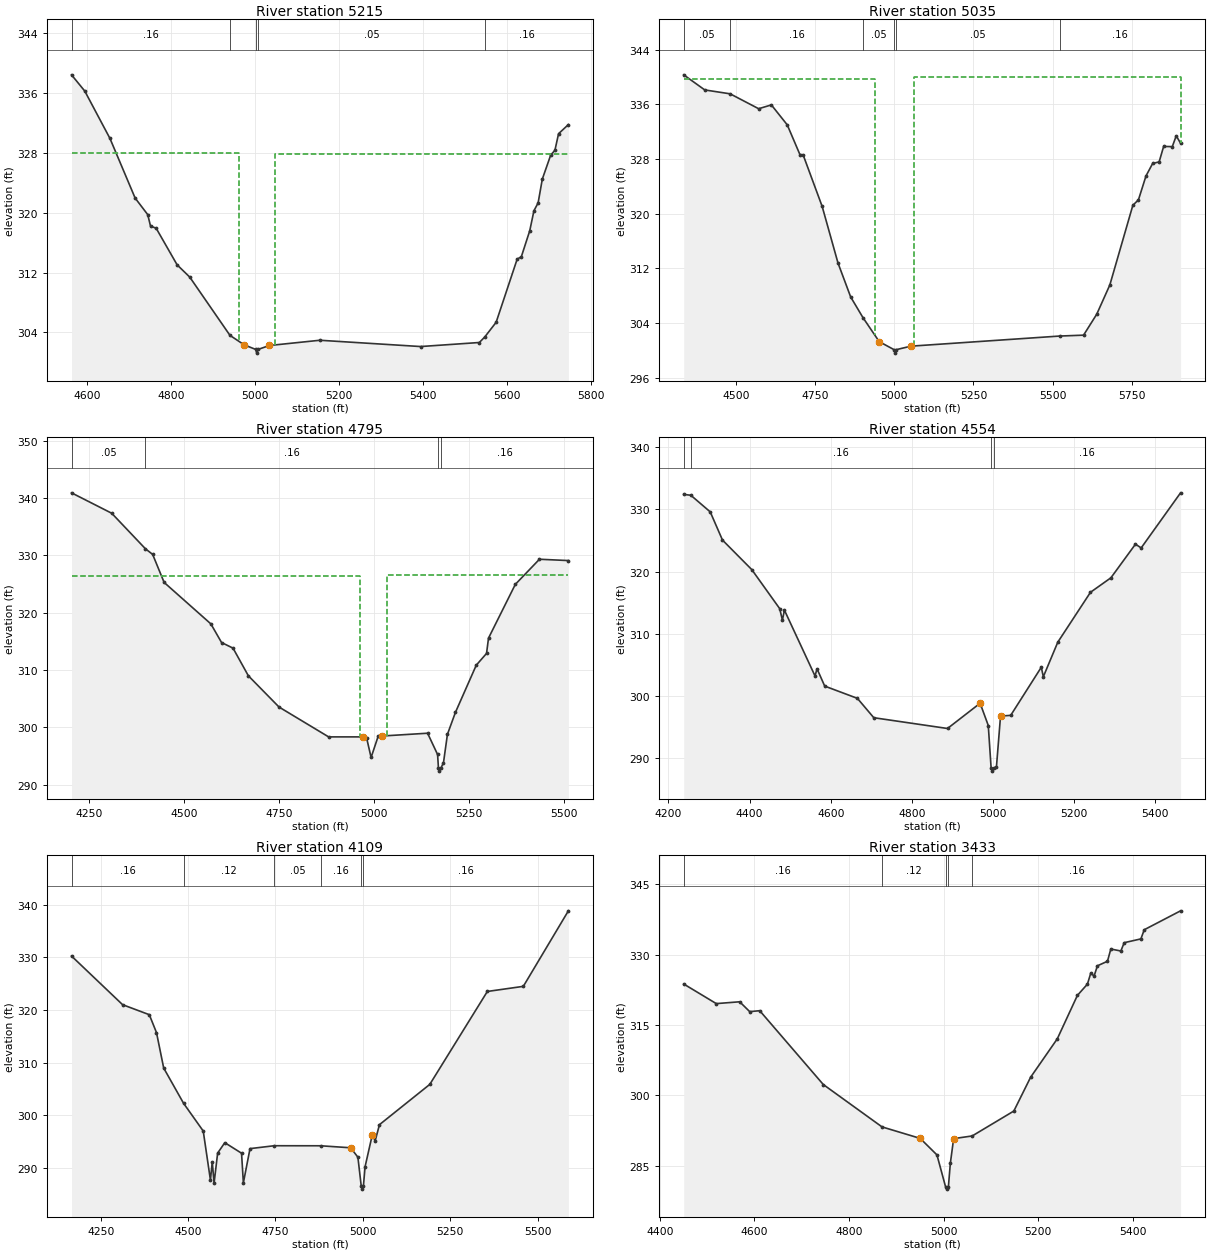
Type RM Length L Ch R = 1 ,5215    ,180,180,180
BEGIN DESCRIPTION:
Mapping XS 28e0298b
END DESCRIPTION:
XS GIS Cut Line= 2
      3765871.18     10548269.34      3764687.54      10548305.8
#Sta/Elev= 30
  4562.1  338.43  4593.7  336.26  4653.7  329.93  4713.7  321.96  4743.8  319.74
  4750.4  318.21  4763.8  317.93  4813.8  313.03  4843.8   311.4  4939.8   303.6
  4973.9  302.33  5000.9  301.73  5003.6  301.23  5006.9  301.73  5033.9  302.25
  5153.9  302.95  5394.1  302.11  5534.1  302.65    5547  303.39  5574.1  305.35
  5624.2  313.79  5634.2  314.12  5654.2  317.59  5664.2  320.26  5674.2  321.32
  5684.2   324.5  5704.2  327.71  5714.2  328.34  5722.9  330.56  5746.3  331.78
#Mann= 5 ,-1 , 0
  4562.1     .16       0  4939.8     .05       0  5000.9     .03       0
  5006.9     .05       0    5547     .16       0
#XS Ineff= 2 , 0
         4960.37  327.97 5046.72          327.84
Permanent Ineff=
       F       F
Bank Sta=4973.9,5033.9
XS Rating Curve= 0 ,0
Exp/Cntr=0.3,0.1

Type RM Length L Ch R = 1 ,5035    ,240,240,240
BEGIN DESCRIPTION:
UNT101 IN BECR 12.0
END DESCRIPTION:
XS GIS Cut Line= 3
      3766135.91     10548136.89       3765281.7     10548102.17
      3764594.41     10548289.61
#Sta/Elev= 30
    4336  340.31  4402.4   338.1  4482.5  337.53  4572.5  335.35  4612.5  335.91
  4662.6  332.99  4702.6  328.64  4712.6  328.61  4772.7  321.06  4822.7  312.77
  4862.7   307.8  4901.4  304.78  4952.8  301.26  4999.8  300.08  5002.6  299.58
  5005.8  300.08  5052.9   300.6    5522  302.08  5597.3  302.21  5638.8  305.27
  5680.2  309.56  5752.8  321.22  5770.4  322.01  5794.3  325.52  5815.3  327.34
  5835.7  327.57  5849.9  329.83  5877.2   329.8  5889.6  331.38  5903.3   330.3
#Mann= 6 ,-1 , 0
    4336     .05       0  4482.5     .16       0  4901.4     .05       0
  4999.8     .03       0  5005.8     .05       0    5522     .16       0
#XS Ineff= 2 , 0
         4939.37  339.66 5061.02          339.97
Permanent Ineff=
       F       F
Bank Sta=4952.8,5052.9
XS Rating Curve= 0 ,0
Exp/Cntr=0.3,0.1

Type RM Length L Ch R = 1 ,4795    ,241,241,241
BEGIN DESCRIPTION:
UNT101 IN BECR 11.0
END DESCRIPTION:
XS GIS Cut Line= 4
      3766191.47     10547977.17       3765594.2     10547907.72
      3765253.93     10547921.61      3764906.72     10547810.51
#Sta/Elev= 30
  4204.8  340.88  4310.5  337.32  4399.2  331.12  4418.1  330.15  4448.3  325.26
  4571.2  318.03  4599.3  314.78  4629.5   313.8  4669.8  308.98  4750.3  303.54
  4880.8  298.33  4970.8  298.33  4980.8  298.12  4992.5  294.74  5010.9  298.41
  5020.9  298.48    5141  298.97  5167.3  295.26  5169.6  292.86  5172.3  292.36
  5175.6  292.86  5182.7  293.78  5193.2  298.78  5214.2   302.6    5269  310.83
    5296  312.88  5301.2  315.55  5371.7  324.92  5435.1   329.3  5511.2  329.07
#Mann= 4 ,-1 , 0
  4204.8     .05       0  4399.2     .16       0  5169.6     .07       0
  5175.6     .16       0
#XS Ineff= 2 , 0
          4964.3  326.39  5033.2          326.59
Permanent Ineff=
       F       F
Bank Sta=4970.8,5020.9
XS Rating Curve= 0 ,0
Exp/Cntr=0.3,0.1

Type RM Length L Ch R = 1 ,4554    ,445,445,445
BEGIN DESCRIPTION:
UNT101 IN BECR 10.0
END DESCRIPTION:
XS GIS Cut Line= 2
       3766034.5     10547825.72      3764819.27     10547672.95
#Sta/Elev= 30
  4237.6   332.4  4255.2  332.26    4303  329.59  4333.2  325.06  4405.5  320.31
  4474.3  314.04  4480.9   312.2  4485.9   313.8  4561.3  303.23  4566.3  304.38
  4585.2   301.6  4665.8  299.63  4706.2  296.52  4887.9  294.79  4968.3  298.85
  4988.4  295.27  4995.4  288.44  4998.2  287.94  5001.4  288.44  5008.5   288.6
  5018.6  296.78  5043.7   296.9  5119.1  304.63  5124.1   303.1  5159.7  308.65
  5240.3  316.67  5290.7     319  5351.2   324.4  5365.3   323.8  5462.4  332.65
#Mann= 4 ,-1 , 0
  4237.6     .05       0  4255.2     .16       0  4995.4     .07       0
  5001.4     .16       0
Bank Sta=4968.3,5018.6
XS Rating Curve= 0 ,0
Exp/Cntr=0.3,0.1

Type RM Length L Ch R = 1 ,4109    ,676,676,676
BEGIN DESCRIPTION:
UNT101 IN BECR 9.0
END DESCRIPTION:
XS GIS Cut Line= 2
      3765985.93     10547589.62      3764604.26     10547256.35
#Sta/Elev= 30
  4166.6  330.22  4312.7  320.98  4389.1  319.08  4409.7  315.68  4430.3  308.95
  4487.1  302.26  4543.4  296.99    4564  287.68  4569.2  291.16  4574.4  287.09
  4584.6   292.8  4605.1  294.78    4653  292.78  4658.2  287.15  4677.2  293.65
  4746.5   294.2  4879.4  294.19  4965.2  293.81  4985.8  292.02  4995.5  286.46
  4998.2  285.96  5001.5  286.46  5006.3   290.2  5026.9  296.25  5035.2  295.12
  5047.5   298.2  5191.5  305.85  5356.1  323.49    5459  324.46  5587.9   338.8
#Mann= 6 ,-1 , 0
  4166.6     .16       0  4487.1     .12       0  4746.5     .05       0
  4879.4     .16       0  4995.5     .07       0  5001.5     .16       0
Bank Sta=4965.2,5026.9
XS Rating Curve= 0 ,0
Exp/Cntr=0.3,0.1

Type RM Length L Ch R = 1 ,3433    ,246,246,246
BEGIN DESCRIPTION:
UNT101 IN BECR 8.0
END DESCRIPTION:
XS GIS Cut Line= 2
      3765944.27     10547422.96      3765201.24     10546679.93
#Sta/Elev= 30
  4450.4  323.74  4519.3  319.56  4568.8  319.95    4590  317.85  4611.2  318.05
  4745.6  302.32  4869.8  293.29  4950.6  290.84    4986  287.32  5004.2  280.53
  5006.9  280.03  5010.2  280.53  5014.3  285.54  5021.3  290.79  5060.5  291.36
  5148.6  296.67    5184  303.86  5240.5  312.06    5283  321.31  5304.2  323.71
  5311.3  326.05  5318.3  325.43  5325.4  327.62  5346.6  328.58  5353.7  331.19
  5374.9  330.77    5382  332.54  5417.3  333.35  5424.4   335.3  5501.2  339.33
#Mann= 5 ,-1 , 0
  4450.4     .16       0  4869.8     .12       0  5004.2     .07       0
  5010.2     .12       0  5060.5     .16       0
Bank Sta=4950.6,5021.3
XS Rating Curve= 0 ,0
Exp/Cntr=0.3,0.1

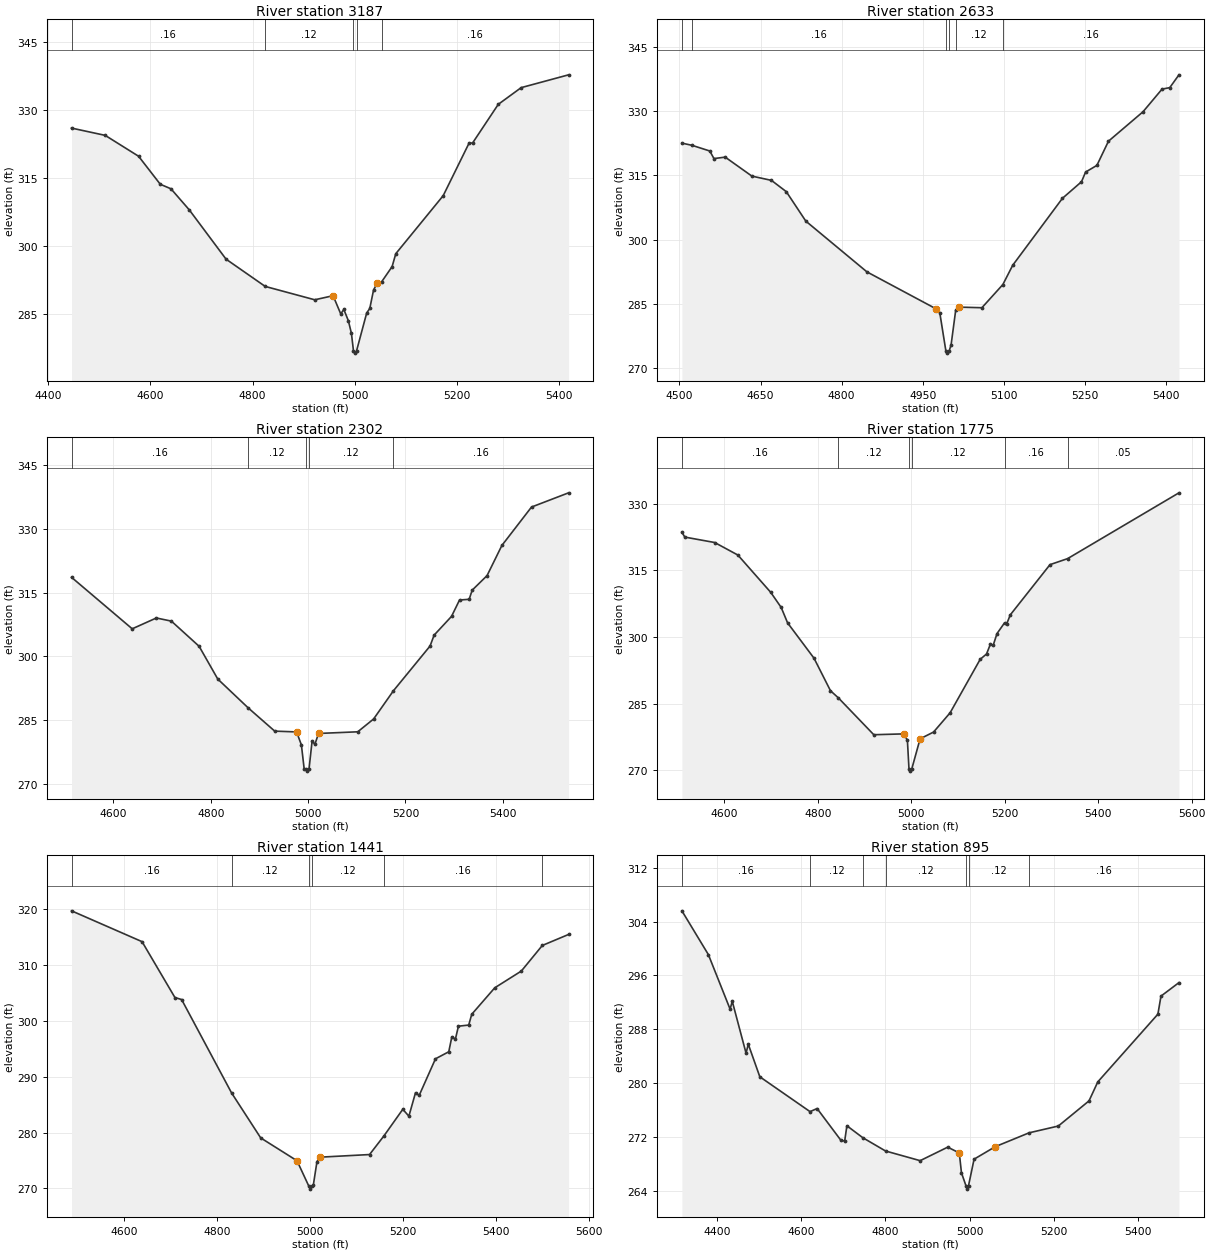
Type RM Length L Ch R = 1 ,3187    ,554,554,554
BEGIN DESCRIPTION:
UNT101 IN BECR 7.0
END DESCRIPTION:
XS GIS Cut Line= 2
      3766108.08     10547122.99       3765304.2     10546575.52
#Sta/Elev= 30
  4445.6  326.09  4511.5  324.48  4576.8  319.87  4619.3  313.68  4640.2  312.68
  4676.2     308    4748  297.14  4824.6  291.12  4921.5  288.17  4957.4  289.07
  4972.4  285.05  4978.4  286.04  4987.3  283.54  4993.3  280.74  4997.3  276.89
    5000  276.39  5003.3  276.89  5023.2  285.27  5029.2  286.25  5036.6  290.34
  5044.2  291.94  5052.4  292.14  5072.9   295.5  5080.1  298.35  5172.9  311.17
  5223.7  322.82  5230.2  322.77  5280.6  331.33  5325.4  335.02  5418.2  337.85
#Mann= 5 ,-1 , 0
  4445.6     .16       0  4824.6     .12       0  4997.3     .07       0
  5003.3     .12       0  5052.4     .16       0
Bank Sta=4957.4,5044.2
XS Rating Curve= 0 ,0
Exp/Cntr=0.3,0.1

Type RM Length L Ch R = 1 ,2633    ,331,331,331
BEGIN DESCRIPTION:
UNT101 IN BECR 6.0
END DESCRIPTION:
XS GIS Cut Line= 2
      3766374.85     10546797.97      3765681.21     10546194.51
#Sta/Elev= 30
  4504.5  322.56  4523.2  322.05  4556.1  320.72  4563.8  318.95  4584.6  319.29
    4634  314.85  4670.1  313.86  4697.6  311.22  4733.7  304.34  4846.7  292.48
  4974.9  283.82  4981.5  282.93  4992.8  273.99  4995.5  273.49  4998.8  273.99
  5002.4   275.4    5011  283.57  5016.6  284.24  5059.4   284.1  5098.2  289.52
  5116.4  294.02  5208.4  309.67  5243.6  313.53  5251.2   315.8  5272.1  317.36
  5293.5  323.01  5357.5   329.9  5392.6  335.18  5406.9  335.53  5423.9  338.52
#Mann= 6 ,-1 , 0
  4504.5     .05       0  4523.2     .16       0  4992.8     .07       0
  4998.8     .16       0    5011     .12       0  5098.2     .16       0
Bank Sta=4974.9,5016.6
XS Rating Curve= 0 ,0
Exp/Cntr=0.3,0.1

Type RM Length L Ch R = 1 ,2302    ,527,527,527
BEGIN DESCRIPTION:
UNT101 IN BECR 5.0
END DESCRIPTION:
XS GIS Cut Line= 4
      3766455.31     10546581.32       3766281.7     10546254.95
      3765885.87     10546046.61      3765684.53     10546081.33
#Sta/Elev= 30
    4514  318.61  4638.7  306.48  4688.3  309.03  4719.2  308.29  4776.2  302.36
  4814.5  294.65    4877  287.86  4931.5  282.39  4976.4   282.2  4986.3  279.15
    4992  273.51    4996  273.47  4998.8  272.97    5002  273.47  5008.3  280.06
    5014  279.28  5021.6  281.84  5102.1  282.23  5134.7  285.25  5175.4  291.89
  5250.7  302.43    5259  304.99  5294.8  309.41  5311.2  313.26    5331  313.43
  5337.3  315.59  5367.8  319.01  5398.2   326.1  5459.1  335.15  5535.3   338.5
#Mann= 5 ,-1 , 0
    4514     .16       0    4877     .12       0    4996     .07       0
    5002     .12       0  5175.4     .16       0
Bank Sta=4976.4,5021.6
XS Rating Curve= 0 ,0
Exp/Cntr=0.3,0.1

Type RM Length L Ch R = 1 ,1775    ,334,334,334
BEGIN DESCRIPTION:
UNT101 IN BECR 4.0
END DESCRIPTION:
XS GIS Cut Line= 3
      3766872.01     10546275.82      3766302.54     10545574.39
      3766149.78     10545525.79
#Sta/Elev= 30
  4509.1  323.58  4515.4  322.49  4579.3  321.27  4628.9  318.45  4699.2  310.06
  4721.6  306.66  4735.3  303.19  4791.9  295.23  4827.1  287.92  4844.1   286.3
  4919.8  278.02  4983.7  278.21  4991.7  276.81  4995.1  270.33  4997.8  269.83
  5001.1  270.33  5018.9   277.1  5047.7  278.62  5083.1  282.95  5147.5  294.99
  5161.1  296.19  5169.1  298.33  5175.5   298.2  5183.5  300.78  5199.7  303.21
  5204.3  302.98  5211.9  304.99  5296.9  316.29  5334.5  317.64  5572.9  332.45
#Mann= 6 ,-1 , 0
  4509.1     .16       0  4844.1     .12       0  4995.1     .07       0
  5001.1     .12       0  5199.7     .16       0  5334.5     .05       0
Bank Sta=4983.7,5018.9
XS Rating Curve= 0 ,0
Exp/Cntr=0.3,0.1

Type RM Length L Ch R = 1 ,1441    ,546,546,546
BEGIN DESCRIPTION:
UNT101 IN BECR 3.0
END DESCRIPTION:
XS GIS Cut Line= 3
       3766969.2      10546220.2      3766913.65     10545845.22
      3766469.18     10545317.41
#Sta/Elev= 30
  4486.8   319.7  4638.5  314.18  4709.2  304.18  4723.6  303.82    4831  287.11
  4893.7  279.05  4971.8  274.96  4997.4  270.38  5000.1  269.88  5003.4  270.38
  5006.9  270.61  5014.7   274.8  5021.2   275.6  5127.8  276.07  5158.4  279.37
  5199.3  284.17  5212.4  282.94  5226.7  287.15  5234.5  286.65  5269.6  293.21
  5298.2  294.47  5304.7  297.11  5312.5  296.75    5319  299.05  5341.1  299.25
  5347.6  301.18  5397.1  305.92  5454.3  308.92  5499.4   313.5  5555.9  315.47
#Mann= 6 ,-1 , 0
  4486.8     .16       0    4831     .12       0  4997.4     .07       0
  5003.4     .12       0  5158.4     .16       0  5499.4     .05       0
Bank Sta=4971.8,5021.2
XS Rating Curve= 0 ,0
Exp/Cntr=0.3,0.1

Type RM Length L Ch R = 1 ,895     ,667,667,667
BEGIN DESCRIPTION:
UNT101 IN BECR 2.0
END DESCRIPTION:
XS GIS Cut Line= 3
       3767349.6     10545960.16      3767149.61     10545310.19
      3766749.65     10545010.22
#Sta/Elev= 30
  4316.8   305.6  4379.6   299.1  4431.2  290.99  4436.4  292.15  4469.1  284.44
  4474.4  285.77  4501.8  280.93    4621  275.75  4637.8  276.21  4693.4  271.56
  4703.2  271.36  4708.5  273.65  4746.1  271.88  4800.2   269.9  4882.4  268.46
  4947.8  270.47  4975.3  269.61  4980.5  266.65  4991.2  264.73    4994  264.23
  4997.2  264.73  5010.4  268.68  5060.4  270.53    5141   272.6  5210.4  273.61
  5283.3  277.35  5304.1  280.17  5446.8  290.24  5454.1  292.92  5496.8  294.93
#Mann= 7 ,-1 , 0
  4316.8     .16       0    4621     .12       0  4746.1     .16       0
  4800.2     .12       0  4991.2     .07       0  4997.2     .12       0
    5141     .16       0
Bank Sta=4975.3,5060.4
XS Rating Curve= 0 ,0
Exp/Cntr=0.3,0.1

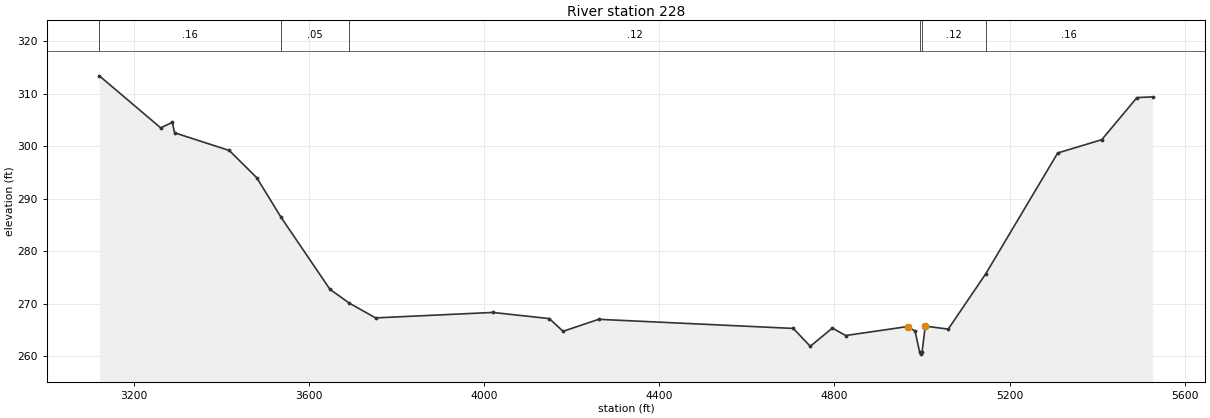
Type RM Length L Ch R = 1 ,228     ,0,0,0
BEGIN DESCRIPTION:
UNT101 IN BECR 1.0
END DESCRIPTION:
XS GIS Cut Line= 4
      3768062.48     10546174.47      3767628.46     10544724.83
      3767081.58     10544646.71      3766743.79     10544681.35
#Sta/Elev= 30
  3121.5  313.43  3261.7   303.5  3288.1  304.56  3293.3  302.57  3418.2  299.19
  3480.9     294  3536.4  286.45  3647.9  272.73  3692.3  270.07  3752.3  267.26
  4019.5   268.3  4148.9  267.13  4180.3   264.7  4261.6  266.99  4706.1  265.25
  4744.7  261.84  4795.2  265.32  4825.5   263.9  4966.9  265.61  4983.9  264.76
  4994.2  260.85    4997  260.35  5000.2  260.85  5007.3  265.69  5059.7  265.12
  5145.5  275.68  5309.8  298.72  5410.3  301.25  5490.7  309.28  5526.7  309.42
#Mann= 6 ,-1 , 0
  3121.5     .16       0  3536.4     .05       0  3692.3     .12       0
  4994.2     .07       0  5000.2     .12       0  5145.5     .16       0
Bank Sta=4966.9,5007.3
XS Rating Curve= 0 ,0
Exp/Cntr=0.3,0.1

Chan Stop Cuts=-1
Use User Specified Reach Order=0
Composite Channel Slope=5