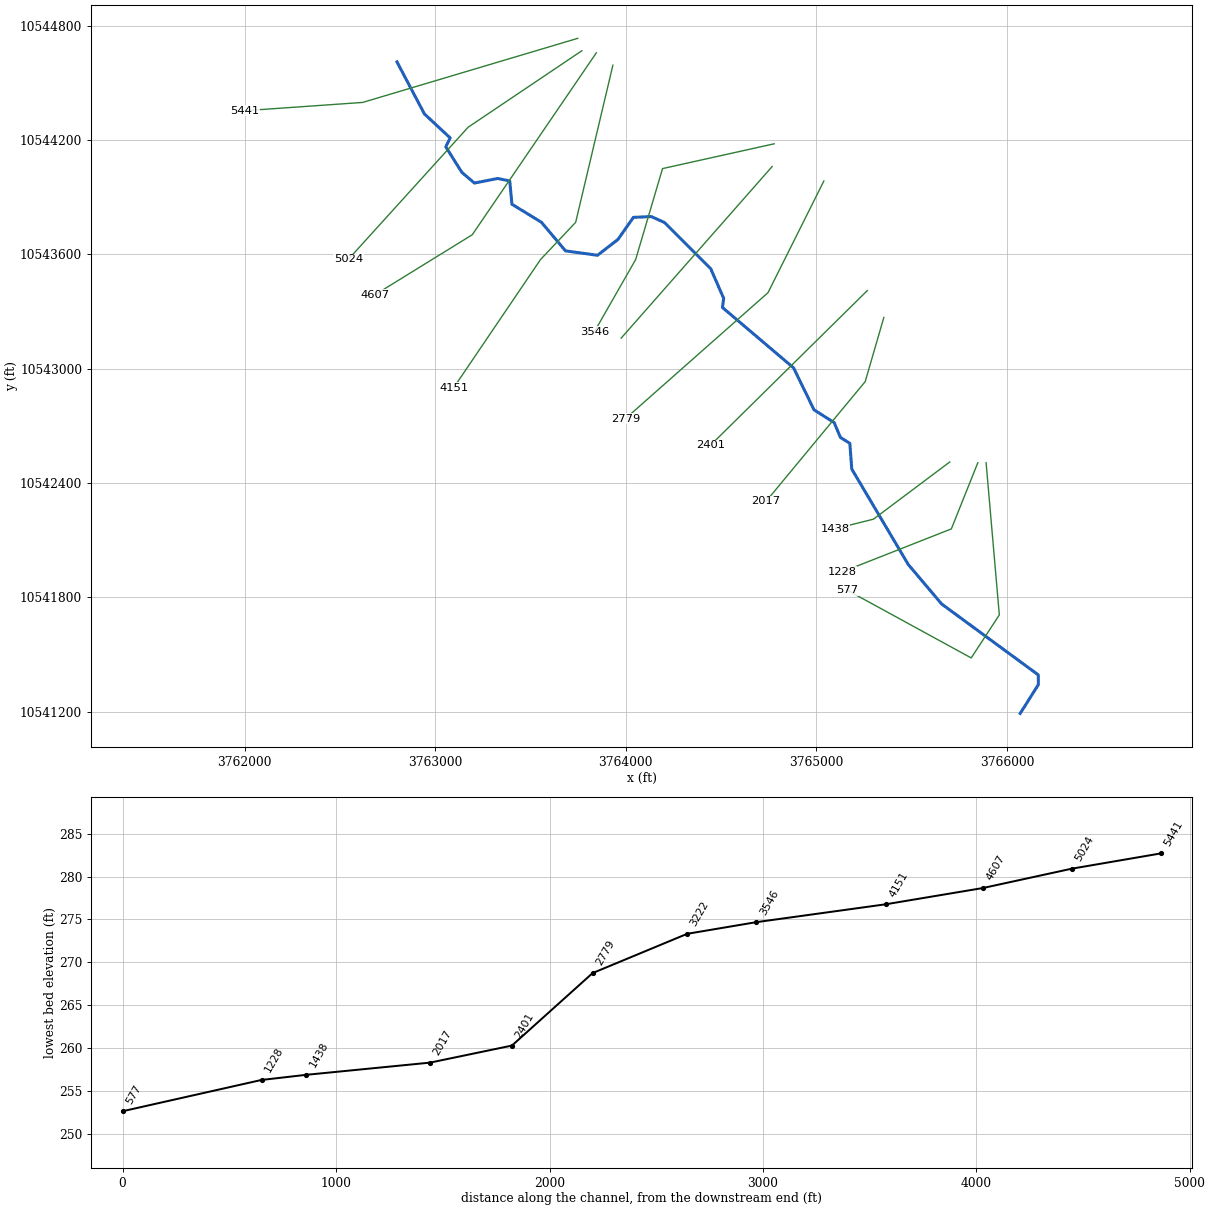
--- UNT103 IN BECR.prj (project) ---

Proj Title=UNT103 IN BECR Base Level Engineering
Current Plan=p01
Default Exp/Contr=0.3,0.1
English Units
Geom File=g01
Flow File=f01
Plan File=p01
BEGIN DESCRIPTION:
UNT103 IN BECR
END DESCRIPTION:

--- UNT103 IN BECR.p01 (plan) ---

Plan Title=Multiple Run
Short Identifier=Multiple
Geom File=g01
Flow File=f01
Subcritical Flow
K Sum by GR= 0
Std Step Tol= 0.01
Critical Tol= 0.01
Num of Std Step Trials= 20
Max Error Tol= 0.3
Flow Tol Ratio= 0.001
Split Flow NTrial= 30
Split Flow Tol= 0.02
Split Flow Ratio= 0.02
Log Output Level= 0
Friction Slope Method= 1
Unsteady Friction Slope Method= 2
Unsteady Bridges Friction Slope Method= 1
Parabolic Critical Depth
Global Vel Dist=  1 , 1 , 1
Global Log Level= 0
CheckData=True
Encroach Param= -1, 0, 0, 0
BEGIN DESCRIPTION:
Multiple Run
END DESCRIPTION:

--- UNT103 IN BECR.f01 (steady flow) ---

Flow Title=Multiple
Number of Profiles=7
Profile Names=10-year,25-year,50-year,1pct_min,100-year,1pct_plu,500-year
River Rch & RM= UNT103 IN BECR,Reach-1,5441
     720     999    1236    1126    1523    2059    2316
River Rch & RM= UNT103 IN BECR,Reach-1,5024
     794    1102    1363    1239    1676    2267    2543
Boundary for River Rch & Prof#=UNT103 IN BECR,Reach-1,1
Up Type=0
Dn Type=3
Dn Slope=0.005
Boundary for River Rch & Prof#=UNT103 IN BECR,Reach-1,2
Up Type=0
Dn Type=3
Dn Slope=0.005
Boundary for River Rch & Prof#=UNT103 IN BECR,Reach-1,3
Up Type=0
Dn Type=3
Dn Slope=0.005
Boundary for River Rch & Prof#=UNT103 IN BECR,Reach-1,4
Up Type=0
Dn Type=3
Dn Slope=0.005
Boundary for River Rch & Prof#=UNT103 IN BECR,Reach-1,5
Up Type=0
Dn Type=3
Dn Slope=0.005
Boundary for River Rch & Prof#=UNT103 IN BECR,Reach-1,6
Up Type=0
Dn Type=3
Dn Slope=0.005
Boundary for River Rch & Prof#=UNT103 IN BECR,Reach-1,7
Up Type=0
Dn Type=3
Dn Slope=0.005

--- UNT103 IN BECR.g01 (geometry) ---

Geom Title=Existing Conditions

River Reach=UNT103 IN BECR,Reach-1
Reach XY= 30
      3762799.61     10544610.19      3762943.50     10544337.00
      3763078.75     10544211.00      3763056.00     10544164.00
      3763140.25     10544030.00      3763206.00     10543974.00
      3763328.00     10543998.00      3763391.50     10543985.00
      3763402.75     10543863.00      3763557.75     10543768.00
      3763684.00     10543618.00      3763852.00     10543595.00
      3763959.00     10543678.00      3764040.25     10543794.00
      3764134.25     10543798.00      3764203.00     10543767.00
      3764446.00     10543524.00      3764513.75     10543369.00
      3764507.25     10543321.00      3764880.50     10543004.00
      3764987.75     10542784.00      3765093.25     10542717.00
      3765126.25     10542639.00      3765175.50     10542608.00
      3765185.75     10542473.00      3765482.25     10541972.00
      3765657.25     10541765.00      3766164.25     10541393.00
      3766164.75     10541342.00      3766069.50     10541191.00

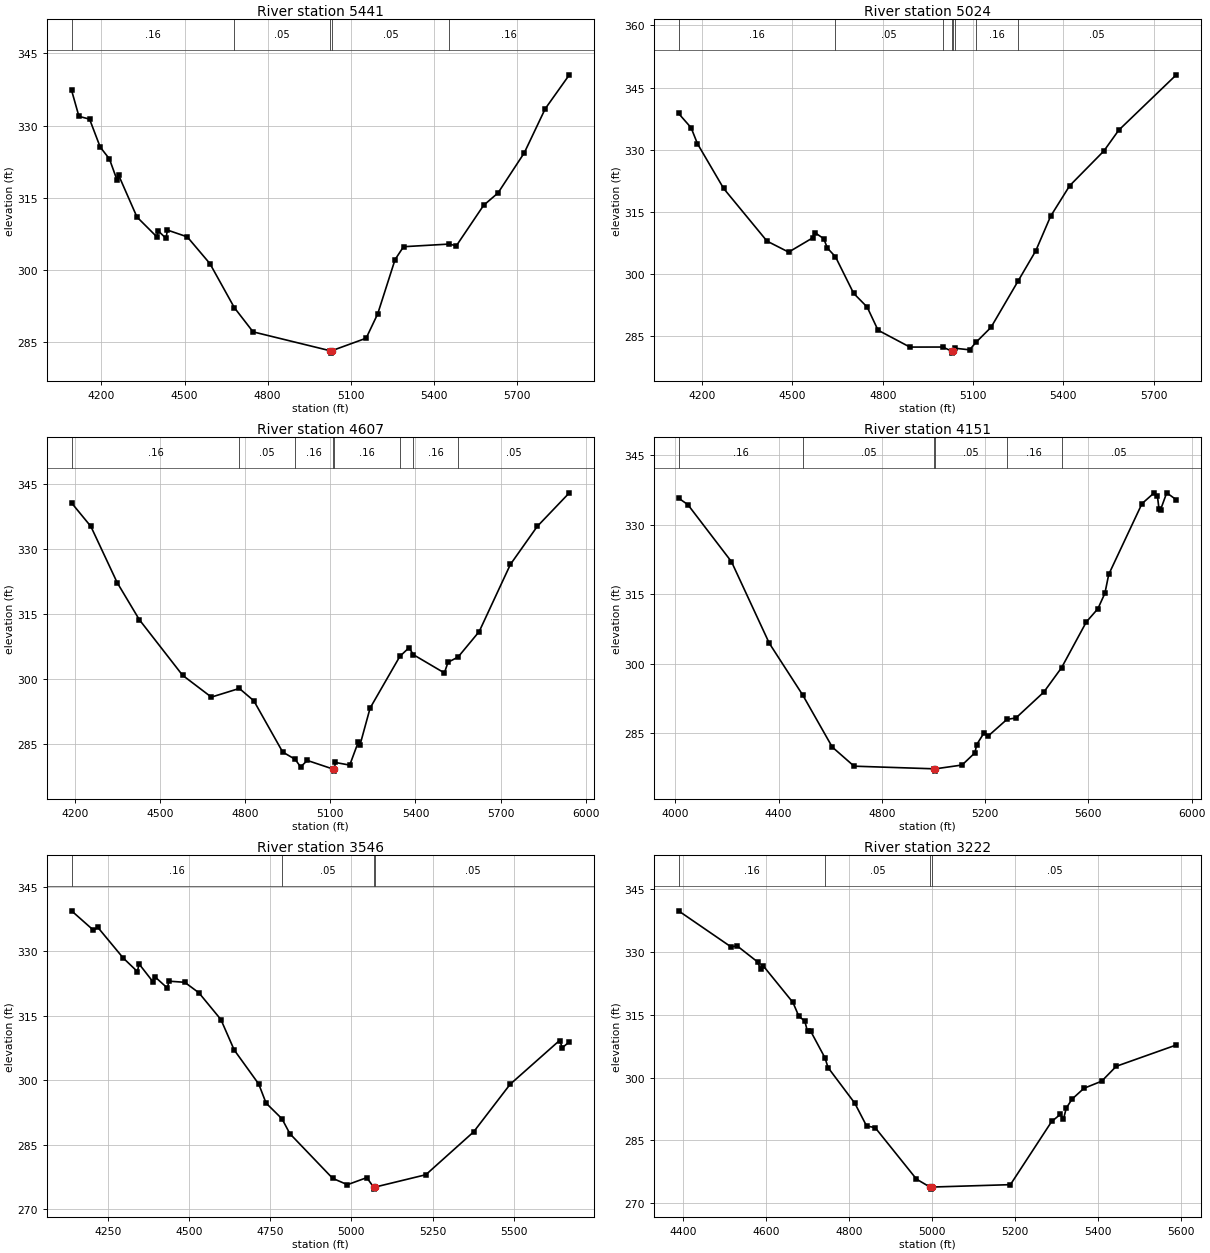
Type RM Length L Ch R = 1,5441,417,417,417
BEGIN DESCRIPTION:
UNT103 IN BECR 11.0
END DESCRIPTION:
XS GIS Cut Line= 3
      3763748.05     10544733.42      3762619.58     10544397.05
      3762002.83     10544353.77
#Sta/Elev= 30
  4092.5  337.35  4119.1  331.92  4157.5  331.34  4195.9  325.52  4229.0  323.08
  4257.0  318.61  4262.2  319.70  4328.5  310.99  4400.0  306.88  4405.3  308.10
  4433.2  306.56  4438.4  308.28  4509.9  306.87  4591.7  301.30  4679.9  292.14
  4747.3  287.12  5025.1  283.20  5027.9  282.70  5031.1  283.20  5155.2  285.80
  5197.0  290.87  5259.6  302.15  5290.1  304.82  5454.8  305.37  5480.5  305.00
  5579.1  313.43  5630.9  315.99  5725.7  324.33  5801.3  333.50  5888.3  340.55
#Mann=5,-1,0
  4092.5    0.16       0  4679.9    0.05       0  5025.1    0.03       0
  5031.1    0.05       0  5454.8    0.16       0
Bank Sta=5025.1,5031.1
Exp/Cntr=0.3,0.1

Type RM Length L Ch R = 1,5024,417,417,417
BEGIN DESCRIPTION:
UNT103 IN BECR 10.0
END DESCRIPTION:
XS GIS Cut Line= 3
      3763769.76     10544668.33      3763172.97     10544266.85
      3762545.41     10543574.37
#Sta/Elev= 30
  4121.6  338.76  4163.5  335.29  4184.5  331.45  4271.5  320.65  4415.5  307.95
  4487.5  305.29  4567.7  308.74  4574.4  310.01  4603.9  308.54  4616.4  306.25
  4643.1  304.16  4703.4  295.35  4748.4  292.03  4784.4  286.46  4890.3  282.38
  4999.1  282.39  5029.0  281.42  5031.8  280.92  5035.0  281.42  5041.1  282.09
  5088.8  281.72  5109.4  283.49  5159.8  287.14  5250.3  298.38  5308.5  305.60
  5357.8  313.94  5421.3  321.32  5534.9  329.70  5584.2  334.71  5775.4  348.06
#Mann=8,-1,0
  4121.6    0.16       0  4643.1    0.05       0  4999.1    0.16       0
  5029.0    0.07       0  5035.0    0.16       0  5041.1    0.12       0
  5109.4    0.16       0  5250.3    0.05       0
Bank Sta=5029,5035
Exp/Cntr=0.3,0.1

Type RM Length L Ch R = 1,4607,456,456,456
BEGIN DESCRIPTION:
UNT103 IN BECR 9.0
END DESCRIPTION:
XS GIS Cut Line= 3
      3763845.70     10544657.45      3763194.67     10543702.61
      3762684.70     10543387.95
#Sta/Elev= 30
  4187.6  340.59  4255.7  335.16  4348.5  322.18  4426.4  313.64  4578.9  300.80
  4680.5  295.75  4779.1  297.75  4830.2  294.90  4931.9  283.07  4975.8  281.39
  4995.2  279.63  5018.6  281.13  5108.4  279.16  5111.1  278.66  5114.4  279.16
  5117.4  280.66  5168.3  280.05  5198.1  285.33  5204.2  284.63  5240.1  293.22
  5345.2  305.18  5377.5  307.16  5392.3  305.56  5502.0  301.33  5514.7  303.80
  5550.2  305.00  5624.7  310.89  5734.7  326.39  5829.3  335.16  5942.5  342.92
#Mann=8,-1,0
  4187.6    0.16       0  4779.1    0.05       0  4975.8    0.16       0
  5108.4    0.07       0  5114.4    0.16       0  5345.2    0.12       0
  5392.3    0.16       0  5550.2    0.05       0
Bank Sta=5108.4,5114.4
Exp/Cntr=0.3,0.1

Type RM Length L Ch R = 1,4151,605,605,605
BEGIN DESCRIPTION:
UNT103 IN BECR 8.0
END DESCRIPTION:
XS GIS Cut Line= 4
      3763932.51     10544592.35      3763737.20     10543767.71
      3763552.74     10543572.40      3763097.00     10542899.64
#Sta/Elev= 30
  4011.9  335.75  4048.1  334.34  4217.1  322.01  4363.5  304.40  4493.4  293.18
  4607.6  281.96  4692.1  277.83  5001.6  277.26  5004.3  276.76  5007.6  277.26
  5110.6  278.08  5160.6  280.73  5166.9  282.46  5196.5  285.10  5211.5  284.33
  5284.2  287.93  5319.3  288.25  5427.2  293.83  5496.2  299.12  5592.0  308.99
  5636.8  311.85  5663.9  315.18  5678.8  319.26  5807.7  334.56  5852.5  336.77
  5867.5  336.16  5873.5  333.43  5879.6  333.23  5903.4  336.89  5940.6  335.40
#Mann=6,-1,0
  4011.9    0.16       0  4493.4    0.05       0  5001.6    0.03       0
  5007.6    0.05       0  5284.2    0.16       0  5496.2    0.05       0
Bank Sta=5001.6,5007.6
Exp/Cntr=0.3,0.1

Type RM Length L Ch R = 1,3546,324,324,324
BEGIN DESCRIPTION:
UNT103 IN BECR 7.0
END DESCRIPTION:
XS GIS Cut Line= 4
      3764778.86     10544180.04      3764192.93     10544049.83
      3764051.87     10543572.40      3763835.58     10543193.89
#Sta/Elev= 30
  4137.6  339.40  4204.7  334.92  4218.8  335.53  4296.9  328.42  4340.5  325.27
  4345.6  327.05  4389.1  322.84  4394.2  324.08  4432.7  321.45  4437.8  323.04
  4486.4  322.78  4530.0  320.34  4597.8  314.12  4638.8  307.04  4714.4  299.12
  4737.0  294.69  4786.0  291.04  4810.4  287.57  4942.2  277.19  4987.7  275.71
  5047.3  277.35  5068.1  275.18  5070.9  274.68  5074.1  275.18  5229.4  278.03
  5376.7  288.00  5489.0  299.05  5641.3  309.24  5650.2  307.59  5671.6  308.93
#Mann=4,-1,0
  4137.6    0.16       0  4786.0    0.05       0  5068.1    0.03       0
  5074.1    0.05       0
Bank Sta=5068.1,5074.1
Exp/Cntr=0.3,0.1

Type RM Length L Ch R = 1,3222,443,443,443
BEGIN DESCRIPTION:
UNT103 IN BECR 6.0
END DESCRIPTION:
XS GIS Cut Line= 2
      3764768.05     10544060.71      3763975.93     10543160.09
#Sta/Elev= 30
  4389.7  339.89  4516.5  331.25  4530.7  331.52  4580.1  327.68  4587.6  325.91
  4594.3  326.67  4665.4  317.98  4679.7  314.66  4693.9  313.53  4700.5  311.04
  4708.1  311.11  4742.6  304.72  4750.0  302.40  4814.4  293.88  4842.8  288.44
  4863.7  288.01  4963.1  275.71  4995.5  273.82  4998.2  273.32  5001.5  273.82
  5189.4  274.39  5288.8  289.50  5309.7  291.20  5317.3  290.08  5323.9  292.69
  5338.1  294.87  5366.6  297.44  5409.3  299.14  5444.4  302.70  5589.1  307.80
#Mann=4,-1,0
  4389.7    0.16       0  4742.6    0.05       0  4995.5    0.03       0
  5001.5    0.05       0
Bank Sta=4995.5,5001.5
Exp/Cntr=0.3,0.1

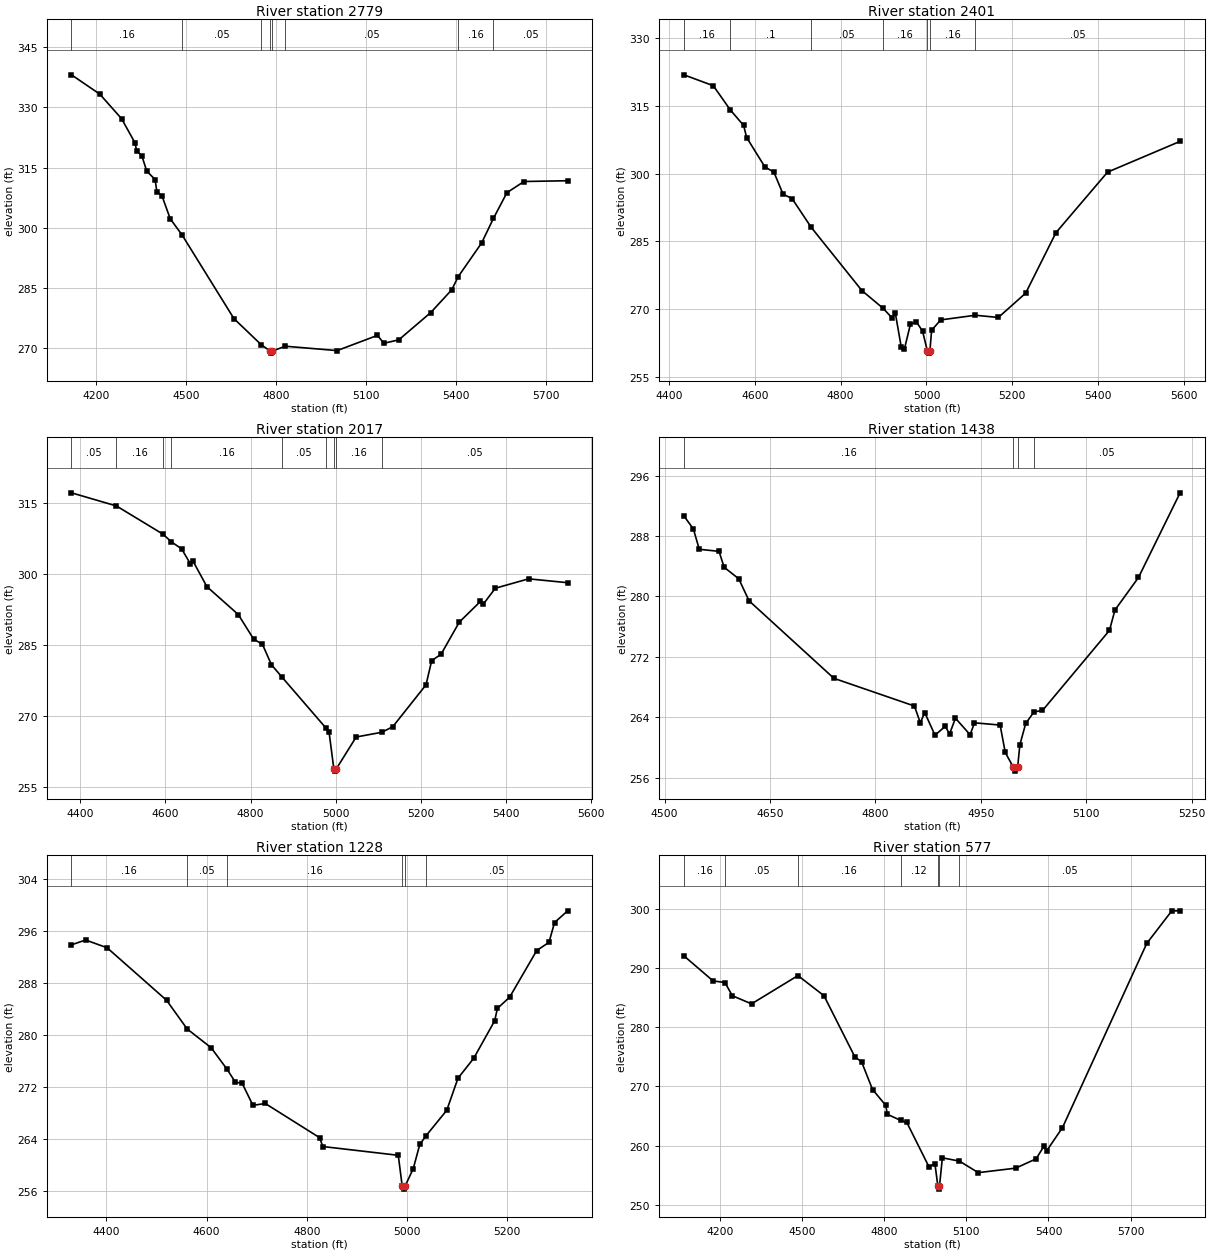
Type RM Length L Ch R = 1,2779,378,378,378
BEGIN DESCRIPTION:
UNT103 IN BECR 5.0
END DESCRIPTION:
XS GIS Cut Line= 3
      3765039.29     10543984.73      3764746.32     10543398.79
      3763997.64     10542736.91
#Sta/Elev= 30
  4117.5  338.11  4211.9  333.30  4284.6  327.17  4329.3  321.15  4335.0  319.09
  4351.7  318.00  4368.4  314.13  4396.4  312.00  4402.1  309.00  4418.8  308.02
  4446.8  302.23  4486.9  298.12  4659.1  277.35  4749.8  270.86  4780.1  269.24
  4782.9  268.74  4786.1  269.24  4830.7  270.46  5003.1  269.37  5137.8  273.17
  5158.7  271.19  5208.7  272.05  5315.2  278.84  5385.4  284.53  5406.6  287.77
  5485.0  296.20  5524.4  302.34  5569.4  308.74  5626.3  311.52  5771.9  311.71
#Mann=8,-1,0
  4117.5    0.16       0  4486.9    0.05       0  4749.8    0.16       0
  4780.1    0.03       0  4786.1    0.16       0  4830.7    0.05       0
  5406.6    0.16       0  5524.4    0.05       0
Bank Sta=4780.1,4786.1
Exp/Cntr=0.3,0.1

Type RM Length L Ch R = 1,2401,384,384,384
BEGIN DESCRIPTION:
UNT103 IN BECR 4.0
END DESCRIPTION:
XS GIS Cut Line= 2
      3765267.17     10543409.66      3764443.58     10542596.91
#Sta/Elev= 30
  4434.4  321.85  4503.0  319.44  4542.7  314.08  4573.7  310.65  4580.8  307.97
  4623.2  301.49  4644.4  300.30  4665.7  295.45  4686.8  294.45  4731.3  288.11
  4849.5  274.12  4898.4  270.24  4920.2  268.04  4927.3  269.22  4941.4  261.55
  4948.5  261.13  4962.7  266.69  4976.8  267.17  4991.0  265.13  5002.1  260.78
  5004.9  260.28  5008.1  260.78  5012.1  265.36  5033.4  267.63  5114.1  268.66
  5167.7  268.17  5231.4  273.55  5302.0  286.93  5422.3  300.32  5591.5  307.13
#Mann=7,-1,0
  4434.4    0.16       0  4542.7     0.1       0  4731.3    0.05       0
  4898.4    0.16       0  5002.1    0.07       0  5008.1    0.16       0
  5114.1    0.05       0
Bank Sta=5002.1,5008.1
Exp/Cntr=0.3,0.1

Type RM Length L Ch R = 1,2017,579,579,579
BEGIN DESCRIPTION:
UNT103 IN BECR 3.0
END DESCRIPTION:
XS GIS Cut Line= 3
      3765353.97     10543268.62      3765256.30     10542932.21
      3764736.42     10542304.03
#Sta/Elev= 30
  4379.2  317.18  4484.9  314.40  4594.2  308.43  4614.1  306.79  4637.9  305.33
  4658.7  302.13  4663.9  302.86  4697.4  297.32  4771.1  291.42  4807.0  286.24
  4827.9  285.11  4848.9  280.81  4872.8  278.28  4977.1  267.40  4984.2  266.64
  4995.5  258.79  4998.3  258.29  5001.5  258.79  5048.0  265.51  5108.6  266.52
  5134.0  267.69  5212.1  276.55  5225.4  281.68  5247.3  283.00  5290.3  289.82
  5339.8  294.19  5346.3  293.58  5374.9  296.99  5453.1  298.98  5544.9  298.16
#Mann=9,-1,0
  4379.2    0.05       0  4484.9    0.16       0  4594.2     0.1       0
  4614.1    0.16       0  4872.8    0.05       0  4977.1    0.16       0
  4995.5    0.07       0  5001.5    0.16       0  5108.6    0.05       0
Bank Sta=4995.5,5001.5
Exp/Cntr=0.3,0.1

Type RM Length L Ch R = 1,1438,210,210,210
BEGIN DESCRIPTION:
UNT103 IN BECR 2.0
END DESCRIPTION:
XS GIS Cut Line= 3
      3765699.60     10542510.18      3765299.61     10542210.19
      3765099.65     10542160.20
#Sta/Elev= 30
  4527.4  290.68  4540.9  288.94  4549.3  286.25  4577.4  285.98  4584.7  283.87
  4605.5  282.34  4620.1  279.43  4740.9  269.16  4855.5  265.49  4863.8  263.27
  4870.1  264.63  4884.7  261.63  4899.3  262.80  4905.5  261.80  4913.8  263.88
  4934.7  261.69  4940.9  263.27  4977.4  262.97  4984.7  259.34  4996.3  257.37
  4999.0  256.87  5002.3  257.37  5005.5  260.36  5013.8  263.18  5025.6  264.72
  5037.7  264.90  5133.0  275.51  5140.8  278.21  5174.3  282.52  5233.5  293.73
#Mann=4,-1,0
  4527.4    0.16       0  4996.3    0.07       0  5002.3    0.16       0
  5025.6    0.05       0
Bank Sta=4996.3,5002.3
Exp/Cntr=0.3,0.1

Type RM Length L Ch R = 1,1228,651,651,651
BEGIN DESCRIPTION:
Mapping XS d33cc5f8
END DESCRIPTION:
XS GIS Cut Line= 3
      3765847.03     10542506.24      3765708.16     10542159.06
      3765135.23     10541933.37
#Sta/Elev= 30
  4330.6  293.89  4358.7  294.64  4401.7  293.44  4520.2  285.36  4561.3  280.94
  4609.1  278.05  4641.2  274.70  4657.5  272.73  4671.0  272.58  4692.5  269.17
  4717.1  269.46  4825.4  264.20  4831.9  262.83  4982.4  261.48  4990.2  256.77
  4993.0  256.27  4996.2  256.77  5012.2  259.41  5025.4  263.17  5038.1  264.52
  5079.1  268.41  5101.5  273.35  5132.9  276.42  5174.7  282.20  5180.1  284.10
  5204.5  285.83  5258.6  293.02  5283.0  294.27  5294.1  297.33  5320.3  299.13
#Mann=6,-1,0
  4330.6    0.16       0  4561.3    0.05       0  4641.2    0.16       0
  4990.2    0.07       0  4996.2    0.16       0  5038.1    0.05       0
Bank Sta=4990.2,4996.2
Exp/Cntr=0.3,0.1

Type RM Length L Ch R = 1,577,0,0,0
BEGIN DESCRIPTION:
UNT103 IN BECR 1.0
END DESCRIPTION:
XS GIS Cut Line= 4
      3765890.45     10542506.30      3765959.89     10541707.67
      3765812.32     10541481.98      3765162.92     10541836.99
#Sta/Elev= 30
  4069.1  292.11  4175.6  287.87  4219.0  287.59  4245.9  285.36  4316.1  283.98
  4485.5  288.77  4580.5  285.36  4693.4  274.99  4717.6  274.19  4757.8  269.48
  4806.4  266.78  4811.4  265.30  4860.6  264.25  4883.0  263.90  4963.3  256.44
  4985.6  256.90  4996.2  253.12  4998.9  252.62  5002.2  253.12  5012.7  257.92
  5075.1  257.36  5143.7  255.41  5280.3  256.17  5354.9  257.75  5382.8  259.84
  5392.9  259.07  5451.2  263.04  5758.9  294.22  5850.1  299.72  5880.5  299.73
#Mann=7,-1,0
  4069.1    0.16       0  4219.0    0.05       0  4485.5    0.16       0
  4860.6    0.12       0  4996.2    0.07       0  5002.2    0.12       0
  5075.1    0.05       0
Bank Sta=4996.2,5002.2
Exp/Cntr=0.3,0.1

Chan Stop Cuts=-1