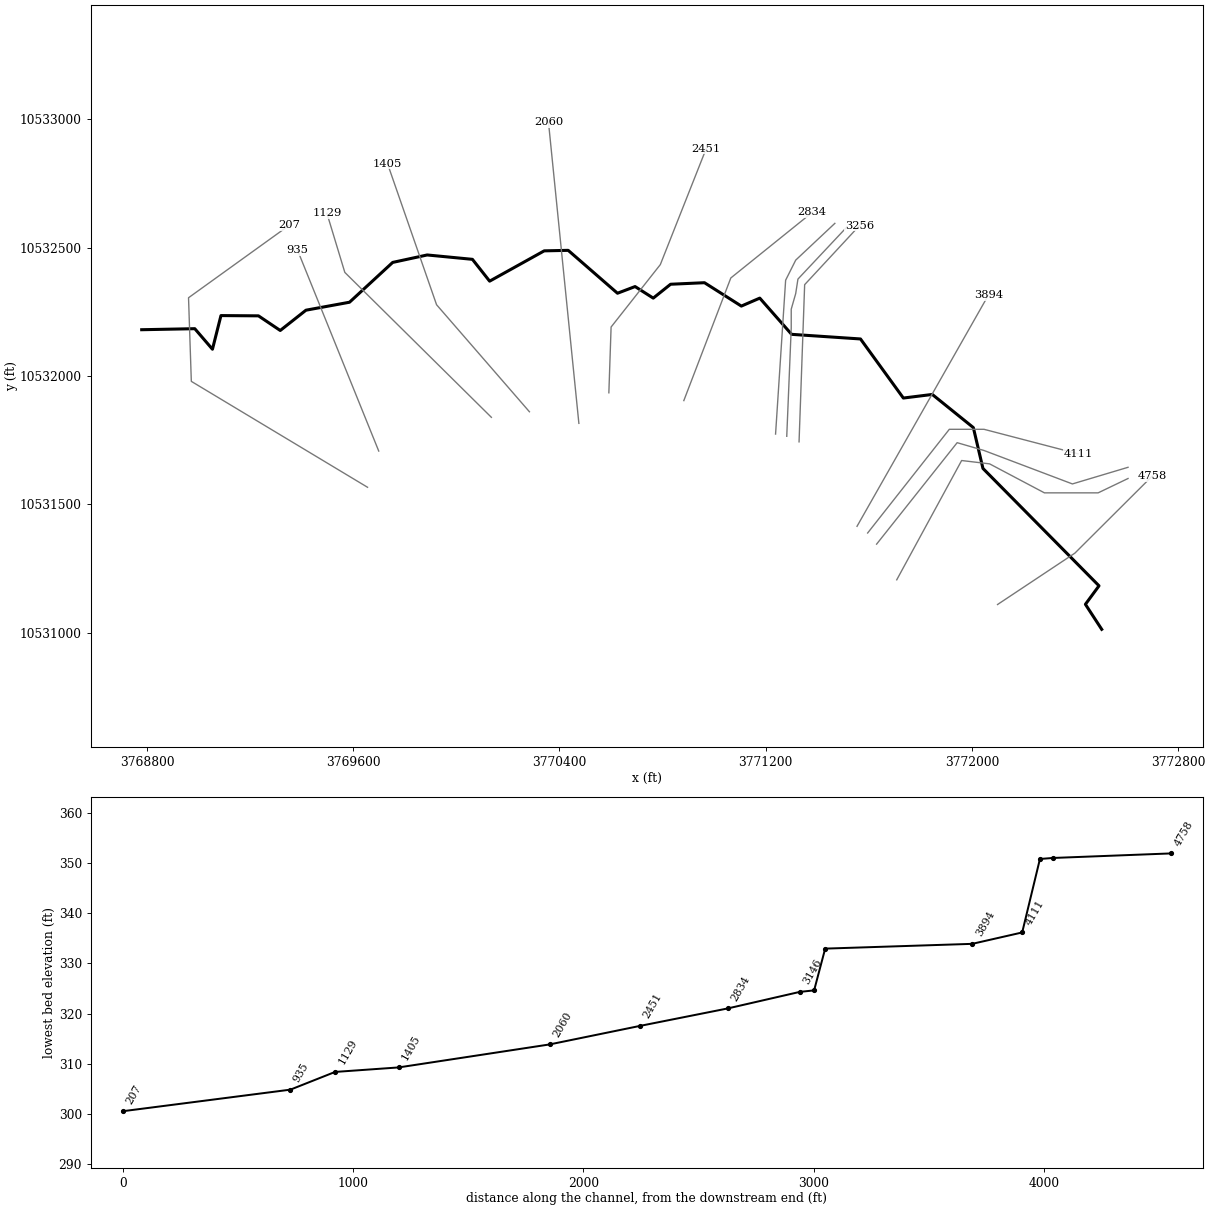
--- UNT105 IN BECR.prj (project) ---

Proj Title=UNT105 IN BECR Base Level Engineering
Current Plan=p01
Default Exp/Contr=0.3,0.1
English Units
Geom File=g01
Flow File=f01
Plan File=p01
BEGIN DESCRIPTION:
UNT105 IN BECR
END DESCRIPTION:

--- UNT105 IN BECR.p01 (plan) ---

Plan Title=Multiple Run
Short Identifier=Multiple
Geom File=g01
Flow File=f01
Subcritical Flow
K Sum by GR= 0
Std Step Tol= 0.01
Critical Tol= 0.01
Num of Std Step Trials= 20
Max Error Tol= 0.3
Flow Tol Ratio= 0.001
Split Flow NTrial= 30
Split Flow Tol= 0.02
Split Flow Ratio= 0.02
Log Output Level= 0
Friction Slope Method= 1
Unsteady Friction Slope Method= 2
Unsteady Bridges Friction Slope Method= 1
Parabolic Critical Depth
Global Vel Dist=  1 , 1 , 1
Global Log Level= 0
CheckData=True
Encroach Param= -1, 0, 0, 0
BEGIN DESCRIPTION:
Multiple Run
END DESCRIPTION:

--- UNT105 IN BECR.f01 (steady flow) ---

Flow Title=Multiple
Number of Profiles=7
Profile Names=10-year,25-year,50-year,1pct_min,100-year,1pct_plu,500-year
River Rch & RM= UNT105 IN BECR,Reach-1,4758
     501     673     814     725     980    1326    1426
Boundary for River Rch & Prof#=UNT105 IN BECR,Reach-1,1
Up Type=0
Dn Type=3
Dn Slope=0.005
Boundary for River Rch & Prof#=UNT105 IN BECR,Reach-1,2
Up Type=0
Dn Type=3
Dn Slope=0.005
Boundary for River Rch & Prof#=UNT105 IN BECR,Reach-1,3
Up Type=0
Dn Type=3
Dn Slope=0.005
Boundary for River Rch & Prof#=UNT105 IN BECR,Reach-1,4
Up Type=0
Dn Type=3
Dn Slope=0.005
Boundary for River Rch & Prof#=UNT105 IN BECR,Reach-1,5
Up Type=0
Dn Type=3
Dn Slope=0.005
Boundary for River Rch & Prof#=UNT105 IN BECR,Reach-1,6
Up Type=0
Dn Type=3
Dn Slope=0.005
Boundary for River Rch & Prof#=UNT105 IN BECR,Reach-1,7
Up Type=0
Dn Type=3
Dn Slope=0.005

--- UNT105 IN BECR.g01 (geometry) ---

Geom Title=Existing Conditions

River Reach=UNT105 IN BECR,Reach-1
Reach XY= 30
      3772503.73     10531013.62      3772440.50     10531111.00
      3772493.25     10531183.00      3772043.00     10531640.00
      3772005.75     10531799.00      3771846.50     10531928.00
      3771734.25     10531914.00      3771568.00     10532144.00
      3771300.75     10532162.00      3771177.25     10532303.00
      3771105.75     10532272.00      3770962.75     10532363.00
      3770831.25     10532357.00      3770764.00     10532303.00
      3770693.50     10532348.00      3770625.25     10532322.00
      3770434.00     10532489.00      3770341.00     10532487.00
      3770129.25     10532369.00      3770062.50     10532454.00
      3769887.00     10532471.00      3769753.25     10532442.00
      3769585.75     10532287.00      3769416.75     10532256.00
      3769317.00     10532177.00      3769232.50     10532234.00
      3769087.00     10532235.00      3769054.00     10532104.00
      3768985.50     10532184.00      3768779.50     10532180.00

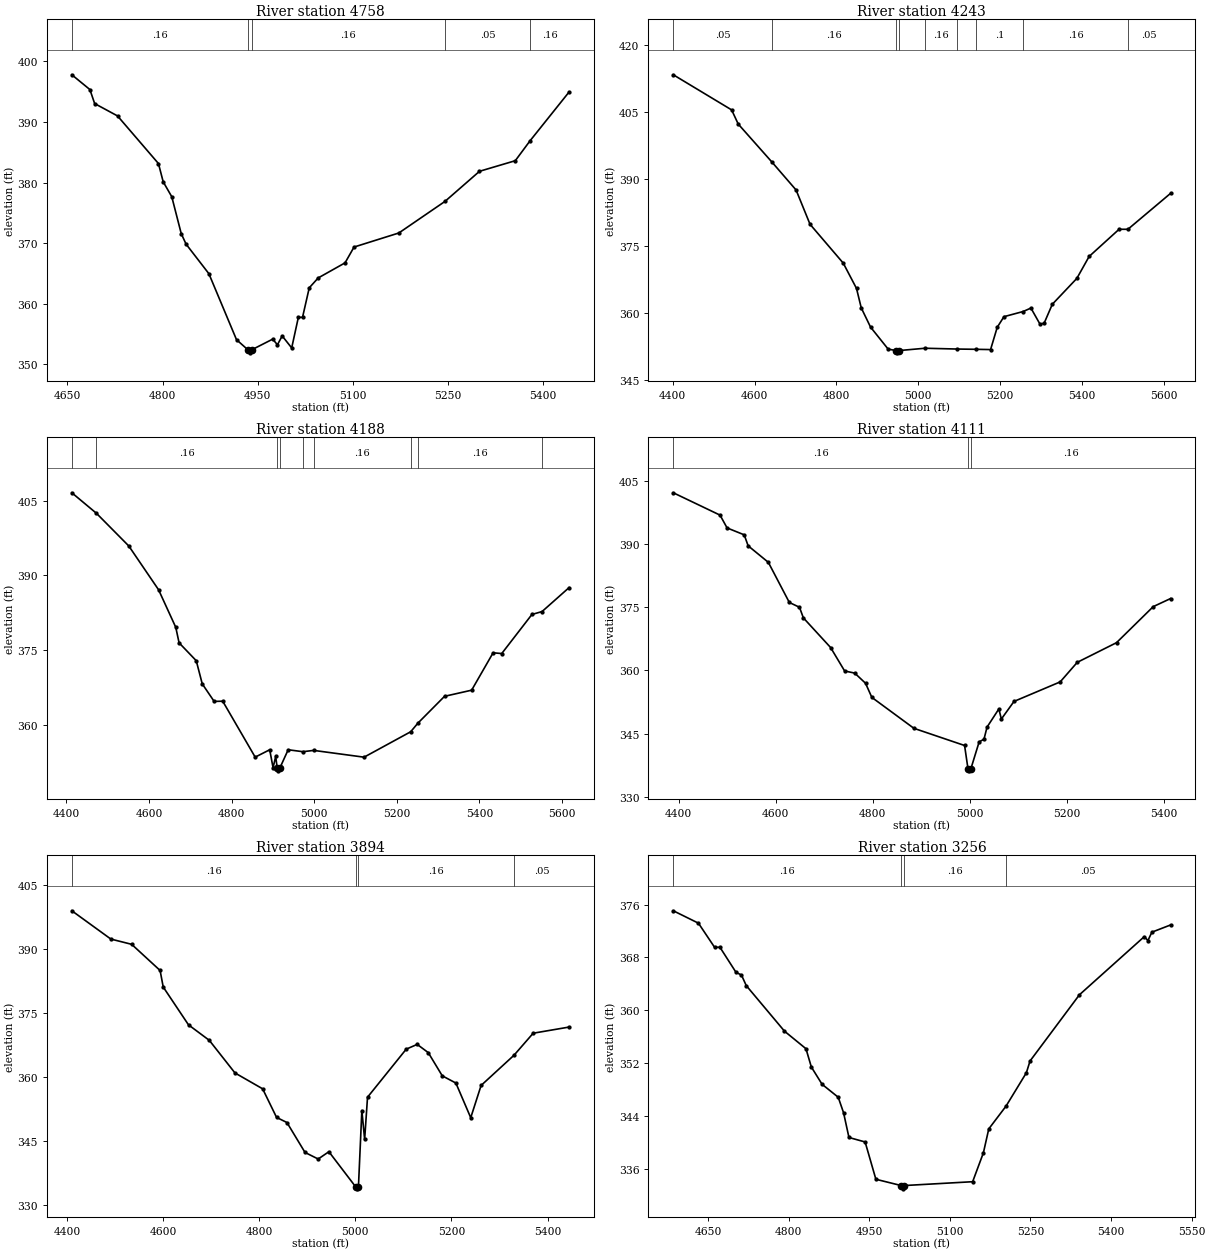
Type RM Length L Ch R = 1,4758,515,515,515
BEGIN DESCRIPTION:
UNT105 IN BECR 10.0
END DESCRIPTION:
XS GIS Cut Line= 3
      3772099.62     10531110.20      3772399.61     10531310.19
      3772699.61     10531610.19
#Sta/Elev= 30
  4656.9  397.79  4685.4  395.35  4692.9  393.04  4729.0  391.00  4793.6  383.14
  4801.1  380.12  4814.6  377.67  4829.6  371.56  4837.2  369.84  4873.2  364.96
  4916.8  354.07  4934.8  352.40  4937.6  351.90  4940.8  352.40  4973.9  354.16
  4981.4  353.23  4988.9  354.69  5003.9  352.71  5014.4  357.76  5021.0  357.76
  5031.6  362.63  5045.7  364.26  5088.1  366.75  5102.3  369.36  5173.0  371.68
  5245.8  376.89  5300.3  381.86  5356.8  383.61  5380.2  386.91  5441.7  394.95
#Mann=5,-1,0
  4656.9    0.16       0  4934.8    0.07       0  4940.8    0.16       0
  5245.8    0.05       0  5380.2    0.16       0
Bank Sta=4934.8,4940.8
Exp/Cntr=0.3,0.1

Type RM Length L Ch R = 1,4243,55,55,55
BEGIN DESCRIPTION:
Mapping XS c45d5e41
END DESCRIPTION:
XS GIS Cut Line= 6
      3771708.58     10531206.35      3771960.33     10531670.78
      3772068.83     10531657.76      3772281.51     10531544.91
      3772489.84     10531544.91      3772605.84     10531600.77
#Sta/Elev= 30
  4401.5  413.28  4544.1  405.41  4560.2  402.24  4641.7  393.82  4701.6  387.47
  4735.7  379.79  4816.9  371.09  4849.3  365.42  4860.9  361.06  4883.6  356.76
  4926.6  351.83  4946.2  351.49  4948.9  350.99  4952.2  351.49  5016.7  352.02
  5095.9  351.84  5142.4  351.78  5177.0  351.72  5193.3  356.72  5209.7  359.09
  5256.7  360.25  5275.6  361.02  5297.9  357.40  5307.9  357.62  5327.9  361.87
  5387.9  367.67  5417.9  372.58  5491.1  378.67  5512.7  378.67  5616.9  386.71
#Mann=9,-1,0
  4401.5    0.05       0  4641.7    0.16       0  4946.2   0.035       0
  4952.2    0.16       0  5016.7    0.16       0  5095.9    0.05       0
  5142.4     0.1       0  5256.7    0.16       0  5512.7    0.05       0
Bank Sta=4946.2,4952.2
Exp/Cntr=0.3,0.1

Type RM Length L Ch R = 1,4188,77,77,77
BEGIN DESCRIPTION:
UNT105 IN BECR 9.0
END DESCRIPTION:
XS GIS Cut Line= 5
      3771630.48     10531345.28      3771942.97     10531740.23
      3772047.13     10531709.84      3772390.02     10531579.64
      3772605.82     10531644.38
#Sta/Elev= 30
  4413.1  406.57  4472.6  402.46  4551.0  395.90  4623.1  387.12  4664.8  379.58
  4672.8  376.47  4714.4  372.88  4728.9  368.24  4757.7  364.72  4778.5  364.76
  4857.1  353.54  4892.3  355.02  4900.4  351.42  4906.8  353.68  4910.5  351.29
  4913.3  350.79  4916.5  351.29  4937.0  355.02  4972.6  354.63  4998.8  354.89
  5120.8  353.53  5233.7  358.63  5251.0  360.34  5315.7  365.74  5381.3  366.97
  5433.3  374.47  5454.2  374.32  5527.3  382.16  5551.8  382.74  5617.3  387.55
#Mann=9,-1,0
  4413.1    0.05       0  4472.6    0.16       0  4910.5    0.07       0
  4916.5    0.16       0  4972.6    0.05       0  4998.8    0.16       0
  5233.7     0.1       0  5251.0    0.16       0  5551.8    0.05       0
Bank Sta=4910.5,4916.5
Exp/Cntr=0.3,0.1

Type RM Length L Ch R = 1,4111,217,217,217
BEGIN DESCRIPTION:
Mapping XS d41f7065
END DESCRIPTION:
XS GIS Cut Line= 4
      3771595.73     10531388.64      3771912.58     10531792.31
      3772047.13     10531792.31      3772411.71     10531696.82
#Sta/Elev= 30
  4389.2  402.21  4485.5  396.90  4500.0  393.86  4535.3  392.22  4543.4  389.61
  4585.0  385.69  4628.3  376.15  4649.2  375.01  4657.2  372.49  4713.3  365.45
  4742.2  359.88  4763.0  359.37  4785.3  356.96  4798.3  353.60  4885.0  346.25
  4989.4  342.17  4996.4  336.65  4999.1  336.15  5002.4  336.65  5019.4  343.03
  5029.4  343.67  5035.7  346.54  5060.0  350.85  5065.2  348.46  5091.2  352.64
  5186.4  357.28  5221.6  361.93  5302.5  366.60  5378.1  375.16  5413.8  377.08
#Mann=3,-1,0
  4389.2    0.16       0  4996.4    0.07       0  5002.4    0.16       0
Bank Sta=4996.4,5002.4
Exp/Cntr=0.3,0.1

Type RM Length L Ch R = 1,3894,638,638,638
BEGIN DESCRIPTION:
UNT105 IN BECR 8.0
END DESCRIPTION:
XS GIS Cut Line= 2
      3771554.49     10531414.67      3772064.44     10532315.21
#Sta/Elev= 30
  4410.0  399.04  4491.2  392.41  4534.5  391.18  4593.7  385.05  4600.2  381.17
  4652.8  372.31  4696.1  368.68  4749.5  361.04  4807.1  357.32  4836.1  350.62
  4857.7  349.42  4895.3  342.41  4922.7  340.87  4945.0  342.58  5000.5  334.38
  5003.2  333.88  5006.5  334.38  5013.6  352.23  5019.4  345.46  5025.4  355.35
  5105.9  366.61  5128.8  367.73  5151.8  365.80  5181.0  360.36  5209.3  358.67
  5240.2  350.55  5261.8  358.11  5330.3  365.19  5370.2  370.35  5444.9  371.79
#Mann=4,-1,0
  4410.0    0.16       0  5000.5    0.07       0  5006.5    0.16       0
  5330.3    0.05       0
Bank Sta=5000.5,5006.5
Exp/Cntr=0.3,0.1

Type RM Length L Ch R = 1,3256,48,48,48
BEGIN DESCRIPTION:
UNT105 IN BECR 7.0
END DESCRIPTION:
XS GIS Cut Line= 3
      3771329.65     10531743.46      3771351.35     10532355.39
      3771563.89     10532585.28
#Sta/Elev= 30
  4585.3  375.06  4632.1  373.18  4662.1  369.53  4672.1  369.53  4702.1  365.72
  4712.1  365.33  4721.1  363.72  4792.2  356.82  4832.2  354.16  4842.2  351.39
  4862.2  348.77  4892.2  346.81  4902.2  344.45  4912.2  340.71  4942.3  340.03
  4962.3  334.38  5009.3  333.43  5012.1  332.93  5015.3  333.43  5142.4  334.01
  5162.4  338.39  5172.4  342.01  5204.6  345.47  5242.4  350.52  5249.2  352.30
  5341.1  362.33  5461.8  371.14  5468.6  370.55  5476.0  371.82  5510.7  372.91
#Mann=4,-1,0
  4585.3    0.16       0  5009.3    0.07       0  5015.3    0.16       0
  5204.6    0.05       0
Bank Sta=5009.3,5015.3
Exp/Cntr=0.3,0.1

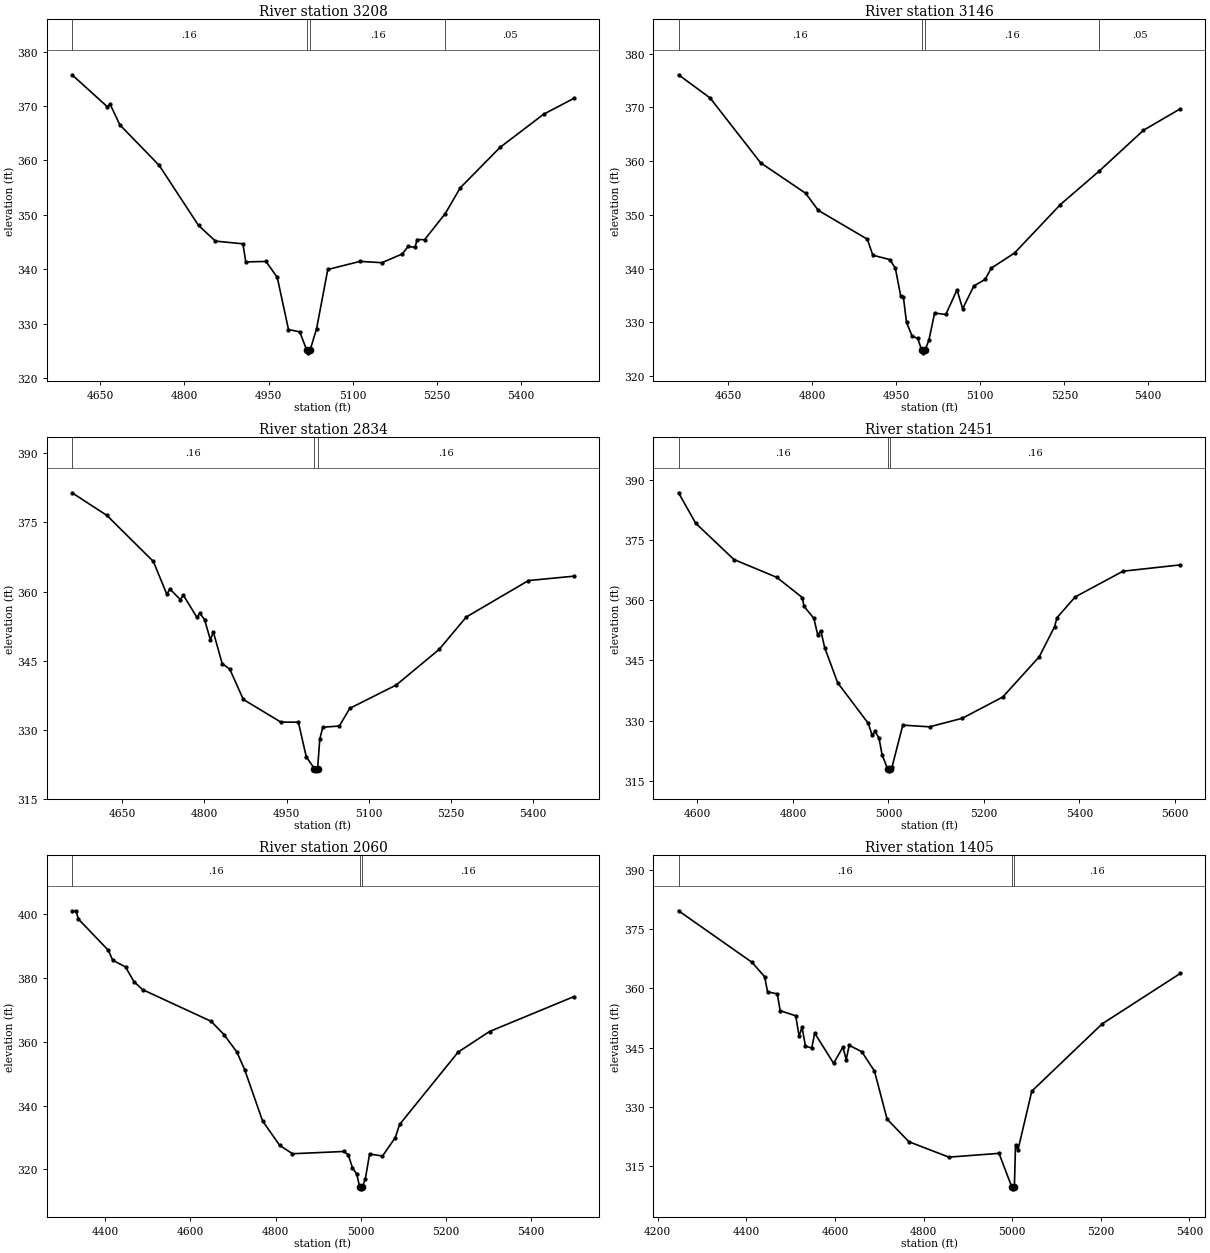
Type RM Length L Ch R = 1,3208,62,62,62
BEGIN DESCRIPTION:
Mapping XS 952cf3e0
END DESCRIPTION:
XS GIS Cut Line= 6
      3771281.91     10531765.14      3771299.27     10532186.12
      3771299.27     10532259.90      3771316.63     10532320.67
      3771325.31     10532377.09      3771515.44     10532580.18
#Sta/Elev= 30
  4600.0  375.75  4662.8  369.87  4667.8  370.32  4685.1  366.54  4755.2  359.08
  4825.2  348.04  4855.3  345.16  4904.3  344.66  4909.3  341.33  4945.3  341.42
  4965.4  338.49  4985.4  328.90  5005.4  328.47  5017.9  325.11  5020.6  324.61
  5023.9  325.11  5035.4  329.04  5055.4  339.94  5112.8  341.43  5151.8  341.19
  5188.2  342.80  5198.3  344.17  5210.8  344.01  5214.4  345.44  5227.8  345.42
  5264.5  350.21  5291.3  354.96  5362.1  362.39  5439.8  368.50  5493.6  371.41
#Mann=4,-1,0
  4600.0    0.16       0  5017.9    0.07       0  5023.9    0.16       0
  5264.5    0.05       0
Bank Sta=5017.9,5023.9
Exp/Cntr=0.3,0.1

Type RM Length L Ch R = 1,3146,312,312,312
BEGIN DESCRIPTION:
Mapping XS c31373fb
END DESCRIPTION:
XS GIS Cut Line= 4
      3771238.51     10531773.80      3771277.57     10532372.75
      3771316.63     10532450.87      3771468.50     10532594.07
#Sta/Elev= 30
  4560.9  376.08  4617.4  371.75  4707.6  359.68  4787.8  354.03  4810.6  350.83
  4898.0  345.48  4908.0  342.49  4938.1  341.67  4948.1  340.09  4957.6  334.98
  4962.6  334.65  4968.1  329.96  4978.2  327.41  4988.2  327.00  4995.2  324.81
  4998.0  324.31  5001.2  324.81  5008.2  326.70  5018.3  331.72  5038.3  331.45
  5058.3  336.03  5068.4  332.52  5088.4  336.76  5108.4  337.97  5119.6  340.08
  5161.1  342.90  5243.0  351.92  5312.6  358.18  5391.4  365.75  5457.2  369.75
#Mann=4,-1,0
  4560.9    0.16       0  4995.2    0.07       0  5001.2    0.16       0
  5312.6    0.05       0
Bank Sta=4995.2,5001.2
Exp/Cntr=0.3,0.1

Type RM Length L Ch R = 1,2834,383,383,383
BEGIN DESCRIPTION:
UNT105 IN BECR 6.0
END DESCRIPTION:
XS GIS Cut Line= 3
      3770882.61     10531904.01      3771064.89     10532381.43
      3771380.32     10532636.36
#Sta/Elev= 30
  4558.2  381.46  4621.8  376.54  4706.7  366.53  4731.4  359.37  4736.7  360.56
  4756.1  358.24  4761.4  359.21  4786.2  354.39  4791.5  355.28  4800.3  353.88
  4810.9  349.47  4816.2  351.22  4832.4  344.33  4846.3  343.12  4871.0  336.54
  4939.5  331.62  4971.6  331.59  4986.0  324.08  5000.7  321.52  5003.4  321.02
  5006.7  321.52  5010.7  327.91  5016.1  330.50  5046.5  330.76  5065.5  334.61
  5150.4  339.68  5228.7  347.41  5278.3  354.46  5391.9  362.38  5474.8  363.33
#Mann=3,-1,0
  4558.2    0.16       0  5000.7    0.07       0  5006.7    0.16       0
Bank Sta=5000.7,5006.7
Exp/Cntr=0.3,0.1

Type RM Length L Ch R = 1,2451,391,391,391
BEGIN DESCRIPTION:
UNT105 IN BECR 5.0
END DESCRIPTION:
XS GIS Cut Line= 4
      3770591.80     10531934.40      3770600.48     10532190.46
      3770791.46     10532433.51      3770969.40     10532884.89
#Sta/Elev= 30
  4560.6  386.70  4596.4  379.14  4676.5  370.10  4766.5  365.65  4819.8  360.62
  4823.2  358.47  4844.0  355.44  4852.1  351.25  4858.4  352.43  4866.5  348.20
  4893.7  339.44  4957.8  329.34  4965.9  326.39  4972.3  327.34  4980.4  325.57
  4986.7  321.55  4998.2  318.02  5000.9  317.52  5004.2  318.02  5007.6  318.51
  5030.1  328.89  5086.2  328.47  5154.6  330.60  5239.4  335.89  5315.8  345.91
  5347.7  353.35  5353.0  355.64  5391.1  360.80  5491.1  367.19  5611.1  368.76
#Mann=3,-1,0
  4560.6    0.16       0  4998.2    0.07       0  5004.2    0.16       0
Bank Sta=4998.2,5004.2
Exp/Cntr=0.3,0.1

Type RM Length L Ch R = 1,2060,655,655,655
BEGIN DESCRIPTION:
UNT105 IN BECR 4.0
END DESCRIPTION:
XS GIS Cut Line= 2
      3770475.48     10531815.45      3770357.62     10532987.13
#Sta/Elev= 30
  4322.3  401.13  4331.6  401.01  4337.1  398.53  4407.5  388.71  4417.5  385.64
  4447.7  383.50  4467.8  378.84  4487.9  376.37  4648.7  366.43  4678.8  362.27
  4709.0  356.81  4727.4  351.23  4769.3  335.18  4809.5  327.48  4839.6  324.86
  4960.2  325.57  4970.3  324.56  4980.3  320.49  4990.4  318.43  4997.4  314.34
  5000.2  313.84  5003.4  314.34  5010.5  316.92  5020.5  324.78  5050.7  324.13
  5080.8  329.91  5090.9  334.04  5228.4  356.78  5302.0  363.23  5499.9  374.18
#Mann=3,-1,0
  4322.3    0.16       0  4997.4    0.07       0  5003.4    0.16       0
Bank Sta=4997.4,5003.4
Exp/Cntr=0.3,0.1

Type RM Length L Ch R = 1,1405,276,276,276
BEGIN DESCRIPTION:
UNT105 IN BECR 3.0
END DESCRIPTION:
XS GIS Cut Line= 3
      3770283.67     10531860.57      3769923.40     10532277.26
      3769732.98     10532826.87
#Sta/Elev= 30
  4247.1  379.61  4412.8  366.58  4441.4  362.93  4448.0  359.12  4469.9  358.58
  4476.5  354.34  4511.6  353.03  4519.2  347.89  4525.8  350.12  4533.5  345.37
  4547.7  344.89  4554.4  348.66  4597.1  341.01  4618.0  345.11  4625.6  341.96
  4632.2  345.56  4660.7  343.96  4689.3  339.05  4717.8  326.89  4767.1  321.17
  4857.3  317.28  4970.4  318.24  4999.1  309.76  5001.9  309.26  5005.1  309.76
  5007.7  320.44  5013.0  319.04  5044.4  333.98  5203.2  351.00  5379.6  363.76
#Mann=3,-1,0
  4247.1    0.16       0  4999.1    0.07       0  5005.1    0.16       0
Bank Sta=4999.1,5005.1
Exp/Cntr=0.3,0.1

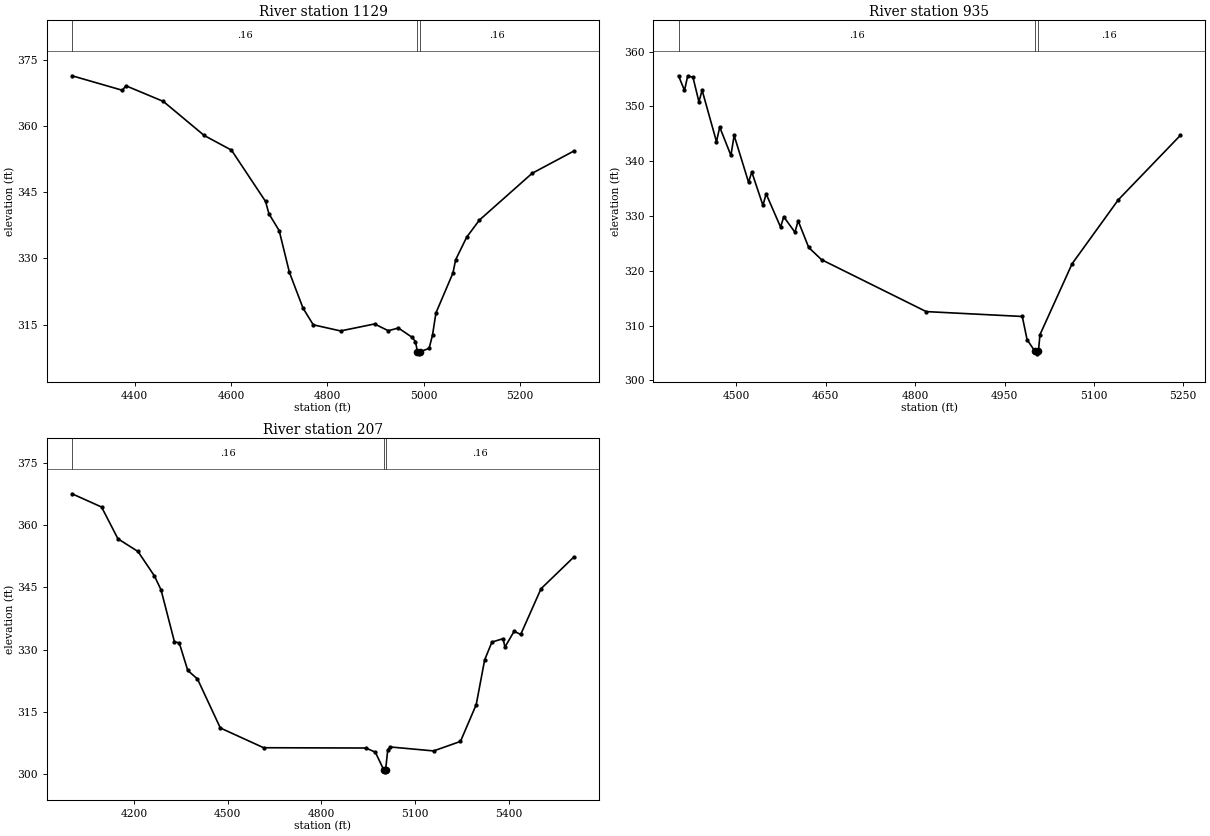
Type RM Length L Ch R = 1,1129,194,194,194
BEGIN DESCRIPTION:
UNT105 IN BECR 2.0
END DESCRIPTION:
XS GIS Cut Line= 3
      3770136.08     10531838.89      3769567.50     10532403.13
      3769498.06     10532633.14
#Sta/Elev= 30
  4270.2  371.37  4374.7  368.08  4381.8  369.11  4459.6  365.56  4544.4  357.84
  4601.0  354.52  4671.7  342.90  4678.7  340.10  4700.0  336.28  4721.2  326.83
  4749.5  318.71  4770.7  314.94  4827.3  313.55  4898.0  315.13  4926.3  313.60
  4947.4  314.21  4975.7  312.12  4982.8  311.14  4986.9  308.86  4989.6  308.36
  4992.9  308.86  5011.1  309.60  5018.2  312.62  5025.3  317.63  5060.6  326.68
  5066.2  329.68  5089.1  334.80  5115.5  338.67  5224.9  349.27  5311.5  354.32
#Mann=3,-1,0
  4270.2    0.16       0  4986.9    0.07       0  4992.9    0.16       0
Bank Sta=4986.9,4992.9
Exp/Cntr=0.3,0.1

Type RM Length L Ch R = 1,935,728,728,728
BEGIN DESCRIPTION:
Mapping XS d5bbc8ac
END DESCRIPTION:
XS GIS Cut Line= 2
      3769699.06     10531707.63      3769384.48     10532488.66
#Sta/Elev= 30
  4403.0  355.58  4413.0  352.90  4418.4  355.58  4427.3  355.28  4437.2  350.83
  4442.6  352.93  4466.7  343.55  4472.1  346.22  4490.9  341.04  4496.3  344.69
  4520.5  336.15  4525.9  338.02  4544.6  331.94  4550.0  334.03  4574.2  327.97
  4579.6  329.84  4598.3  327.02  4603.7  329.11  4621.4  324.25  4642.9  322.02
  4818.6  312.54  4979.8  311.65  4987.9  307.40  5000.9  305.33  5003.7  304.83
  5006.9  305.33  5009.5  308.33  5063.4  321.27  5140.9  332.94  5245.0  344.70
#Mann=3,-1,0
  4403.0    0.16       0  5000.9    0.07       0  5006.9    0.16       0
Bank Sta=5000.9,5006.9
Exp/Cntr=0.3,0.1

Type RM Length L Ch R = 1,207,0,0,0
BEGIN DESCRIPTION:
UNT105 IN BECR 1.0
END DESCRIPTION:
XS GIS Cut Line= 4
      3769655.61     10531566.63      3768972.05     10531978.94
      3768961.20     10532304.46      3769350.82     10532585.86
#Sta/Elev= 30
  4002.4  367.54  4096.7  364.35  4149.1  356.69  4213.2  353.63  4265.6  347.75
  4286.9  344.39  4329.7  331.88  4345.2  331.59  4372.4  324.96  4403.4  322.92
  4476.5  311.10  4615.0  306.34  4942.0  306.27  4972.0  305.28  4999.0  301.03
  5001.8  300.53  5005.0  301.03  5012.0  305.91  5020.5  306.52  5158.5  305.57
  5244.4  307.86  5294.7  316.71  5321.8  327.53  5345.0  331.80  5380.6  332.62
  5386.7  330.60  5416.1  334.42  5437.0  333.63  5502.0  344.66  5607.0  352.30
#Mann=3,-1,0
  4002.4    0.16       0  4999.0    0.07       0  5005.0    0.16       0
Bank Sta=4999,5005
Exp/Cntr=0.3,0.1

Chan Stop Cuts=-1