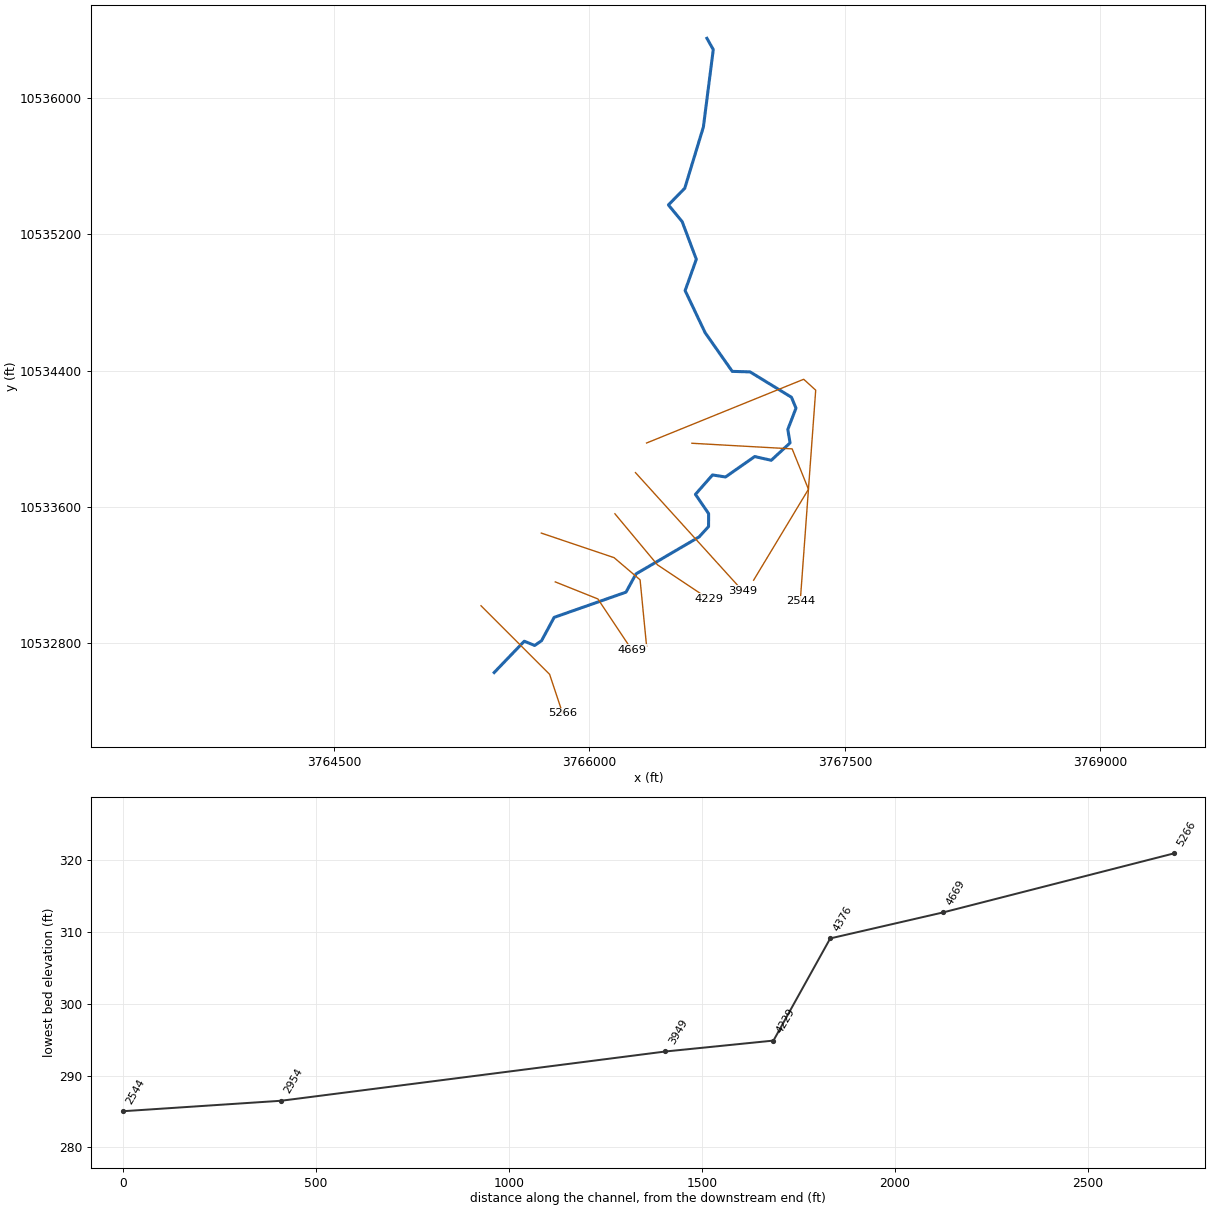
--- UNT106 IN BECR.prj (project) ---

Proj Title=UNT106 IN BECR Base Level Engineering
Current Plan=p01
Default Exp/Contr=0.3,0.1
English Units
Geom File=g01
Flow File=f01
Plan File=p01
Y Axis Title=Elevation
X Axis Title(PF)=Main Channel Distance
X Axis Title(XS)=Station
BEGIN DESCRIPTION:
UNT106 IN BECR
END DESCRIPTION:
DSS Export Rating Curves= 0
DSS Export Rating Curve Sorted= 0
DSS Export Volume Flow Curves= 0
DXF OffsetX= 0
DXF OffsetY= 0
DXF ScaleX= 1
DXF ScaleY= 10

--- UNT106 IN BECR.p01 (plan) ---

Plan Title=Multiple Run
Short Identifier=Multiple
Geom File=g01
Flow File=f01
Subcritical Flow
K Sum by GR= 0
Std Step Tol= 0.01
Critical Tol= 0.01
Num of Std Step Trials= 20
Max Error Tol= 0.3
Flow Tol Ratio= 0.001
Split Flow NTrial= 30
Split Flow Tol= 0.02
Split Flow Ratio= 0.02
Log Output Level= 0
Friction Slope Method= 1
Unsteady Friction Slope Method= 2
Unsteady Bridges Friction Slope Method= 1
Parabolic Critical Depth
Global Vel Dist=  1 , 1 , 1
Global Log Level= 0
CheckData=True
Encroach Param= -1, 0, 0, 0
BEGIN DESCRIPTION:
Multiple Run
END DESCRIPTION:

--- UNT106 IN BECR.f01 (steady flow) ---

Flow Title=Multiple
Number of Profiles=7
Profile Names=10-year,25-year,50-year,1pct_min,100-year,1pct_plu,500-year
River Rch & RM= UNT106 IN BECR,Reach-1,5266
     432     579     701     625     845    1143    1232
Boundary for River Rch & Prof#=UNT106 IN BECR,Reach-1,1
Up Type=0
Dn Type=3
Dn Slope=0.005
Boundary for River Rch & Prof#=UNT106 IN BECR,Reach-1,2
Up Type=0
Dn Type=3
Dn Slope=0.005
Boundary for River Rch & Prof#=UNT106 IN BECR,Reach-1,3
Up Type=0
Dn Type=3
Dn Slope=0.005
Boundary for River Rch & Prof#=UNT106 IN BECR,Reach-1,4
Up Type=0
Dn Type=3
Dn Slope=0.005
Boundary for River Rch & Prof#=UNT106 IN BECR,Reach-1,5
Up Type=0
Dn Type=3
Dn Slope=0.005
Boundary for River Rch & Prof#=UNT106 IN BECR,Reach-1,6
Up Type=0
Dn Type=3
Dn Slope=0.005
Boundary for River Rch & Prof#=UNT106 IN BECR,Reach-1,7
Up Type=0
Dn Type=3
Dn Slope=0.005

--- UNT106 IN BECR.g01 (geometry) ---

Geom Title=Existing Conditions
Program Version=4.10

River Reach=UNT106 IN BECR  ,Reach-1
Reach XY= 30
      3765440.84     10532628.09       3765617.5       10532812.
      3765678.75       10532787.        3765719.       10532815.
        3765793.       10532952.      3766214.75       10533100.
       3766273.4     10533207.09       3766643.5       10533424.
      3766699.25       10533485.      3766699.75       10533561.
      3766622.25       10533674.       3766722.5       10533788.
      3766798.75       10533776.      3766970.25       10533896.
      3767067.25       10533874.      3767177.75       10533976.
       3767164.5       10534055.       3767212.5       10534180.
        3767186.       10534244.        3766943.       10534393.
       3766838.5       10534396.      3766679.25       10534623.
      3766561.75       10534870.       3766627.5       10535054.
      3766544.41     10535275.04      3766463.75       10535373.
      3766559.61     10535470.91       3766668.9     10535830.38
        3766727.       10536285.      3766689.75       10536351.

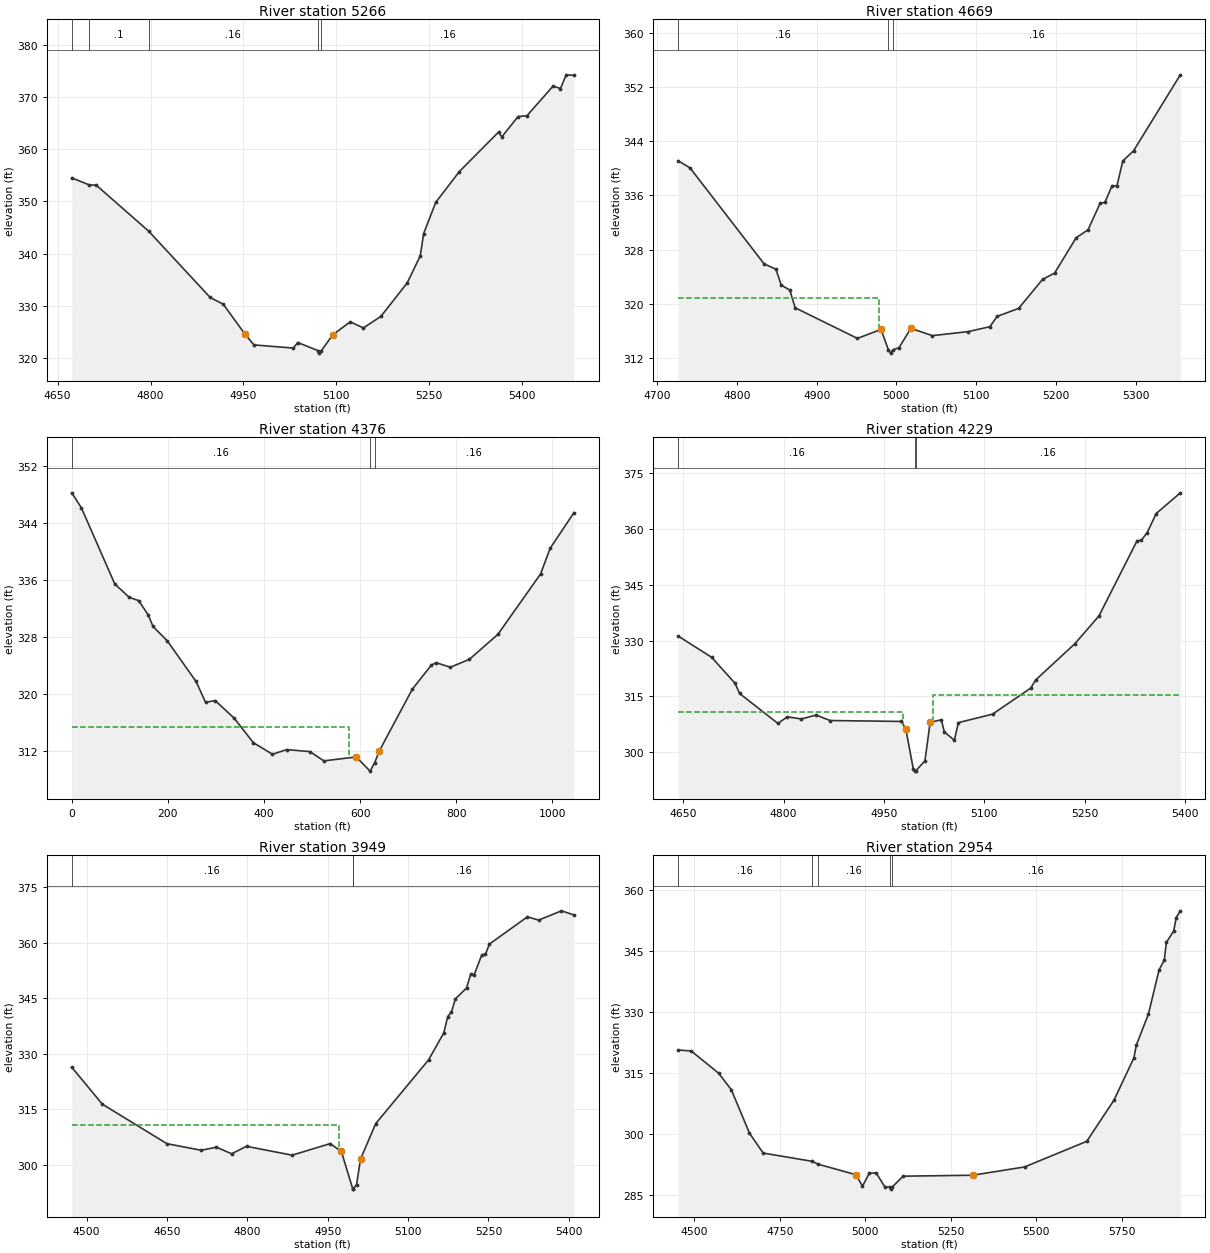
Type RM Length L Ch R = 1 ,5266    ,597,597,597
BEGIN DESCRIPTION:
UNT106 IN BECR 5.0
END DESCRIPTION:
XS GIS Cut Line= 3
      3765363.53      10533020.3      3765766.28     10532617.54
      3765842.66     10532388.42
#Sta/Elev= 30
  4672.8  354.48  4700.8  353.15  4712.5  353.07    4797  344.29  4896.4   331.6
  4917.6   330.3  4952.9  324.54  4967.1  322.52  5030.7  321.92  5037.8  322.98
  5070.2  321.45  5072.9  320.95  5076.2  321.45  5094.4  324.45  5122.7  326.94
  5143.9  325.77  5172.2  327.98  5214.6  334.37  5235.8  339.55  5241.2   343.8
  5260.7  349.78    5299   355.7  5362.2  363.24  5367.5  362.32  5393.8  366.22
  5408.2  366.38  5450.4  372.06  5462.3  371.57  5471.5   374.2  5483.9  374.12
#Mann= 5 ,-1 , 0
  4672.8     .16       0  4700.8      .1       0    4797     .16       0
  5070.2     .07       0  5076.2     .16       0
Bank Sta=4952.9,5094.4
XS Rating Curve= 0 ,0
Exp/Cntr=0.3,0.1

Type RM Length L Ch R = 1 ,4669    ,293,293,293
BEGIN DESCRIPTION:
UNT106 IN BECR 4.0
END DESCRIPTION:
XS GIS Cut Line= 3
      3765799.62     10533160.19      3766049.61     10533060.19
      3766249.61     10532760.19
#Sta/Elev= 30
  4726.3  341.11  4741.1  340.07    4834  325.91  4848.8  325.12  4855.5  322.78
  4866.3  322.04    4873  319.43  4951.1  314.91  4980.7  316.24  4989.9  313.24
  4992.6  312.74  4995.9  313.24  5003.1  313.53  5018.1  316.39  5045.1  315.32
  5090.2  315.92  5117.2  316.64  5126.3  318.16  5153.3  319.34  5183.3  323.62
  5198.4  324.55  5225.4  329.75  5240.4  330.95  5255.4  334.83  5261.5  334.98
  5270.5  337.45  5276.5  337.39    5284   341.1  5297.5   342.6  5356.1   353.8
#Mann= 3 ,-1 , 0
  4726.3     .16       0  4989.9     .07       0  4995.9     .16       0
#XS Ineff= 2 , 0
         4978.41  320.89
Permanent Ineff=
       F       F
Bank Sta=4980.7,5018.1
XS Rating Curve= 0 ,0
Exp/Cntr=0.3,0.1

Type RM Length L Ch R = 1 ,4376    ,147,147,147
XS GIS Cut Line= 4
     3765717.538     10533446.69     3766144.621    10533302.593
     3766297.399    10533172.385     3766335.594     10532781.76
#Sta/Elev= 30
       0  348.17   19.89  346.08   89.49  335.38  119.32  333.51  139.21  333.04
  159.09  331.04  169.04  329.42  198.87  327.38  258.53   321.7  278.41  318.76
   298.3  319.02  338.07  316.53  377.85   313.1  417.62  311.48  447.45  312.13
   495.6  311.85  524.48  310.55  591.89   311.1  620.78  309.11  630.41  310.31
  640.04  311.96  708.71  320.62  748.24  323.99  758.12  324.33  787.77  323.69
   827.3   324.8  886.59   328.3  975.53  336.79  995.29  340.37 1044.71  345.37
#Mann= 3 ,-1 , 0
       0     .16       0  620.78     .07       0  630.41     .16       0
#XS Ineff= 2 , 0
           577.5  315.33
Permanent Ineff=
       F       F
Bank Sta=591.89,640.04
XS Rating Curve= 0 ,0
Exp/Cntr=0.3,0.1

Type RM Length L Ch R = 1 ,4229    ,280,280,280
BEGIN DESCRIPTION:
UNT106 IN BECR 3.0
END DESCRIPTION:
XS GIS Cut Line= 3
      3766149.63     10533560.16      3766399.61     10533260.19
      3766699.58     10533060.21
#Sta/Elev= 30
  4642.3  331.19  4692.4  325.48  4727.5  318.45    4734  315.77  4791.3  307.72
  4805.6  309.48  4826.5  308.91  4848.6  309.96  4869.4  308.49  4976.2  308.24
  4982.7  306.21    4994  295.38  4996.7  294.88  4997.2  294.88  5011.3  297.65
  5019.1     308  5035.8  308.69  5040.3  305.46  5055.3  303.17  5061.3  307.92
  5112.4   310.2  5169.5   317.2    5177  319.41  5235.6  329.15  5271.6  336.61
  5328.7  356.86  5334.7   356.9  5343.8  359.04  5357.3  364.16  5393.3  369.72
#Mann= 3 ,-1 , 0
  4642.3     .16       0  4996.7     .07       0  4997.2     .16       0
#XS Ineff= 2 , 0
         4979.09  310.83 5024.09          315.43
Permanent Ineff=
       F       F
Bank Sta=4982.7,5019.1
XS Rating Curve= 0 ,0
Exp/Cntr=0.3,0.1

Type RM Length L Ch R = 1 ,3949    ,995,995,995
BEGIN DESCRIPTION:
UNT106 IN BECR 2.0
END DESCRIPTION:
XS GIS Cut Line= 2
       3766270.2     10533801.88      3766899.55     10533107.43
#Sta/Elev= 30
  4472.2  326.31  4529.3  316.32  4649.9  305.64  4713.8  303.87  4742.2   304.7
  4770.6  302.92  4798.4  304.93  4883.5  302.54  4954.4  305.66  4975.4  303.57
  4996.8  293.36  4997.3  293.36  5003.8  294.59  5011.2  301.47  5039.6  311.08
  5138.3  328.32  5166.6  335.59  5174.1  340.03  5180.8  341.19  5188.3   344.8
  5209.2  347.75  5216.7  351.44  5223.4  351.37  5237.6   356.7  5244.4  356.87
  5251.8  359.62  5322.8  366.98  5343.7  366.09  5386.3   368.6  5409.4  367.49
#Mann= 3 ,-1 , 0
  4472.2     .16       0  4996.8     .07       0  4997.3     .16       0
#XS Ineff= 2 , 0
         4970.68  310.66
Permanent Ineff=
       F       F
Bank Sta=4975.4,5011.2
XS Rating Curve= 0 ,0
Exp/Cntr=0.3,0.1

Type RM Length L Ch R = 1 ,2954    ,410,410,410
BEGIN DESCRIPTION:
Mapping XS 08655dfb
END DESCRIPTION:
XS GIS Cut Line= 4
       3766601.6     10533973.99      3767190.17       10533941.
      3767285.71     10533703.94      3766963.69     10533170.01
#Sta/Elev= 30
    4453  320.64  4491.1  320.39  4571.2  314.95  4608.2   310.9  4661.3  300.25
  4701.4  295.35  4844.3  293.33  4862.1  292.62  4972.2  290.05  4991.9  287.24
  5011.9  290.38  5031.9   290.5    5057  287.09  5072.7     287  5075.5   286.5
  5078.7     287  5110.7  289.68  5313.9  289.91    5466  291.94  5647.9  298.23
  5727.5  308.32  5785.7  318.68  5792.9  321.82  5828.4  329.47  5859.5  340.31
  5874.7  342.69  5880.8  347.04  5902.2  349.82  5909.7  353.14  5921.6  354.79
#Mann= 5 ,-1 , 0
    4453     .16       0  4844.3     .05       0  4862.1     .16       0
  5072.7     .07       0  5078.7     .16       0
Bank Sta=4972.2,5313.9
XS Rating Curve= 0 ,0
Exp/Cntr=0.3,0.1

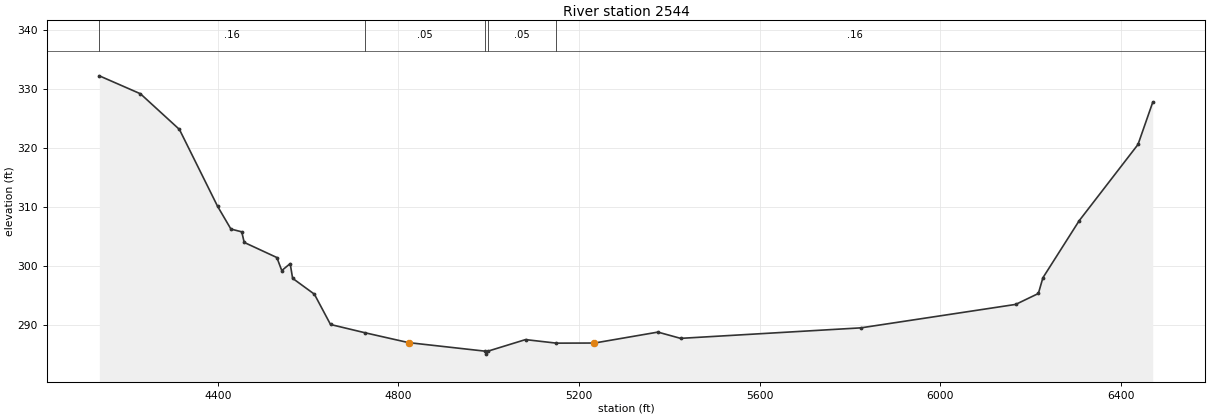
Type RM Length L Ch R = 1 ,2544    ,0,0,0
BEGIN DESCRIPTION:
UNT106 IN BECR 1.0
END DESCRIPTION:
XS GIS Cut Line= 4
      3766335.31     10533975.46      3767257.78      10534349.7
      3767328.29      10534285.7      3767237.67     10533047.63
#Sta/Elev= 30
  4137.9  332.17  4228.9  329.13  4315.2  323.09  4399.7  310.07  4429.2  306.22
  4453.2  305.75  4458.6  303.96  4530.9   301.4  4541.8  299.19  4560.4  300.37
  4565.8  297.88    4614  295.19  4649.7  290.06  4725.4  288.67  4822.4  286.99
  4992.1  285.54  4994.8  285.04  4998.1  285.54  5081.4   287.5  5149.7   286.9
  5234.1  286.92  5374.5  288.77  5424.7  287.71  5823.9  289.49  6166.6  293.46
  6216.8  295.31  6226.8  297.97    6307  307.62  6437.4  320.55    6470   327.7
#Mann= 5 ,-1 , 0
  4137.9     .16       0  4725.4     .05       0  4992.1     .03       0
  4998.1     .05       0  5149.7     .16       0
Bank Sta=4822.4,5234.1
XS Rating Curve= 0 ,0
Exp/Cntr=0.3,0.1

Chan Stop Cuts=-1
Use User Specified Reach Order=0
Composite Channel Slope=5