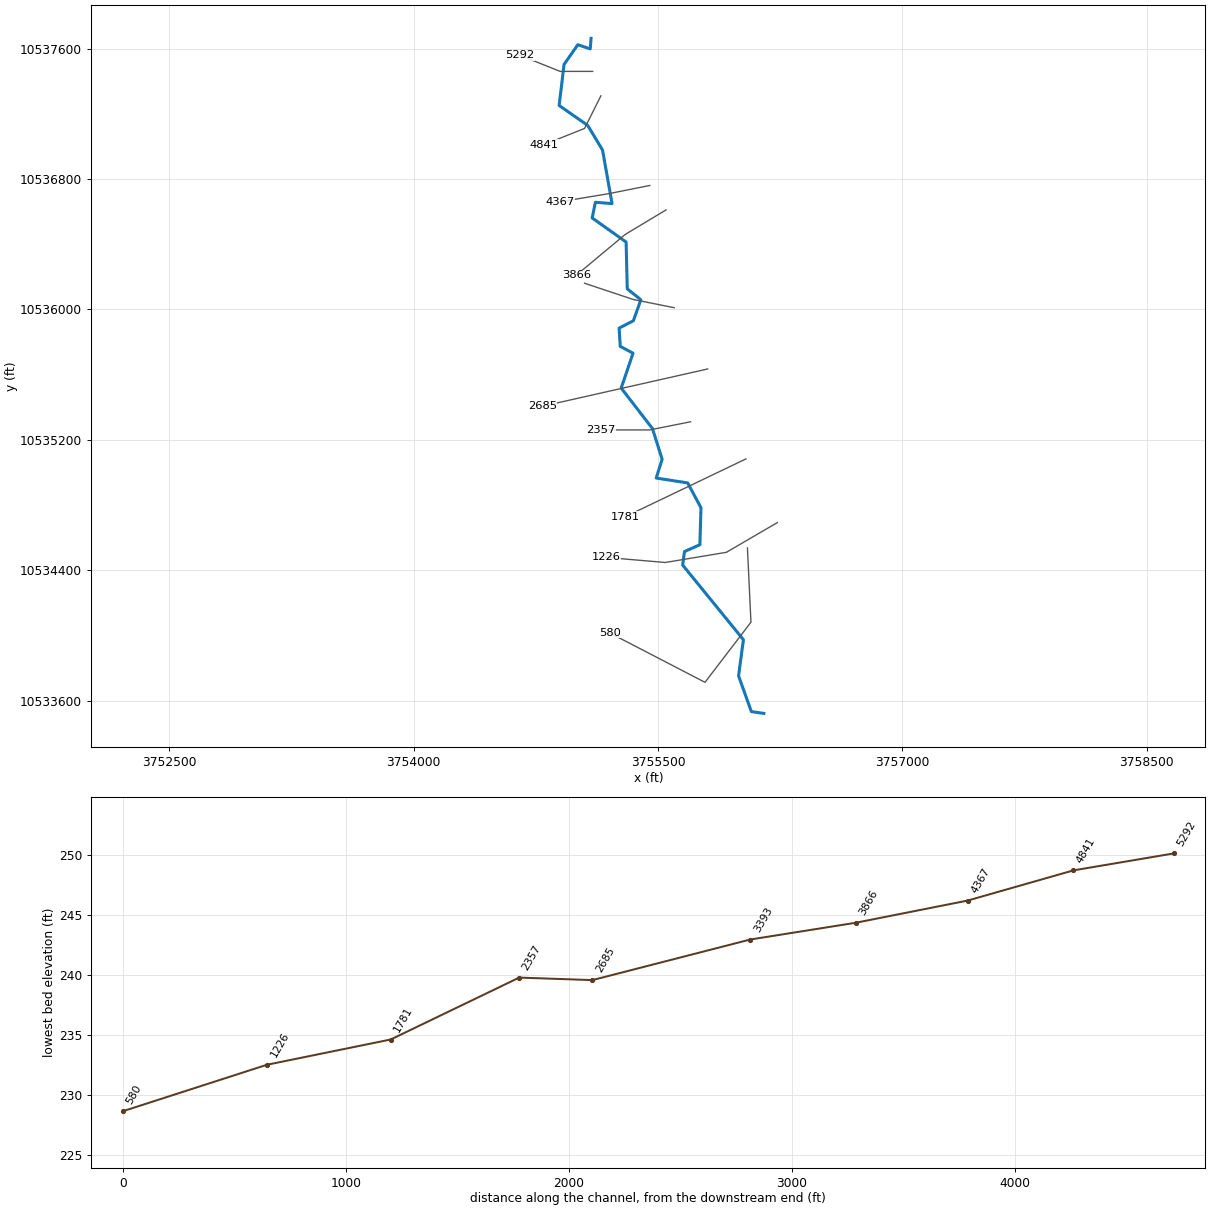
--- UNT107 IN BECR.prj (project) ---

Proj Title=UNT107 IN BECR Base Level Engineering
Current Plan=p01
Default Exp/Contr=0.3,0.1
English Units
Geom File=g01
Flow File=f01
Plan File=p01
BEGIN DESCRIPTION:
UNT107 IN BECR
END DESCRIPTION:

--- UNT107 IN BECR.p01 (plan) ---

Plan Title=Multiple Run
Short Identifier=Multiple
Geom File=g01
Flow File=f01
Subcritical Flow
K Sum by GR= 0
Std Step Tol= 0.01
Critical Tol= 0.01
Num of Std Step Trials= 20
Max Error Tol= 0.3
Flow Tol Ratio= 0.001
Split Flow NTrial= 30
Split Flow Tol= 0.02
Split Flow Ratio= 0.02
Log Output Level= 0
Friction Slope Method= 1
Unsteady Friction Slope Method= 2
Unsteady Bridges Friction Slope Method= 1
Parabolic Critical Depth
Global Vel Dist=  1 , 1 , 1
Global Log Level= 0
CheckData=True
Encroach Param= -1, 0, 0, 0
BEGIN DESCRIPTION:
Multiple Run
END DESCRIPTION:

--- UNT107 IN BECR.f01 (steady flow) ---

Flow Title=Multiple
Number of Profiles=7
Profile Names=10-year,25-year,50-year,1pct_min,100-year,1pct_plu,500-year
River Rch & RM= UNT107 IN BECR,Reach-1,5292
     596     811     989     887    1200    1622    1772
Boundary for River Rch & Prof#=UNT107 IN BECR,Reach-1,1
Up Type=0
Dn Type=3
Dn Slope=0.005
Boundary for River Rch & Prof#=UNT107 IN BECR,Reach-1,2
Up Type=0
Dn Type=3
Dn Slope=0.005
Boundary for River Rch & Prof#=UNT107 IN BECR,Reach-1,3
Up Type=0
Dn Type=3
Dn Slope=0.005
Boundary for River Rch & Prof#=UNT107 IN BECR,Reach-1,4
Up Type=0
Dn Type=3
Dn Slope=0.005
Boundary for River Rch & Prof#=UNT107 IN BECR,Reach-1,5
Up Type=0
Dn Type=3
Dn Slope=0.005
Boundary for River Rch & Prof#=UNT107 IN BECR,Reach-1,6
Up Type=0
Dn Type=3
Dn Slope=0.005
Boundary for River Rch & Prof#=UNT107 IN BECR,Reach-1,7
Up Type=0
Dn Type=3
Dn Slope=0.005

--- UNT107 IN BECR.g01 (geometry) ---

Geom Title=Existing Conditions

River Reach=UNT107 IN BECR,Reach-1
Reach XY= 30
      3755089.50     10537663.00      3755084.50     10537598.00
      3755008.50     10537624.00      3754923.75     10537503.00
      3754893.50     10537251.00      3755068.50     10537129.00
      3755159.75     10536978.00      3755218.25     10536649.00
      3755116.00     10536657.00      3755096.25     10536561.00
      3755304.50     10536413.00      3755311.50     10536126.00
      3755395.00     10536059.00      3755349.00     10535930.00
      3755261.50     10535885.00      3755268.50     10535773.00
      3755347.00     10535731.00      3755274.25     10535517.00
      3755466.00     10535269.00      3755525.50     10535080.00
      3755489.25     10534965.00      3755682.25     10534935.00
      3755763.75     10534783.00      3755757.25     10534556.00
      3755662.75     10534514.00      3755651.50     10534431.00
      3756024.25     10533973.00      3755994.50     10533751.00
      3756073.00     10533532.00      3756149.50     10533521.00

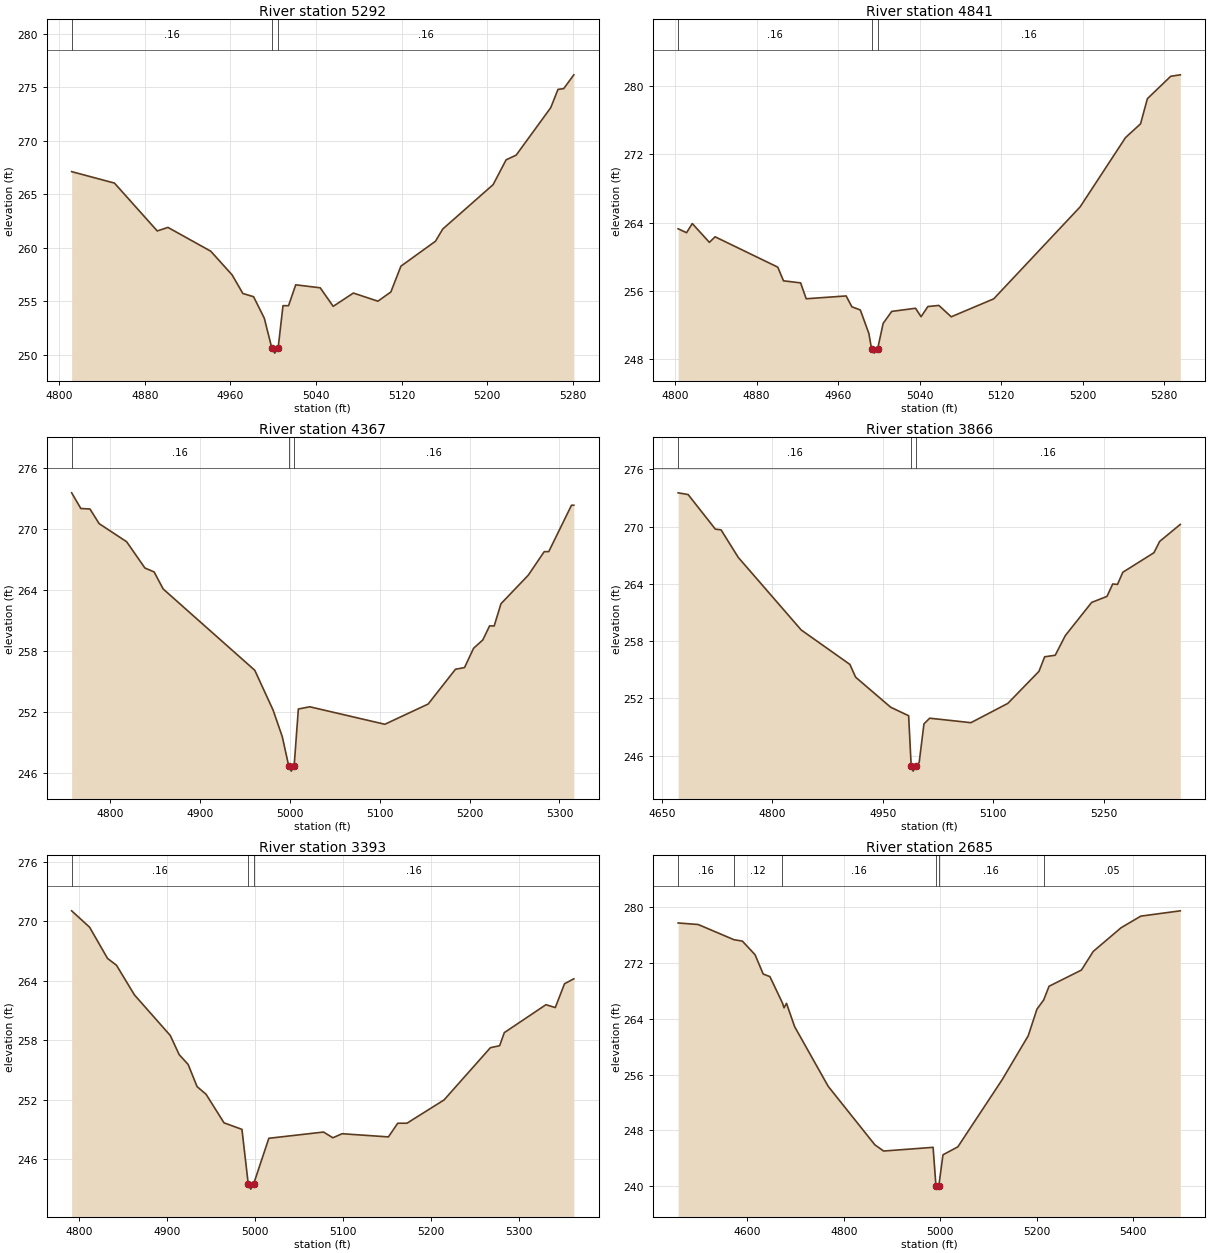
Type RM Length L Ch R = 1,5292,451,451,451
BEGIN DESCRIPTION:
UNT107 IN BECR 10.0
END DESCRIPTION:
XS GIS Cut Line= 3
      3755099.62     10537460.19      3754899.61     10537460.19
      3754649.58     10537560.20
#Sta/Elev= 30
  4811.7  267.11  4851.7  266.04  4891.7  261.57  4901.7  261.90  4941.7  259.68
  4961.7  257.46  4971.7  255.73  4981.7  255.43  4991.7  253.43  4998.7  250.66
  5001.5  250.16  5004.7  250.66  5009.2  254.59  5014.4  254.59  5021.1  256.54
  5044.0  256.26  5056.1  254.53  5075.0  255.77  5097.9  255.01  5110.0  255.87
  5119.4  258.28  5151.7  260.61  5158.5  261.75  5205.6  265.90  5217.7  268.21
  5227.1  268.65  5259.4  273.08  5266.2  274.79  5271.5  274.86  5281.0  276.15
#Mann=3,-1,0
  4811.7    0.16       0  4998.7    0.07       0  5004.7    0.16       0
Bank Sta=4998.7,5004.7
Exp/Cntr=0.3,0.1

Type RM Length L Ch R = 1,4841,474,474,474
BEGIN DESCRIPTION:
UNT107 IN BECR 9.0
END DESCRIPTION:
XS GIS Cut Line= 3
      3755149.59     10537310.16      3755049.61     10537110.19
      3754799.64     10537010.20
#Sta/Elev= 30
  4802.9  263.29  4811.2  262.83  4816.8  263.90  4833.6  261.70  4839.2  262.35
  4900.7  258.80  4906.3  257.20  4923.1  256.96  4928.6  255.10  4967.8  255.43
  4973.4  254.16  4981.7  253.79  4990.1  251.04  4992.7  249.24  4995.5  248.74
  4998.7  249.24  5004.1  252.22  5012.5  253.62  5035.9  253.99  5041.3  253.00
  5048.0  254.19  5058.8  254.32  5070.9  252.99  5112.6  255.09  5197.4  265.85
  5241.9  273.95  5256.7  275.57  5263.4  278.51  5286.3  281.13  5295.7  281.30
#Mann=3,-1,0
  4802.9    0.16       0  4992.7    0.07       0  4998.7    0.16       0
Bank Sta=4992.7,4998.7
Exp/Cntr=0.3,0.1

Type RM Length L Ch R = 1,4367,501,501,501
BEGIN DESCRIPTION:
UNT107 IN BECR 8.0
END DESCRIPTION:
XS GIS Cut Line= 3
      3755449.58     10536760.18      3755199.61     10536710.19
      3754899.57     10536660.18
#Sta/Elev= 30
  4756.9  273.60  4767.1  272.06  4777.3  272.01  4787.5  270.57  4818.1  268.79
  4838.5  266.20  4848.7  265.82  4858.8  264.14  4960.8  256.14  4981.2  252.22
  4991.4  249.61  4998.6  246.72  5001.4  246.22  5004.6  246.72  5009.3  252.33
  5022.0  252.55  5105.6  250.83  5153.8  252.82  5184.2  256.24  5194.3  256.41
  5204.4  258.31  5214.6  259.12  5222.2  260.51  5227.3  260.50  5234.9  262.69
  5265.3  265.50  5283.0  267.81  5288.1  267.82  5313.4  272.38  5316.0  272.38
#Mann=3,-1,0
  4756.9    0.16       0  4998.6    0.07       0  5004.6    0.16       0
Bank Sta=4998.6,5004.6
Exp/Cntr=0.3,0.1

Type RM Length L Ch R = 1,3866,473,473,473
BEGIN DESCRIPTION:
UNT107 IN BECR 7.0
END DESCRIPTION:
XS GIS Cut Line= 3
      3755549.64     10536610.21      3755299.61     10536460.19
      3754999.61     10536210.19
#Sta/Elev= 30
  4671.9  273.55  4685.5  273.37  4722.5  269.74  4730.2  269.67  4753.6  266.78
  4839.1  259.17  4905.2  255.56  4913.0  254.22  4960.6  251.07  4985.0  250.18
  4988.5  244.87  4991.2  244.37  4994.5  244.87  4999.3  245.27  5005.8  249.32
  5013.6  249.92  5069.6  249.45  5119.7  251.47  5162.0  254.83  5169.8  256.36
  5184.1  256.52  5197.8  258.58  5233.6  262.06  5254.4  262.69  5262.2  263.99
  5268.7  263.95  5275.9  265.22  5318.2  267.27  5326.0  268.46  5354.0  270.24
#Mann=3,-1,0
  4671.9    0.16       0  4988.5    0.07       0  4994.5    0.16       0
Bank Sta=4988.5,4994.5
Exp/Cntr=0.3,0.1

Type RM Length L Ch R = 1,3393,708,708,708
BEGIN DESCRIPTION:
UNT107 IN BECR 6.0
END DESCRIPTION:
XS GIS Cut Line= 3
      3755599.58     10536010.19      3755349.61     10536060.19
      3755049.56     10536160.20
#Sta/Elev= 30
  4791.2  271.05  4811.6  269.40  4832.0  266.25  4842.2  265.56  4862.6  262.57
  4903.4  258.47  4913.5  256.54  4923.7  255.55  4933.9  253.31  4944.1  252.54
  4964.5  249.66  4984.9  249.00  4992.1  243.47  4994.9  242.97  4998.1  243.47
  5015.5  248.10  5077.7  248.73  5088.3  248.15  5098.8  248.56  5151.5  248.24
  5162.1  249.62  5172.6  249.62  5214.8  251.97  5267.5  257.24  5278.0  257.44
  5283.3  258.76  5330.7  261.58  5341.3  261.29  5351.8  263.69  5362.4  264.19
#Mann=3,-1,0
  4791.2    0.16       0  4992.1    0.07       0  4998.1    0.16       0
Bank Sta=4992.1,4998.1
Exp/Cntr=0.3,0.1

Type RM Length L Ch R = 1,2685,328,328,328
BEGIN DESCRIPTION:
UNT107 IN BECR 5.0
END DESCRIPTION:
XS GIS Cut Line= 2
      3755805.25     10535634.34      3754789.68     10535405.18
#Sta/Elev= 30
  4456.7  277.73  4498.3  277.51  4572.5  275.33  4589.9  275.13  4616.2  273.18
  4633.1  270.41  4647.0  270.04  4673.0  266.26  4676.3  265.57  4681.4  266.21
  4698.3  262.86  4767.9  254.31  4864.6  245.93  4882.8  245.04  4985.3  245.57
  4991.2  240.08  4994.0  239.58  4997.2  240.08  5005.8  244.50  5036.6  245.64
  5128.8  255.30  5182.5  261.56  5200.6  265.37  5214.6  266.70  5225.7  268.66
  5292.8  270.98  5317.3  273.65  5374.9  277.04  5415.9  278.71  5497.8  279.47
#Mann=6,-1,0
  4456.7    0.16       0  4572.5    0.12       0  4673.0    0.16       0
  4991.2    0.07       0  4997.2    0.16       0  5214.6    0.05       0
Bank Sta=4991.2,4997.2
Exp/Cntr=0.3,0.1

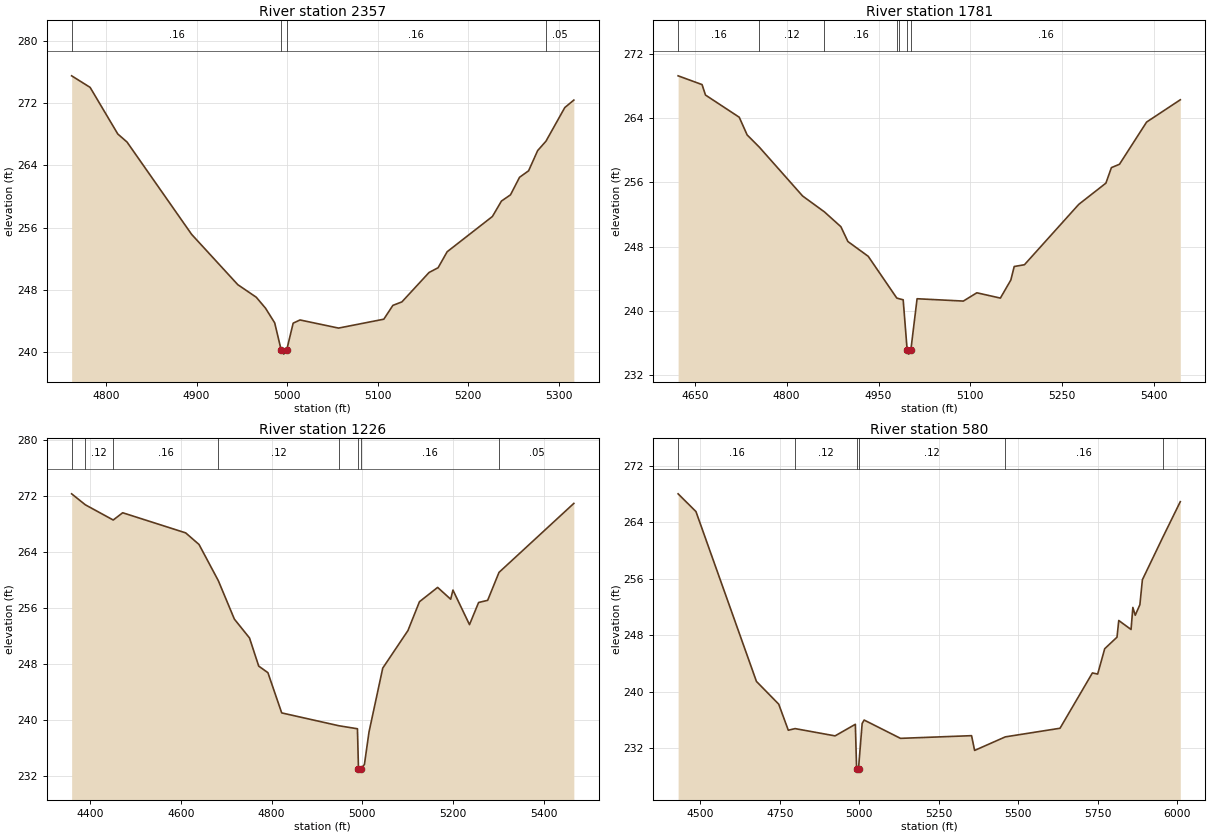
Type RM Length L Ch R = 1,2357,576,576,576
BEGIN DESCRIPTION:
UNT107 IN BECR 4.0
END DESCRIPTION:
XS GIS Cut Line= 3
      3755699.66     10535310.20      3755449.61     10535260.19
      3755149.61     10535260.19
#Sta/Elev= 30
  4761.9  275.48  4782.3  274.00  4812.9  268.02  4823.1  266.99  4894.5  255.15
  4945.5  248.70  4965.9  247.09  4976.1  245.69  4986.3  243.80  4993.5  240.29
  4996.3  239.79  4999.5  240.29  5006.7  243.76  5014.3  244.17  5056.9  243.13
  5106.9  244.27  5116.9  246.04  5126.9  246.49  5156.9  250.26  5166.9  250.87
  5176.9  252.92  5226.9  257.44  5236.9  259.42  5246.9  260.22  5256.9  262.47
  5266.9  263.30  5276.9  265.89  5286.1  267.10  5306.9  271.41  5316.9  272.37
#Mann=4,-1,0
  4761.9    0.16       0  4993.5    0.07       0  4999.5    0.16       0
  5286.1    0.05       0
Bank Sta=4993.5,4999.5
Exp/Cntr=0.3,0.1

Type RM Length L Ch R = 1,1781,555,555,555
BEGIN DESCRIPTION:
UNT107 IN BECR 3.0
END DESCRIPTION:
XS GIS Cut Line= 2
      3756039.60     10535082.24      3755300.03     10534728.08
#Sta/Elev= 30
  4622.8  269.24  4661.9  268.15  4667.5  266.85  4722.6  264.09  4735.5  261.89
  4755.5  260.36  4826.1  254.29  4861.6  252.32  4888.6  250.47  4900.0  248.63
  4933.2  246.79  4979.8  241.60  4984.1  241.50  4990.3  241.38  4996.8  235.12
  4999.5  234.62  5002.8  235.12  5013.0  241.51  5088.5  241.22  5110.6  242.25
  5149.0  241.59  5166.1  243.84  5171.6  245.52  5188.3  245.74  5277.0  253.25
  5321.3  255.89  5330.3  257.82  5343.5  258.24  5387.8  263.49  5442.8  266.26
#Mann=7,-1,0
  4622.8    0.16       0  4755.5    0.12       0  4861.6    0.16       0
  4979.8    0.12       0  4984.1    0.16       0  4996.8    0.07       0
  5002.8    0.16       0
Bank Sta=4996.8,5002.8
Exp/Cntr=0.3,0.1

Type RM Length L Ch R = 1,1226,646,646,646
BEGIN DESCRIPTION:
UNT107 IN BECR 2.0
END DESCRIPTION:
XS GIS Cut Line= 4
      3756232.35     10534691.64      3755919.82     10534509.33
      3755544.82     10534446.83      3755180.24     10534478.08
#Sta/Elev= 30
  4359.0  272.36  4389.2  270.79  4450.7  268.61  4471.6  269.65  4610.5  266.77
  4640.0  265.11  4682.6  259.92  4718.0  254.42  4751.4  251.72  4771.7  247.69
  4792.0  246.75  4822.4  240.99  4948.6  239.15  4989.5  238.72  4991.8  233.01
  4994.5  232.51  4997.8  233.01  5004.9  233.61  5015.0  238.25  5045.3  247.40
  5101.0  252.79  5126.3  256.91  5166.4  258.96  5195.2  257.27  5200.2  258.58
  5236.7  253.63  5256.8  256.80  5276.8  257.11  5301.8  261.11  5466.9  270.99
#Mann=8,-1,0
  4359.0    0.16       0  4389.2    0.12       0  4450.7    0.16       0
  4682.6    0.12       0  4948.6    0.16       0  4991.8    0.07       0
  4997.8    0.16       0  5301.8    0.05       0
Bank Sta=4991.8,4997.8
Exp/Cntr=0.3,0.1

Type RM Length L Ch R = 1,580,0,0,0
BEGIN DESCRIPTION:
UNT107 IN BECR 1.0
END DESCRIPTION:
XS GIS Cut Line= 4
      3756048.87     10534536.25      3756070.57     10534080.50
      3755788.45     10533711.58      3755203.77     10534014.75
#Sta/Elev= 30
  4430.4  268.02  4486.5  265.51  4676.7  241.47  4746.8  238.25  4776.9  234.56
  4798.3  234.79  4924.0  233.76  4987.8  235.40  4991.7  229.13  4994.4  228.63
  4997.7  229.13  5009.2  235.52  5015.5  236.00  5129.7  233.41  5353.3  233.79
  5362.8  231.70  5459.4  233.62  5631.4  234.84  5733.3  242.67  5749.8  242.51
  5772.0  246.10  5810.6  247.73  5816.2  250.09  5854.8  248.82  5860.5  251.94
  5868.0  250.83  5882.6  252.33  5890.5  255.86  5955.0  261.90  6009.7  266.91
#Mann=6,-1,0
  4430.4    0.16       0  4798.3    0.12       0  4991.7    0.07       0
  4997.7    0.12       0  5459.4    0.16       0  5955.0    0.05       0
Bank Sta=4991.7,4997.7
Exp/Cntr=0.3,0.1

Chan Stop Cuts=-1