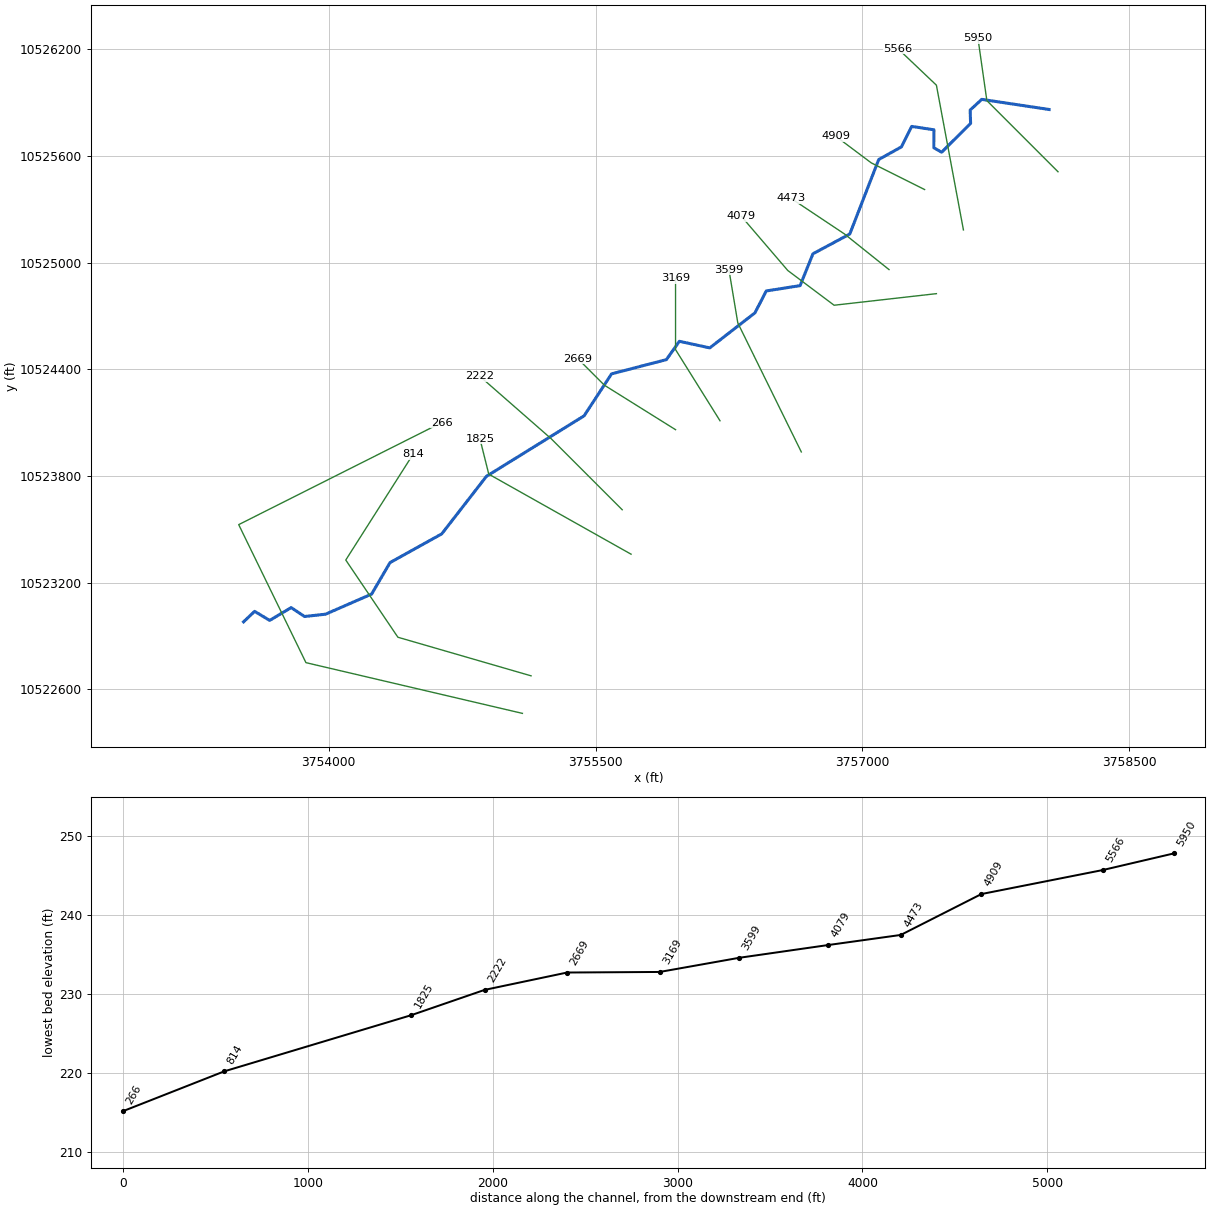
--- UNT108 IN BECR.prj (project) ---

Proj Title=UNT108 IN BECR Base Level Engineering
Current Plan=p01
Default Exp/Contr=0.3,0.1
English Units
Geom File=g01
Flow File=f01
Plan File=p01
BEGIN DESCRIPTION:
UNT108 IN BECR
END DESCRIPTION:

--- UNT108 IN BECR.p01 (plan) ---

Plan Title=Multiple Run
Short Identifier=Multiple
Geom File=g01
Flow File=f01
Subcritical Flow
K Sum by GR= 0
Std Step Tol= 0.01
Critical Tol= 0.01
Num of Std Step Trials= 20
Max Error Tol= 0.3
Flow Tol Ratio= 0.001
Split Flow NTrial= 30
Split Flow Tol= 0.02
Split Flow Ratio= 0.02
Log Output Level= 0
Friction Slope Method= 1
Unsteady Friction Slope Method= 2
Unsteady Bridges Friction Slope Method= 1
Parabolic Critical Depth
Global Vel Dist=  1 , 1 , 1
Global Log Level= 0
CheckData=True
Encroach Param= -1, 0, 0, 0
BEGIN DESCRIPTION:
Multiple Run
END DESCRIPTION:

--- UNT108 IN BECR.f01 (steady flow) ---

Flow Title=Multiple
Number of Profiles=7
Profile Names=10-year,25-year,50-year,1pct_min,100-year,1pct_plu,500-year
River Rch & RM= UNT108 IN BECR,Reach-1,5950
     814    1126    1389    1259    1703    2303    2569
Boundary for River Rch & Prof#=UNT108 IN BECR,Reach-1,1
Up Type=0
Dn Type=3
Dn Slope=0.005
Boundary for River Rch & Prof#=UNT108 IN BECR,Reach-1,2
Up Type=0
Dn Type=3
Dn Slope=0.005
Boundary for River Rch & Prof#=UNT108 IN BECR,Reach-1,3
Up Type=0
Dn Type=3
Dn Slope=0.005
Boundary for River Rch & Prof#=UNT108 IN BECR,Reach-1,4
Up Type=0
Dn Type=3
Dn Slope=0.005
Boundary for River Rch & Prof#=UNT108 IN BECR,Reach-1,5
Up Type=0
Dn Type=3
Dn Slope=0.005
Boundary for River Rch & Prof#=UNT108 IN BECR,Reach-1,6
Up Type=0
Dn Type=3
Dn Slope=0.005
Boundary for River Rch & Prof#=UNT108 IN BECR,Reach-1,7
Up Type=0
Dn Type=3
Dn Slope=0.005

--- UNT108 IN BECR.g01 (geometry) ---

Geom Title=Existing Conditions

River Reach=UNT108 IN BECR,Reach-1
Reach XY= 30
      3758049.61     10525860.19      3757671.00     10525917.00
      3757605.75     10525857.00      3757608.25     10525782.00
      3757445.50     10525620.00      3757401.50     10525645.00
      3757402.25     10525746.00      3757277.25     10525765.00
      3757219.50     10525650.00      3757091.75     10525579.00
      3756929.00     10525160.00      3756722.00     10525049.00
      3756649.75     10524870.00      3756459.50     10524840.00
      3756396.00     10524717.00      3756142.00     10524520.00
      3755971.00     10524557.00      3755898.25     10524454.00
      3755590.00     10524374.00      3755435.50     10524138.00
      3754886.50     10523798.00      3754635.18     10523474.31
      3754344.50     10523313.00      3754241.00     10523136.00
      3753982.25     10523023.00      3753864.00     10523010.00
      3753788.75     10523060.00      3753668.00     10522988.00
      3753583.25     10523039.00      3753521.25     10522980.00

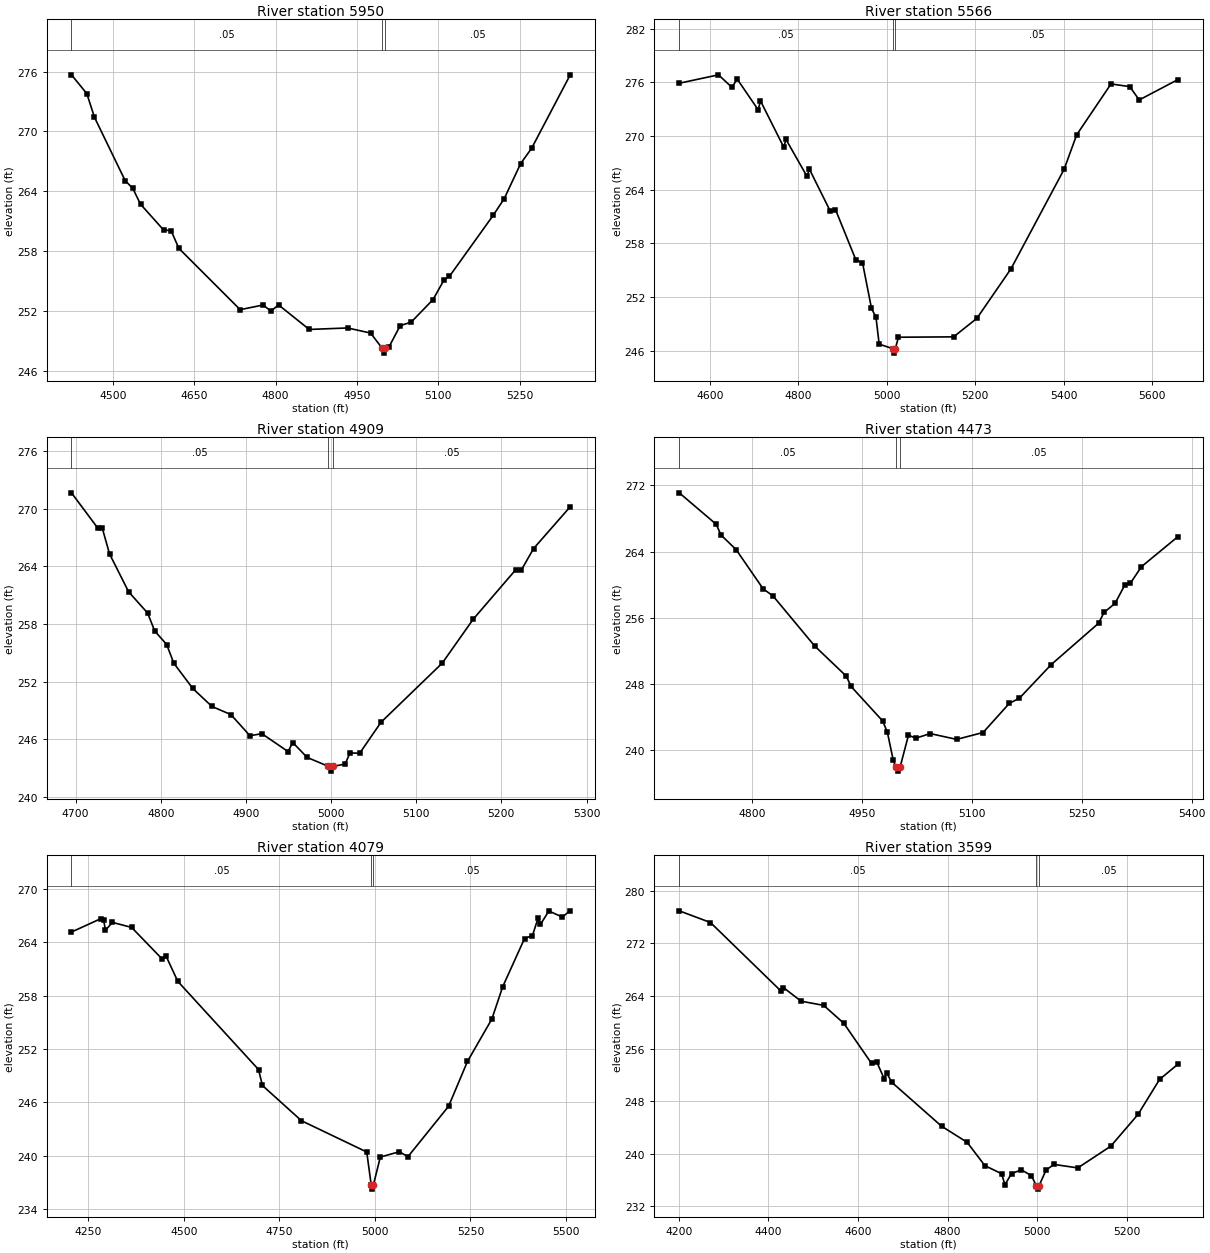
Type RM Length L Ch R = 1,5950,384,384,384
BEGIN DESCRIPTION:
UNT108 IN BECR 11.0
END DESCRIPTION:
XS GIS Cut Line= 3
      3758099.60     10525510.20      3757699.61     10525910.19
      3757649.61     10526260.16
#Sta/Elev= 30
  4423.5  275.67  4451.8  273.79  4465.9  271.42  4522.5  265.08  4536.6  264.30
  4550.8  262.72  4593.2  260.15  4607.3  260.06  4621.5  258.30  4734.6  252.16
  4777.0  252.63  4791.2  252.01  4805.3  252.64  4861.9  250.18  4932.6  250.33
  4975.0  249.82  4996.3  248.31  4999.0  247.81  5002.3  248.31  5009.4  248.47
  5029.6  250.56  5049.8  250.91  5090.2  253.17  5110.4  255.13  5120.5  255.50
  5201.3  261.62  5221.5  263.28  5251.8  266.79  5272.0  268.32  5342.7  275.62
#Mann=3,-1,0
  4423.5    0.05       0  4996.3    0.03       0  5002.3    0.05       0
Bank Sta=4996.3,5002.3
Exp/Cntr=0.3,0.1

Type RM Length L Ch R = 1,5566,657,657,657
BEGIN DESCRIPTION:
UNT108 IN BECR 10.0
END DESCRIPTION:
XS GIS Cut Line= 3
      3757567.96     10525182.97      3757416.06     10525996.74
      3757199.01     10526202.93
#Sta/Elev= 30
  4531.1  275.91  4619.8  276.85  4650.3  275.44  4662.0  276.38  4709.6  272.93
  4714.7  273.94  4767.3  268.76  4772.4  269.62  4820.0  265.48  4825.1  266.32
  4872.7  261.58  4884.3  261.78  4930.5  256.13  4945.4  255.84  4965.7  250.73
  4975.9  249.72  4983.1  246.72  5013.6  246.21  5016.3  245.71  5019.6  246.21
  5026.7  247.49  5151.4  247.53  5204.0  249.60  5281.1  255.14  5401.3  266.28
  5429.6  270.13  5507.3  275.83  5549.7  275.53  5571.1  274.04  5658.3  276.31
#Mann=3,-1,0
  4531.1    0.05       0  5013.6    0.03       0  5019.6    0.05       0
Bank Sta=5013.6,5019.6
Exp/Cntr=0.3,0.1

Type RM Length L Ch R = 1,4909,436,436,436
BEGIN DESCRIPTION:
UNT108 IN BECR 9.0
END DESCRIPTION:
XS GIS Cut Line= 3
      3757349.59     10525410.20      3757049.61     10525560.19
      3756849.60     10525710.19
#Sta/Elev= 30
  4695.2  271.66  4725.9  268.01  4731.5  267.95  4739.9  265.30  4762.3  261.35
  4784.6  259.14  4793.0  257.26  4807.0  255.86  4815.4  253.91  4837.7  251.28
  4860.1  249.41  4882.4  248.56  4904.8  246.36  4918.8  246.57  4949.5  244.71
  4955.1  245.65  4971.9  244.10  4996.8  243.17  4999.6  242.67  5002.8  243.17
  5016.6  243.41  5022.2  244.56  5033.7  244.54  5058.7  247.76  5130.6  253.92
  5167.0  258.50  5217.0  263.66  5223.3  263.59  5237.9  265.86  5280.6  270.18
#Mann=3,-1,0
  4695.2    0.05       0  4996.8    0.03       0  5002.8    0.05       0
Bank Sta=4996.8,5002.8
Exp/Cntr=0.3,0.1

Type RM Length L Ch R = 1,4473,394,394,394
BEGIN DESCRIPTION:
UNT108 IN BECR 8.0
END DESCRIPTION:
XS GIS Cut Line= 3
      3757149.65     10524960.16      3756899.61     10525160.19
      3756599.58     10525360.21
#Sta/Elev= 30
  4700.3  271.08  4750.8  267.28  4757.2  266.00  4778.0  264.22  4814.8  259.50
  4828.4  258.63  4885.2  252.60  4928.5  248.95  4934.9  247.72  4978.1  243.55
  4984.5  242.19  4992.5  238.83  4995.9  238.00  4998.6  237.50  5001.9  238.00
  5013.3  241.83  5023.5  241.48  5043.0  242.03  5079.1  241.33  5115.2  242.16
  5151.2  245.69  5164.7  246.29  5208.3  250.36  5272.9  255.34  5280.4  256.65
  5295.4  257.74  5308.9  259.98  5316.5  260.19  5331.5  262.17  5381.1  265.78
#Mann=3,-1,0
  4700.3    0.05       0  4995.9    0.03       0  5001.9    0.05       0
Bank Sta=4995.9,5001.9
Exp/Cntr=0.3,0.1

Type RM Length L Ch R = 1,4079,480,480,480
BEGIN DESCRIPTION:
UNT108 IN BECR 7.0
END DESCRIPTION:
XS GIS Cut Line= 4
      3757416.02     10524824.86      3756840.97     10524759.76
      3756580.55     10524955.07      3756320.14     10525258.89
#Sta/Elev= 30
  4206.2  265.16  4283.1  266.67  4290.1  266.55  4295.2  265.37  4313.3  266.25
  4363.6  265.68  4444.1  262.10  4454.2  262.41  4484.4  259.61  4695.7  249.68
  4705.8  247.89  4808.0  243.92  4978.8  240.40  4990.4  236.72  4993.2  236.22
  4996.4  236.72  5014.3  239.83  5064.3  240.43  5086.6  239.87  5193.0  245.55
  5242.4  250.60  5306.1  255.36  5334.6  259.01  5391.7  264.43  5412.5  264.77
  5426.8  266.69  5433.4  266.02  5455.3  267.53  5490.5  266.85  5510.6  267.55
#Mann=3,-1,0
  4206.2    0.05       0  4990.4    0.03       0  4996.4    0.05       0
Bank Sta=4990.4,4996.4
Exp/Cntr=0.3,0.1

Type RM Length L Ch R = 1,3599,430,430,430
BEGIN DESCRIPTION:
UNT108 IN BECR 6.0
END DESCRIPTION:
XS GIS Cut Line= 3
      3756656.50     10523935.13      3756299.61     10524660.19
      3756249.60     10524960.22
#Sta/Elev= 30
  4201.1  276.96  4270.7  275.18  4427.9  264.76  4433.5  265.28  4472.9  263.21
  4523.4  262.57  4568.3  259.84  4630.2  253.73  4641.4  254.02  4658.2  251.43
  4663.8  252.33  4674.9  250.89  4786.3  244.19  4843.5  241.73  4882.9  238.19
  4920.1  236.96  4927.8  235.29  4942.4  236.98  4964.6  237.54  4986.9  236.66
  4997.8  235.11  5000.5  234.61  5003.8  235.11  5019.4  237.50  5037.1  238.37
  5090.3  237.84  5163.8  241.14  5224.7  245.98  5272.8  251.31  5313.4  253.60
#Mann=3,-1,0
  4201.1    0.05       0  4997.8    0.03       0  5003.8    0.05       0
Bank Sta=4997.8,5003.8
Exp/Cntr=0.3,0.1

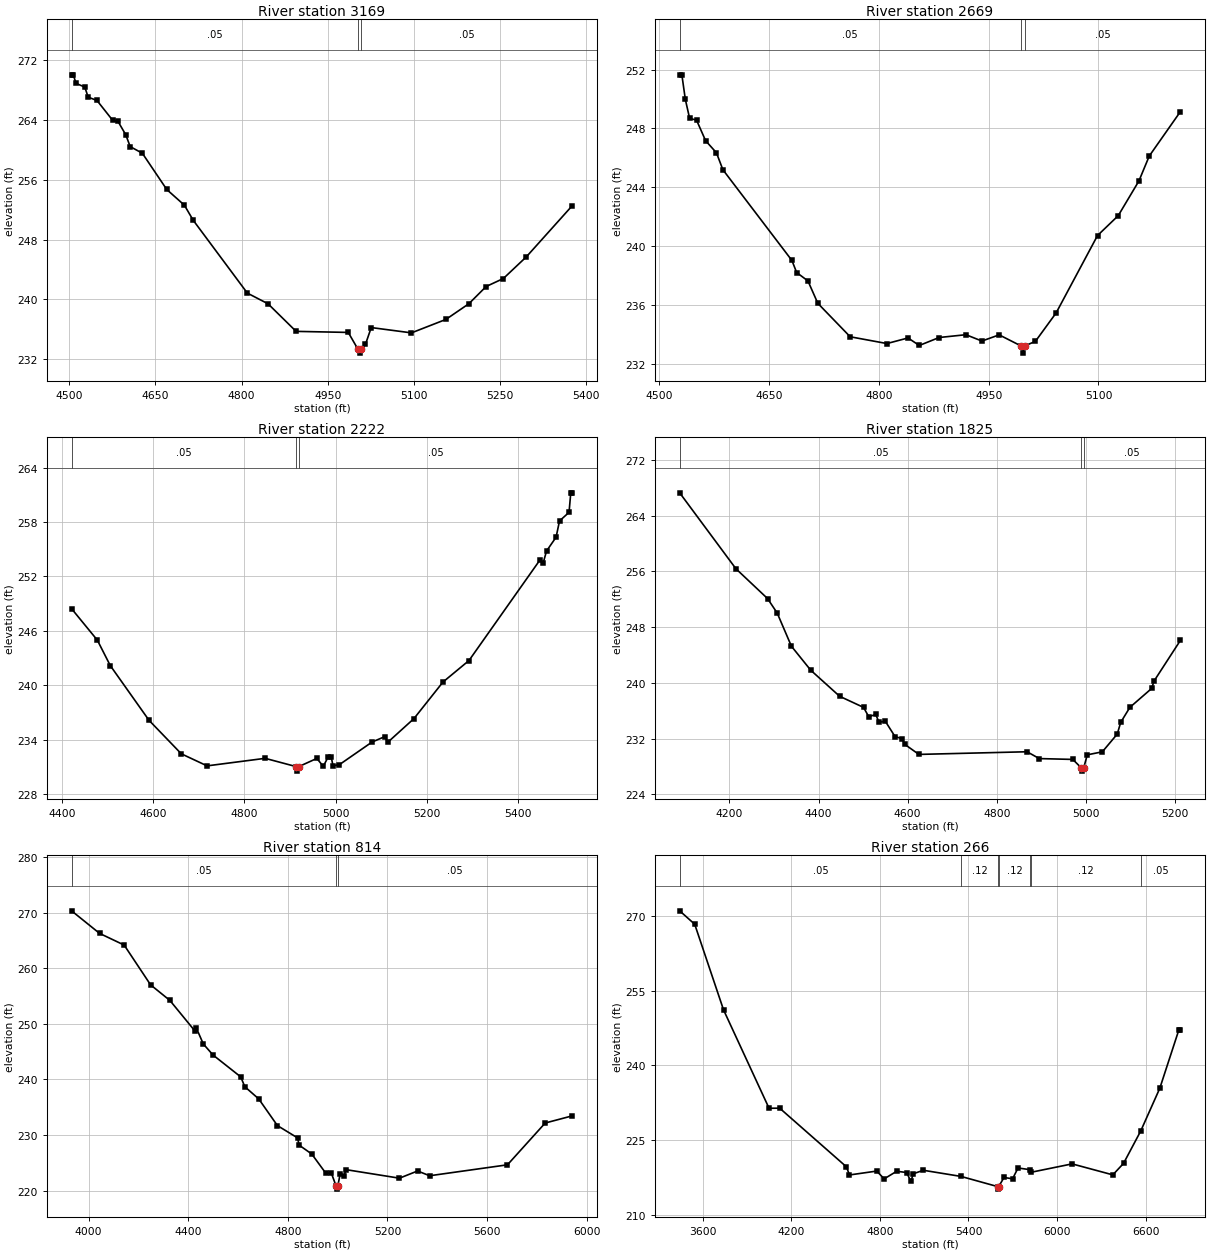
Type RM Length L Ch R = 1,3169,500,500,500
BEGIN DESCRIPTION:
UNT108 IN BECR 5.0
END DESCRIPTION:
XS GIS Cut Line= 3
      3756199.62     10524110.17      3755949.61     10524510.19
      3755949.61     10524910.17
#Sta/Elev= 30
  4503.9  270.05  4506.9  270.05  4511.6  268.91  4526.9  268.41  4532.8  267.06
  4548.1  266.62  4575.3  263.98  4584.7  263.82  4598.3  262.02  4605.9  260.45
  4627.1  259.56  4669.6  254.71  4700.3  252.61  4715.6  250.60  4809.9  240.85
  4845.9  239.42  4894.8  235.73  4985.6  235.59  5002.6  233.32  5005.4  232.82
  5008.6  233.32  5015.6  234.01  5025.6  236.24  5095.6  235.53  5155.6  237.33
  5195.6  239.43  5225.6  241.73  5255.6  242.80  5295.6  245.70  5375.6  252.55
#Mann=3,-1,0
  4503.9    0.05       0  5002.6    0.03       0  5008.6    0.05       0
Bank Sta=5002.6,5008.6
Exp/Cntr=0.3,0.1

Type RM Length L Ch R = 1,2669,447,447,447
BEGIN DESCRIPTION:
UNT108 IN BECR 4.0
END DESCRIPTION:
XS GIS Cut Line= 3
      3755949.64     10524060.17      3755549.61     10524310.19
      3755399.58     10524460.21
#Sta/Elev= 30
  4528.0  251.64  4531.0  251.64  4535.7  249.98  4541.6  248.68  4551.0  248.57
  4563.4  247.17  4578.2  246.35  4587.0  245.20  4681.3  239.04  4687.8  238.22
  4703.2  237.65  4716.7  236.13  4760.9  233.86  4811.1  233.40  4839.9  233.78
  4855.3  233.27  4882.4  233.81  4919.0  234.00  4940.8  233.57  4964.4  233.99
  4993.8  233.25  4996.5  232.75  4999.8  233.25  5013.9  233.55  5042.2  235.48
  5098.7  240.73  5127.0  242.08  5155.3  244.44  5169.4  246.13  5211.9  249.14
#Mann=3,-1,0
  4528.0    0.05       0  4993.8    0.03       0  4999.8    0.05       0
Bank Sta=4993.8,4999.8
Exp/Cntr=0.3,0.1

Type RM Length L Ch R = 1,2222,397,397,397
BEGIN DESCRIPTION:
UNT108 IN BECR 3.0
END DESCRIPTION:
XS GIS Cut Line= 3
      3755649.57     10523610.22      3755249.61     10524010.19
      3754849.64     10524360.16
#Sta/Elev= 30
  4421.3  248.45  4477.8  244.98  4506.1  242.18  4591.0  236.15  4661.7  232.46
  4718.2  231.13  4845.5  231.96  4913.2  231.05  4916.0  230.55  4919.2  231.05
  4958.7  231.95  4972.8  231.08  4983.4  232.10  4990.3  232.10  4994.1  231.13
  5008.3  231.27  5079.5  233.75  5107.0  234.34  5114.6  233.75  5171.5  236.34
  5235.1  240.37  5292.1  242.74  5447.7  253.83  5454.4  253.45  5462.0  254.81
  5482.9  256.33  5490.4  258.12  5511.3  259.07  5515.1  261.22  5518.4  261.22
#Mann=3,-1,0
  4421.3    0.05       0  4913.2    0.03       0  4919.2    0.05       0
Bank Sta=4913.2,4919.2
Exp/Cntr=0.3,0.1

Type RM Length L Ch R = 1,1825,1011,1011,1011
BEGIN DESCRIPTION:
UNT108 IN BECR 2.0
END DESCRIPTION:
XS GIS Cut Line= 3
      3755699.58     10523360.21      3754899.61     10523810.19
      3754849.61     10524010.19
#Sta/Elev= 30
  4088.3  267.29  4214.5  256.40  4285.5  252.12  4307.2  250.04  4339.1  245.28
  4382.4  241.84  4447.4  238.09  4501.0  236.50  4512.8  235.16  4528.4  235.48
  4535.7  234.38  4550.1  234.49  4571.7  232.31  4587.7  232.00  4593.4  231.20
  4625.3  229.75  4868.1  230.13  4895.6  229.15  4970.8  229.03  4989.4  227.85
  4992.2  227.35  4995.4  227.85  5003.3  229.69  5037.1  230.12  5070.6  232.67
  5078.3  234.34  5098.9  236.50  5147.9  239.22  5153.0  240.26  5212.3  246.11
#Mann=3,-1,0
  4088.3    0.05       0  4989.4    0.03       0  4995.4    0.05       0
Bank Sta=4989.4,4995.4
Exp/Cntr=0.3,0.1

Type RM Length L Ch R = 1,814,548,548,548
BEGIN DESCRIPTION:
UNT108 IN BECR 1.0
END DESCRIPTION:
XS GIS Cut Line= 4
      3755137.42     10522676.42      3754388.71     10522893.44
      3754095.74     10523327.47      3754475.06     10523923.53
#Sta/Elev= 30
  3932.0  270.38  4044.3  266.32  4143.1  264.21  4249.1  257.05  4326.6  254.24
  4427.4  248.72  4432.6  249.29  4460.7  246.40  4499.7  244.41  4610.9  240.47
  4627.3  238.70  4683.2  236.50  4758.3  231.69  4839.1  229.48  4845.2  228.18
  4896.1  226.57  4953.1  223.07  4974.1  223.20  4994.2  220.75  4996.9  220.25
  5000.2  220.75  5010.1  222.99  5025.0  222.53  5033.4  223.76  5248.0  222.22
  5320.8  223.52  5369.1  222.66  5681.5  224.63  5833.0  232.16  5941.7  233.45
#Mann=3,-1,0
  3932.0    0.05       0  4994.2    0.03       0  5000.2    0.05       0
Bank Sta=4994.2,5000.2
Exp/Cntr=0.3,0.1

Type RM Length L Ch R = 1,266,0,0,0
BEGIN DESCRIPTION:
Mapping XS e906394b
END DESCRIPTION:
XS GIS Cut Line= 4
      3755088.72     10522465.39      3753871.86     10522750.54
      3753493.86     10523526.43      3754634.46     10524100.04
#Sta/Elev= 30
  3445.0  271.00  3546.8  268.31  3741.9  251.15  4050.1  231.42  4122.0  231.44
  4573.9  219.68  4594.4  218.05  4778.9  218.83  4829.5  217.27  4914.1  218.79
  4981.7  218.54  5009.8  216.75  5026.8  218.29  5094.4  218.99  5349.2  217.76
  5598.6  215.71  5601.3  215.21  5604.6  215.71  5640.6  217.55  5698.6  217.28
  5735.5  219.45  5818.7  219.10  5825.9  218.60  6101.6  220.27  6377.2  218.07
  6449.8  220.37  6566.4  226.88  6695.4  235.44  6823.7  247.08  6834.6  247.04
#Mann=7,-1,0
  3445.0    0.05       0  5349.2    0.12       0  5598.6    0.03       0
  5604.6    0.12       0  5818.7    0.07       0  5825.9    0.12       0
  6566.4    0.05       0
Bank Sta=5598.6,5604.6
Exp/Cntr=0.3,0.1

Chan Stop Cuts=-1