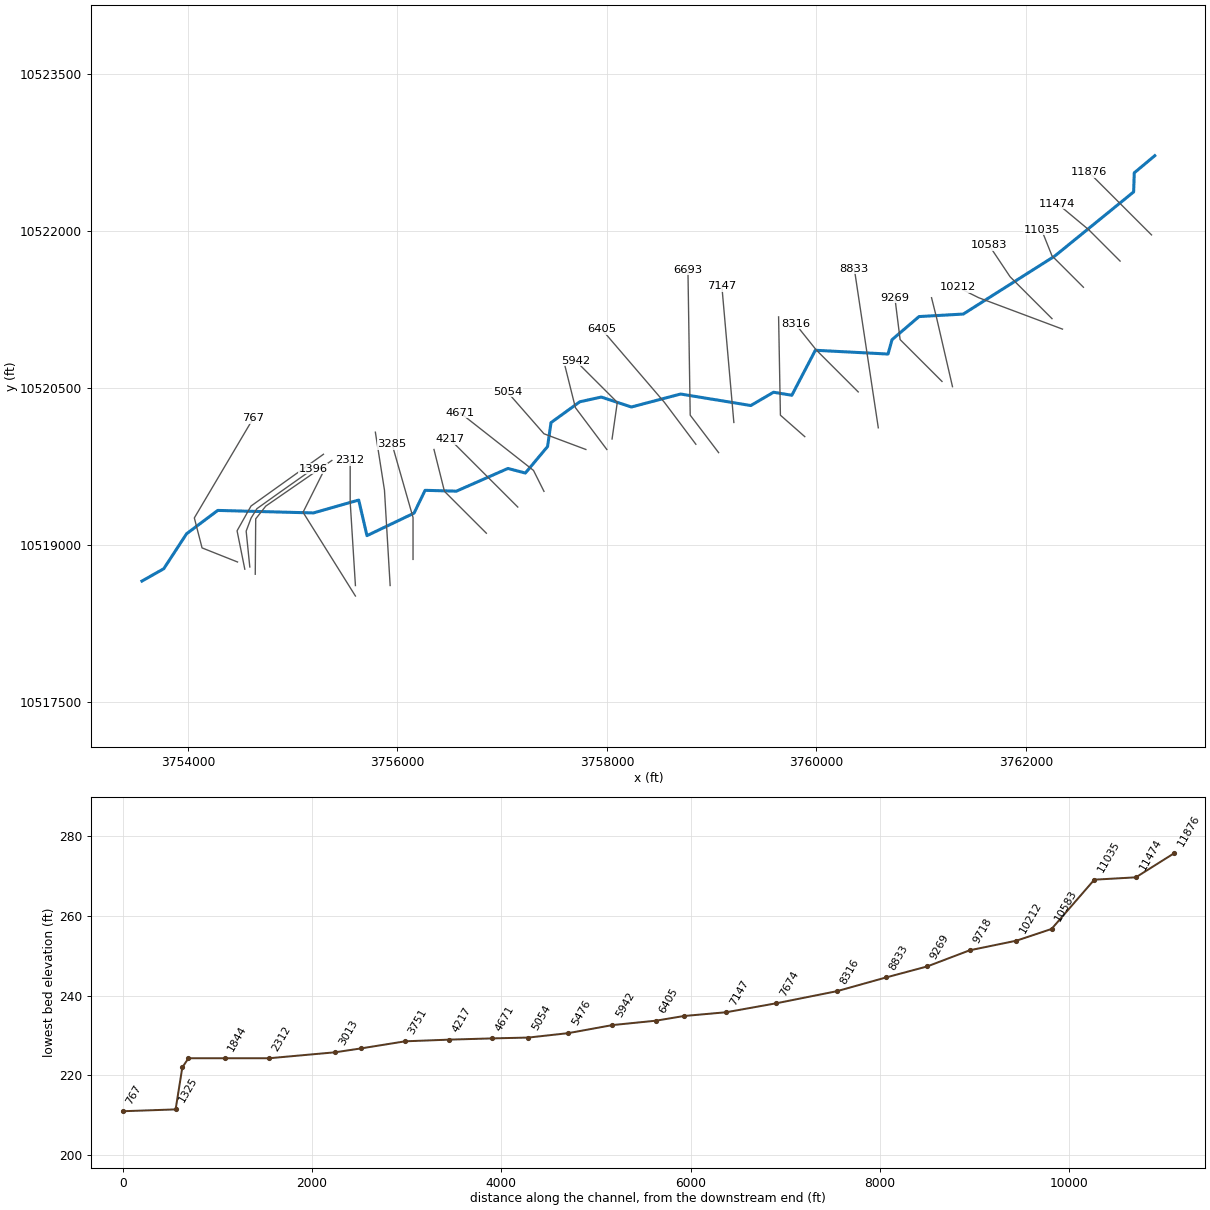
--- UNT109 IN BECR.prj (project) ---

Proj Title=UNT109 IN BECR Base Level Engineering
Current Plan=p01
Default Exp/Contr=0.3,0.1
English Units
Geom File=g01
Flow File=f01
Plan File=p01
Y Axis Title=Elevation
X Axis Title(PF)=Main Channel Distance
X Axis Title(XS)=Station
BEGIN DESCRIPTION:
UNT109 IN BECR
END DESCRIPTION:
DSS Export Rating Curves= 0
DSS Export Rating Curve Sorted= 0
DSS Export Volume Flow Curves= 0
DXF OffsetX= 0
DXF OffsetY= 0
DXF ScaleX= 1
DXF ScaleY= 10

--- UNT109 IN BECR.p01 (plan) ---

Plan Title=Multiple Run
Short Identifier=Multiple
Geom File=g01
Flow File=f01
Subcritical Flow
K Sum by GR= 0
Std Step Tol= 0.01
Critical Tol= 0.01
Num of Std Step Trials= 20
Max Error Tol= 0.3
Flow Tol Ratio= 0.001
Split Flow NTrial= 30
Split Flow Tol= 0.02
Split Flow Ratio= 0.02
Log Output Level= 0
Friction Slope Method= 1
Unsteady Friction Slope Method= 2
Unsteady Bridges Friction Slope Method= 1
Parabolic Critical Depth
Global Vel Dist=  1 , 1 , 1
Global Log Level= 0
CheckData=True
Encroach Param= -1, 0, 0, 0
BEGIN DESCRIPTION:
Multiple Run
END DESCRIPTION:

--- UNT109 IN BECR.f01 (steady flow) ---

Flow Title=Multiple
Program Version=4.10
Number of Profiles= 7
Profile Names=10-year,25-year,50-year,1pct_min,100-year,1pct_plu,500-year
River Rch & RM=UNT109 IN BECR,Reach-1         ,11876
     898    1261    1573    1442    1950    2638    3010
River Rch & RM=UNT109 IN BECR,Reach-1         ,10583
    1265    1804    2272    2102    2842    3844    4465
River Rch & RM=UNT109 IN BECR,Reach-1         ,7147
    1448    2066    2604    2407    3255    4402    5108
Boundary for River Rch & Prof#=UNT109 IN BECR,Reach-1         , 1
Up Type= 0
Dn Type= 3
Dn Slope=0.002
Boundary for River Rch & Prof#=UNT109 IN BECR,Reach-1         , 2
Up Type= 0
Dn Type= 3
Dn Slope=0.002
Boundary for River Rch & Prof#=UNT109 IN BECR,Reach-1         , 3
Up Type= 0
Dn Type= 3
Dn Slope=0.002
Boundary for River Rch & Prof#=UNT109 IN BECR,Reach-1         , 4
Up Type= 0
Dn Type= 3
Dn Slope=0.002
Boundary for River Rch & Prof#=UNT109 IN BECR,Reach-1         , 5
Up Type= 0
Dn Type= 3
Dn Slope=0.002
Boundary for River Rch & Prof#=UNT109 IN BECR,Reach-1         , 6
Up Type= 0
Dn Type= 3
Dn Slope=0.002
Boundary for River Rch & Prof#=UNT109 IN BECR,Reach-1         , 7
Up Type= 0
Dn Type= 3
Dn Slope=0.002
DSS Import GetInterval= 0
DSS Import GetPeak= 0
DSS Import FillOption= 0

--- UNT109 IN BECR.g01 (geometry) ---

Geom Title=Existing Conditions
Program Version=4.10

River Reach=UNT109 IN BECR  ,Reach-1
Reach XY= 30
      3763230.75       10522717.        3763035.       10522553.
        3763029.       10522371.      3762275.75       10521758.
       3761402.5       10521204.      3760980.25       10521180.
      3760722.25       10520959.      3760684.25       10520822.
       3759990.5       10520858.      3759765.75       10520428.
        3759591.       10520457.      3759374.25       10520330.
      3758704.25       10520440.        3758234.       10520316.
       3757946.5       10520411.      3757741.75       10520366.
        3757467.       10520167.      3757433.75       10519938.
        3757222.       10519685.       3757055.5       10519729.
      3756563.75       10519512.      3756264.75       10519520.
      3756159.25       10519302.        3755710.       10519087.
        3755631.       10519427.      3755198.25       10519304.
      3754285.25       10519328.      3753987.75       10519105.
        3753770.       10518771.       3753561.5       10518653.

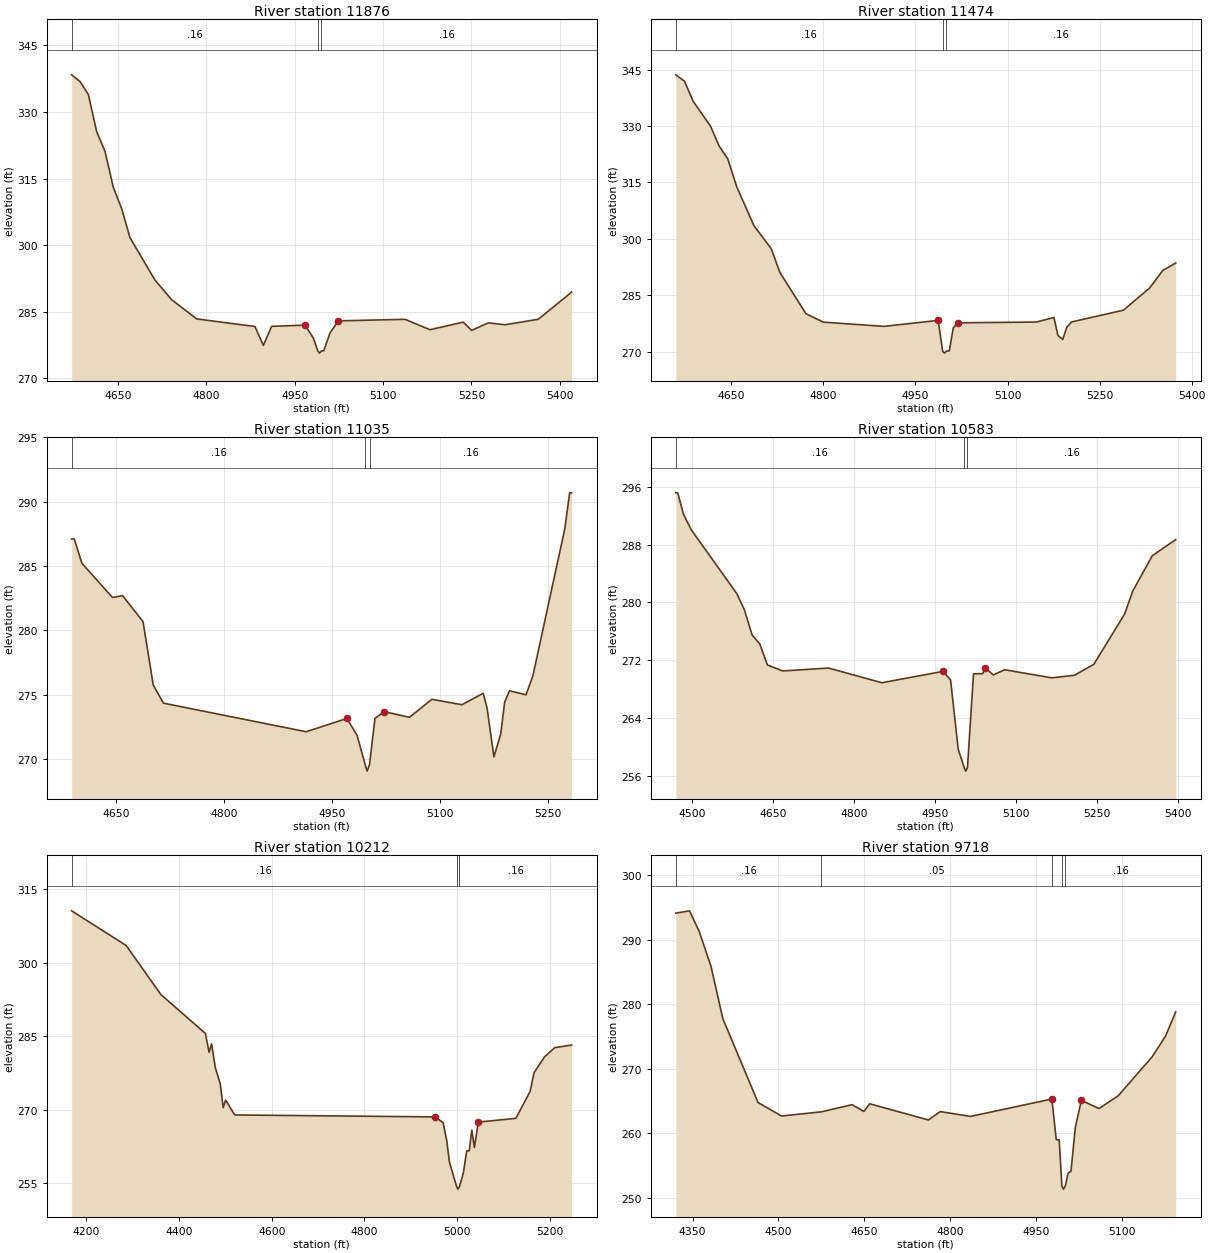
Type RM Length L Ch R = 1 ,11876   ,402,402,402
BEGIN DESCRIPTION:
UNT109 IN BECR 24.0
END DESCRIPTION:
XS GIS Cut Line= 3
      3763199.62     10521960.17      3762899.61     10522260.19
      3762599.64     10522560.15
#Sta/Elev= 30
  4571.5  338.38  4585.7  336.87  4599.8  333.95  4613.9  325.61  4628.1  321.12
  4642.2  313.03  4656.4   308.2  4670.5  301.67  4712.9  292.12  4741.2   287.7
  4783.7  283.36  4882.6  281.65  4896.8  277.39  4910.9  281.69  4967.5  281.96
  4981.6  279.09  4989.2  276.15    4992  275.65  4995.2  276.15  4999.3  276.15
  5009.9  280.18  5024.1  282.92  5137.2  283.27  5179.6  280.93  5236.2  282.64
  5250.3  280.77  5278.6  282.47  5306.9  282.04  5363.5  283.29    5420   289.4
#Mann= 3 ,-1 , 0
  4571.5     .16       0  4989.2     .07       0  4995.2     .16       0
Bank Sta=4967.5,5024.1
XS Rating Curve= 0 ,0
Exp/Cntr=0.3,0.1

Type RM Length L Ch R = 1 ,11474   ,439,439,439
BEGIN DESCRIPTION:
UNT109 IN BECR 23.0
END DESCRIPTION:
XS GIS Cut Line= 3
      3762899.58     10521710.22      3762599.61     10522010.19
      3762299.63     10522260.17
#Sta/Elev= 30
  4559.4  343.59  4573.5  341.92  4587.6  336.59  4615.9  329.97  4630.1  324.66
  4644.2  321.23  4658.4  313.98  4686.6  303.54  4714.9  297.41  4729.1  291.07
  4771.5  280.12  4799.8  277.88  4898.8  276.76  4986.9  278.35  4994.3  270.15
    4997  269.65  5000.3  270.15  5005.1  270.27  5011.6  276.38  5019.4   277.7
    5147  277.91  5175.6  279.13  5182.1  274.36  5189.9  273.27  5196.4   276.5
  5204.3  277.93  5288.9  281.07  5331.8     287  5352.7  291.57  5374.1   293.6
#Mann= 3 ,-1 , 0
  4559.4     .16       0  4994.3     .07       0  5000.3     .16       0
Bank Sta=4986.9,5019.4
XS Rating Curve= 0 ,0
Exp/Cntr=0.3,0.1

Type RM Length L Ch R = 1 ,11035   ,452,452,452
BEGIN DESCRIPTION:
UNT109 IN BECR 22.0
END DESCRIPTION:
XS GIS Cut Line= 3
      3762549.63     10521460.17      3762249.61     10521760.19
      3762149.59     10522010.23
#Sta/Elev= 30
  4588.7   287.1  4592.3   287.1  4602.9  285.21  4645.3  282.55  4659.4  282.69
  4687.7  280.68  4701.9  275.75    4716  274.34    4914  272.12  4970.6  273.15
  4984.7  271.83  4995.9  269.56  4998.6  269.06  5001.9  269.56  5009.5  273.16
  5022.4  273.68  5057.4  273.24  5088.4  274.64  5130.1  274.22  5159.7  275.11
  5165.1  273.93  5174.5  270.17    5184  271.95  5189.4  274.42  5196.1   275.3
    5219  274.99  5228.4  276.42  5272.8  287.88  5279.6  290.68  5282.3  290.68
#Mann= 3 ,-1 , 0
  4588.7     .16       0  4995.9     .07       0  5001.9     .16       0
Bank Sta=4970.6,5022.4
XS Rating Curve= 0 ,0
Exp/Cntr=0.3,0.1

Type RM Length L Ch R = 1 ,10583   ,371,371,371
BEGIN DESCRIPTION:
UNT109 IN BECR 21.0
END DESCRIPTION:
XS GIS Cut Line= 3
      3762249.63     10521160.17      3761849.61     10521560.19
      3761649.59     10521860.22
#Sta/Elev= 30
  4469.5  295.15  4473.1  295.15  4483.7   292.2  4497.8  290.08  4582.7  281.21
  4596.8  278.95  4610.9  275.51  4625.1  274.27  4639.2  271.37  4667.5  270.54
  4752.4  270.94  4851.4  268.91  4964.5  270.48  4978.6   269.3  4992.8  259.71
  5003.9   257.2  5006.7   256.7  5009.9   257.2  5021.1  270.14  5038.2  270.17
  5042.7  270.98  5057.7  269.99  5078.8  270.71  5165.9  269.59    5208  269.94
    5244  271.46  5301.1  278.41  5316.1  281.57  5352.2  286.45  5395.8  288.69
#Mann= 3 ,-1 , 0
  4469.5     .16       0  5003.9     .07       0  5009.9     .16       0
Bank Sta=4964.5,5042.7
XS Rating Curve= 0 ,0
Exp/Cntr=0.3,0.1

Type RM Length L Ch R = 1 ,10212   ,494,494,494
BEGIN DESCRIPTION:
UNT109 IN BECR 20.0
END DESCRIPTION:
XS GIS Cut Line= 3
      3762349.63     10521060.18      3761549.61     10521360.19
      3761349.64     10521460.18
#Sta/Elev= 30
  4168.6  310.64  4286.1  303.56  4360.9  293.54    4457  285.58    4465  281.72
  4470.3  283.47  4478.3  278.61    4489  275.28  4495.3  270.42  4500.6  271.96
  4520.2  268.92  4952.7  268.52  4969.6  267.33  4977.6  263.53    4983  259.35
  4998.7  254.26  5001.4  253.76  5004.7  254.26  5013.2  257.07  5020.4   261.6
  5025.8   261.6  5031.4  265.82    5037  262.27  5045.4  267.46  5126.4  268.23
  5157.2  273.75  5165.6  277.55  5187.9  280.77  5210.3  282.68  5246.6   283.2
#Mann= 3 ,-1 , 0
  4168.6     .16       0  4998.7     .07       0  5004.7     .16       0
Bank Sta=4952.7,5045.4
XS Rating Curve= 0 ,0
Exp/Cntr=0.3,0.1

Type RM Length L Ch R = 1 ,9718    ,449,449,449
BEGIN DESCRIPTION:
UNT109 IN BECR 19.0
END DESCRIPTION:
XS GIS Cut Line= 3
      3761299.62     10520510.15      3761149.61     10521160.19
       3761099.6     10521360.21
#Sta/Elev= 30
  4320.7  294.16  4344.7  294.52  4361.8  291.27  4382.3  285.87  4402.8  277.81
  4464.4  264.78  4505.5  262.69    4575  263.34  4628.6  264.45  4649.2   263.4
  4659.4  264.59    4762  262.08  4782.6  263.38  4835.6  262.63  4977.6  265.33
  4978.1  264.92  4985.3  259.01  4990.4  259.01  4995.1  251.85  4997.9  251.35
  5001.1  251.85  5005.9  253.82    5011  254.13  5018.7  260.99  5029.1  265.12
    5060  263.85  5093.5  265.83  5152.7  271.87  5175.9  275.05    5194  278.85
#Mann= 5 ,-1 , 0
  4320.7     .16       0    4575     .05       0  4978.1     .16       0
  4995.1     .07       0  5001.1     .16       0
Bank Sta=4977.6,5029.1
XS Rating Curve= 0 ,0
Exp/Cntr=0.3,0.1

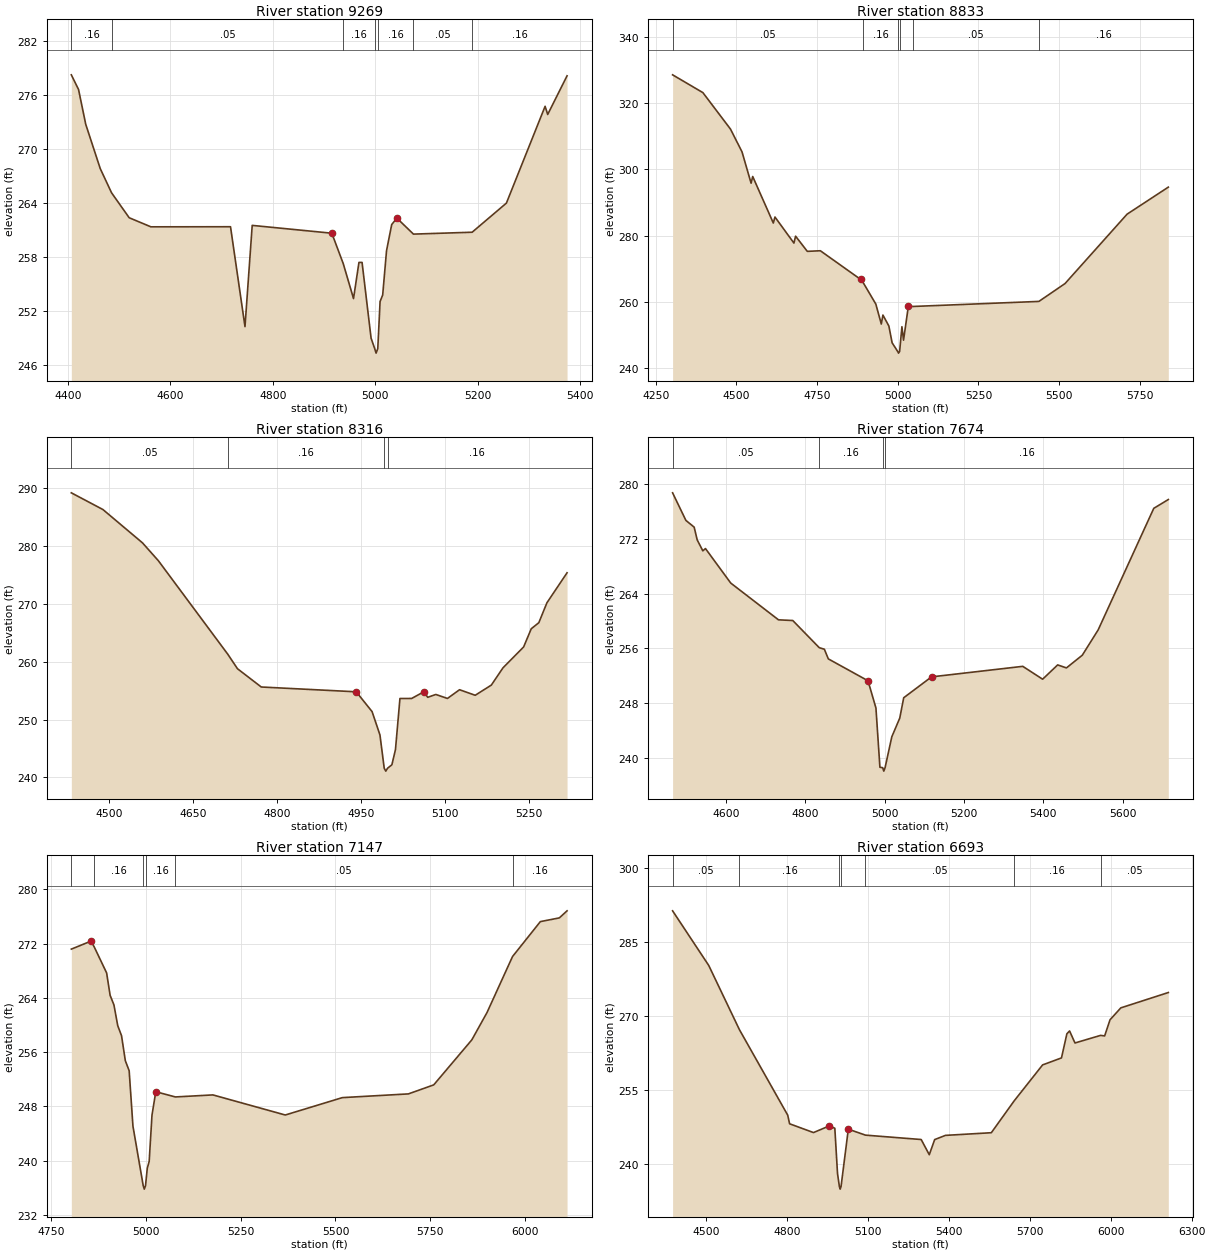
Type RM Length L Ch R = 1 ,9269    ,436,436,436
BEGIN DESCRIPTION:
UNT109 IN BECR 18.0
END DESCRIPTION:
XS GIS Cut Line= 3
      3761199.58     10520560.22      3760799.61     10520960.19
       3760749.6     10521360.23
#Sta/Elev= 30
  4406.2  278.26  4420.3  276.63  4434.4  272.75  4462.7  267.83  4484.9  265.13
  4519.3  262.36  4561.7  261.35  4717.3  261.36  4745.6  250.25  4759.7  261.51
  4915.3  260.64  4937.6  257.26  4957.7  253.37  4968.3  257.39  4974.4  257.39
    4992  248.97  4999.1   247.8  5001.8   247.3  5005.1   247.8  5009.6  253.04
  5014.7  253.77  5022.2  258.69  5032.3   261.6  5042.4  262.32  5074.8  260.54
  5189.5  260.75  5256.5  263.99  5332.1  274.76  5337.2  273.85    5375  278.15
#Mann= 7 ,-1 , 0
  4406.2     .16       0  4484.9     .05       0  4937.6     .16       0
  4999.1     .07       0  5005.1     .16       0  5074.8     .05       0
  5189.5     .16       0
Bank Sta=4915.3,5042.4
XS Rating Curve= 0 ,0
Exp/Cntr=0.3,0.1

Type RM Length L Ch R = 1 ,8833    ,517,517,517
BEGIN DESCRIPTION:
UNT109 IN BECR 17.0
END DESCRIPTION:
XS GIS Cut Line= 2
      3760591.27     10520117.35      3760362.32      10521636.7
#Sta/Elev= 30
  4302.1  328.48    4396  323.11  4481.5  312.12  4517.3  305.24  4545.4  295.79
  4550.4  297.81  4614.3  283.77  4619.4  285.59  4678.2  277.72  4683.3  279.81
  4719.6  275.23  4760.1  275.41  4885.1  266.76  4892.9  265.79    4932  259.33
    4949  253.31    4954  256.01  4972.4  252.72  4982.5  247.65  4999.8  245.03
  5002.5  244.53  5005.8  245.03  5012.9   252.5  5017.9  248.44  5033.1  258.85
  5046.2   258.6  5437.5  260.13  5518.5  265.52  5710.7  286.44  5838.6   294.6
#Mann= 6 ,-1 , 0
  4302.1     .05       0  4892.9     .16       0  4999.8     .07       0
  5005.8     .16       0  5046.2     .05       0  5437.5     .16       0
Bank Sta=4885.1,5033.1
XS Rating Curve= 0 ,0
Exp/Cntr=0.3,0.1

Type RM Length L Ch R = 1 ,8316    ,642,642,642
BEGIN DESCRIPTION:
UNT109 IN BECR 16.0
END DESCRIPTION:
XS GIS Cut Line= 3
      3760399.57     10520460.22      3759999.61     10520860.19
       3759799.6     10521110.19
#Sta/Elev= 30
  4432.2   289.2  4488.7  286.31  4559.4  280.55  4587.7  277.47  4711.9  261.29
  4729.1   258.8  4771.6  255.64  4941.3  254.81  4969.6  251.39  4983.7  247.35
  4991.3   241.6  4994.1   241.1  4997.3   241.6    5005   242.2  5011.4  244.82
  5019.4  253.65  5040.3  253.66  5061.9   254.8  5069.1  253.86  5083.5  254.35
  5104.3  253.66  5125.9  255.17  5153.9  254.21  5182.7  255.97  5203.5  258.95
  5240.4  262.56    5254   265.7  5267.6  266.76    5282  270.19    5318  275.38
#Mann= 4 ,-1 , 0
  4432.2     .05       0  4711.9     .16       0  4991.3     .07       0
  4997.3     .16       0
Bank Sta=4941.3,5061.9
XS Rating Curve= 0 ,0
Exp/Cntr=0.3,0.1

Type RM Length L Ch R = 1 ,7674    ,527,527,527
BEGIN DESCRIPTION:
UNT109 IN BECR 15.0
END DESCRIPTION:
XS GIS Cut Line= 3
      3759889.52     10520032.83      3759656.85     10520237.72
      3759639.52     10521176.93
#Sta/Elev= 30
  4465.4  278.75  4498.9  274.72  4519.8  273.73  4527.4  271.87  4541.6  270.27
  4548.3   270.6  4611.9  265.56  4732.3  260.18  4768.3  260.08    4835  256.11
  4847.9  255.88  4857.9  254.47  4957.9  251.27  4977.9  247.29  4987.9  238.63
  4994.9  238.56  4997.7  238.06  5000.9  238.56  5017.9  243.08  5037.9  245.81
  5047.9  248.79    5118  251.84    5348  253.38    5398   251.5  5435.9  253.59
    5458  253.15    5498  255.01    5538  258.71  5678.1  276.48  5714.8  277.77
#Mann= 4 ,-1 , 0
  4465.4     .05       0    4835     .16       0  4994.9     .07       0
  5000.9     .16       0
Bank Sta=4957.9,5118
XS Rating Curve= 0 ,0
Exp/Cntr=0.3,0.1

Type RM Length L Ch R = 1 ,7147    ,454,454,454
BEGIN DESCRIPTION:
UNT109 IN BECR 14.0
END DESCRIPTION:
XS GIS Cut Line= 2
       3759212.4      10520168.3      3759097.82     10521470.37
#Sta/Elev= 30
  4803.5  271.18  4855.6  272.36  4864.5  271.43  4896.6  267.67  4905.8  264.37
  4915.8  262.97  4925.9   259.9  4935.9  258.42  4945.9  254.74    4956  253.26
    4966  245.09  4993.1  236.32  4995.9  235.82  4999.1  236.32  5003.8   238.9
  5008.8  239.92  5016.2  246.73  5026.2  250.17  5077.9   249.4  5176.8   249.7
  5367.6  246.74  5518.1   249.3  5692.4  249.85  5759.1  251.18  5859.5  257.81
  5899.6  261.84  5966.9  270.09  6040.2  275.23  6090.3  275.78  6110.6  276.82
#Mann= 6 ,-1 , 0
  4803.5     .05       0  4864.5     .16       0  4993.1     .07       0
  4999.1     .16       0  5077.9     .05       0  5966.9     .16       0
Bank Sta=4855.6,5026.2
XS Rating Curve= 0 ,0
Exp/Cntr=0.3,0.1

Type RM Length L Ch R = 1 ,6693    ,288,288,288
BEGIN DESCRIPTION:
Mapping XS 933e67b5
END DESCRIPTION:
XS GIS Cut Line= 3
      3759066.93     10519880.03      3758795.69     10520238.07
        3758774.     10521626.12
#Sta/Elev= 30
  4376.1  291.29  4510.2   280.2  4623.7   267.2  4802.8  249.85  4809.8   248.1
  4898.4  246.32  4957.4  247.68  4977.4  247.19  4987.4  238.01  4994.4  235.35
  4997.2  234.85  5000.4  235.35  5027.4  247.01    5091   245.8  5297.5  244.91
  5327.5  241.83  5347.5   244.9  5387.5  245.75  5557.5  246.29    5642  252.74
  5747.5  260.04  5817.5  261.46  5837.5  266.35  5847.5  266.93  5867.5  264.49
  5962.5  266.03  5977.5  265.92  5997.5   269.2  6037.5  271.61  6213.5  274.72
#Mann= 7 ,-1 , 0
  4376.1     .05       0  4623.7     .16       0  4994.4     .07       0
  5000.4     .16       0    5091     .05       0    5642     .16       0
  5962.5     .05       0
Bank Sta=4957.4,5027.4
XS Rating Curve= 0 ,0
Exp/Cntr=0.3,0.1

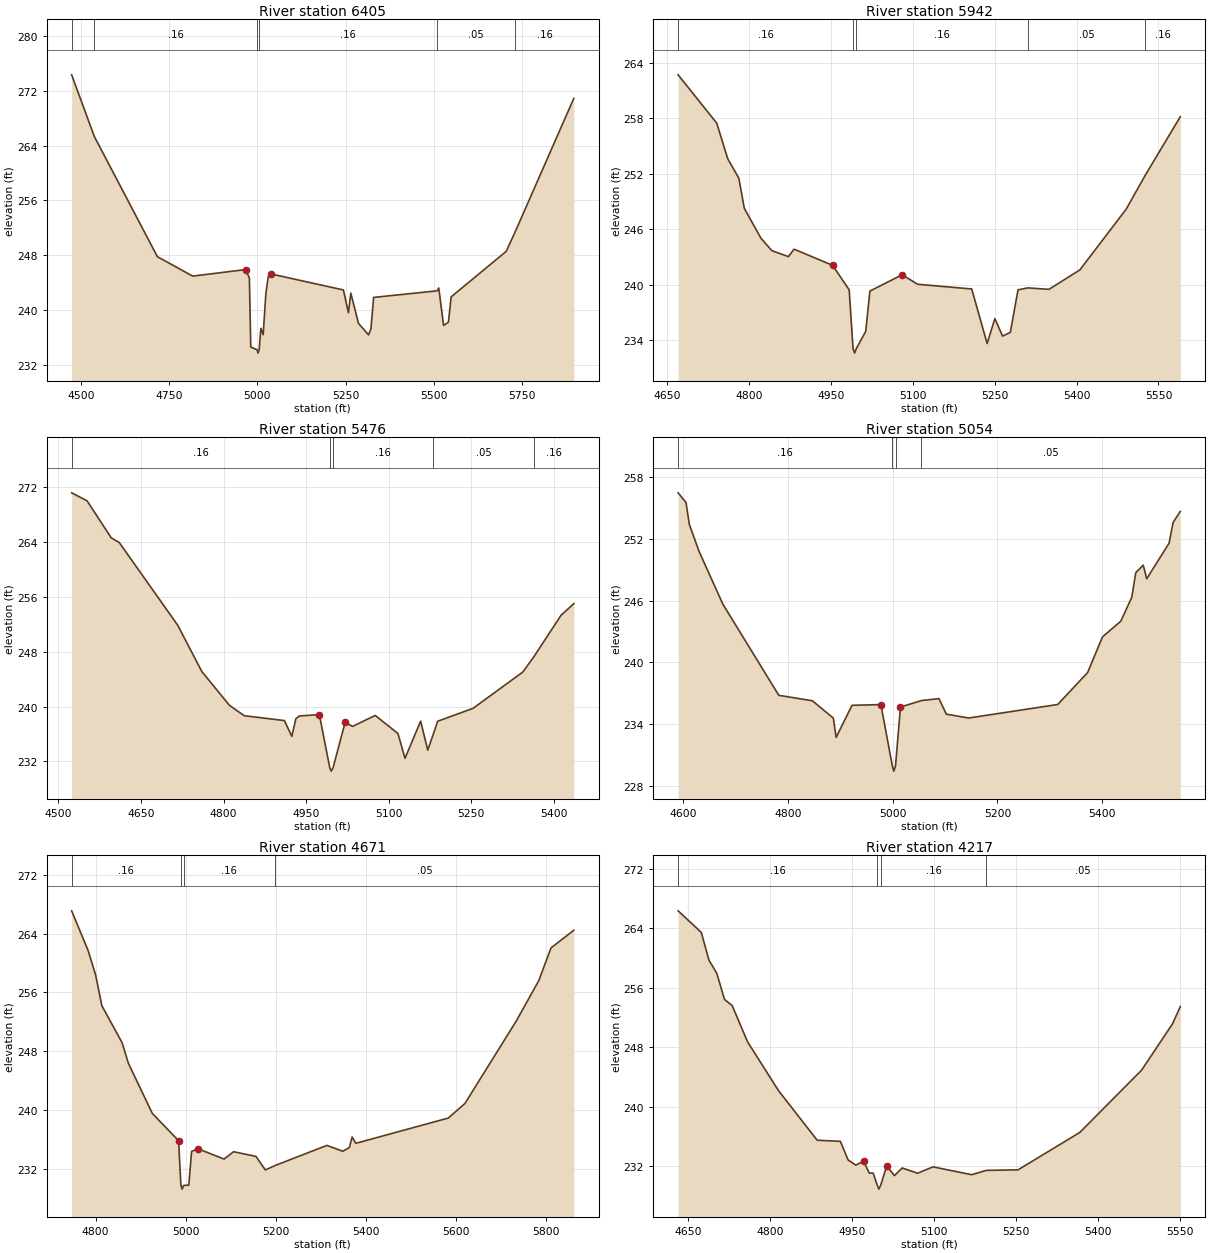
Type RM Length L Ch R = 1 ,6405    ,463,463,463
BEGIN DESCRIPTION:
UNT109 IN BECR 13.0
END DESCRIPTION:
XS GIS Cut Line= 3
      3758849.64     10519960.15      3758549.61     10520360.19
      3757949.61     10521060.19
#Sta/Elev= 30
  4474.3  274.36  4538.7  265.33  4717.1  247.79  4817.1  244.95  4967.1  245.91
  4977.6  244.66  4981.5  234.59  4999.3   234.2  5002.1   233.7  5005.3   234.2
    5010  237.32  5016.6  236.39  5024.3  242.42  5030.9  244.83  5038.6  245.27
  5243.8  242.93  5258.1   239.6  5264.7  242.47  5286.6  238.04  5315.1  236.37
  5321.7  237.23  5329.4  241.84  5509.1   242.8  5513.8  243.22  5527.5  237.74
  5541.2  238.23  5548.9  241.92  5704.8  248.57    5730  251.39  5896.3  270.93
#Mann= 6 ,-1 , 0
  4474.3     .05       0  4538.7     .16       0  4999.3     .07       0
  5005.3     .16       0  5509.1     .05       0    5730     .16       0
Bank Sta=4967.1,5038.6
XS Rating Curve= 0 ,0
Exp/Cntr=0.3,0.1

Type RM Length L Ch R = 1 ,5942    ,466,466,466
BEGIN DESCRIPTION:
UNT109 IN BECR 12.0
END DESCRIPTION:
XS GIS Cut Line= 3
      3758049.62     10520010.24      3758099.61     10520360.19
       3757699.6     10520760.19
#Sta/Elev= 30
  4670.8   262.7  4741.5  257.47  4761.7  253.61  4781.9  251.52    4792  248.25
  4822.3  245.03  4842.5  243.67  4872.8  243.03  4882.9  243.84  4953.6  242.09
  4983.9  239.44    4991  233.09  4993.8  232.59    4997  233.09  5014.2  234.94
  5021.8   239.3  5080.9  241.07  5109.2  240.04  5208.2  239.53  5236.4  233.63
  5250.6  236.32  5264.7  234.43  5278.9  234.84    5293  239.44  5310.9  239.65
  5349.6  239.49  5406.1  241.59    5491  248.17  5525.3  251.78    5590  258.17
#Mann= 5 ,-1 , 0
  4670.8     .16       0    4991     .07       0    4997     .16       0
  5310.9     .05       0  5525.3     .16       0
Bank Sta=4953.6,5080.9
XS Rating Curve= 0 ,0
Exp/Cntr=0.3,0.1

Type RM Length L Ch R = 1 ,5476    ,422,422,422
BEGIN DESCRIPTION:
UNT109 IN BECR 11.0
END DESCRIPTION:
XS GIS Cut Line= 3
      3757999.61     10519910.19      3757699.61     10520310.19
      3757599.61     10520710.18
#Sta/Elev= 30
  4524.1   271.2  4552.2  270.03    4596  264.63  4610.6  263.94  4716.8  251.87
  4760.6  245.11  4810.6  240.19  4837.6  238.66  4910.6  237.95  4924.1  235.64
  4931.4  238.22  4937.6  238.62  4974.1  238.82    4993  231.07  4995.7  230.57
    4999  231.07    5021  237.71  5034.4   237.1  5075.6   238.7  5116.9  236.06
  5129.7  232.44  5158.1  237.87    5171  233.64  5180.8  235.89    5189  237.85
  5253.4  239.74  5343.6  245.03  5363.3  247.21  5413.2  253.33  5436.4  255.02
#Mann= 5 ,-1 , 0
  4524.1     .16       0    4993     .07       0    4999     .16       0
  5180.8     .05       0  5363.3     .16       0
Bank Sta=4974.1,5021
XS Rating Curve= 0 ,0
Exp/Cntr=0.3,0.1

Type RM Length L Ch R = 1 ,5054    ,383,383,383
BEGIN DESCRIPTION:
UNT109 IN BECR 10.0
END DESCRIPTION:
XS GIS Cut Line= 3
      3757799.57      10519910.2      3757399.61     10520060.19
      3757049.59     10520460.21
#Sta/Elev= 30
  4590.3  256.44  4605.4   255.5  4611.6   253.4  4630.3  250.76  4675.7  245.65
  4782.5  236.81  4846.6  236.28  4886.6   234.6    4892  232.73  4922.2  235.84
  4977.4  235.91  4999.3  229.96  5002.1  229.46  5005.3  229.96  5014.8  235.67
  5054.8   236.3  5088.2  236.49  5102.4  234.98  5145.1  234.61    5315  235.92
    5372  239.01  5400.4  242.47  5435.5     244  5456.4  246.32    5464   248.7
  5478.3  249.43  5484.9  248.11  5527.6  251.56  5535.2  253.56    5549  254.64
#Mann= 4 ,-1 , 0
  4590.3     .16       0  4999.3     .07       0  5005.3     .16       0
  5054.8     .05       0
Bank Sta=4977.4,5014.8
XS Rating Curve= 0 ,0
Exp/Cntr=0.3,0.1

Type RM Length L Ch R = 1 ,4671    ,454,454,454
BEGIN DESCRIPTION:
UNT109 IN BECR 9.0
END DESCRIPTION:
XS GIS Cut Line= 3
      3757399.63     10519510.15      3757299.61     10519710.19
      3756599.59      10520260.2
#Sta/Elev= 30
  4746.9  267.11  4783.3  261.73  4800.1  258.38    4814  254.19  4858.8  249.17
  4872.7  246.38  4925.8  239.55  4984.1  235.84  4989.2  229.75    4992  229.25
  4995.2  229.75  5006.7  229.79    5013  234.39  5027.5  234.73    5085  233.34
  5106.1  234.34  5155.8   233.7  5176.6  231.86  5198.1  232.46  5313.1   235.2
  5348.3   234.4  5362.8  234.91  5369.1  236.33  5377.2  235.48  5582.4  238.92
  5619.1  240.89  5733.3  252.14    5783  257.61  5810.2  262.07  5860.8  264.47
#Mann= 4 ,-1 , 0
  4746.9     .16       0  4989.2     .07       0  4995.2     .16       0
  5198.1     .05       0
Bank Sta=4984.1,5027.5
XS Rating Curve= 0 ,0
Exp/Cntr=0.3,0.1

Type RM Length L Ch R = 1 ,4217    ,466,466,466
BEGIN DESCRIPTION:
UNT109 IN BECR 8.0
END DESCRIPTION:
XS GIS Cut Line= 3
      3757149.62     10519360.18      3756899.61     10519610.19
      3756499.58     10520010.22
#Sta/Elev= 30
  4631.6  266.33    4674  263.43  4688.2  259.68  4702.3  257.96  4716.5  254.43
  4730.6  253.59  4758.9  248.71  4815.5  242.16  4886.2  235.51  4928.6  235.36
  4942.7  232.87  4956.9  232.16    4971   232.7  4981.6  231.09  4988.7  231.09
  4996.3  229.44  4999.1  228.94  5002.3  229.44  5013.5  232.06  5027.6  230.75
  5041.7  231.78    5070  231.08  5098.3  231.93    5169  230.88  5195.7  231.46
  5253.9  231.53    5367  236.56  5480.1  244.93  5536.7  251.16  5550.9  253.46
#Mann= 4 ,-1 , 0
  4631.6     .16       0  4996.3     .07       0  5002.3     .16       0
  5195.7     .05       0
Bank Sta=4971,5013.5
XS Rating Curve= 0 ,0
Exp/Cntr=0.3,0.1

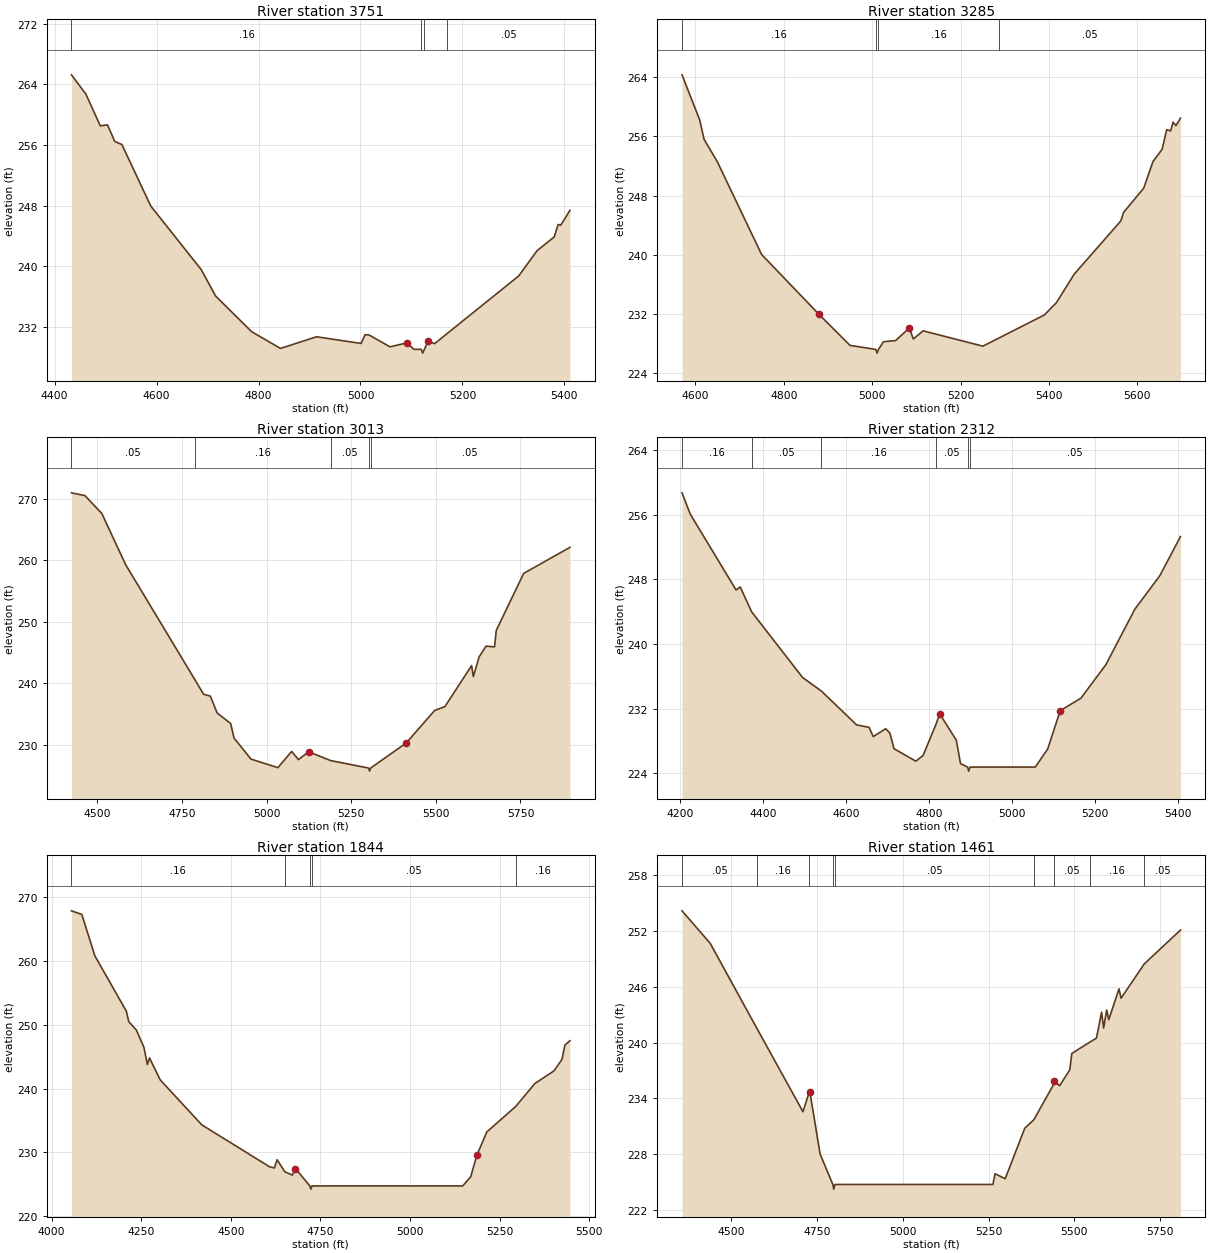
Type RM Length L Ch R = 1 ,3751    ,466,466,466
BEGIN DESCRIPTION:
UNT109 IN BECR 7.0
END DESCRIPTION:
XS GIS Cut Line= 3
      3756849.63     10519110.17      3756449.61     10519510.19
      3756349.61     10519910.17
#Sta/Elev= 30
    4433  265.27  4461.3  262.73  4489.6  258.53  4503.7  258.66  4517.9  256.48
    4532  256.06  4588.6  247.94  4687.6  239.55  4715.9  236.05  4786.6  231.35
  4843.1  229.14  4913.9  230.68  5001.3   229.8    5009  230.95  5016.8  230.92
    5058  229.35  5091.5  229.88  5104.4  229.03  5119.4  229.02  5122.2  228.52
  5125.4  229.02  5132.7  230.12  5145.6  229.77  5170.7  231.14  5310.5  238.71
  5346.6  242.05  5380.1  243.86  5387.8   245.5    5393  245.42    5411  247.37
#Mann= 4 ,-1 , 0
    4433     .16       0  5119.4     .07       0  5125.4     .16       0
  5170.7     .05       0
Bank Sta=5091.5,5132.7
XS Rating Curve= 0 ,0
Exp/Cntr=0.3,0.1

Type RM Length L Ch R = 1 ,3285    ,272,272,272
BEGIN DESCRIPTION:
UNT109 IN BECR 6.0
END DESCRIPTION:
XS GIS Cut Line= 3
      3756149.61     10518860.14      3756149.61     10519260.19
       3755949.6     10519960.23
#Sta/Elev= 30
  4569.6   264.3  4609.6  258.21  4619.6  255.58  4649.6  252.56  4749.6  240.06
  4879.6  231.97  4949.6  227.79  5008.2  227.24    5011  226.74  5014.2  227.24
  5025.5  228.28  5052.8  228.43    5084  230.12  5093.1  228.65  5115.2  229.75
  5250.5  227.68  5287.9  228.81  5389.6  231.89  5416.9  233.55  5457.2   237.4
  5562.5  244.57    5569  245.74  5614.5     249  5635.3  252.58  5656.1  254.25
  5666.5   256.9  5675.6  256.74  5680.8  257.92  5687.3  257.44  5697.7  258.45
#Mann= 4 ,-1 , 0
  4569.6     .16       0  5008.2     .07       0  5014.2     .16       0
  5287.9     .05       0
Bank Sta=4879.6,5084
XS Rating Curve= 0 ,0
Exp/Cntr=0.3,0.1

Type RM Length L Ch R = 1 ,3013    ,701,701,701
BEGIN DESCRIPTION:
UNT109 IN BECR 5.0
END DESCRIPTION:
XS GIS Cut Line= 3
       3755931.1      10518610.5      3755876.85     10519521.92
      3755790.06     10520075.22
#Sta/Elev= 30
  4423.1  270.94  4462.9  270.49  4512.9  267.58  4583.1  259.29  4787.9  240.61
  4813.5  238.25  4833.5  237.94  4853.6  235.21  4893.6   233.5  4903.6  231.14
  4953.7  227.72  5033.1  226.33  5073.9  228.97    5094  227.64    5124  228.92
    5189  227.48  5301.3  226.27  5304.1  225.77  5307.3  226.27  5412.7  230.35
  5496.3  235.61  5526.7  236.24  5605.7   242.9  5610.7  241.12  5627.9  244.32
  5648.2  246.05  5673.4  245.94  5678.5  248.61  5759.5  257.86  5896.2  262.09
#Mann= 5 ,-1 , 0
  4423.1     .05       0  4787.9     .16       0    5189     .05       0
  5301.3     .07       0  5307.3     .05       0
Bank Sta=5124,5412.7
XS Rating Curve= 0 ,0
Exp/Cntr=0.3,0.1

Type RM Length L Ch R = 1 ,2312    ,468,468,468
BEGIN DESCRIPTION:
UNT109 IN BECR 4.0
END DESCRIPTION:
XS GIS Cut Line= 3
      3755599.61     10518610.19      3755549.61     10519410.19
      3755549.61     10519810.23
#Sta/Elev= 30
  4205.4  258.71  4225.4  256.06  4335.7  246.69  4345.7  247.06  4373.4  243.97
    4496  235.86  4541.4  234.18  4626.2  229.99  4656.3  229.69  4666.3  228.54
  4696.4  229.52  4706.4  228.99  4716.4  227.05    4769   225.5  4786.5  226.21
  4818.2  230.14  4826.6  231.36  4866.7  228.09  4876.7  225.21  4893.7  224.77
  4896.5  224.27  4899.7  224.77    5057  224.77    5087  227.02    5117  231.75
    5167   233.3    5227  237.43    5297  244.31    5357  248.44    5407   253.3
#Mann= 6 ,-1 , 0
  4205.4     .16       0  4373.4     .05       0  4541.4     .16       0
  4818.2     .05       0  4893.7    .033       0  4899.7     .05       0
Bank Sta=4826.6,5117
XS Rating Curve= 0 ,0
Exp/Cntr=0.3,0.1

Type RM Length L Ch R = 1 ,1844    ,383,383,383
BEGIN DESCRIPTION:
UNT109 IN BECR 3.0
END DESCRIPTION:
XS GIS Cut Line= 3
      3755599.61     10518510.19      3755099.61     10519310.19
       3755299.6     10519710.18
#Sta/Elev= 30
  4055.4  267.78  4084.3  267.22  4120.8  260.73  4208.7  252.07  4215.2  250.46
  4236.4  249.15  4257.6  246.44  4267.1  243.74    4273  244.79    4303  241.35
  4419.2  234.31  4607.9  227.77  4621.4  227.58  4629.1  228.87  4650.6  226.98
  4671.6  226.47  4680.4  227.49  4720.4  224.77  4723.2  224.27  4726.4  224.77
  5146.9  224.77  5169.3   226.2  5186.1  229.53    5214   233.2  5294.5  237.18
  5348.2  240.78  5401.3  242.75  5423.7  244.53    5432   246.8    5446  247.47
#Mann= 5 ,-1 , 0
  4055.4     .16       0  4650.6     .05       0  4720.4    .033       0
  4726.4     .05       0  5294.5     .16       0
Bank Sta=4680.4,5186.1
XS Rating Curve= 0 ,0
Exp/Cntr=0.3,0.1

Type RM Length L Ch R = 1 ,1461    ,65,65,65
BEGIN DESCRIPTION:
Mapping XS 0f554734
END DESCRIPTION:
XS GIS Cut Line= 4
      3754643.34     10518718.11      3754647.68      10519247.6
      3754743.84      10519369.4      3755374.51     10519805.23
#Sta/Elev= 30
  4357.6  254.14  4439.7  250.65  4575.2  241.55  4709.7  232.58    4728  234.68
  4729.7  234.74  4759.7  228.03  4796.7  224.77  4799.4  224.27  4802.7  224.77
  5262.8  224.77  5268.9  225.92  5298.6  225.39  5355.4   230.8    5382  231.72
  5439.7  235.51  5441.9  235.89  5456.8  235.36  5486.5  237.07  5492.6  238.83
  5546.2  240.08  5564.2  240.47  5579.1  243.26  5585.2  241.56    5594   243.5
  5600.1  242.46  5629.8  245.76  5635.9  244.76  5703.4  248.44  5808.9  252.08
#Mann= 9 ,-1 , 0
  4357.6     .05       0  4575.2     .16       0    4728     .05       0
  4796.7    .033       0  4802.7     .05       0    5382     .16       0
  5439.7     .05       0  5546.2     .16       0  5703.4     .05       0
Bank Sta=4729.7,5441.9
XS Rating Curve= 0 ,0
Exp/Cntr=0.3,0.1

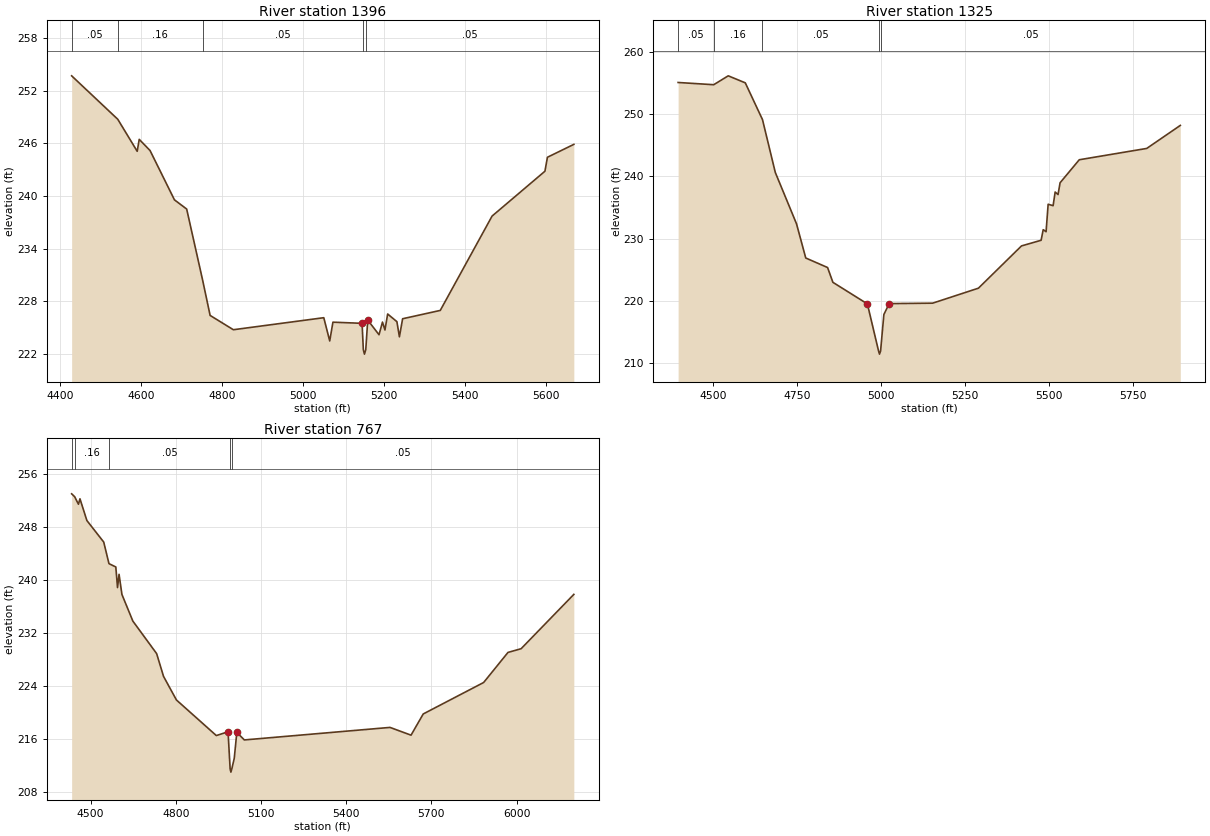
Type RM Length L Ch R = 1 ,1396    ,71,71,71
BEGIN DESCRIPTION:
UNT109 IN BECR 2.0
END DESCRIPTION:
XS GIS Cut Line= 6
      3754591.26     10518787.54      3754556.54     10519130.42
      3754604.28     10519256.29      3754659.54     10519344.97
      3754873.42     10519497.84      3755195.05     10519724.83
#Sta/Elev= 30
  4428.3   253.7  4542.2  248.75  4590.2   245.1  4595.2  246.46  4621.9  245.19
  4682.2  239.57  4712.4  238.52  4751.6  230.46  4770.3   226.4  4827.7  224.77
    5051  226.14  5065.7  223.49  5073.6  225.63  5145.6   225.5  5148.7  222.49
  5151.5  221.99  5154.7  222.49  5159.6  225.87  5187.4   224.2    5196  225.64
  5202.1  224.74  5208.8  226.56  5231.6  225.69  5237.8  223.96  5245.7  226.02
  5338.7  226.97  5466.7  237.72  5597.2  242.83  5603.4  244.42  5668.6  245.89
#Mann= 5 ,-1 , 0
  4428.3     .05       0  4542.2     .16       0  4751.6     .05       0
  5148.7     .03       0  5154.7     .05       0
Bank Sta=5145.6,5159.6
XS Rating Curve= 0 ,0
Exp/Cntr=0.3,0.1

Type RM Length L Ch R = 1 ,1325    ,558,558,558
BEGIN DESCRIPTION:
Mapping XS 958f1da8
END DESCRIPTION:
XS GIS Cut Line= 4
      3754543.56     10518766.42      3754469.78     10519133.14
      3754602.86      10519369.9      3755294.44     10519864.48
#Sta/Elev= 30
  4396.5   255.1  4502.5  254.74  4545.8  256.17  4596.6  255.04  4647.8  249.14
    4686  240.64  4749.2  232.38  4776.7  226.89  4841.7  225.36  4857.6  222.98
  4960.3  219.51  4993.6  211.94  4996.4  211.44  4999.6  211.94  5009.4  217.81
  5025.3  219.56  5154.7  219.63  5291.1  222.04  5419.3  228.83  5477.8  229.74
    5484  231.44  5492.6  231.12  5498.7  235.53  5513.5   235.3  5519.6  237.49
  5528.2  237.09  5534.3  238.98  5591.4  242.68  5792.4   244.5  5892.4   248.2
#Mann= 5 ,-1 , 0
  4396.5     .05       0  4502.5     .16       0  4647.8     .05       0
  4993.6     .03       0  4999.6     .05       0
Bank Sta=4960.3,5025.3
XS Rating Curve= 0 ,0
Exp/Cntr=0.3,0.1

Type RM Length L Ch R = 1 ,767     ,0,0,0
BEGIN DESCRIPTION:
UNT109 IN BECR 1.0
END DESCRIPTION:
XS GIS Cut Line= 4
      3754474.09     10518835.27      3754135.53     10518969.83
      3754061.75     10519256.29       3754625.3       10520210.
#Sta/Elev= 30
  4433.6  252.99  4444.3  252.55  4457.5  251.42  4462.9  252.24  4487.2  248.96
  4546.5  245.71    4565  242.45  4589.1  241.95  4595.1  238.84  4600.5  240.84
  4610.6   237.8  4649.1  233.78  4732.8  228.87  4757.1  225.43  4802.5  221.87
  4942.9   216.5  4984.2  217.07  4991.5  211.48  4994.2  210.98  4997.5  211.48
    5006  213.06  5015.1  216.98  5041.6  215.84  5554.3  217.73  5628.4  216.56
  5671.3  219.76    5884  224.51  5969.7  229.05  6015.9  229.61  6201.5  237.81
#Mann= 5 ,-1 , 0
  4433.6     .05       0  4444.3     .16       0    4565     .05       0
  4991.5     .03       0  4997.5     .05       0
Bank Sta=4984.2,5015.1
XS Rating Curve= 0 ,0
Exp/Cntr=0.3,0.1

Chan Stop Cuts=-1
Use User Specified Reach Order=0
Composite Channel Slope=5