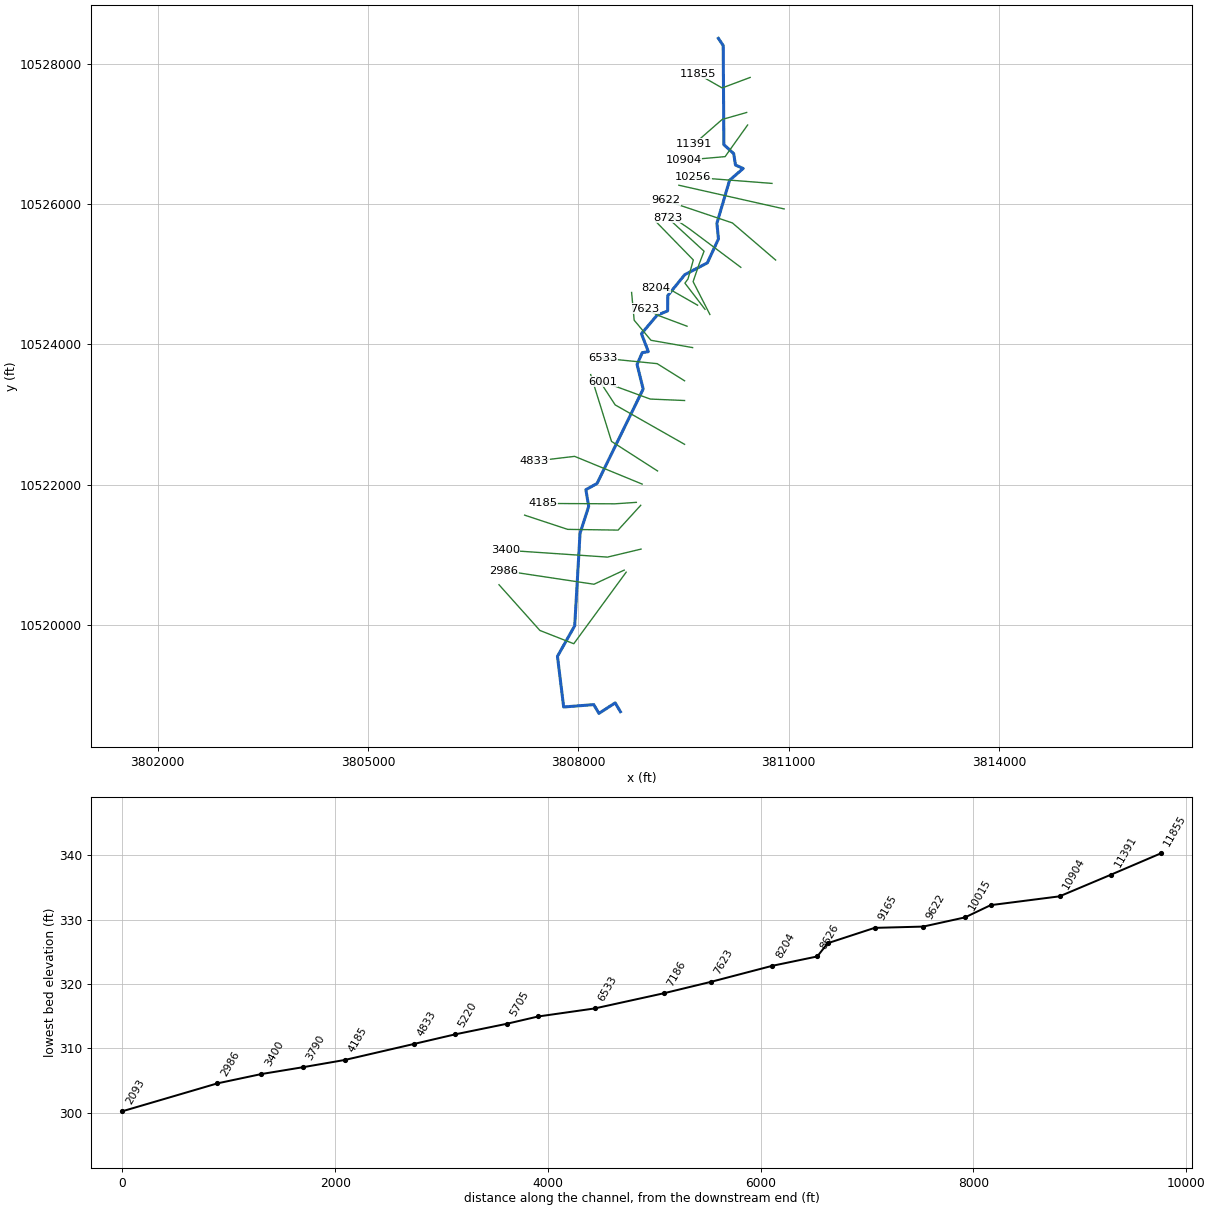
--- UNT112 IN BECR.prj (project) ---

Proj Title=UNT112 IN BECR Base Level Engineering
Current Plan=p01
Default Exp/Contr=0.3,0.1
English Units
Geom File=g01
Flow File=f01
Plan File=p01
BEGIN DESCRIPTION:
UNT112 IN BECR
END DESCRIPTION:

--- UNT112 IN BECR.p01 (plan) ---

Plan Title=Multiple Run
Short Identifier=Multiple
Geom File=g01
Flow File=f01
Subcritical Flow
K Sum by GR= 0
Std Step Tol= 0.01
Critical Tol= 0.01
Num of Std Step Trials= 20
Max Error Tol= 0.3
Flow Tol Ratio= 0.001
Split Flow NTrial= 30
Split Flow Tol= 0.02
Split Flow Ratio= 0.02
Log Output Level= 0
Friction Slope Method= 1
Unsteady Friction Slope Method= 2
Unsteady Bridges Friction Slope Method= 1
Parabolic Critical Depth
Global Vel Dist=  1 , 1 , 1
Global Log Level= 0
CheckData=True
Encroach Param= -1, 0, 0, 0
BEGIN DESCRIPTION:
Multiple Run
END DESCRIPTION:

--- UNT112 IN BECR.f01 (steady flow) ---

Flow Title=Multiple
Number of Profiles=7
Profile Names=10-year,25-year,50-year,1pct_min,100-year,1pct_plu,500-year
River Rch & RM= UNT112 IN BECR,Reach-1,11855
     980    1357    1675    1518    2053    2776    3093
River Rch & RM= UNT112 IN BECR,Reach-1,7186
    1138    1580    1954    1772    2396    3240    3616
Boundary for River Rch & Prof#=UNT112 IN BECR,Reach-1,1
Up Type=0
Dn Type=3
Dn Slope=0.005
Boundary for River Rch & Prof#=UNT112 IN BECR,Reach-1,2
Up Type=0
Dn Type=3
Dn Slope=0.005
Boundary for River Rch & Prof#=UNT112 IN BECR,Reach-1,3
Up Type=0
Dn Type=3
Dn Slope=0.005
Boundary for River Rch & Prof#=UNT112 IN BECR,Reach-1,4
Up Type=0
Dn Type=3
Dn Slope=0.005
Boundary for River Rch & Prof#=UNT112 IN BECR,Reach-1,5
Up Type=0
Dn Type=3
Dn Slope=0.005
Boundary for River Rch & Prof#=UNT112 IN BECR,Reach-1,6
Up Type=0
Dn Type=3
Dn Slope=0.005
Boundary for River Rch & Prof#=UNT112 IN BECR,Reach-1,7
Up Type=0
Dn Type=3
Dn Slope=0.005

--- UNT112 IN BECR.g01 (geometry) ---

Geom Title=Existing Conditions

River Reach=UNT112 IN BECR,Reach-1
Reach XY= 30
      3809995.75     10528368.00      3810065.00     10528265.00
      3810074.50     10526851.00      3810214.50     10526723.00
      3810240.00     10526560.00      3810349.75     10526511.00
      3810156.00     10526343.00      3809975.00     10525729.00
      3809997.25     10525506.00      3809838.50     10525164.00
      3809517.25     10524996.00      3809275.00     10524698.00
      3809272.50     10524479.00      3809120.00     10524415.00
      3808899.25     10524153.00      3808997.50     10523898.00
      3808910.75     10523883.00      3808836.50     10523715.00
      3808923.75     10523364.00      3808266.00     10522016.00
      3808106.75     10521928.00      3808147.00     10521690.00
      3808023.75     10521305.00      3807947.75     10519986.00
      3807701.75     10519550.00      3807790.25     10518827.00
      3808219.25     10518861.00      3808293.50     10518736.00
      3808524.75     10518886.00      3808599.50     10518760.00

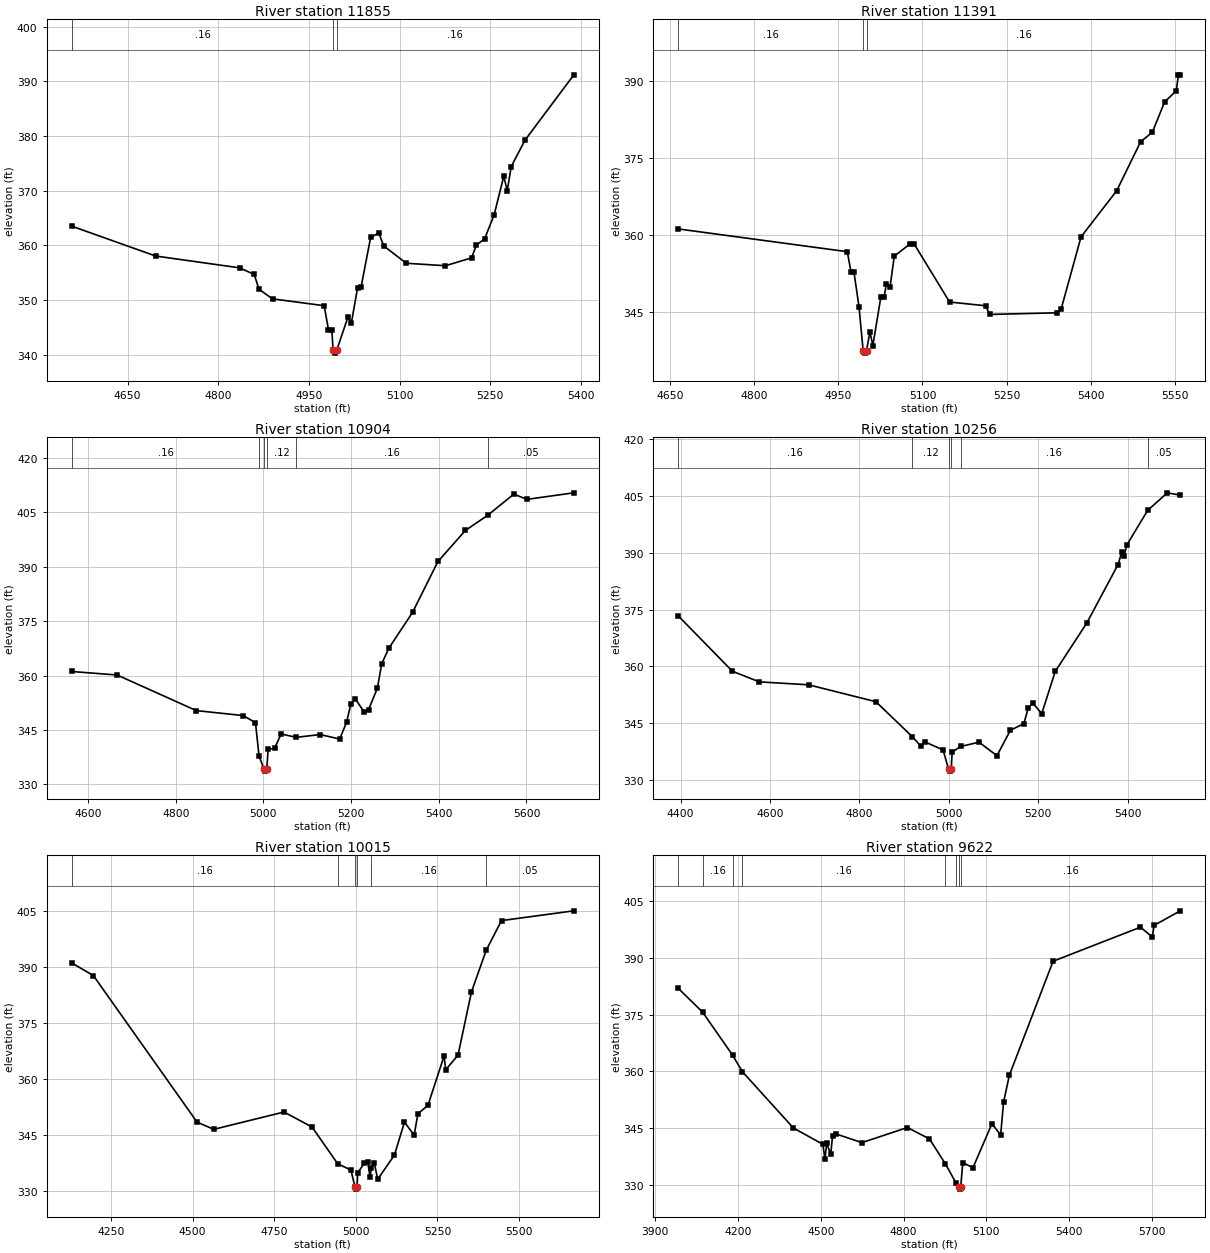
Type RM Length L Ch R = 1,11855,464,464,464
BEGIN DESCRIPTION:
UNT112 IN BECR 20.0
END DESCRIPTION:
XS GIS Cut Line= 3
      3810449.62     10527810.19      3810049.61     10527660.19
      3809699.63     10527860.18
#Sta/Elev= 30
  4557.8  363.52  4696.6  358.06  4835.5  355.90  4859.5  354.69  4867.5  351.97
  4889.8  350.23  4975.2  348.98  4982.3  344.61  4987.9  344.61  4989.9  340.81
  4992.7  340.31  4995.9  340.81  5014.5  346.90  5020.3  345.90  5030.4  352.22
  5036.1  352.31  5052.0  361.45  5065.6  362.29  5073.5  359.93  5111.0  356.74
  5175.8  356.29  5219.0  357.73  5226.9  360.06  5240.6  361.21  5256.4  365.64
  5272.2  372.64  5278.0  370.00  5284.5  374.42  5307.5  379.27  5388.1  391.19
#Mann=3,-1,0
  4557.8    0.16       0  4989.9    0.07       0  4995.9    0.16       0
Bank Sta=4989.9,4995.9
Exp/Cntr=0.3,0.1

Type RM Length L Ch R = 1,11391,487,487,487
BEGIN DESCRIPTION:
UNT112 IN BECR 19.0
END DESCRIPTION:
XS GIS Cut Line= 3
      3810399.56     10527310.17      3810049.61     10527210.19
      3809649.58     10526860.16
#Sta/Elev= 30
  4664.4  361.24  4966.0  356.80  4972.5  352.85  4977.7  352.92  4986.8  346.08
  4994.2  337.53  4996.9  337.03  5000.2  337.53  5006.3  341.19  5011.5  338.50
  5025.8  347.98  5031.7  347.98  5035.5  350.48  5042.1  349.85  5049.7  355.93
  5078.2  358.35  5084.8  358.37  5148.4  346.99  5213.0  346.26  5219.6  344.57
  5340.1  344.89  5347.3  345.59  5382.9  359.71  5446.4  368.68  5489.2  378.25
  5510.0  380.08  5531.9  386.00  5552.7  388.16  5556.5  391.28  5559.9  391.28
#Mann=3,-1,0
  4664.4    0.16       0  4994.2    0.07       0  5000.2    0.16       0
Bank Sta=4994.2,5000.2
Exp/Cntr=0.3,0.1

Type RM Length L Ch R = 1,10904,648,648,648
BEGIN DESCRIPTION:
UNT112 IN BECR 18.0
END DESCRIPTION:
XS GIS Cut Line= 3
      3810413.21     10527131.57      3810092.00     10526680.15
      3809503.13     10526628.19
#Sta/Elev= 30
  4562.9  361.11  4666.5  360.14  4846.9  350.33  4954.2  348.95  4981.9  347.01
  4990.1  337.77  5001.6  334.14  5004.4  333.64  5007.6  334.14  5010.8  339.69
  5025.5  339.91  5040.3  343.88  5075.1  342.96  5129.4  343.72  5174.0  342.49
  5189.6  347.06  5199.7  352.18  5209.7  353.56  5229.8  349.93  5239.8  350.57
  5259.9  356.50  5269.9  363.26  5286.1  367.52  5340.2  377.41  5398.2  391.45
  5460.7  399.99  5512.1  404.22  5571.1  410.01  5601.2  408.57  5708.1  410.37
#Mann=6,-1,0
  4562.9    0.16       0  4990.1    0.12       0  5001.6    0.07       0
  5007.6    0.12       0  5075.1    0.16       0  5512.1    0.05       0
Bank Sta=5001.6,5007.6
Exp/Cntr=0.3,0.1

Type RM Length L Ch R = 1,10256,241,241,241
BEGIN DESCRIPTION:
UNT112 IN BECR 17.0
END DESCRIPTION:
XS GIS Cut Line= 2
      3810760.38     10526298.21      3809640.64     10526385.01
#Sta/Elev= 30
  4394.8  373.33  4515.9  358.69  4576.1  355.88  4686.4  355.10  4836.9  350.63
  4918.8  341.34  4937.2  338.91  4947.2  339.97  4987.3  337.87  4999.5  332.77
  5002.3  332.27  5005.5  332.77  5007.5  337.31  5026.8  338.80  5067.6  339.92
  5107.7  336.35  5137.8  343.08  5167.9  344.82  5177.9  349.05  5187.9  350.25
  5208.0  347.48  5238.1  358.64  5308.3  371.36  5378.5  386.87  5387.2  390.26
  5392.2  389.19  5398.6  392.15  5444.8  401.21  5488.8  405.87  5517.9  405.26
#Mann=6,-1,0
  4394.8    0.16       0  4918.8    0.12       0  4999.5    0.07       0
  5005.5    0.12       0  5026.8    0.16       0  5444.8    0.05       0
Bank Sta=4999.5,5005.5
Exp/Cntr=0.3,0.1

Type RM Length L Ch R = 1,10015,393,393,393
BEGIN DESCRIPTION:
UNT112 IN BECR 16.0
END DESCRIPTION:
XS GIS Cut Line= 2
      3810934.00     10525933.63      3809433.46     10526271.90
#Sta/Elev= 30
  4129.7  391.03  4195.7  387.68  4513.5  348.35  4564.7  346.41  4780.0  351.06
  4865.8  347.03  4944.4  337.18  4985.0  335.48  4997.6  330.87  5000.3  330.37
  5003.6  330.87  5005.7  334.75  5026.0  337.33  5036.3  337.64  5043.8  333.56
  5046.7  335.91  5056.8  337.29  5067.0  333.01  5118.3  339.53  5149.0  348.34
  5178.7  344.87  5190.1  350.59  5220.8  352.83  5270.3  366.07  5275.4  362.39
  5313.1  366.34  5354.1  383.24  5399.6  394.49  5446.3  402.41  5667.9  405.03
#Mann=6,-1,0
  4129.7    0.16       0  4944.4    0.12       0  4997.6    0.07       0
  5003.6    0.12       0  5046.7    0.16       0  5399.6    0.05       0
Bank Sta=4997.6,5003.6
Exp/Cntr=0.3,0.1

Type RM Length L Ch R = 1,9622,457,457,457
BEGIN DESCRIPTION:
UNT112 IN BECR 15.0
END DESCRIPTION:
XS GIS Cut Line= 3
      3810812.45     10525204.49      3810196.17     10525733.97
      3809242.95     10526054.60
#Sta/Elev= 30
  3984.1  381.93  4072.3  375.65  4180.7  364.31  4216.5  359.92  4401.3  345.06
  4507.8  340.78  4515.2  336.92  4522.0  341.07  4536.3  338.09  4542.9  342.99
  4557.1  343.46  4649.3  341.21  4814.1  345.20  4893.9  342.18  4951.7  335.59
  4989.9  330.59  5001.0  329.44  5003.7  328.94  5007.0  329.44  5014.5  335.94
  5051.4  334.58  5120.0  346.18  5151.7  343.23  5162.2  351.87  5183.3  359.01
  5341.6  389.08  5658.1  398.07  5700.3  395.50  5707.8  398.56  5802.3  402.38
#Mann=8,-1,0
  3984.1     0.1       0  4072.3    0.16       0  4180.7    0.05       0
  4216.5    0.16       0  4951.7    0.12       0  4989.9    0.16       0
  5001.0    0.07       0  5007.0    0.16       0
Bank Sta=5001,5007
Exp/Cntr=0.3,0.1

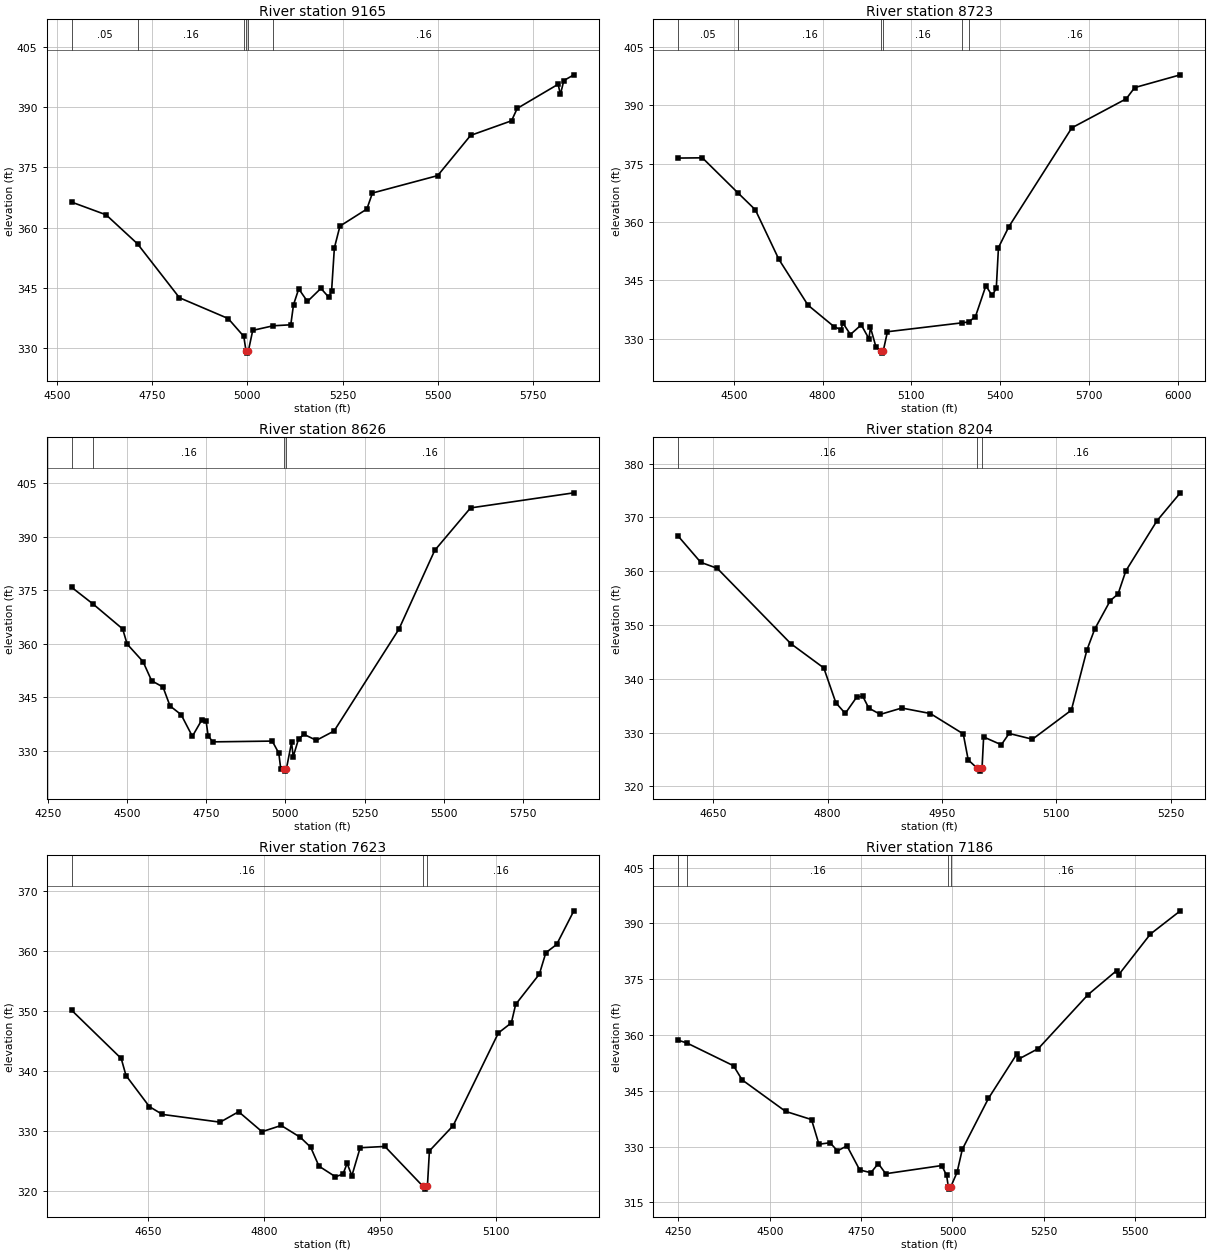
Type RM Length L Ch R = 1,9165,442,442,442
BEGIN DESCRIPTION:
Mapping XS 616f8db8
END DESCRIPTION:
XS GIS Cut Line= 3
      3810316.05     10525100.48      3809588.65     10525645.59
      3809250.07     10525878.26
#Sta/Elev= 30
  4538.3  366.35  4628.5  363.20  4711.1  355.97  4821.3  342.54  4949.4  337.36
  4990.5  332.91  4996.4  329.24  4999.2  328.74  5002.4  329.24  5014.0  334.41
  5067.6  335.55  5114.0  335.80  5121.2  340.80  5134.9  344.75  5157.8  341.61
  5193.2  344.87  5214.0  342.65  5221.2  344.12  5228.6  354.95  5243.2  360.38
  5314.0  364.63  5328.6  368.62  5500.1  372.96  5586.7  382.98  5694.3  386.62
  5709.2  389.70  5816.8  395.72  5822.8  393.17  5831.7  396.64  5858.1  398.07
#Mann=6,-1,0
  4538.3    0.05       0  4711.1    0.16       0  4990.5    0.12       0
  4996.4    0.07       0  5002.4    0.12       0  5067.6    0.16       0
Bank Sta=4996.4,5002.4
Exp/Cntr=0.3,0.1

Type RM Length L Ch R = 1,8723,97,97,97
BEGIN DESCRIPTION:
UNT112 IN BECR 14.0
END DESCRIPTION:
XS GIS Cut Line= 5
      3809875.26     10524427.58      3809635.70     10524896.30
      3809719.03     10525139.35      3809791.95     10525330.32
      3809271.09     10525809.51
#Sta/Elev= 30
  4312.7  376.41  4394.2  376.47  4514.5  367.46  4573.1  363.13  4652.5  350.42
  4750.8  338.67  4838.5  333.17  4862.8  332.33  4868.1  334.15  4894.1  331.13
  4930.7  333.60  4956.6  330.06  4961.9  332.93  4980.6  327.88  4998.8  326.85
  5001.5  326.35  5004.8  326.85  5019.2  331.84  5272.6  334.14  5293.2  334.34
  5316.4  335.73  5351.6  343.63  5372.5  341.15  5386.7  342.95  5394.1  353.44
  5429.3  358.80  5641.9  384.17  5825.7  391.62  5854.0  394.49  6008.2  397.77
#Mann=6,-1,0
  4312.7    0.05       0  4514.5    0.16       0  4998.8    0.07       0
  5004.8    0.16       0  5272.6    0.12       0  5293.2    0.16       0
Bank Sta=4998.8,5004.8
Exp/Cntr=0.3,0.1

Type RM Length L Ch R = 1,8626,422,422,422
BEGIN DESCRIPTION:
UNT112 IN BECR 13.0
END DESCRIPTION:
XS GIS Cut Line= 5
      3809805.54     10524501.34      3809519.09     10524874.59
      3809562.78     10524934.49      3809639.17     10525205.32
      3809107.93     10525750.45
#Sta/Elev= 30
  4324.6  375.79  4393.1  371.05  4485.5  364.15  4499.6  359.91  4549.9  354.99
  4577.0  349.64  4613.1  347.85  4635.1  342.58  4670.4  340.12  4705.8  334.05
  4734.8  338.52  4749.3  338.29  4755.6  334.26  4770.1  332.50  4958.3  332.72
  4979.1  329.34  4985.4  324.81  4996.8  324.80  4999.6  324.30  5002.8  324.80
  5019.4  332.34  5024.6  328.35  5041.4  333.30  5058.6  334.61  5097.8  332.93
  5153.9  335.55  5358.8  364.08  5472.0  386.17  5585.2  398.07  5911.8  402.30
#Mann=4,-1,0
  4324.6    0.05       0  4393.1    0.16       0  4996.8    0.07       0
  5002.8    0.16       0
Bank Sta=4996.8,5002.8
Exp/Cntr=0.3,0.1

Type RM Length L Ch R = 1,8204,581,581,581
BEGIN DESCRIPTION:
UNT112 IN BECR 12.0
END DESCRIPTION:
XS GIS Cut Line= 3
      3809699.63     10524560.18      3809349.61     10524760.19
      3809099.59     10524810.19
#Sta/Elev= 30
  4604.3  366.52  4633.8  361.66  4655.4  360.55  4751.9  346.54  4795.1  342.03
  4810.9  335.56  4823.2  333.57  4838.3  336.62  4846.2  336.75  4854.1  334.56
  4869.2  333.40  4897.3  334.58  4934.7  333.56  4977.9  329.77  4984.4  324.93
  4996.5  323.35  4999.3  322.85  5002.5  323.35  5004.6  329.20  5027.8  327.75
  5038.0  329.85  5068.6  328.78  5119.6  334.18  5140.0  345.37  5150.2  349.25
  5170.6  354.55  5180.8  355.77  5191.0  360.07  5231.8  369.38  5262.4  374.58
#Mann=3,-1,0
  4604.3    0.16       0  4996.5    0.07       0  5002.5    0.16       0
Bank Sta=4996.5,5002.5
Exp/Cntr=0.3,0.1

Type RM Length L Ch R = 1,7623,437,437,437
BEGIN DESCRIPTION:
UNT112 IN BECR 11.0
END DESCRIPTION:
XS GIS Cut Line= 3
      3809549.64     10524260.18      3809149.61     10524410.19
      3808949.64     10524510.17
#Sta/Elev= 30
  4550.6  350.13  4614.7  342.11  4620.9  339.27  4651.2  334.09  4668.1  332.79
  4742.9  331.50  4766.9  333.24  4797.2  329.91  4822.1  330.95  4847.0  328.96
  4860.3  327.32  4871.0  324.17  4892.4  322.40  4902.2  322.85  4907.5  324.63
  4913.7  322.58  4924.4  327.24  4956.5  327.45  5005.6  320.84  5008.3  320.34
  5011.6  320.84  5014.2  326.71  5044.9  330.91  5103.6  346.37  5120.4  348.05
  5126.0  351.13  5156.7  356.17  5165.1  359.74  5179.1  361.11  5201.4  366.72
#Mann=3,-1,0
  4550.6    0.16       0  5005.6    0.07       0  5011.6    0.16       0
Bank Sta=5005.6,5011.6
Exp/Cntr=0.3,0.1

Type RM Length L Ch R = 1,7186,653,653,653
BEGIN DESCRIPTION:
UNT112 IN BECR 10.0
END DESCRIPTION:
XS GIS Cut Line= 4
      3809628.78     10523955.32      3809035.00     10524059.49
      3808795.42     10524345.95      3808758.96     10524741.79
#Sta/Elev= 30
  4249.6  358.61  4274.0  357.83  4401.0  351.74  4424.4  347.95  4543.2  339.49
  4614.3  337.28  4634.6  330.65  4665.0  331.06  4685.3  328.87  4711.3  330.22
  4746.2  323.74  4776.7  323.01  4797.0  325.46  4817.3  322.73  4970.7  324.93
  4984.0  322.26  4988.8  319.09  4991.5  318.59  4994.8  319.09  5012.6  323.12
  5026.9  329.29  5098.5  342.99  5176.6  354.98  5183.1  353.64  5234.9  356.36
  5370.7  370.83  5449.4  377.34  5454.4  376.15  5541.5  387.13  5623.4  393.38
#Mann=4,-1,0
  4249.6    0.05       0  4274.0    0.16       0  4988.8    0.07       0
  4994.8    0.16       0
Bank Sta=4988.8,4994.8
Exp/Cntr=0.3,0.1

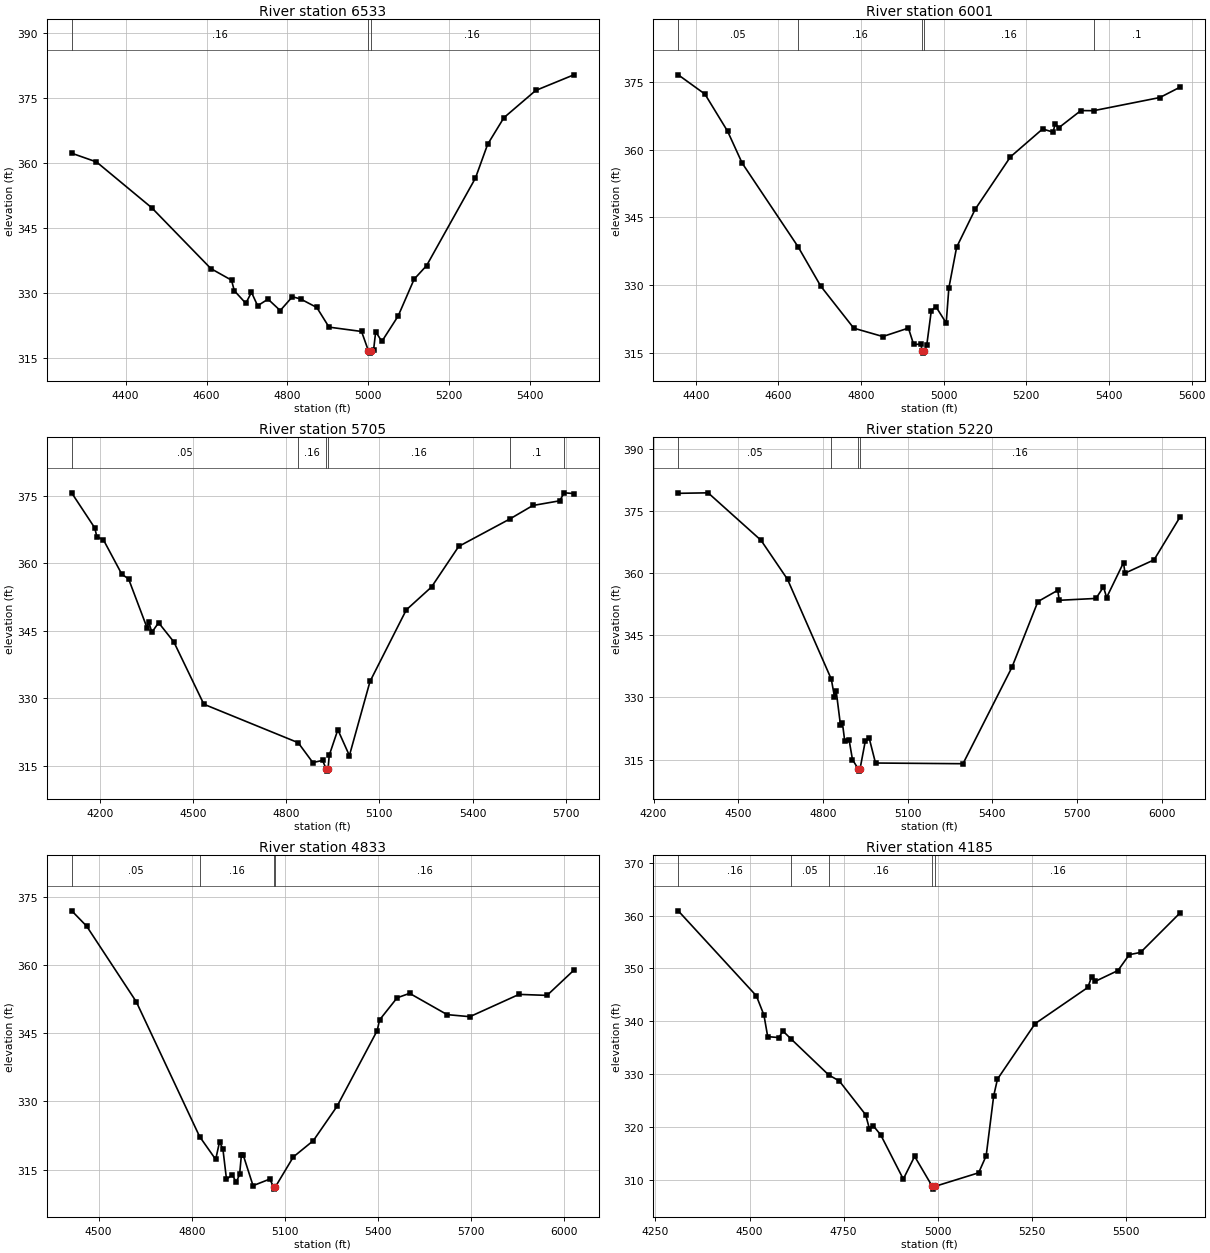
Type RM Length L Ch R = 1,6533,532,532,532
BEGIN DESCRIPTION:
UNT112 IN BECR 9.0
END DESCRIPTION:
XS GIS Cut Line= 3
      3809514.15     10523481.38      3809123.54     10523726.16
      3808347.53     10523804.28
#Sta/Elev= 30
  4267.0  362.27  4328.1  360.27  4464.8  349.70  4610.9  335.69  4661.8  333.03
  4668.7  330.60  4697.2  327.69  4711.1  330.24  4726.4  327.13  4752.0  328.66
  4782.2  326.03  4812.3  329.21  4832.4  328.70  4872.6  326.74  4902.8  322.21
  4983.2  321.21  5000.3  316.72  5003.0  316.22  5006.3  316.72  5013.1  317.05
  5018.1  321.14  5033.4  318.92  5073.6  324.76  5113.2  333.26  5144.0  336.39
  5264.6  356.53  5294.8  364.32  5335.0  370.46  5413.7  376.74  5507.9  380.34
#Mann=3,-1,0
  4267.0    0.16       0  5000.3    0.07       0  5006.3    0.16       0
Bank Sta=5000.3,5006.3
Exp/Cntr=0.3,0.1

Type RM Length L Ch R = 1,6001,296,296,296
BEGIN DESCRIPTION:
UNT112 IN BECR 8.0
END DESCRIPTION:
XS GIS Cut Line= 3
      3809514.15     10523200.12      3809024.59     10523220.95
      3808343.48     10523470.51
#Sta/Elev= 30
  4357.5  376.52  4422.1  372.26  4477.0  364.04  4512.2  357.00  4647.5  338.51
  4702.4  329.80  4782.4  320.49  4852.8  318.64  4914.7  320.51  4927.4  316.88
  4945.2  316.96  4947.5  315.47  4950.3  314.97  4953.5  315.47  4959.3  316.87
  4970.0  324.28  4981.0  325.28  5006.2  321.63  5012.6  329.38  5031.4  338.39
  5076.5  346.81  5161.7  358.38  5239.6  364.55  5264.8  363.85  5270.1  365.71
  5278.8  364.82  5332.1  368.61  5363.1  368.59  5523.4  371.50  5572.9  373.82
#Mann=5,-1,0
  4357.5    0.05       0  4647.5    0.16       0  4947.5    0.07       0
  4953.5    0.16       0  5363.1     0.1       0
Bank Sta=4947.5,4953.5
Exp/Cntr=0.3,0.1

Type RM Length L Ch R = 1,5705,485,485,485
BEGIN DESCRIPTION:
UNT112 IN BECR 7.0
END DESCRIPTION:
XS GIS Cut Line= 3
      3809514.14     10522575.13      3808524.59     10523137.61
      3808264.40     10523538.31
#Sta/Elev= 30
  4109.8  375.55  4184.0  367.79  4190.3  365.89  4211.9  365.14  4271.0  357.52
  4292.7  356.49  4351.8  345.70  4357.5  346.93  4367.6  344.65  4389.3  346.77
  4438.3  342.51  4534.9  328.68  4838.5  320.14  4885.7  315.73  4916.9  316.21
  4928.7  314.33  4931.4  313.83  4934.7  314.33  4938.5  317.35  4966.2  323.01
  5003.4  317.28  5069.7  333.73  5186.5  349.62  5267.7  354.70  5355.3  363.71
  5519.4  369.78  5593.9  372.79  5680.3  373.83  5694.6  375.60  5725.8  375.44
#Mann=6,-1,0
  4109.8    0.05       0  4838.5    0.16       0  4928.7    0.07       0
  4934.7    0.16       0  5519.4     0.1       0  5694.6    0.16       0
Bank Sta=4928.7,4934.7
Exp/Cntr=0.3,0.1

Type RM Length L Ch R = 1,5220,387,387,387
BEGIN DESCRIPTION:
UNT112 IN BECR 6.0
END DESCRIPTION:
XS GIS Cut Line= 3
      3809128.76     10522194.90      3808472.50     10522616.78
      3808175.61     10523569.95
#Sta/Elev= 30
  4287.5  379.35  4393.3  379.47  4580.8  367.99  4674.6  358.56  4829.7  334.42
  4841.0  330.15  4847.0  331.57  4862.2  323.32  4869.0  323.88  4877.4  319.40
  4892.6  319.78  4904.7  314.97  4925.4  312.69  4928.2  312.19  4931.4  312.69
  4950.0  319.42  4964.1  320.11  4986.3  314.15  5296.2  313.98  5469.3  337.25
  5561.6  353.18  5631.9  355.91  5637.1  353.49  5767.2  353.94  5793.9  356.72
  5805.0  354.16  5864.8  362.58  5870.1  360.05  5972.9  363.26  6066.0  373.73
#Mann=4,-1,0
  4287.5    0.05       0  4829.7    0.16       0  4925.4    0.07       0
  4931.4    0.16       0
Bank Sta=4925.4,4931.4
Exp/Cntr=0.3,0.1

Type RM Length L Ch R = 1,4833,648,648,648
BEGIN DESCRIPTION:
UNT112 IN BECR 5.0
END DESCRIPTION:
XS GIS Cut Line= 3
      3808909.97     10522007.42      3807946.46     10522403.24
      3807374.09     10522335.60
#Sta/Elev= 30
  4413.4  371.88  4461.3  368.51  4621.3  351.89  4825.4  322.25  4877.2  317.23
  4889.5  321.06  4900.3  319.59  4912.0  312.88  4930.6  313.80  4943.5  312.23
  4954.3  313.95  4960.0  318.18  4965.4  318.30  4997.6  311.46  5051.6  312.91
  5063.6  311.20  5066.4  310.70  5069.6  311.20  5127.3  317.77  5191.9  321.36
  5267.9  328.87  5397.6  345.54  5405.3  347.90  5461.9  352.76  5502.2  353.74
  5623.1  349.06  5696.3  348.61  5854.7  353.51  5945.0  353.29  6031.4  358.83
#Mann=4,-1,0
  4413.4    0.05       0  4825.4    0.16       0  5063.6    0.07       0
  5069.6    0.16       0
Bank Sta=5063.6,5069.6
Exp/Cntr=0.3,0.1

Type RM Length L Ch R = 1,4185,395,395,395
BEGIN DESCRIPTION:
UNT112 IN BECR 4.0
END DESCRIPTION:
XS GIS Cut Line= 3
      3808826.65     10521746.99      3808519.38     10521726.16
      3807493.97     10521731.36
#Sta/Elev= 30
  4310.7  360.89  4518.2  344.80  4538.3  341.17  4548.3  337.08  4578.4  336.90
  4588.4  338.16  4611.2  336.58  4710.1  329.84  4738.4  328.69  4808.4  322.30
  4818.4  319.64  4828.4  320.23  4848.4  318.49  4908.4  310.12  4938.5  314.42
  4985.5  308.72  4988.2  308.22  4991.5  308.72  5108.5  311.31  5128.5  314.53
  5148.5  325.88  5158.5  329.04  5258.5  339.54  5398.5  346.39  5408.5  348.41
  5418.5  347.55  5478.5  349.59  5508.5  352.59  5538.5  353.02  5644.1  360.54
#Mann=5,-1,0
  4310.7    0.16       0  4611.2    0.05       0  4710.1    0.16       0
  4985.5    0.07       0  4991.5    0.16       0
Bank Sta=4985.5,4991.5
Exp/Cntr=0.3,0.1

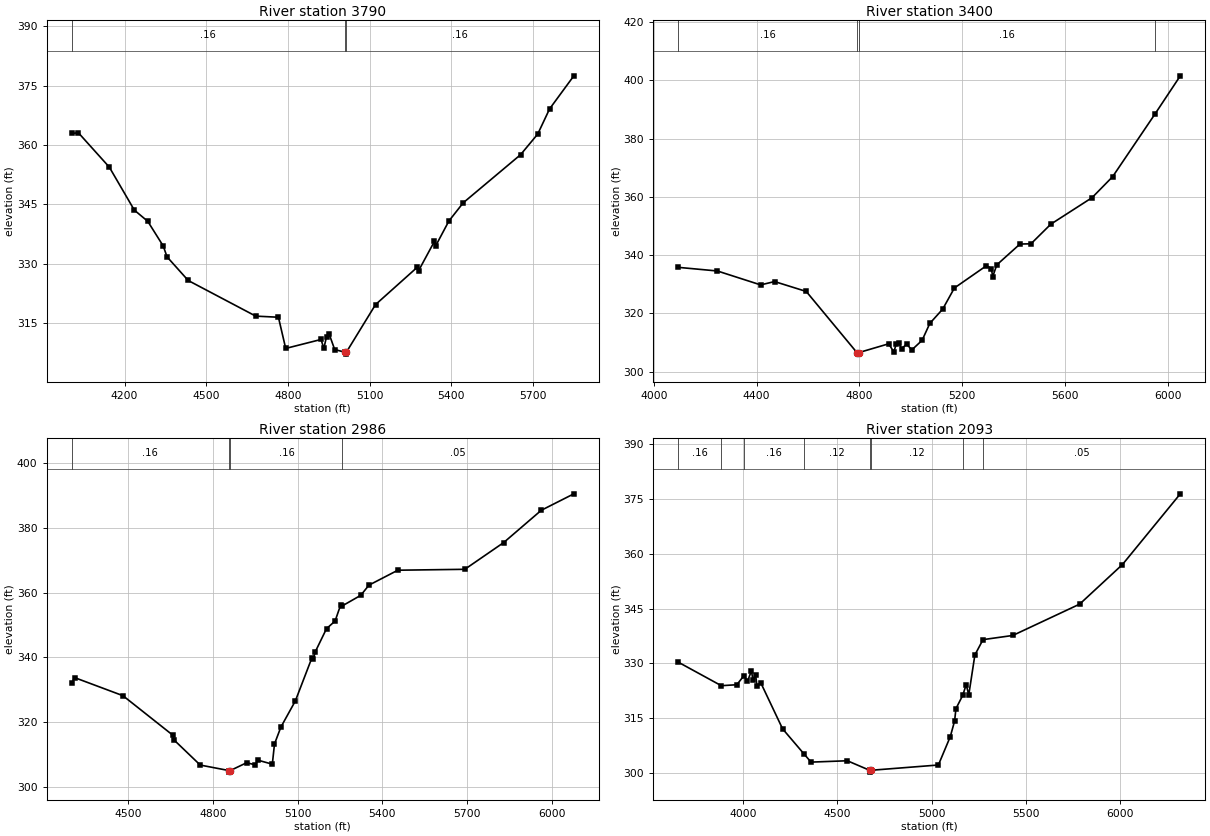
Type RM Length L Ch R = 1,3790,390,390,390
BEGIN DESCRIPTION:
UNT112 IN BECR 3.0
END DESCRIPTION:
XS GIS Cut Line= 4
      3808889.15     10521705.30      3808566.25     10521351.16
      3807847.50     10521361.57      3807233.73     10521564.43
#Sta/Elev= 30
  4006.1  362.90  4030.5  363.06  4144.0  354.38  4235.9  343.51  4285.2  340.68
  4342.0  334.45  4356.2  331.68  4433.9  325.71  4682.0  316.70  4765.3  316.42
  4792.0  308.53  4922.0  310.80  4932.0  308.52  4942.0  311.50  4952.0  312.10
  4972.0  308.25  5009.0  307.59  5011.8  307.09  5015.0  307.59  5122.1  319.62
  5274.9  329.03  5280.2  328.19  5338.4  335.60  5343.6  334.54  5391.5  340.75
  5444.2  345.36  5654.8  357.52  5718.0  362.75  5761.4  369.10  5850.6  377.47
#Mann=3,-1,0
  4006.1    0.16       0  5009.0    0.07       0  5015.0    0.16       0
Bank Sta=5009,5015
Exp/Cntr=0.3,0.1

Type RM Length L Ch R = 1,3400,414,414,414
BEGIN DESCRIPTION:
UNT112 IN BECR 2.0
END DESCRIPTION:
XS GIS Cut Line= 3
      3808894.40     10521080.33      3808415.21     10520965.74
      3806956.86     10521064.70
#Sta/Elev= 30
  4095.1  335.80  4247.6  334.55  4415.9  329.78  4470.2  330.92  4593.4  327.53
  4790.9  306.53  4793.6  306.03  4796.9  306.53  4914.1  309.57  4934.2  306.81
  4944.2  309.58  4954.2  309.75  4964.3  307.91  4984.3  309.44  5004.4  307.48
  5044.4  310.77  5074.5  316.58  5124.6  321.48  5170.1  328.72  5295.0  336.37
  5314.1  335.40  5319.1  332.57  5335.1  336.65  5425.3  343.79  5468.2  343.88
  5545.6  350.62  5706.0  359.71  5786.1  366.91  5950.4  388.33  6049.5  401.50
#Mann=4,-1,0
  4095.1    0.16       0  4790.9    0.07       0  4796.9    0.16       0
  5950.4    0.05       0
Bank Sta=4790.9,4796.9
Exp/Cntr=0.3,0.1

Type RM Length L Ch R = 1,2986,893,893,893
BEGIN DESCRIPTION:
Mapping XS 1c6d38c5
END DESCRIPTION:
XS GIS Cut Line= 3
      3808653.09     10520779.99      3808222.50     10520578.59
      3806932.70     10520772.75
#Sta/Elev= 30
  4299.5  332.08  4309.8  333.75  4480.8  328.18  4656.6  316.06  4663.5  314.38
  4754.9  306.76  4855.7  305.08  4858.4  304.58  4861.7  305.08  4919.4  307.48
  4949.1  306.85  4959.8  308.26  5010.4  307.03  5018.1  313.28  5040.7  318.47
  5092.1  326.57  5151.0  339.93  5156.1  339.40  5162.1  341.63  5202.5  348.87
  5232.9  351.22  5253.1  356.32  5258.8  355.92  5323.9  359.16  5352.9  362.30
  5455.3  366.91  5692.7  367.19  5830.7  375.46  5963.6  385.40  6079.2  390.49
#Mann=4,-1,0
  4299.5    0.16       0  4855.7    0.07       0  4861.7    0.16       0
  5258.8    0.05       0
Bank Sta=4855.7,4861.7
Exp/Cntr=0.3,0.1

Type RM Length L Ch R = 1,2093,0,0,0
BEGIN DESCRIPTION:
UNT112 IN BECR 1.0
END DESCRIPTION:
XS GIS Cut Line= 4
      3808681.30     10520750.89      3807934.35     10519729.51
      3807451.67     10519918.86      3806868.34     10520571.63
#Sta/Elev= 30
  3658.2  330.34  3886.3  323.90  3968.5  324.16  4006.2  326.65  4024.9  325.07
  4045.8  327.94  4054.2  325.46  4067.9  326.86  4075.1  323.87  4096.0  324.62
  4211.0  312.09  4324.1  305.24  4361.6  302.99  4553.9  303.36  4672.1  300.75
  4674.8  300.25  4678.1  300.75  5036.1  302.20  5099.3  309.98  5122.0  314.24
  5129.1  317.62  5164.7  321.22  5183.3  324.15  5197.2  321.43  5229.4  332.31
  5272.5  336.50  5430.1  337.64  5784.3  346.21  6010.9  357.04  6317.5  376.39
#Mann=8,-1,0
  3658.2    0.16       0  3886.3     0.1       0  4006.2    0.16       0
  4324.1    0.12       0  4672.1    0.07       0  4678.1    0.12       0
  5164.7    0.16       0  5272.5    0.05       0
Bank Sta=4672.1,4678.1
Exp/Cntr=0.3,0.1

Chan Stop Cuts=-1