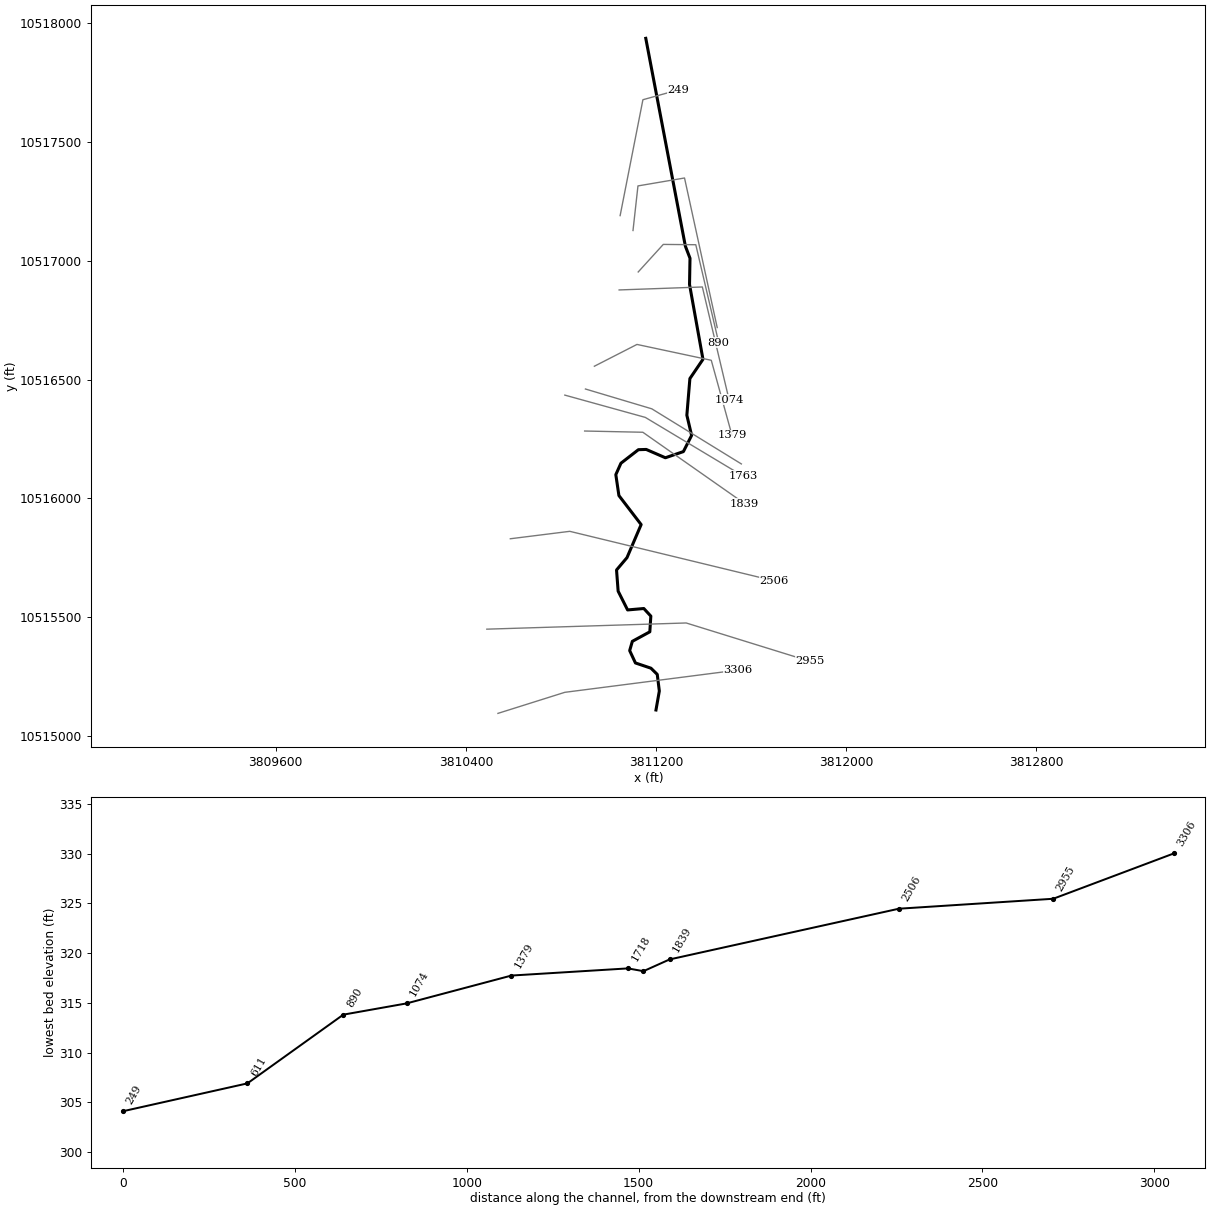
--- UNT119 IN BECR.prj (project) ---

Proj Title=UNT119 IN BECR Base Level Engineering
Current Plan=p01
Default Exp/Contr=0.3,0.1
English Units
Geom File=g01
Flow File=f01
Plan File=p01
Y Axis Title=Elevation
X Axis Title(PF)=Main Channel Distance
X Axis Title(XS)=Station
BEGIN DESCRIPTION:
UNT119 IN BECR
END DESCRIPTION:
DSS Export Rating Curves= 0
DSS Export Rating Curve Sorted= 0
DSS Export Volume Flow Curves= 0
DXF OffsetX= 0
DXF OffsetY= 0
DXF ScaleX= 1
DXF ScaleY= 10

--- UNT119 IN BECR.p01 (plan) ---

Plan Title=Multiple Run
Short Identifier=Multiple
Geom File=g01
Flow File=f01
Subcritical Flow
K Sum by GR= 0
Std Step Tol= 0.01
Critical Tol= 0.01
Num of Std Step Trials= 20
Max Error Tol= 0.3
Flow Tol Ratio= 0.001
Split Flow NTrial= 30
Split Flow Tol= 0.02
Split Flow Ratio= 0.02
Log Output Level= 0
Friction Slope Method= 1
Unsteady Friction Slope Method= 2
Unsteady Bridges Friction Slope Method= 1
Parabolic Critical Depth
Global Vel Dist=  1 , 1 , 1
Global Log Level= 0
CheckData=True
Encroach Param= -1, 0, 0, 0
BEGIN DESCRIPTION:
Multiple Run
END DESCRIPTION:

--- UNT119 IN BECR.f01 (steady flow) ---

Flow Title=Multiple
Program Version=4.10
Number of Profiles= 7
Profile Names=10-year,25-year,50-year,1pct_min,100-year,1pct_plu,500-year
River Rch & RM=UNT119 IN BECR,Reach-1         ,3306
     318     414     492     431     582     788     818
Boundary for River Rch & Prof#=UNT119 IN BECR,Reach-1         , 1
Up Type= 0
Dn Type= 3
Dn Slope=0.0124
Boundary for River Rch & Prof#=UNT119 IN BECR,Reach-1         , 2
Up Type= 0
Dn Type= 3
Dn Slope=0.0124
Boundary for River Rch & Prof#=UNT119 IN BECR,Reach-1         , 3
Up Type= 0
Dn Type= 3
Dn Slope=0.0124
Boundary for River Rch & Prof#=UNT119 IN BECR,Reach-1         , 4
Up Type= 0
Dn Type= 3
Dn Slope=0.0124
Boundary for River Rch & Prof#=UNT119 IN BECR,Reach-1         , 5
Up Type= 0
Dn Type= 3
Dn Slope=0.0124
Boundary for River Rch & Prof#=UNT119 IN BECR,Reach-1         , 6
Up Type= 0
Dn Type= 3
Dn Slope=0.0124
Boundary for River Rch & Prof#=UNT119 IN BECR,Reach-1         , 7
Up Type= 0
Dn Type= 3
Dn Slope=0.0124
DSS Import GetInterval= 0
DSS Import GetPeak= 0
DSS Import FillOption= 0

--- UNT119 IN BECR.g01 (geometry) ---

Geom Title=Existing Conditions
Program Version=4.10

River Reach=UNT119 IN BECR  ,Reach-1
Reach XY= 30
      3811199.61     10515110.19      3811213.75       10515190.
        3811205.       10515260.       3811178.5       10515286.
      3811113.25       10515308.        3811089.       10515360.
      3811100.25       10515399.      3811173.75       10515439.
        3811178.       10515505.       3811148.5       10515537.
      3811080.25       10515531.       3811040.5       10515610.
      3811033.75       10515699.      3811077.75       10515751.
      3811137.25       10515890.      3811043.75       10516012.
      3811030.75       10516100.      3811052.25       10516148.
      3811125.75       10516205.       3811158.5       10516206.
      3811239.25       10516171.        3811315.       10516197.
       3811349.5       10516265.       3811329.5       10516350.
      3811342.25       10516504.      3811397.25       10516585.
      3811340.75       10516900.      3811342.75       10517010.
      3811323.25       10517061.      3811156.75       10517935.

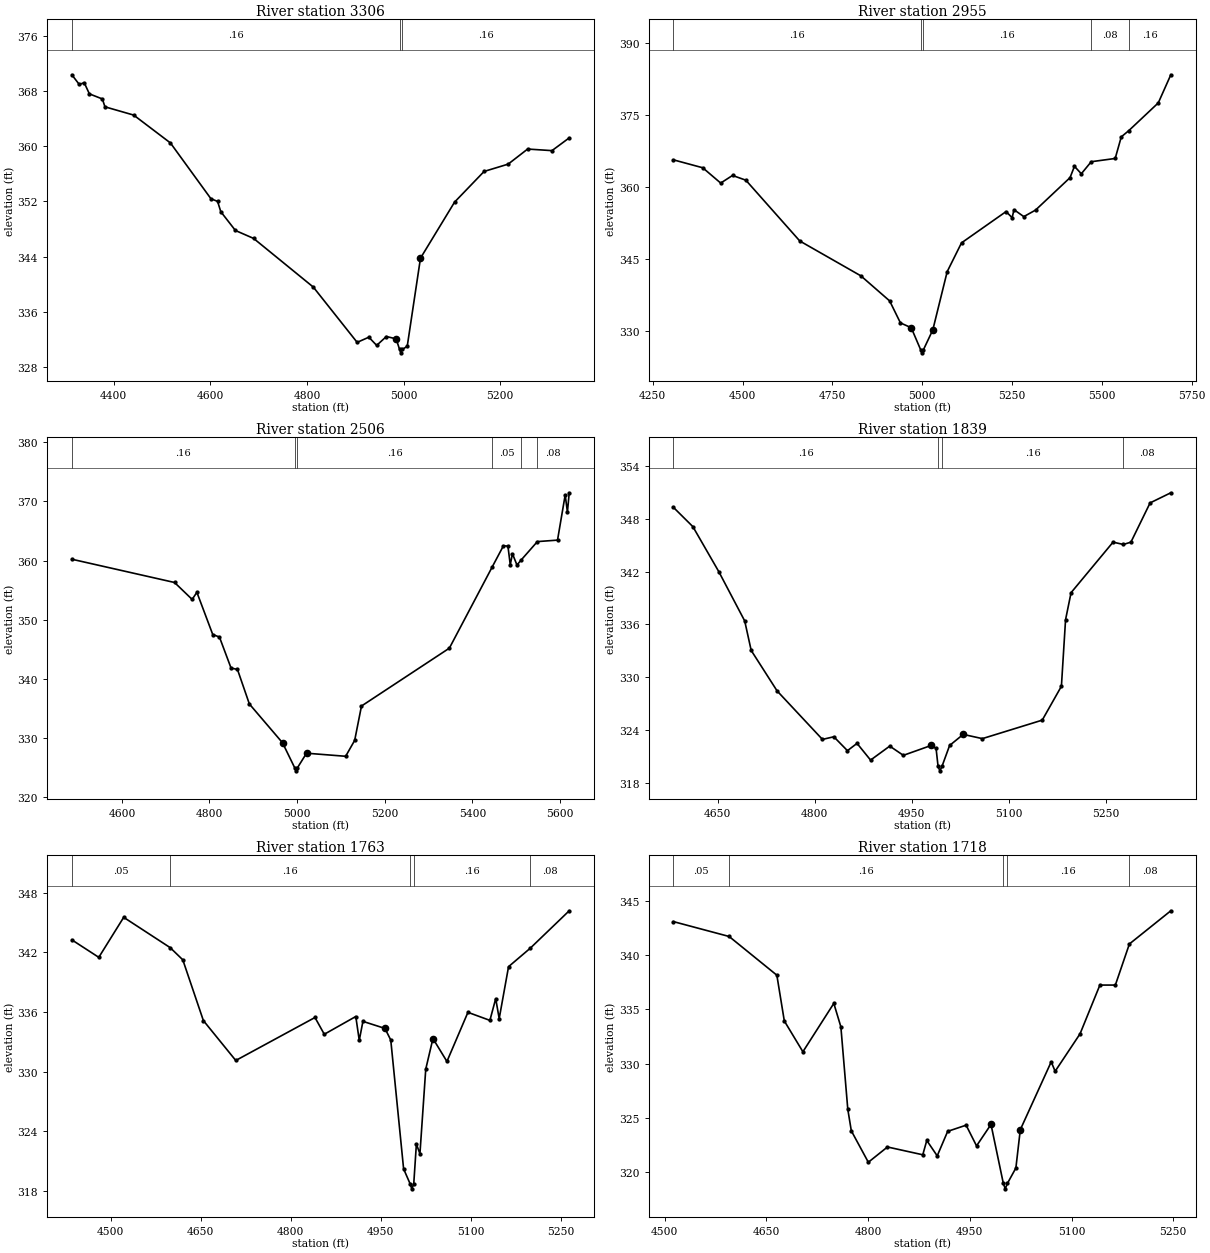
Type RM Length L Ch R = 1 ,3306    ,351,351,351
BEGIN DESCRIPTION:
UNT119 IN BECR 5.0
END DESCRIPTION:
XS GIS Cut Line= 3
      3810534.99     10515095.98      3810816.25     10515184.53
      3811544.98     10515278.22
#Sta/Elev= 30
  4313.4  370.38  4328.7  368.98    4339  369.23  4349.7  367.61  4376.6  366.87
  4381.9  365.73  4441.4  364.53  4517.4  360.49  4601.3  352.39  4615.1     352
  4621.7  350.51    4652  347.78  4689.6  346.63  4813.3  339.56    4904  331.54
  4928.2  332.29  4944.4   331.1  4964.5  332.39  4984.7  332.05  4991.8  330.52
  4994.5  330.02  4997.8  330.52  5007.7  330.98  5035.1  343.76  5105.7   351.9
  5166.8  356.35  5216.6  357.41  5256.9   359.6  5307.3  359.37    5343  361.22
#Mann= 3 ,-1 , 0
  4313.4     .16       0  4991.8     .07       0  4997.8     .16       0
Bank Sta=4984.7,5035.1
XS Rating Curve= 0 ,0
Exp/Cntr=0.3,0.1

Type RM Length L Ch R = 1 ,2955    ,449,449,449
BEGIN DESCRIPTION:
UNT119 IN BECR 4.0
END DESCRIPTION:
XS GIS Cut Line= 3
      3810488.17     10515450.15      3811326.67     10515476.19
      3811847.51     10515314.73
#Sta/Elev= 30
  4307.8  365.68  4389.3  364.03  4439.3  360.84  4472.2  362.43  4509.3  361.44
  4659.4  348.77  4829.5   341.5  4909.5  336.28  4939.5   331.7  4969.6  330.69
  4996.6  325.96  4999.3  325.46  5002.6  325.96  5029.6  330.24  5069.6  342.38
  5109.5  348.38  5233.5   354.9  5250.3  353.63  5255.6  355.29  5282.9  353.85
  5315.5  355.21  5411.5  361.97  5423.8  364.33  5442.9  362.78  5470.5  365.29
  5537.2  365.97  5554.1  370.47  5575.2  371.78  5657.1  377.55    5692  383.41
#Mann= 5 ,-1 , 0
  4307.8     .16       0  4996.6     .07       0  5002.6     .16       0
  5470.5     .08       0  5575.2     .16       0
Bank Sta=4969.6,5029.6
XS Rating Curve= 0 ,0
Exp/Cntr=0.3,0.1

Type RM Length L Ch R = 1 ,2506    ,667,667,667
BEGIN DESCRIPTION:
UNT119 IN BECR 3.0
END DESCRIPTION:
XS GIS Cut Line= 3
      3810587.07     10515830.36      3810837.09     10515861.61
      3811695.56      10515653.5
#Sta/Elev= 30
  4485.8  360.22  4720.2  356.29  4760.4  353.43  4771.2  354.63  4807.4   347.5
  4822.7  347.07  4849.2  341.83  4863.8   341.6    4891  335.76  4966.7   329.2
  4994.6  324.96  4997.4  324.46  5000.6  324.96  5021.5  327.44  5110.8  326.92
  5131.4  329.61  5146.9  335.41  5347.5  345.19  5445.7  358.97  5470.9  362.49
  5481.2  362.44  5486.5   359.3  5491.6  361.14  5501.8  359.24  5511.4  360.09
  5548.4   363.2  5594.4  363.45  5611.9  371.08    5617  368.19  5621.1  371.45
#Mann= 6 ,-1 , 0
  4485.8     .16       0  4994.6     .07       0  5000.6     .16       0
  5445.7     .05       0  5511.4     .16       0  5548.4     .08       0
Bank Sta=4966.7,5021.5
XS Rating Curve= 0 ,0
Exp/Cntr=0.3,0.1

Type RM Length L Ch R = 1 ,1839    ,76,76,76
BEGIN DESCRIPTION:
UNT119 IN BECR 2.0
END DESCRIPTION:
XS GIS Cut Line= 3
      3810899.63     10516283.48      3811144.38     10516278.28
      3811572.66     10515978.11
#Sta/Elev= 30
    4582  349.29    4612   347.1    4652  341.99    4692  336.39    4702  333.04
    4742  328.44    4812  322.93  4829.6  323.23  4850.6  321.65  4865.4  322.48
  4886.3  320.58  4915.9  322.17  4936.9  321.12  4979.7  322.24  4987.4  321.92
  4990.5  319.86  4993.3  319.36  4996.5  319.86  5008.3  322.24  5029.3   323.5
  5058.9  323.02  5151.3  325.12  5180.9  328.97  5187.3  336.53  5195.8   339.6
  5260.6  345.34  5276.6  345.08  5288.2  345.34  5317.8   349.8  5349.8  350.95
#Mann= 4 ,-1 , 0
    4582     .16       0  4990.5     .07       0  4996.5     .16       0
  5276.6     .08       0
Bank Sta=4979.7,5029.3
XS Rating Curve= 0 ,0
Exp/Cntr=0.3,0.1

Type RM Length L Ch R = 1 ,1763    ,45,45,45
BEGIN DESCRIPTION:
Mapping XS 8187c910
END DESCRIPTION:
XS GIS Cut Line= 3
       3810816.3     10516434.51      3811154.79     10516340.78
      3811564.39     10516095.02
#Sta/Elev= 30
  4435.4  343.26  4480.3   341.5  4521.8  345.53  4599.2  342.48  4620.3  341.25
  4654.6  335.13  4708.6  331.11  4840.6  335.44  4856.1  333.75  4908.6  335.54
  4914.4  333.14  4920.5  335.05  4957.2  334.34  4966.9  333.17  4988.3  320.19
  4999.2  318.68  5001.9  318.18  5005.2  318.68  5009.6  322.69  5015.5  321.71
  5025.2  330.24  5037.2  333.32  5060.5  331.01  5095.5  335.96  5132.1  335.15
  5141.8  337.34  5147.6  335.33  5163.2  340.56  5199.2  342.41  5264.3  346.19
#Mann= 5 ,-1 , 0
  4435.4     .05       0  4599.2     .16       0  4999.2     .07       0
  5005.2     .16       0  5199.2     .08       0
Bank Sta=4957.2,5037.2
XS Rating Curve= 0 ,0
Exp/Cntr=0.3,0.1

Type RM Length L Ch R = 1 ,1718    ,339,339,339
BEGIN DESCRIPTION:
Mapping XS 684f7616
END DESCRIPTION:
XS GIS Cut Line= 3
      3810902.99     10516460.16       3811182.2     10516376.81
      3811558.69     10516145.04
#Sta/Elev= 30
  4512.9   343.1    4595  341.73  4665.4  338.16  4676.4  333.94  4703.8   331.1
  4749.4  335.56  4759.8   333.4    4770   325.8  4775.2  323.81  4800.3  320.91
  4828.5  322.32  4880.6   321.6  4886.5  322.92  4901.9   321.5  4917.3  323.76
  4944.5  324.33  4959.9  322.42  4981.2   324.4  4999.4  318.96  5002.2  318.46
  5005.4  318.96  5017.9  320.38  5024.4  323.91    5070  330.17  5075.8   329.3
  5112.5  332.75  5141.8  337.25  5164.6  337.25  5185.3  341.04  5246.4   344.1
#Mann= 5 ,-1 , 0
  4512.9     .05       0    4595     .16       0  4999.4     .07       0
  5005.4     .16       0  5185.3     .08       0
Bank Sta=4981.2,5024.4
XS Rating Curve= 0 ,0
Exp/Cntr=0.3,0.1

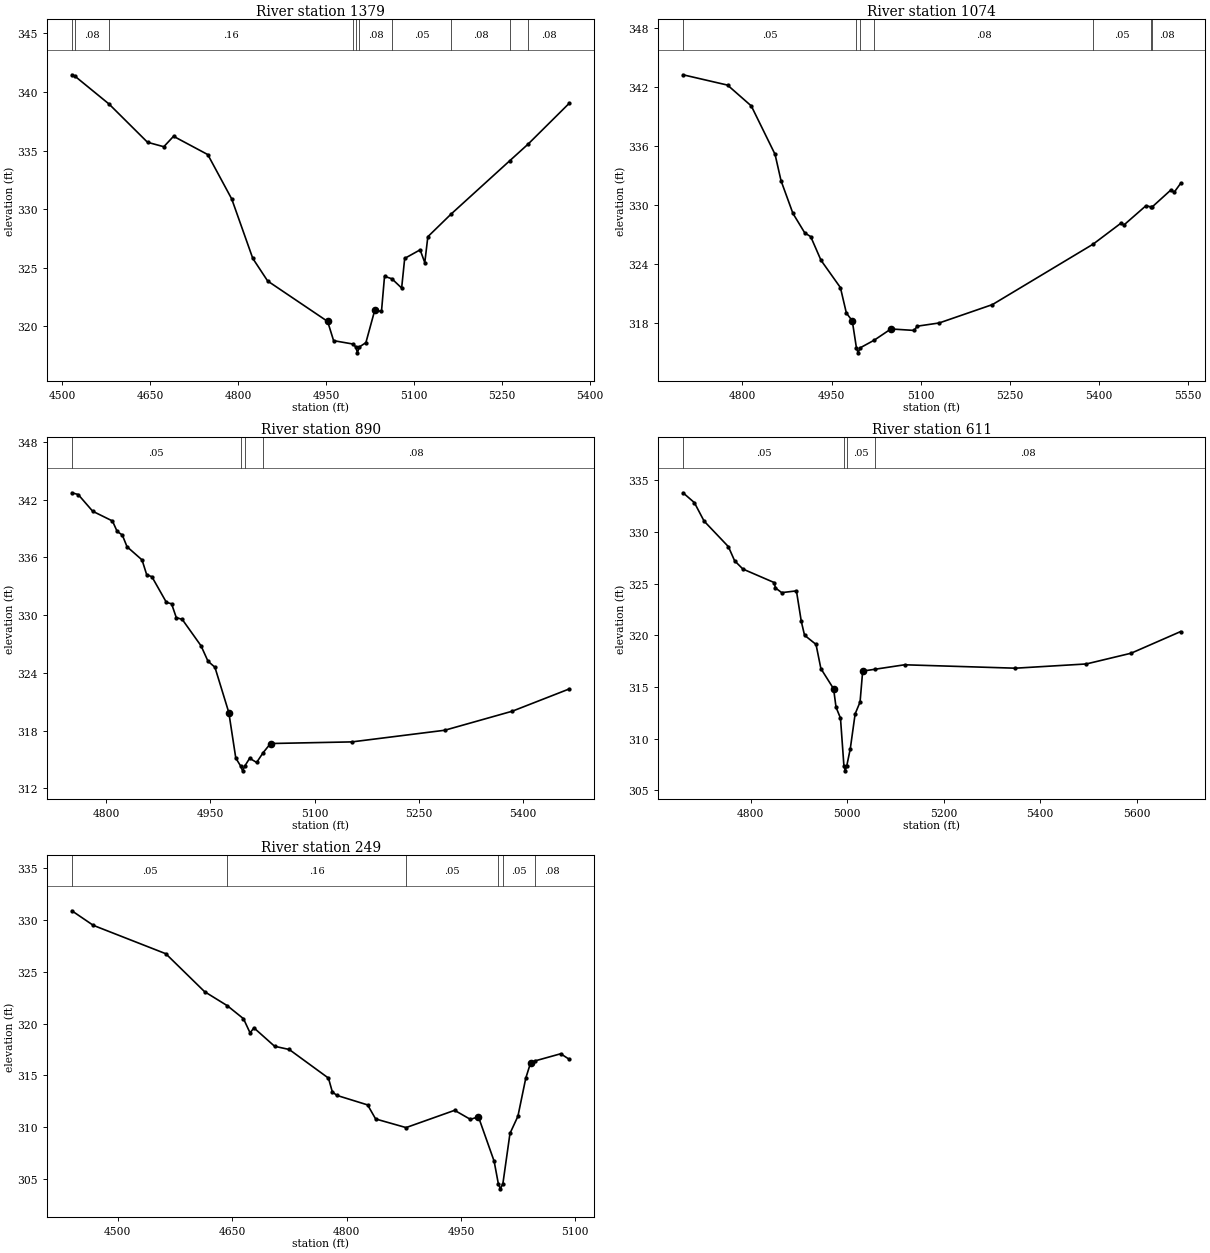
Type RM Length L Ch R = 1 ,1379    ,305,305,305
BEGIN DESCRIPTION:
Mapping XS 9872ea10
END DESCRIPTION:
XS GIS Cut Line= 4
      3810940.52     10516555.97       3811119.7     10516647.64
       3811432.2     10516580.98      3811519.58     10516264.73
#Sta/Elev= 30
    4516  341.47    4521  341.36  4579.3  338.98  4645.1  335.71  4672.9  335.33
  4689.5  336.22  4747.9  334.66  4788.8  330.87  4824.7   325.8  4850.1  323.87
  4952.4  320.42  4962.6  318.78  4995.8  318.49  5000.5  318.24  5003.2  317.74
  5006.5  318.24  5017.7  318.61  5032.9  321.39  5044.3  321.27  5049.5  324.27
  5062.1  324.06  5078.7  323.27  5083.9   325.8  5110.2  326.53  5118.2  325.44
  5123.4  327.65  5162.8  329.57  5263.5  334.15  5294.2  335.54  5364.9  339.05
#Mann= 10 ,-1 , 0
    4516     .05       0    4521     .08       0  4579.3     .16       0
  4995.8     .08       0  5000.5     .07       0  5006.5     .08       0
  5062.1     .05       0  5162.8     .08       0  5263.5     .16       0
  5294.2     .08       0
Bank Sta=4952.4,5032.9
XS Rating Curve= 0 ,0
Exp/Cntr=0.3,0.1

Type RM Length L Ch R = 1 ,1074    ,184,184,184
BEGIN DESCRIPTION:
Mapping XS 8b80e5fc
END DESCRIPTION:
XS GIS Cut Line= 3
      3811044.66     10516876.81       3811394.7     10516889.31
      3811507.11      10516414.7
#Sta/Elev= 30
  4699.9  343.23  4774.9  342.18  4814.9  340.06  4854.9  335.14    4865  332.45
    4885  329.13    4905  327.14    4915  326.76  4932.3  324.36    4965  321.58
    4975     319    4985  318.19    4992  315.44  4994.8  314.94    4998  315.44
    5022  316.23  5050.1  317.37  5089.2  317.22  5094.3  317.65  5131.4  317.98
  5221.1  319.85  5390.7     326  5437.5  328.13  5442.6  327.95  5479.7  329.91
  5488.9  329.77  5490.6  329.81    5522  331.53  5527.1  331.27  5537.9  332.17
#Mann= 7 ,-1 , 0
  4699.9     .05       0    4992     .03       0    4998     .05       0
    5022     .08       0  5390.7     .05       0  5488.9     .16       0
  5490.6     .08       0
Bank Sta=4985,5050.1
XS Rating Curve= 0 ,0
Exp/Cntr=0.3,0.1

Type RM Length L Ch R = 1 ,890     ,279,279,279
BEGIN DESCRIPTION:
Mapping XS 98772fba
END DESCRIPTION:
XS GIS Cut Line= 4
      3811124.91     10516952.42      3811230.37     10517068.29
      3811367.09     10517066.99      3811463.44     10516655.52
#Sta/Elev= 30
  4750.6  342.72  4759.7  342.54  4780.6   340.8    4809  339.79  4815.8   338.7
  4823.2  338.33    4830  337.11  4851.6  335.74  4858.3   334.2  4865.8  333.99
  4886.7  331.32  4894.1  331.18  4900.9  329.74  4909.4  329.56  4936.5  326.81
  4946.5  325.21  4956.5  324.58  4976.5  319.87  4986.5  315.14  4993.5  314.31
  4996.3  313.81  4999.5  314.31  5006.5  315.12  5016.5  314.68    5026  315.71
  5036.5  316.65  5153.7  316.82  5287.2  318.03  5384.4  320.01  5466.6  322.33
#Mann= 4 ,-1 , 0
  4750.6     .05       0  4993.5     .03       0  4999.5     .05       0
    5026     .08       0
Bank Sta=4976.5,5036.5
XS Rating Curve= 0 ,0
Exp/Cntr=0.3,0.1

Type RM Length L Ch R = 1 ,611     ,362,362,362
BEGIN DESCRIPTION:
Mapping XS cd9ebb77
END DESCRIPTION:
XS GIS Cut Line= 4
      3811103.03     10517126.79      3811123.87     10517314.31
       3811319.7     10517347.64      3811457.19     10516718.52
#Sta/Elev= 30
  4659.7   333.8  4683.2  332.85  4703.4  331.06  4753.7  328.59  4766.7  327.22
  4783.9  326.42  4848.4  325.12  4851.4  324.59  4864.3  324.14  4894.8  324.31
  4904.9  321.35  4911.6  320.02  4935.4  319.13  4945.5  316.79  4971.8  314.84
  4976.9  313.05  4986.1     312  4993.2   307.4    4996   306.9  4999.2   307.4
  5006.4  309.03  5016.5  312.41  5026.7  313.56  5032.1  316.55  5057.9  316.73
    5119  317.16  5348.7  316.83  5495.7  317.24  5588.6  318.28    5691  320.37
#Mann= 4 ,-1 , 0
  4659.7     .05       0  4993.2     .04       0  4999.2     .05       0
  5057.9     .08       0
Bank Sta=4971.8,5032.1
XS Rating Curve= 0 ,0
Exp/Cntr=0.3,0.1

Type RM Length L Ch R = 1 ,249     ,0,0,0
BEGIN DESCRIPTION:
UNT119 IN BECR 1.0
END DESCRIPTION:
XS GIS Cut Line= 3
      3811048.87     10517189.31       3811144.7     10517676.81
      3811294.69     10517718.47
#Sta/Elev= 30
  4439.7  330.84  4467.8  329.44  4562.9  326.71  4613.8  323.06  4643.6  321.71
  4664.8  320.46  4673.4   319.1  4678.5  319.58  4705.6  317.81  4724.8   317.5
  4776.2  314.75  4781.3  313.43  4787.1  313.09  4827.6  312.17  4838.1  310.82
    4878  309.99  4941.7  311.65  4962.4  310.78  4972.9  311.03  4993.5  306.76
    4999   304.6  5001.7   304.1    5005   304.6  5014.3  309.43  5024.7  311.08
    5035  314.74  5041.4  316.24  5046.5  316.39  5080.8  317.09  5092.2  316.55
#Mann= 6 ,-1 , 0
  4439.7     .05       0  4643.6     .16       0    4878     .05       0
    4999     .03       0    5005     .05       0  5046.5     .08       0
Bank Sta=4972.9,5041.4
XS Rating Curve= 0 ,0
Exp/Cntr=0.3,0.1

Chan Stop Cuts=-1
Use User Specified Reach Order=0
Composite Channel Slope=5