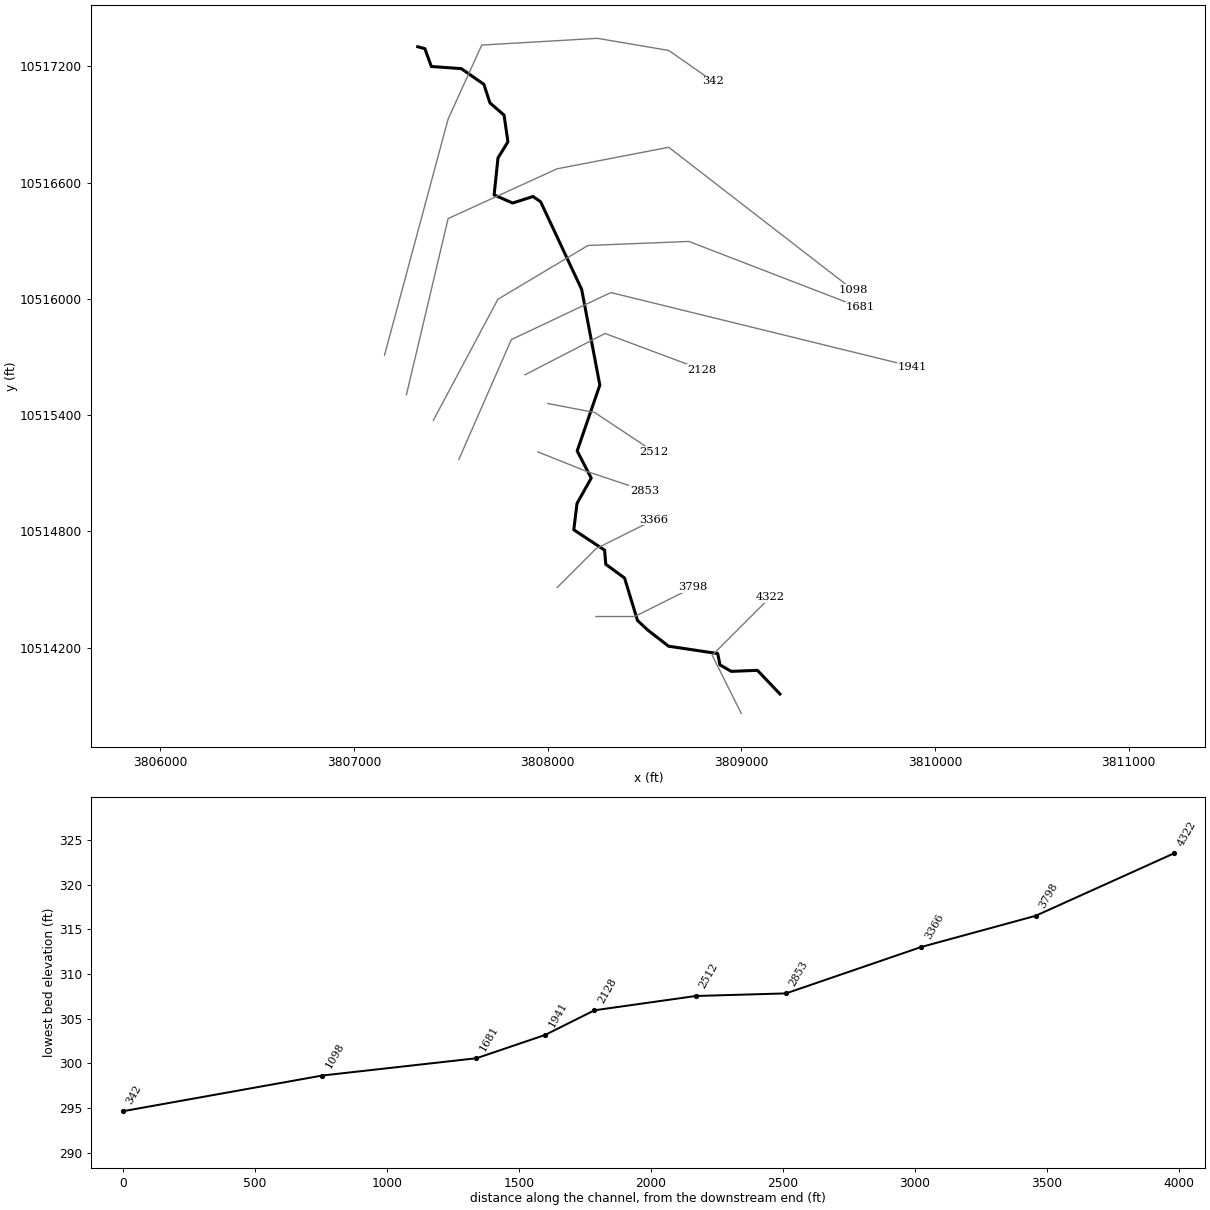
--- UNT120 IN BECR.prj (project) ---

Proj Title=UNT120 IN BECR Base Level Engineering
Current Plan=p01
Default Exp/Contr=0.3,0.1
English Units
Geom File=g01
Flow File=f01
Plan File=p01
Y Axis Title=Elevation
X Axis Title(PF)=Main Channel Distance
X Axis Title(XS)=Station
BEGIN DESCRIPTION:
UNT120 IN BECR
END DESCRIPTION:
DSS Export Rating Curves= 0
DSS Export Rating Curve Sorted= 0
DSS Export Volume Flow Curves= 0
DXF OffsetX= 0
DXF OffsetY= 0
DXF ScaleX= 1
DXF ScaleY= 10

--- UNT120 IN BECR.p01 (plan) ---

Plan Title=Multiple Run
Short Identifier=Multiple
Geom File=g01
Flow File=f01
Subcritical Flow
K Sum by GR= 0
Std Step Tol= 0.01
Critical Tol= 0.01
Num of Std Step Trials= 20
Max Error Tol= 0.3
Flow Tol Ratio= 0.001
Split Flow NTrial= 30
Split Flow Tol= 0.02
Split Flow Ratio= 0.02
Log Output Level= 0
Friction Slope Method= 1
Unsteady Friction Slope Method= 2
Unsteady Bridges Friction Slope Method= 1
Parabolic Critical Depth
Global Vel Dist=  1 , 1 , 1
Global Log Level= 0
CheckData=True
Encroach Param= -1, 0, 0, 0
BEGIN DESCRIPTION:
Multiple Run
END DESCRIPTION:

--- UNT120 IN BECR.f01 (steady flow) ---

Flow Title=Multiple
Number of Profiles=7
Profile Names=10-year,25-year,50-year,1pct_min,100-year,1pct_plu,500-year
River Rch & RM= UNT120 IN BECR,Reach-1,4322
     569     770     937     839    1135    1535    1670
Boundary for River Rch & Prof#=UNT120 IN BECR,Reach-1,1
Up Type=0
Dn Type=3
Dn Slope=0.005
Boundary for River Rch & Prof#=UNT120 IN BECR,Reach-1,2
Up Type=0
Dn Type=3
Dn Slope=0.005
Boundary for River Rch & Prof#=UNT120 IN BECR,Reach-1,3
Up Type=0
Dn Type=3
Dn Slope=0.005
Boundary for River Rch & Prof#=UNT120 IN BECR,Reach-1,4
Up Type=0
Dn Type=3
Dn Slope=0.005
Boundary for River Rch & Prof#=UNT120 IN BECR,Reach-1,5
Up Type=0
Dn Type=3
Dn Slope=0.005
Boundary for River Rch & Prof#=UNT120 IN BECR,Reach-1,6
Up Type=0
Dn Type=3
Dn Slope=0.005
Boundary for River Rch & Prof#=UNT120 IN BECR,Reach-1,7
Up Type=0
Dn Type=3
Dn Slope=0.005

--- UNT120 IN BECR.g01 (geometry) ---

Geom Title=Existing Conditions
Program Version=4.10

River Reach=UNT120 IN BECR  ,Reach-1
Reach XY= 30
      3809199.61     10513960.19      3809083.05     10514082.34
      3808947.78     10514077.05      3808889.66     10514110.87
      3808878.04     10514168.99      3808624.41     10514207.04
      3808516.61     10514290.52      3808463.78     10514340.19
      3808397.25       10514559.      3808300.25       10514630.
        3808294.       10514703.        3808135.       10514808.
      3808151.75       10514944.        3808225.       10515075.
       3808152.5       10515215.       3808269.5       10515555.
      3808175.75       10516049.      3807963.93     10516501.46
      3807924.52     10516528.71      3807819.25       10516495.
      3807723.75       10516537.      3807743.75       10516728.
        3807795.       10516811.        3807775.       10516949.
      3807702.25       10517012.      3807670.75       10517108.
      3807554.25       10517189.       3807399.5       10517200.
      3807366.25       10517292.       3807329.5       10517302.

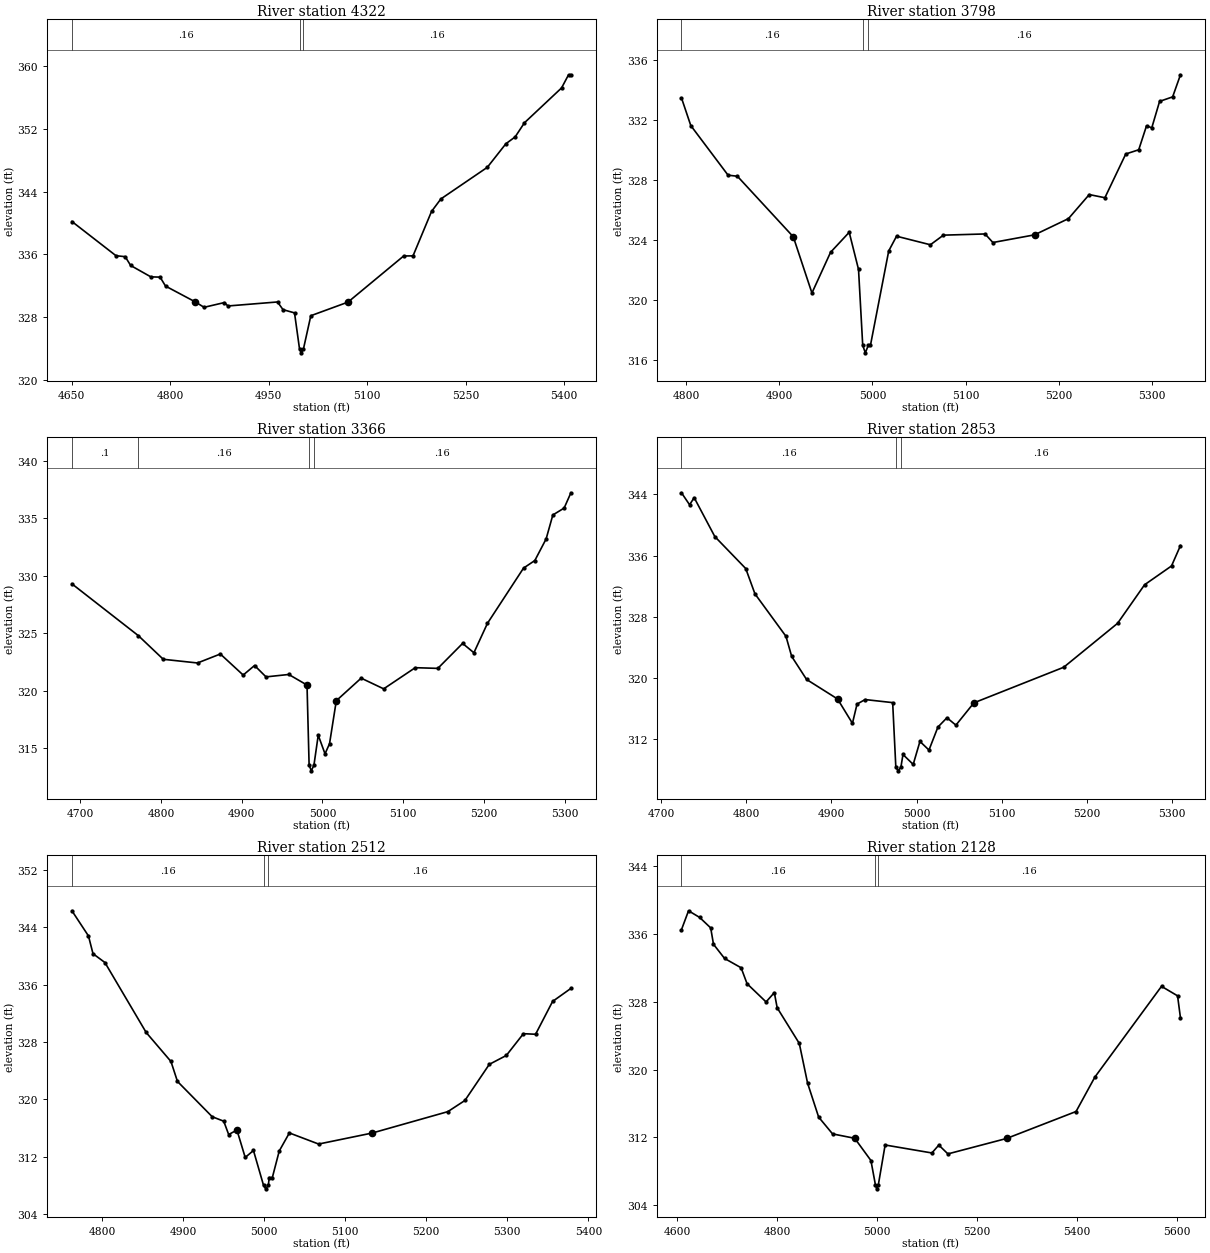
Type RM Length L Ch R = 1 ,4322    ,524,524,524
BEGIN DESCRIPTION:
UNT120 IN BECR 7.0
END DESCRIPTION:
XS GIS Cut Line= 3
      3808999.61     10513860.19      3808849.61     10514160.19
      3809149.63     10514460.21
#Sta/Elev= 30
  4650.6  340.19  4717.7  335.84  4731.7  335.72    4740   334.6  4770.8  333.15
  4784.8  333.12  4793.1  331.98  4837.9  329.99  4851.8  329.28  4882.6  329.88
  4888.2  329.45  4963.6  329.96    4972  328.98  4989.5  328.57  4997.1  323.99
  4999.9  323.49  5003.1  323.99  5014.3  328.21  5070.9  329.94  5155.7  335.81
  5169.9  335.82  5198.1  341.47  5212.3  343.06    5283  347.08  5311.3  350.08
  5325.4  350.95  5339.6  352.75  5396.1  357.18  5406.7  358.85  5410.3  358.85
#Mann= 3 ,-1 , 0
  4650.6     .16       0  4997.1     .07       0  5003.1     .16       0
Bank Sta=4837.9,5070.9
XS Rating Curve= 0 ,0
Exp/Cntr=0.3,0.1

Type RM Length L Ch R = 1 ,3798    ,432,432,432
BEGIN DESCRIPTION:
UNT120 IN BECR 6.0
END DESCRIPTION:
XS GIS Cut Line= 3
      3808249.57     10514360.19      3808449.61     10514360.19
      3808749.65     10514510.21
#Sta/Elev= 30
  4795.1  333.46  4805.1  331.62  4845.1  328.32  4855.1  328.25  4915.1  324.22
  4935.1  320.48  4955.1  323.19  4975.1  324.52  4985.1  322.05  4989.6     317
  4992.4   316.5  4995.6     317  4997.9     317  5017.5  323.28  5025.9  324.26
  5062.2  323.69  5076.2  324.33  5120.9  324.41  5129.3  323.84    5174  324.35
  5210.4  325.43  5232.7  327.03  5249.5  326.82  5271.9  329.73  5285.8  330.01
  5294.2  331.61  5299.8  331.47  5308.2  333.23  5322.2  333.53  5330.6     335
#Mann= 3 ,-1 , 0
  4795.1     .16       0  4989.6     .07       0  4995.6     .16       0
Bank Sta=4915.1,5174
XS Rating Curve= 0 ,0
Exp/Cntr=0.3,0.1

Type RM Length L Ch R = 1 ,3366    ,513,513,513
BEGIN DESCRIPTION:
UNT120 IN BECR 5.0
END DESCRIPTION:
XS GIS Cut Line= 3
      3808049.58     10514510.16      3808249.61     10514710.19
      3808549.61     10514860.19
#Sta/Elev= 30
  4689.6  329.28    4772  324.77  4802.8  322.72  4845.2   322.4  4873.5  323.18
  4901.8  321.35  4915.9  322.18  4930.1  321.19  4958.3   321.4  4980.9  320.48
  4983.5  313.52  4986.2  313.02  4989.5  313.52  4994.8  316.12  5003.2   314.5
  5008.8  315.38  5017.2  319.12    5048  321.08  5075.9  320.15    5115  321.99
    5143  321.93  5173.7   324.1  5187.7  323.29  5204.5  325.85  5249.2  330.65
  5263.2  331.31  5277.2  333.19  5285.5  335.27  5299.5  335.87  5307.9   337.2
#Mann= 4 ,-1 , 0
  4689.6      .1       0    4772     .16       0  4983.5     .07       0
  4989.5     .16       0
Bank Sta=4980.9,5017.2
XS Rating Curve= 0 ,0
Exp/Cntr=0.3,0.1

Type RM Length L Ch R = 1 ,2853    ,341,341,341
BEGIN DESCRIPTION:
UNT120 IN BECR 4.0
END DESCRIPTION:
XS GIS Cut Line= 3
      3807949.57     10515210.21      3808199.61     10515110.19
      3808499.58      10515010.2
#Sta/Elev= 30
  4724.1  344.22  4733.6  342.65    4739  343.58  4763.2  338.49  4799.5   334.3
  4810.3  330.99  4846.7  325.43  4853.4   322.8  4870.9  319.78  4907.2  317.23
  4924.7  314.04  4930.1  316.56  4939.6  317.15  4971.9  316.75  4975.6  308.32
  4978.3  307.82  4981.6  308.32    4984  309.96    4996  308.66  5003.9  311.67
  5014.5  310.54    5025  313.55  5035.6  314.77  5046.1   313.8  5067.2  316.72
  5172.6  321.38  5235.8  327.13  5267.5  332.18  5299.1  334.64  5309.6  337.31
#Mann= 3 ,-1 , 0
  4724.1     .16       0  4975.6     .07       0  4981.6     .16       0
Bank Sta=4907.2,5067.2
XS Rating Curve= 0 ,0
Exp/Cntr=0.3,0.1

Type RM Length L Ch R = 1 ,2512    ,384,384,384
BEGIN DESCRIPTION:
UNT120 IN BECR 3.0
END DESCRIPTION:
XS GIS Cut Line= 3
      3807999.62     10515460.19      3808242.52     10515413.72
      3808549.59      10515210.2
#Sta/Elev= 30
  4762.8  346.33  4783.2  342.82  4788.8  340.34  4803.5  339.11  4854.4  329.35
    4885   325.3    4893  322.52  4935.9  317.59  4950.1  316.97  4956.2  315.11
  4966.4  315.73  4976.6  311.91  4986.8  312.88  4999.2  308.03  5001.9  307.53
  5005.2  308.03  5006.2  309.11  5010.1  309.11  5018.6  312.81  5031.1  315.33
  5067.2  313.78  5133.4  315.32  5226.6   318.3  5247.7  319.86  5277.8   324.9
  5298.8  326.14  5319.9  329.18  5334.9   329.1  5355.9  333.68  5378.5   335.5
#Mann= 3 ,-1 , 0
  4762.8     .16       0  4999.2     .07       0  5005.2     .16       0
Bank Sta=4966.4,5133.4
XS Rating Curve= 0 ,0
Exp/Cntr=0.3,0.1

Type RM Length L Ch R = 1 ,2128    ,187,187,187
BEGIN DESCRIPTION:
UNT120 IN BECR 2.0
END DESCRIPTION:
XS GIS Cut Line= 3
      3807883.17     10515608.18      3808296.34     10515821.71
      3808795.06     10515635.33
#Sta/Elev= 30
  4609.1  336.49  4623.2  338.72  4645.3  337.94  4667.5   336.7  4673.1  334.77
  4695.2   333.1  4728.3     332  4740.2  330.12  4778.2  327.97  4794.7  329.07
  4800.4  327.28  4844.6  323.08  4861.2  318.39  4883.3  314.39  4911.1  312.41
  4955.4  311.89  4987.8  309.27  4996.7  306.43  4999.4  305.93  5002.7  306.43
  5016.2   311.1  5109.7  310.16  5123.5  311.09  5141.7  310.05    5259  311.87
  5397.9  315.05  5435.5  319.11  5568.7  329.81  5600.8  328.69  5606.6  326.09
#Mann= 3 ,-1 , 0
  4609.1     .16       0  4996.7     .07       0  5002.7     .16       0
Bank Sta=4955.4,5259
XS Rating Curve= 0 ,0
Exp/Cntr=0.3,0.1

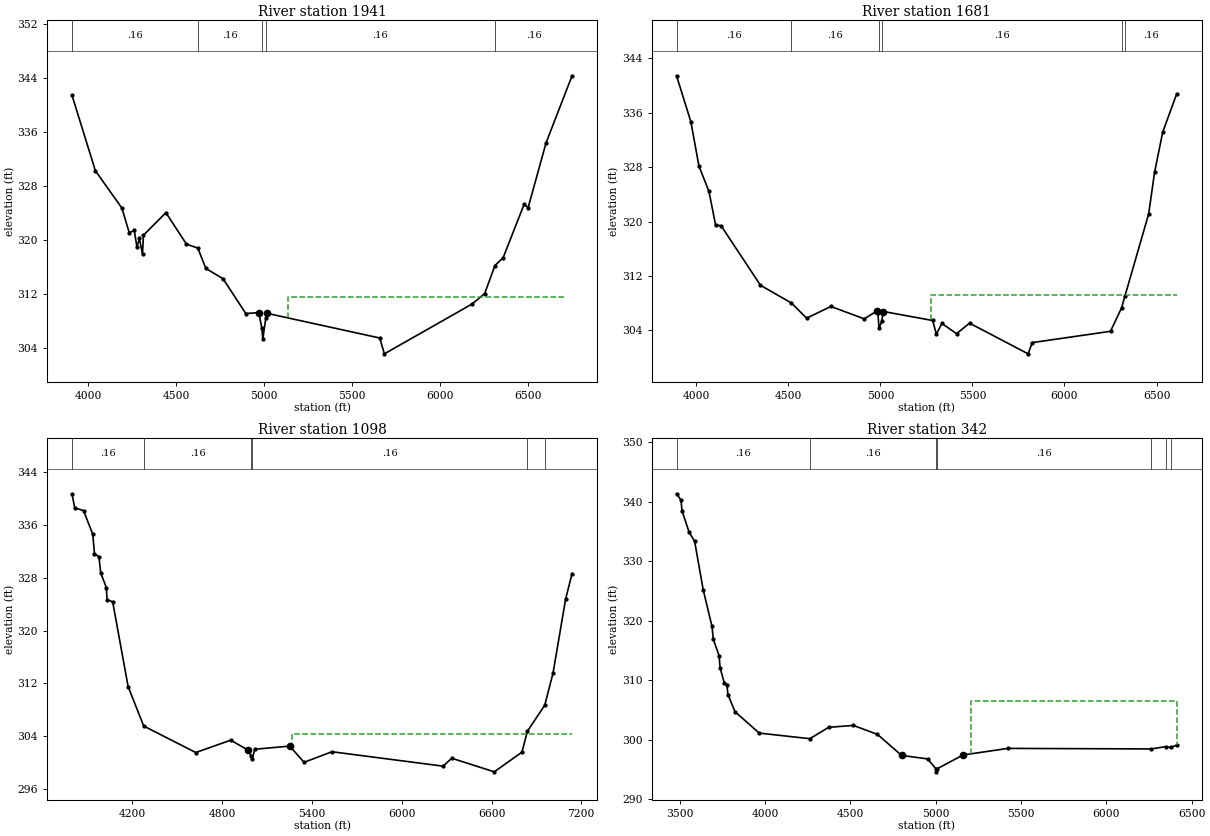
Type RM Length L Ch R = 1 ,1941    ,260,260,260
BEGIN DESCRIPTION:
Mapping XS b85eb1cd
END DESCRIPTION:
XS GIS Cut Line= 4
      3807541.84     10515171.76      3807812.65     10515789.78
      3808326.54     10516032.84      3809882.12     10515650.89
#Sta/Elev= 30
  3907.1  341.42  4040.2  330.25  4191.4  324.72  4232.7  321.08  4261.5  321.42
  4276.6  318.96  4290.4  320.24  4308.3  317.94  4313.7  320.72  4441.5  324.05
  4558.4   319.4  4623.1  318.81  4668.6   315.8  4766.5  314.28  4896.1  309.13
  4969.9  309.27  4987.2  306.97  4992.7  305.36  5009.9  308.47  5015.5  309.17
    5658  305.51  5684.5  303.17  6183.2  310.54  6255.3  312.09  6313.3  316.23
    6360  317.39  6479.5  325.29  6502.4  324.81  6604.2  334.37  6752.1   344.3
#Mann= 5 ,-1 , 0
  3907.1     .16       0  4623.1     .16       0  4987.2     .07       0
  5009.9     .16       0  6313.3     .16       0
#XS Ineff= 1 ,-1
 5134.66 6705.68311.5976
Permanent Ineff=
       F
Bank Sta=4969.9,5015.5
XS Rating Curve= 0 ,0
Exp/Cntr=0.3,0.1

Type RM Length L Ch R = 1 ,1681    ,583,583,583
BEGIN DESCRIPTION:
Mapping XS 078acfb2
END DESCRIPTION:
XS GIS Cut Line= 5
       3807409.9     10515373.15      3807743.21     10515998.11
      3808208.49     10516275.89      3808729.32     10516296.73
      3809611.23     10515956.46
#Sta/Elev= 30
  3892.6  341.41  3970.3  334.66  4014.2  328.15  4068.8  324.41  4104.6   319.5
  4134.6  319.38  4348.6  310.63  4516.1  308.04  4599.2   305.8  4731.2  307.52
  4912.1   305.7  4980.3  306.84  4986.1  306.61  4992.7  304.32  5007.5  305.35
    5016  306.78    5284  305.46    5304  303.45  5334.1  305.02  5414.1  303.52
  5484.2  305.07  5802.5  300.56  5825.1  302.21  6250.1  303.87    6310   307.3
  6329.1   309.1  6457.5  321.13  6489.7  327.26  6533.7  333.12  6609.3  338.73
#Mann= 6 ,-1 , 0
  3892.6     .16       0  4516.1     .16       0  4992.7     .07       0
  5007.5     .16       0    6310     .05       0  6329.1     .16       0
#XS Ineff= 2 , 0
                         5273.86          309.25
Permanent Ineff=
       F       F
Bank Sta=4980.3,5016
XS Rating Curve= 0 ,0
Exp/Cntr=0.3,0.1

Type RM Length L Ch R = 1 ,1098    ,756,756,756
BEGIN DESCRIPTION:
Mapping XS b6d301e9
END DESCRIPTION:
XS GIS Cut Line= 5
      3807270.98     10515505.04      3807486.26     10516414.78
      3808048.76     10516671.73      3808625.15     10516782.84
       3809575.6     10516047.45
#Sta/Elev= 30
  3796.1  340.69  3814.3  338.56  3873.3  338.15    3935  334.56  3946.3  331.65
  3976.1  331.16  3988.5   328.7  4025.7  326.49  4030.8  324.66  4067.9  324.36
  4171.3  311.53  4275.5  305.56  4623.5  301.55  4856.7  303.42  4971.8  301.93
  4994.8     301  5000.3  300.54  5017.9  302.05  5251.4  302.52  5347.1  300.07
  5533.5  301.67  6276.4  299.49    6334  300.69  6618.4  298.63  6803.4  301.61
  6839.7  304.77  6955.6  308.71  7010.7  313.53  7095.8  324.84  7138.1  328.61
#Mann= 6 ,-1 , 0
  3796.1     .16       0  4275.5     .16       0  4994.8     .07       0
  5000.3     .16       0  6839.7     .12       0  6955.6     .16       0
#XS Ineff= 1 ,-1
 5263.64 7277.27  304.37
Permanent Ineff=
       F
Bank Sta=4971.8,5251.4
XS Rating Curve= 0 ,0
Exp/Cntr=0.3,0.1

Type RM Length L Ch R = 1 ,342     ,0,0,0
BEGIN DESCRIPTION:
UNT120 IN BECR 1.0
END DESCRIPTION:
XS GIS Cut Line= 6
      3807157.93     10515709.49      3807486.26     10516928.67
      3807659.88     10517310.61       3808257.1     10517345.34
      3808625.15     10517282.84       3808852.8     10517124.18
#Sta/Elev= 30
  3480.8  341.36    3507  340.29  3512.6  338.54    3554  334.93  3586.8  333.37
  3636.9  325.24  3688.6  319.06  3696.3  316.91  3730.1  314.15  3736.2   312.1
  3761.1  309.51  3776.2  309.24  3781.9  307.61  3823.3  304.74  3965.5  301.14
  4261.9   300.2  4372.2  302.11  4517.2  302.43  4658.6  300.92    4800  297.39
  4952.6   296.8  5001.2  295.13    5004  294.63  5007.2  295.13    5160  297.46
  5423.1  298.57  6262.4  298.48  6347.4  298.86  6378.2  298.73    6412  299.11
#Mann= 7 ,-1 , 0
  3480.8     .16       0  4261.9     .16       0  5001.2     .03       0
  5007.2     .16       0  6262.4     .12       0  6347.4     .16       0
  6378.2     .12       0
#XS Ineff= 1 ,-1
  5205.4 6440.34   306.5
Permanent Ineff=
       F
Bank Sta=4800,5160
XS Rating Curve= 0 ,0
Exp/Cntr=0.3,0.1

Chan Stop Cuts=-1
Use User Specified Reach Order=0
Composite Channel Slope=5