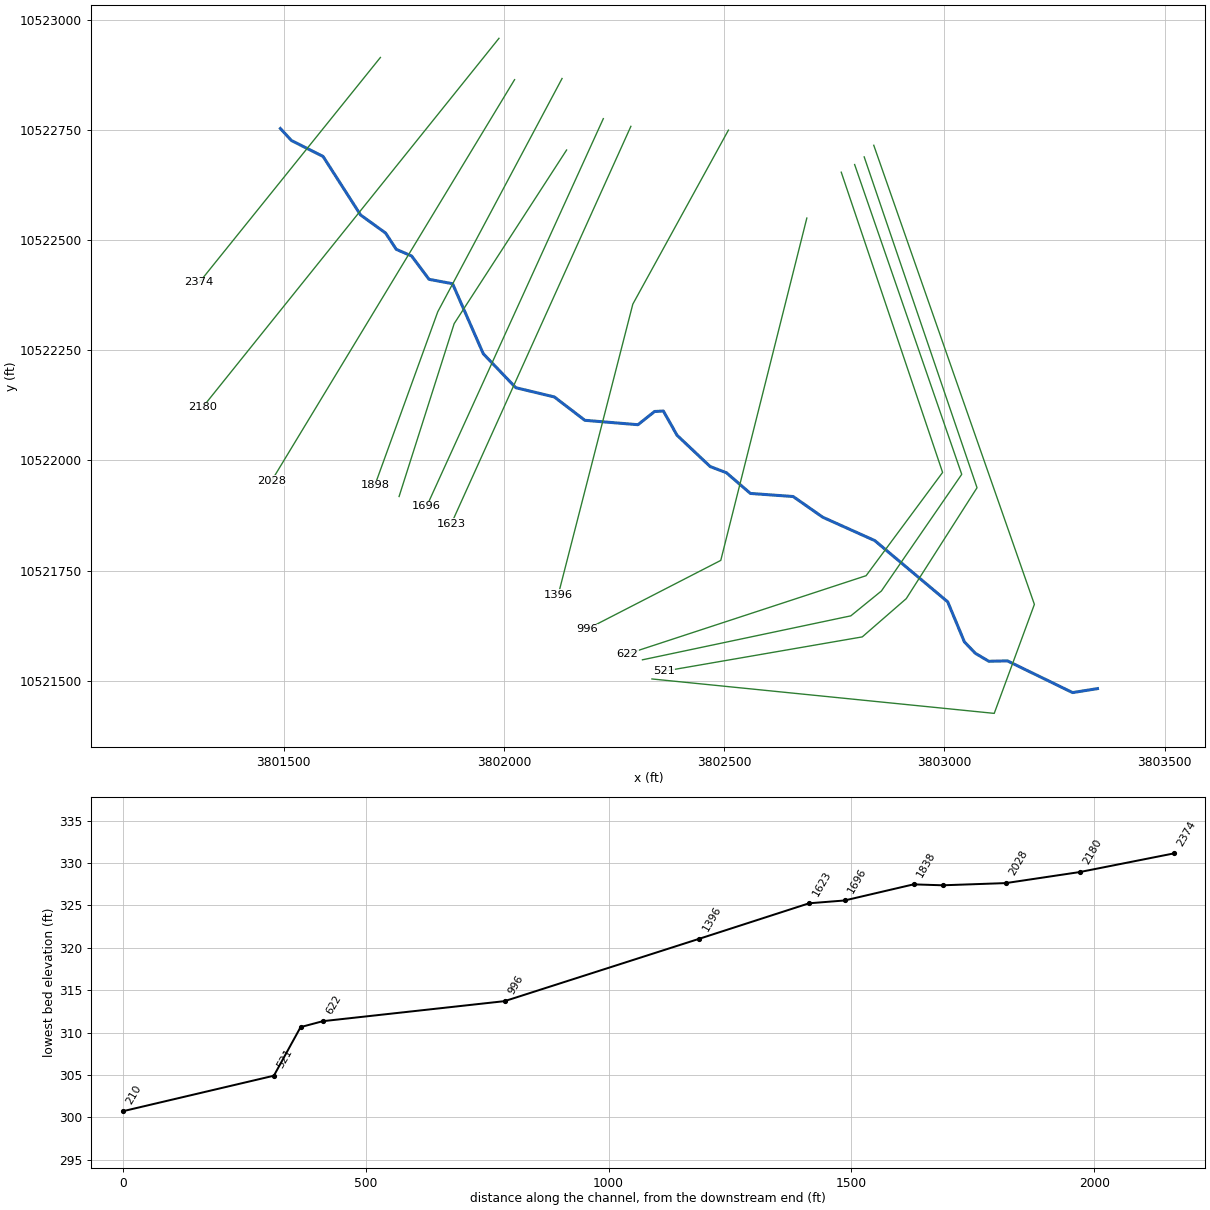
--- UNT124 IN BECR.prj (project) ---

Proj Title=UNT124 IN BECR Base Level Engineering
Current Plan=p01
Default Exp/Contr=0.3,0.1
English Units
Geom File=g01
Flow File=f01
Plan File=p01
Y Axis Title=Elevation
X Axis Title(PF)=Main Channel Distance
X Axis Title(XS)=Station
BEGIN DESCRIPTION:
UNT124 IN BECR
END DESCRIPTION:
DSS Export Rating Curves= 0
DSS Export Rating Curve Sorted= 0
DSS Export Volume Flow Curves= 0
DXF OffsetX= 0
DXF OffsetY= 0
DXF ScaleX= 1
DXF ScaleY= 10

--- UNT124 IN BECR.p01 (plan) ---

Plan Title=Multiple Run
Short Identifier=Multiple
Geom File=g01
Flow File=f01
Subcritical Flow
K Sum by GR= 0
Std Step Tol= 0.01
Critical Tol= 0.01
Num of Std Step Trials= 20
Max Error Tol= 0.3
Flow Tol Ratio= 0.001
Split Flow NTrial= 30
Split Flow Tol= 0.02
Split Flow Ratio= 0.02
Log Output Level= 0
Friction Slope Method= 1
Unsteady Friction Slope Method= 2
Unsteady Bridges Friction Slope Method= 1
Parabolic Critical Depth
Global Vel Dist=  1 , 1 , 1
Global Log Level= 0
CheckData=True
Encroach Param= -1, 0, 0, 0
BEGIN DESCRIPTION:
Multiple Run
END DESCRIPTION:

--- UNT124 IN BECR.f01 (steady flow) ---

Flow Title=Multiple
Program Version=4.10
Number of Profiles= 7
Profile Names=10-year,25-year,50-year,1pct_min,100-year,1pct_plu,500-year
River Rch & RM=UNT124 IN BECR,Reach-1         ,2374
     497     671     815     730     988    1336    1451
Boundary for River Rch & Prof#=UNT124 IN BECR,Reach-1         , 1
Up Type= 0
Dn Type= 3
Dn Slope=0.016
Boundary for River Rch & Prof#=UNT124 IN BECR,Reach-1         , 2
Up Type= 0
Dn Type= 3
Dn Slope=0.016
Boundary for River Rch & Prof#=UNT124 IN BECR,Reach-1         , 3
Up Type= 0
Dn Type= 3
Dn Slope=0.016
Boundary for River Rch & Prof#=UNT124 IN BECR,Reach-1         , 4
Up Type= 0
Dn Type= 3
Dn Slope=0.016
Boundary for River Rch & Prof#=UNT124 IN BECR,Reach-1         , 5
Up Type= 0
Dn Type= 3
Dn Slope=0.016
Boundary for River Rch & Prof#=UNT124 IN BECR,Reach-1         , 6
Up Type= 0
Dn Type= 3
Dn Slope=0.016
Boundary for River Rch & Prof#=UNT124 IN BECR,Reach-1         , 7
Up Type= 0
Dn Type= 3
Dn Slope=0.016
DSS Import GetInterval= 0
DSS Import GetPeak= 0
DSS Import FillOption= 0

--- UNT124 IN BECR.g01 (geometry) ---

Geom Title=Existing Conditions
Program Version=4.10

River Reach=UNT124 IN BECR  ,Reach-1
Reach XY= 30
      3801492.71     10522753.29      3801517.75       10522726.
       3801589.5       10522690.      3801674.75       10522557.
       3801731.5       10522516.      3801755.75       10522479.
       3801790.5       10522464.        3801830.       10522411.
       3801883.5       10522401.      3801953.25       10522242.
        3802027.       10522165.       3802114.5       10522144.
      3802183.75       10522091.      3802304.25       10522081.
        3802342.       10522111.        3802362.       10522112.
        3802393.       10522057.      3802468.25       10521986.
        3802505.       10521972.       3802559.5       10521925.
       3802656.5       10521918.      3802723.75       10521871.
      3802841.75       10521818.      3803007.25       10521679.
      3803045.25       10521588.      3803070.25       10521562.
      3803100.75       10521544.      3803142.75       10521545.
      3803290.75       10521473.      3803347.25       10521482.

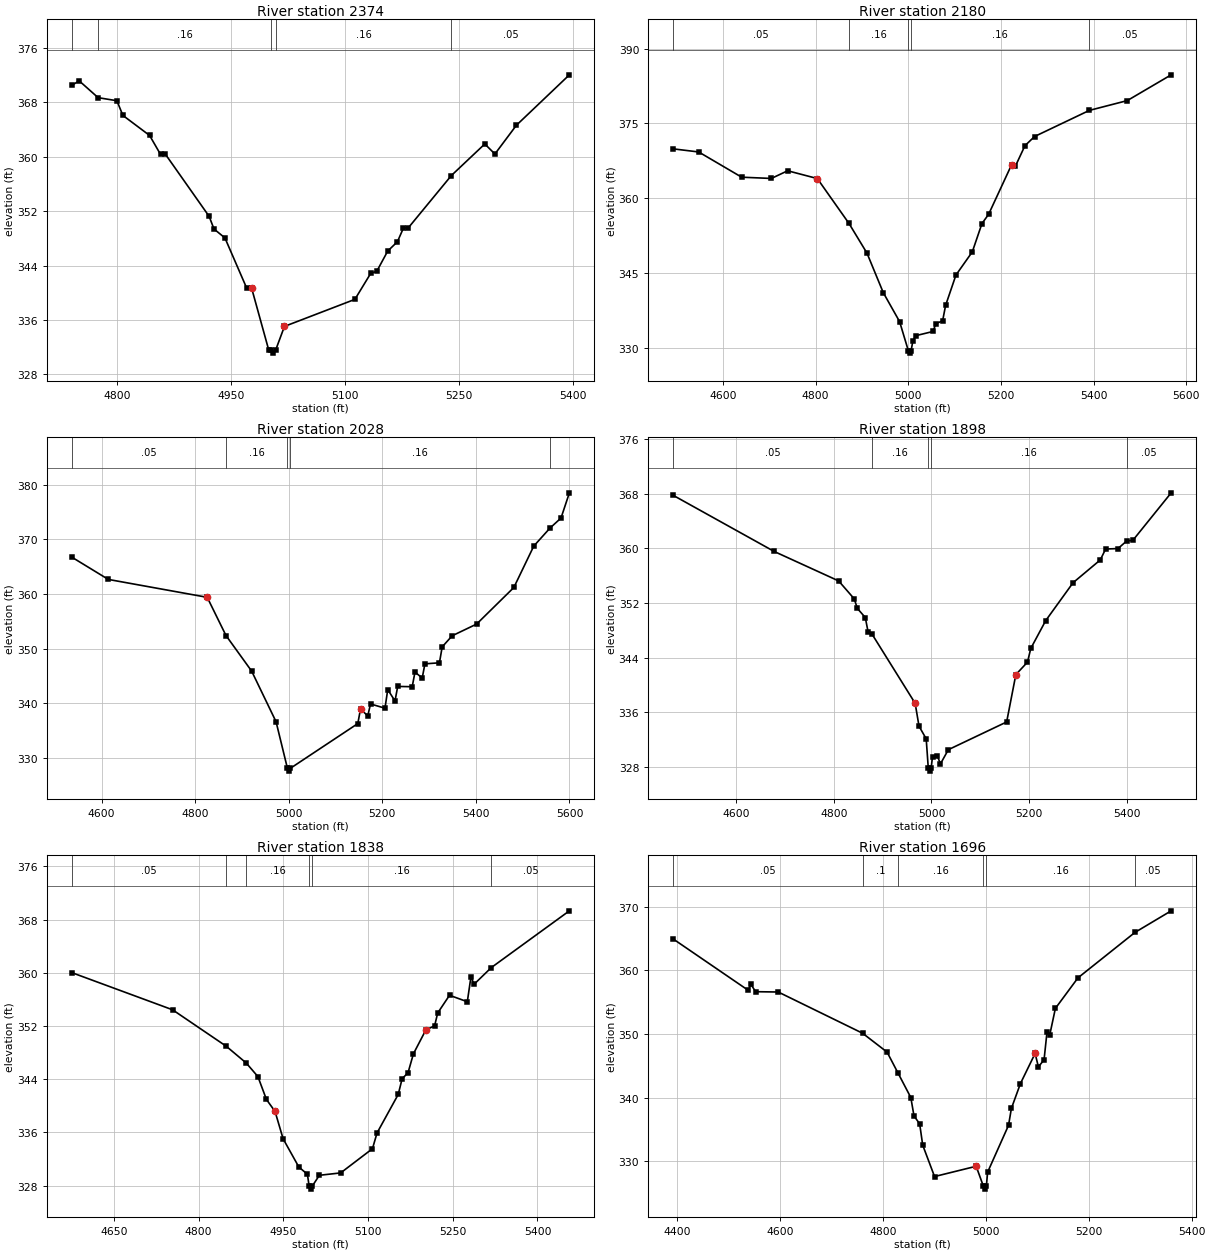
Type RM Length L Ch R = 1 ,2374    ,194,194,194
BEGIN DESCRIPTION:
UNT124 IN BECR 5.0
END DESCRIPTION:
XS GIS Cut Line= 2
       3801719.7     10522914.54       3801308.5      10522403.8
#Sta/Elev= 30
  4739.9  370.51    4750  371.18  4774.9  368.71  4799.6  368.26  4807.5   366.1
  4842.7  363.15  4857.1  360.36  4863.5  360.39  4921.1  351.25  4927.5  349.39
  4941.9  348.08  4970.7  340.66  4977.1  340.68  4999.5  331.63  5002.9  331.63
  5005.7  331.13  5008.9  331.63  5020.3  335.06  5113.1  339.04  5133.9  342.86
  5141.9  343.17  5156.3  346.14  5169.1  347.52  5177.1  349.55  5183.5  349.57
  5240.2  357.26  5284.2   361.9  5297.5  360.42  5325.8  364.65  5395.6  372.07
#Mann= 5 ,-1 , 0
  4739.9     .05       0  4774.9     .16       0  5002.9     .07       0
  5008.9     .16       0  5240.2     .05       0
Bank Sta=4977.1,5020.3
XS Rating Curve= 0 ,0
Exp/Cntr=0.3,0.1

Type RM Length L Ch R = 1 ,2180    ,152,152,152
BEGIN DESCRIPTION:
Mapping XS 3dca8ac5
END DESCRIPTION:
XS GIS Cut Line= 2
      3801988.79     10522957.94      3801316.03     10522120.25
#Sta/Elev= 30
  4492.9  369.89  4547.6  369.27  4640.4  364.21  4704.4  363.96  4739.6   365.5
  4803.6  363.94    4872  354.93  4910.8  348.98    4946  341.05  4981.2  335.25
    5000  329.43  5002.8  328.93    5006  329.43    5010  331.44  5016.5  332.44
  5053.2  333.27  5059.6  334.85    5074   335.4  5080.5  338.51  5102.8  344.59
  5138.1  349.24  5158.9  354.91  5173.3  356.77  5222.9  366.71  5230.9  366.38
  5251.7  370.53  5272.5  372.37  5390.8  377.61  5472.5  379.57  5567.3  384.74
#Mann= 5 ,-1 , 0
  4492.9     .05       0    4872     .16       0    5000     .07       0
    5006     .16       0  5390.8     .05       0
Bank Sta=4803.6,5222.9
XS Rating Curve= 0 ,0
Exp/Cntr=0.3,0.1

Type RM Length L Ch R = 1 ,2028    ,130,130,130
BEGIN DESCRIPTION:
Mapping XS 2e645d51
END DESCRIPTION:
XS GIS Cut Line= 2
      3802024.25     10522864.17       3801472.9     10521953.93
#Sta/Elev= 30
  4535.6  366.77  4614.2  362.67  4825.6   359.4  4865.7  352.42  4920.6  345.91
  4972.8  336.65  4997.1  328.13  4999.9  327.63  5003.1  328.13  5147.5  336.32
  5153.3  338.98  5168.8  337.73  5174.7  339.91  5205.6  339.13  5211.5  342.54
    5227  340.45  5232.8  343.11  5263.8  343.06  5269.7  345.72  5285.2  344.66
    5291  347.24    5322  347.43  5327.9  350.34  5349.2  352.37  5401.5  354.51
  5481.1   361.2  5523.7  368.77  5558.5  372.07  5581.9  373.89  5599.8   378.5
#Mann= 5 ,-1 , 0
  4535.6     .05       0  4865.7     .16       0  4997.1     .07       0
  5003.1     .16       0  5558.5     .05       0
Bank Sta=4825.6,5153.3
XS Rating Curve= 0 ,0
Exp/Cntr=0.3,0.1

Type RM Length L Ch R = 1 ,1898    ,60,60,60
BEGIN DESCRIPTION:
UNT124 IN BECR 4.0
END DESCRIPTION:
XS GIS Cut Line= 3
      3802131.99     10522866.75      3801849.89     10522337.27
       3801707.2     10521943.79
#Sta/Elev= 30
  4471.9  367.74  4678.3  359.53  4810.1  355.22  4841.9   352.6  4848.4  351.19
  4864.6  349.86  4870.3  347.76  4878.2  347.45  4966.6   337.3  4974.5  333.95
  4989.2   332.1  4993.4  327.87  4996.2  327.37  4999.4  327.87  5002.1  329.49
  5011.9  329.61  5018.4  328.44  5034.5  330.51  5153.8  334.57  5172.6   341.5
  5196.4  343.33  5203.2  345.34  5233.8  349.42  5289.7  354.96  5345.3  358.29
  5356.3  359.89  5381.6  359.96  5399.2  361.06  5412.2  361.18  5490.4  368.12
#Mann= 5 ,-1 , 0
  4471.9     .05       0  4878.2     .16       0  4993.4     .07       0
  4999.4     .16       0  5399.2     .05       0
Bank Sta=4966.6,5172.6
XS Rating Curve= 0 ,0
Exp/Cntr=0.3,0.1

Type RM Length L Ch R = 1 ,1838    ,142,142,142
BEGIN DESCRIPTION:
Mapping XS 7d07a34d
END DESCRIPTION:
XS GIS Cut Line= 3
      3802142.33     10522704.49       3801887.1     10522310.37
      3801762.11     10521918.04
#Sta/Elev= 30
  4575.2  360.05    4754  354.45    4849  348.97  4884.5  346.44  4905.1   344.4
  4920.2  340.96  4935.4  339.17  4949.7  335.05  4977.6   330.8  4992.7  329.72
  4995.7  327.98  4998.5  327.48  5001.7  327.98  5013.9  329.56  5051.6  329.92
  5107.9  333.56    5116  335.93  5153.5  341.72  5160.4  344.08  5170.9  344.99
  5180.4  347.83  5202.4  351.42  5217.9  352.04  5223.4  353.97  5244.3  356.63
  5275.8  355.66  5282.3  359.44  5287.6  358.27  5318.2  360.79  5456.5  369.33
#Mann= 6 ,-1 , 0
  4575.2     .05       0    4849      .1       0  4884.5     .16       0
  4995.7     .07       0  5001.7     .16       0  5318.2     .05       0
Bank Sta=4935.4,5202.4
XS Rating Curve= 0 ,0
Exp/Cntr=0.3,0.1

Type RM Length L Ch R = 1 ,1696    ,73,73,73
BEGIN DESCRIPTION:
Mapping XS aa24530e
END DESCRIPTION:
XS GIS Cut Line= 2
      3802225.66     10522775.67       3801824.6     10521895.43
#Sta/Elev= 30
  4392.9  364.94  4538.2  356.89  4543.7   357.8  4552.8  356.66  4596.7  356.61
  4760.6  350.12  4808.2  347.15  4829.4  343.86  4854.3     340  4860.5   337.1
  4871.5  335.86  4877.4  332.51  4900.4  327.56  4981.3  329.18  4995.1  326.08
  4997.9  325.58  5001.1  326.08  5003.6  328.26  5044.2  335.63  5049.7  338.28
  5067.3   342.2  5095.8  346.94  5102.2  344.83  5113.2  345.94  5118.9  350.28
  5124.3  349.87  5135.2  354.03  5179.1  358.84  5289.8  365.99  5360.2  369.39
#Mann= 6 ,-1 , 0
  4392.9     .05       0  4760.6      .1       0  4829.4     .16       0
  4995.1     .07       0  5001.1     .16       0  5289.8     .05       0
Bank Sta=4981.3,5095.8
XS Rating Curve= 0 ,0
Exp/Cntr=0.3,0.1

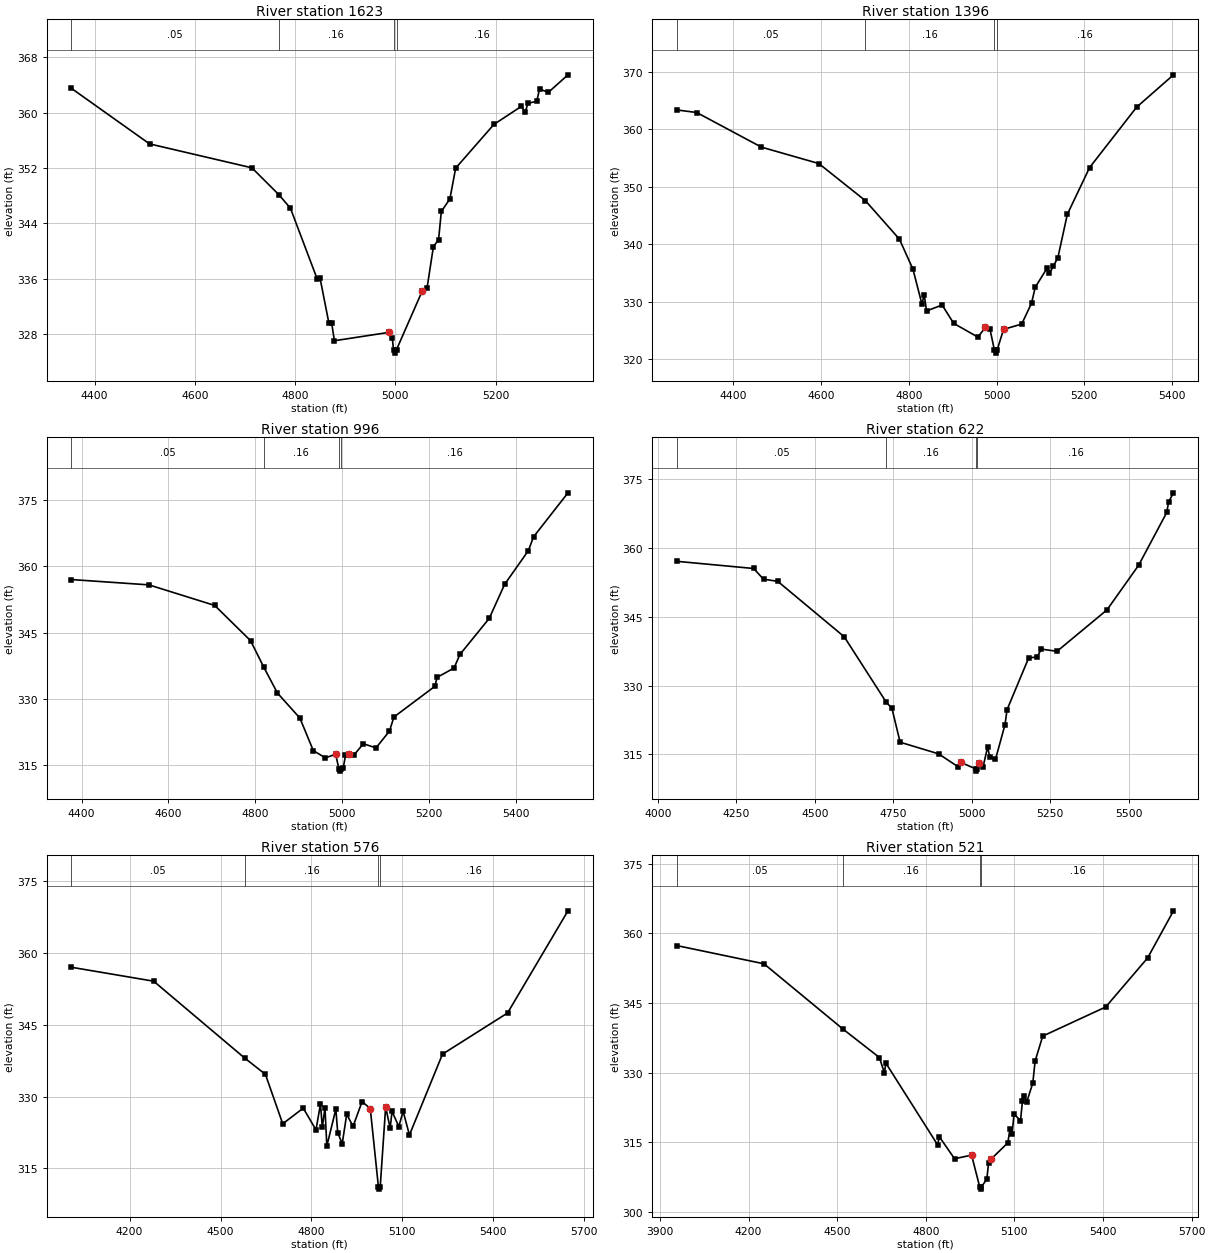
Type RM Length L Ch R = 1 ,1623    ,227,227,227
BEGIN DESCRIPTION:
UNT124 IN BECR 3.0
END DESCRIPTION:
XS GIS Cut Line= 2
      3802288.24     10522758.23      3801880.29     10521855.53
#Sta/Elev= 30
  4353.8  363.51  4509.5  355.49  4713.8  352.03  4767.5  348.15  4790.6   346.2
  4844.1  335.95  4849.6  336.14  4867.2  329.65  4872.7  329.67  4878.4  327.04
  4988.1  328.26  4993.8  327.47  4996.3  325.75    4999  325.25  5002.3  325.75
    5054  334.29  5063.1   334.6  5075.9  340.63  5086.2  341.64  5091.7  345.72
  5108.8  347.54  5120.3  351.98  5196.6   358.3  5251.5  360.92    5259  360.04
  5264.5  361.36  5282.1  361.64  5287.6  363.41  5305.3  362.94  5344.4  365.47
#Mann= 4 ,-1 , 0
  4353.8     .05       0  4767.5     .16       0  4996.3     .07       0
  5002.3     .16       0
Bank Sta=4988.1,5054
XS Rating Curve= 0 ,0
Exp/Cntr=0.3,0.1

Type RM Length L Ch R = 1 ,1396    ,400,400,400
BEGIN DESCRIPTION:
Mapping XS 28d903f1
END DESCRIPTION:
XS GIS Cut Line= 3
       3802509.6     10522749.57       3802292.6     10522354.63
      3802123.36     10521695.02
#Sta/Elev= 30
  4271.5  363.32  4316.4  362.88  4463.9  356.86  4594.7  354.01  4700.8  347.56
  4778.3  340.88  4809.3  335.64  4829.8  329.56  4834.9  331.24  4840.3  328.38
  4875.7  329.42  4902.2  326.22  4957.2  323.84  4974.5  325.52  4984.8  325.24
    4995  321.55  4997.7  321.05    5001  321.55  5015.8  325.18  5057.1   326.1
  5079.5  329.71    5088   332.5  5115.1  335.83  5120.3   334.9  5129.3  336.16
  5139.7  337.67  5161.1  345.17  5211.9  353.31    5319   363.8  5403.1  369.43
#Mann= 4 ,-1 , 0
  4271.5     .05       0  4700.8     .16       0    4995     .07       0
    5001     .16       0
Bank Sta=4974.5,5015.8
XS Rating Curve= 0 ,0
Exp/Cntr=0.3,0.1

Type RM Length L Ch R = 1 ,996     ,374,374,374
BEGIN DESCRIPTION:
UNT124 IN BECR 2.0
END DESCRIPTION:
XS GIS Cut Line= 3
      3802687.57     10522549.98      3802492.25     10521773.03
       3802188.4     10521616.77
#Sta/Elev= 30
  4376.8     357    4555   355.8  4706.5  351.15    4789  343.19  4819.1  337.26
  4850.9  331.35  4902.5   325.7  4933.4  318.35  4961.2  316.71  4984.9  317.52
  4992.3  314.21    4995  313.71  4998.3  314.21  5002.3  314.43  5007.5  317.25
  5015.9  317.56  5026.2  317.25  5048.6   319.9  5077.7  318.96  5108.7  322.76
    5119  325.94    5213  332.86  5218.6  334.92  5257.3     337  5270.9  340.07
  5338.3  348.22  5373.8  355.92  5428.3  363.52  5440.4  366.66  5519.6   376.6
#Mann= 4 ,-1 , 0
  4376.8     .05       0  4819.1     .16       0  4992.3     .07       0
  4998.3     .16       0
Bank Sta=4984.9,5015.9
XS Rating Curve= 0 ,0
Exp/Cntr=0.3,0.1

Type RM Length L Ch R = 1 ,622     ,46,46,46
BEGIN DESCRIPTION:
Mapping XS a8b7c47b
END DESCRIPTION:
XS GIS Cut Line= 4
      3802765.68     10522654.13      3802995.72     10521972.68
      3802822.11     10521738.31      3802279.55     10521560.35
#Sta/Elev= 30
    4061  357.07  4305.2  355.51  4336.7  353.17  4381.8  352.72  4593.7  340.64
  4727.9  326.35  4745.7  325.06  4771.9  317.65  4894.4  315.12  4957.6  312.26
  4965.3  313.25  5012.4  311.85  5015.2  311.35  5018.4  311.85  5021.7  313.07
  5036.3  312.32  5050.9  316.66  5057.1  314.42  5075.8  313.92  5106.1  321.49
  5112.7  324.75  5181.6  336.04  5208.2  336.21  5221.9  337.94  5271.8  337.46
    5431  346.49  5531.7   356.2  5621.8  367.76  5627.2     370  5642.9     372
#Mann= 4 ,-1 , 0
    4061     .05       0  4727.9     .16       0  5012.4     .07       0
  5018.4     .16       0
Bank Sta=4965.3,5021.7
XS Rating Curve= 0 ,0
Exp/Cntr=0.3,0.1

Type RM Length L Ch R = 1 ,576     ,55,55,55
BEGIN DESCRIPTION:
Mapping XS 595b30df
END DESCRIPTION:
XS GIS Cut Line= 5
      3802796.06     10522671.49      3803039.13     10521968.34
      3802856.83     10521703.59      3802787.39     10521647.16
       3802314.5     10521547.38
#Sta/Elev= 30
  4008.2  357.03  4279.3  354.12  4579.6  338.05  4648.1  334.65  4705.2  324.31
    4773  327.58  4814.9  323.04  4829.8  328.44  4835.8  323.56  4844.6   327.7
  4850.7  319.63  4880.5  327.38  4886.6  322.46  4901.5  320.14  4916.3  326.28
  4937.3  323.78  4967.1  328.96  4994.1  327.48  5020.9  311.15  5023.6  310.65
  5026.9  311.15  5044.8  327.83  5059.7  323.37  5065.8  326.91  5088.2  323.74
  5102.5  326.91  5123.3  321.97  5232.4  338.87    5447  347.47  5646.4  368.83
#Mann= 4 ,-1 , 0
  4008.2     .05       0  4579.6     .16       0  5020.9     .07       0
  5026.9     .16       0
Bank Sta=4994.1,5044.8
XS Rating Curve= 0 ,0
Exp/Cntr=0.3,0.1

Type RM Length L Ch R = 1 ,521     ,311,311,311
BEGIN DESCRIPTION:
Mapping XS 75d24271
END DESCRIPTION:
XS GIS Cut Line= 5
      3802817.76     10522688.85      3803073.85     10521937.96
      3802913.26     10521686.23      3802813.43     10521599.42
      3802363.36     10521521.52
#Sta/Elev= 30
  3957.5  357.33  4251.9  353.42  4519.4  339.37  4642.8  333.25  4659.5  329.97
  4664.8  332.03  4839.8  314.46  4845.7  316.19  4897.3  311.46  4954.9  312.24
  4982.3  305.42  4985.1  304.92  4988.3  305.42  5006.5  307.06  5012.4  310.56
    5021  311.38  5077.8   314.9  5084.5  317.78  5092.1  316.83  5098.7  321.07
  5120.5  319.67  5127.2  323.84  5133.8  325.06  5141.4  323.63  5162.3  327.79
  5169.9  332.46  5195.8  337.86  5408.9  344.12    5551  354.68  5638.5  364.82
#Mann= 4 ,-1 , 0
  3957.5     .05       0  4519.4     .16       0  4982.3     .07       0
  4988.3     .16       0
Bank Sta=4954.9,5021
XS Rating Curve= 0 ,0
Exp/Cntr=0.3,0.1

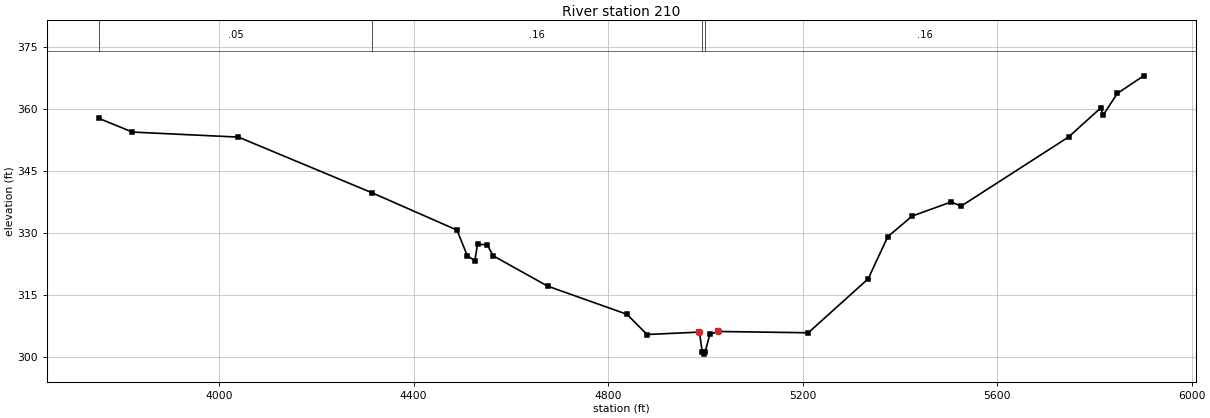
Type RM Length L Ch R = 1 ,210     ,0,0,0
BEGIN DESCRIPTION:
UNT124 IN BECR 1.0
END DESCRIPTION:
XS GIS Cut Line= 4
      3802839.49      10522715.2      3803204.06     10521673.21
      3803112.91     10521425.81      3802336.01     10521503.93
#Sta/Elev= 30
  3752.8  357.78  3821.7  354.47  4039.8  353.25  4315.4  339.73  4489.1  330.75
  4510.3  324.58  4525.8   323.3  4531.5  327.32  4551.5  327.18  4563.3  324.55
  4675.6  317.19  4838.7  310.37    4880  305.48  4987.8  306.06  4993.5  301.23
  4996.2  300.73  4999.5  301.23  5009.1  305.52  5026.9  306.21  5211.6   305.9
  5334.8  318.96    5375  329.14  5425.2  334.14  5505.6  337.56  5525.7  336.53
  5746.8  353.27    5813  360.31    5818  358.58  5847.3  363.84  5901.2  368.08
#Mann= 4 ,-1 , 0
  3752.8     .05       0  4315.4     .16       0  4993.5     .07       0
  4999.5     .16       0
Bank Sta=4987.8,5026.9
XS Rating Curve= 0 ,0
Exp/Cntr=0.3,0.1

Chan Stop Cuts=-1
Use User Specified Reach Order=0
Composite Channel Slope=5