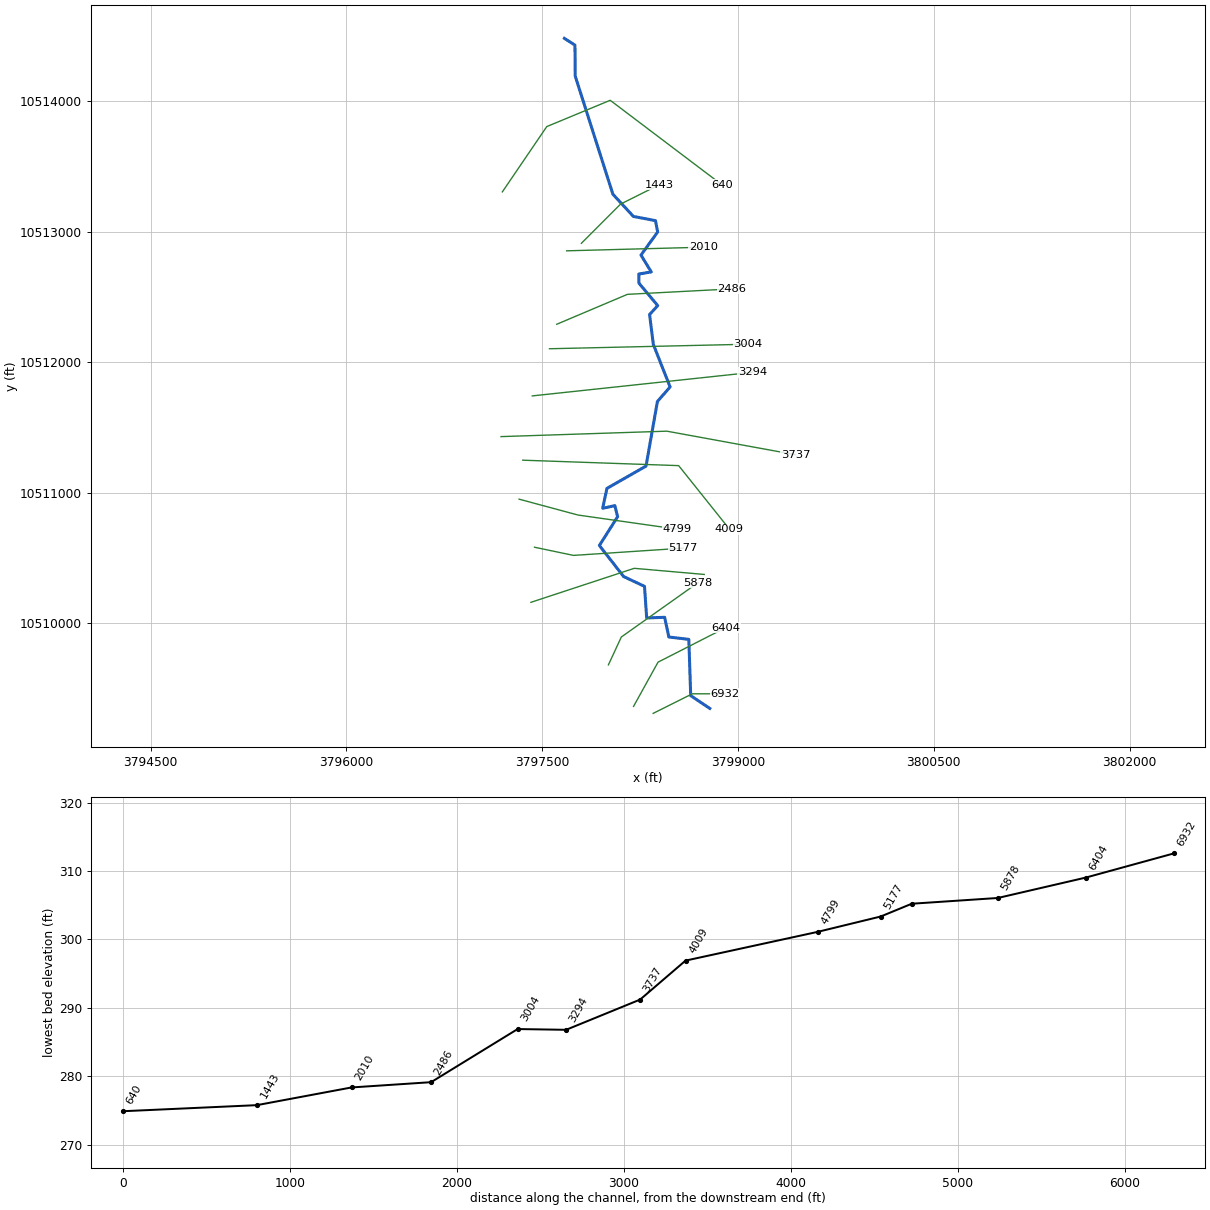
--- UNT128 IN BECR.prj (project) ---

Proj Title=UNT128 IN BECR Base Level Engineering
Current Plan=p01
Default Exp/Contr=0.3,0.1
English Units
Geom File=g01
Flow File=f01
Plan File=p01
BEGIN DESCRIPTION:
UNT128 IN BECR
END DESCRIPTION:

--- UNT128 IN BECR.p01 (plan) ---

Plan Title=Multiple Run
Short Identifier=Multiple
Geom File=g01
Flow File=f01
Subcritical Flow
K Sum by GR= 0
Std Step Tol= 0.01
Critical Tol= 0.01
Num of Std Step Trials= 20
Max Error Tol= 0.3
Flow Tol Ratio= 0.001
Split Flow NTrial= 30
Split Flow Tol= 0.02
Split Flow Ratio= 0.02
Log Output Level= 0
Friction Slope Method= 1
Unsteady Friction Slope Method= 2
Unsteady Bridges Friction Slope Method= 1
Parabolic Critical Depth
Global Vel Dist=  1 , 1 , 1
Global Log Level= 0
CheckData=True
Encroach Param= -1, 0, 0, 0
BEGIN DESCRIPTION:
Multiple Run
END DESCRIPTION:

--- UNT128 IN BECR.f01 (steady flow) ---

Flow Title=Multiple
Number of Profiles=7
Profile Names=10-year,25-year,50-year,1pct_min,100-year,1pct_plu,500-year
River Rch & RM= UNT128 IN BECR,Reach-1,6932
     516     695     841     750    1015    1373    1480
Boundary for River Rch & Prof#=UNT128 IN BECR,Reach-1,1
Up Type=0
Dn Type=3
Dn Slope=0.005
Boundary for River Rch & Prof#=UNT128 IN BECR,Reach-1,2
Up Type=0
Dn Type=3
Dn Slope=0.005
Boundary for River Rch & Prof#=UNT128 IN BECR,Reach-1,3
Up Type=0
Dn Type=3
Dn Slope=0.005
Boundary for River Rch & Prof#=UNT128 IN BECR,Reach-1,4
Up Type=0
Dn Type=3
Dn Slope=0.005
Boundary for River Rch & Prof#=UNT128 IN BECR,Reach-1,5
Up Type=0
Dn Type=3
Dn Slope=0.005
Boundary for River Rch & Prof#=UNT128 IN BECR,Reach-1,6
Up Type=0
Dn Type=3
Dn Slope=0.005
Boundary for River Rch & Prof#=UNT128 IN BECR,Reach-1,7
Up Type=0
Dn Type=3
Dn Slope=0.005

--- UNT128 IN BECR.g01 (geometry) ---

Geom Title=Existing Conditions

River Reach=UNT128 IN BECR,Reach-1
Reach XY= 30
      3798783.19     10509348.24      3798637.25     10509446.00
      3798623.00     10509877.00      3798470.00     10509895.00
      3798437.50     10510046.00      3798300.00     10510041.00
      3798283.25     10510283.00      3798123.50     10510358.00
      3797937.50     10510596.00      3798077.25     10510816.00
      3798056.25     10510901.00      3797962.75     10510881.00
      3797995.50     10511033.00      3798295.00     10511204.00
      3798382.25     10511699.00      3798479.50     10511810.00
      3798351.00     10512136.00      3798322.25     10512365.00
      3798384.75     10512433.00      3798240.75     10512605.00
      3798239.75     10512675.00      3798335.25     10512691.00
      3798256.25     10512820.00      3798384.25     10512997.00
      3798367.25     10513084.00      3798198.25     10513116.00
      3798041.25     10513286.00      3797752.50     10514191.00
      3797750.50     10514428.00      3797669.50     10514480.00

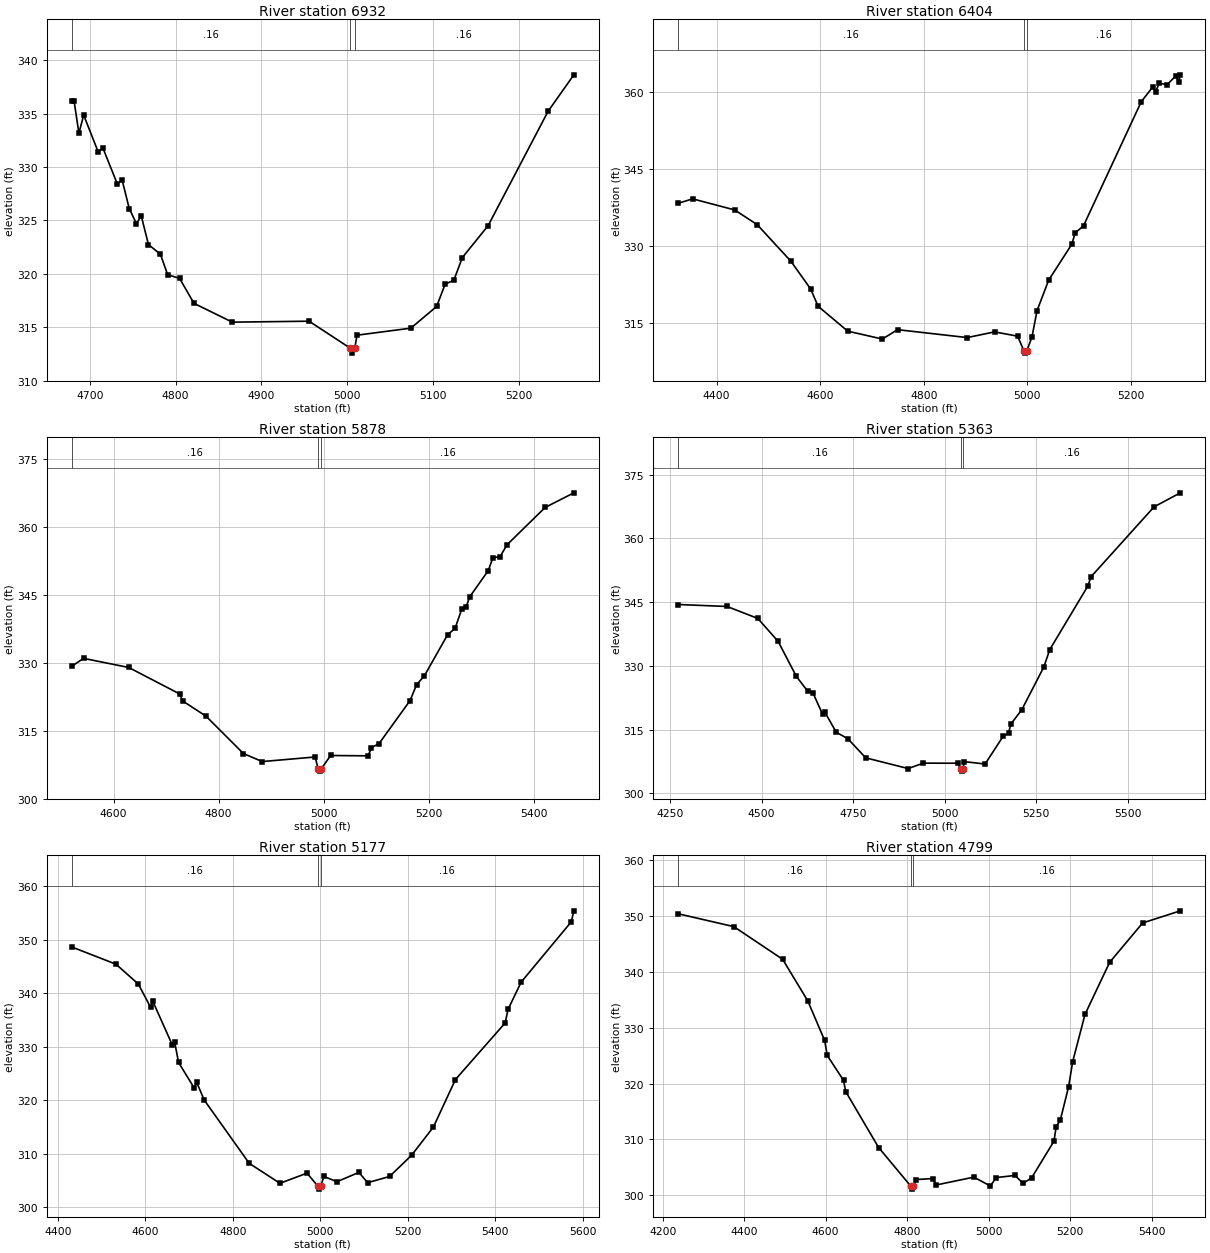
Type RM Length L Ch R = 1,6932,528,528,528
BEGIN DESCRIPTION:
UNT128 IN BECR 13.0
END DESCRIPTION:
XS GIS Cut Line= 3
      3798349.65     10509310.21      3798649.61     10509460.19
      3798899.65     10509460.19
#Sta/Elev= 30
  4679.0  336.19  4681.7  336.19  4687.3  333.17  4692.9  334.87  4709.7  331.44
  4715.3  331.79  4732.1  328.42  4737.6  328.83  4746.0  326.12  4754.4  324.70
  4760.0  325.44  4768.4  322.75  4782.4  321.83  4790.8  319.92  4804.7  319.58
  4821.5  317.24  4866.2  315.48  4955.7  315.57  5003.0  313.08  5005.7  312.58
  5009.0  313.08  5011.6  314.26  5074.4  314.92  5104.4  316.95  5114.4  319.05
  5124.4  319.39  5134.4  321.53  5164.4  324.51  5234.4  335.23  5264.4  338.64
#Mann=3,-1,0
  4679.0    0.16       0  5003.0    0.07       0  5009.0    0.16       0
Bank Sta=5003,5009
Exp/Cntr=0.3,0.1

Type RM Length L Ch R = 1,6404,526,526,526
BEGIN DESCRIPTION:
UNT128 IN BECR 12.0
END DESCRIPTION:
XS GIS Cut Line= 3
      3798199.47     10509363.81      3798386.98     10509702.37
      3798906.24     10509967.19
#Sta/Elev= 30
  4325.8  338.23  4353.6  339.09  4434.9  336.93  4478.4  334.06  4543.7  326.91
  4581.5  321.55  4596.0  318.17  4653.2  313.32  4720.2  311.78  4749.4  313.61
  4884.1  312.07  4936.9  313.18  4981.4  312.34  4993.4  309.54  4996.2  309.04
  4999.4  309.54  5009.2  312.22  5018.9  317.30  5041.3  323.24  5086.2  330.27
  5092.5  332.43  5108.7  333.85  5220.3  358.02  5242.5  360.89  5248.1  359.89
  5254.6  361.62  5270.4  361.35  5287.0  363.06  5292.6  361.79  5295.7  363.25
#Mann=3,-1,0
  4325.8    0.16       0  4993.4    0.07       0  4999.4    0.16       0
Bank Sta=4993.4,4999.4
Exp/Cntr=0.3,0.1

Type RM Length L Ch R = 1,5878,515,515,515
BEGIN DESCRIPTION:
UNT128 IN BECR 11.0
END DESCRIPTION:
XS GIS Cut Line= 3
      3798006.76     10509681.51      3798105.73     10509895.08
      3798694.28     10510311.75
#Sta/Elev= 30
  4520.2  329.20  4542.6  330.94  4628.7  328.93  4725.9  323.08  4731.4  321.54
  4775.9  318.19  4847.3  309.93  4883.0  308.17  4983.9  309.18  4989.5  306.56
  4992.3  306.06  4995.5  306.56  5013.4  309.51  5084.8  309.43  5091.1  311.23
  5105.7  312.15  5164.7  321.63  5177.1  325.13  5191.9  327.08  5236.2  336.15
  5250.4  337.55  5263.2  341.82  5271.9  342.38  5278.0  344.46  5313.7  350.31
  5322.4  353.13  5336.2  353.39  5349.4  356.00  5422.0  364.23  5476.7  367.46
#Mann=3,-1,0
  4520.2    0.16       0  4989.5    0.07       0  4995.5    0.16       0
Bank Sta=4989.5,4995.5
Exp/Cntr=0.3,0.1

Type RM Length L Ch R = 1,5363,186,186,186
BEGIN DESCRIPTION:
UNT128 IN BECR 10.0
END DESCRIPTION:
XS GIS Cut Line= 3
      3797413.05     10510160.71      3798204.69     10510421.12
      3798741.17     10510374.25
#Sta/Elev= 30
  4272.0  344.44  4405.2  343.98  4489.5  341.16  4544.8  335.78  4594.7  327.53
  4626.3  323.97  4640.2  323.60  4666.8  318.56  4672.0  319.20  4703.8  314.37
  4735.6  312.84  4784.2  308.35  4900.0  305.83  4942.1  307.10  5036.9  307.08
  5044.4  305.72  5047.1  305.22  5050.4  305.72  5053.5  307.46  5110.4  306.89
  5160.5  313.51  5174.5  314.09  5180.6  316.26  5210.7  319.67  5270.9  329.72
  5287.2  333.83  5391.4  348.81  5399.8  350.96  5572.1  367.42  5643.9  370.73
#Mann=3,-1,0
  4272.0    0.16       0  5044.4    0.07       0  5050.4    0.16       0
Bank Sta=5044.4,5050.4
Exp/Cntr=0.3,0.1

Type RM Length L Ch R = 1,5177,378,378,378
BEGIN DESCRIPTION:
UNT128 IN BECR 9.0
END DESCRIPTION:
XS GIS Cut Line= 3
      3797440.77     10510582.59      3797739.42     10510520.08
      3798579.66     10510575.63
#Sta/Elev= 30
  4432.1  348.63  4533.1  345.41  4584.2  341.70  4612.2  337.34  4617.3  338.48
  4662.1  330.25  4667.2  330.83  4676.1  327.04  4712.1  322.23  4717.2  323.37
  4734.8  320.00  4837.6  308.17  4907.8  304.44  4969.6  306.34  4995.0  303.85
  4997.7  303.35  5001.0  303.85  5008.0  305.72  5038.1  304.74  5088.2  306.48
  5108.2  304.55  5158.3  305.72  5208.4  309.67  5258.5  314.97  5308.7  323.84
  5422.4  334.43  5428.9  336.96  5459.0  342.07  5573.4  353.33  5579.3  355.39
#Mann=3,-1,0
  4432.1    0.16       0  4995.0    0.07       0  5001.0    0.16       0
Bank Sta=4995,5001
Exp/Cntr=0.3,0.1

Type RM Length L Ch R = 1,4799,790,790,790
BEGIN DESCRIPTION:
UNT128 IN BECR 8.0
END DESCRIPTION:
XS GIS Cut Line= 3
      3797322.79     10510950.62      3797774.14     10510829.11
      3798531.10     10510721.47
#Sta/Elev= 30
  4238.3  350.40  4374.7  348.10  4494.5  342.25  4556.0  334.83  4597.5  327.74
  4604.0  325.03  4644.0  320.56  4649.2  318.57  4730.0  308.55  4809.3  301.60
  4812.0  301.10  4815.3  301.60  4822.4  302.82  4862.8  302.99  4871.7  301.85
  4963.8  303.25  5004.2  301.66  5018.5  303.17  5064.8  303.55  5084.3  302.13
  5105.2  303.09  5160.2  309.68  5165.8  312.27  5175.9  313.47  5196.1  319.41
  5206.2  323.93  5236.5  332.40  5296.9  341.71  5377.9  348.76  5470.3  350.93
#Mann=3,-1,0
  4238.3    0.16       0  4809.3    0.07       0  4815.3    0.16       0
Bank Sta=4809.3,4815.3
Exp/Cntr=0.3,0.1

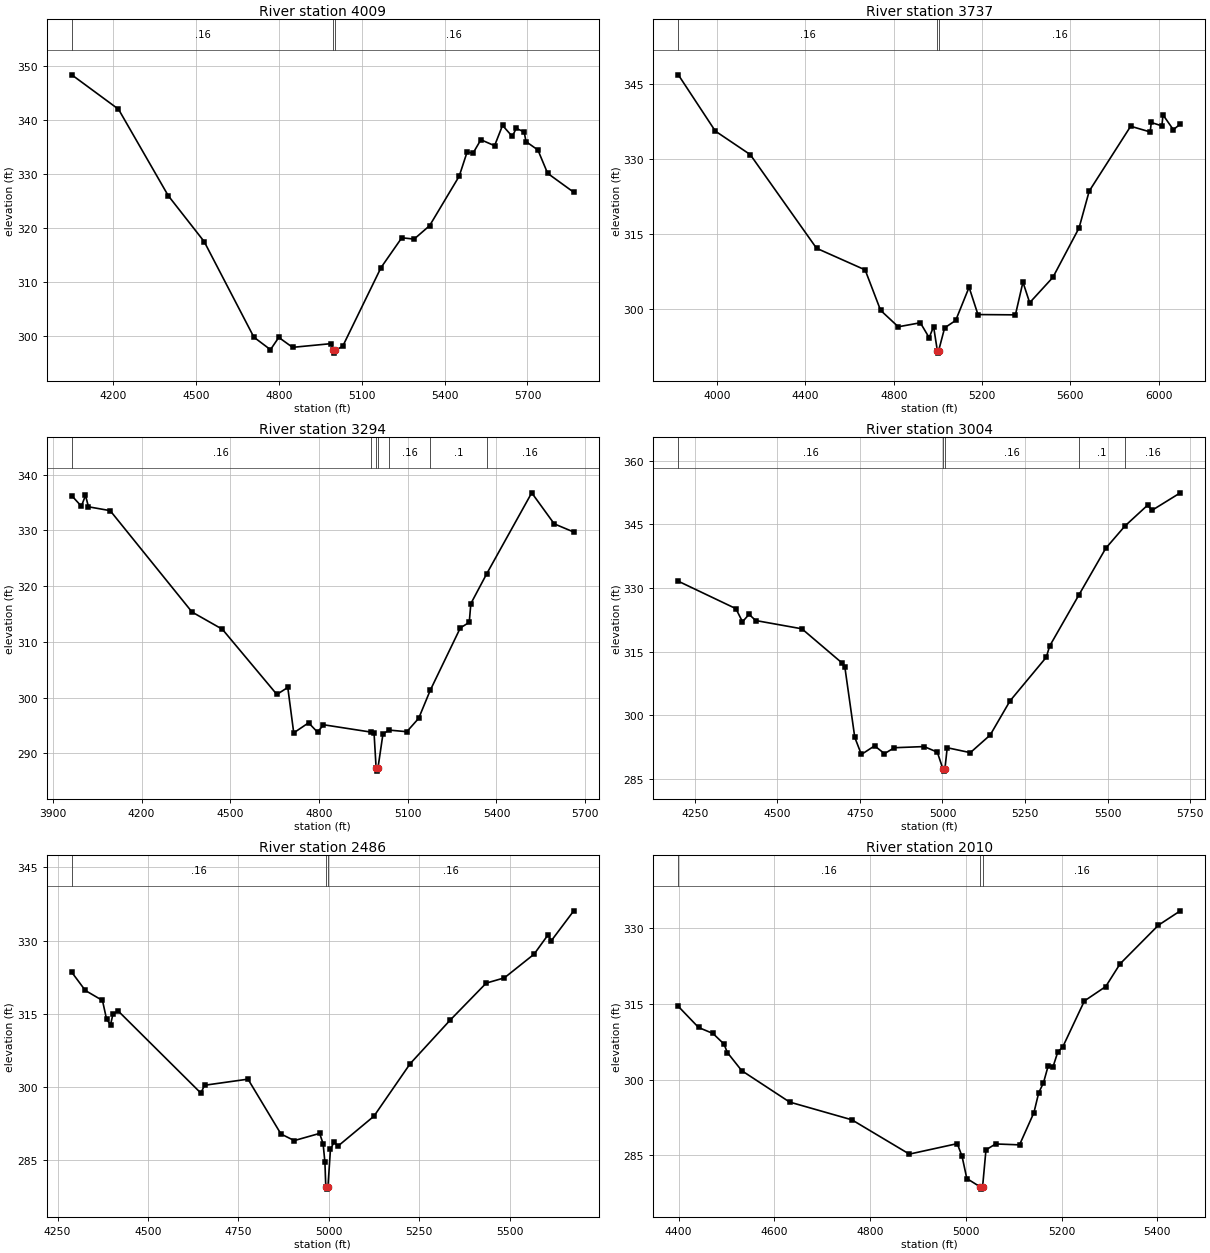
Type RM Length L Ch R = 1,4009,272,272,272
BEGIN DESCRIPTION:
UNT128 IN BECR 7.0
END DESCRIPTION:
XS GIS Cut Line= 3
      3797350.51     10511249.25      3798544.97     10511207.58
      3798933.85     10510721.48
#Sta/Elev= 30
  4049.8  348.44  4219.0  342.07  4399.1  326.06  4529.2  317.56  4709.3  299.85
  4769.3  297.54  4799.4  299.81  4849.4  297.97  4989.5  298.66  4996.5  297.40
  4999.2  296.90  5002.5  297.40  5030.6  298.14  5169.6  312.74  5244.8  318.26
  5289.5  318.02  5345.5  320.50  5452.7  329.67  5481.5  334.17  5502.4  333.90
  5531.2  336.42  5580.8  335.31  5609.6  339.08  5644.8  337.03  5659.2  338.52
  5688.0  337.87  5694.5  336.08  5737.7  334.52  5772.9  330.20  5867.5  326.69
#Mann=3,-1,0
  4049.8    0.16       0  4996.5    0.07       0  5002.5    0.16       0
Bank Sta=4996.5,5002.5
Exp/Cntr=0.3,0.1

Type RM Length L Ch R = 1,3737,443,443,443
BEGIN DESCRIPTION:
Mapping XS 3571e828
END DESCRIPTION:
XS GIS Cut Line= 3
      3797183.89     10511429.80      3798454.69     10511471.47
      3799440.82     10511290.91
#Sta/Elev= 30
  3824.0  346.90  3991.6  335.64  4149.9  330.93  4450.1  312.19  4670.2  307.86
  4740.2  299.77  4820.3  296.47  4920.3  297.28  4960.3  294.29  4980.3  296.51
  4997.3  291.70  5000.1  291.20  5003.3  291.70  5030.4  296.26  5080.4  297.74
  5141.1  304.38  5181.3  298.92  5351.0  298.86  5385.1  305.41  5415.6  301.29
  5520.7  306.36  5639.3  316.26  5685.3  323.63  5873.1  336.61  5961.4  335.47
  5966.5  337.36  6014.5  336.68  6019.6  338.89  6066.3  335.92  6098.0  337.04
#Mann=3,-1,0
  3824.0    0.16       0  4997.3    0.07       0  5003.3    0.16       0
Bank Sta=4997.3,5003.3
Exp/Cntr=0.3,0.1

Type RM Length L Ch R = 1,3294,290,290,290
BEGIN DESCRIPTION:
UNT128 IN BECR 6.0
END DESCRIPTION:
XS GIS Cut Line= 2
      3797423.43     10511741.61      3799110.90     10511922.16
#Sta/Elev= 30
  3964.1  336.24  3996.6  334.35  4010.5  336.30  4020.6  334.25  4093.9  333.56
  4370.7  315.35  4473.2  312.26  4657.5  300.55  4694.4  301.81  4714.5  293.65
  4764.8  295.46  4795.0  293.77  4815.1  295.11  4975.4  293.79  4986.1  293.58
  4993.1  287.28  4995.9  286.78  4999.1  287.28  5016.2  293.46  5036.9  294.15
  5096.7  293.86  5136.9  296.26  5175.9  301.28  5277.7  312.50  5307.9  313.50
  5313.3  316.86  5366.6  322.19  5519.1  336.76  5595.1  331.19  5661.2  329.72
#Mann=7,-1,0
  3964.1    0.16       0  4975.4    0.12       0  4993.1    0.07       0
  4999.1    0.12       0  5036.9    0.16       0  5175.9     0.1       0
  5366.6    0.16       0
Bank Sta=4993.1,4999.1
Exp/Cntr=0.3,0.1

Type RM Length L Ch R = 1,3004,518,518,518
BEGIN DESCRIPTION:
UNT128 IN BECR 5.0
END DESCRIPTION:
XS GIS Cut Line= 2
      3797555.39     10512102.72      3799075.39     10512137.42
#Sta/Elev= 30
  4200.0  331.59  4374.3  325.14  4394.3  322.05  4414.3  323.80  4434.3  322.34
  4574.3  320.39  4694.3  312.45  4704.3  311.43  4734.4  294.84  4754.4  290.81
  4794.4  292.84  4824.4  291.01  4854.4  292.40  4944.4  292.67  4984.4  291.36
  5001.4  287.39  5004.2  286.89  5007.4  287.39  5014.4  292.40  5084.4  291.24
  5144.5  295.38  5204.5  303.41  5314.5  313.70  5324.5  316.31  5413.0  328.33
  5494.6  339.35  5552.6  344.58  5621.1  349.48  5634.6  348.28  5720.4  352.40
#Mann=5,-1,0
  4200.0    0.16       0  5001.4    0.07       0  5007.4    0.16       0
  5413.0     0.1       0  5552.6    0.16       0
Bank Sta=5001.4,5007.4
Exp/Cntr=0.3,0.1

Type RM Length L Ch R = 1,2486,476,476,476
BEGIN DESCRIPTION:
UNT128 IN BECR 4.0
END DESCRIPTION:
XS GIS Cut Line= 3
      3797610.92     10512290.21      3798152.61     10512519.39
      3798951.25     10512561.05
#Sta/Elev= 30
  4289.4  323.53  4326.9  319.80  4374.3  317.75  4385.7  313.90  4396.6  312.79
  4403.4  314.99  4418.3  315.56  4646.3  298.79  4656.6  300.39  4776.6  301.64
  4867.8  290.41  4904.6  289.06  4974.7  290.53  4984.3  288.42  4989.3  284.63
  4991.7  279.62  4994.5  279.12  4997.7  279.62  5004.7  287.32  5014.8  288.78
  5024.8  287.89  5124.9  294.06  5225.0  304.81  5335.2  313.70  5435.3  321.31
  5485.4  322.38  5567.6  327.23  5605.6  331.13  5615.6  330.02  5677.3  336.11
#Mann=3,-1,0
  4289.4    0.16       0  4991.7    0.07       0  4997.7    0.16       0
Bank Sta=4991.7,4997.7
Exp/Cntr=0.3,0.1

Type RM Length L Ch R = 1,2010,567,567,567
BEGIN DESCRIPTION:
UNT128 IN BECR 3.0
END DESCRIPTION:
XS GIS Cut Line= 2
      3797687.28     10512852.72      3798735.32     10512880.48
#Sta/Elev= 30
  4399.6  314.47  4441.9  310.30  4471.9  309.12  4494.9  307.03  4502.0  305.35
  4532.0  301.77  4632.0  295.56  4762.1  292.05  4882.1  285.27  4982.1  287.34
  4992.1  284.86  5002.1  280.45  5029.1  278.85  5031.9  278.35  5035.1  278.85
  5042.1  286.11  5062.2  287.28  5112.2  287.10  5142.2  293.46  5152.2  297.37
  5162.2  299.38  5172.2  302.76  5182.2  302.54  5192.2  305.49  5202.2  306.40
  5247.7  315.55  5292.2  318.39  5322.2  322.88  5402.3  330.52  5448.0  333.36
#Mann=3,-1,0
  4399.6    0.16       0  5029.1    0.07       0  5035.1    0.16       0
Bank Sta=5029.1,5035.1
Exp/Cntr=0.3,0.1

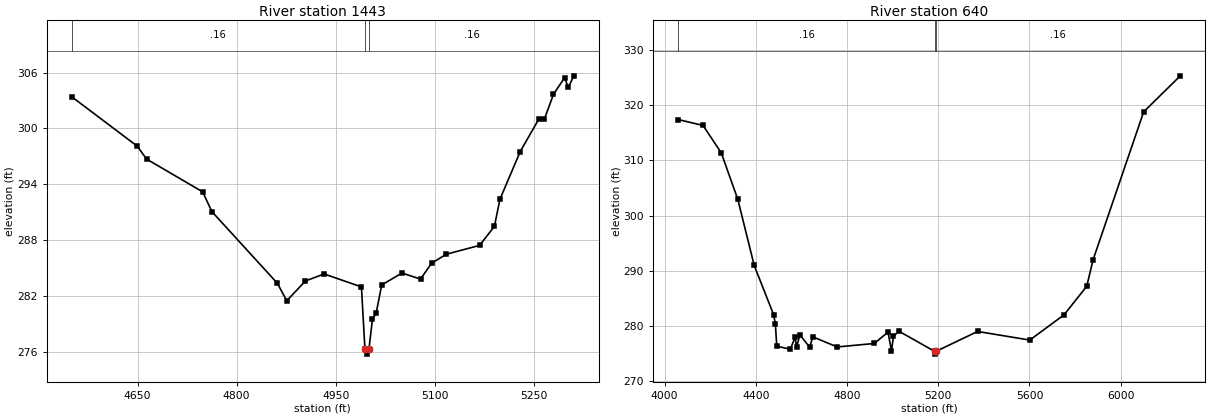
Type RM Length L Ch R = 1,1443,803,803,803
BEGIN DESCRIPTION:
UNT128 IN BECR 2.0
END DESCRIPTION:
XS GIS Cut Line= 3
      3797799.60     10512910.18      3798099.61     10513210.19
      3798399.62     10513360.19
#Sta/Elev= 30
  4550.5  303.40  4649.5  298.10  4663.7  296.71  4748.5  293.19  4762.6  291.06
  4861.6  283.37  4875.8  281.49  4904.1  283.62  4932.4  284.37  4988.8  282.98
  4994.1  276.26  4996.9  275.76  5000.1  276.26  5005.5  279.51  5011.1  280.18
  5019.5  283.19  5050.2  284.47  5078.2  283.82  5095.0  285.53  5117.3  286.49
  5167.6  287.44  5190.0  289.48  5198.4  292.40  5229.1  297.52  5257.1  300.99
  5265.5  300.98  5279.4  303.67  5296.2  305.45  5301.8  304.40  5310.2  305.65
#Mann=3,-1,0
  4550.5    0.16       0  4994.1    0.07       0  5000.1    0.16       0
Bank Sta=4994.1,5000.1
Exp/Cntr=0.3,0.1

Type RM Length L Ch R = 1,640,0,0,0
BEGIN DESCRIPTION:
UNT128 IN BECR 1.0
END DESCRIPTION:
XS GIS Cut Line= 4
      3797194.27     10513304.10      3797534.55     10513804.11
      3798020.67     10514005.50      3798874.73     10513359.74
#Sta/Elev= 30
  4059.9  317.41  4168.6  316.34  4248.7  311.36  4321.2  302.92  4393.0  290.96
  4478.5  281.98  4485.8  280.35  4491.9  276.31  4551.1  275.77  4572.6  277.90
  4578.6  276.17  4593.6  278.38  4635.8  276.14  4650.5  278.00  4756.8  276.17
  4919.1  276.80  4979.9  278.86  4994.9  275.47  5003.8  278.08  5027.4  279.03
  5184.2  275.37  5187.0  274.87  5190.2  275.37  5372.6  278.98  5601.5  277.42
  5751.3  281.98  5851.2  287.17  5879.1  291.98  6100.9  318.81  6261.6  325.34
#Mann=3,-1,0
  4059.9    0.16       0  5184.2    0.07       0  5190.2    0.16       0
Bank Sta=5184.2,5190.2
Exp/Cntr=0.3,0.1

Chan Stop Cuts=-1