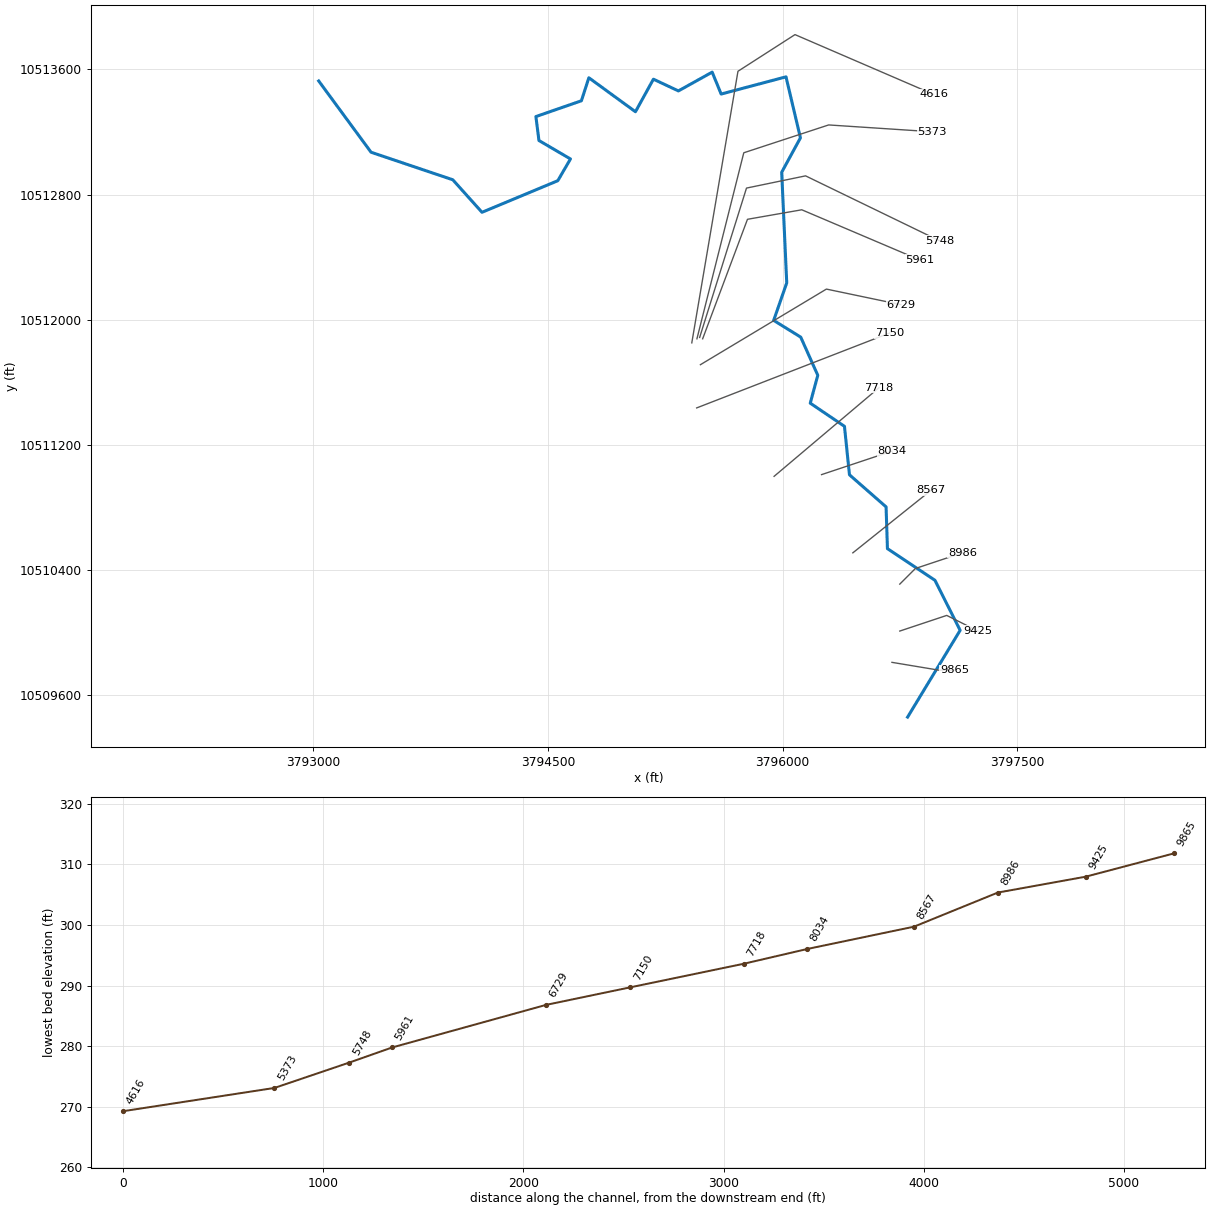
--- UNT132 IN BECR.prj (project) ---

Proj Title=UNT132 IN BECR Base Level Engineering
Current Plan=p01
Default Exp/Contr=0.3,0.1
English Units
Geom File=g01
Flow File=f01
Plan File=p01
Y Axis Title=Elevation
X Axis Title(PF)=Main Channel Distance
X Axis Title(XS)=Station
BEGIN DESCRIPTION:
UNT132 IN BECR
END DESCRIPTION:
DSS Export Rating Curves= 0
DSS Export Rating Curve Sorted= 0
DSS Export Volume Flow Curves= 0
DXF OffsetX= 0
DXF OffsetY= 0
DXF ScaleX= 1
DXF ScaleY= 10

--- UNT132 IN BECR.p01 (plan) ---

Plan Title=Multiple Run
Short Identifier=Multiple
Geom File=g01
Flow File=f01
Subcritical Flow
K Sum by GR= 0
Std Step Tol= 0.01
Critical Tol= 0.01
Num of Std Step Trials= 20
Max Error Tol= 0.3
Flow Tol Ratio= 0.001
Split Flow NTrial= 30
Split Flow Tol= 0.02
Split Flow Ratio= 0.02
Log Output Level= 0
Friction Slope Method= 1
Unsteady Friction Slope Method= 2
Unsteady Bridges Friction Slope Method= 1
Parabolic Critical Depth
Global Vel Dist=  1 , 1 , 1
Global Log Level= 0
CheckData=True
Encroach Param= -1, 0, 0, 0
BEGIN DESCRIPTION:
Multiple Run
END DESCRIPTION:

--- UNT132 IN BECR.f01 (steady flow) ---

Flow Title=Multiple
Number of Profiles=7
Profile Names=10-year,25-year,50-year,1pct_min,100-year,1pct_plu,500-year
River Rch & RM= UNT132 IN BECR,Reach-1,9865
     344     448     531     464     628     849     877
Boundary for River Rch & Prof#=UNT132 IN BECR,Reach-1,1
Up Type=0
Dn Type=3
Dn Slope=0.005
Boundary for River Rch & Prof#=UNT132 IN BECR,Reach-1,2
Up Type=0
Dn Type=3
Dn Slope=0.005
Boundary for River Rch & Prof#=UNT132 IN BECR,Reach-1,3
Up Type=0
Dn Type=3
Dn Slope=0.005
Boundary for River Rch & Prof#=UNT132 IN BECR,Reach-1,4
Up Type=0
Dn Type=3
Dn Slope=0.005
Boundary for River Rch & Prof#=UNT132 IN BECR,Reach-1,5
Up Type=0
Dn Type=3
Dn Slope=0.005
Boundary for River Rch & Prof#=UNT132 IN BECR,Reach-1,6
Up Type=0
Dn Type=3
Dn Slope=0.005
Boundary for River Rch & Prof#=UNT132 IN BECR,Reach-1,7
Up Type=0
Dn Type=3
Dn Slope=0.005

--- UNT132 IN BECR.g01 (geometry) ---

Geom Title=Existing Conditions
Program Version=4.10

River Reach=UNT132 IN BECR  ,Reach-1
Reach XY= 30
      3796799.61     10509460.19       3797135.5       10510015.
      3796974.25       10510335.      3796670.75       10510537.
        3796662.       10510804.        3796428.       10511009.
        3796396.       10511319.      3796177.25       10511467.
       3796225.5       10511645.       3796116.5       10511889.
       3795943.5       10511996.        3796027.       10512236.
      3795994.75       10512943.       3796114.5       10513163.
      3796022.25       10513553.      3795607.75       10513443.
      3795550.25       10513583.       3795334.5       10513463.
      3795174.75       10513538.        3795060.       10513330.
        3794762.       10513547.       3794714.5       10513400.
       3794423.5       10513299.        3794443.       10513146.
       3794644.5       10513028.       3794563.5       10512889.
        3794079.       10512687.      3793892.25       10512895.
      3793369.75       10513071.      3793035.12     10513526.55

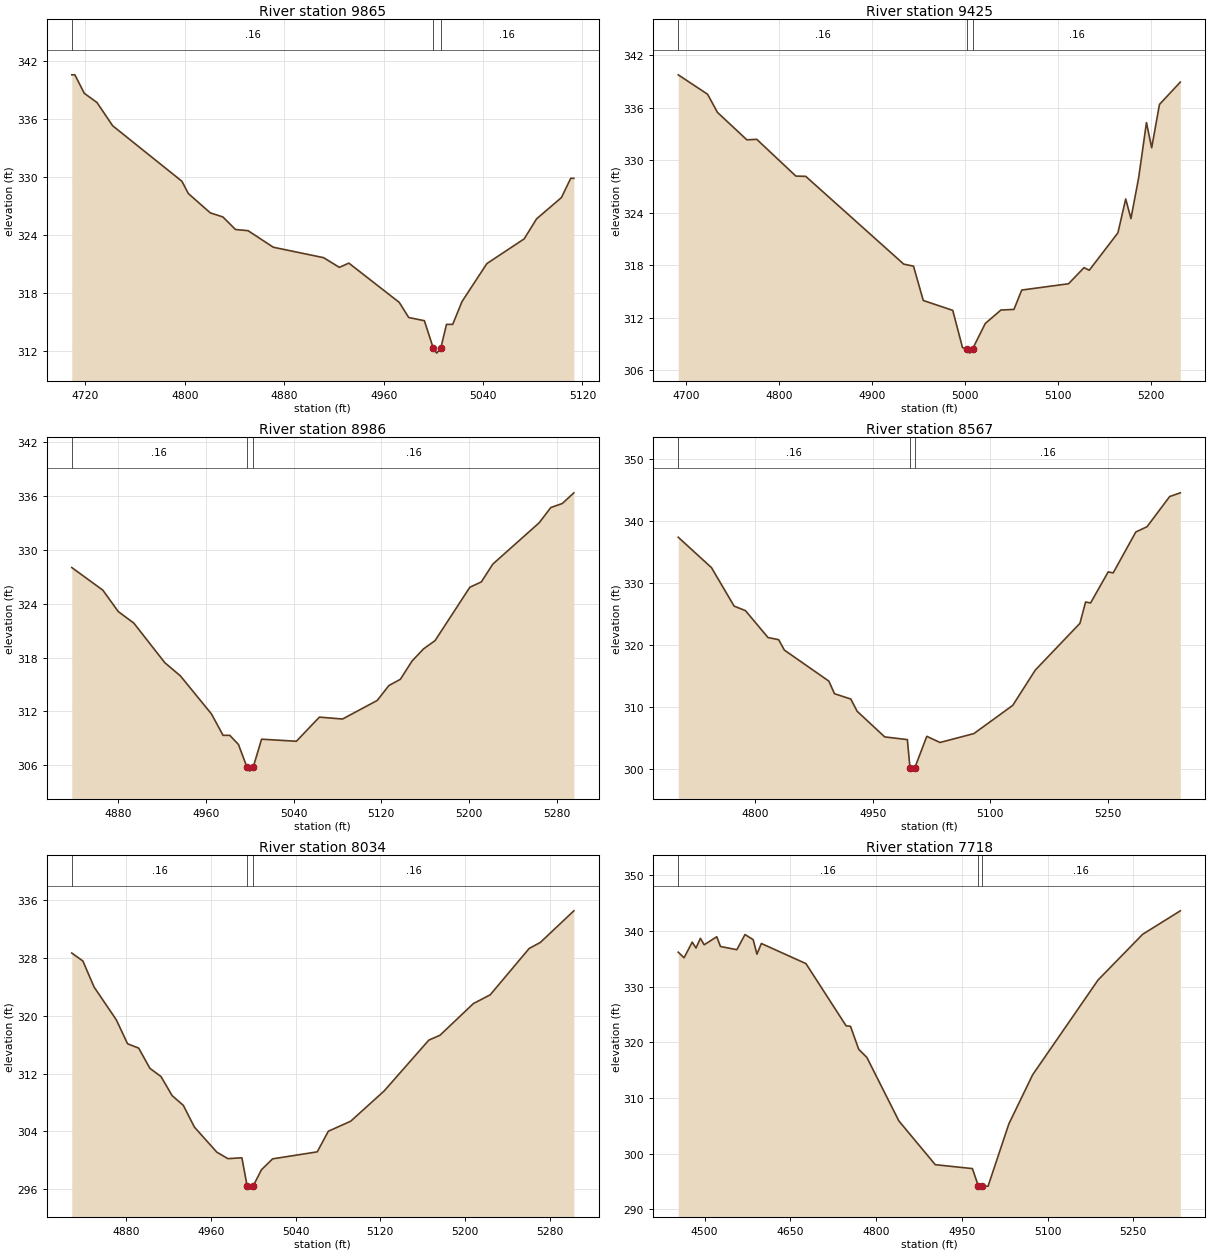
Type RM Length L Ch R = 1 ,9865    ,440,440,440
BEGIN DESCRIPTION:
UNT132 IN BECR 9.0
END DESCRIPTION:
XS GIS Cut Line= 3
      3796699.63     10509810.19      3796999.61     10509760.19
      3797099.59     10509760.19
#Sta/Elev= 30
    4709  340.56  4711.5  340.56  4719.1  338.65  4729.3   337.7  4741.9   335.3
  4797.7  329.56  4802.8   328.3  4820.5   326.3  4830.6  325.88  4840.8  324.58
  4850.9  324.46  4871.2  322.75  4911.7  321.67  4924.4  320.67    4932  321.11
  4972.6  317.05  4980.2  315.49  4992.8  315.16    5000  312.31  5002.7  311.81
    5006  312.31  5010.6  314.78  5015.6  314.78  5023.1  317.14  5043.1  321.06
  5073.1  323.61  5083.1  325.68  5103.1  327.88  5110.6  329.87  5113.1  329.87
#Mann= 3 ,-1 , 0
    4709     .16       0    5000     .07       0    5006     .16       0
Bank Sta=5000,5006
XS Rating Curve= 0 ,0
Exp/Cntr=0.3,0.1

Type RM Length L Ch R = 1 ,9425    ,439,439,439
BEGIN DESCRIPTION:
UNT132 IN BECR 8.0
END DESCRIPTION:
XS GIS Cut Line= 3
      3796749.59     10510010.18      3797049.61     10510110.19
      3797249.65     10510010.17
#Sta/Elev= 30
  4691.4  339.74    4723  337.52  4733.6  335.45  4765.2  332.32  4775.8  332.38
  4817.9  328.18  4828.5  328.15  4933.9  318.13  4944.4   317.9  4954.9  313.98
  4986.6  312.85  4997.1   308.6    5002  308.47  5004.8  307.97    5008  308.47
  5021.6  311.36  5038.4  312.89  5052.4  312.96  5060.8  315.17  5111.1  315.89
  5127.8  317.73  5133.4  317.43  5164.2   321.7  5172.6  325.57  5178.2  323.33
  5186.5  327.98  5194.9  334.29  5200.5  331.41  5208.9  336.36  5231.3  338.91
#Mann= 3 ,-1 , 0
  4691.4     .16       0    5002     .07       0    5008     .16       0
Bank Sta=5002,5008
XS Rating Curve= 0 ,0
Exp/Cntr=0.3,0.1

Type RM Length L Ch R = 1 ,8986    ,419,419,419
BEGIN DESCRIPTION:
UNT132 IN BECR 7.0
END DESCRIPTION:
XS GIS Cut Line= 3
      3796749.62      10510310.2      3796849.61     10510410.19
      3797149.58     10510510.18
#Sta/Elev= 30
  4837.9  328.05  4866.2  325.53  4880.3  323.14  4894.5  321.85  4922.7  317.44
  4936.9  315.97  4965.2  311.73  4975.8  309.34  4981.9  309.34  4989.8  308.33
  4997.4  305.85  5000.1  305.35  5003.4  305.85  5010.9  308.91  5042.6  308.68
  5063.6  311.37  5084.7  311.16  5116.3  313.23  5126.9  314.89  5137.4  315.59
    5148  317.62  5158.5  318.98    5169   319.9  5200.7  325.85  5211.2  326.45
  5221.7  328.44  5263.9  333.04  5274.5  334.74    5285  335.19  5295.5  336.38
#Mann= 3 ,-1 , 0
  4837.9     .16       0  4997.4     .07       0  5003.4     .16       0
Bank Sta=4997.4,5003.4
XS Rating Curve= 0 ,0
Exp/Cntr=0.3,0.1

Type RM Length L Ch R = 1 ,8567    ,533,533,533
BEGIN DESCRIPTION:
UNT132 IN BECR 6.0
END DESCRIPTION:
XS GIS Cut Line= 3
       3796449.6     10510510.18      3796699.61     10510710.19
      3796949.59     10510910.17
#Sta/Elev= 30
    4702  337.43  4744.4  332.53  4773.3  326.32  4787.7   325.6  4816.5  321.26
  4830.1  320.91  4837.3  319.24  4894.1  314.23  4901.3   312.2  4922.1  311.34
  4930.1  309.38  4965.3  305.24  4994.2   304.8  4997.6  300.22  5000.3  299.72
  5003.6  300.22    5019  305.33  5035.8  304.34    5079  305.77  5128.6  310.32
  5157.4  316.02  5214.3  323.55  5221.5  326.99  5227.9  326.84  5250.3  331.84
  5256.7  331.68  5285.5  338.27  5299.9  339.13  5328.7  343.99  5342.3  344.59
#Mann= 3 ,-1 , 0
    4702     .16       0  4997.6     .07       0  5003.6     .16       0
Bank Sta=4997.6,5003.6
XS Rating Curve= 0 ,0
Exp/Cntr=0.3,0.1

Type RM Length L Ch R = 1 ,8034    ,316,316,316
BEGIN DESCRIPTION:
UNT132 IN BECR 5.0
END DESCRIPTION:
XS GIS Cut Line= 3
      3796249.64      10511010.2      3796399.61     10511060.19
       3796699.6     10511160.18
#Sta/Elev= 30
  4828.6  328.65  4839.1  327.55  4849.7  323.95  4870.7  319.42  4881.3  316.12
  4891.8  315.52  4902.4  312.73  4912.9  311.59  4923.4  308.96    4934  307.61
  4944.5   304.6  4965.6  301.15  4976.1  300.25  4989.3  300.37  4994.2  296.54
    4997  296.04  5000.2  296.54  5007.8  298.72  5018.3  300.22  5060.5  301.19
    5071  304.04  5092.1  305.42  5123.7   309.6  5165.9  316.62  5176.4  317.29
    5208  321.67  5223.9  322.88  5260.7  329.28  5271.3  330.12  5302.9  334.48
#Mann= 3 ,-1 , 0
  4828.6     .16       0  4994.2     .07       0  5000.2     .16       0
Bank Sta=4994.2,5000.2
XS Rating Curve= 0 ,0
Exp/Cntr=0.3,0.1

Type RM Length L Ch R = 1 ,7718    ,568,568,568
BEGIN DESCRIPTION:
UNT132 IN BECR 4.0
END DESCRIPTION:
XS GIS Cut Line= 2
      3795946.14     10510999.15      3796617.02     10511566.02
#Sta/Elev= 30
    4454  336.18  4464.2  335.18  4478.5  337.99  4485.1  336.93  4492.8  338.67
  4499.4  337.51  4521.4  338.95  4527.9   337.2  4556.5  336.63  4570.8  339.35
  4585.1  338.43  4591.7  335.82  4599.4  337.74  4677.4  334.13  4747.7  322.95
  4755.4  322.86  4769.7  318.74    4784  317.27    4840  305.86  4903.7     298
  4968.6   297.3  4979.2  294.11    4982  293.61  4985.2  294.11    4996  294.14
  5032.3  305.31    5074  314.16  5188.4  331.18  5266.4  339.39  5332.3  343.61
#Mann= 3 ,-1 , 0
    4454     .16       0  4979.2     .07       0  4985.2     .16       0
Bank Sta=4979.2,4985.2
XS Rating Curve= 0 ,0
Exp/Cntr=0.3,0.1

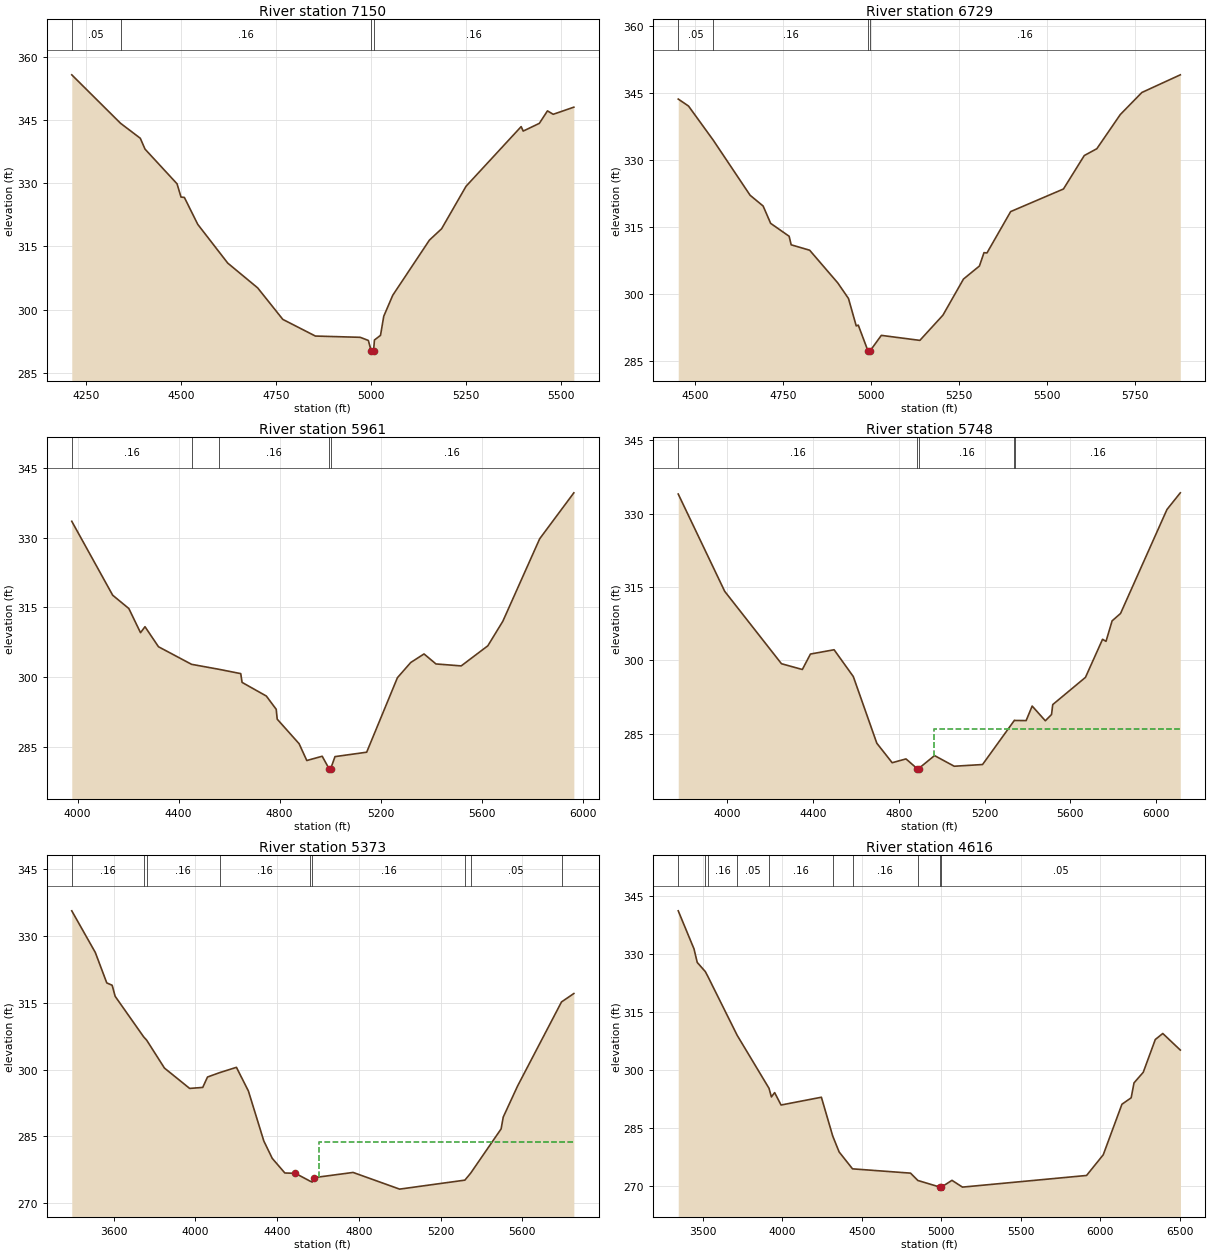
Type RM Length L Ch R = 1 ,7150    ,421,421,421
BEGIN DESCRIPTION:
UNT132 IN BECR 3.0
END DESCRIPTION:
XS GIS Cut Line= 2
       3795451.3     10511436.63      3796684.36     10511915.28
#Sta/Elev= 30
  4212.4  355.71  4340.9  344.22  4392.9  340.67  4405.4  338.09  4489.8  329.86
  4500.2  326.72    4509  326.64  4544.3  320.25  4623.3  311.06  4702.2  305.18
  4768.4  297.71  4854.2  293.76  4972.2  293.46  4993.7  292.72  5001.4  290.21
  5004.1  289.71  5007.4  290.21  5009.8  292.82  5025.8  293.93  5034.3  298.45
    5058  303.43  5154.6  316.51  5186.7   319.2  5251.1  329.28  5396.3  343.43
  5401.7  342.37  5444.2   344.2  5465.6  347.16  5480.7  346.35  5535.1  348.04
#Mann= 4 ,-1 , 0
  4212.4     .05       0  4340.9     .16       0  5001.4     .07       0
  5007.4     .16       0
Bank Sta=5001.4,5007.4
XS Rating Curve= 0 ,0
Exp/Cntr=0.3,0.1

Type RM Length L Ch R = 1 ,6729    ,768,768,768
BEGIN DESCRIPTION:
UNT132 IN BECR 2.0
END DESCRIPTION:
XS GIS Cut Line= 3
      3795475.11     10511712.88      3796280.66     10512196.21
      3796756.53     10512096.61
#Sta/Elev= 30
  4452.7  343.62  4481.9  342.06  4552.1  334.43  4656.8  322.11  4693.7  319.71
  4715.1  315.83  4767.6  312.94  4773.4  311.03  4825.9  309.82  4905.6  302.52
  4936.1  299.03  4958.1   292.9  4963.9  293.07  4991.4  287.31  4994.1  286.81
  4997.4  287.31  5029.4  290.78  5138.8  289.66  5204.3   295.3  5262.6  303.37
  5307.9  306.29  5320.9  309.28  5329.3  309.21  5396.6  318.46  5546.5  323.51
  5605.6  330.99  5641.3  332.52  5707.8  340.15  5769.1  345.09  5878.3  349.04
#Mann= 4 ,-1 , 0
  4452.7     .05       0  4552.1     .16       0  4991.4     .07       0
  4997.4     .16       0
Bank Sta=4991.4,4997.4
XS Rating Curve= 0 ,0
Exp/Cntr=0.3,0.1

Type RM Length L Ch R = 1 ,5961    ,213,213,213
BEGIN DESCRIPTION:
Mapping XS fa71c3de
END DESCRIPTION:
XS GIS Cut Line= 4
      3795489.54     10511878.52      3795775.98     10512642.37
       3796123.2     10512703.13      3796878.45     10512381.93
#Sta/Elev= 30
  3976.7  333.52  4138.8  317.62  4202.8  314.76  4249.1  309.56  4266.8  310.85
  4320.2  306.54  4451.2  302.76  4558.7   301.7  4646.1  300.76  4651.4  298.87
  4747.4  295.94  4786.7  293.08  4790.5  290.97  4877.4  285.68  4907.8  282.07
  4968.8  282.99  4996.2  280.29    4999  279.79  5002.2  280.29  5019.5  282.91
    5145  283.86  5266.8  299.88  5319.5  303.15  5372.2  304.99  5419.5  302.84
  5519.5  302.42  5624.9  306.74  5684.4  312.02  5830.4  329.76  5965.7  339.64
#Mann= 5 ,-1 , 0
  3976.7     .16       0  4451.2     .05       0  4558.7     .16       0
  4996.2     .07       0  5002.2     .16       0
Bank Sta=4996.2,5002.2
XS Rating Curve= 0 ,0
Exp/Cntr=0.3,0.1

Type RM Length L Ch R = 1 ,5748    ,375,375,375
BEGIN DESCRIPTION:
Mapping XS bb7843a7
END DESCRIPTION:
XS GIS Cut Line= 4
      3795470.28     10511887.03      3795769.75     10512841.88
      3796147.36     10512920.01      3797005.67     10512503.86
#Sta/Elev= 30
  3772.4  333.99    3989  314.09  4253.6  299.28  4350.9   298.1  4388.6  301.26
  4498.9  302.14  4588.4  296.66    4698  283.02  4769.6  279.03    4834  279.81
  4886.3  277.81    4889  277.31  4892.3  277.81    4967  280.49  5058.9  278.31
  5190.8  278.66  5339.6  287.72  5343.8  287.67    5394  287.65  5422.1  290.62
  5483.5  287.61  5512.4  288.89    5518  290.92  5670.5  296.49  5750.2  304.28
  5766.3  303.86  5794.7  308.05    5834  309.56  6050.3  330.82  6112.6  334.24
#Mann= 5 ,-1 , 0
  3772.4     .16       0  4886.3     .07       0  4892.3     .16       0
  5339.6     .05       0  5343.8     .16       0
#XS Ineff= 2 , 0
                         4965.91          286.03
Permanent Ineff=
       F       F
Bank Sta=4886.3,4892.3
XS Rating Curve= 0 ,0
Exp/Cntr=0.3,0.1

Type RM Length L Ch R = 1 ,5373    ,757,757,757
BEGIN DESCRIPTION:
Mapping XS 73274d9c
END DESCRIPTION:
XS GIS Cut Line= 4
      3795452.91     10511878.34      3795752.39     10513067.58
      3796294.93     10513245.53      3796954.66     10513202.13
#Sta/Elev= 30
  3394.3  335.67  3509.6  326.31  3565.7  319.47  3592.1  318.94  3606.8  316.45
  3746.8  307.31  3760.9  306.61  3848.2  300.32  3971.5  295.75  4035.6  295.97
  4058.9  298.31  4118.1  299.29  4200.6  300.49  4259.2  295.17  4334.6  283.95
  4375.9  280.03  4437.7  276.74  4489.3  276.66  4561.5   274.9  4571.8   274.7
  4582.1   275.7  4771.9  276.86  4999.7  273.11  5319.2  275.13  5347.4  276.69
  5496.7  286.65    5507   289.3  5577.2  296.28  5792.4  315.19  5852.8  317.08
#Mann= 9 ,-1 , 0
  3394.3     .16       0  3746.8     .05       0  3760.9     .16       0
  4118.1     .16       0  4561.5     .07       0  4571.8     .16       0
  5319.2     .16       0  5347.4     .05       0  5792.4     .16       0
#XS Ineff= 2 , 0
                         4603.98          283.75
Permanent Ineff=
       F       F
Bank Sta=4489.3,4582.1
XS Rating Curve= 0 ,0
Exp/Cntr=0.3,0.1

Type RM Length L Ch R = 1 ,4616    ,0,0,0
BEGIN DESCRIPTION:
UNT132 IN BECR 1.0
END DESCRIPTION:
XS GIS Cut Line= 4
      3795420.07      10511852.4      3795715.22     10513588.55
       3796079.8     10513822.92      3796964.88     10513441.12
#Sta/Elev= 30
  3344.4  341.17  3443.6  331.34  3463.9  327.84  3514.9  325.46  3529.9  324.29
  3715.3     309  3915.6  295.31  3930.5  293.09  3950.8  294.21  3991.3     291
  4244.9  293.01  4316.3  282.98  4356.5  278.88  4440.8  274.51  4805.7   273.4
  4851.6  271.51  4992.5  269.77  4995.3  269.27  4998.5  269.77  5066.5  271.54
  5132.4  269.79  5913.1   272.8  6018.1  278.15  6135.6   291.2  6193.6  292.86
  6211.6  296.72  6269.6  299.45  6345.5  307.93  6392.6  309.48  6502.8   305.2
#Mann= 10 ,-1 , 0
  3344.4     .16       0  3514.9     .05       0  3529.9     .16       0
  3715.3     .05       0  3915.6     .16       0  4316.3      .1       0
  4440.8     .16       0  4851.6     .05       0  4992.5     .03       0
  4998.5     .05       0
Bank Sta=4992.5,4998.5
XS Rating Curve= 0 ,0
Exp/Cntr=0.3,0.1

Chan Stop Cuts=-1
Use User Specified Reach Order=0
Composite Channel Slope=5