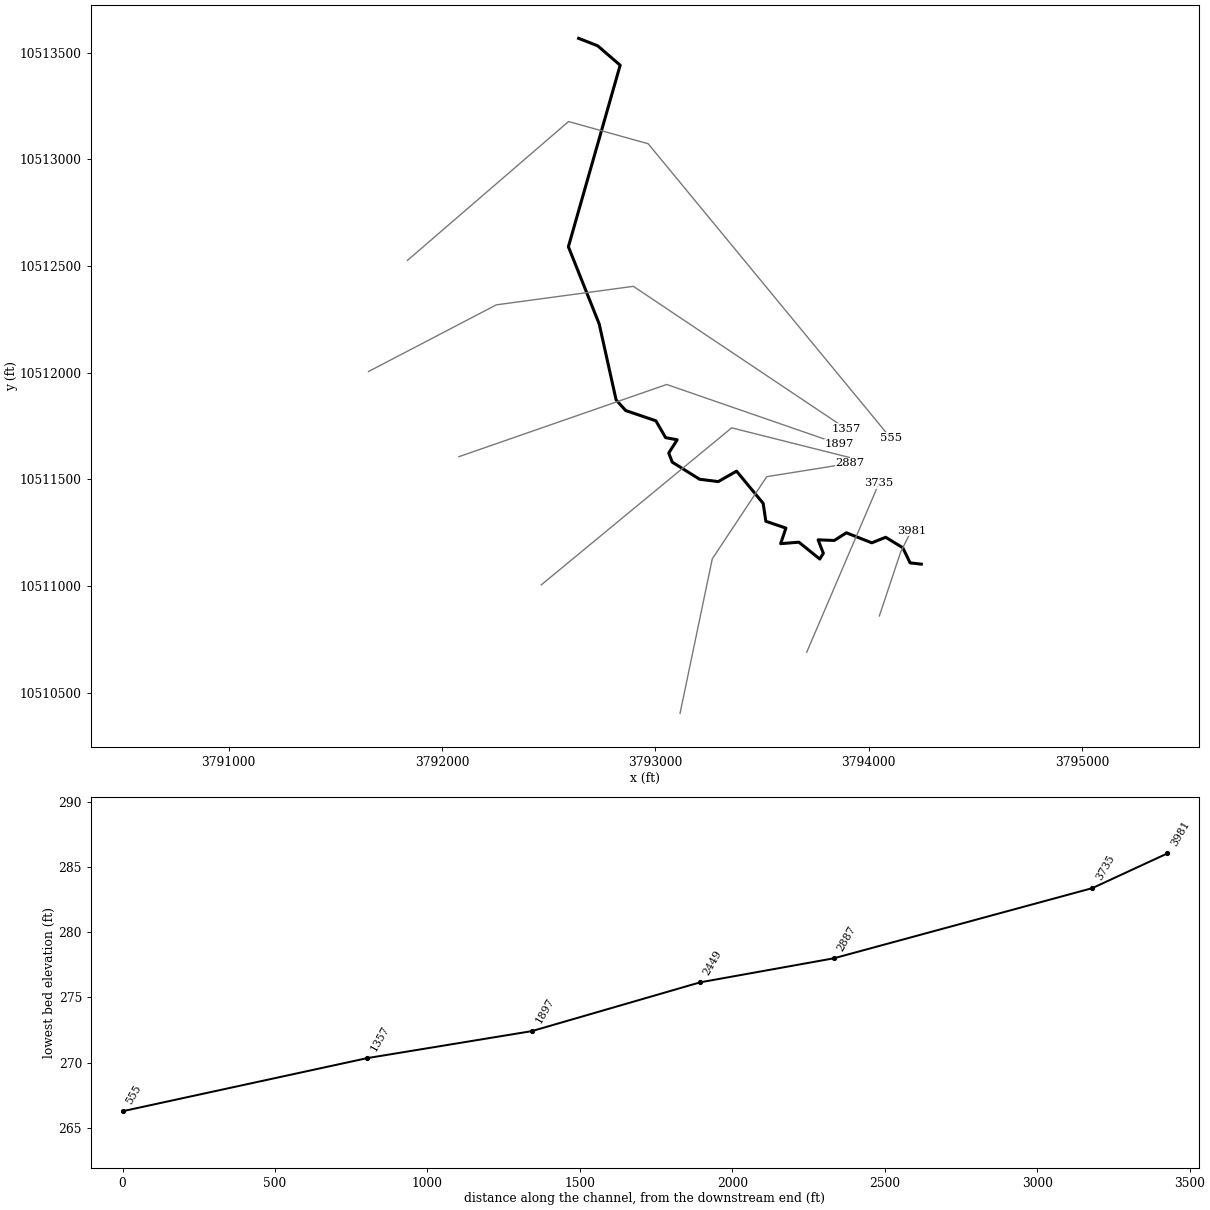
--- UNT133 IN BECR.prj (project) ---

Proj Title=UNT133 IN BECR Base Level Engineering
Current Plan=p01
Default Exp/Contr=0.3,0.1
English Units
Geom File=g01
Flow File=f01
Plan File=p01
Y Axis Title=Elevation
X Axis Title(PF)=Main Channel Distance
X Axis Title(XS)=Station
BEGIN DESCRIPTION:
UNT133 IN BECR
END DESCRIPTION:
DSS Export Rating Curves= 0
DSS Export Rating Curve Sorted= 0
DSS Export Volume Flow Curves= 0
DXF OffsetX= 0
DXF OffsetY= 0
DXF ScaleX= 1
DXF ScaleY= 10

--- UNT133 IN BECR.p01 (plan) ---

Plan Title=Multiple Run
Short Identifier=Multiple
Geom File=g01
Flow File=f01
Subcritical Flow
K Sum by GR= 0
Std Step Tol= 0.01
Critical Tol= 0.01
Num of Std Step Trials= 20
Max Error Tol= 0.3
Flow Tol Ratio= 0.001
Split Flow NTrial= 30
Split Flow Tol= 0.02
Split Flow Ratio= 0.02
Log Output Level= 0
Friction Slope Method= 1
Unsteady Friction Slope Method= 2
Unsteady Bridges Friction Slope Method= 1
Parabolic Critical Depth
Global Vel Dist=  1 , 1 , 1
Global Log Level= 0
CheckData=True
Encroach Param= -1, 0, 0, 0
BEGIN DESCRIPTION:
Multiple Run
END DESCRIPTION:

--- UNT133 IN BECR.f01 (steady flow) ---

Flow Title=Multiple
Number of Profiles=7
Profile Names=10-year,25-year,50-year,1pct_min,100-year,1pct_plu,500-year
River Rch & RM= UNT133 IN BECR,Reach-1,3981
     365     478     569     499     675     913     952
Boundary for River Rch & Prof#=UNT133 IN BECR,Reach-1,1
Up Type=0
Dn Type=3
Dn Slope=0.005
Boundary for River Rch & Prof#=UNT133 IN BECR,Reach-1,2
Up Type=0
Dn Type=3
Dn Slope=0.005
Boundary for River Rch & Prof#=UNT133 IN BECR,Reach-1,3
Up Type=0
Dn Type=3
Dn Slope=0.005
Boundary for River Rch & Prof#=UNT133 IN BECR,Reach-1,4
Up Type=0
Dn Type=3
Dn Slope=0.005
Boundary for River Rch & Prof#=UNT133 IN BECR,Reach-1,5
Up Type=0
Dn Type=3
Dn Slope=0.005
Boundary for River Rch & Prof#=UNT133 IN BECR,Reach-1,6
Up Type=0
Dn Type=3
Dn Slope=0.005
Boundary for River Rch & Prof#=UNT133 IN BECR,Reach-1,7
Up Type=0
Dn Type=3
Dn Slope=0.005

--- UNT133 IN BECR.g01 (geometry) ---

Geom Title=Existing Conditions
Program Version=4.10

River Reach=UNT133 IN BECR  ,Reach-1
Reach XY= 30
      3794246.25       10511103.      3794193.75       10511109.
       3794159.5       10511180.      3794079.25       10511229.
      3794014.25       10511203.        3793895.       10511250.
      3793838.25       10511214.       3793762.5       10511217.
        3793787.       10511154.      3793770.25       10511127.
       3793672.5       10511206.        3793587.       10511199.
       3793611.5       10511272.       3793517.5       10511304.
        3793505.       10511388.      3793380.25       10511539.
       3793294.5       10511490.        3793207.       10511501.
        3793079.       10511581.       3793062.5       10511624.
        3793102.       10511686.      3793047.75       10511696.
      3793002.25       10511775.      3792860.75       10511823.
      3792815.75       10511873.       3792736.5       10512229.
        3792592.       10512591.      3792834.75       10513442.
      3792729.25       10513533.        3792640.       10513568.

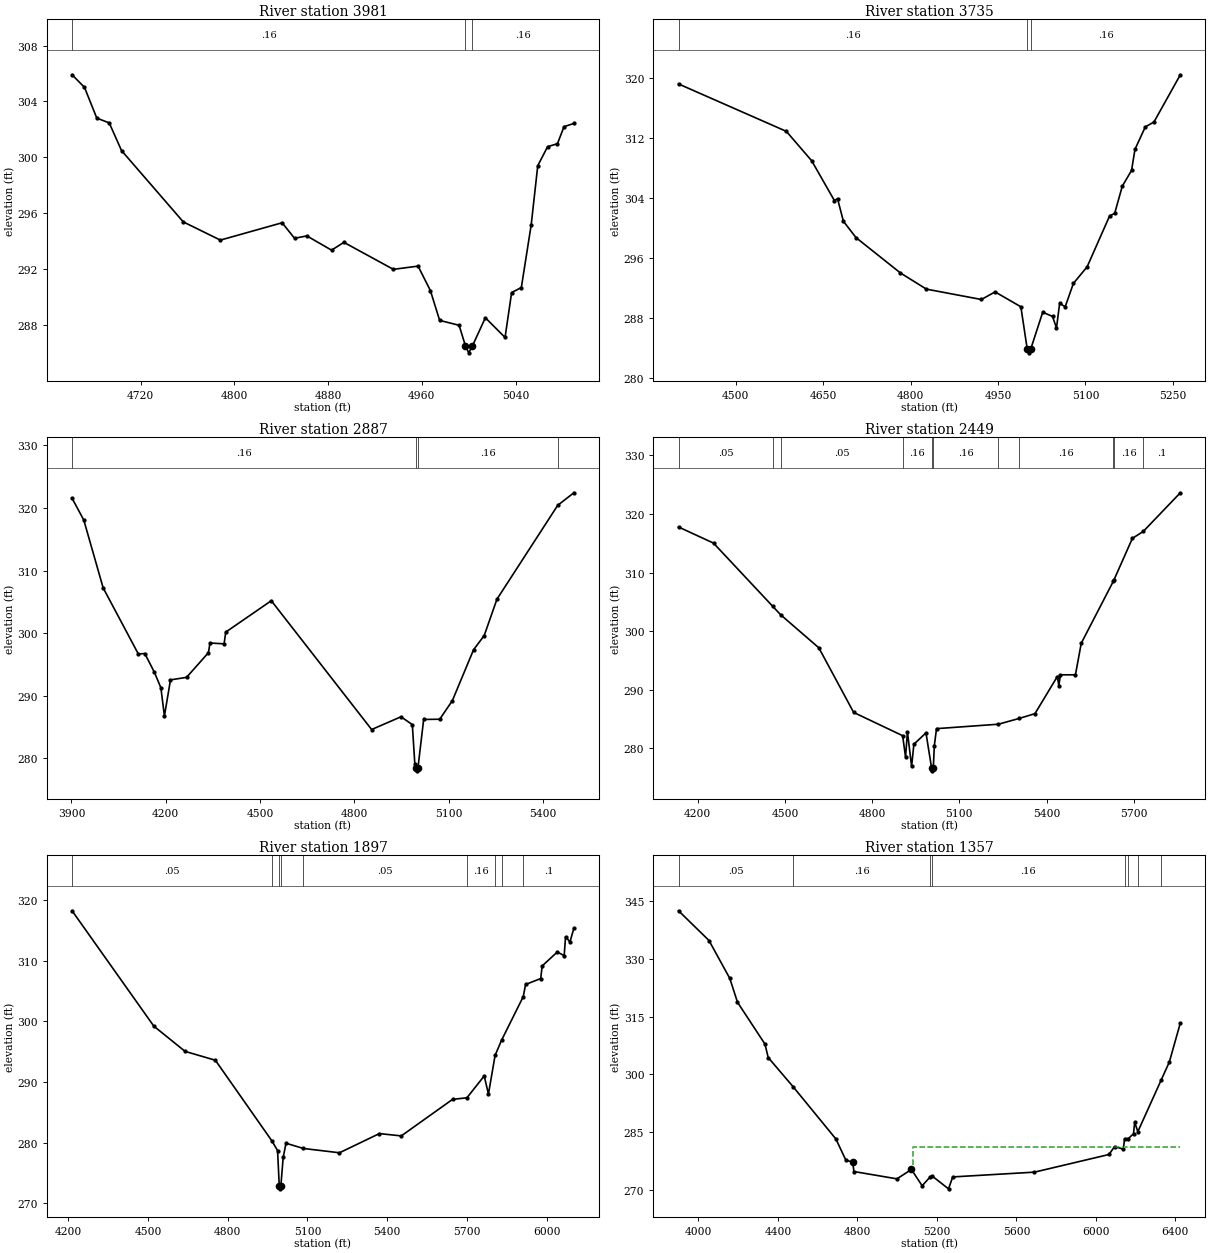
Type RM Length L Ch R = 1 ,3981    ,246,246,246
BEGIN DESCRIPTION:
UNT133 IN BECR 5.0
END DESCRIPTION:
XS GIS Cut Line= 3
       3794049.6     10510860.16      3794149.61     10511160.19
      3794199.62     10511260.22
#Sta/Elev= 30
  4661.6  305.91  4672.2  305.01  4682.7  302.81  4693.3  302.47  4703.8  300.49
  4756.5  295.39  4788.1  294.09  4840.8  295.33  4851.4  294.22  4861.9  294.39
    4883  293.37  4893.5  293.93  4935.7     292  4956.8  292.23  4967.3  290.48
  4975.2  288.35  4991.8     288  4997.2  286.53    5000  286.03  5003.2  286.53
  5014.2  288.54    5031  287.13  5036.6  290.34  5044.9   290.7  5053.3  295.18
  5058.9  299.41  5067.3  300.77  5075.7  300.98  5081.3   302.2  5089.7  302.43
#Mann= 3 ,-1 , 0
  4661.6     .16       0  4997.2     .07       0  5003.2     .16       0
Bank Sta=4997.2,5003.2
XS Rating Curve= 0 ,0
Exp/Cntr=0.3,0.1

Type RM Length L Ch R = 1 ,3735    ,848,848,848
BEGIN DESCRIPTION:
UNT133 IN BECR 4.0
END DESCRIPTION:
XS GIS Cut Line= 2
      3793709.14      10510690.1      3794047.67     10511481.75
#Sta/Elev= 30
  4401.9  319.16  4586.9  312.85  4630.4  308.93  4669.3  303.64  4674.7  303.89
  4684.8  300.88  4706.5   298.7  4782.7     294  4827.2  291.85  4921.5  290.47
  4945.1  291.48  4989.3   289.5  5000.2  283.87  5002.9  283.37  5006.2  283.87
  5026.8  288.78  5043.7  288.21  5050.4  286.67  5055.8  289.94  5065.4  289.51
  5079.4  292.61    5103  294.82  5141.6   301.6  5150.2  301.92  5163.3  305.55
  5179.2  307.65  5185.1  310.46  5202.8  313.44  5217.7   314.1  5262.9  320.38
#Mann= 3 ,-1 , 0
  4401.9     .16       0  5000.2     .07       0  5006.2     .16       0
Bank Sta=5000.2,5006.2
XS Rating Curve= 0 ,0
Exp/Cntr=0.3,0.1

Type RM Length L Ch R = 1 ,2887    ,438,438,438
BEGIN DESCRIPTION:
UNT133 IN BECR 3.0
END DESCRIPTION:
XS GIS Cut Line= 4
       3793115.4     10510403.69      3793266.43     10511127.61
      3793521.64     10511513.03      3793911.23     10511575.36
#Sta/Elev= 30
  3901.9  321.56  3939.2  318.07  4000.8  307.23  4112.8  296.66  4133.3  296.74
  4163.9  293.73  4184.4  291.27  4195.7  286.76    4215  292.53  4266.1  292.93
  4335.6  296.87  4340.7  298.42  4385.6  298.29  4390.7  300.16  4535.7  305.18
  4854.9  284.59  4948.2  286.63  4984.3  285.38  4992.3   279.1  4996.3  278.49
  4999.1  277.99  5002.3  278.49  5020.4   286.2  5071.5  286.24  5111.7  289.21
  5179.1  297.34    5213  299.61  5253.5  305.42  5446.8  320.42  5498.2  322.43
#Mann= 4 ,-1 , 0
  3901.9     .16       0  4996.3     .07       0  5002.3     .16       0
  5446.8      .1       0
Bank Sta=4996.3,5002.3
XS Rating Curve= 0 ,0
Exp/Cntr=0.3,0.1

Type RM Length L Ch R = 1 ,2449    ,552,552,552
BEGIN DESCRIPTION:
Mapping XS 247921c1
END DESCRIPTION:
XS GIS Cut Line= 3
      3792465.03     10511005.92      3793357.39     10511742.04
      3793909.49     10511603.15
#Sta/Elev= 30
  4134.1  317.77  4254.4  315.02  4457.5  304.26    4486  302.76  4616.7  297.15
  4736.5  286.12    4905  282.15    4915   278.5  4921.5  282.79  4935.8   276.9
  4943.7  280.69  4985.3  282.63  5004.5  276.65  5007.3  276.15  5010.5  276.65
    5014  280.44  5021.5  283.35  5234.6  284.11  5306.9  285.11  5360.1  285.91
  5437.2  292.25  5442.3  290.68  5447.9  292.54  5499.4  292.54  5519.4  297.93
  5629.7   308.5  5632.2  308.77  5695.3  315.83  5732.7  317.01  5860.2  323.61
#Mann= 11 ,-1 , 0
  4134.1     .05       0  4457.5     .16       0    4486     .05       0
    4905     .16       0  5004.5     .07       0  5010.5     .16       0
  5234.6     .05       0  5306.9     .16       0  5629.7      .1       0
  5632.2     .16       0  5732.7      .1       0
Bank Sta=5004.5,5010.5
XS Rating Curve= 0 ,0
Exp/Cntr=0.3,0.1

Type RM Length L Ch R = 1 ,1897    ,540,540,540
BEGIN DESCRIPTION:
UNT133 IN BECR 2.0
END DESCRIPTION:
XS GIS Cut Line= 3
      3792078.94     10511606.78      3793052.89     10511945.32
       3793863.4     10511664.76
#Sta/Elev= 30
  4214.1  318.21  4521.8  299.21  4639.6  295.05  4753.5  293.59  4965.6  280.35
  4987.6  278.72    4994  272.91  4996.8  272.41    5000  272.91  5008.8  277.59
  5019.4  279.92  5084.9  279.06  5220.6  278.35  5370.9  281.51  5453.4  281.13
  5646.1  287.14  5700.4  287.41  5765.4     291  5781.4  288.03  5806.4  294.39
  5830.9   296.9  5912.4  304.07  5921.2  306.07  5978.2  307.05  5983.5  309.12
  6040.6  311.42  6066.4  310.82  6071.7  313.93  6088.3  313.07  6102.9  315.34
#Mann= 9 ,-1 , 0
  4214.1     .05       0  4965.6     .16       0    4994     .07       0
    5000     .16       0  5084.9     .05       0  5700.4     .16       0
  5806.4      .1       0  5830.9     .16       0  5912.4      .1       0
Bank Sta=4994,5000
XS Rating Curve= 0 ,0
Exp/Cntr=0.3,0.1

Type RM Length L Ch R = 1 ,1357    ,802,802,802
BEGIN DESCRIPTION:
Mapping XS db9ae11f
END DESCRIPTION:
XS GIS Cut Line= 4
      3791655.32     10512006.08      3792254.28     10512318.58
      3792896.64     10512405.39      3793894.78     10511737.07
#Sta/Elev= 30
  3899.7  342.46    4053  334.75  4157.8   324.9  4196.3  318.74  4334.5  307.89
  4350.9   304.4  4477.8  296.73  4691.7  283.26  4742.1  277.73  4775.7  277.31
  4782.5  274.83  4998.7  272.93  5071.4  275.36  5125.6  271.14  5165.5  273.41
    5176  273.66  5258.2  270.34  5279.5  273.43  5690.8  274.67    6066  279.25
  6093.5   281.3  6138.1  280.64  6144.1  283.33  6163.2  283.38  6189.1  284.62
  6195.1  287.64  6210.8  285.16  6329.1  298.65  6369.2   303.2  6424.7  313.35
#Mann= 8 ,-1 , 0
  3899.7     .05       0  4477.8     .16       0  5165.5     .05       0
    5176     .16       0  6144.1      .1       0  6163.2     .16       0
  6210.8      .1       0  6329.1     .16       0
#XS Ineff= 2 , 0
                         5081.82          281.31
Permanent Ineff=
       F       F
Bank Sta=4775.7,5071.4
XS Rating Curve= 0 ,0
Exp/Cntr=0.3,0.1

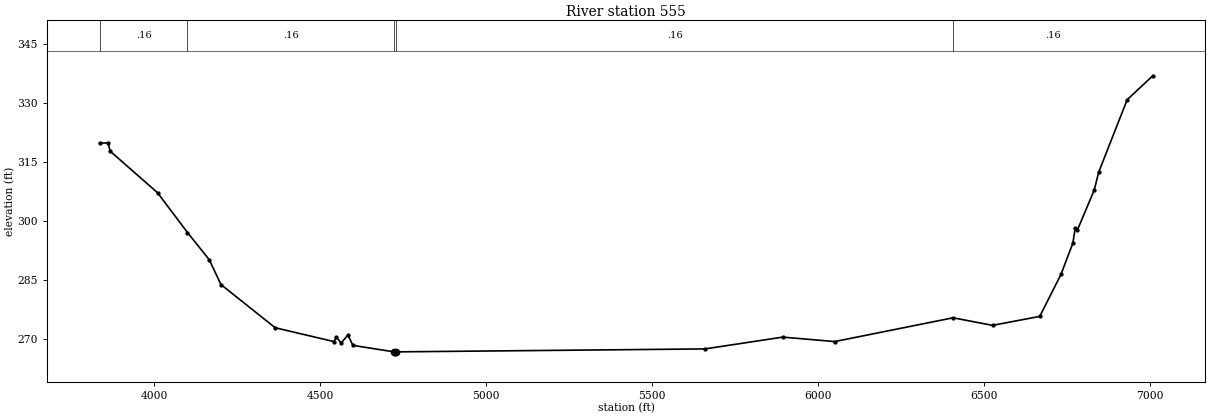
Type RM Length L Ch R = 1 ,555     ,0,0,0
BEGIN DESCRIPTION:
UNT133 IN BECR 1.0
END DESCRIPTION:
XS GIS Cut Line= 4
       3791837.6      10512526.9      3792592.82     10513177.96
      3792966.09     10513073.79      3794102.56      10511694.4
#Sta/Elev= 30
  3836.2  319.82  3861.4   319.9    3868  317.78  4010.5  307.23  4100.8  297.11
  4166.4  290.19  4201.5  283.89    4365   272.9  4541.6  269.39  4549.3  270.51
  4563.6  269.02  4584.4  271.08  4598.7  268.43    4723  266.77  4725.7  266.27
    4729  266.77  5659.2  267.52  5893.8  270.52  6050.1  269.39  6406.5  275.43
  6525.7  273.51  6667.8  275.79  6731.6  286.45  6767.4   294.4  6774.6  298.23
  6781.1  297.74    6832  307.94  6845.1  312.42    6931  330.86  7008.1  336.95
#Mann= 5 ,-1 , 0
  3836.2     .16       0  4100.8     .16       0    4723     .03       0
    4729     .16       0  6406.5     .16       0
Bank Sta=4723,4729
XS Rating Curve= 0 ,0
Exp/Cntr=0.3,0.1

Chan Stop Cuts=-1
Use User Specified Reach Order=0
Composite Channel Slope=5