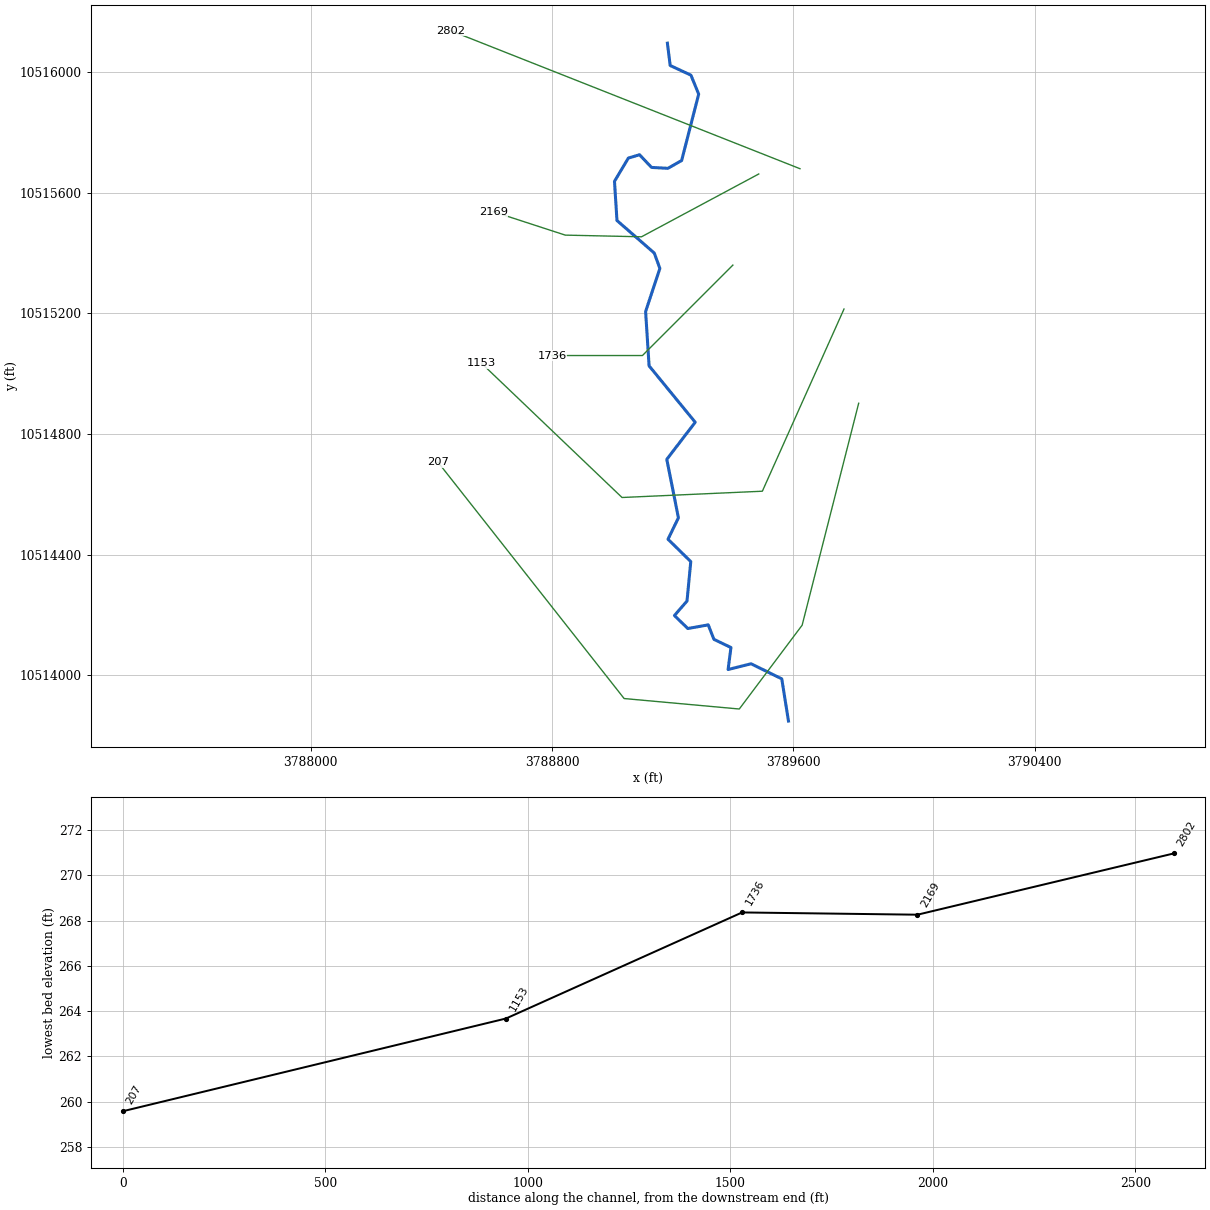
--- UNT135 IN BECR.prj (project) ---

Proj Title=UNT135 IN BECR Base Level Engineering
Current Plan=p01
Default Exp/Contr=0.3,0.1
English Units
Geom File=g01
Flow File=f01
Plan File=p01
BEGIN DESCRIPTION:
UNT135 IN BECR
END DESCRIPTION:

--- UNT135 IN BECR.p01 (plan) ---

Plan Title=Multiple Run
Short Identifier=Multiple
Geom File=g01
Flow File=f01
Subcritical Flow
K Sum by GR= 0
Std Step Tol= 0.01
Critical Tol= 0.01
Num of Std Step Trials= 20
Max Error Tol= 0.3
Flow Tol Ratio= 0.001
Split Flow NTrial= 30
Split Flow Tol= 0.02
Split Flow Ratio= 0.02
Log Output Level= 0
Friction Slope Method= 1
Unsteady Friction Slope Method= 2
Unsteady Bridges Friction Slope Method= 1
Parabolic Critical Depth
Global Vel Dist=  1 , 1 , 1
Global Log Level= 0
CheckData=True
Encroach Param= -1, 0, 0, 0
BEGIN DESCRIPTION:
Multiple Run
END DESCRIPTION:

--- UNT135 IN BECR.f01 (steady flow) ---

Flow Title=Multiple
Number of Profiles=7
Profile Names=10-year,25-year,50-year,1pct_min,100-year,1pct_plu,500-year
River Rch & RM= UNT135 IN BECR,Reach-1,2802
     966    1346    1669    1520    2056    2781    3130
Boundary for River Rch & Prof#=UNT135 IN BECR,Reach-1,1
Up Type=0
Dn Type=3
Dn Slope=0.005
Boundary for River Rch & Prof#=UNT135 IN BECR,Reach-1,2
Up Type=0
Dn Type=3
Dn Slope=0.005
Boundary for River Rch & Prof#=UNT135 IN BECR,Reach-1,3
Up Type=0
Dn Type=3
Dn Slope=0.005
Boundary for River Rch & Prof#=UNT135 IN BECR,Reach-1,4
Up Type=0
Dn Type=3
Dn Slope=0.005
Boundary for River Rch & Prof#=UNT135 IN BECR,Reach-1,5
Up Type=0
Dn Type=3
Dn Slope=0.005
Boundary for River Rch & Prof#=UNT135 IN BECR,Reach-1,6
Up Type=0
Dn Type=3
Dn Slope=0.005
Boundary for River Rch & Prof#=UNT135 IN BECR,Reach-1,7
Up Type=0
Dn Type=3
Dn Slope=0.005

--- UNT135 IN BECR.g01 (geometry) ---

Geom Title=Existing Conditions

River Reach=UNT135 IN BECR,Reach-1
Reach XY= 30
      3789182.50     10516096.00      3789191.75     10516022.00
      3789260.50     10515990.00      3789286.25     10515927.00
      3789229.75     10515707.00      3789184.25     10515681.00
      3789130.00     10515684.00      3789090.00     10515726.00
      3789053.00     10515715.00      3789007.00     10515638.00
      3789015.25     10515508.00      3789139.00     10515400.00
      3789157.50     10515349.00      3789110.25     10515206.00
      3789121.75     10515026.00      3789274.75     10514839.00
      3789180.50     10514716.00      3789219.00     10514522.00
      3789184.50     10514451.00      3789260.00     10514377.00
      3789247.50     10514246.00      3789205.75     10514198.00
      3789250.25     10514155.00      3789318.00     10514167.00
      3789336.75     10514119.00      3789393.25     10514092.00
      3789383.75     10514019.00      3789460.00     10514038.00
      3789561.75     10513988.00      3789584.00     10513848.00

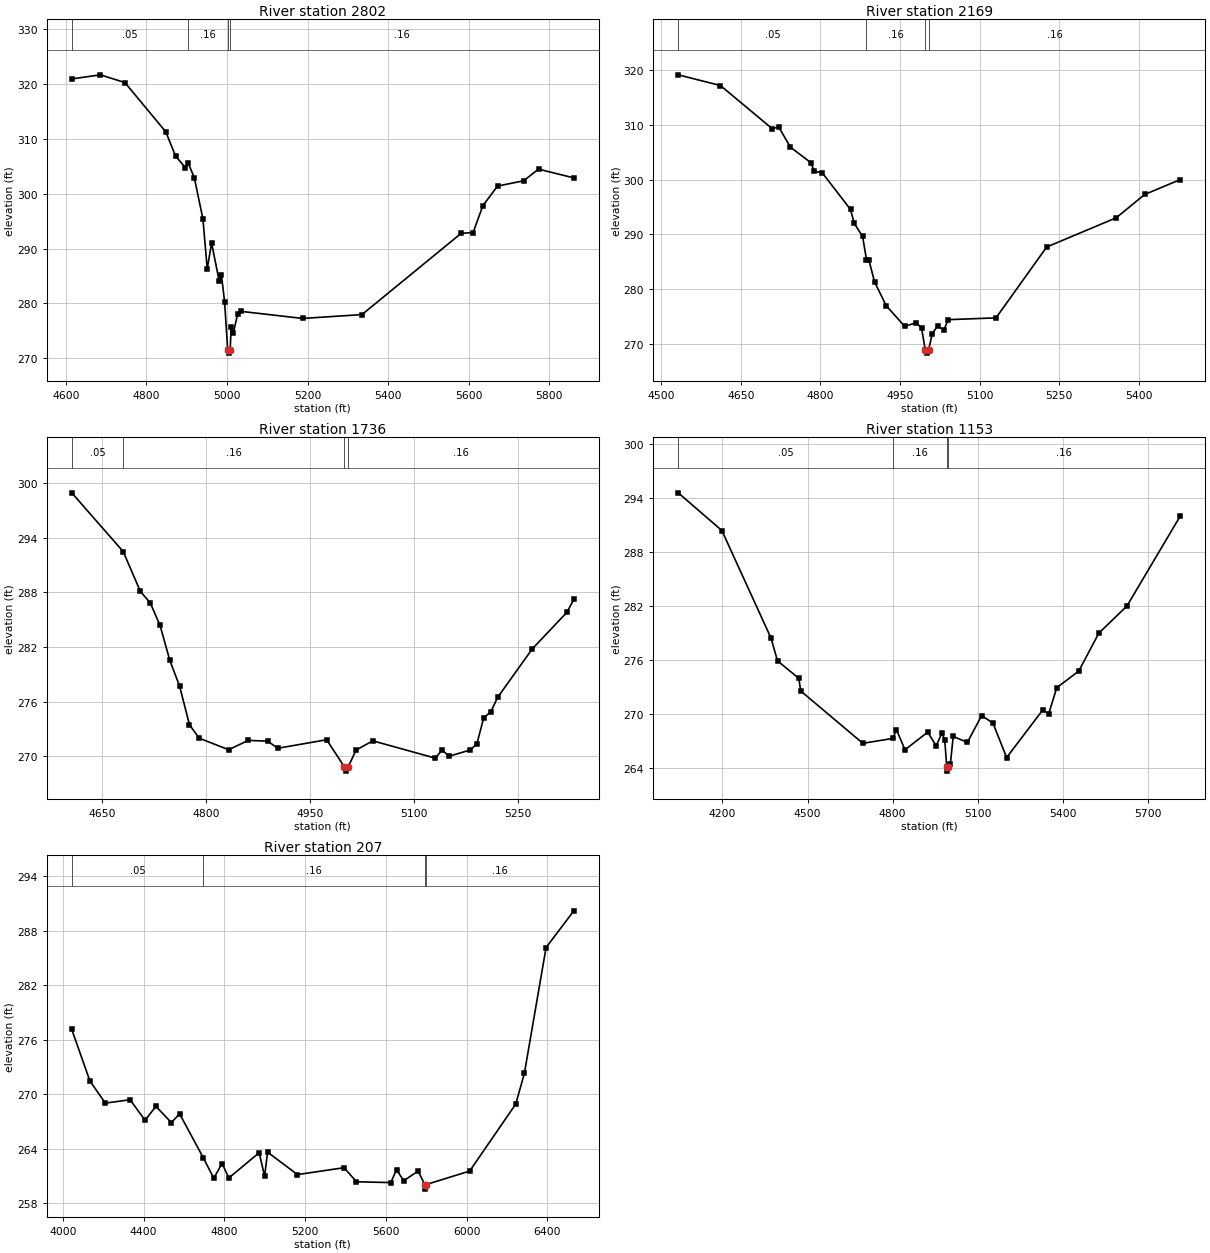
Type RM Length L Ch R = 1,2802,633,633,633
BEGIN DESCRIPTION:
UNT135 IN BECR 4.0
END DESCRIPTION:
XS GIS Cut Line= 2
      3789622.29     10515679.71      3788463.60     10516137.64
#Sta/Elev= 30
  4614.8  320.85  4685.8  321.60  4746.7  320.19  4848.1  311.23  4872.5  306.81
  4896.8  304.71  4903.8  305.52  4918.8  302.91  4940.3  295.37  4950.9  286.29
  4961.8  291.00  4980.6  284.09  4986.0  285.27  4994.0  280.35  5001.8  271.47
  5004.5  270.97  5007.8  271.47  5010.4  275.69  5015.8  274.65  5026.3  278.04
  5034.7  278.57  5187.6  277.28  5334.9  277.98  5581.0  292.76  5610.7  292.91
  5635.1  297.82  5671.4  301.36  5736.0  302.32  5773.0  304.44  5860.7  302.85
#Mann=4,-1,0
  4614.8    0.05       0  4903.8    0.16       0  5001.8    0.07       0
  5007.8    0.16       0
Bank Sta=5001.8,5007.8
Exp/Cntr=0.3,0.1

Type RM Length L Ch R = 1,2169,433,433,433
BEGIN DESCRIPTION:
UNT135 IN BECR 3.0
END DESCRIPTION:
XS GIS Cut Line= 4
      3789485.54     10515662.32      3789096.61     10515453.96
      3788843.83     10515459.52      3788604.94     10515537.30
#Sta/Elev= 30
  4532.4  319.17  4611.9  317.21  4709.3  309.32  4721.6  309.63  4743.5  305.95
  4781.7  303.13  4788.7  301.53  4803.7  301.23  4856.8  294.54  4863.8  291.98
  4879.5  289.61  4886.8  285.38  4891.4  285.28  4902.0  281.30  4923.9  276.95
  4958.9  273.14  4980.6  273.85  4990.6  272.83  4997.6  268.76  5000.4  268.26
  5003.6  268.76  5010.6  271.81  5020.6  273.22  5032.5  272.48  5040.6  274.38
  5130.7  274.71  5226.1  287.67  5357.1  293.02  5410.6  297.28  5477.7  300.01
#Mann=4,-1,0
  4532.4    0.05       0  4886.8    0.16       0  4997.6    0.07       0
  5003.6    0.16       0
Bank Sta=4997.6,5003.6
Exp/Cntr=0.3,0.1

Type RM Length L Ch R = 1,1736,583,583,583
BEGIN DESCRIPTION:
UNT135 IN BECR 2.0
END DESCRIPTION:
XS GIS Cut Line= 3
      3789399.64     10515360.22      3789099.61     10515060.19
      3788799.62     10515060.19
#Sta/Elev= 30
  4606.2  298.95  4680.4  292.49  4705.2  288.11  4719.4  286.85  4733.5  284.39
  4747.7  280.52  4761.8  277.69  4776.0  273.45  4790.1  271.98  4832.5  270.71
  4860.8  271.74  4889.1  271.65  4903.2  270.87  4973.9  271.81  4999.2  268.86
  5002.0  268.36  5005.2  268.86  5016.4  270.68  5040.5  271.69  5130.5  269.79
  5140.5  270.68  5150.5  270.00  5180.5  270.67  5190.5  271.32  5200.5  274.23
  5210.5  274.85  5220.5  276.46  5270.5  281.79  5320.5  285.82  5330.5  287.24
#Mann=4,-1,0
  4606.2    0.05       0  4680.4    0.16       0  4999.2    0.07       0
  5005.2    0.16       0
Bank Sta=4999.2,5005.2
Exp/Cntr=0.3,0.1

Type RM Length L Ch R = 1,1153,946,946,946
BEGIN DESCRIPTION:
Mapping XS 81eaa97c
END DESCRIPTION:
XS GIS Cut Line= 4
      3789768.15     10515214.37      3789497.34     10514610.25
      3789032.06     10514589.42      3788566.80     10515033.84
#Sta/Elev= 30
  4043.9  294.59  4197.8  290.40  4371.1  278.46  4394.2  275.92  4469.3  273.98
  4475.9  272.58  4695.1  266.76  4800.3  267.30  4813.8  268.27  4843.8  266.04
  4923.9  268.00  4953.9  266.48  4973.9  267.90  4984.0  267.18  4991.0  264.17
  4993.7  263.67  4997.0  264.17  5004.0  264.49  5014.0  267.53  5064.0  266.86
  5114.1  269.84  5154.1  269.01  5202.4  265.18  5329.5  270.45  5350.9  270.05
  5379.2  272.94  5456.8  274.78  5527.6  279.00  5626.7  282.01  5815.1  292.02
#Mann=4,-1,0
  4043.9    0.05       0  4800.3    0.16       0  4991.0    0.07       0
  4997.0    0.16       0
Bank Sta=4991,4997
Exp/Cntr=0.3,0.1

Type RM Length L Ch R = 1,207,0,0,0
BEGIN DESCRIPTION:
UNT135 IN BECR 1.0
END DESCRIPTION:
XS GIS Cut Line= 5
      3789816.79     10514901.96      3789629.28     10514165.81
      3789420.95     10513888.03      3789039.00     10513922.75
      3788421.87     10514706.30
#Sta/Elev= 30
  4043.9  277.15  4133.6  271.48  4210.2  269.04  4332.9  269.41  4406.9  267.15
  4460.8  268.68  4537.4  266.90  4578.3  267.86  4695.4  263.03  4747.4  260.77
  4788.7  262.39  4822.4  260.80  4972.4  263.58  4999.5  260.98  5014.1  263.64
  5162.2  261.17  5393.1  261.93  5454.6  260.38  5624.4  260.29  5653.3  261.71
  5688.5  260.49  5760.2  261.56  5793.0  260.07  5795.7  259.57  5799.0  260.07
  6015.6  261.56  6243.9  268.94  6286.6  272.32  6394.1  286.17  6531.7  290.21
#Mann=4,-1,0
  4043.9    0.05       0  4695.4    0.16       0  5793.0    0.07       0
  5799.0    0.16       0
Bank Sta=5793,5799
Exp/Cntr=0.3,0.1

Chan Stop Cuts=-1