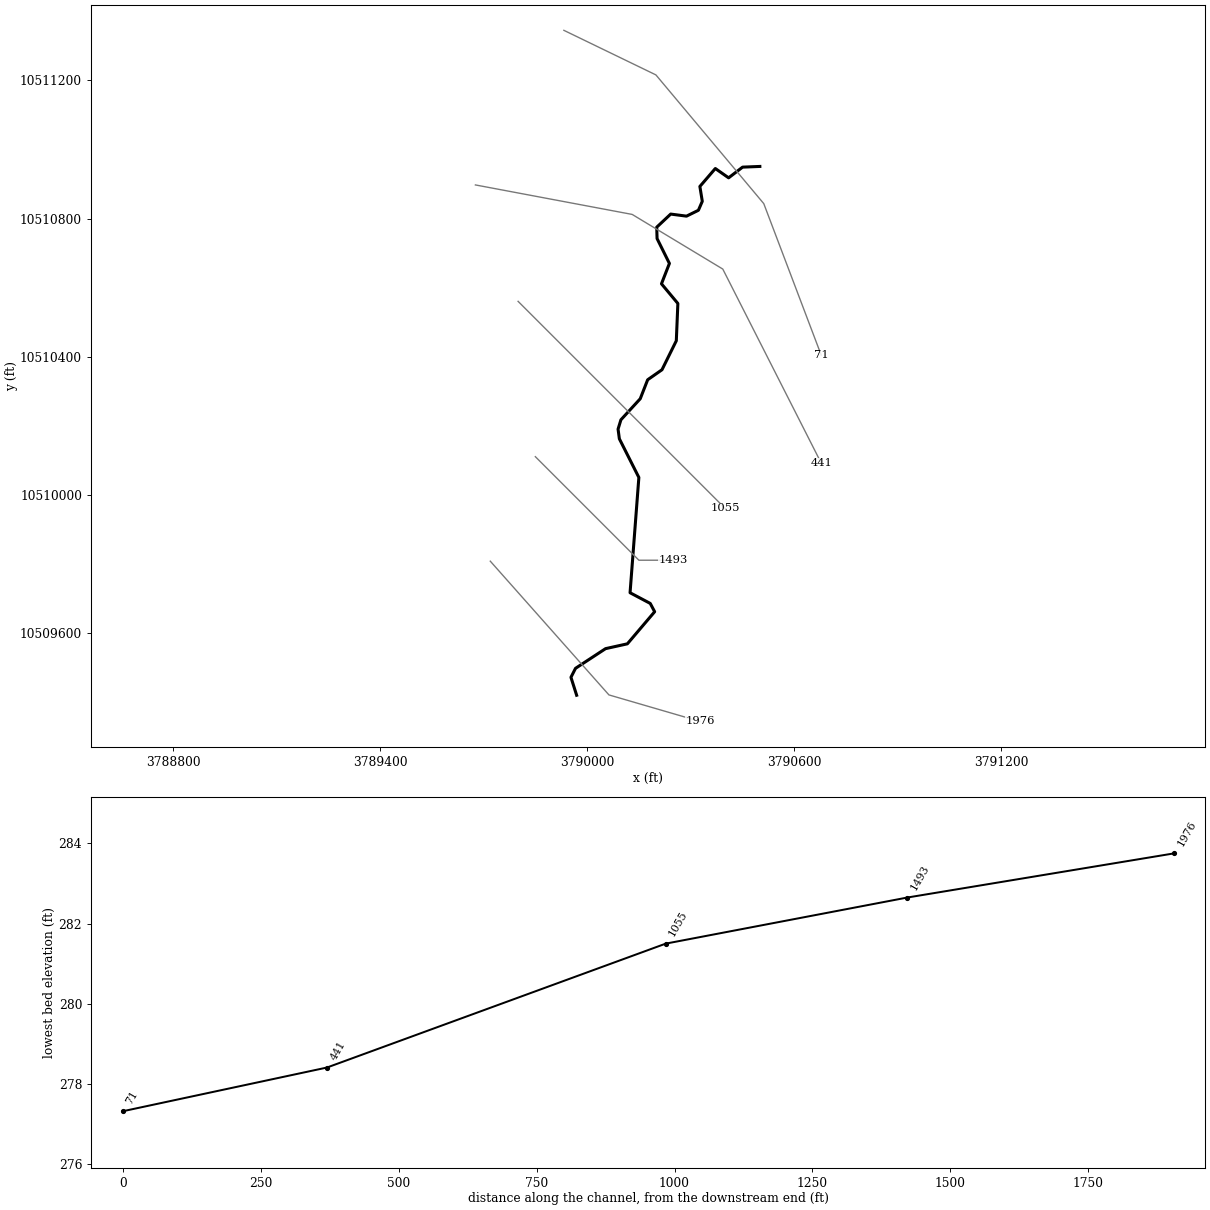
--- UNT136 IN BECR.prj (project) ---

Proj Title=UNT136 IN BECR Base Level Engineering
Current Plan=p01
Default Exp/Contr=0.3,0.1
English Units
Geom File=g01
Flow File=f01
Plan File=p01
Y Axis Title=Elevation
X Axis Title(PF)=Main Channel Distance
X Axis Title(XS)=Station
BEGIN DESCRIPTION:
UNT136 IN BECR
END DESCRIPTION:
DSS Export Rating Curves= 0
DSS Export Rating Curve Sorted= 0
DSS Export Volume Flow Curves= 0
DXF OffsetX= 0
DXF OffsetY= 0
DXF ScaleX= 1
DXF ScaleY= 10

--- UNT136 IN BECR.p01 (plan) ---

Plan Title=Multiple Run
Short Identifier=Multiple
Geom File=g01
Flow File=f01
Subcritical Flow
K Sum by GR= 0
Std Step Tol= 0.01
Critical Tol= 0.01
Num of Std Step Trials= 20
Max Error Tol= 0.3
Flow Tol Ratio= 0.001
Split Flow NTrial= 30
Split Flow Tol= 0.02
Split Flow Ratio= 0.02
Log Output Level= 0
Friction Slope Method= 1
Unsteady Friction Slope Method= 2
Unsteady Bridges Friction Slope Method= 1
Parabolic Critical Depth
Global Vel Dist=  1 , 1 , 1
Global Log Level= 0
CheckData=True
Encroach Param= -1, 0, 0, 0
BEGIN DESCRIPTION:
Multiple Run
END DESCRIPTION:

--- UNT136 IN BECR.f01 (steady flow) ---

Flow Title=Multiple
Number of Profiles=7
Profile Names=10-year,25-year,50-year,1pct_min,100-year,1pct_plu,500-year
River Rch & RM= UNT136 IN BECR,Reach-1,1976
     281     364     430     376     508     687     709
Boundary for River Rch & Prof#=UNT136 IN BECR,Reach-1,1
Up Type=0
Dn Type=3
Dn Slope=0.005
Boundary for River Rch & Prof#=UNT136 IN BECR,Reach-1,2
Up Type=0
Dn Type=3
Dn Slope=0.005
Boundary for River Rch & Prof#=UNT136 IN BECR,Reach-1,3
Up Type=0
Dn Type=3
Dn Slope=0.005
Boundary for River Rch & Prof#=UNT136 IN BECR,Reach-1,4
Up Type=0
Dn Type=3
Dn Slope=0.005
Boundary for River Rch & Prof#=UNT136 IN BECR,Reach-1,5
Up Type=0
Dn Type=3
Dn Slope=0.005
Boundary for River Rch & Prof#=UNT136 IN BECR,Reach-1,6
Up Type=0
Dn Type=3
Dn Slope=0.005
Boundary for River Rch & Prof#=UNT136 IN BECR,Reach-1,7
Up Type=0
Dn Type=3
Dn Slope=0.005

--- UNT136 IN BECR.g01 (geometry) ---

Geom Title=Existing Conditions
Program Version=4.10

River Reach=UNT136 IN BECR  ,Reach-1
Reach XY= 30
      3789969.25       10509419.      3789952.75       10509471.
        3789966.       10509497.        3790053.       10509554.
      3790116.25       10509568.      3790195.25       10509661.
       3790182.5       10509685.        3790124.       10509716.
       3790149.5       10510050.        3790093.       10510162.
      3790089.25       10510190.       3790097.5       10510217.
       3790153.5       10510278.        3790175.       10510333.
       3790216.5       10510362.        3790258.       10510446.
       3790262.5       10510554.        3790215.       10510611.
        3790238.       10510670.      3790202.25       10510742.
      3790201.25       10510775.      3790241.75       10510813.
       3790287.5       10510807.        3790322.       10510824.
      3790333.25       10510850.      3790326.25       10510893.
        3790371.       10510945.       3790409.5       10510918.
        3790450.       10510949.        3790500.       10510951.

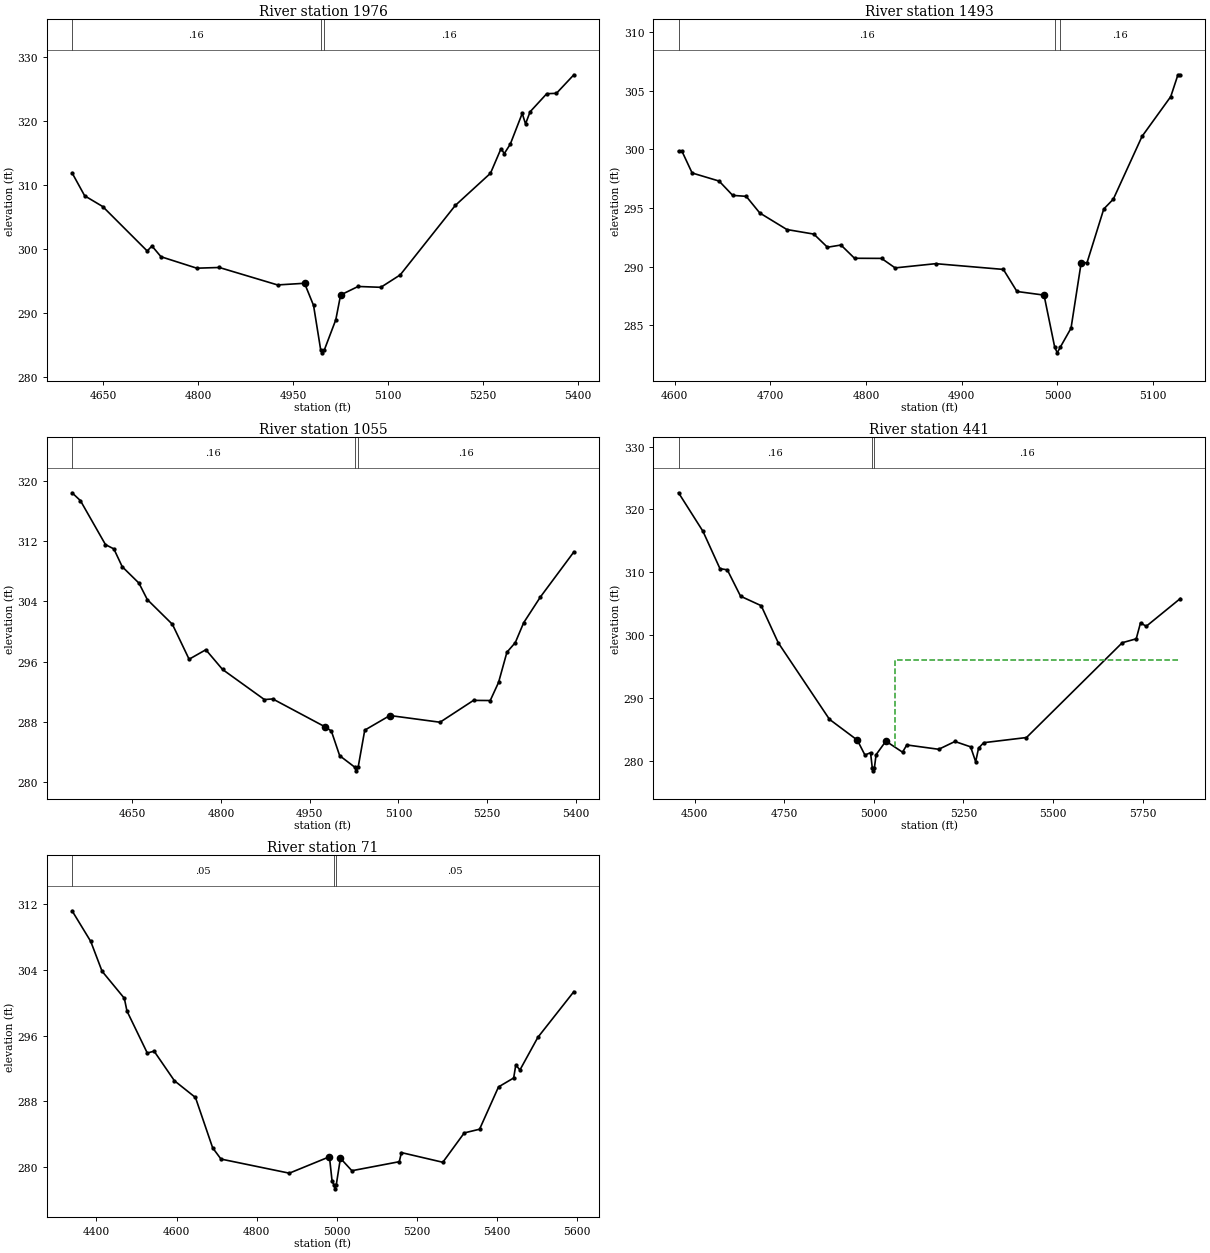
Type RM Length L Ch R = 1 ,1976    ,483,483,483
BEGIN DESCRIPTION:
UNT136 IN BECR 4.0
END DESCRIPTION:
XS GIS Cut Line= 3
      3789719.05     10509807.47      3790062.78     10509419.99
      3790325.97     10509343.31
#Sta/Elev= 30
  4601.3   311.9  4621.2  308.31  4649.7  306.63  4719.9  299.68  4727.4  300.46
  4741.7  298.78  4798.2  296.99  4833.7   297.1  4925.7  294.37  4968.3  294.63
  4982.5  291.16  4993.7  284.25  4996.5  283.75  4999.7  284.25  5017.6  288.92
  5025.2   292.8  5052.8  294.13  5088.7     294  5119.3  295.94  5206.2   306.8
  5261.8  311.84  5278.4  315.68  5283.6  314.92    5293  316.38  5311.9   321.2
  5317.1  319.55  5324.3  321.45  5350.6  324.28  5365.9  324.34  5393.4  327.24
#Mann= 3 ,-1 , 0
  4601.3     .16       0  4993.7     .07       0  4999.7     .16       0
Bank Sta=4968.3,5025.2
XS Rating Curve= 0 ,0
Exp/Cntr=0.3,0.1

Type RM Length L Ch R = 1 ,1493    ,438,438,438
BEGIN DESCRIPTION:
UNT136 IN BECR 3.0
END DESCRIPTION:
XS GIS Cut Line= 3
       3789849.6      10510110.2      3790149.61     10509810.19
      3790249.63     10509810.19
#Sta/Elev= 30
  4604.1  299.83  4607.7  299.83  4618.3  297.98  4646.5  297.29  4660.7  296.07
  4674.8  295.99    4689  294.57  4717.3  293.16  4745.5  292.77  4759.7  291.65
  4773.8  291.84    4788  290.71  4816.2   290.7  4830.4  289.89  4872.8  290.25
  4943.5  289.76  4957.7  287.88    4986  287.57  4997.1  283.15  4999.8  282.65
  5003.1  283.15  5014.2  284.75  5024.8  290.33  5030.9  290.33  5048.4  294.91
  5058.4  295.75  5088.4   301.1  5118.4  304.49  5125.9  306.35  5128.4  306.35
#Mann= 3 ,-1 , 0
  4604.1     .16       0  4997.1     .07       0  5003.1     .16       0
Bank Sta=4986,5024.8
XS Rating Curve= 0 ,0
Exp/Cntr=0.3,0.1

Type RM Length L Ch R = 1 ,1055    ,614,614,614
BEGIN DESCRIPTION:
UNT136 IN BECR 2.0
END DESCRIPTION:
XS GIS Cut Line= 3
      3789799.64     10510560.16      3790099.61     10510260.19
      3790399.62     10509960.18
#Sta/Elev= 30
  4548.1   318.4  4562.2  317.36  4604.6  311.52  4618.8  310.95  4632.9  308.59
  4661.2  306.41  4675.3  304.23  4717.8  300.94    4746  296.31  4774.3  297.57
  4802.6  294.95  4873.3  290.96  4887.5  291.04  4975.9  287.34  4986.5  286.79
  5000.6  283.51  5025.9     282  5028.6   281.5  5031.9     282    5043   286.9
  5085.5  288.84  5170.3  287.95  5226.9  290.85  5255.2  290.83  5269.3  293.24
  5283.4  297.24  5297.6  298.52  5311.7  301.15    5340  304.57  5396.6  310.55
#Mann= 3 ,-1 , 0
  4548.1     .16       0  5025.9     .07       0  5031.9     .16       0
Bank Sta=4975.9,5085.5
XS Rating Curve= 0 ,0
Exp/Cntr=0.3,0.1

Type RM Length L Ch R = 1 ,441     ,370,370,370
BEGIN DESCRIPTION:
Mapping XS 25690cc5
END DESCRIPTION:
XS GIS Cut Line= 4
      3789675.93     10510897.43      3790130.14       10510812.
      3790392.64     10510653.67      3790678.06     10510091.17
#Sta/Elev= 30
  4455.3  322.66  4523.4  316.53  4570.8  310.59  4591.3   310.4  4628.3   306.2
  4685.9  304.69  4733.3   298.8  4876.2  286.61  4953.9   283.3  4975.2  280.92
  4990.8   281.3  4995.6  278.91  4998.4  278.41  5001.6  278.91  5006.3  280.98
  5033.6  283.14    5080  281.38    5092  282.53    5181  281.84  5226.2  283.08
  5269.9  282.23    5284  279.86  5292.1  282.02  5306.4  282.89  5425.7  283.71
  5692.9   298.8  5731.8  299.42  5743.8  301.97  5759.7  301.41  5854.8  305.83
#Mann= 3 ,-1 , 0
  4455.3     .16       0  4995.6     .07       0  5001.6     .16       0
#XS Ineff= 2 , 0
                         5060.25           296.1
Permanent Ineff=
       F       F
Bank Sta=4953.9,5033.6
XS Rating Curve= 0 ,0
Exp/Cntr=0.3,0.1

Type RM Length L Ch R = 1 ,71      ,0,0,0
BEGIN DESCRIPTION:
UNT136 IN BECR 1.0
END DESCRIPTION:
XS GIS Cut Line= 4
      3789932.25     10511345.32      3790198.89     10511216.17
      3790511.39     10510843.25      3790677.76     10510404.45
#Sta/Elev= 30
  4339.4  311.23    4386  307.49  4414.2  303.86  4469.8  300.56  4476.4     299
  4527.1  293.88  4544.1  294.11  4594.8   290.5  4647.3  288.46  4690.2  282.32
    4711  280.95  4881.5  279.23  4981.6  281.23  4988.2  278.26  4992.7  277.82
  4995.5  277.32  4998.7  277.82    5009  281.05  5037.6  279.53  5155.9  280.63
  5161.2  281.74  5264.5  280.56    5318  284.14  5356.2  284.59  5403.5  289.75
  5441.3  290.84  5446.6  292.42    5457  291.82  5501.6  295.79  5591.5  301.37
#Mann= 3 ,-1 , 0
  4339.4     .05       0  4992.7     .03       0  4998.7     .05       0
Bank Sta=4981.6,5009
XS Rating Curve= 0 ,0
Exp/Cntr=0.3,0.1

Chan Stop Cuts=-1
Use User Specified Reach Order=0
Composite Channel Slope=5