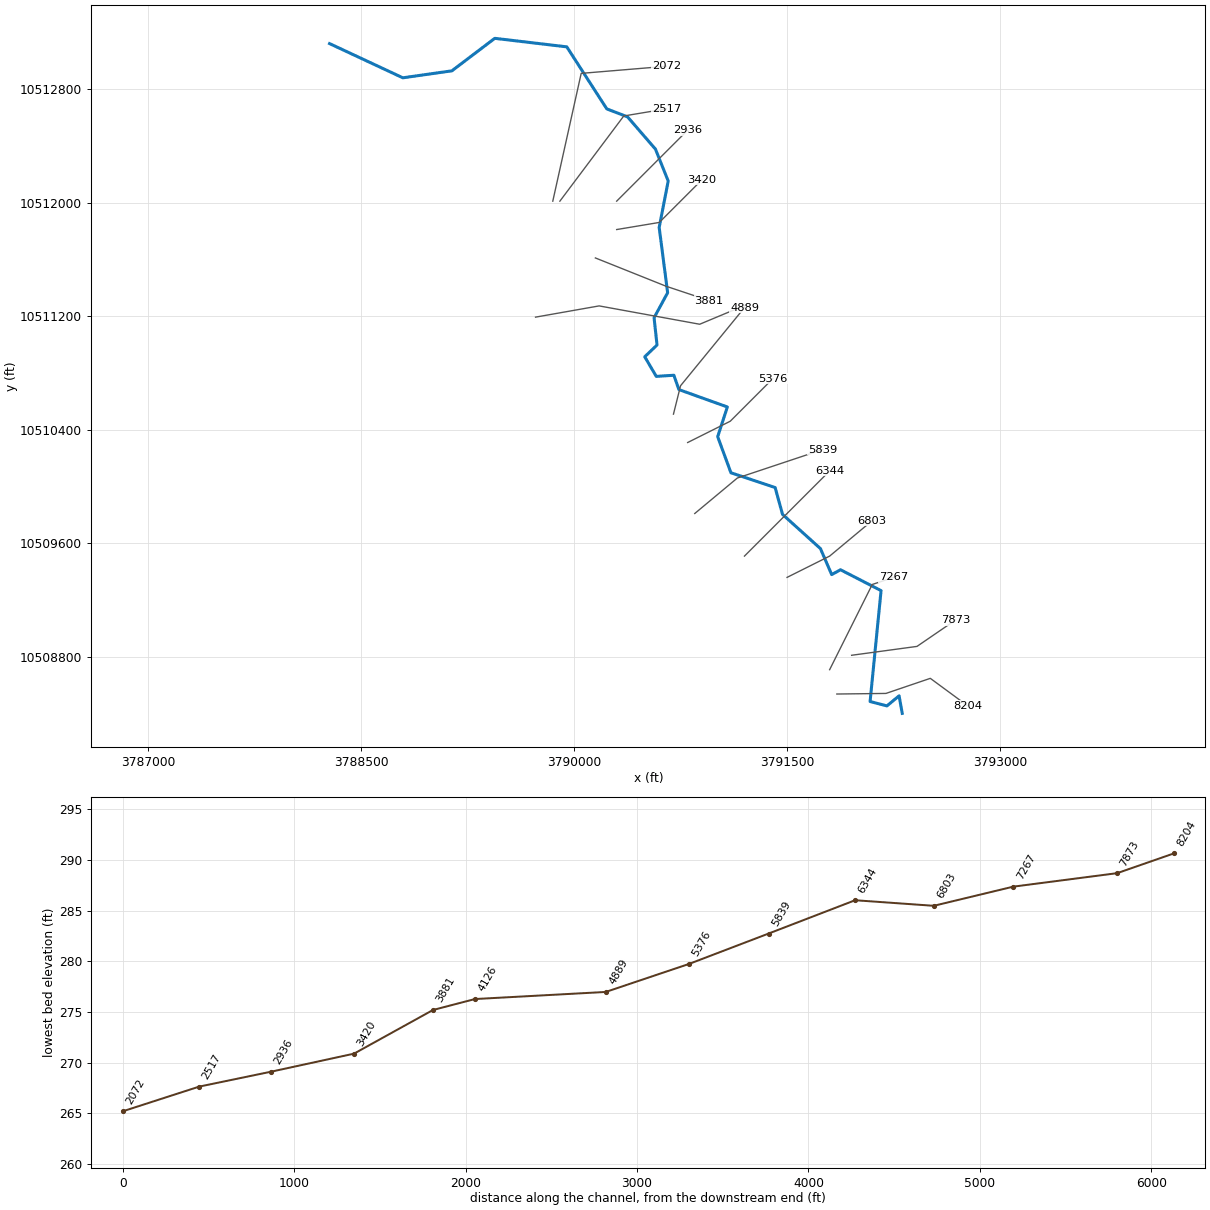
--- UNT137 IN BECR.prj (project) ---

Proj Title=UNT137 IN BECR Base Level Engineering
Current Plan=p01
Default Exp/Contr=0.3,0.1
English Units
Geom File=g01
Flow File=f01
Plan File=p01
Y Axis Title=Elevation
X Axis Title(PF)=Main Channel Distance
X Axis Title(XS)=Station
BEGIN DESCRIPTION:
UNT137 IN BECR
END DESCRIPTION:
DSS Export Rating Curves= 0
DSS Export Rating Curve Sorted= 0
DSS Export Volume Flow Curves= 0
DXF OffsetX= 0
DXF OffsetY= 0
DXF ScaleX= 1
DXF ScaleY= 10

--- UNT137 IN BECR.p01 (plan) ---

Plan Title=Multiple Run
Short Identifier=Multiple
Geom File=g01
Flow File=f01
Subcritical Flow
K Sum by GR= 0
Std Step Tol= 0.01
Critical Tol= 0.01
Num of Std Step Trials= 20
Max Error Tol= 0.3
Flow Tol Ratio= 0.001
Split Flow NTrial= 30
Split Flow Tol= 0.02
Split Flow Ratio= 0.02
Log Output Level= 0
Friction Slope Method= 1
Unsteady Friction Slope Method= 2
Unsteady Bridges Friction Slope Method= 1
Parabolic Critical Depth
Global Vel Dist=  1 , 1 , 1
Global Log Level= 0
CheckData=True
Encroach Param= -1, 0, 0, 0
BEGIN DESCRIPTION:
Multiple Run
END DESCRIPTION:

--- UNT137 IN BECR.f01 (steady flow) ---

Flow Title=Multiple
Number of Profiles=7
Profile Names=10-year,25-year,50-year,1pct_min,100-year,1pct_plu,500-year
River Rch & RM= UNT137 IN BECR,Reach-1,8204
     385     509     610     539     728     985    1040
River Rch & RM= UNT137 IN BECR,Reach-1,4126
     655     892    1090     979    1324    1791    1960
Boundary for River Rch & Prof#=UNT137 IN BECR,Reach-1,1
Up Type=0
Dn Type=3
Dn Slope=0.005
Boundary for River Rch & Prof#=UNT137 IN BECR,Reach-1,2
Up Type=0
Dn Type=3
Dn Slope=0.005
Boundary for River Rch & Prof#=UNT137 IN BECR,Reach-1,3
Up Type=0
Dn Type=3
Dn Slope=0.005
Boundary for River Rch & Prof#=UNT137 IN BECR,Reach-1,4
Up Type=0
Dn Type=3
Dn Slope=0.005
Boundary for River Rch & Prof#=UNT137 IN BECR,Reach-1,5
Up Type=0
Dn Type=3
Dn Slope=0.005
Boundary for River Rch & Prof#=UNT137 IN BECR,Reach-1,6
Up Type=0
Dn Type=3
Dn Slope=0.005
Boundary for River Rch & Prof#=UNT137 IN BECR,Reach-1,7
Up Type=0
Dn Type=3
Dn Slope=0.005

--- UNT137 IN BECR.g01 (geometry) ---

Geom Title=Existing Conditions
Program Version=4.10

River Reach=UNT137 IN BECR  ,Reach-1
Reach XY= 30
      3792310.91     10508402.42      3792288.75       10508526.
        3792203.       10508455.       3792084.5       10508486.
      3792161.75       10509267.      3791876.25       10509414.
        3791814.       10509380.      3791734.75       10509563.
      3791467.75       10509804.      3791415.75       10509993.
       3791104.5       10510097.        3791011.       10510351.
      3791079.13     10510560.64      3790737.75       10510683.
       3790702.5       10510784.       3790578.5       10510776.
      3790497.25       10510914.      3790583.75       10510997.
        3790563.       10511189.       3790658.5       10511365.
        3790599.       10511825.       3790662.5       10512152.
       3790572.5       10512377.        3790376.       10512604.
        3790230.       10512660.      3789948.25       10513097.
        3789441.       10513157.      3789138.75       10512928.
       3788793.5       10512879.      3788277.25       10513120.

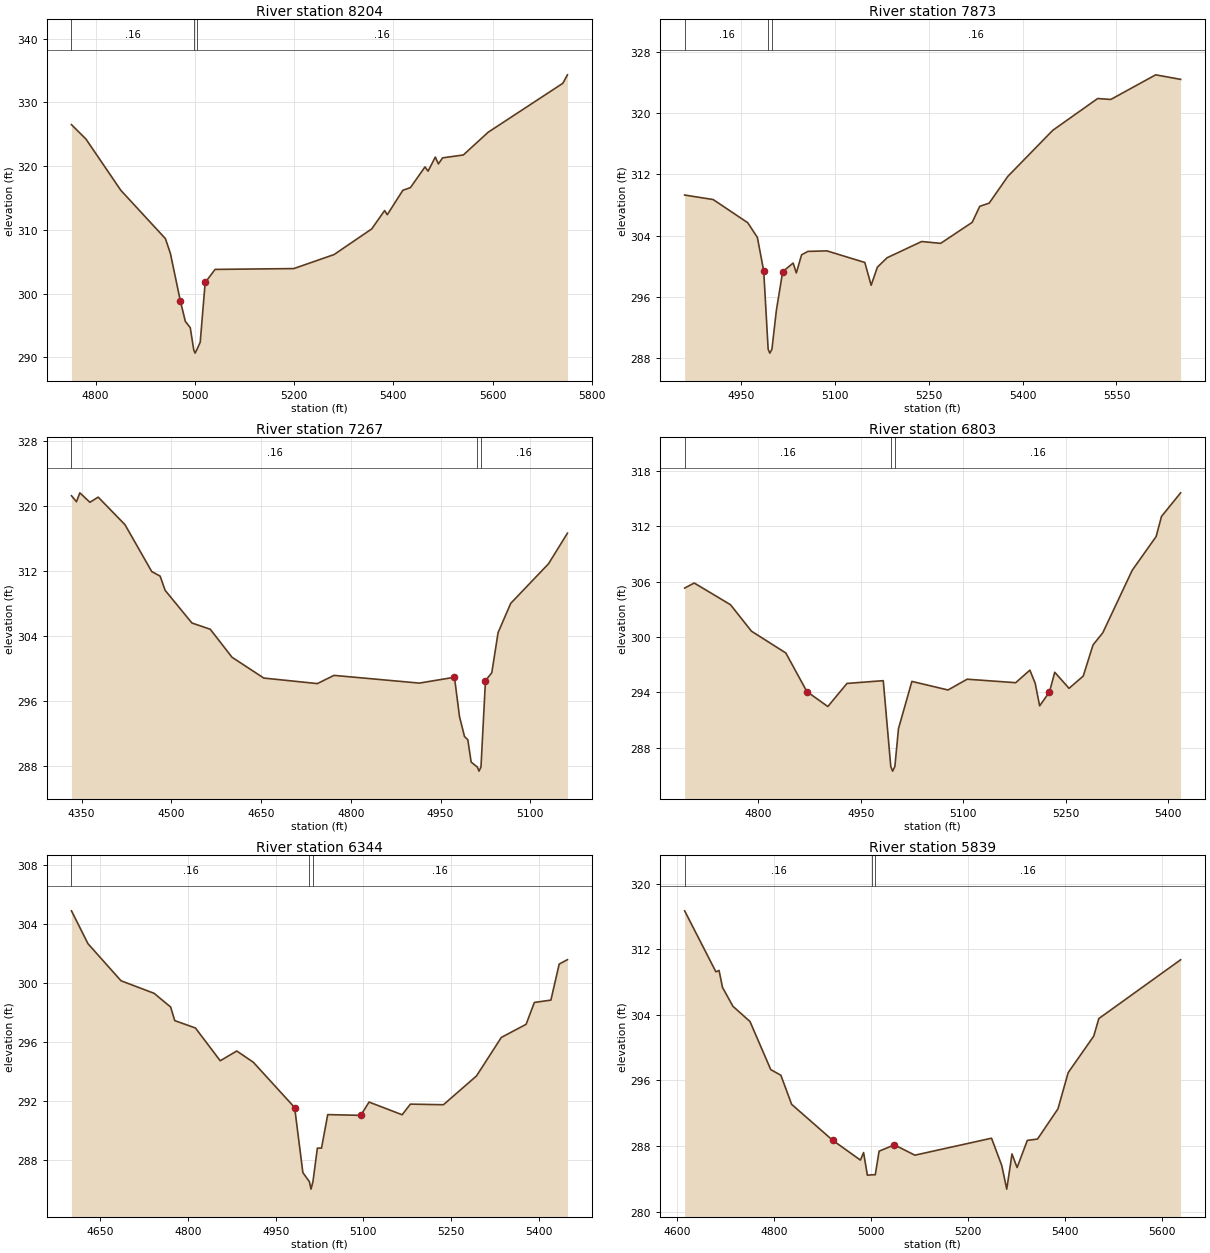
Type RM Length L Ch R = 1 ,8204    ,331,331,331
BEGIN DESCRIPTION:
UNT137 IN BECR 14.0
END DESCRIPTION:
XS GIS Cut Line= 4
      3791850.28     10508538.74      3792196.11     10508542.91
      3792508.61     10508649.16      3792769.05     10508457.48
#Sta/Elev= 30
  4751.4  326.51  4780.7  324.24  4850.7  316.22  4940.7  308.62  4950.7  306.31
  4970.7  298.88  4980.8  295.64  4990.8  294.64  4997.8  291.15  5000.5  290.65
  5003.8  291.15  5010.8  292.36  5020.8  301.74  5040.8  303.79  5199.4  303.92
  5280.5  306.12  5356.3  310.14  5382.4  313.03  5387.7  312.37  5419.1  316.21
  5434.4  316.63  5463.7  319.88  5469.9  319.21  5484.5  321.42  5490.7  320.35
  5499.2   321.3  5540.9  321.75    5591  325.32  5741.4     333  5750.7  334.33
#Mann= 3 ,-1 , 0
  4751.4     .16       0  4997.8     .07       0  5003.8     .16       0
Bank Sta=4970.7,5020.8
XS Rating Curve= 0 ,0
Exp/Cntr=0.3,0.1

Type RM Length L Ch R = 1 ,7873    ,606,606,606
BEGIN DESCRIPTION:
UNT137 IN BECR 13.0
END DESCRIPTION:
XS GIS Cut Line= 3
      3791954.46     10508811.66      3792414.86     10508874.16
      3792685.16     10509059.21
#Sta/Elev= 30
  4860.3  309.31  4905.9  308.72  4961.1   305.7  4976.5  303.78  4986.6  299.42
  4993.7   289.2  4996.4   288.7  4999.7   289.2  5006.8  294.26  5016.9  299.32
  5033.6  300.44  5038.7  299.15  5047.1  301.52  5057.2  301.96  5087.5  302.03
  5148.1  300.52  5158.2  297.55  5168.2  299.91  5183.6  301.13  5238.9  303.25
  5269.2  303.01  5319.6  305.75  5331.7  307.84  5346.7  308.25  5376.5  311.74
  5448.2  317.74    5520  321.89    5541  321.77  5612.7  324.98  5652.5  324.39
#Mann= 3 ,-1 , 0
  4860.3     .16       0  4993.7     .07       0  4999.7     .16       0
Bank Sta=4986.6,5016.9
XS Rating Curve= 0 ,0
Exp/Cntr=0.3,0.1

Type RM Length L Ch R = 1 ,7267    ,464,464,464
BEGIN DESCRIPTION:
UNT137 IN BECR 12.0
END DESCRIPTION:
XS GIS Cut Line= 3
       3791799.6     10508710.18      3792099.61     10509310.19
      3792249.56     10509360.17
#Sta/Elev= 30
  4333.1  321.22  4341.5  320.49  4347.1  321.58  4363.9  320.42  4377.8  321.05
  4422.6  317.66  4467.3   311.9  4481.3  311.34  4489.6   309.6  4534.4  305.58
  4565.1  304.81  4601.4  301.37  4654.5  298.81    4744  298.13  4771.9  299.14
  4914.5  298.19  4973.2  298.91  4981.6  294.08    4990  291.62  4995.5  291.23
  5001.1  288.48  5011.5  287.87  5014.2  287.37  5017.5  287.87    5025  298.49
  5035.6  299.47  5046.1   304.4  5067.2  307.99  5130.4  312.86    5162  316.62
#Mann= 3 ,-1 , 0
  4333.1     .16       0  5011.5     .07       0  5017.5     .16       0
Bank Sta=4973.2,5025
XS Rating Curve= 0 ,0
Exp/Cntr=0.3,0.1

Type RM Length L Ch R = 1 ,6803    ,459,459,459
BEGIN DESCRIPTION:
UNT137 IN BECR 11.0
END DESCRIPTION:
XS GIS Cut Line= 3
      3791499.61     10509360.19      3791799.61     10509510.19
      3792099.59     10509760.17
#Sta/Elev= 30
    4692  305.31    4706  305.86  4759.1  303.51  4789.8  300.64  4840.1  298.28
  4870.9   294.1  4901.6  292.48  4929.6  294.98  4982.7  295.28  4993.7  285.98
  4996.4  285.48  4999.7  285.98    5005  290.09  5024.6   295.2  5077.5  294.27
  5105.5  295.44  5176.5  295.06  5197.3  296.42  5205.1  294.99  5211.6  292.55
  5225.9  294.05  5233.7  296.19  5254.6  294.45  5275.4  295.78  5289.7  299.15
    5304  300.47    5347  307.23  5382.1   310.9  5389.9  313.07  5417.9  315.63
#Mann= 3 ,-1 , 0
    4692     .16       0  4993.7     .07       0  4999.7     .16       0
Bank Sta=4870.9,5225.9
XS Rating Curve= 0 ,0
Exp/Cntr=0.3,0.1

Type RM Length L Ch R = 1 ,6344    ,505,505,505
BEGIN DESCRIPTION:
UNT137 IN BECR 10.0
END DESCRIPTION:
XS GIS Cut Line= 3
      3791199.63     10509510.21      3791499.61     10509810.19
      3791799.61     10510110.19
#Sta/Elev= 30
  4600.7  304.89    4629  302.66  4685.5  300.15  4742.1   299.3  4770.4  298.37
  4777.4  297.45  4812.8  296.95  4855.2  294.73  4883.5  295.39  4911.8  294.63
  4982.5  291.56  4996.6  287.15  5007.8  286.53  5010.5  286.03  5013.8  286.53
  5021.4  288.81  5028.5  288.81  5039.1  291.08  5095.6  291.03  5109.8  291.93
  5166.4  291.07  5180.5  291.79  5237.1  291.75  5293.6   293.7  5336.1  296.31
  5378.5   297.2  5392.6  298.68  5420.9  298.84  5435.1  301.28  5449.2  301.58
#Mann= 3 ,-1 , 0
  4600.7     .16       0  5007.8     .07       0  5013.8     .16       0
Bank Sta=4982.5,5095.6
XS Rating Curve= 0 ,0
Exp/Cntr=0.3,0.1

Type RM Length L Ch R = 1 ,5839    ,463,463,463
BEGIN DESCRIPTION:
UNT137 IN BECR 9.0
END DESCRIPTION:
XS GIS Cut Line= 3
      3790849.58     10509810.17      3791149.61     10510060.19
      3791749.61     10510260.19
#Sta/Elev= 30
  4616.3  316.68  4680.8  309.24  4687.3  309.41  4694.4  307.34  4715.9  305.04
  4751.1  303.18    4794  297.31  4814.8  296.63    4837  293.08  4921.6   288.7
  4978.9  286.28  4985.4   287.2  4993.2  284.44  5003.6  284.49  5009.5  284.49
  5017.4  287.37    5049  288.14  5091.2  286.88  5249.3  288.95  5270.4  285.62
  5280.7  282.74  5291.5  287.03    5302  285.37  5323.1  288.68  5344.2  288.85
  5386.3  292.53  5407.4  296.95  5460.1   301.4  5470.6  303.54  5639.3  310.71
#Mann= 3 ,-1 , 0
  4616.3     .16       0  5003.6     .07       0  5009.5     .16       0
Bank Sta=4921.6,5049
XS Rating Curve= 0 ,0
Exp/Cntr=0.3,0.1

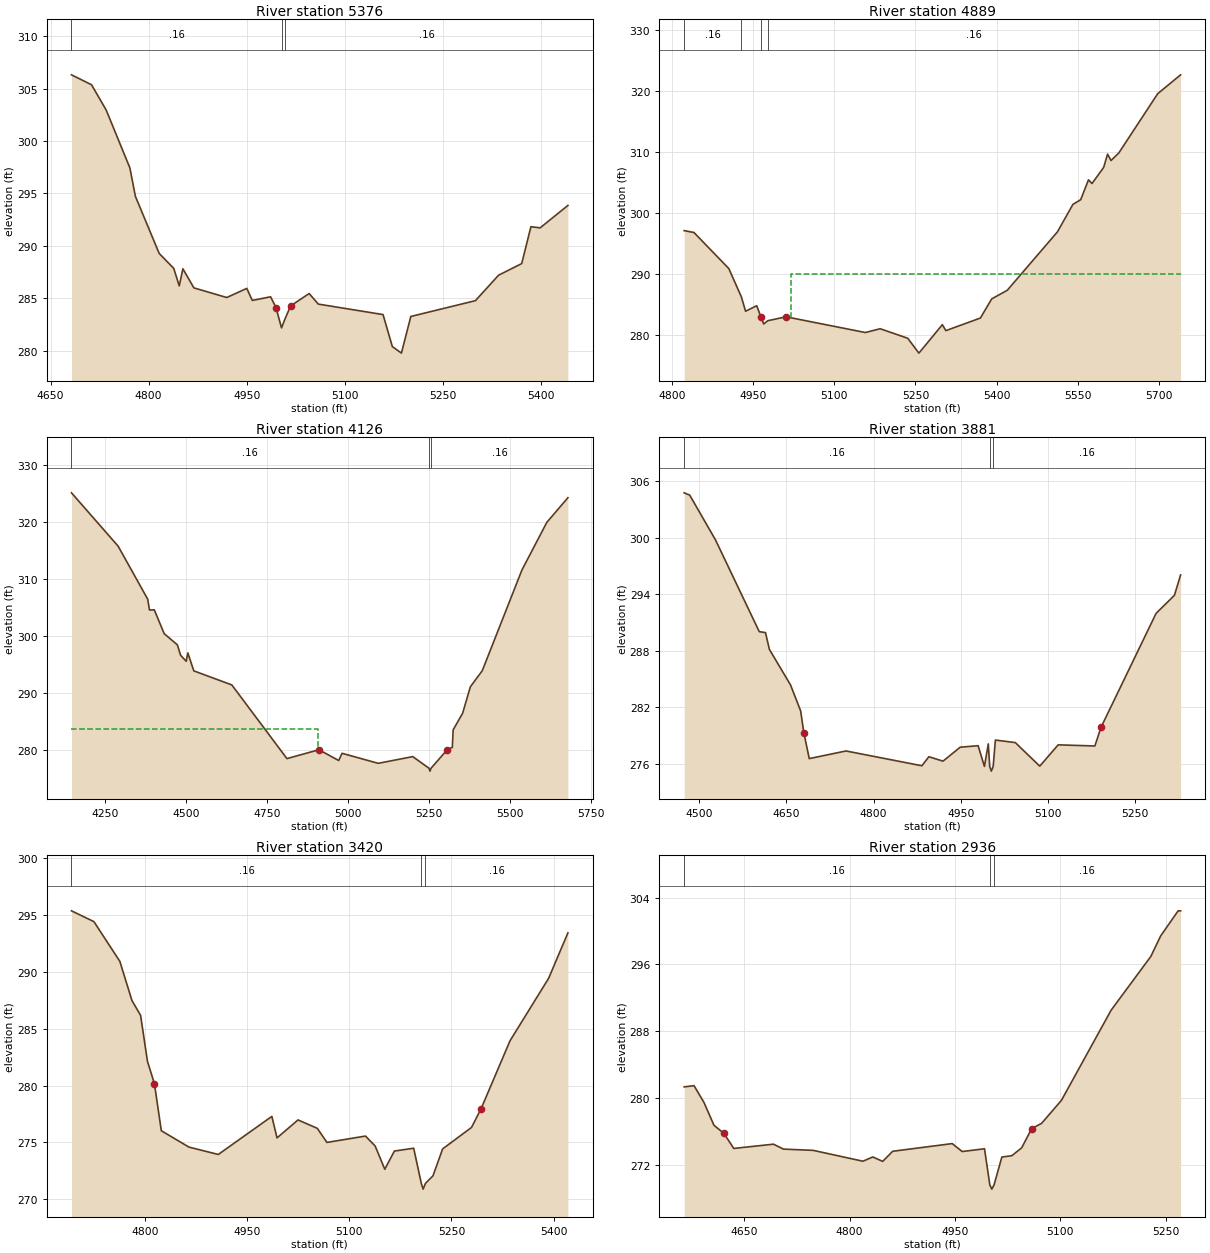
Type RM Length L Ch R = 1 ,5376    ,487,487,487
BEGIN DESCRIPTION:
UNT137 IN BECR 8.0
END DESCRIPTION:
XS GIS Cut Line= 3
      3790799.61     10510310.19      3791099.61     10510460.19
      3791399.63     10510760.21
#Sta/Elev= 30
  4681.9  306.32  4712.6  305.37    4735  302.96  4771.3  297.43  4779.7  294.72
  4816.1  289.27  4838.4  287.84  4846.8  286.17  4852.4   287.8  4869.2  285.98
  4919.5  285.06  4950.2  285.93  4958.6  284.78  4986.6  285.13  4994.9   284.1
  5003.3  282.16  5008.9  283.05  5017.3  284.26  5045.6  285.44  5059.7  284.43
  5158.7  283.43  5172.9  280.38  5186.8  279.75  5201.2  283.25  5300.1  284.76
  5335.5  287.19  5370.9   288.3    5385  291.82  5399.1  291.71  5441.6  293.85
#Mann= 3 ,-1 , 0
  4681.9     .16       0  5003.3     .07       0  5008.9     .16       0
Bank Sta=4994.9,5017.3
XS Rating Curve= 0 ,0
Exp/Cntr=0.3,0.1

Type RM Length L Ch R = 1 ,4889    ,763,763,763
BEGIN DESCRIPTION:
UNT137 IN BECR 7.0
END DESCRIPTION:
XS GIS Cut Line= 3
       3790699.6     10510510.16      3790749.61     10510710.19
       3791199.6     10511260.17
#Sta/Elev= 30
    4823  297.08  4841.1  296.77  4905.5  290.85  4928.7   286.2  4936.4  283.85
    4957  284.76  4964.8  282.91  4969.9  281.76  4977.6   282.3  5011.1  282.94
  5157.7  280.36    5185  280.98  5235.9  279.42  5256.5  276.98  5299.8  281.65
  5306.3  280.67  5370.1  282.74    5391  285.88  5419.7  287.29  5512.3  296.87
    5541  301.39  5555.3  302.15  5569.7  305.41  5576.2  304.81  5597.7  307.44
  5604.9  309.63  5611.3  308.58  5625.7  309.82  5697.5  319.54  5739.8  322.64
#Mann= 4 ,-1 , 0
    4823     .16       0  4928.7     .16       0  4964.8     .07       0
  4977.6     .16       0
#XS Ineff= 2 , 0
                         5021.02             290
Permanent Ineff=
       F       F
Bank Sta=4964.8,5011.1
XS Rating Curve= 0 ,0
Exp/Cntr=0.3,0.1

Type RM Length L Ch R = 1 ,4126    ,245,245,245
BEGIN DESCRIPTION:
UNT137 IN BECR 6.0
END DESCRIPTION:
XS GIS Cut Line= 4
      3789728.01     10511193.25      3790175.97     10511272.42
       3790884.3     10511143.25      3791213.43     10511280.74
#Sta/Elev= 30
  4145.9  325.13  4289.7  315.78  4381.1  306.46  4386.5  304.56  4401.4  304.59
  4431.9  300.41  4472.5  298.45  4482.6  296.61  4499.8  295.57  4504.9  297.03
  4523.3  293.88  4640.6  291.41  4810.6  278.48  4909.4  280.03  4970.4  278.14
  4980.6  279.41  5092.4  277.65  5198.8  278.83  5249.1  276.78  5251.9  276.28
  5255.1  276.78  5305.4  280.05  5320.8  280.44  5323.5  283.53  5352.7  286.44
  5376.5  291.08  5413.3  293.91  5535.6  311.58  5612.5  319.95  5677.5  324.27
#Mann= 3 ,-1 , 0
  4145.9     .16       0  5249.1     .07       0  5255.1     .16       0
#XS Ineff= 2 , 0
         4905.11  283.76
Permanent Ineff=
       F       F
Bank Sta=4909.4,5305.4
XS Rating Curve= 0 ,0
Exp/Cntr=0.3,0.1

Type RM Length L Ch R = 1 ,3881    ,461,461,461
BEGIN DESCRIPTION:
UNT137 IN BECR 5.0
END DESCRIPTION:
XS GIS Cut Line= 3
      3790149.58      10511610.2      3790649.61     10511410.19
      3790949.63     10511310.18
#Sta/Elev= 30
  4473.9  304.75  4483.4  304.51  4527.8  299.76  4603.2  290.01  4613.9  289.91
  4620.7  288.12    4657  284.36  4674.5  281.59  4679.9  279.29  4689.3  276.53
  4752.6  277.34  4883.2  275.77  4895.3  276.73  4919.6  276.26  4949.2  277.74
  4980.1   277.9  4990.9   275.7  4997.6  278.09    5000   275.7  5002.8   275.2
    5006   275.7  5009.8   278.5  5044.1  278.23  5086.2  275.73  5117.9  277.99
  5181.1  277.87  5191.6  279.84  5286.5  291.95  5318.1  293.87  5328.7  296.03
#Mann= 3 ,-1 , 0
  4473.9     .16       0    5000     .07       0    5006     .16       0
Bank Sta=4679.9,5191.6
XS Rating Curve= 0 ,0
Exp/Cntr=0.3,0.1

Type RM Length L Ch R = 1 ,3420    ,484,484,484
BEGIN DESCRIPTION:
UNT137 IN BECR 4.0
END DESCRIPTION:
XS GIS Cut Line= 3
      3790299.61     10511810.19      3790599.61     10511860.19
      3790899.61     10512160.19
#Sta/Elev= 30
  4692.5  295.38  4725.4  294.43  4763.5  290.93  4781.2  287.49  4793.9  286.18
    4804  282.13  4814.2  280.17  4824.3  276.03  4864.8  274.59  4907.9  273.94
  4986.5  277.29  4994.1   275.4  5024.9  276.98  5053.2  276.24  5067.3     275
  5123.9  275.56  5138.1  274.68  5152.2  272.64  5166.3  274.24  5194.6  274.49
  5205.8  271.39  5208.5  270.89  5211.8  271.39  5222.9  272.06  5237.1  274.43
  5279.5  276.32  5293.6  277.98    5336  283.95  5392.6  289.44  5420.9  293.44
#Mann= 3 ,-1 , 0
  4692.5     .16       0  5205.8     .07       0  5211.8     .16       0
Bank Sta=4814.2,5293.6
XS Rating Curve= 0 ,0
Exp/Cntr=0.3,0.1

Type RM Length L Ch R = 1 ,2936    ,419,419,419
BEGIN DESCRIPTION:
UNT137 IN BECR 3.0
END DESCRIPTION:
XS GIS Cut Line= 3
      3790299.61     10512010.19      3790599.61     10512310.19
       3790799.6     10512510.18
#Sta/Elev= 30
  4564.4  281.35  4578.5  281.49  4592.7  279.47  4606.8  276.76    4621  275.78
  4635.1  273.98  4691.7  274.49  4705.8   273.9  4748.2  273.75    4819  272.45
  4833.1  272.96  4847.2  272.43  4861.4  273.64  4946.2  274.56  4960.4  273.61
  4992.2  273.94  4999.8  269.61  5002.6  269.11  5005.8  269.61  5016.9  272.95
  5031.1  273.11  5045.2  274.06  5059.4  276.35  5073.5  276.98  5101.8  279.74
  5172.5  290.52  5229.1  296.96  5243.2  299.43    5268  302.42  5271.5  302.42
#Mann= 3 ,-1 , 0
  4564.4     .16       0  4999.8     .07       0  5005.8     .16       0
Bank Sta=4621,5059.4
XS Rating Curve= 0 ,0
Exp/Cntr=0.3,0.1

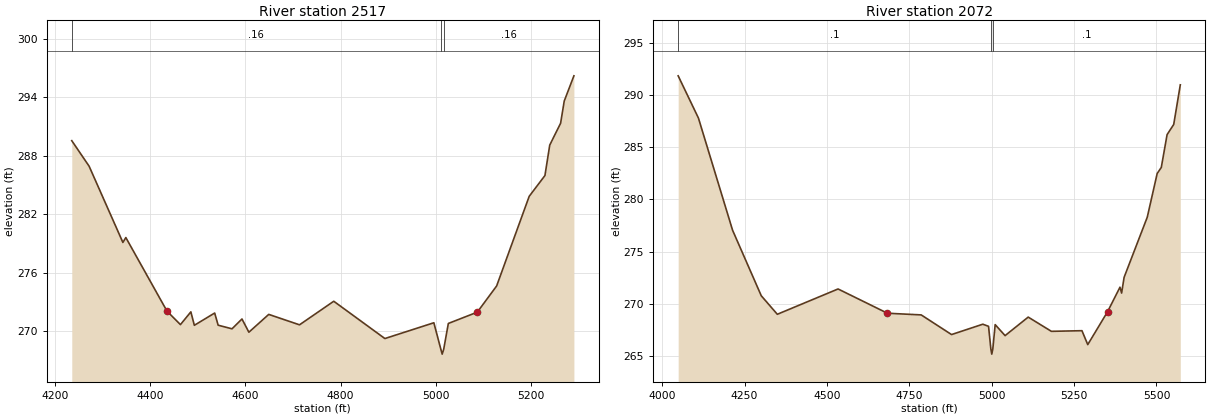
Type RM Length L Ch R = 1 ,2517    ,445,445,445
BEGIN DESCRIPTION:
UNT137 IN BECR 2.0
END DESCRIPTION:
XS GIS Cut Line= 3
      3789899.63     10512010.22      3790349.61     10512610.19
      3790649.61     10512660.19
#Sta/Elev= 30
  4235.7  289.56  4272.1  286.94    4343  279.11  4349.2  279.61  4435.7  272.05
  4463.8  270.67  4485.7  271.98    4493   270.6  4535.7  271.86    4543  270.61
  4572.1  270.24    4593  271.25  4607.5  269.89  4649.2  271.72  4713.8  270.65
  4785.7  273.07    4893  269.24  4995.8  270.86  5010.5  268.14  5013.3  267.64
  5016.5  268.14  5026.2  270.79    5087  271.95  5127.6  274.64    5196  283.85
    5229  285.98  5239.1  289.11  5261.9  291.35  5269.5  293.63  5289.8  296.22
#Mann= 3 ,-1 , 0
  4235.7     .16       0  5010.5     .07       0  5016.5     .16       0
Bank Sta=4435.7,5087
XS Rating Curve= 0 ,0
Exp/Cntr=0.3,0.1

Type RM Length L Ch R = 1 ,2072    ,0,0,0
BEGIN DESCRIPTION:
UNT137 IN BECR 1.0
END DESCRIPTION:
XS GIS Cut Line= 3
      3789849.61      10512010.2      3790049.61     10512910.19
      3790649.58     10512960.19
#Sta/Elev= 30
  4048.4  291.82  4109.9  287.78  4213.6  277.05  4300.6  270.79  4349.3  269.02
  4533.7  271.44  4683.5  269.12    4786  268.96  4878.1  267.08  4972.9  268.07
  4990.4  267.87  4997.4  265.71  5000.2  265.21  5003.4  265.71  5010.5  268.03
  5040.6  266.98  5110.8  268.75  5181.1  267.39  5273.9  267.45  5291.5  266.12
  5351.7  269.27  5389.3  271.61  5394.3  271.05  5401.8  272.55  5472.1   278.3
  5502.2  282.48  5514.7  283.06  5532.3   286.2  5552.4  287.17  5572.4  290.96
#Mann= 3 ,-1 , 0
  4048.4      .1       0  4997.4     .05       0  5003.4      .1       0
Bank Sta=4683.5,5351.7
XS Rating Curve= 0 ,0
Exp/Cntr=0.3,0.1

Chan Stop Cuts=-1
Use User Specified Reach Order=0
Composite Channel Slope=5