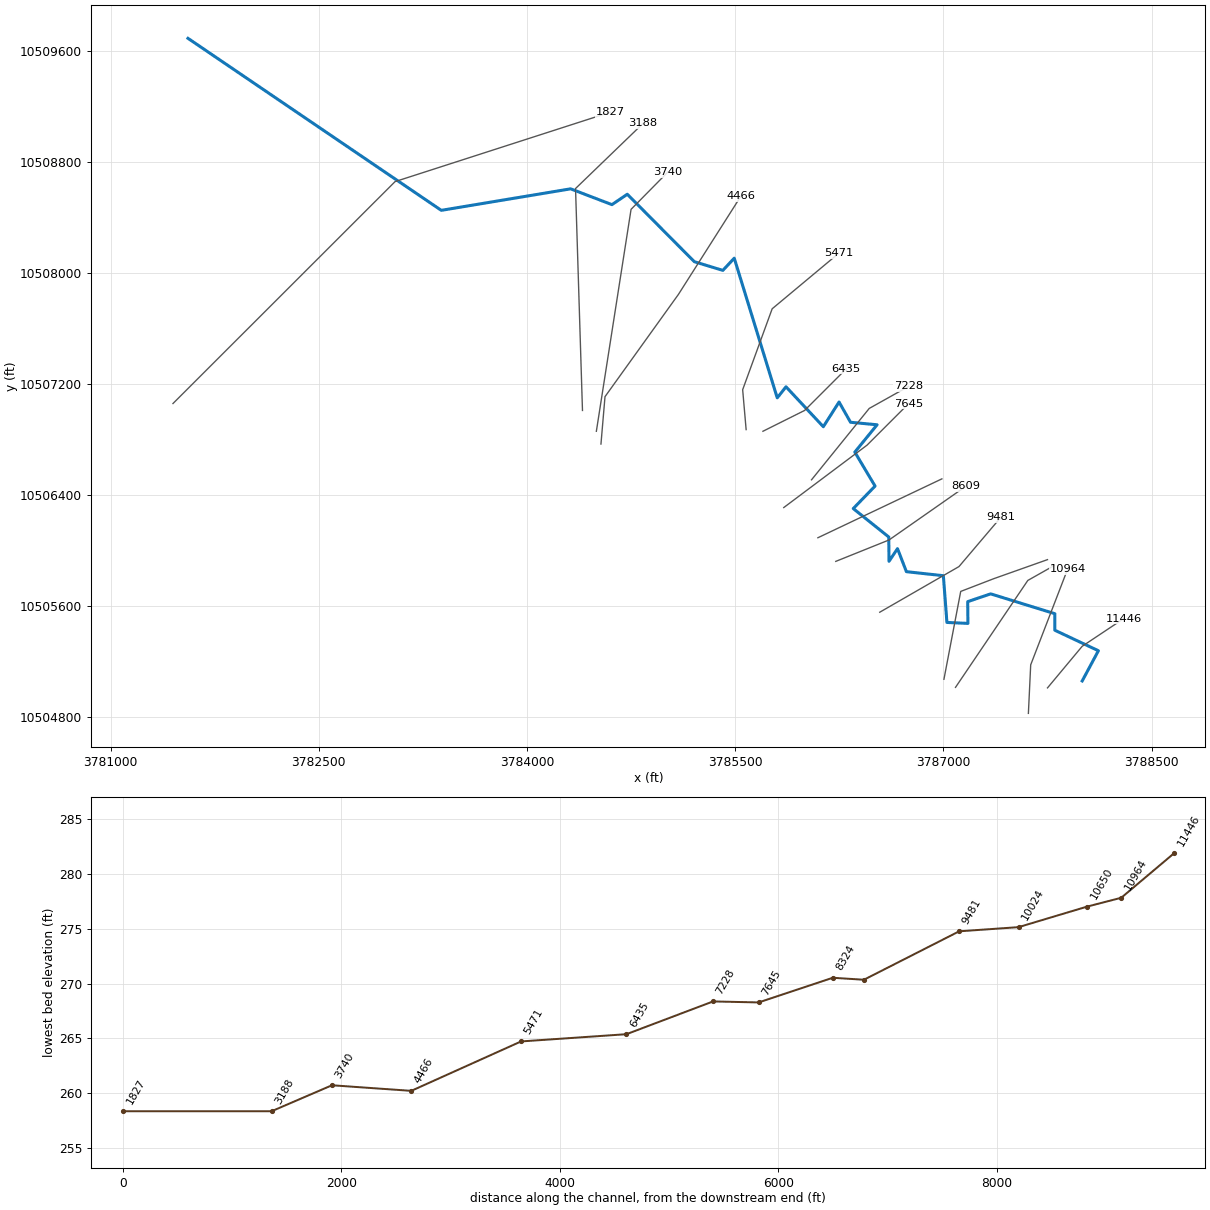
--- UNT138 IN BECR.prj (project) ---

Proj Title=UNT138 IN BECR Base Level Engineering
Current Plan=p01
Default Exp/Contr=0.3,0.1
English Units
Geom File=g01
Flow File=f01
Plan File=p01
Y Axis Title=Elevation
X Axis Title(PF)=Main Channel Distance
X Axis Title(XS)=Station
BEGIN DESCRIPTION:
UNT138 IN BECR
END DESCRIPTION:
DSS Export Rating Curves= 0
DSS Export Rating Curve Sorted= 0
DSS Export Volume Flow Curves= 0
DXF OffsetX= 0
DXF OffsetY= 0
DXF ScaleX= 1
DXF ScaleY= 10

--- UNT138 IN BECR.p01 (plan) ---

Plan Title=Multiple Run
Short Identifier=Multiple
Geom File=g01
Flow File=f01
Subcritical Flow
K Sum by GR= 0
Std Step Tol= 0.01
Critical Tol= 0.01
Num of Std Step Trials= 20
Max Error Tol= 0.3
Flow Tol Ratio= 0.001
Split Flow NTrial= 30
Split Flow Tol= 0.02
Split Flow Ratio= 0.02
Log Output Level= 0
Friction Slope Method= 1
Unsteady Friction Slope Method= 2
Unsteady Bridges Friction Slope Method= 1
Parabolic Critical Depth
Global Vel Dist=  1 , 1 , 1
Global Log Level= 0
CheckData=True
Encroach Param= -1, 0, 0, 0
BEGIN DESCRIPTION:
Multiple Run
END DESCRIPTION:

--- UNT138 IN BECR.f01 (steady flow) ---

Flow Title=Multiple
Program Version=4.10
Number of Profiles= 7
Profile Names=10-year,25-year,50-year,1pct_min,100-year,1pct_plu,500-year
River Rch & RM=UNT138 IN BECR,Reach-1         ,11446
     619     840    1023     916    1239    1675    1823
River Rch & RM=UNT138 IN BECR,Reach-1         ,4466
    1020    1420    1759    1600    2164    2927    3287
River Rch & RM=UNT138 IN BECR,Reach-1         ,1827
    1020    1420    1759    1600    2164    2927    3287
Boundary for River Rch & Prof#=UNT138 IN BECR,Reach-1         , 1
Up Type= 0
Dn Type= 3
Dn Slope=0.0012
Boundary for River Rch & Prof#=UNT138 IN BECR,Reach-1         , 2
Up Type= 0
Dn Type= 3
Dn Slope=0.0012
Boundary for River Rch & Prof#=UNT138 IN BECR,Reach-1         , 3
Up Type= 0
Dn Type= 3
Dn Slope=0.0012
Boundary for River Rch & Prof#=UNT138 IN BECR,Reach-1         , 4
Up Type= 0
Dn Type= 3
Dn Slope=0.0012
Boundary for River Rch & Prof#=UNT138 IN BECR,Reach-1         , 5
Up Type= 0
Dn Type= 3
Dn Slope=0.0012
Boundary for River Rch & Prof#=UNT138 IN BECR,Reach-1         , 6
Up Type= 0
Dn Type= 3
Dn Slope=0.0012
Boundary for River Rch & Prof#=UNT138 IN BECR,Reach-1         , 7
Up Type= 0
Dn Type= 3
Dn Slope=0.0012
DSS Import GetInterval= 0
DSS Import GetPeak= 0
DSS Import FillOption= 0

--- UNT138 IN BECR.g01 (geometry) ---

Geom Title=Existing Conditions
Program Version=4.10

River Reach=UNT138 IN BECR  ,Reach-1
Reach XY= 30
      3787999.61     10505060.19      3788116.25       10505278.
      3787802.25       10505426.       3787802.5       10505545.
        3787340.       10505688.      3787174.75       10505632.
      3787176.25       10505475.        3787025.       10505482.
      3786999.25       10505819.      3786733.25       10505848.
        3786669.       10506014.        3786608.       10505923.
        3786606.       10506098.      3786350.25       10506303.
      3786507.25       10506465.       3786361.5       10506710.
        3786522.       10506907.      3786330.75       10506925.
        3786248.       10507071.       3786134.5       10506893.
      3785865.75       10507181.      3785802.75       10507101.
        3785493.       10508108.      3785410.75       10508020.
        3785205.       10508083.       3784722.5       10508569.
      3784611.75       10508494.       3784314.5       10508608.
       3783382.5       10508453.      3781557.75       10509693.

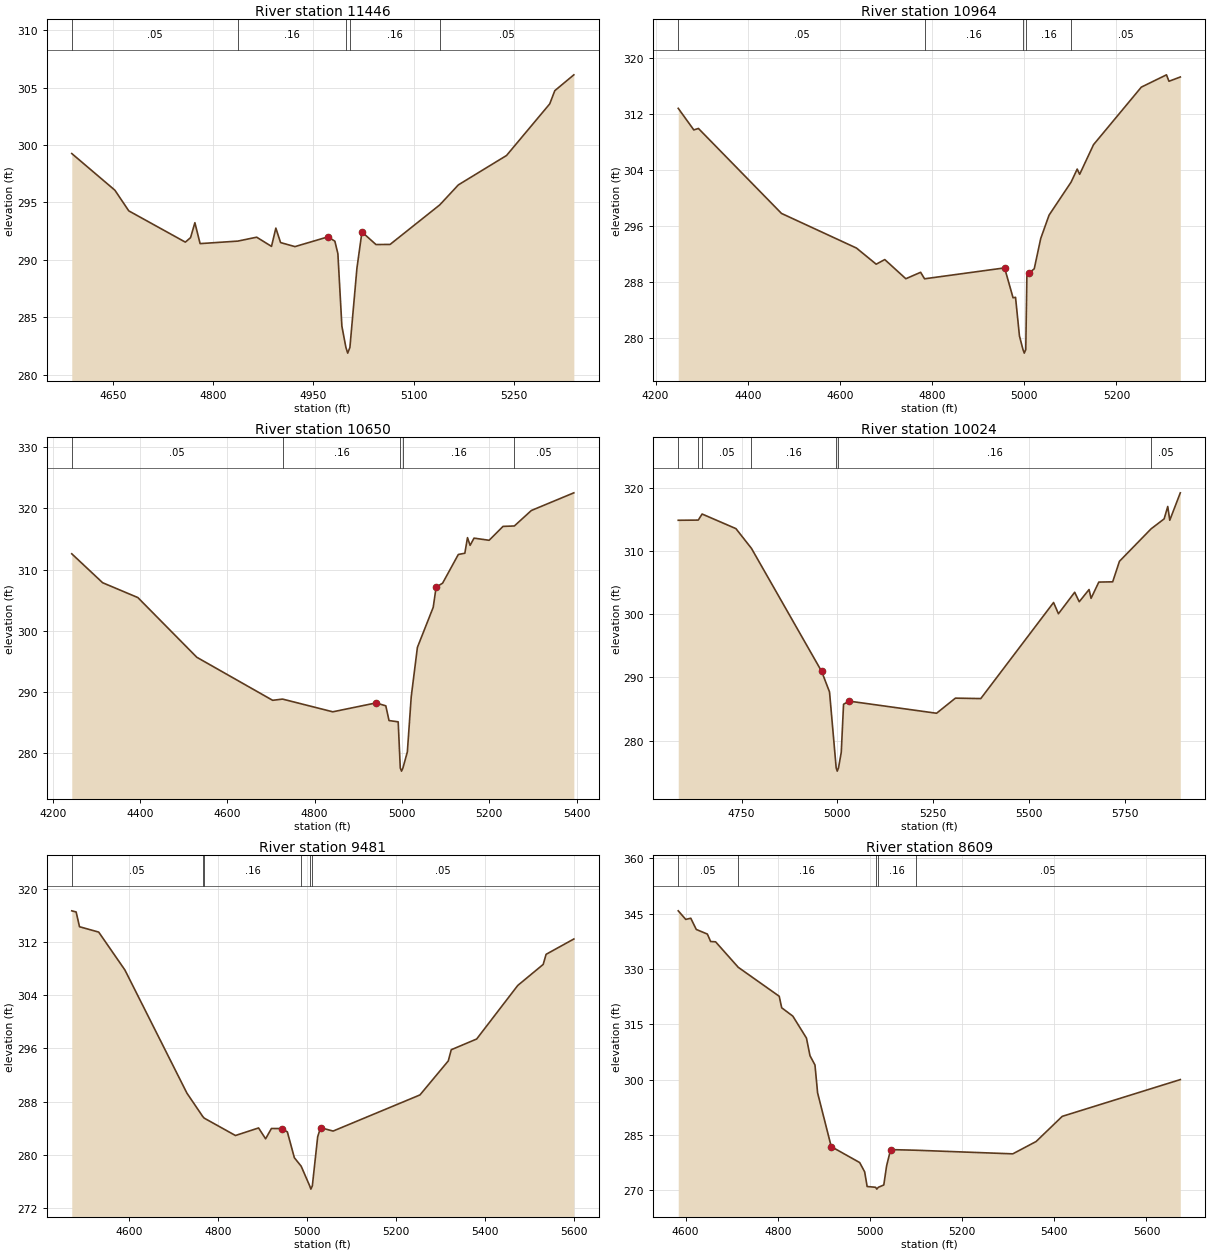
Type RM Length L Ch R = 1 ,11446   ,482,482,482
BEGIN DESCRIPTION:
UNT138 IN BECR 15.0
END DESCRIPTION:
XS GIS Cut Line= 3
      3787749.59     10505010.16      3787999.61     10505310.19
      3788299.61     10505510.19
#Sta/Elev= 30
  4588.6  299.26  4653.1  296.07  4673.9  294.27  4758.5  291.55  4766.3  291.94
  4772.8  293.24  4780.6  291.42  4837.1  291.64  4865.2  291.98  4887.4  291.18
  4893.9  292.77    4901  291.51  4922.5  291.16    4972  292.01  4982.2  291.63
  4986.7  290.55  4992.7  284.23  4998.7  282.39  5001.4  281.89  5004.7  282.39
  5015.2  289.28  5022.7  292.43  5043.7  291.34  5064.8  291.35  5139.1  294.79
  5166.9  296.53    5239  299.09  5303.6  303.58  5311.2  304.73  5339.7  306.11
#Mann= 5 ,-1 , 0
  4588.6     .05       0  4837.1     .16       0  4998.7     .07       0
  5004.7     .16       0  5139.1     .05       0
Bank Sta=4972,5022.7
XS Rating Curve= 0 ,0
Exp/Cntr=0.3,0.1

Type RM Length L Ch R = 1 ,10964   ,314,314,314
BEGIN DESCRIPTION:
UNT138 IN BECR 14.0
END DESCRIPTION:
XS GIS Cut Line= 3
      3787611.89      10504826.4      3787628.55     10505176.42
      3787894.36     10505865.84
#Sta/Elev= 30
  4249.2  312.85    4283  309.76    4293  309.97  4473.2  297.82  4635.8  292.87
  4678.7  290.56  4697.3  291.22    4743  288.48  4775.1   289.4  4783.6  288.47
  4957.3  290.03  4975.6  285.76    4981  285.82  4989.5   280.3  4997.2  278.34
    5000  277.84  5003.2  278.34  5005.6  288.78    5011  289.34  5021.6   289.9
  5035.6  294.22  5053.8  297.58  5101.5  302.29  5114.8  304.16  5120.1  303.41
  5150.2  307.65  5253.9  315.88  5308.5  317.64  5313.9  316.72  5338.5  317.33
#Mann= 5 ,-1 , 0
  4249.2     .05       0  4783.6     .16       0  4997.2     .07       0
  5003.2     .16       0  5101.5     .05       0
Bank Sta=4957.3,5011
XS Rating Curve= 0 ,0
Exp/Cntr=0.3,0.1

Type RM Length L Ch R = 1 ,10650   ,626,626,626
BEGIN DESCRIPTION:
UNT138 IN BECR 13.0
END DESCRIPTION:
XS GIS Cut Line= 3
      3787086.88     10505013.91      3787607.72     10505784.75
      3787799.41      10505893.1
#Sta/Elev= 30
  4243.4  312.57  4314.1  307.84  4394.9  305.41  4529.9  295.65  4703.7  288.61
  4726.4  288.81  4841.5  286.73  4940.4  288.18    4963  287.71  4970.4   285.3
  4991.4  285.09  4996.2  277.53    4999  277.03  5002.2  277.53  5012.4  280.18
  5021.3  289.22  5035.4  297.26  5071.7  303.83  5078.3  307.11  5093.2  307.77
  5129.2  312.46  5144.1  312.66  5150.2  315.21  5156.2  313.95  5165.2  315.13
  5199.8  314.78  5231.6  317.05  5257.6  317.12  5296.5  319.65  5393.9  322.54
#Mann= 5 ,-1 , 0
  4243.4     .05       0  4726.4     .16       0  4996.2     .07       0
  5002.2     .16       0  5257.6     .05       0
Bank Sta=4940.4,5078.3
XS Rating Curve= 0 ,0
Exp/Cntr=0.3,0.1

Type RM Length L Ch R = 1 ,10024   ,543,543,543
BEGIN DESCRIPTION:
UNT138 IN BECR 12.0
END DESCRIPTION:
XS GIS Cut Line= 4
      3787003.56     10505072.27      3787124.39     10505705.58
      3787361.89     10505797.25       3787749.4     10505934.76
#Sta/Elev= 30
  4584.6  314.82  4636.9  314.85  4646.9  315.81  4735.2   313.5  4775.7  310.38
  4958.9  290.93  4979.5  287.68  4996.9  275.66  4999.6  275.16  5002.9  275.66
  5010.1  278.13  5016.1  285.73  5030.4  286.23  5258.9  284.31  5308.1   286.7
  5374.3  286.63  5564.3  301.82    5577  300.04  5619.4  303.44  5631.3  301.94
  5656.9  303.87  5662.2  302.48  5682.4  305.05  5718.6  305.09  5736.2  308.33
  5818.9  313.47  5852.9  315.04  5862.3     317  5867.6  314.83  5895.1  319.16
#Mann= 7 ,-1 , 0
  4584.6     .05       0  4636.9     .16       0  4646.9     .05       0
  4775.7     .16       0  4996.9     .07       0  5002.9     .16       0
  5818.9     .05       0
Bank Sta=4958.9,5030.4
XS Rating Curve= 0 ,0
Exp/Cntr=0.3,0.1

Type RM Length L Ch R = 1 ,9481    ,872,872,872
BEGIN DESCRIPTION:
UNT138 IN BECR 11.0
END DESCRIPTION:
XS GIS Cut Line= 3
      3786541.08      10505555.6      3787111.89     10505884.75
      3787415.32     10506242.22
#Sta/Elev= 30
  4471.8  316.77  4481.6   316.6  4489.2  314.37  4532.3  313.56  4591.2  307.84
  4730.5  289.26  4765.8  285.76  4769.1   285.5  4839.5  282.87  4891.4  284.01
  4907.2  282.37  4920.3  283.93  4943.4  283.92  4956.1  283.41  4971.8  279.52
  4987.1  278.24  5006.2  275.28  5008.9  274.78  5012.2  275.28  5024.2  282.69
  5030.7  284.05  5058.8  283.54  5253.9  288.99  5317.6  294.13  5324.2  295.81
  5381.3  297.43  5473.6  305.51  5530.7  308.68  5537.3  310.21  5599.6  312.52
#Mann= 6 ,-1 , 0
  4471.8     .05       0  4765.8      .1       0  4769.1     .16       0
  4987.1     .05       0  5006.2    .035       0  5012.2     .05       0
Bank Sta=4943.4,5030.7
XS Rating Curve= 0 ,0
Exp/Cntr=0.3,0.1

Type RM Length L Ch R = 1 ,8609    ,285,285,285
BEGIN DESCRIPTION:
UNT138 IN BECR 10.0
END DESCRIPTION:
XS GIS Cut Line= 3
      3786224.35     10505922.23      3786607.72     10506076.42
      3787161.87      10506463.9
#Sta/Elev= 30
  4584.1  345.77  4600.5  343.44  4611.3  343.77  4623.2  340.73  4647.3  339.47
  4654.4  337.46  4665.2  337.37  4714.3  330.47  4803.2  322.62  4808.6   319.5
  4832.8  317.23  4862.3  311.29    4870  306.51  4880.8  303.99  4886.5  296.44
  4916.1  281.88  4977.8  277.56  4988.6  275.04    4994  271.07  5012.3  270.86
    5015  270.36  5018.3  270.86  5030.1  271.48  5036.2  276.65  5044.9  281.07
  5099.7   280.9    5310  279.92  5360.6  283.26  5417.3  290.08  5673.5  300.04
#Mann= 5 ,-1 , 0
  4584.1     .05       0  4714.3     .16       0  5012.3     .07       0
  5018.3     .16       0  5099.7     .05       0
Bank Sta=4916.1,5044.9
XS Rating Curve= 0 ,0
Exp/Cntr=0.3,0.1

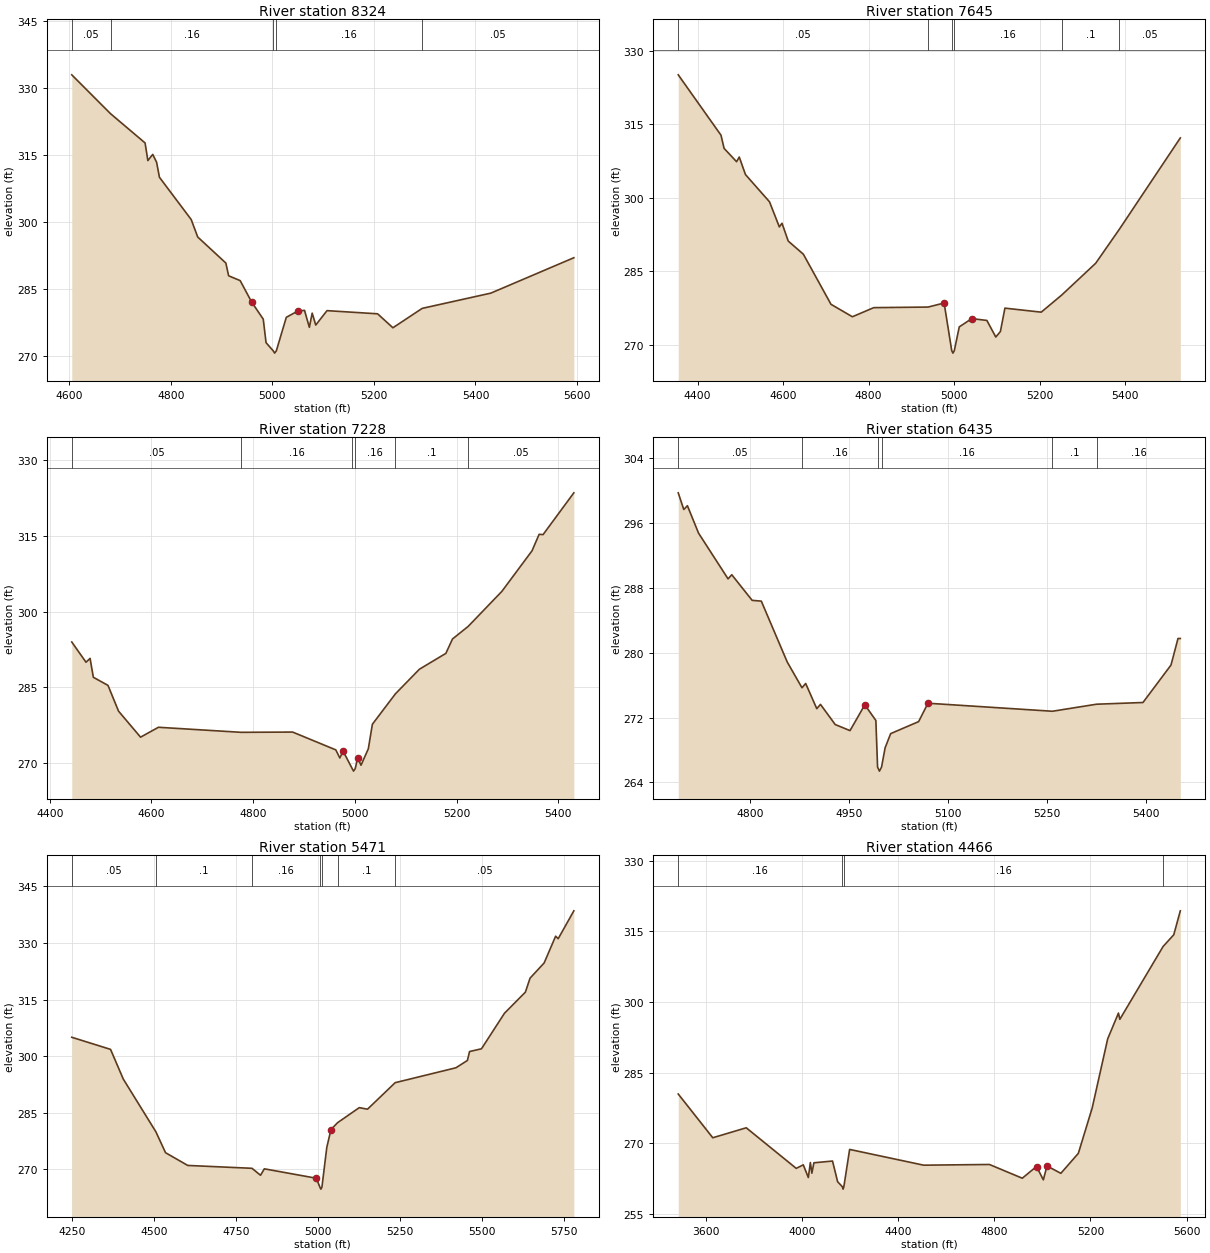
Type RM Length L Ch R = 1 ,8324    ,679,679,679
BEGIN DESCRIPTION:
UNT138 IN BECR 9.0
END DESCRIPTION:
XS GIS Cut Line= 2
      3786095.51     10506092.57      3786988.77     10506517.07
#Sta/Elev= 30
  4604.8  332.97  4681.1  324.26  4749.2  317.69  4754.7  313.74  4764.3  315.12
  4771.9  313.36  4777.5  309.99  4840.1   300.5  4852.9  296.59  4908.3  290.75
  4913.8  287.89  4936.5  286.81  4959.2  281.99    4982  278.16  4987.5  272.89
  5001.7  271.04  5004.4  270.54  5007.7  271.04  5027.4  278.57  5050.1  279.98
  5063.3  280.13  5072.8  276.33  5078.4  279.51  5085.4  276.84  5107.6  280.07
  5207.2  279.36  5237.4  276.23  5295.1  280.58  5430.3     284  5593.8  291.94
#Mann= 5 ,-1 , 0
  4604.8     .05       0  4681.1     .16       0  5001.7     .07       0
  5007.7     .16       0  5295.1     .05       0
Bank Sta=4959.2,5050.1
XS Rating Curve= 0 ,0
Exp/Cntr=0.3,0.1

Type RM Length L Ch R = 1 ,7645    ,417,417,417
BEGIN DESCRIPTION:
UNT138 IN BECR 8.0
END DESCRIPTION:
XS GIS Cut Line= 3
      3785849.61     10506310.19      3786449.61     10506760.19
      3786749.63     10507060.21
#Sta/Elev= 30
  4354.9  325.14  4454.9  312.81  4462.2  310.11  4491.4  307.39  4497.6  308.35
  4512.2  304.76  4568.4   299.2  4591.4  294.07  4597.6  294.82  4612.2  291.18
  4647.6  288.49  4712.2  278.26  4762.2  275.72  4812.2  277.58  4939.3   277.7
  4976.8  278.53  4994.6  268.79  4997.4  268.29  5000.6  268.79  5012.2  273.65
  5041.4  275.34  5076.8  274.97  5097.6  271.58  5108.4   272.7    5119  277.48
  5203.9  276.66  5251.9  280.16  5331.2  286.64  5386.6  293.59  5529.2  312.25
#Mann= 6 ,-1 , 0
  4354.9     .05       0  4939.3     .16       0  4994.6     .07       0
  5000.6     .16       0  5251.9      .1       0  5386.6     .05       0
Bank Sta=4976.8,5041.4
XS Rating Curve= 0 ,0
Exp/Cntr=0.3,0.1

Type RM Length L Ch R = 1 ,7228    ,793,793,793
BEGIN DESCRIPTION:
UNT138 IN BECR 7.0
END DESCRIPTION:
XS GIS Cut Line= 3
      3786049.58     10506510.15      3786465.32     10507024.87
      3786749.15     10507183.72
#Sta/Elev= 30
  4443.4  293.97  4471.4  289.96  4479.4  290.72  4485.8  286.98  4514.6  285.37
  4535.4  280.26  4578.6  275.11  4613.8  277.07  4776.2  276.07  4877.6  276.12
  4962.4  272.59  4970.3  270.99  4976.8  272.34  4994.6  268.88  4997.3  268.38
  5000.6  268.88  5005.5  271.04  5011.9  269.55  5026.3   272.8  5034.3  277.67
  5079.6   283.7  5126.7  288.57  5178.7  291.71  5191.8  294.57  5222.6  297.06
  5288.8     304  5348.1  312.04  5362.1  315.31  5369.8  315.25  5430.3  323.53
#Mann= 6 ,-1 , 0
  4443.4     .05       0  4776.2     .16       0  4994.6     .07       0
  5000.6     .16       0  5079.6      .1       0  5222.6     .05       0
Bank Sta=4976.8,5005.5
XS Rating Curve= 0 ,0
Exp/Cntr=0.3,0.1

Type RM Length L Ch R = 1 ,6435    ,964,964,964
BEGIN DESCRIPTION:
UNT138 IN BECR 6.0
END DESCRIPTION:
XS GIS Cut Line= 3
      3785699.64      10506860.2      3785999.61     10507010.19
      3786299.58     10507310.16
#Sta/Elev= 30
  4691.9  299.74  4700.3  297.68  4705.8  298.15  4722.6  294.77  4767.3  289.12
  4772.9  289.63  4803.7  286.47  4817.6  286.37  4856.8  278.86  4879.1  275.68
  4884.7  276.21  4901.5   273.1  4907.1  273.63  4929.4  271.14  4951.8  270.39
  4974.2  273.58  4990.9  271.64  4993.5  265.89  4996.3  265.39  4999.5  265.89
  5004.9  268.27  5013.3  270.02  5055.6   271.5  5069.7  273.77    5258  272.78
  5324.9  273.65    5395  273.86  5437.4  278.48    5448  281.76  5451.5  281.76
#Mann= 6 ,-1 , 0
  4691.9     .05       0  4879.1     .16       0  4993.5     .07       0
  4999.5     .16       0    5258      .1       0  5324.9     .16       0
Bank Sta=4974.2,5069.7
XS Rating Curve= 0 ,0
Exp/Cntr=0.3,0.1

Type RM Length L Ch R = 1 ,5471    ,1005,1005,1005
BEGIN DESCRIPTION:
UNT138 IN BECR 5.0
END DESCRIPTION:
XS GIS Cut Line= 4
      3785578.56     10506872.21      3785553.55     10507159.75
      3785766.05     10507743.08      3786244.89     10508142.81
#Sta/Elev= 30
  4248.3  304.99  4366.7  301.78  4405.6  293.91  4505.3  279.91  4534.6  274.39
  4602.5  271.01  4798.6  270.25  4824.7  268.41  4836.4  270.11    4995  267.62
  5006.2  265.23    5009  264.73  5012.2  265.23    5027  275.75  5039.8  280.52
    5060  282.34  5126.2  286.33  5151.4  285.92  5235.9  292.95  5421.4   296.9
  5456.5  298.84    5463  301.21  5499.4  301.93  5569.7  311.36  5633.5  316.95
  5647.8  320.66  5690.8  324.69  5725.9  331.79  5733.7  331.11  5781.5  338.51
#Mann= 7 ,-1 , 0
  4248.3     .05       0  4505.3      .1       0  4798.6     .16       0
  5006.2     .07       0  5012.2     .16       0    5060      .1       0
  5235.9     .05       0
Bank Sta=4995,5039.8
XS Rating Curve= 0 ,0
Exp/Cntr=0.3,0.1

Type RM Length L Ch R = 1 ,4466    ,726,726,726
BEGIN DESCRIPTION:
UNT138 IN BECR 4.0
END DESCRIPTION:
XS GIS Cut Line= 4
      3784532.72     10506768.12      3784561.89     10507109.75
      3785091.05     10507847.25      3785540.91     10508555.36
#Sta/Elev= 30
  3484.6  280.44  3628.3  271.14  3767.7  273.26  3975.7  264.63  4005.1  265.38
    4026  262.69  4034.5  265.87  4040.7  263.61  4049.3  265.82  4126.7  266.19
    4148  261.79  4167.8  260.72  4170.6  260.22  4173.8  260.72  4197.9  268.66
  4506.1  265.31  4779.6  265.46  4916.4  262.54  4975.6  265.03  5004.1   262.2
  5019.3  265.15  5076.9  263.58  5149.7  267.82  5207.3  277.46  5271.8  292.15
  5316.6  297.64  5322.5  296.32  5502.6  311.81  5546.9  314.29  5574.1  319.38
#Mann= 4 ,-1 , 0
  3484.6     .16       0  4167.8     .07       0  4173.8     .16       0
  5502.6     .05       0
Bank Sta=4975.6,5019.3
XS Rating Curve= 0 ,0
Exp/Cntr=0.3,0.1

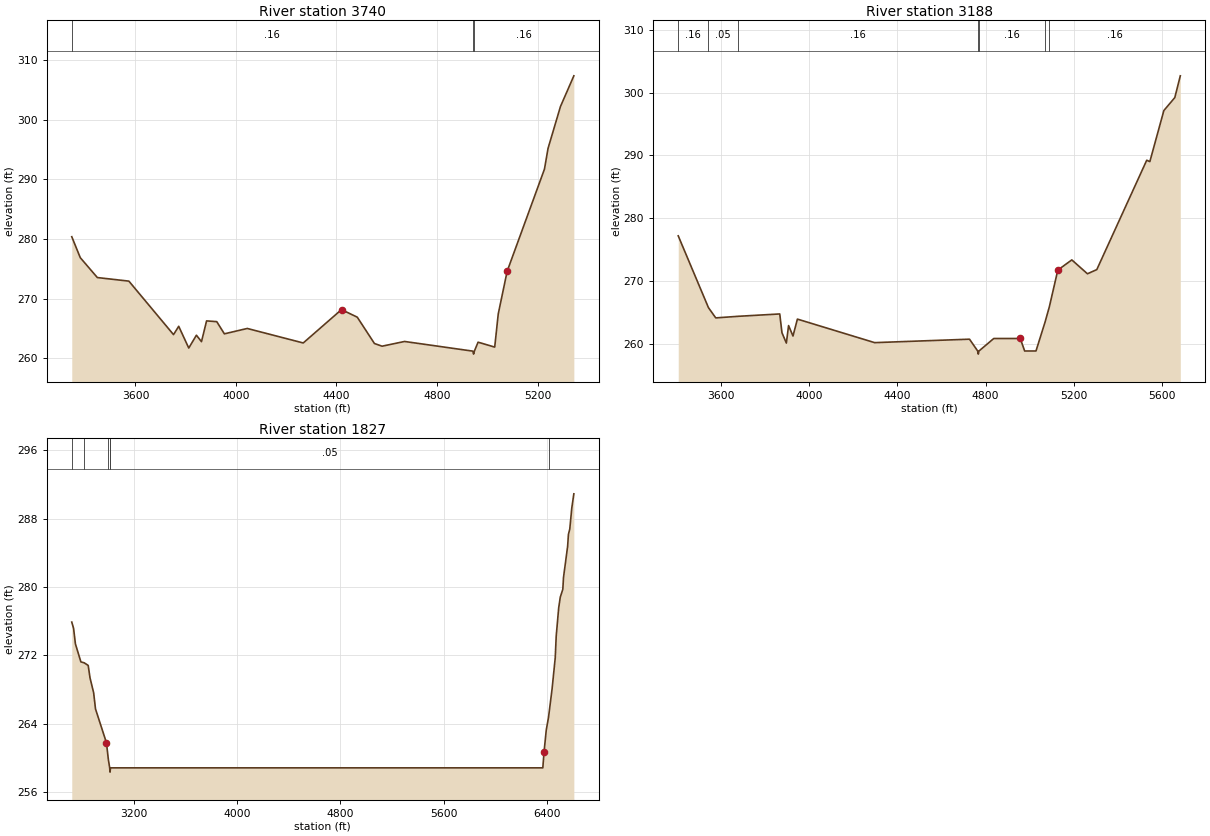
Type RM Length L Ch R = 1 ,3740    ,552,552,552
BEGIN DESCRIPTION:
UNT138 IN BECR 3.0
END DESCRIPTION:
XS GIS Cut Line= 3
       3784499.6     10506860.15      3784749.61     10508460.19
       3785015.3     10508729.82
#Sta/Elev= 30
  3346.6   280.4  3380.5  276.89  3448.4  273.56  3573.9  272.96  3751.5     264
  3772.2  265.39  3812.2  261.75  3842.6   263.9  3862.8  262.82  3883.1   266.3
  3923.6  266.17  3953.9  264.13    4045  265.03  4267.7   262.6    4420  268.19
  4482.8  266.92  4551.1  262.51  4581.4  262.06    4671  262.85  4942.8  261.23
  4945.6  260.73  4948.8  261.23  4963.5  262.73  5029.7  261.91  5043.8  267.47
  5079.2  274.61  5227.7  291.73  5241.9   295.2  5291.3  302.21  5344.6  307.36
#Mann= 3 ,-1 , 0
  3346.6     .16       0  4942.8     .07       0  4948.8     .16       0
Bank Sta=4420,5079.2
XS Rating Curve= 0 ,0
Exp/Cntr=0.3,0.1

Type RM Length L Ch R = 1 ,3188    ,1361,1361,1361
BEGIN DESCRIPTION:
UNT138 IN BECR 2.0
END DESCRIPTION:
XS GIS Cut Line= 3
      3784399.61     10507010.14      3784349.61     10508610.19
      3784835.73     10509079.47
#Sta/Elev= 30
  3406.6   277.2  3543.7  265.76  3576.7  264.13  3676.4  264.38  3866.9  264.76
  3876.9  261.77  3896.9  260.12  3906.9  262.91  3926.9  261.24  3946.9  263.94
  4297.1  260.19  4727.3  260.74  4764.3  258.86  4767.1  258.36  4770.3  258.86
  4837.3  260.85  4957.4  260.85  4977.4  258.86  5028.7  258.86  5069.9  263.47
  5089.3   265.9  5127.7  271.75  5191.2  273.37    5262  271.16  5304.4  271.82
  5530.8  289.24    5545  289.03  5608.5  297.16  5658.1  299.22  5683.1  302.69
#Mann= 7 ,-1 , 0
  3406.6     .16       0  3543.7     .05       0  3676.4     .16       0
  4764.3     .07       0  4770.3     .16       0  5069.9     .05       0
  5089.3     .16       0
Bank Sta=4957.4,5127.7
XS Rating Curve= 0 ,0
Exp/Cntr=0.3,0.1

Type RM Length L Ch R = 1 ,1827    ,0,0,0
BEGIN DESCRIPTION:
UNT138 IN BECR 1.0
END DESCRIPTION:
XS GIS Cut Line= 3
       3781449.6     10507060.18      3783049.61     10508660.19
      3784599.61     10509160.19
#Sta/Elev= 30
  2717.3   275.9  2731.5  275.16  2745.6  273.35    2788  271.25  2813.5  271.14
  2844.6  270.84  2858.7  269.39    2887  267.63  2901.2  265.75    2986   261.8
  3001.6  259.75  3011.3  258.86    3014  258.36  3017.3  258.86  6368.3  258.86
  6377.5  260.69  6395.1   263.3  6412.3  264.75  6440.6  268.16  6464.5  271.74
  6472.1  274.28  6491.3  277.57  6503.6  278.82  6523.3  279.74  6528.6  281.13
  6560.6  284.77  6566.7  286.16  6577.2  286.78  6592.7  289.23  6608.7   290.9
#Mann= 6 ,-1 , 0
  2717.3      .1       0  2813.5     .16       0  3001.6     .05       0
  3011.3    .033       0  3017.3     .05       0  6412.3     .16       0
Bank Sta=2986,6377.5
XS Rating Curve= 0 ,0
Exp/Cntr=0.3,0.1

Chan Stop Cuts=-1
Use User Specified Reach Order=0
Composite Channel Slope=5