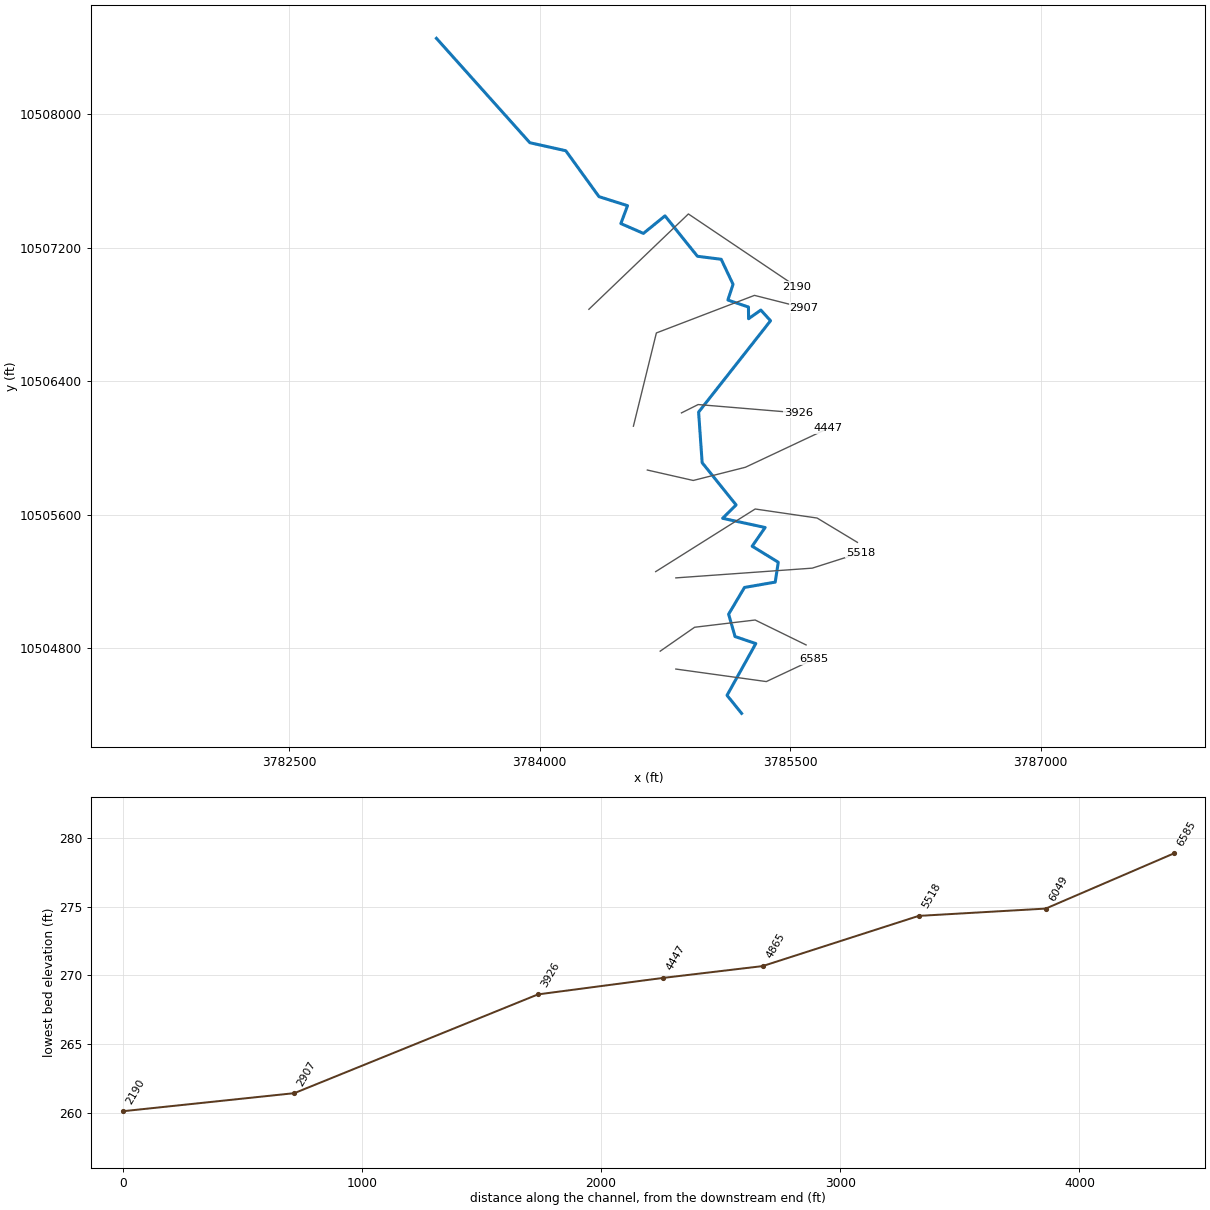
--- UNT139 IN BECR.prj (project) ---

Proj Title=UNT139 IN BECR Base Level Engineering
Current Plan=p01
Default Exp/Contr=0.3,0.1
English Units
Geom File=g01
Flow File=f01
Plan File=p01
BEGIN DESCRIPTION:
UNT139 IN BECR
END DESCRIPTION:

--- UNT139 IN BECR.p01 (plan) ---

Plan Title=Multiple Run
Short Identifier=Multiple
Geom File=g01
Flow File=f01
Subcritical Flow
K Sum by GR= 0
Std Step Tol= 0.01
Critical Tol= 0.01
Num of Std Step Trials= 20
Max Error Tol= 0.3
Flow Tol Ratio= 0.001
Split Flow NTrial= 30
Split Flow Tol= 0.02
Split Flow Ratio= 0.02
Log Output Level= 0
Friction Slope Method= 1
Unsteady Friction Slope Method= 2
Unsteady Bridges Friction Slope Method= 1
Parabolic Critical Depth
Global Vel Dist=  1 , 1 , 1
Global Log Level= 0
CheckData=True
Encroach Param= -1, 0, 0, 0
BEGIN DESCRIPTION:
Multiple Run
END DESCRIPTION:

--- UNT139 IN BECR.f01 (steady flow) ---

Flow Title=Multiple
Number of Profiles=7
Profile Names=10-year,25-year,50-year,1pct_min,100-year,1pct_plu,500-year
River Rch & RM= UNT139 IN BECR,Reach-1,6585
     501     665     799     706     954    1290    1364
Boundary for River Rch & Prof#=UNT139 IN BECR,Reach-1,1
Up Type=0
Dn Type=3
Dn Slope=0.005
Boundary for River Rch & Prof#=UNT139 IN BECR,Reach-1,2
Up Type=0
Dn Type=3
Dn Slope=0.005
Boundary for River Rch & Prof#=UNT139 IN BECR,Reach-1,3
Up Type=0
Dn Type=3
Dn Slope=0.005
Boundary for River Rch & Prof#=UNT139 IN BECR,Reach-1,4
Up Type=0
Dn Type=3
Dn Slope=0.005
Boundary for River Rch & Prof#=UNT139 IN BECR,Reach-1,5
Up Type=0
Dn Type=3
Dn Slope=0.005
Boundary for River Rch & Prof#=UNT139 IN BECR,Reach-1,6
Up Type=0
Dn Type=3
Dn Slope=0.005
Boundary for River Rch & Prof#=UNT139 IN BECR,Reach-1,7
Up Type=0
Dn Type=3
Dn Slope=0.005

--- UNT139 IN BECR.g01 (geometry) ---

Geom Title=Existing Conditions

River Reach=UNT139 IN BECR,Reach-1
Reach XY= 30
      3785209.75     10504411.00      3785122.50     10504519.00
      3785294.75     10504829.00      3785170.50     10504871.00
      3785132.00     10505005.00      3785227.00     10505165.00
      3785411.00     10505197.00      3785429.25     10505316.00
      3785273.00     10505412.00      3785350.50     10505524.00
      3785096.00     10505579.00      3785176.75     10505659.00
      3784973.50     10505912.00      3784952.25     10506215.00
      3785383.00     10506762.00      3785324.75     10506826.00
      3785251.50     10506774.00      3785250.75     10506844.00
      3785127.50     10506886.00      3785158.50     10506980.00
      3785087.50     10507130.00      3784945.25     10507148.00
      3784751.00     10507390.00      3784621.75     10507285.00
      3784486.75     10507344.00      3784526.75     10507451.00
      3784355.75     10507505.00      3784157.00     10507780.00
      3783941.75     10507828.00      3783382.50     10508453.00

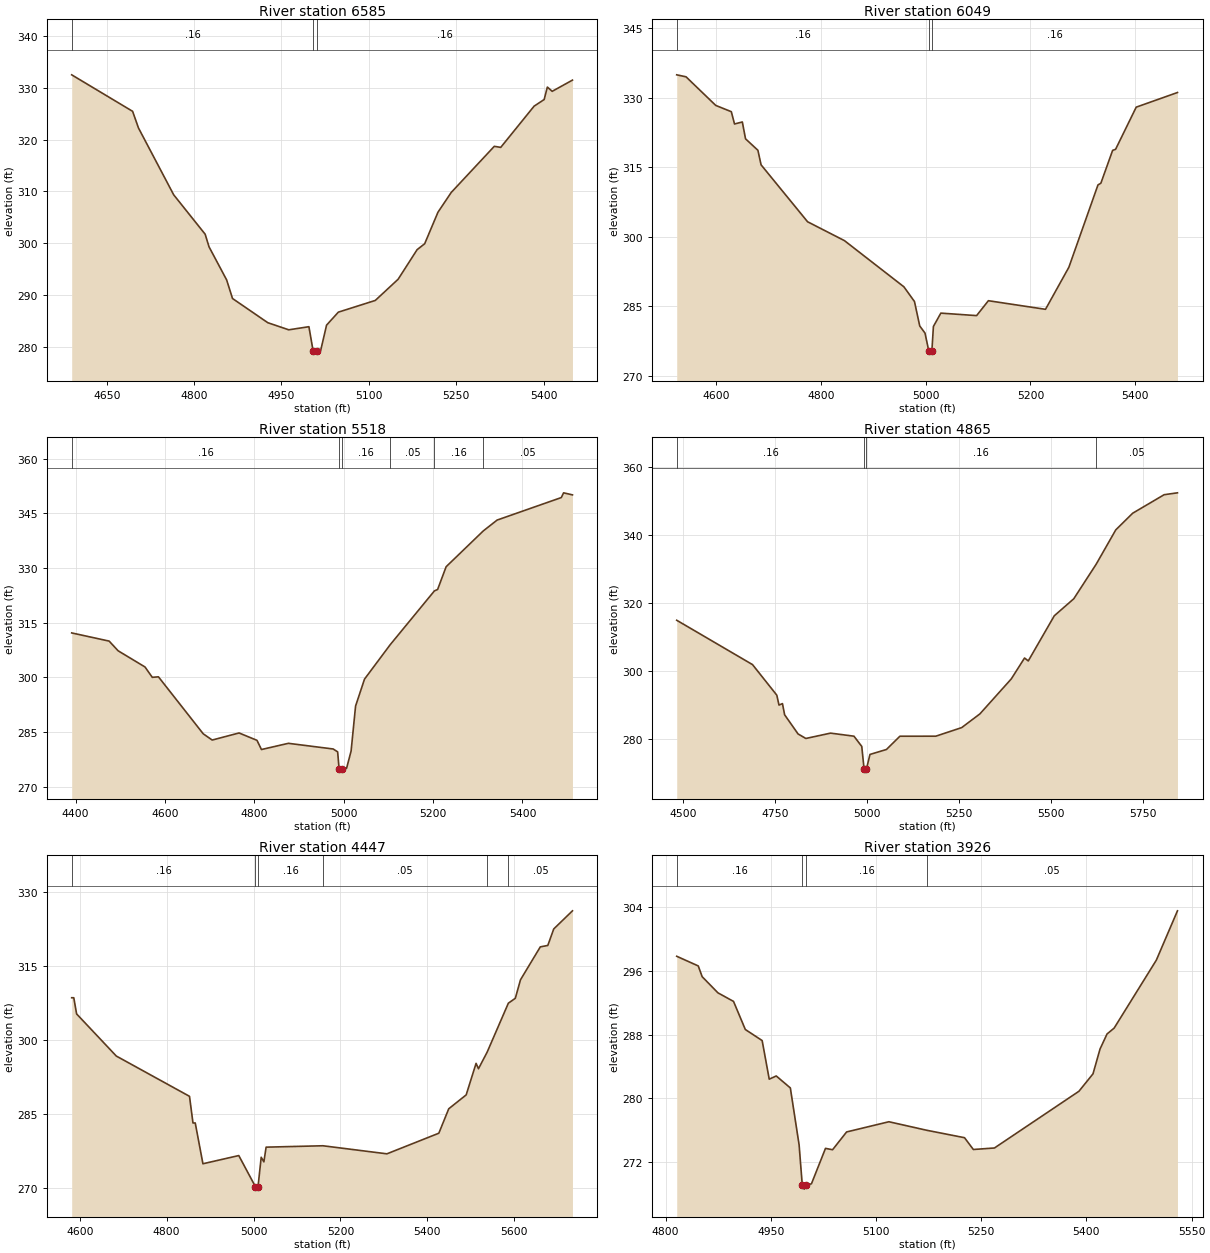
Type RM Length L Ch R = 1,6585,536,536,536
BEGIN DESCRIPTION:
UNT139 IN BECR 7.0
END DESCRIPTION:
XS GIS Cut Line= 3
      3784816.03     10504676.42      3785357.72     10504601.42
      3785641.05     10504734.75
#Sta/Elev= 30
  4589.7  332.46  4694.3  325.43  4704.4  322.22  4764.9  309.34  4818.9  301.76
  4825.5  299.34  4855.8  292.95  4865.9  289.37  4926.5  284.71  4962.5  283.34
  4997.1  283.94  5004.2  279.35  5007.0  278.85  5010.2  279.35  5017.3  279.37
  5027.4  284.24  5047.6  286.74  5111.1  289.00  5150.3  293.08  5182.9  298.78
  5195.9  299.92  5218.7  305.99  5241.5  309.80  5315.5  318.69  5326.5  318.48
  5383.8  326.42  5401.1  327.70  5406.6  330.10  5414.9  329.28  5449.7  331.44
#Mann=3,-1,0
  4589.7    0.16       0  5004.2    0.07       0  5010.2    0.16       0
Bank Sta=5004.2,5010.2
Exp/Cntr=0.3,0.1

Type RM Length L Ch R = 1,6049,531,531,531
BEGIN DESCRIPTION:
UNT139 IN BECR 6.0
END DESCRIPTION:
XS GIS Cut Line= 4
      3784722.26     10504783.46      3784928.41     10504926.68
      3785290.82     10504970.08      3785595.75     10504820.86
#Sta/Elev= 30
  4525.0  334.95  4542.8  334.52  4599.5  328.34  4629.2  326.99  4635.3  324.33
  4650.2  324.77  4656.3  321.13  4679.9  318.66  4686.0  315.51  4774.7  303.22
  4845.1  299.14  4958.5  289.17  4978.7  285.99  4988.7  280.72  4998.8  279.17
  5005.9  275.35  5008.6  274.85  5011.9  275.35  5014.8  280.61  5029.0  283.49
  5097.2  282.95  5119.7  286.17  5228.7  284.31  5273.3  293.40  5328.8  311.17
  5334.3  311.54  5356.8  318.64  5362.4  318.86  5401.8  327.97  5480.5  331.13
#Mann=3,-1,0
  4525.0    0.16       0  5005.9    0.07       0  5011.9    0.16       0
Bank Sta=5005.9,5011.9
Exp/Cntr=0.3,0.1

Type RM Length L Ch R = 1,5518,653,653,653
BEGIN DESCRIPTION:
UNT139 IN BECR 5.0
END DESCRIPTION:
XS GIS Cut Line= 3
      3784816.05     10505222.25      3785632.72     10505280.58
      3785920.21     10505372.25
#Sta/Elev= 30
  4391.4  312.20  4475.2  309.96  4495.2  307.31  4555.4  302.87  4571.7  300.03
  4585.5  300.17  4685.7  284.55  4705.8  282.84  4765.9  284.78  4806.0  282.76
  4816.0  280.24  4876.2  281.94  4976.4  280.39  4986.5  279.60  4989.8  274.82
  4992.5  274.32  4995.8  274.82  5006.5  275.11  5016.6  279.83  5026.6  292.16
  5046.6  299.54  5104.2  308.99  5203.0  323.72  5210.2  324.11  5229.2  330.34
  5312.3  340.15  5343.3  343.13  5486.9  349.30  5492.1  350.60  5511.9  350.04
#Mann=6,-1,0
  4391.4    0.16       0  4989.8    0.07       0  4995.8    0.16       0
  5104.2    0.05       0  5203.0    0.16       0  5312.3    0.05       0
Bank Sta=4989.8,4995.8
Exp/Cntr=0.3,0.1

Type RM Length L Ch R = 1,4865,418,418,418
BEGIN DESCRIPTION:
UNT139 IN BECR 4.0
END DESCRIPTION:
XS GIS Cut Line= 4
      3784695.23     10505259.75      3785291.05     10505634.75
      3785661.89     10505580.58      3785903.18     10505434.98
#Sta/Elev= 30
  4483.0  314.99  4689.0  301.96  4755.0  292.98  4760.9  290.08  4770.3  290.51
  4776.2  287.23  4812.7  281.60  4833.9  280.27  4901.0  281.84  4964.6  280.94
  4985.8  277.93  4992.2  271.18  4995.0  270.68  4998.2  271.18  5008.1  275.58
  5052.9  277.04  5089.4  280.93  5187.0  280.94  5257.3  283.46  5306.8  287.49
  5392.1  297.77  5428.1  303.90  5438.2  303.04  5508.9  316.30  5561.8  321.29
  5622.8  331.46  5675.9  341.52  5721.9  346.42  5807.4  351.86  5843.6  352.41
#Mann=4,-1,0
  4483.0    0.16       0  4992.2    0.07       0  4998.2    0.16       0
  5622.8    0.05       0
Bank Sta=4992.2,4998.2
Exp/Cntr=0.3,0.1

Type RM Length L Ch R = 1,4447,521,521,521
BEGIN DESCRIPTION:
UNT139 IN BECR 3.0
END DESCRIPTION:
XS GIS Cut Line= 4
      3784645.24     10505868.08      3784920.22     10505805.58
      3785232.72     10505884.75      3785728.59     10506118.10
#Sta/Elev= 30
  4581.6  308.53  4586.4  308.53  4592.9  305.26  4684.2  296.74  4852.7  288.59
  4860.7  283.20  4865.9  283.20  4883.6  274.95  4966.1  276.61  5004.4  270.32
  5007.1  269.82  5010.4  270.32  5017.7  276.27  5023.9  275.34  5029.0  278.31
  5159.7  278.59  5307.0  276.96  5426.5  281.13  5449.3  286.07  5489.4  288.88
  5512.2  295.26  5517.7  294.17  5537.8  297.55  5586.5  307.43  5602.5  308.42
  5614.4  312.16  5660.0  318.82  5677.3  319.11  5690.9  322.44  5734.0  326.11
#Mann=6,-1,0
  4581.6    0.16       0  5004.4    0.07       0  5010.4    0.16       0
  5159.7    0.05       0  5537.8    0.16       0  5586.5    0.05       0
Bank Sta=5004.4,5010.4
Exp/Cntr=0.3,0.1

Type RM Length L Ch R = 1,3926,1019,1019,1019
BEGIN DESCRIPTION:
UNT139 IN BECR 2.0
END DESCRIPTION:
XS GIS Cut Line= 3
      3784849.62     10506210.19      3784949.61     10506260.19
      3785549.64     10506210.19
#Sta/Elev= 30
  4815.9  297.83  4846.6  296.62  4852.2  295.27  4874.6  293.25  4896.9  292.17
  4913.7  288.65  4937.7  287.26  4947.8  282.42  4957.8  282.82  4977.9  281.32
  4990.4  274.17  4994.9  269.13  4997.7  268.63  5000.9  269.13  5008.0  269.30
  5028.0  273.74  5038.1  273.57  5058.1  275.80  5118.4  277.08  5172.4  276.01
  5226.2  275.08  5238.8  273.60  5268.9  273.79  5389.3  280.90  5409.4  283.09
  5419.4  286.20  5429.4  288.09  5439.5  288.82  5499.7  297.35  5529.8  303.53
#Mann=4,-1,0
  4815.9    0.16       0  4994.9    0.07       0  5000.9    0.16       0
  5172.4    0.05       0
Bank Sta=4994.9,5000.9
Exp/Cntr=0.3,0.1

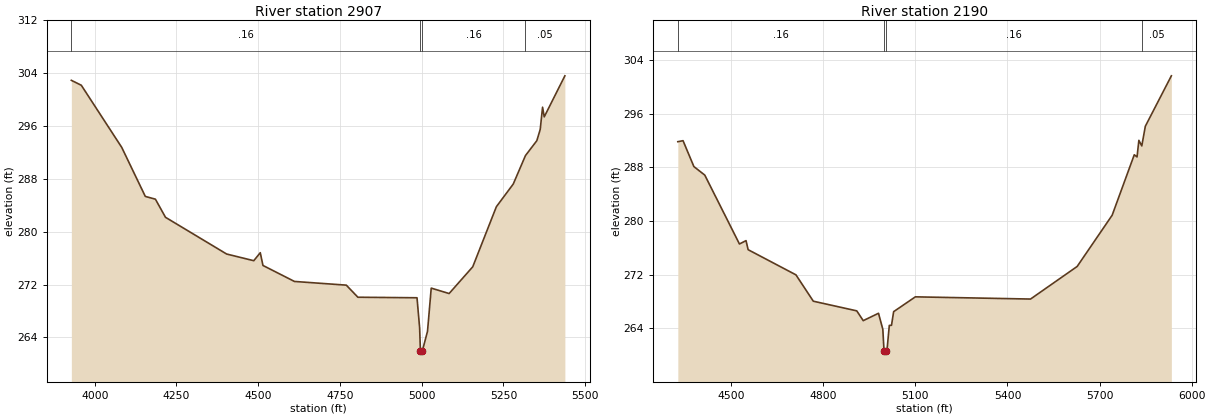
Type RM Length L Ch R = 1,2907,717,717,717
BEGIN DESCRIPTION:
Mapping XS e6d28964
END DESCRIPTION:
XS GIS Cut Line= 4
      3784561.89     10506130.59      3784699.39     10506688.92
      3785286.89     10506913.92      3785582.71     10506838.92
#Sta/Elev= 30
  3928.5  302.91  3959.0  302.16  4082.6  292.76  4154.7  285.34  4185.6  284.92
  4216.4  282.18  4403.4  276.62  4486.4  275.61  4506.3  276.82  4514.5  274.89
  4610.8  272.47  4769.4  271.91  4804.8  270.08  4985.6  270.00  4993.7  265.40
  4996.0  261.97  4998.8  261.47  5002.0  261.97  5017.7  264.92  5029.1  271.46
  5083.8  270.64  5156.1  274.69  5228.3  283.78  5279.9  287.21  5317.3  291.52
  5352.1  293.78  5362.4  295.48  5369.6  298.84  5374.7  297.38  5437.8  303.59
#Mann=4,-1,0
  3928.5    0.16       0  4996.0    0.07       0  5002.0    0.16       0
  5317.3    0.05       0
Bank Sta=4996,5002
Exp/Cntr=0.3,0.1

Type RM Length L Ch R = 1,2190,0,0,0
BEGIN DESCRIPTION:
UNT139 IN BECR 1.0
END DESCRIPTION:
XS GIS Cut Line= 3
      3784295.24     10506830.60      3784891.05     10507401.42
      3785540.10     10506964.56
#Sta/Elev= 30
  4326.4  291.83  4343.4  291.98  4378.7  288.12  4414.2  286.85  4527.1  276.58
  4548.5  277.08  4555.4  275.73  4711.1  271.98  4767.7  268.05  4909.2  266.61
  4930.3  265.15  4980.0  266.25  4994.1  263.86  4998.0  260.66  5000.8  260.16
  5004.0  260.66  5008.3  261.06  5015.2  264.44  5022.4  264.46  5029.3  266.49
  5100.1  268.70  5475.2  268.37  5627.1  273.23  5741.1  280.87  5813.1  289.88
  5822.1  289.56  5828.1  292.03  5837.6  291.20  5849.1  294.13  5933.9  301.65
#Mann=4,-1,0
  4326.4    0.16       0  4998.0    0.07       0  5004.0    0.16       0
  5837.6    0.05       0
Bank Sta=4998,5004
Exp/Cntr=0.3,0.1

Chan Stop Cuts=-1