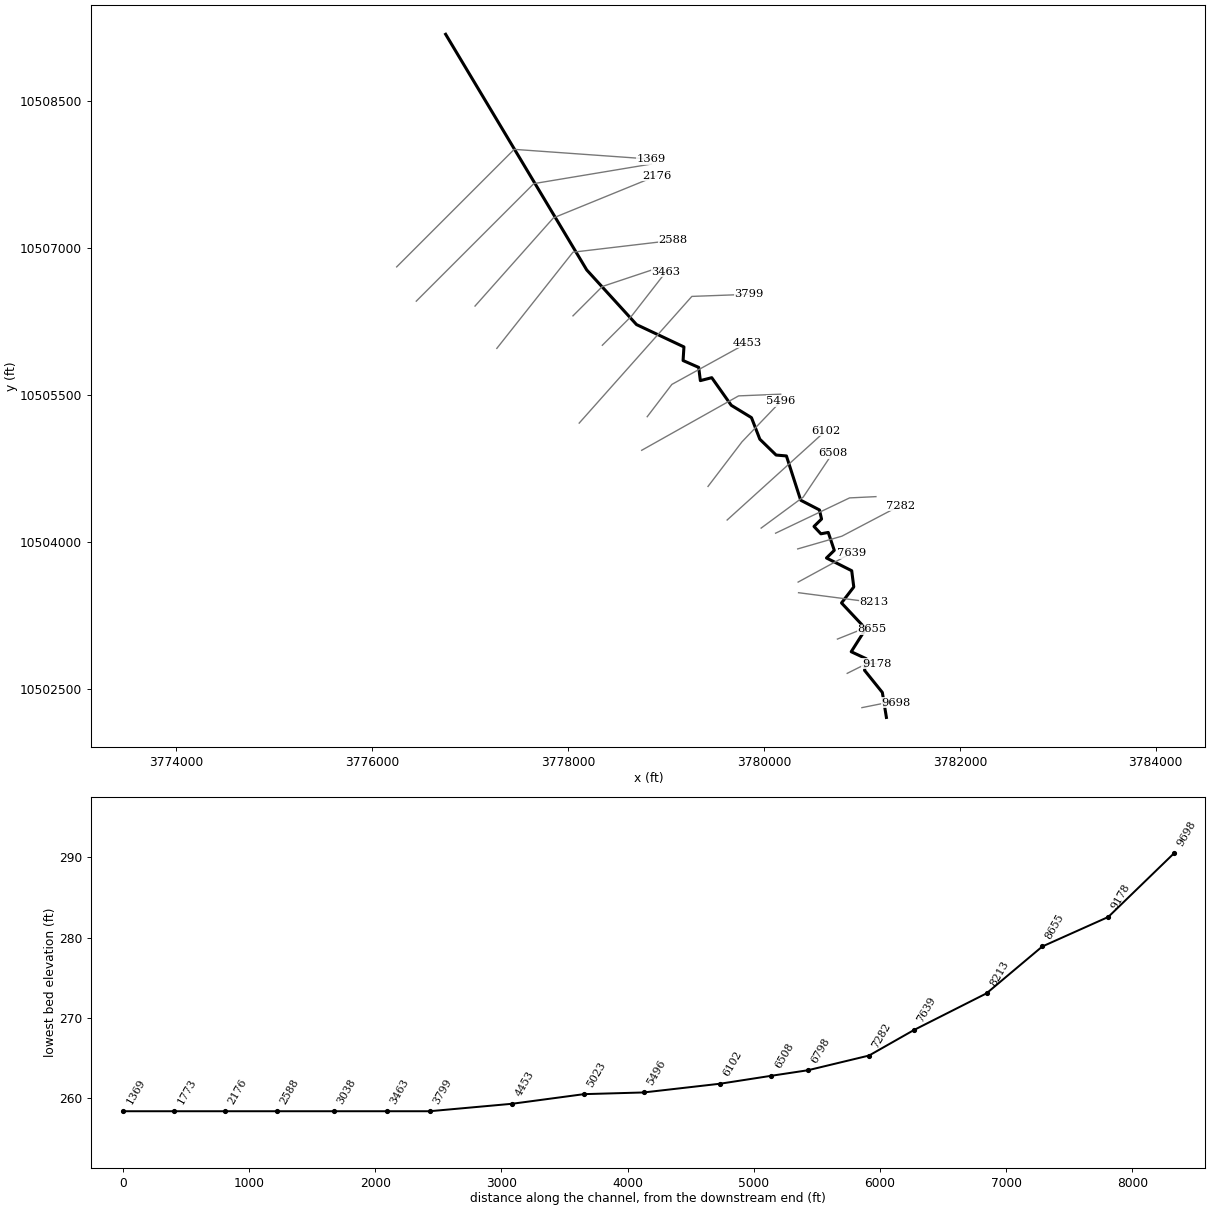
--- UNT140 IN BECR.prj (project) ---

Proj Title=UNT140 IN BECR Base Level Engineering
Current Plan=p01
Default Exp/Contr=0.3,0.1
English Units
Geom File=g01
Flow File=f01
Plan File=p01
Y Axis Title=Elevation
X Axis Title(PF)=Main Channel Distance
X Axis Title(XS)=Station
BEGIN DESCRIPTION:
UNT140 IN BECR
END DESCRIPTION:
DSS Export Rating Curves= 0
DSS Export Rating Curve Sorted= 0
DSS Export Volume Flow Curves= 0
DXF OffsetX= 0
DXF OffsetY= 0
DXF ScaleX= 1
DXF ScaleY= 10

--- UNT140 IN BECR.p01 (plan) ---

Plan Title=Multiple Run
Short Identifier=Multiple
Geom File=g01
Flow File=f01
Subcritical Flow
K Sum by GR= 0
Std Step Tol= 0.01
Critical Tol= 0.01
Num of Std Step Trials= 20
Max Error Tol= 0.3
Flow Tol Ratio= 0.001
Split Flow NTrial= 30
Split Flow Tol= 0.02
Split Flow Ratio= 0.02
Log Output Level= 0
Friction Slope Method= 1
Unsteady Friction Slope Method= 2
Unsteady Bridges Friction Slope Method= 1
Parabolic Critical Depth
Global Vel Dist=  1 , 1 , 1
Global Log Level= 0
CheckData=True
Encroach Param= -1, 0, 0, 0
BEGIN DESCRIPTION:
Multiple Run
END DESCRIPTION:

--- UNT140 IN BECR.f01 (steady flow) ---

Flow Title=Multiple
Program Version=4.10
Number of Profiles= 7
Profile Names=10-year,25-year,50-year,1pct_min,100-year,1pct_plu,500-year
River Rch & RM=UNT140 IN BECR,Reach-1         ,9698
     273     354     418     364     492     666     684
River Rch & RM=UNT140 IN BECR,Reach-1         ,7282
     612     826    1002     894    1209    1635    1763
River Rch & RM=UNT140 IN BECR,Reach-1         ,6798
     612     826    1002     894    1209    1635    1763
Boundary for River Rch & Prof#=UNT140 IN BECR,Reach-1         , 1
Up Type= 0
Dn Type= 3
Dn Slope=0.001
Boundary for River Rch & Prof#=UNT140 IN BECR,Reach-1         , 2
Up Type= 0
Dn Type= 3
Dn Slope=0.001
Boundary for River Rch & Prof#=UNT140 IN BECR,Reach-1         , 3
Up Type= 0
Dn Type= 3
Dn Slope=0.001
Boundary for River Rch & Prof#=UNT140 IN BECR,Reach-1         , 4
Up Type= 0
Dn Type= 3
Dn Slope=0.001
Boundary for River Rch & Prof#=UNT140 IN BECR,Reach-1         , 5
Up Type= 0
Dn Type= 3
Dn Slope=0.001
Boundary for River Rch & Prof#=UNT140 IN BECR,Reach-1         , 6
Up Type= 0
Dn Type= 3
Dn Slope=0.001
Boundary for River Rch & Prof#=UNT140 IN BECR,Reach-1         , 7
Up Type= 0
Dn Type= 3
Dn Slope=0.001
DSS Import GetInterval= 0
DSS Import GetPeak= 0
DSS Import FillOption= 0

--- UNT140 IN BECR.g01 (geometry) ---

Geom Title=Existing Conditions
Program Version=4.10

River Reach=UNT140 IN BECR  ,Reach-1
Reach XY= 30
      3781249.61     10502210.19      3781208.25       10502465.
       3781026.5       10502691.       3781044.5       10502809.
       3780890.5       10502881.      3781038.75       10503115.
      3780791.25       10503379.       3780916.5       10503542.
       3780895.5       10503708.      3780637.75       10503838.
       3780717.5       10503916.        3780656.       10504099.
      3780580.75       10504085.      3780510.25       10504160.
       3780587.5       10504236.      3780565.75       10504329.
       3780374.5       10504428.      3780228.75       10504880.
       3780123.5       10504889.      3779957.25       10505051.
        3779872.       10505271.      3779665.75       10505397.
       3779466.5       10505679.      3779350.25       10505649.
        3779333.       10505784.      3779173.75       10505854.
       3779182.5       10505993.       3778698.5       10506221.
        3778190.       10506779.       3776749.5       10509185.

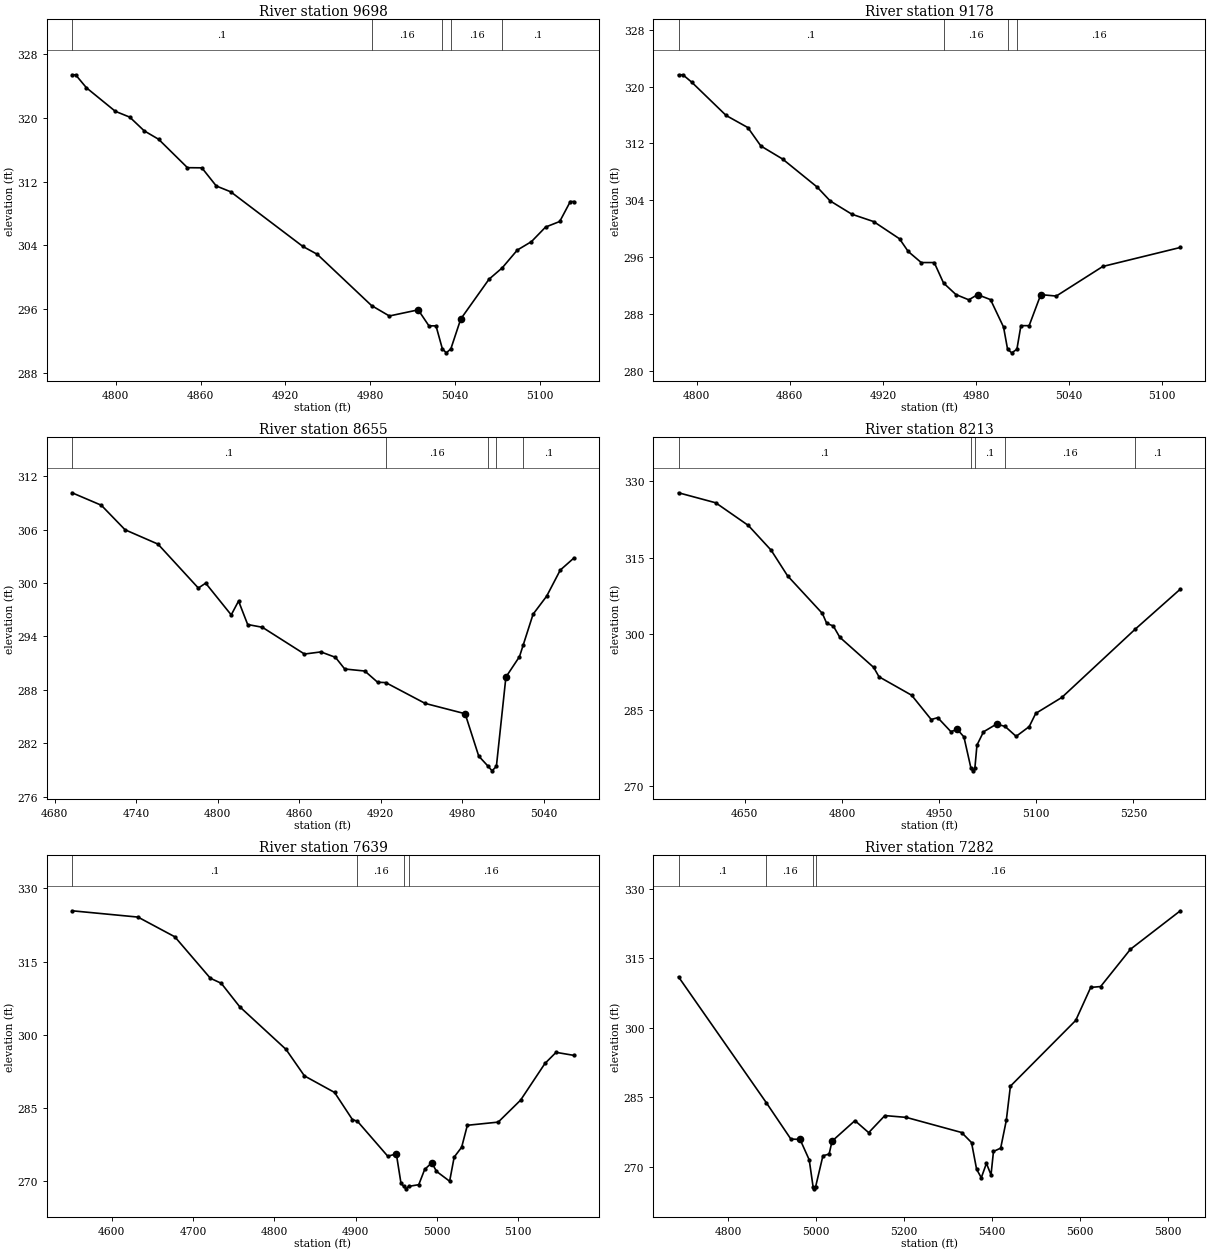
Type RM Length L Ch R = 1 ,9698    ,520,520,520
BEGIN DESCRIPTION:
UNT140 IN BECR 18.0
END DESCRIPTION:
XS GIS Cut Line= 3
      3780999.61     10502310.19      3781249.61     10502360.19
      3781349.56     10502360.19
#Sta/Elev= 30
  4769.1  325.42  4771.6  325.42  4779.3  323.78  4799.7  320.83  4809.9   320.1
  4820.1  318.38  4830.3  317.32  4850.7  313.75  4860.9  313.73  4871.1  311.45
  4881.3  310.72  4932.3  303.86  4942.5  302.87  4980.9  296.43  4993.5  295.12
  5013.9  295.89  5021.5  293.88  5026.5  293.88    5031  290.99  5033.8  290.49
    5037  290.99    5044  294.74    5064  299.74  5073.3  301.16    5084   303.4
    5094  304.46    5104  306.29    5114  306.99  5121.5   309.5    5124   309.5
#Mann= 5 ,-1 , 0
  4769.1      .1       0  4980.9     .16       0    5031     .07       0
    5037     .16       0  5073.3      .1       0
Bank Sta=5013.9,5044
XS Rating Curve= 0 ,0
Exp/Cntr=0.3,0.1

Type RM Length L Ch R = 1 ,9178    ,523,523,523
BEGIN DESCRIPTION:
UNT140 IN BECR 17.0
END DESCRIPTION:
XS GIS Cut Line= 3
      3780849.63      10502660.2      3781049.61     10502760.19
      3781149.62     10502760.19
#Sta/Elev= 30
  4788.2  321.65    4791  321.65  4796.6  320.63  4818.9  315.93  4832.9  314.23
  4841.3  311.64  4855.3  309.81  4877.6  305.87    4886  303.92    4900  302.05
    4914  301.02  4930.7   298.6  4936.3  296.82  4944.7  295.26  4953.1  295.26
  4959.1  292.38  4967.1  290.76  4975.4  290.02    4981  290.75  4989.4  290.05
  4997.8  286.19  5000.4  283.07  5003.1  282.57  5006.4  283.07    5009  286.39
  5014.3  286.39  5021.8  290.75  5031.8  290.55  5061.8  294.71  5111.8  297.38
#Mann= 4 ,-1 , 0
  4788.2      .1       0  4959.1     .16       0  5000.4     .07       0
  5006.4     .16       0
Bank Sta=4981,5021.8
XS Rating Curve= 0 ,0
Exp/Cntr=0.3,0.1

Type RM Length L Ch R = 1 ,8655    ,442,442,442
BEGIN DESCRIPTION:
UNT140 IN BECR 16.0
END DESCRIPTION:
XS GIS Cut Line= 3
      3780749.63      10503010.2      3780999.61     10503110.19
      3781099.58     10503110.19
#Sta/Elev= 30
  4692.9  310.15  4714.4  308.75  4731.9  305.99  4756.1  304.38  4785.8  299.44
  4791.2  299.99    4810  296.42  4815.4  297.98  4822.1  295.34  4832.9  295.03
  4863.9  292.02    4876  292.26  4886.7  291.65  4893.5  290.34  4908.3  290.11
  4917.7  288.85  4923.7  288.81  4952.7  286.47  4982.1  285.31  4992.1  280.55
  4999.1  279.39  5001.9  278.89  5005.1  279.39  5012.1  289.43  5022.1  291.73
  5024.8  293.02  5032.1   296.5  5042.1  298.53  5052.1  301.46  5062.1  302.81
#Mann= 5 ,-1 , 0
  4692.9      .1       0  4923.7     .16       0  4999.1     .07       0
  5005.1     .16       0  5024.8      .1       0
Bank Sta=4982.1,5012.1
XS Rating Curve= 0 ,0
Exp/Cntr=0.3,0.1

Type RM Length L Ch R = 1 ,8213    ,574,574,574
BEGIN DESCRIPTION:
UNT140 IN BECR 15.0
END DESCRIPTION:
XS GIS Cut Line= 2
      3780352.72      10503483.6      3781120.96     10503383.77
#Sta/Elev= 30
  4547.7  327.74  4605.1  325.77  4655.5  321.31  4690.7  316.44    4716  311.41
  4769.8     304  4776.5  302.04  4786.6  301.55  4796.7  299.32    4849  293.39
  4857.2  291.55  4907.6  287.92  4937.8  283.14  4947.9  283.51  4968.1  280.77
  4978.2  281.19  4988.3  279.72  4999.2  273.55  5001.9  273.05  5005.2  273.55
  5008.4   278.1  5018.5  280.72  5038.7  282.25  5051.9  281.78  5068.9  279.83
  5089.1  281.75  5099.2  284.35  5139.5  287.49  5252.3  300.86  5322.4  308.79
#Mann= 5 ,-1 , 0
  4547.7      .1       0  4999.2     .07       0  5005.2      .1       0
  5051.9     .16       0  5252.3      .1       0
Bank Sta=4978.2,5038.7
XS Rating Curve= 0 ,0
Exp/Cntr=0.3,0.1

Type RM Length L Ch R = 1 ,7639    ,357,357,357
BEGIN DESCRIPTION:
UNT140 IN BECR 14.0
END DESCRIPTION:
XS GIS Cut Line= 2
      3780348.37      10503592.1      3780890.89     10503887.23
#Sta/Elev= 30
  4551.1  325.41  4632.2  324.12  4677.6  320.08  4721.3   311.6  4734.7  310.57
  4757.4  305.77  4814.4  297.04  4837.1  291.61  4874.2  288.22  4896.1  282.68
  4902.4  282.31  4939.7  275.16  4950.2  275.65  4955.9  269.66  4959.3  268.99
  4962.1  268.49  4965.3  268.99  4977.8  269.34  4985.1  272.47  4993.9  273.83
  4999.6  272.07  5015.8  270.05  5021.4  274.99  5030.6  277.01  5037.6   281.5
  5075.6  282.15  5103.1  286.64  5133.1  294.15  5146.8  296.43  5168.7  295.81
#Mann= 4 ,-1 , 0
  4551.1      .1       0  4902.4     .16       0  4959.3     .07       0
  4965.3     .16       0
Bank Sta=4950.2,4993.9
XS Rating Curve= 0 ,0
Exp/Cntr=0.3,0.1

Type RM Length L Ch R = 1 ,7282    ,484,484,484
BEGIN DESCRIPTION:
Mapping XS e629f49d
END DESCRIPTION:
XS GIS Cut Line= 3
        3780344.     10503930.64      3780795.43     10504060.86
      3781390.07     10504373.37
#Sta/Elev= 30
  4686.5  311.01  4886.4  283.85  4942.1  276.03  4962.9  275.97  4983.8  271.56
  4992.5   265.8  4995.2   265.3  4998.5   265.8    5015  272.43  5029.1   272.8
  5035.8  275.59  5087.8  280.01  5119.1  277.42  5155.9   281.1  5204.6  280.71
  5330.5  277.45  5353.1  275.28  5364.6  269.53  5375.3  267.69    5387   270.8
  5397.4   268.3    5403  273.36  5419.4  274.08  5432.2  280.07  5441.5  287.44
  5590.1  301.62  5624.2  308.74  5646.8  308.93  5714.6  316.97  5828.1  325.27
#Mann= 4 ,-1 , 0
  4686.5      .1       0  4886.4     .16       0  4992.5     .07       0
  4998.5     .16       0
Bank Sta=4962.9,5035.8
XS Rating Curve= 0 ,0
Exp/Cntr=0.3,0.1

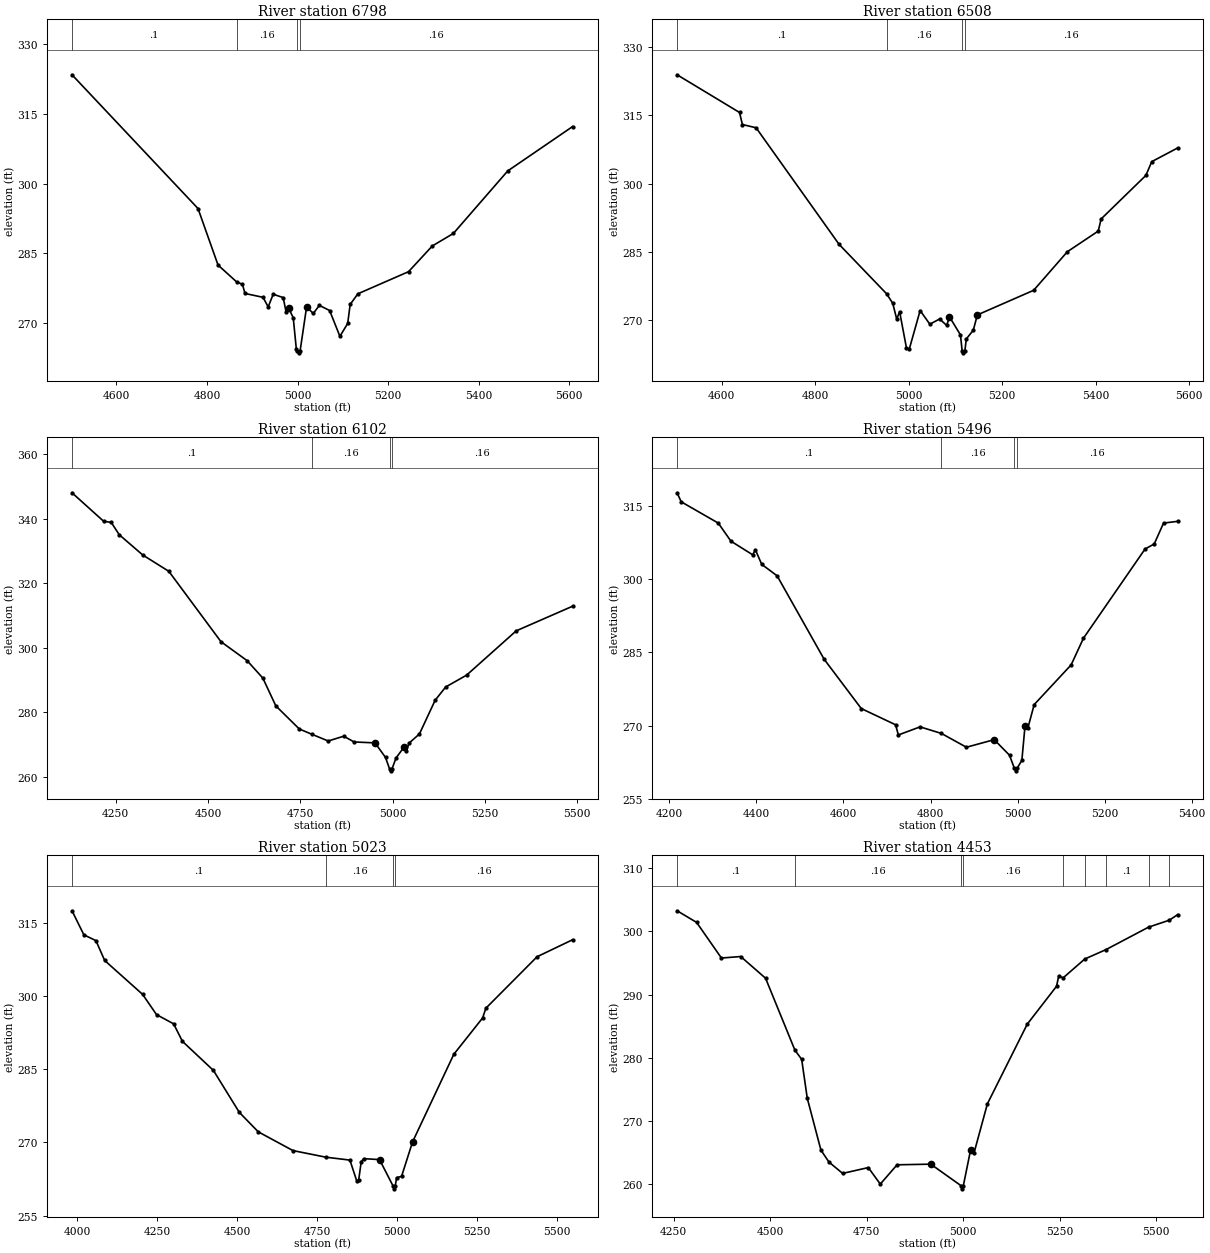
Type RM Length L Ch R = 1 ,6798    ,290,290,290
BEGIN DESCRIPTION:
UNT140 IN BECR 13.0
END DESCRIPTION:
XS GIS Cut Line= 3
      3780118.34     10504091.24      3780873.55     10504451.48
       3781142.6      10504464.5
#Sta/Elev= 30
  4501.7  323.46  4780.1  294.61  4824.4  282.41  4865.2   278.8  4878.4  278.23
  4883.9  276.28  4923.8  275.45  4935.2  273.38  4946.3  276.11  4968.4  275.39
  4974.7  272.32  4980.2  273.18  4990.6  271.03  4997.4  264.29  4999.9  263.97
  5002.7  263.47  5005.9  263.97  5020.1  273.37  5034.9  271.96  5048.3  273.71
    5071   272.6  5093.7  267.03  5110.9  269.81  5116.4  273.92  5133.5  276.21
  5245.4  280.98  5297.9  286.53  5344.5  289.23  5464.6  302.72  5607.8  312.28
#Mann= 4 ,-1 , 0
  4501.7      .1       0  4865.2     .16       0  4999.9     .07       0
  5005.9     .16       0
Bank Sta=4980.2,5020.1
XS Rating Curve= 0 ,0
Exp/Cntr=0.3,0.1

Type RM Length L Ch R = 1 ,6508    ,406,406,406
BEGIN DESCRIPTION:
UNT140 IN BECR 12.0
END DESCRIPTION:
XS GIS Cut Line= 3
      3779970.74      10504143.3      3780400.46     10504460.16
      3780699.27     10504906.21
#Sta/Elev= 30
  4504.4  323.95  4637.9  315.66  4644.1  313.01  4673.4  312.29  4850.9  286.65
  4952.5  275.78  4965.7  273.69  4974.2   270.2  4980.4  271.85    4995  263.88
  5001.2  263.64  5024.3  272.08  5045.1  269.08  5066.1  270.23  5081.1  268.81
  5087.1   270.7  5110.6  266.72  5114.1  263.28  5116.9  262.78  5120.1  263.28
  5123.1  265.84  5138.1  267.77  5146.7  271.12  5267.2  276.54  5339.3  285.03
  5405.3  289.56  5411.5  292.23  5507.3  301.82  5519.8  304.84  5575.2  307.85
#Mann= 4 ,-1 , 0
  4504.4      .1       0  4952.5     .16       0  5114.1     .07       0
  5120.1     .16       0
Bank Sta=5087.1,5146.7
XS Rating Curve= 0 ,0
Exp/Cntr=0.3,0.1

Type RM Length L Ch R = 1 ,6102    ,606,606,606
BEGIN DESCRIPTION:
UNT140 IN BECR 11.0
END DESCRIPTION:
XS GIS Cut Line= 2
      3779623.55     10504225.79      3780629.39     10505136.25
#Sta/Elev= 30
  4131.3  348.01  4216.7  339.21  4237.7  338.81  4259.3  335.01  4322.8  328.74
  4393.8  323.65  4535.1  301.83    4606  295.95  4648.6  290.54  4683.7  281.94
  4747.3  274.77  4782.1   273.1  4825.7  271.04  4867.8  272.53    4896  270.74
  4952.7  270.46  4981.1  265.93  4992.3  262.29  4995.1  261.79  4998.3  262.29
  5009.5  265.75  5030.5  269.06  5037.9  267.86  5044.7  270.36    5073  273.23
  5115.6  283.68    5144  287.78  5200.8  291.46  5335.3   305.2    5488  312.83
#Mann= 4 ,-1 , 0
  4131.3      .1       0  4782.1     .16       0  4992.3     .07       0
  4998.3     .16       0
Bank Sta=4952.7,5030.5
XS Rating Curve= 0 ,0
Exp/Cntr=0.3,0.1

Type RM Length L Ch R = 1 ,5496    ,473,473,473
BEGIN DESCRIPTION:
UNT140 IN BECR 10.0
END DESCRIPTION:
XS GIS Cut Line= 3
      3779428.22     10504568.65      3779775.46      10505024.4
      3780174.72     10505441.01
#Sta/Elev= 30
  4217.7  317.75  4227.1   315.9  4312.3  311.53  4341.4  307.82  4391.3  305.03
  4397.6  306.04  4412.1  303.07  4447.5  300.71  4555.5   283.6  4640.8  273.48
  4719.7  270.15    4726  268.06  4775.9  269.72  4824.8  268.38  4882.4  265.54
  4946.3   267.1  4981.5  263.89  4992.6   261.2  4995.4   260.7  4998.6   261.2
  5009.8  262.84    5017  269.88  5023.9  269.59  5038.1  274.29    5123  282.44
  5151.3  287.91  5292.8  306.21  5313.9  307.25  5335.3  311.53  5367.7  311.89
#Mann= 4 ,-1 , 0
  4217.7      .1       0  4824.8     .16       0  4992.6     .07       0
  4998.6     .16       0
Bank Sta=4946.3,5017
XS Rating Curve= 0 ,0
Exp/Cntr=0.3,0.1

Type RM Length L Ch R = 1 ,5023    ,570,570,570
BEGIN DESCRIPTION:
UNT140 IN BECR 9.0
END DESCRIPTION:
XS GIS Cut Line= 3
      3778751.17      10504937.6      3779740.74     10505493.15
      3780170.44     10505510.51
#Sta/Elev= 30
    3983  317.48  4020.1  312.55  4057.8  311.36  4085.2  307.29  4203.8  300.34
  4247.2   296.2  4300.7  294.31  4328.2  290.72  4425.1  284.76  4506.1  276.16
  4565.4  272.17  4673.8  268.33  4776.4  266.98  4851.8  266.38  4873.4  262.07
  4879.2  262.26  4887.2  266.05  4895.1  266.68  4944.5  266.48  4987.4  260.99
  4990.2  260.49  4993.4  260.99  4997.8  262.79  5013.3  263.04  5047.7  270.11
  5176.8  288.08  5266.8  295.52  5276.8   297.5    5437  308.06  5547.9  311.54
#Mann= 4 ,-1 , 0
    3983      .1       0  4776.4     .16       0  4987.4     .07       0
  4993.4     .16       0
Bank Sta=4944.5,5047.7
XS Rating Curve= 0 ,0
Exp/Cntr=0.3,0.1

Type RM Length L Ch R = 1 ,4453    ,654,654,654
BEGIN DESCRIPTION:
UNT140 IN BECR 8.0
END DESCRIPTION:
XS GIS Cut Line= 3
      3778807.59     10505280.49      3779059.32     10505610.34
      3779831.41     10506035.42
#Sta/Elev= 30
  4259.2  303.24  4309.6  301.41    4374  295.77  4423.9  296.01  4488.3  292.58
  4564.3  281.21  4581.8  279.76  4596.3  273.61  4631.7  265.41  4652.5  263.52
  4687.9  261.73  4754.4  262.65  4785.4  260.04  4828.9  263.09  4916.1  263.19
  4994.5  259.79  4997.3  259.29  5000.5  259.79  5019.3  265.44  5028.3  264.99
  5062.8  272.73  5166.1  285.33  5241.8   291.3  5247.5  292.93    5259  292.64
  5315.1  295.62  5369.5  297.09  5480.1  300.65  5533.8  301.75  5555.5  302.63
#Mann= 9 ,-1 , 0
  4259.2      .1       0  4564.3     .16       0  4994.5     .07       0
  5000.5     .16       0    5259     .08       0  5315.1     .05       0
  5369.5      .1       0  5480.1     .16       0  5533.8     .05       0
Bank Sta=4916.1,5019.3
XS Rating Curve= 0 ,0
Exp/Cntr=0.3,0.1

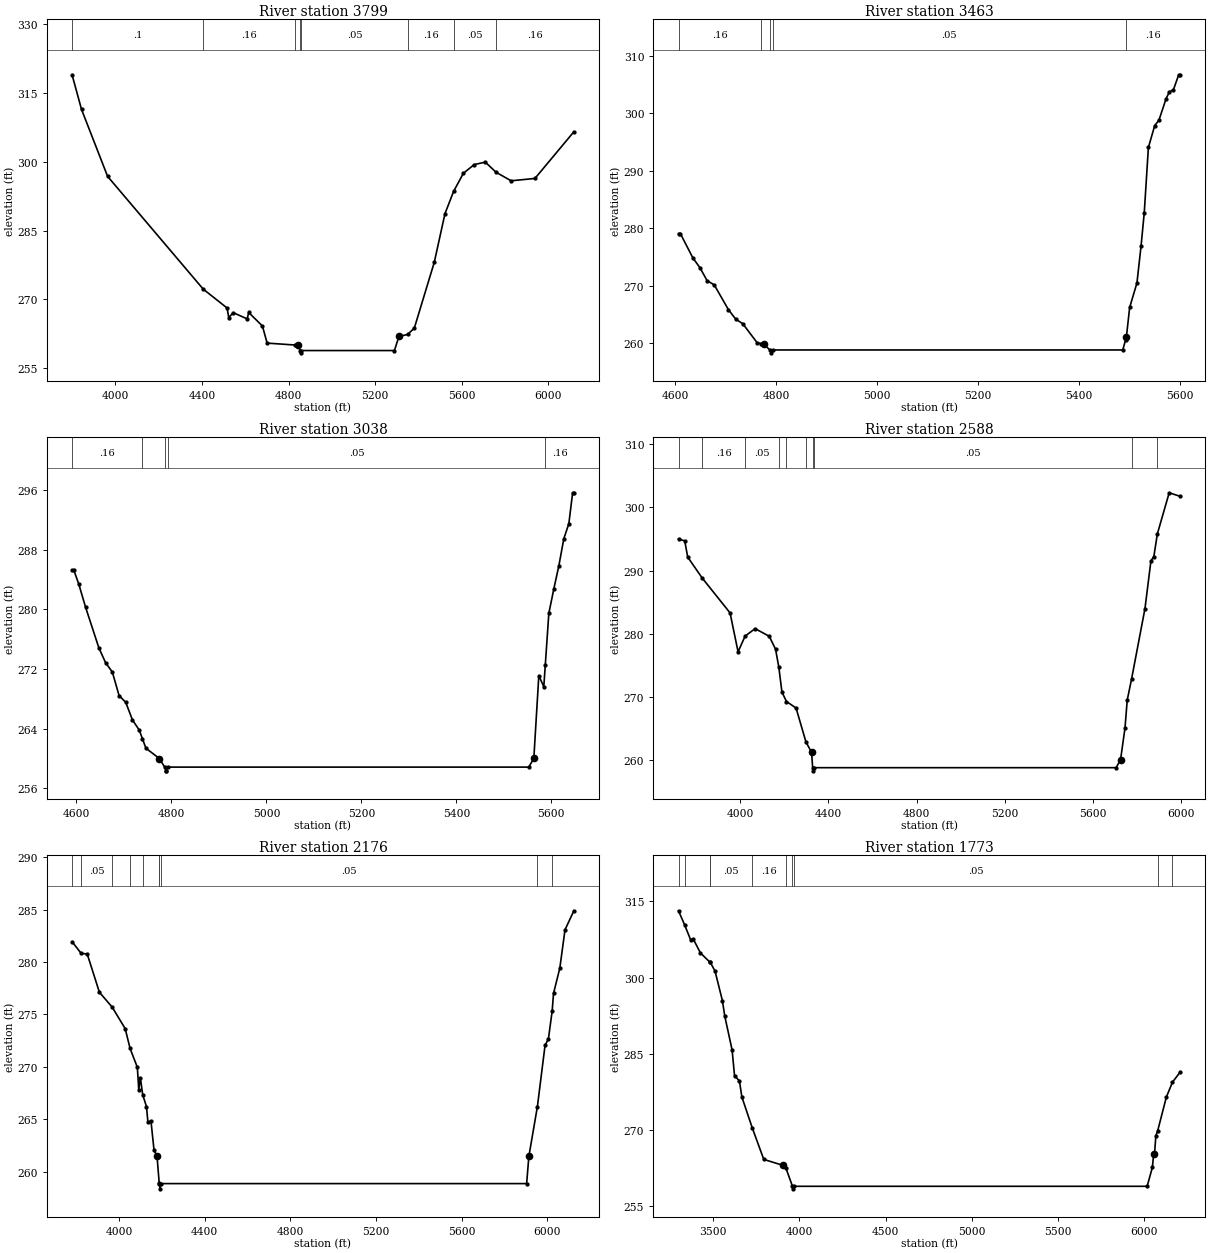
Type RM Length L Ch R = 1 ,3799    ,336,336,336
BEGIN DESCRIPTION:
UNT140 IN BECR 7.0
END DESCRIPTION:
XS GIS Cut Line= 3
      3778113.12     10505215.36      3779263.31     10506508.77
      3779849.25     10506530.48
#Sta/Elev= 30
  3800.2     319  3843.9  311.44  3964.3  296.84  4405.7  272.26  4516.2  268.13
  4523.7  266.05  4544.6  267.12    4609  265.76  4615.7  267.17  4679.2  264.21
    4701  260.48  4831.5  260.06  4842.3  260.07  4853.5  258.86  4856.2  258.36
  4859.5  258.86  5288.8  258.86  5309.7  261.94  5349.6  262.36  5380.8  263.77
  5472.8   278.1  5522.1  288.69    5562  293.56  5607.4  297.53  5657.4  299.42
  5708.4  299.95  5758.5  297.73  5827.6  295.88  5937.6  296.39  6117.4  306.57
#Mann= 8 ,-1 , 0
  3800.2      .1       0  4405.7     .16       0  4831.5     .05       0
  4853.5    .033       0  4859.5     .05       0  5349.6     .16       0
    5562     .05       0  5758.5     .16       0
Bank Sta=4842.3,5309.7
XS Rating Curve= 0 ,0
Exp/Cntr=0.3,0.1

Type RM Length L Ch R = 1 ,3463    ,425,425,425
BEGIN DESCRIPTION:
UNT140 IN BECR 6.0
END DESCRIPTION:
XS GIS Cut Line= 3
      3778349.58     10506010.16      3778649.61     10506310.19
      3778999.61     10506760.19
#Sta/Elev= 30
  4606.5   279.1  4610.1   279.1  4634.8  274.88    4649  273.15  4663.1  270.91
  4677.3  270.17  4705.5  265.85  4719.7  264.23  4733.8  263.42  4762.1  260.14
  4769.7  259.97  4776.2  259.82  4787.4  258.86  4790.1  258.36  4793.4  258.86
  5486.9  258.86  5492.3  260.59  5494.1  261.17  5500.5  266.26  5514.9  270.49
  5523.1  276.95  5529.4  282.69  5537.6  294.06  5550.2  297.88  5558.4  298.78
  5572.8  302.57  5579.2  303.73  5587.3  304.12  5597.7   306.7  5600.9   306.7
#Mann= 5 ,-1 , 0
  4606.5     .16       0  4769.7     .05       0  4787.4    .033       0
  4793.4     .05       0  5492.3     .16       0
Bank Sta=4776.2,5494.1
XS Rating Curve= 0 ,0
Exp/Cntr=0.3,0.1

Type RM Length L Ch R = 1 ,3038    ,450,450,450
BEGIN DESCRIPTION:
UNT140 IN BECR 5.0
END DESCRIPTION:
XS GIS Cut Line= 3
      3778049.63     10506310.21      3778349.61     10506610.19
      3778949.62     10506810.19
#Sta/Elev= 30
  4590.7  285.28  4594.2  285.28  4604.8  283.38    4619  280.31  4647.2  274.82
  4661.4  272.83  4675.5   271.6  4689.7  268.44  4703.8  267.53  4717.9  265.17
  4732.1  263.83  4738.8  262.67  4746.2  261.39  4774.5  260.01  4785.7  258.86
  4788.4  258.36  4788.9  258.36  4791.7  258.86  5552.5  258.86  5563.1  260.03
  5573.6  271.11  5584.1  269.64  5587.3   272.6  5594.7  279.46  5605.2  282.73
  5615.8  285.83  5626.3  289.47  5636.8  291.46  5644.8  295.61  5647.4  295.61
#Mann= 5 ,-1 , 0
  4590.7     .16       0  4738.8     .05       0  4785.7    .033       0
  4791.7     .05       0  5587.3     .16       0
Bank Sta=4774.5,5563.1
XS Rating Curve= 0 ,0
Exp/Cntr=0.3,0.1

Type RM Length L Ch R = 1 ,2588    ,412,412,412
BEGIN DESCRIPTION:
UNT140 IN BECR 4.0
END DESCRIPTION:
XS GIS Cut Line= 3
      3777272.19     10505978.16      3778049.61     10506960.19
      3779069.12     10507080.61
#Sta/Elev= 30
  3718.9  294.99    3747  294.68  3760.6  292.12  3827.1  288.78  3952.9  283.31
  3989.3  277.16  4021.3  279.64  4066.7  280.82  4130.8  279.62  4159.7  277.56
  4174.4  274.72  4188.5  270.81  4209.1  269.31  4252.6  268.29  4297.5  262.94
  4323.1  261.27  4328.2  258.86  4330.9  258.36  4334.2  258.86  5706.5  258.86
  5726.6  260.15  5746.8  265.14  5756.8  269.53  5776.5  272.85  5837.4  283.99
  5864.5  291.53  5877.7   292.2  5893.7  295.79  5947.4  302.28    5998  301.71
#Mann= 10 ,-1 , 0
  3718.9     .05       0  3827.1     .16       0  4021.3     .05       0
  4174.4      .1       0  4209.1     .16       0  4297.5     .05       0
  4328.2    .033       0  4334.2     .05       0  5776.5     .16       0
  5893.7     .05       0
Bank Sta=4323.1,5726.6
XS Rating Curve= 0 ,0
Exp/Cntr=0.3,0.1

Type RM Length L Ch R = 1 ,2176    ,403,403,403
BEGIN DESCRIPTION:
UNT140 IN BECR 3.0
END DESCRIPTION:
XS GIS Cut Line= 3
      3777049.59     10506410.17      3777849.61     10507310.19
      3778904.17     10507740.34
#Sta/Elev= 30
  3780.2  281.93  3822.6  280.82  3850.9  280.76  3907.8  277.11  3967.2   275.7
  4028.2  273.64  4051.1  271.75    4085  269.95  4091.7  267.79  4099.2  268.96
  4109.9  267.34  4127.7   266.2  4134.4   264.7  4148.6  264.83  4162.8  262.07
    4177  261.45    4187  258.93  4188.2  258.86    4191  258.36  4194.2  258.86
  5902.8  258.86  5913.2  261.46  5953.1  266.21  5988.8  272.05  6004.4  272.65
    6022  275.32  6028.4     277  6057.8  279.42  6081.9  283.06  6123.3  284.88
#Mann= 10 ,-1 , 0
  3780.2     .16       0  3822.6     .05       0  3967.2     .16       0
  4051.1      .1       0  4109.9     .16       0    4187     .05       0
  4188.2    .033       0  4194.2     .05       0  5953.1     .16       0
    6022      .1       0
Bank Sta=4177,5913.2
XS Rating Curve= 0 ,0
Exp/Cntr=0.3,0.1

Type RM Length L Ch R = 1 ,1773    ,404,404,404
BEGIN DESCRIPTION:
UNT140 IN BECR 2.0
END DESCRIPTION:
XS GIS Cut Line= 3
      3776449.64     10506460.22      3777649.61     10507660.19
      3778849.64     10507860.19
#Sta/Elev= 30
  3297.8  313.15  3333.7  310.32  3368.5  307.39  3382.6  307.63    3425  304.84
    3478  303.09    3481  303.07  3509.9  301.25  3552.3  295.47  3566.5  292.35
  3608.9  285.71    3623  280.63  3651.3  279.64  3665.5  276.46  3725.4  270.42
  3792.7  264.16  3905.9  262.97  3921.9  262.39  3959.4  258.86  3962.2  258.36
  3965.4  258.86  6018.7  258.86  6049.2  262.59  6056.8  265.29  6061.8  265.34
  6069.4  268.82  6079.7  269.77  6130.3  276.44  6165.7  279.37  6211.4  281.41
#Mann= 10 ,-1 , 0
  3297.8     .16       0  3333.7     .05       0    3478     .08       0
    3481     .05       0  3725.4     .16       0  3921.9     .05       0
  3959.4    .033       0  3965.4     .05       0  6079.7     .16       0
  6165.7      .1       0
Bank Sta=3905.9,6056.8
XS Rating Curve= 0 ,0
Exp/Cntr=0.3,0.1

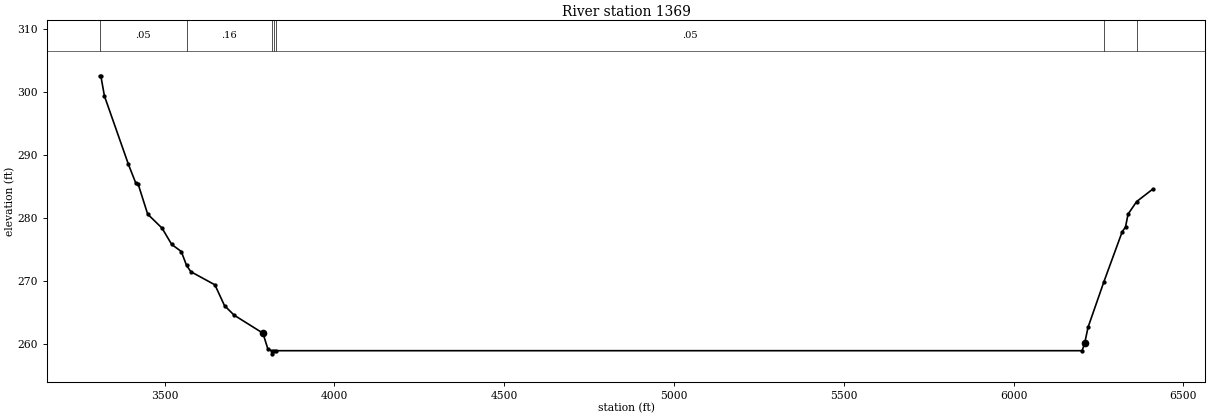
Type RM Length L Ch R = 1 ,1369    ,0,0,0
BEGIN DESCRIPTION:
UNT140 IN BECR 1.0
END DESCRIPTION:
XS GIS Cut Line= 3
      3776249.61     10506810.19      3777449.61     10508010.19
      3778849.59     10507910.19
#Sta/Elev= 30
  3308.9  302.52  3312.4  302.52    3323  299.31  3393.8  288.43    3415  285.52
    3422  285.37  3450.3  280.55  3492.7  278.32    3521  275.74  3549.3  274.61
  3564.9  272.39  3577.6   271.4  3648.3  269.32  3676.6  266.01  3704.9   264.5
  3789.7  261.64  3803.9  259.18    3815  258.86  3817.8  258.36    3821  258.86
  3828.9  258.86  6201.5  258.86    6209  260.04    6219  262.58  6265.8  269.83
  6319.3  277.72  6329.3  278.51  6336.8  280.55    6362  282.54  6409.5  284.52
#Mann= 7 ,-1 , 0
  3308.9     .05       0  3564.9     .16       0    3815    .033       0
    3821     .16       0  3828.9     .05       0  6265.8     .16       0
    6362      .1       0
Bank Sta=3789.7,6209
XS Rating Curve= 0 ,0
Exp/Cntr=0.3,0.1

Chan Stop Cuts=-1
Use User Specified Reach Order=0
Composite Channel Slope=5