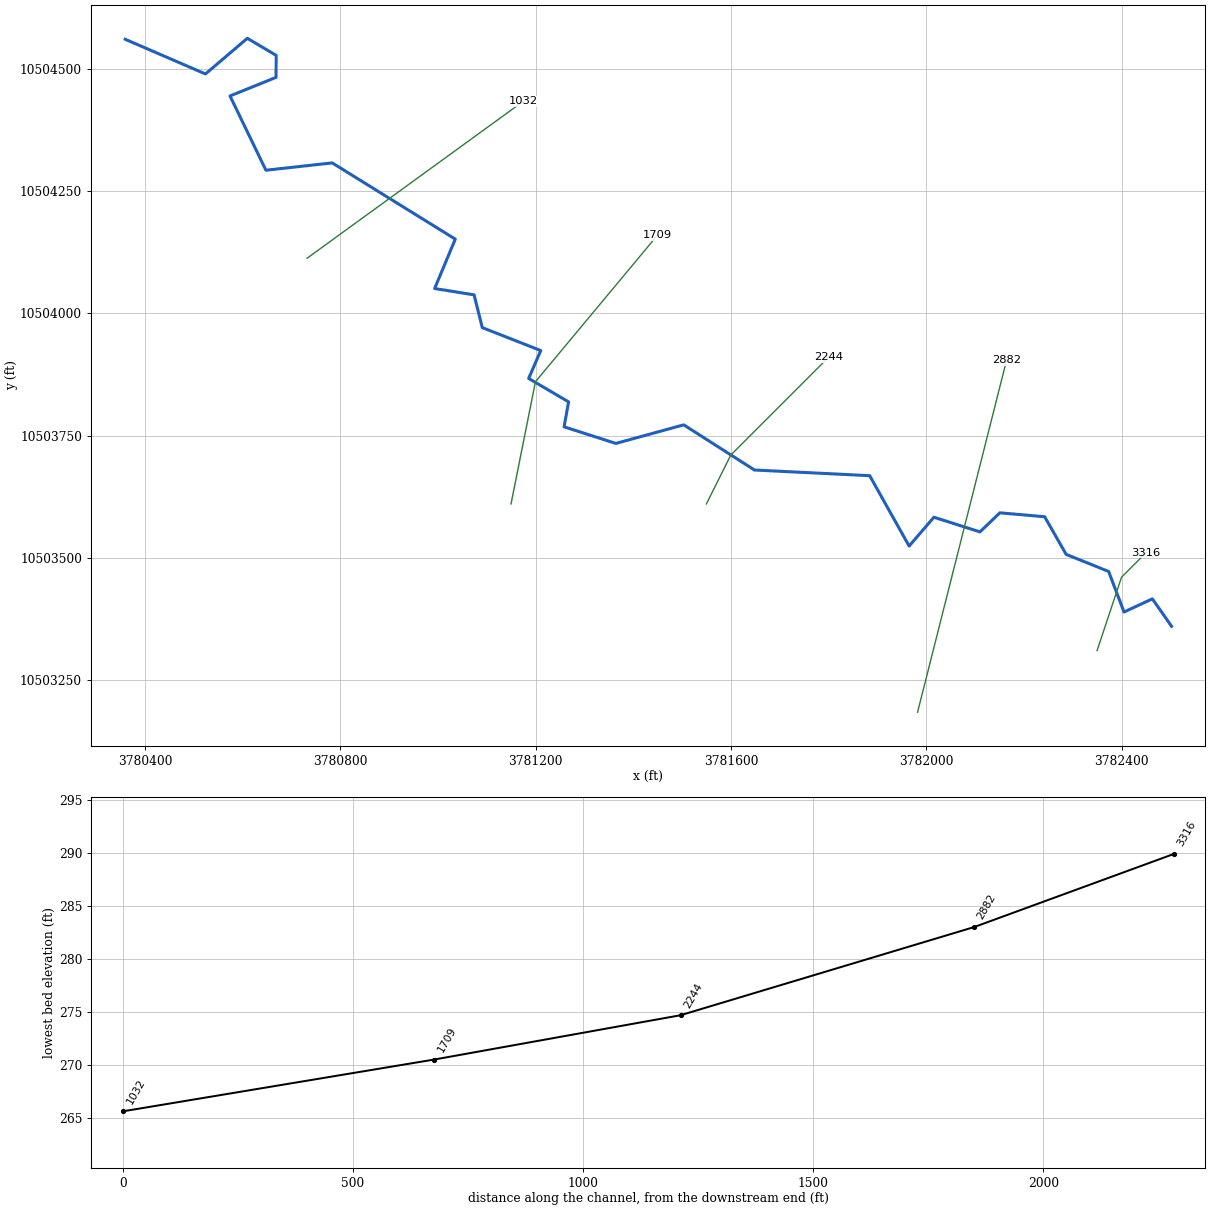
--- UNT141 IN BECR.prj (project) ---

Proj Title=UNT141 IN BECR Base Level Engineering
Current Plan=p01
Default Exp/Contr=0.3,0.1
English Units
Geom File=g01
Flow File=f01
Plan File=p01
BEGIN DESCRIPTION:
UNT141 IN BECR
END DESCRIPTION:

--- UNT141 IN BECR.p01 (plan) ---

Plan Title=Multiple Run
Short Identifier=Multiple
Geom File=g01
Flow File=f01
Subcritical Flow
K Sum by GR= 0
Std Step Tol= 0.01
Critical Tol= 0.01
Num of Std Step Trials= 20
Max Error Tol= 0.3
Flow Tol Ratio= 0.001
Split Flow NTrial= 30
Split Flow Tol= 0.02
Split Flow Ratio= 0.02
Log Output Level= 0
Friction Slope Method= 1
Unsteady Friction Slope Method= 2
Unsteady Bridges Friction Slope Method= 1
Parabolic Critical Depth
Global Vel Dist=  1 , 1 , 1
Global Log Level= 0
CheckData=True
Encroach Param= -1, 0, 0, 0
BEGIN DESCRIPTION:
Multiple Run
END DESCRIPTION:

--- UNT141 IN BECR.f01 (steady flow) ---

Flow Title=Multiple
Number of Profiles=7
Profile Names=10-year,25-year,50-year,1pct_min,100-year,1pct_plu,500-year
River Rch & RM= UNT141 IN BECR,Reach-1,3316
     190     239     277     237     320     433     428
Boundary for River Rch & Prof#=UNT141 IN BECR,Reach-1,1
Up Type=0
Dn Type=3
Dn Slope=0.005
Boundary for River Rch & Prof#=UNT141 IN BECR,Reach-1,2
Up Type=0
Dn Type=3
Dn Slope=0.005
Boundary for River Rch & Prof#=UNT141 IN BECR,Reach-1,3
Up Type=0
Dn Type=3
Dn Slope=0.005
Boundary for River Rch & Prof#=UNT141 IN BECR,Reach-1,4
Up Type=0
Dn Type=3
Dn Slope=0.005
Boundary for River Rch & Prof#=UNT141 IN BECR,Reach-1,5
Up Type=0
Dn Type=3
Dn Slope=0.005
Boundary for River Rch & Prof#=UNT141 IN BECR,Reach-1,6
Up Type=0
Dn Type=3
Dn Slope=0.005
Boundary for River Rch & Prof#=UNT141 IN BECR,Reach-1,7
Up Type=0
Dn Type=3
Dn Slope=0.005

--- UNT141 IN BECR.g01 (geometry) ---

Geom Title=Existing Conditions

River Reach=UNT141 IN BECR,Reach-1
Reach XY= 30
      3782502.12     10503359.80      3782462.75     10503416.00
      3782404.75     10503389.00      3782373.25     10503472.00
      3782286.25     10503507.00      3782242.25     10503584.00
      3782150.50     10503592.00      3782109.75     10503553.00
      3782015.50     10503583.00      3781964.75     10503524.00
      3781884.00     10503668.00      3781648.14     10503679.59
      3781503.25     10503772.00      3781364.25     10503734.00
      3781258.25     10503768.00      3781267.50     10503819.00
      3781185.75     10503867.00      3781210.50     10503924.00
      3781090.75     10503971.00      3781074.00     10504038.00
      3780993.25     10504051.00      3781035.50     10504152.00
      3780783.50     10504308.00      3780647.75     10504293.00
      3780574.25     10504445.00      3780668.50     10504483.00
      3780668.75     10504528.00      3780609.75     10504563.00
      3780524.00     10504490.00      3780359.50     10504561.00

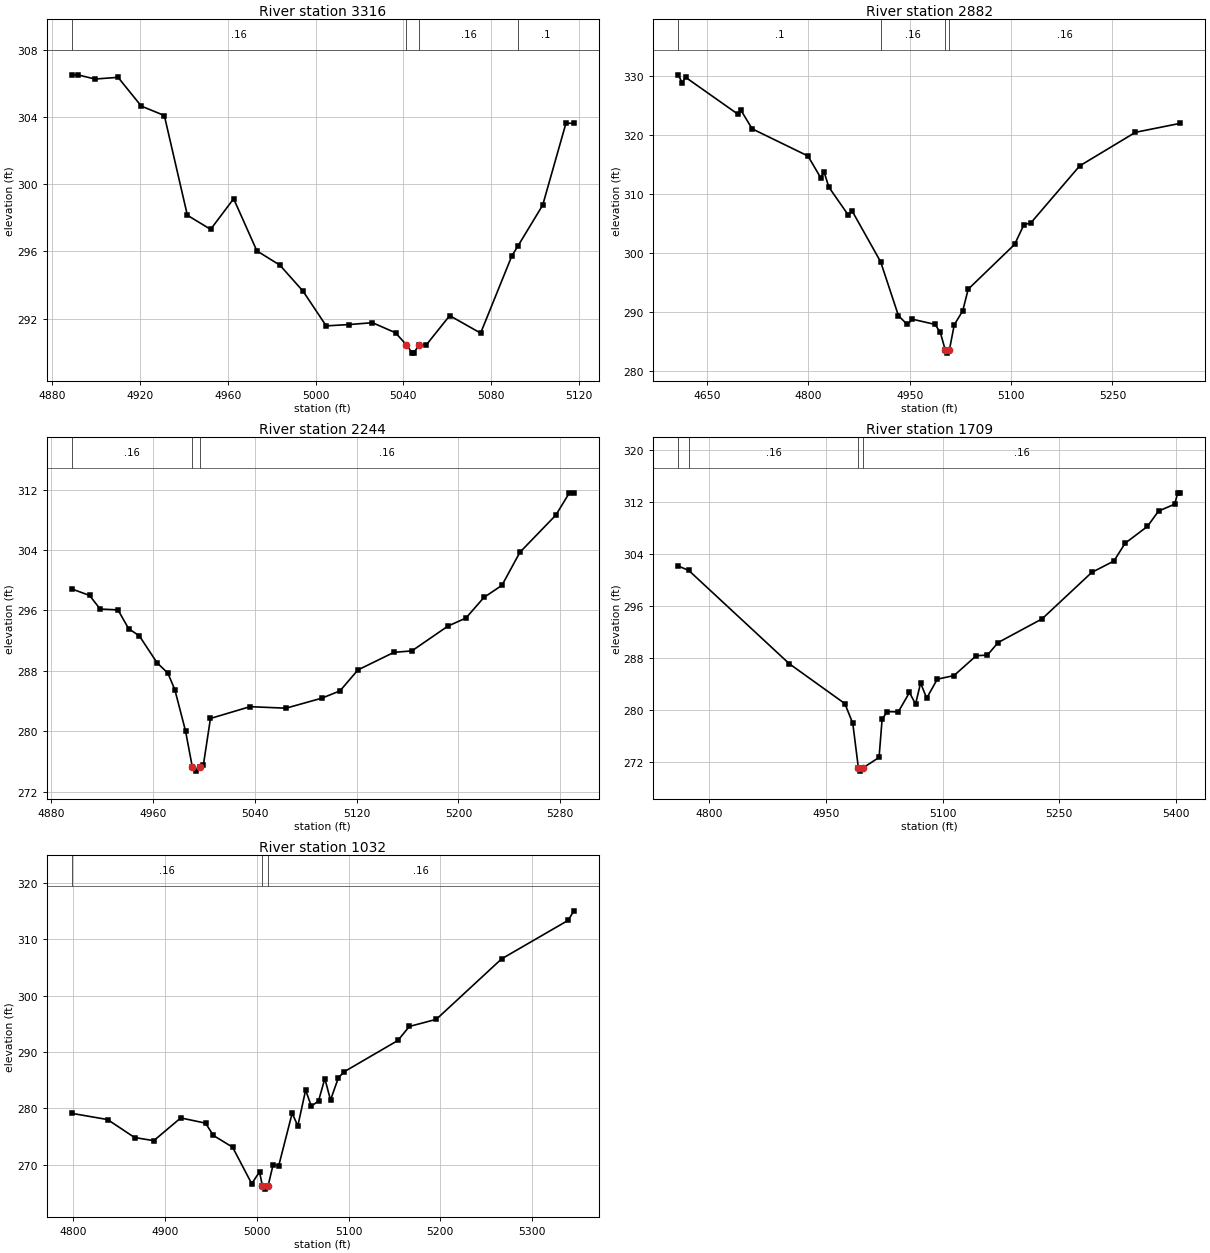
Type RM Length L Ch R = 1,3316,434,434,434
BEGIN DESCRIPTION:
UNT141 IN BECR 5.0
END DESCRIPTION:
XS GIS Cut Line= 3
      3782349.60     10503310.16      3782399.61     10503460.19
      3782449.64     10503510.22
#Sta/Elev= 28
  4888.8  306.50  4891.5  306.50  4899.4  306.25  4909.9  306.35  4920.5  304.64
  4931.0  304.08  4941.5  298.15  4952.1  297.31  4962.6  299.13  4973.2  296.03
  4983.7  295.18  4994.2  293.64  5004.8  291.57  5015.3  291.65  5025.9  291.76
  5036.4  291.16  5041.3  290.45  5044.1  289.95  5044.6  289.95  5047.3  290.45
  5050.5  290.45  5061.1  292.18  5075.2  291.14  5089.4  295.72  5092.3  296.34
  5103.5  298.75  5114.1  303.62  5117.7  303.62
#Mann=4,-1,0
  4888.8    0.16       0  5041.3    0.07       0  5047.3    0.16       0
  5092.3     0.1       0
Bank Sta=5041.3,5047.3
Exp/Cntr=0.3,0.1

Type RM Length L Ch R = 1,2882,638,638,638
BEGIN DESCRIPTION:
UNT141 IN BECR 4.0
END DESCRIPTION:
XS GIS Cut Line= 2
      3781982.05     10503184.10      3782164.35     10503904.60
#Sta/Elev= 30
  4607.2  330.16  4613.0  328.81  4618.1  329.74  4695.0  323.54  4700.2  324.13
  4716.6  321.02  4799.2  316.42  4818.0  312.76  4823.2  313.68  4830.1  311.16
  4859.1  306.39  4864.2  307.19  4906.8  298.51  4933.2  289.38  4946.2  287.90
  4953.9  288.79  4987.3  287.91  4995.1  286.57  5002.5  283.55  5005.2  283.05
  5008.5  283.55  5015.8  287.84  5028.3  290.21  5036.4  293.87  5105.1  301.45
  5118.9  304.79  5129.2  305.10  5201.4  314.74  5284.0  320.43  5350.4  321.95
#Mann=4,-1,0
  4607.2     0.1       0  4906.8    0.16       0  5002.5    0.07       0
  5008.5    0.16       0
Bank Sta=5002.5,5008.5
Exp/Cntr=0.3,0.1

Type RM Length L Ch R = 1,2244,535,535,535
BEGIN DESCRIPTION:
UNT141 IN BECR 3.0
END DESCRIPTION:
XS GIS Cut Line= 3
      3781549.62     10503610.20      3781599.61     10503710.19
      3781799.59     10503910.17
#Sta/Elev= 30
  4896.1  298.84  4910.1  297.98  4918.4  296.18  4932.4  296.07  4940.8  293.58
  4949.2  292.63  4963.2  289.05  4971.6  287.71  4977.1  285.51  4985.5  280.05
  4990.9  275.23  4993.7  274.73  4996.9  275.23  4999.5  275.50  5005.1  281.70
  5036.2  283.26  5064.5  283.06  5092.7  284.39  5106.9  285.35  5121.0  288.12
  5149.3  290.45  5163.4  290.64  5191.7  293.92  5205.9  294.99  5220.0  297.71
  5234.2  299.32  5248.3  303.69  5276.6  308.62  5287.2  311.56  5290.7  311.56
#Mann=3,-1,0
  4896.1    0.16       0  4990.9    0.07       0  4996.9    0.16       0
Bank Sta=4990.9,4996.9
Exp/Cntr=0.3,0.1

Type RM Length L Ch R = 1,1709,677,677,677
BEGIN DESCRIPTION:
UNT141 IN BECR 2.0
END DESCRIPTION:
XS GIS Cut Line= 3
      3781149.61     10503610.19      3781199.61     10503860.19
      3781449.63     10504160.22
#Sta/Elev= 30
  4760.0  302.11  4773.5  301.43  4902.8  287.07  4974.2  280.94  4984.4  277.91
  4991.6  271.05  4994.3  270.55  4997.6  271.05  5018.2  272.66  5022.1  278.52
  5028.6  279.71  5042.9  279.66  5057.3  282.65  5065.1  280.86  5071.6  284.11
  5079.4  281.78  5093.1  284.70  5114.5  285.25  5143.2  288.31  5157.5  288.40
  5171.2  290.33  5227.8  293.98  5291.6  301.12  5320.2  302.88  5334.5  305.61
  5363.2  308.20  5377.5  310.56  5398.3  311.63  5402.2  313.37  5405.5  313.37
#Mann=4,-1,0
  4760.0     0.1       0  4773.5    0.16       0  4991.6    0.07       0
  4997.6    0.16       0
Bank Sta=4991.6,4997.6
Exp/Cntr=0.3,0.1

Type RM Length L Ch R = 1,1032,0,0,0
BEGIN DESCRIPTION:
UNT141 IN BECR 1.0
END DESCRIPTION:
XS GIS Cut Line= 2
      3780732.07     10504112.95      3781174.66     10504434.04
#Sta/Elev= 30
  4798.6  279.11  4837.6  278.01  4867.0  274.82  4887.9  274.26  4917.3  278.30
  4944.3  277.37  4952.8  275.19  4973.7  273.11  4994.6  266.62  5003.1  268.73
  5006.3  266.16  5009.0  265.66  5012.3  266.16  5017.8  269.95  5024.0  269.81
  5038.6  279.13  5044.8  276.89  5053.3  283.25  5059.5  280.36  5067.4  281.34
  5074.2  285.29  5080.4  281.47  5088.9  285.40  5095.1  286.48  5153.8  292.05
  5166.2  294.53  5195.6  295.80  5266.7  306.53  5339.2  313.37  5345.4  315.06
#Mann=3,-1,0
  4798.6    0.16       0  5006.3    0.07       0  5012.3    0.16       0
Bank Sta=5006.3,5012.3
Exp/Cntr=0.3,0.1

Chan Stop Cuts=-1