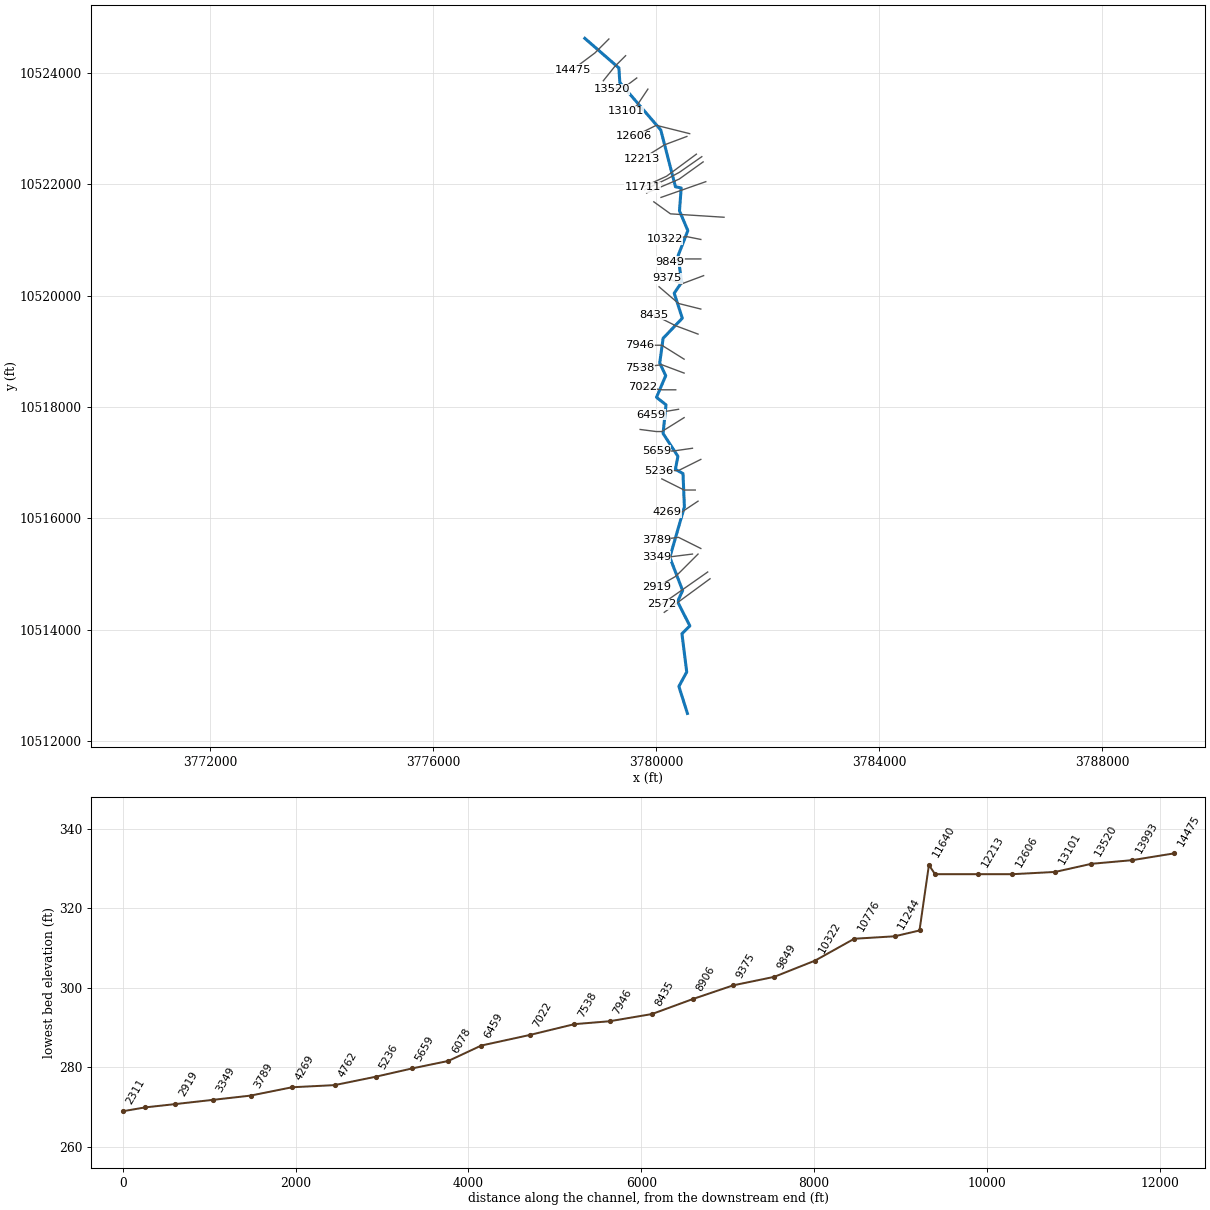
--- UNT143 IN BECR.prj (project) ---

Proj Title=UNT143 IN BECR Base Level Engineering
Current Plan=p01
Default Exp/Contr=0.3,0.1
English Units
Geom File=g01
Flow File=f01
Plan File=p01
BEGIN DESCRIPTION:
UNT143 IN BECR
END DESCRIPTION:

--- UNT143 IN BECR.p01 (plan) ---

Plan Title=Multiple Run
Short Identifier=Multiple
Geom File=g01
Flow File=f01
Subcritical Flow
K Sum by GR= 0
Std Step Tol= 0.01
Critical Tol= 0.01
Num of Std Step Trials= 20
Max Error Tol= 0.3
Flow Tol Ratio= 0.001
Split Flow NTrial= 30
Split Flow Tol= 0.02
Split Flow Ratio= 0.02
Log Output Level= 0
Friction Slope Method= 1
Unsteady Friction Slope Method= 2
Unsteady Bridges Friction Slope Method= 1
Parabolic Critical Depth
Global Vel Dist=  1 , 1 , 1
Global Log Level= 0
CheckData=True
Encroach Param= -1, 0, 0, 0
BEGIN DESCRIPTION:
Multiple Run
END DESCRIPTION:

--- UNT143 IN BECR.f01 (steady flow) ---

Flow Title=Multiple
Number of Profiles=7
Profile Names=10-year,25-year,50-year,1pct_min,100-year,1pct_plu,500-year
River Rch & RM= UNT143 IN BECR,Reach-1,14475
     905    1246    1532    1383    1870    2529    2798
River Rch & RM= UNT143 IN BECR,Reach-1,6459
     980    1350    1662    1500    2028    2743    3033
Boundary for River Rch & Prof#=UNT143 IN BECR,Reach-1,1
Up Type=0
Dn Type=3
Dn Slope=0.005
Boundary for River Rch & Prof#=UNT143 IN BECR,Reach-1,2
Up Type=0
Dn Type=3
Dn Slope=0.005
Boundary for River Rch & Prof#=UNT143 IN BECR,Reach-1,3
Up Type=0
Dn Type=3
Dn Slope=0.005
Boundary for River Rch & Prof#=UNT143 IN BECR,Reach-1,4
Up Type=0
Dn Type=3
Dn Slope=0.005
Boundary for River Rch & Prof#=UNT143 IN BECR,Reach-1,5
Up Type=0
Dn Type=3
Dn Slope=0.005
Boundary for River Rch & Prof#=UNT143 IN BECR,Reach-1,6
Up Type=0
Dn Type=3
Dn Slope=0.005
Boundary for River Rch & Prof#=UNT143 IN BECR,Reach-1,7
Up Type=0
Dn Type=3
Dn Slope=0.005

--- UNT143 IN BECR.g01 (geometry) ---

Geom Title=Existing Conditions

River Reach=UNT143 IN BECR,Reach-1
Reach XY= 30
      3778717.51     10524621.99      3779329.00     10524090.00
      3779345.75     10523829.00      3780080.75     10522976.00
      3780344.00     10521956.00      3780447.25     10521935.00
      3780416.25     10521524.00      3780566.50     10521169.00
      3780390.00     10520715.00      3780455.50     10520241.00
      3780322.00     10520045.00      3780467.25     10519596.00
      3780122.25     10519234.00      3780062.00     10518790.00
      3780169.50     10518564.00      3780003.75     10518175.00
      3780174.75     10518040.00      3780121.75     10517526.00
      3780388.50     10517115.00      3780342.75     10516881.00
      3780479.50     10516806.00      3780504.75     10516207.00
      3780243.25     10515301.00      3780473.00     10514704.00
      3780381.25     10514506.00      3780603.00     10514070.00
      3780460.50     10513930.00      3780546.39     10513242.97
      3780405.76     10512982.55      3780558.75     10512499.00

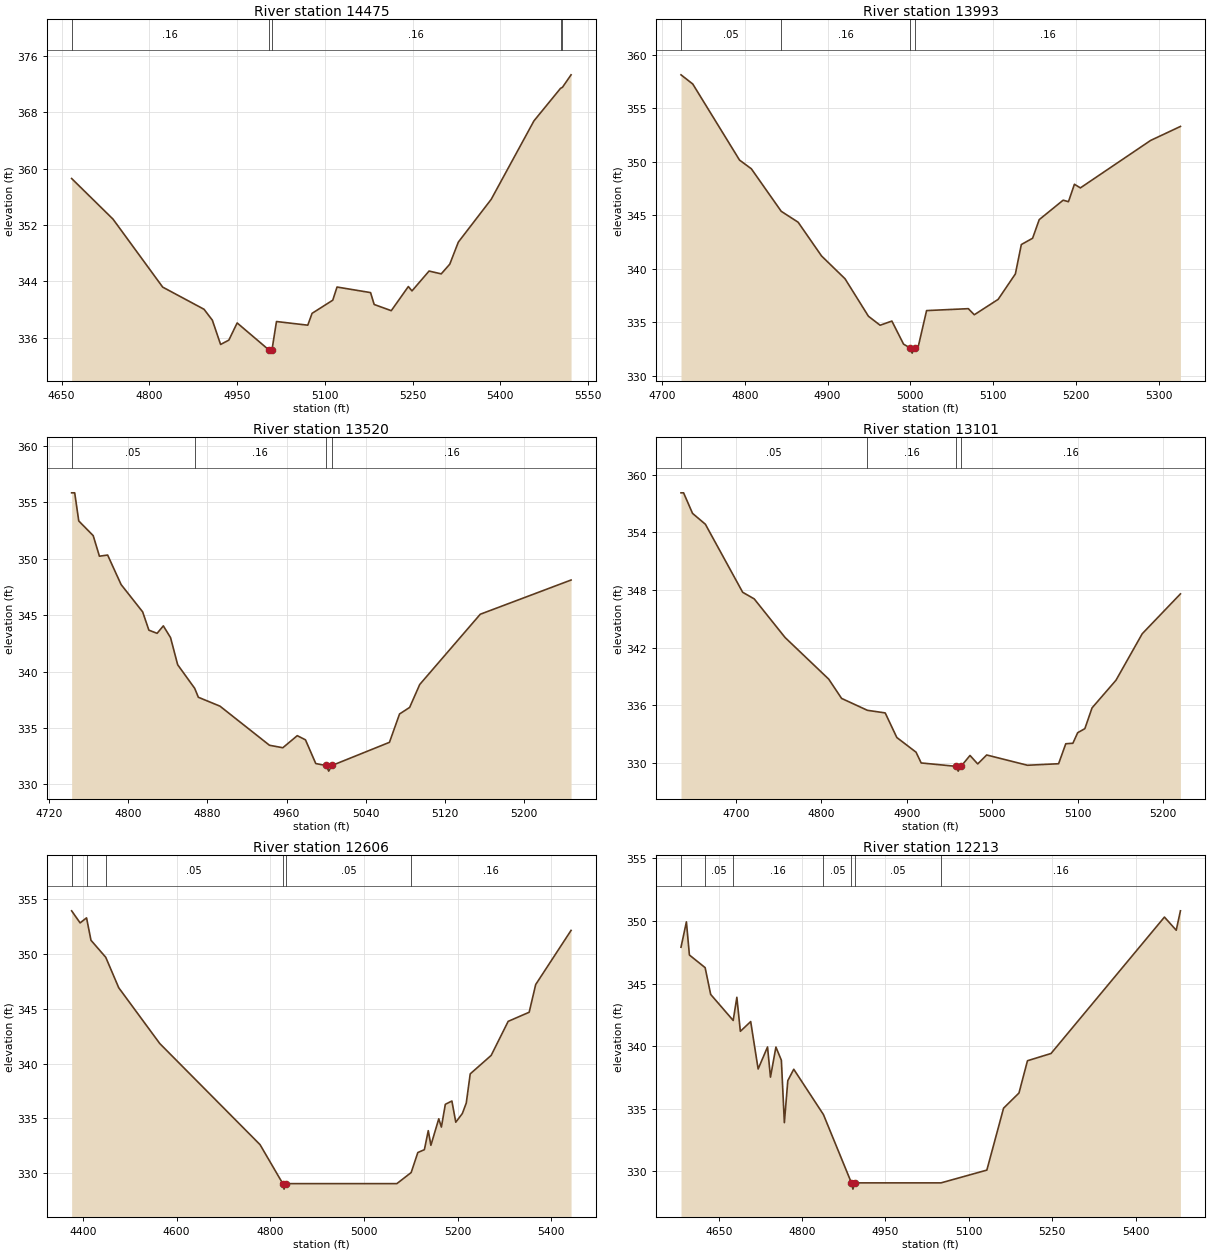
Type RM Length L Ch R = 1,14475,482,482,482
BEGIN DESCRIPTION:
UNT143 IN BECR 31.0
END DESCRIPTION:
XS GIS Cut Line= 3
      3779149.64     10524610.22      3778899.61     10524360.19
      3778499.61     10524060.19
#Sta/Elev= 30
  4667.3  358.61  4738.1  352.83  4822.9  343.18  4893.6  340.03  4907.8  338.48
  4921.9  335.03  4936.0  335.65  4950.2  338.09  5003.8  334.30  5006.5  333.80
  5009.8  334.30  5017.4  338.29  5070.9  337.77  5078.2  339.45  5113.6  341.32
  5120.9  343.19  5178.2  342.40  5184.4  340.71  5213.6  339.83  5242.8  343.26
  5249.0  342.64  5278.2  345.46  5299.0  345.06  5313.6  346.44  5328.2  349.57
  5384.4  355.65  5457.4  366.79  5502.9  371.42  5506.2  371.57  5520.9  373.34
#Mann=5,-1,0
  4667.3    0.16       0  5003.8    0.07       0  5009.8    0.16       0
  5502.9     0.1       0  5506.2    0.16       0
Bank Sta=5003.8,5009.8
Exp/Cntr=0.3,0.1

Type RM Length L Ch R = 1,13993,473,473,473
BEGIN DESCRIPTION:
UNT143 IN BECR 30.0
END DESCRIPTION:
XS GIS Cut Line= 3
      3779449.63     10524310.21      3779249.61     10524110.19
      3779049.62     10523860.21
#Sta/Elev= 30
  4723.1  358.14  4737.3  357.28  4793.8  350.16  4808.0  349.35  4844.1  345.37
  4864.5  344.35  4892.8  341.19  4921.1  339.06  4949.4  335.55  4963.5  334.71
  4977.7  335.10  4991.8  332.94  4999.4  332.60  5002.2  332.10  5005.4  332.60
  5009.2  332.60  5019.6  336.08  5070.0  336.26  5077.2  335.69  5106.0  337.13
  5126.8  339.51  5134.0  342.26  5147.6  342.85  5155.6  344.59  5184.5  346.41
  5190.9  346.27  5198.1  347.90  5205.3  347.56  5290.1  352.00  5326.1  353.31
#Mann=4,-1,0
  4723.1    0.05       0  4844.1    0.16       0  4999.4    0.07       0
  5005.4    0.16       0
Bank Sta=4999.4,5005.4
Exp/Cntr=0.3,0.1

Type RM Length L Ch R = 1,13520,419,419,419
BEGIN DESCRIPTION:
UNT143 IN BECR 29.0
END DESCRIPTION:
XS GIS Cut Line= 3
      3779649.57     10523910.16      3779449.61     10523760.19
      3779199.61     10523710.19
#Sta/Elev= 30
  4742.7  355.82  4745.8  355.82  4749.9  353.33  4764.5  352.03  4770.8  350.21
  4779.1  350.31  4792.7  347.70  4814.5  345.28  4820.8  343.66  4829.1  343.38
  4835.4  344.04  4842.7  343.00  4849.9  340.60  4867.1  338.51  4870.8  337.72
  4892.7  336.93  4942.7  333.47  4956.2  333.25  4970.8  334.32  4979.1  333.95
  4989.5  331.85  4999.9  331.68  5002.6  331.18  5005.9  331.68  5064.0  333.73
  5074.2  336.24  5084.4  336.82  5094.6  338.85  5155.8  345.07  5247.6  348.10
#Mann=4,-1,0
  4742.7    0.05       0  4867.1    0.16       0  4999.9    0.07       0
  5005.9    0.16       0
Bank Sta=4999.9,5005.9
Exp/Cntr=0.3,0.1

Type RM Length L Ch R = 1,13101,495,495,495
BEGIN DESCRIPTION:
UNT143 IN BECR 28.0
END DESCRIPTION:
XS GIS Cut Line= 3
      3779849.59     10523710.16      3779649.61     10523410.19
      3779449.63     10523310.20
#Sta/Elev= 30
  4636.0  358.11  4639.0  358.11  4649.5  355.97  4664.5  354.84  4708.1  347.76
  4721.6  347.07  4757.7  343.05  4808.7  338.72  4823.8  336.71  4854.0  335.47
  4874.8  335.20  4888.4  332.64  4910.9  331.11  4916.9  329.99  4957.5  329.64
  4960.2  329.14  4963.5  329.64  4974.0  330.77  4983.0  329.89  4993.5  330.82
  5041.2  329.75  5077.6  329.91  5086.0  331.99  5094.3  332.04  5099.9  333.14
  5108.3  333.56  5116.7  335.72  5144.7  338.60  5175.4  343.44  5220.1  347.59
#Mann=4,-1,0
  4636.0    0.05       0  4854.0    0.16       0  4957.5    0.07       0
  4963.5    0.16       0
Bank Sta=4957.5,4963.5
Exp/Cntr=0.3,0.1

Type RM Length L Ch R = 1,12606,393,393,393
BEGIN DESCRIPTION:
UNT143 IN BECR 27.0
END DESCRIPTION:
XS GIS Cut Line= 3
      3780599.64     10522910.18      3779999.61     10523060.19
      3779599.62     10522860.19
#Sta/Elev= 30
  4376.2  353.90  4394.3  352.80  4408.0  353.26  4417.5  351.22  4449.0  349.67
  4476.7  346.90  4564.3  341.82  4778.2  332.62  4826.8  329.07  4829.5  328.57
  4832.8  329.07  5070.2  329.07  5100.7  330.08  5114.9  331.90  5128.9  332.16
  5137.2  333.89  5142.8  332.56  5159.6  334.97  5165.2  334.22  5173.6  336.29
  5187.6  336.59  5195.9  334.66  5209.9  335.45  5218.3  336.41  5226.7  339.06
  5271.4  340.74  5307.7  343.84  5352.5  344.67  5366.4  347.19  5441.9  352.12
#Mann=6,-1,0
  4376.2    0.05       0  4408.0    0.16       0  4449.0    0.05       0
  4826.8   0.035       0  4832.8    0.05       0  5100.7    0.16       0
Bank Sta=4826.8,4832.8
Exp/Cntr=0.3,0.1

Type RM Length L Ch R = 1,12213,502,502,502
BEGIN DESCRIPTION:
UNT143 IN BECR 26.0
END DESCRIPTION:
XS GIS Cut Line= 3
      3780549.56     10522860.17      3780149.61     10522710.19
      3779749.65     10522460.21
#Sta/Elev= 30
  4582.0  347.90  4591.7  349.93  4597.1  347.28  4625.4  346.27  4635.4  344.13
  4675.9  342.05  4682.5  343.90  4688.8  341.18  4707.4  341.96  4720.8  338.17
  4737.7  339.93  4743.0  337.52  4752.8  339.92  4762.6  338.87  4768.0  333.88
  4774.2  337.24  4784.9  338.15  4838.3  334.53  4888.7  329.07  4891.4  328.57
  4894.7  329.07  5050.0  329.07  5132.4  330.09  5162.5  335.04  5190.2  336.25
  5205.5  338.83  5247.9  339.41  5452.0  350.31  5473.2  349.26  5480.8  350.81
#Mann=7,-1,0
  4582.0    0.16       0  4625.4    0.05       0  4675.9    0.16       0
  4838.3    0.05       0  4888.7   0.033       0  4894.7    0.05       0
  5050.0    0.16       0
Bank Sta=4888.7,4894.7
Exp/Cntr=0.3,0.1

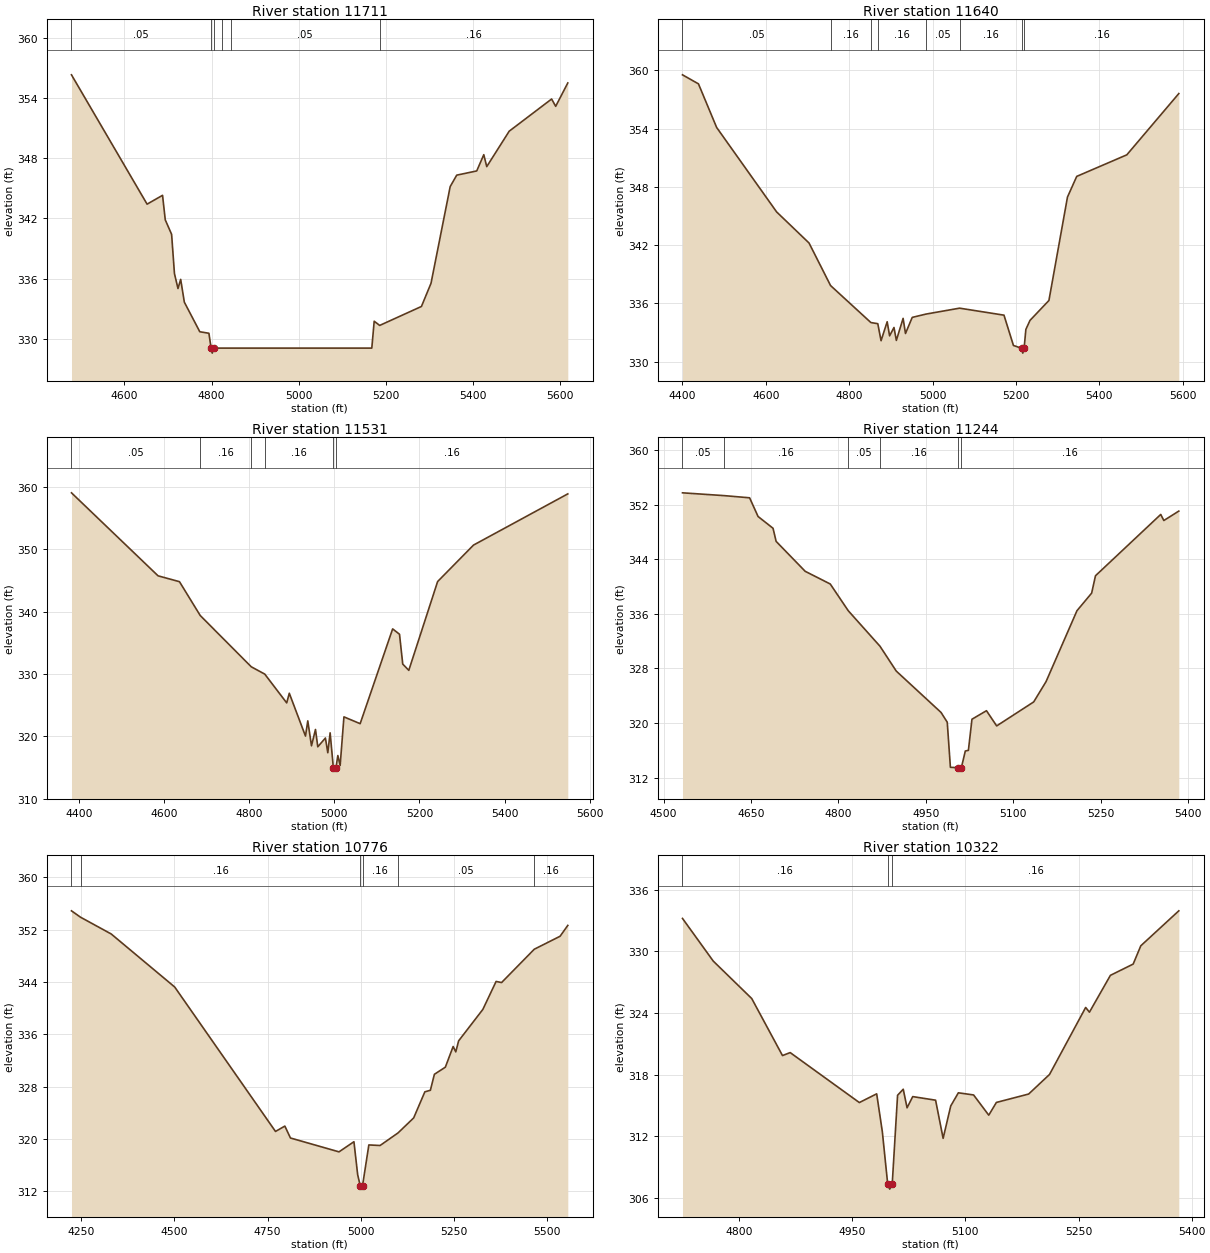
Type RM Length L Ch R = 1,11711,71,71,71
BEGIN DESCRIPTION:
UNT143 IN BECR 25.0
END DESCRIPTION:
XS GIS Cut Line= 3
      3780719.52     10522541.76      3780184.76     10522145.90
      3779754.39     10521948.06
#Sta/Elev= 30
  4478.4  356.31  4651.9  343.42  4687.4  344.30  4693.6  341.86  4708.2  340.41
  4714.7  336.50  4722.8  335.01  4729.0  335.92  4737.4  333.65  4772.9  330.70
  4793.8  330.55  4798.8  329.07  4801.5  328.57  4804.8  329.07  4824.4  329.07
  4844.2  329.07  5167.6  329.07  5173.1  331.75  5185.7  331.33  5281.5  333.22
  5303.5  335.53  5347.5  345.17  5362.5  346.31  5408.4  346.73  5424.6  348.35
  5431.4  347.16  5482.9  350.69  5580.3  353.90  5589.6  353.17  5617.4  355.50
#Mann=6,-1,0
  4478.4    0.05       0  4798.8   0.035       0  4804.8    0.05       0
  4824.4    0.16       0  4844.2    0.05       0  5185.7    0.16       0
Bank Sta=4798.8,4804.8
Exp/Cntr=0.3,0.1

Type RM Length L Ch R = 1,11640,109,109,109
BEGIN DESCRIPTION:
Mapping XS 4b3dee48
END DESCRIPTION:
XS GIS Cut Line= 4
      3780816.73     10522496.61      3780413.93     10522215.34
      3780209.07     10522104.23      3779788.88     10521902.82
#Sta/Elev= 30
  4400.4  359.54  4438.7  358.61  4482.3  354.12  4626.2  345.42  4703.9  342.22
  4755.5  337.84  4852.2  334.03  4868.8  333.91  4876.6  332.16  4891.3  334.11
  4897.1  332.66  4907.6  333.52  4913.3  332.19  4929.5  334.46  4935.2  332.90
  4951.4  334.56  4984.3  334.90  5064.9  335.51  5171.4  334.79  5194.1  331.67
  5213.7  331.38  5216.5  330.88  5219.7  331.38  5223.9  333.32  5233.8  334.25
  5279.2  336.30  5323.7  346.95  5345.9  349.08  5466.0  351.30  5590.7  357.61
#Mann=8,-1,0
  4400.4    0.05       0  4755.5    0.16       0  4852.2    0.05       0
  4868.8    0.16       0  4984.3    0.05       0  5064.9    0.16       0
  5213.7   0.035       0  5219.7    0.16       0
Bank Sta=5213.7,5219.7
Exp/Cntr=0.3,0.1

Type RM Length L Ch R = 1,11531,287,287,287
BEGIN DESCRIPTION:
Mapping XS f1dd5595
END DESCRIPTION:
XS GIS Cut Line= 4
      3780841.02     10522402.84      3780410.45     10522093.81
      3780257.68     10522027.84      3779825.79     10521844.72
#Sta/Elev= 30
  4383.0  359.04  4586.3  345.73  4636.6  344.79  4685.3  339.37  4805.2  331.14
  4836.9  329.97  4888.4  325.35  4894.5  326.90  4932.5  320.03  4937.9  322.47
  4946.6  318.47  4956.0  321.09  4961.4  318.31  4979.3  319.72  4984.9  317.36
  4990.4  320.55  4998.0  314.91  5000.8  314.41  5004.0  314.91  5008.5  316.91
  5013.9  315.31  5022.8  323.11  5060.9  322.02  5137.2  337.22  5153.3  336.36
  5160.9  331.58  5175.1  330.57  5242.8  344.81  5327.1  350.66  5548.5  358.87
#Mann=6,-1,0
  4383.0    0.05       0  4685.3    0.16       0  4805.2    0.05       0
  4836.9    0.16       0  4998.0    0.07       0  5004.0    0.16       0
Bank Sta=4998,5004
Exp/Cntr=0.3,0.1

Type RM Length L Ch R = 1,11244,468,468,468
BEGIN DESCRIPTION:
UNT143 IN BECR 24.0
END DESCRIPTION:
XS GIS Cut Line= 2
      3780888.27     10522047.76      3780084.72     10521765.13
#Sta/Elev= 30
  4532.5  353.76  4603.9  353.35  4647.7  353.03  4662.2  350.29  4687.9  348.56
  4693.2  346.64  4743.1  342.25  4786.1  340.39  4817.0  336.47  4871.5  331.26
  4899.4  327.62  4976.3  321.55  4986.9  320.12  4992.3  313.51  5005.1  313.45
  5007.8  312.95  5011.1  313.45  5017.9  315.90  5023.2  316.00  5029.3  320.56
  5054.2  321.81  5071.7  319.58  5135.3  323.10  5156.5  326.08  5209.5  336.47
  5234.7  339.05  5241.3  341.60  5353.3  350.59  5358.6  349.70  5384.3  351.08
#Mann=6,-1,0
  4532.5    0.05       0  4603.9    0.16       0  4817.0    0.05       0
  4871.5    0.16       0  5005.1    0.07       0  5011.1    0.16       0
Bank Sta=5005.1,5011.1
Exp/Cntr=0.3,0.1

Type RM Length L Ch R = 1,10776,454,454,454
BEGIN DESCRIPTION:
UNT143 IN BECR 23.0
END DESCRIPTION:
XS GIS Cut Line= 3
      3781216.04     10521408.86      3780254.90     10521469.97
      3779955.91     10521685.91
#Sta/Elev= 30
  4223.9  354.89  4248.3  353.91  4330.5  351.35  4500.9  343.24  4771.4  321.15
  4796.5  321.97  4811.5  320.15  4941.8  318.03  4981.9  319.58  4991.9  314.54
  4998.9  312.83  5001.6  312.33  5004.9  312.83  5021.9  319.09  5052.0  319.00
  5100.3  320.93  5142.2  323.22  5172.2  327.21  5187.0  327.45  5197.8  329.89
  5227.2  330.98  5248.1  334.14  5255.2  333.32  5262.8  335.00  5327.8  339.81
  5363.4  344.09  5378.1  343.92  5465.9  349.02  5535.1  351.00  5555.8  352.66
#Mann=6,-1,0
  4223.9    0.05       0  4248.3    0.16       0  4998.9    0.07       0
  5004.9    0.16       0  5100.3    0.05       0  5465.9    0.16       0
Bank Sta=4998.9,5004.9
Exp/Cntr=0.3,0.1

Type RM Length L Ch R = 1,10322,473,473,473
BEGIN DESCRIPTION:
UNT143 IN BECR 22.0
END DESCRIPTION:
XS GIS Cut Line= 3
      3780799.60     10521010.19      3780549.61     10521060.19
      3780149.56     10521010.18
#Sta/Elev= 30
  4724.9  333.22  4765.7  329.06  4816.7  325.41  4857.5  319.85  4867.7  320.14
  4959.4  315.27  4982.4  316.12  4989.9  312.42  4997.0  307.33  4999.7  306.83
  5003.0  307.33  5010.1  315.98  5017.6  316.57  5022.7  314.76  5030.2  315.85
  5060.5  315.50  5070.5  311.78  5080.6  314.94  5090.7  316.22  5110.9  316.01
  5131.0  314.04  5141.1  315.28  5183.9  316.10  5211.6  318.01  5259.5  324.54
  5264.5  324.08  5292.3  327.67  5322.5  328.77  5332.6  330.55  5383.0  333.96
#Mann=3,-1,0
  4724.9    0.16       0  4997.0    0.07       0  5003.0    0.16       0
Bank Sta=4997,5003
Exp/Cntr=0.3,0.1

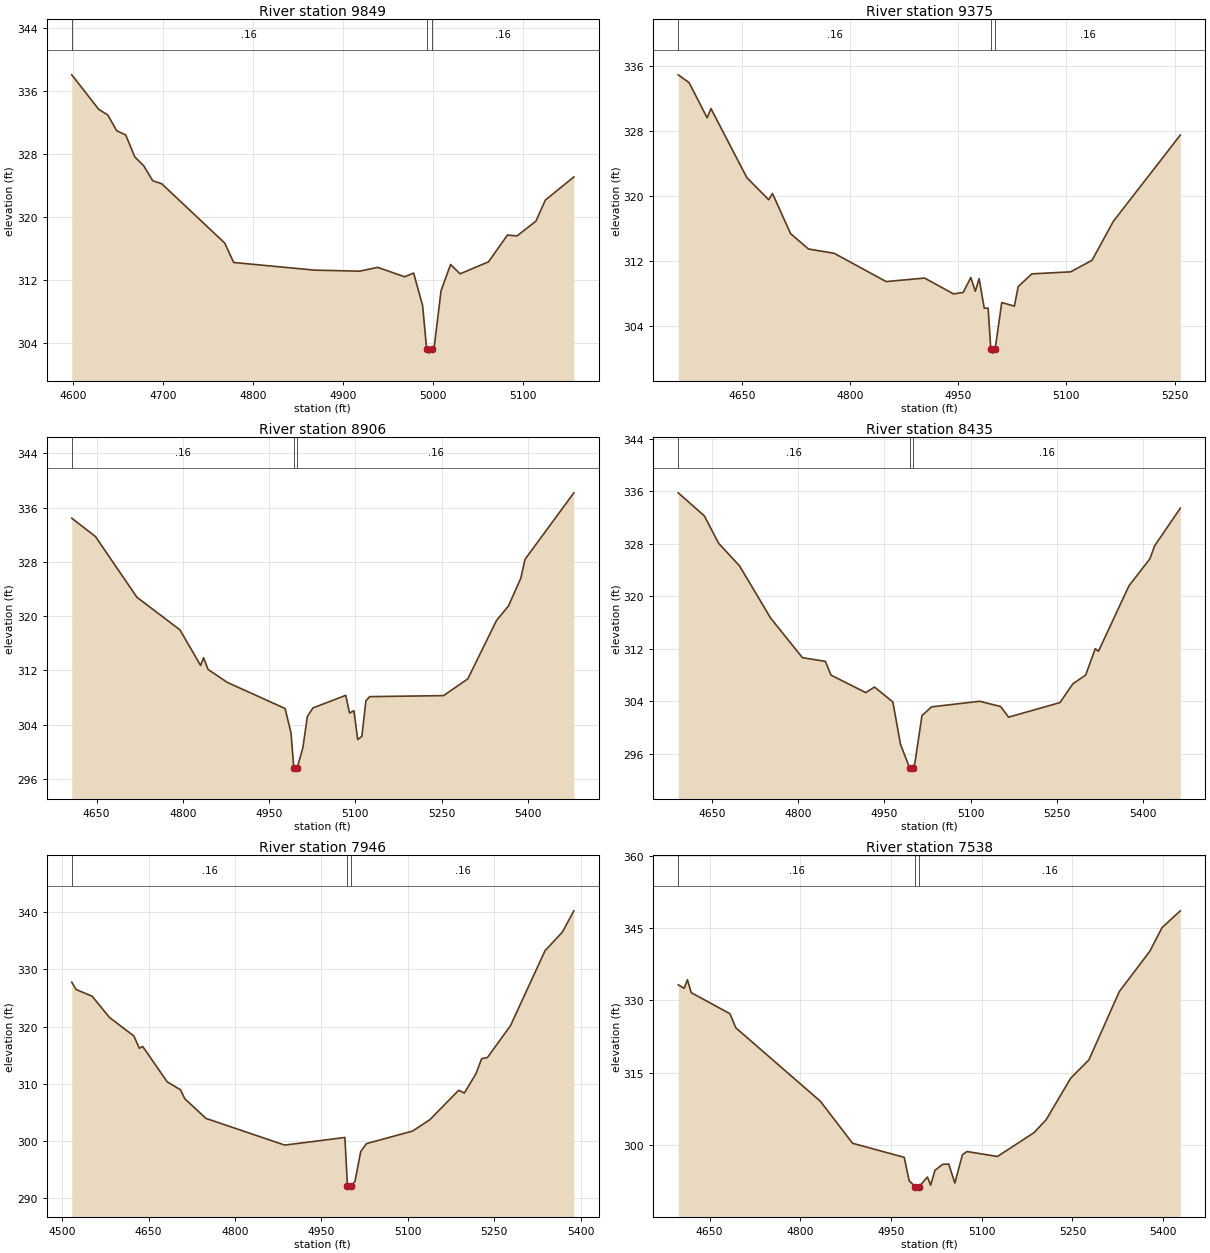
Type RM Length L Ch R = 1,9849,474,474,474
BEGIN DESCRIPTION:
UNT143 IN BECR 21.0
END DESCRIPTION:
XS GIS Cut Line= 3
      3780799.60     10520660.19      3780399.61     10520660.19
      3780249.62     10520610.19
#Sta/Elev= 30
  4598.1  338.05  4628.1  333.67  4638.1  332.96  4648.1  330.95  4658.1  330.42
  4668.1  327.65  4678.1  326.51  4688.1  324.61  4698.1  324.23  4768.1  316.71
  4778.1  314.24  4868.1  313.27  4918.1  313.14  4938.1  313.62  4968.1  312.43
  4978.1  312.90  4988.1  308.77  4992.6  303.24  4995.3  302.74  4998.6  303.24
  5000.7  303.24  5008.6  310.66  5019.2  313.99  5029.7  312.80  5061.3  314.32
  5082.4  317.72  5093.0  317.61  5114.0  319.48  5124.6  322.17  5156.2  325.09
#Mann=3,-1,0
  4598.1    0.16       0  4992.6    0.07       0  4998.6    0.16       0
Bank Sta=4992.6,4998.6
Exp/Cntr=0.3,0.1

Type RM Length L Ch R = 1,9375,469,469,469
BEGIN DESCRIPTION:
UNT143 IN BECR 20.0
END DESCRIPTION:
XS GIS Cut Line= 3
      3780849.62     10520360.19      3780449.61     10520210.19
      3780199.58     10520310.20
#Sta/Elev= 30
  4561.5  334.95  4576.6  333.98  4601.6  329.64  4606.9  330.78  4656.7  322.26
  4687.0  319.54  4692.3  320.30  4717.3  315.36  4742.2  313.46  4777.8  312.93
  4849.9  309.44  4903.3  309.87  4943.3  307.92  4956.7  308.09  4967.4  309.94
  4973.6  308.25  4978.9  309.80  4986.0  306.16  4991.4  306.16  4995.1  301.11
  4997.9  300.61  5001.1  301.11  5010.3  306.85  5027.8  306.41  5033.1  308.82
  5052.0  310.39  5105.8  310.64  5135.5  312.06  5165.1  316.87  5258.0  327.52
#Mann=3,-1,0
  4561.5    0.16       0  4995.1    0.07       0  5001.1    0.16       0
Bank Sta=4995.1,5001.1
Exp/Cntr=0.3,0.1

Type RM Length L Ch R = 1,8906,471,471,471
BEGIN DESCRIPTION:
UNT143 IN BECR 19.0
END DESCRIPTION:
XS GIS Cut Line= 3
      3780799.56     10519760.20      3780399.61     10519860.19
      3780049.64     10520160.16
#Sta/Elev= 30
  4606.8  334.43  4648.0  331.73  4720.1  322.78  4794.9  317.98  4830.9  312.72
  4836.1  313.86  4843.8  312.14  4877.3  310.23  4977.8  306.38  4988.1  302.80
  4992.9  297.65  4995.6  297.15  4998.9  297.65  5008.8  300.62  5016.5  305.19
  5026.2  306.46  5083.3  308.32  5089.9  305.71  5097.5  306.05  5104.1  301.81
  5111.3  302.27  5118.4  307.52  5125.0  308.13  5253.4  308.28  5295.6  310.75
  5345.6  319.37  5366.4  321.51  5387.8  325.59  5395.0  328.36  5480.0  338.17
#Mann=3,-1,0
  4606.8    0.16       0  4992.9    0.07       0  4998.9    0.16       0
Bank Sta=4992.9,4998.9
Exp/Cntr=0.3,0.1

Type RM Length L Ch R = 1,8435,489,489,489
BEGIN DESCRIPTION:
UNT143 IN BECR 18.0
END DESCRIPTION:
XS GIS Cut Line= 3
      3780749.62     10519310.18      3780349.61     10519460.19
      3779949.63     10519660.18
#Sta/Elev= 30
  4590.8  335.78  4636.2  332.28  4661.1  328.10  4697.6  324.65  4751.9  316.68
  4807.1  310.67  4847.1  310.11  4856.9  308.01  4917.4  305.35  4932.6  306.20
  4964.6  303.92  4978.0  297.44  4993.7  293.89  4996.4  293.39  4999.7  293.89
  5002.9  294.60  5015.3  301.85  5032.0  303.18  5115.8  304.03  5152.2  303.23
  5166.1  301.61  5255.6  303.83  5278.0  306.68  5300.3  308.02  5317.1  312.04
  5322.7  311.65  5375.8  321.62  5412.1  325.71  5420.5  327.71  5465.2  333.44
#Mann=3,-1,0
  4590.8    0.16       0  4993.7    0.07       0  4999.7    0.16       0
Bank Sta=4993.7,4999.7
Exp/Cntr=0.3,0.1

Type RM Length L Ch R = 1,7946,408,408,408
BEGIN DESCRIPTION:
UNT143 IN BECR 17.0
END DESCRIPTION:
XS GIS Cut Line= 3
      3780499.59     10518860.20      3780099.61     10519110.19
      3779699.59     10519110.19
#Sta/Elev= 30
  4516.7  327.76  4524.3  326.48  4552.1  325.31  4582.1  321.60  4624.6  318.35
  4634.0  316.22  4639.9  316.52  4682.4  310.34  4705.4  308.96  4713.0  307.38
  4749.6  303.95  4886.4  299.28  4990.9  300.61  4995.4  292.08  4998.1  291.58
  5001.4  292.08  5008.4  292.92  5018.4  298.15  5028.4  299.54  5108.4  301.73
  5138.4  303.72  5188.4  308.86  5198.4  308.39  5218.4  311.75  5228.4  314.39
  5238.4  314.60  5278.4  320.16  5338.4  333.27  5368.4  336.51  5388.4  340.24
#Mann=3,-1,0
  4516.7    0.16       0  4995.4    0.07       0  5001.4    0.16       0
Bank Sta=4995.4,5001.4
Exp/Cntr=0.3,0.1

Type RM Length L Ch R = 1,7538,516,516,516
BEGIN DESCRIPTION:
UNT143 IN BECR 16.0
END DESCRIPTION:
XS GIS Cut Line= 3
      3780499.65     10518610.17      3780099.61     10518760.19
      3779699.56     10518710.18
#Sta/Elev= 30
  4598.0  333.23  4607.8  332.50  4613.2  334.28  4619.4  331.61  4683.5  327.23
  4693.3  324.30  4833.0  309.09  4886.4  300.36  4971.8  297.44  4979.9  292.58
  4990.2  291.35  4993.0  290.85  4996.2  291.35  5010.1  293.36  5015.5  291.68
  5022.6  294.75  5035.3  295.99  5045.4  296.05  5055.5  292.12  5068.1  297.99
  5075.6  298.65  5126.0  297.62  5186.5  302.57  5206.6  305.26  5247.0  313.84
  5277.2  317.65  5327.6  331.84  5378.0  340.19  5398.1  345.08  5428.4  348.57
#Mann=3,-1,0
  4598.0    0.16       0  4990.2    0.07       0  4996.2    0.16       0
Bank Sta=4990.2,4996.2
Exp/Cntr=0.3,0.1

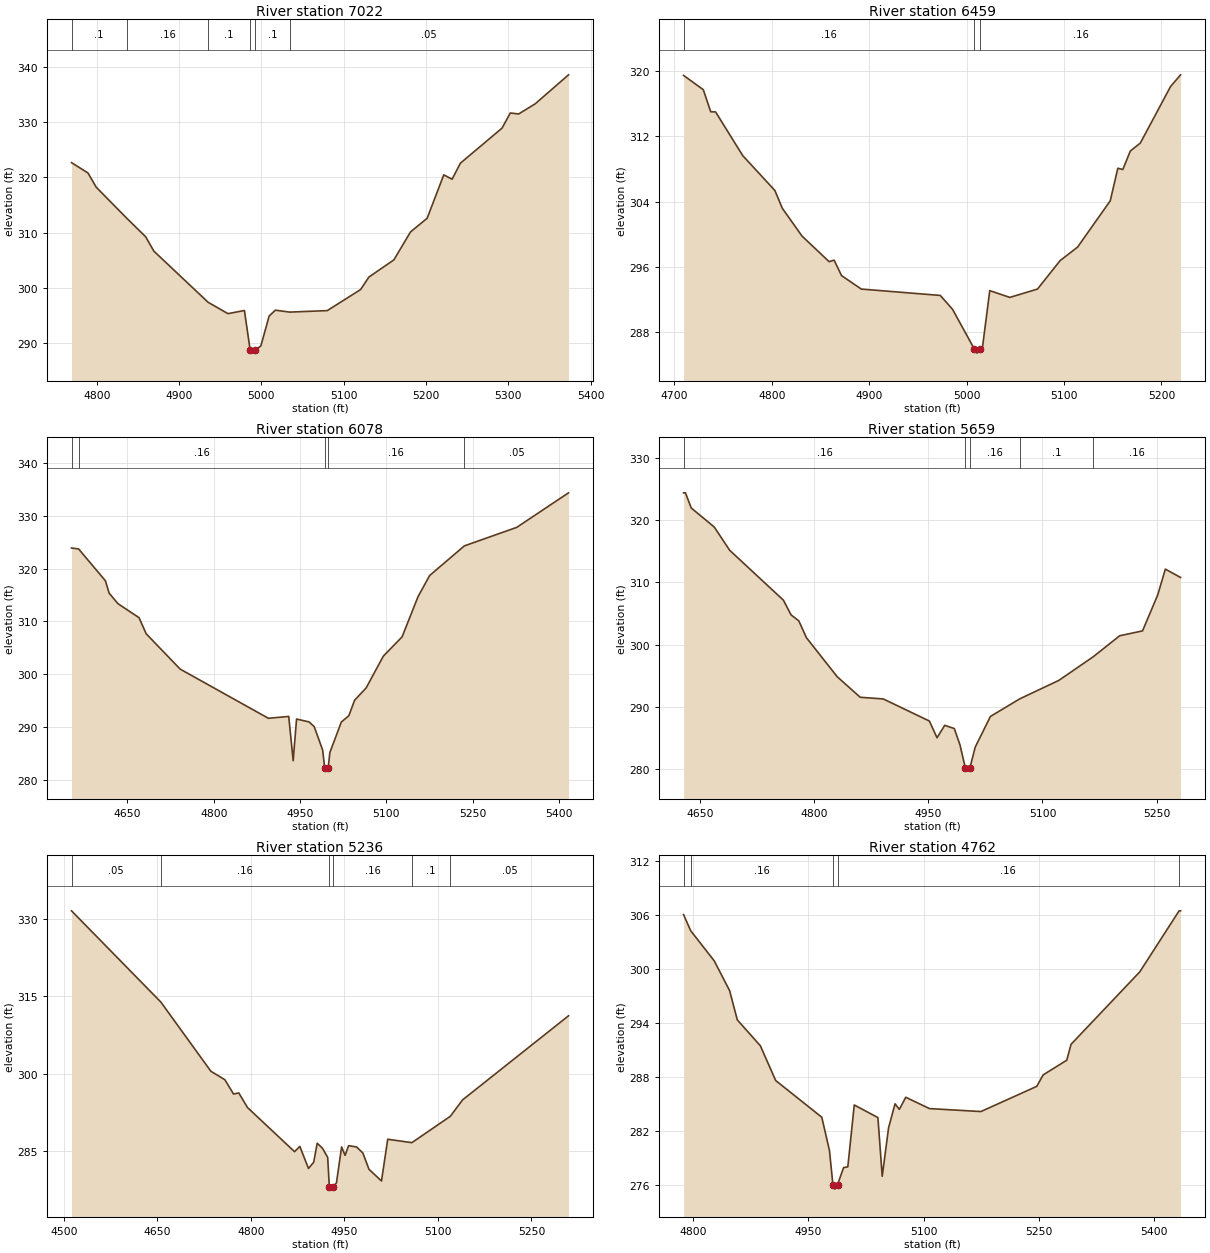
Type RM Length L Ch R = 1,7022,563,563,563
BEGIN DESCRIPTION:
UNT143 IN BECR 15.0
END DESCRIPTION:
XS GIS Cut Line= 3
      3780349.64     10518310.19      3780099.61     10518310.19
      3779749.60     10518360.19
#Sta/Elev= 30
  4769.4  322.68  4789.4  320.80  4799.4  318.22  4836.5  312.59  4859.4  309.24
  4869.4  306.63  4935.3  297.35  4959.4  295.29  4979.4  295.86  4986.4  288.63
  4989.2  288.13  4992.4  288.63  4999.4  289.46  5009.4  294.85  5016.9  295.92
  5034.4  295.57  5080.0  295.84  5120.4  299.65  5130.6  301.93  5160.9  305.04
  5181.1  310.11  5201.3  312.59  5221.5  320.46  5231.6  319.67  5241.7  322.58
  5292.2  328.93  5302.3  331.68  5312.4  331.50  5332.6  333.35  5373.0  338.60
#Mann=6,-1,0
  4769.4     0.1       0  4836.5    0.16       0  4935.3     0.1       0
  4986.4    0.07       0  4992.4     0.1       0  5034.4    0.05       0
Bank Sta=4986.4,4992.4
Exp/Cntr=0.3,0.1

Type RM Length L Ch R = 1,6459,381,381,381
BEGIN DESCRIPTION:
UNT143 IN BECR 14.0
END DESCRIPTION:
XS GIS Cut Line= 3
      3780399.60     10517960.19      3780099.61     10517910.19
      3779899.59     10517860.18
#Sta/Elev= 30
  4709.4  319.45  4729.7  317.70  4737.3  315.00  4742.3  314.98  4770.2  309.63
  4803.2  305.36  4810.8  303.19  4831.0  299.79  4858.9  296.65  4864.0  296.84
  4871.6  294.95  4891.9  293.30  4973.0  292.52  4985.6  290.82  5008.0  285.96
  5010.7  285.46  5014.0  285.96  5016.1  285.96  5023.8  293.11  5044.4  292.28
  5072.8  293.30  5096.0  296.78  5114.0  298.44  5147.5  304.10  5155.3  308.09
  5160.4  307.93  5168.1  310.19  5178.4  311.17  5209.4  318.08  5219.7  319.52
#Mann=3,-1,0
  4709.4    0.16       0  5008.0    0.07       0  5014.0    0.16       0
Bank Sta=5008,5014
Exp/Cntr=0.3,0.1

Type RM Length L Ch R = 1,6078,419,419,419
BEGIN DESCRIPTION:
UNT143 IN BECR 13.0
END DESCRIPTION:
XS GIS Cut Line= 4
      3780499.59     10517810.17      3780099.61     10517560.19
      3779999.61     10517560.19      3779710.41     10517597.75
#Sta/Elev= 30
  4553.0  323.90  4565.3  323.73  4611.9  317.69  4618.4  315.33  4633.8  313.34
  4670.3  310.69  4682.7  307.64  4741.7  300.94  4895.0  291.61  4930.3  291.96
  4938.0  283.56  4943.9  291.47  4965.7  290.92  4974.6  290.02  4989.3  285.56
  4992.8  282.09  4995.5  281.59  4998.8  282.09  5001.7  285.10  5021.7  290.91
  5034.7  292.09  5044.7  295.03  5064.7  297.36  5094.7  303.41  5127.2  307.05
  5154.9  314.68  5175.1  318.69  5235.4  324.31  5326.4  327.82  5416.3  334.37
#Mann=5,-1,0
  4553.0    0.05       0  4565.3    0.16       0  4992.8    0.07       0
  4998.8    0.16       0  5235.4    0.05       0
Bank Sta=4992.8,4998.8
Exp/Cntr=0.3,0.1

Type RM Length L Ch R = 1,5659,423,423,423
BEGIN DESCRIPTION:
UNT143 IN BECR 12.0
END DESCRIPTION:
XS GIS Cut Line= 3
      3780649.56     10517260.18      3780299.61     10517210.19
      3779999.62     10517210.19
#Sta/Elev= 30
  4628.1  324.36  4630.6  324.36  4638.2  321.93  4668.5  318.87  4688.7  315.15
  4759.4  307.14  4769.5  304.77  4779.6  303.83  4789.7  301.11  4830.1  294.86
  4860.4  291.56  4890.7  291.29  4951.3  287.75  4961.4  285.06  4971.5  287.06
  4984.1  286.54  4991.6  283.91  4998.6  280.21  5001.4  279.71  5004.6  280.21
  5011.6  283.56  5031.6  288.48  5070.1  291.30  5121.6  294.27  5166.9  298.07
  5201.6  301.43  5231.6  302.21  5251.6  307.99  5261.6  312.12  5281.6  310.78
#Mann=5,-1,0
  4628.1    0.16       0  4998.6    0.07       0  5004.6    0.16       0
  5070.1     0.1       0  5166.9    0.16       0
Bank Sta=4998.6,5004.6
Exp/Cntr=0.3,0.1

Type RM Length L Ch R = 1,5236,474,474,474
BEGIN DESCRIPTION:
UNT143 IN BECR 11.0
END DESCRIPTION:
XS GIS Cut Line= 3
      3780799.61     10517060.19      3780399.61     10516860.19
      3780049.62     10516860.19
#Sta/Elev= 30
  4512.2  331.51  4655.5  313.84  4735.8  300.43  4758.2  298.80  4772.1  296.03
  4780.5  296.24  4794.5  293.41  4870.0  284.86  4878.4  285.89  4892.3  281.61
  4900.7  282.84  4906.3  286.50  4914.7  285.54  4923.1  283.75  4925.7  278.11
  4928.4  277.61  4931.7  278.11  4937.1  278.79  4945.4  285.78  4951.0  284.15
  4956.6  286.02  4969.4  285.78  4979.4  284.63  4989.4  281.44  5009.4  279.19
  5019.4  287.27  5058.1  286.61  5119.8  291.71  5139.4  294.89  5309.4  311.18
#Mann=6,-1,0
  4512.2    0.05       0  4655.5    0.16       0  4925.7    0.07       0
  4931.7    0.16       0  5058.1     0.1       0  5119.8    0.05       0
Bank Sta=4925.7,4931.7
Exp/Cntr=0.3,0.1

Type RM Length L Ch R = 1,4762,493,493,493
BEGIN DESCRIPTION:
UNT143 IN BECR 10.0
END DESCRIPTION:
XS GIS Cut Line= 3
      3780699.57     10516510.19      3780499.61     10516510.19
      3780099.59     10516710.20
#Sta/Elev= 30
  4787.4  306.05  4796.7  304.26  4827.4  300.90  4847.4  297.59  4857.4  294.34
  4887.4  291.46  4907.4  287.59  4967.4  283.51  4977.4  279.81  4981.9  276.01
  4984.6  275.51  4987.9  276.01  4995.8  277.90  5001.3  277.99  5009.7  284.87
  5040.5  283.47  5046.1  276.94  5054.4  282.34  5062.8  285.00  5068.4  284.38
  5076.8  285.73  5107.6  284.47  5174.6  284.14  5247.3  286.94  5255.7  288.22
  5286.4  289.85  5292.0  291.62  5381.5  299.68  5432.7  306.47  5434.6  306.47
#Mann=5,-1,0
  4787.4    0.05       0  4796.7    0.16       0  4981.9    0.07       0
  4987.9    0.16       0  5432.7    0.05       0
Bank Sta=4981.9,4987.9
Exp/Cntr=0.3,0.1

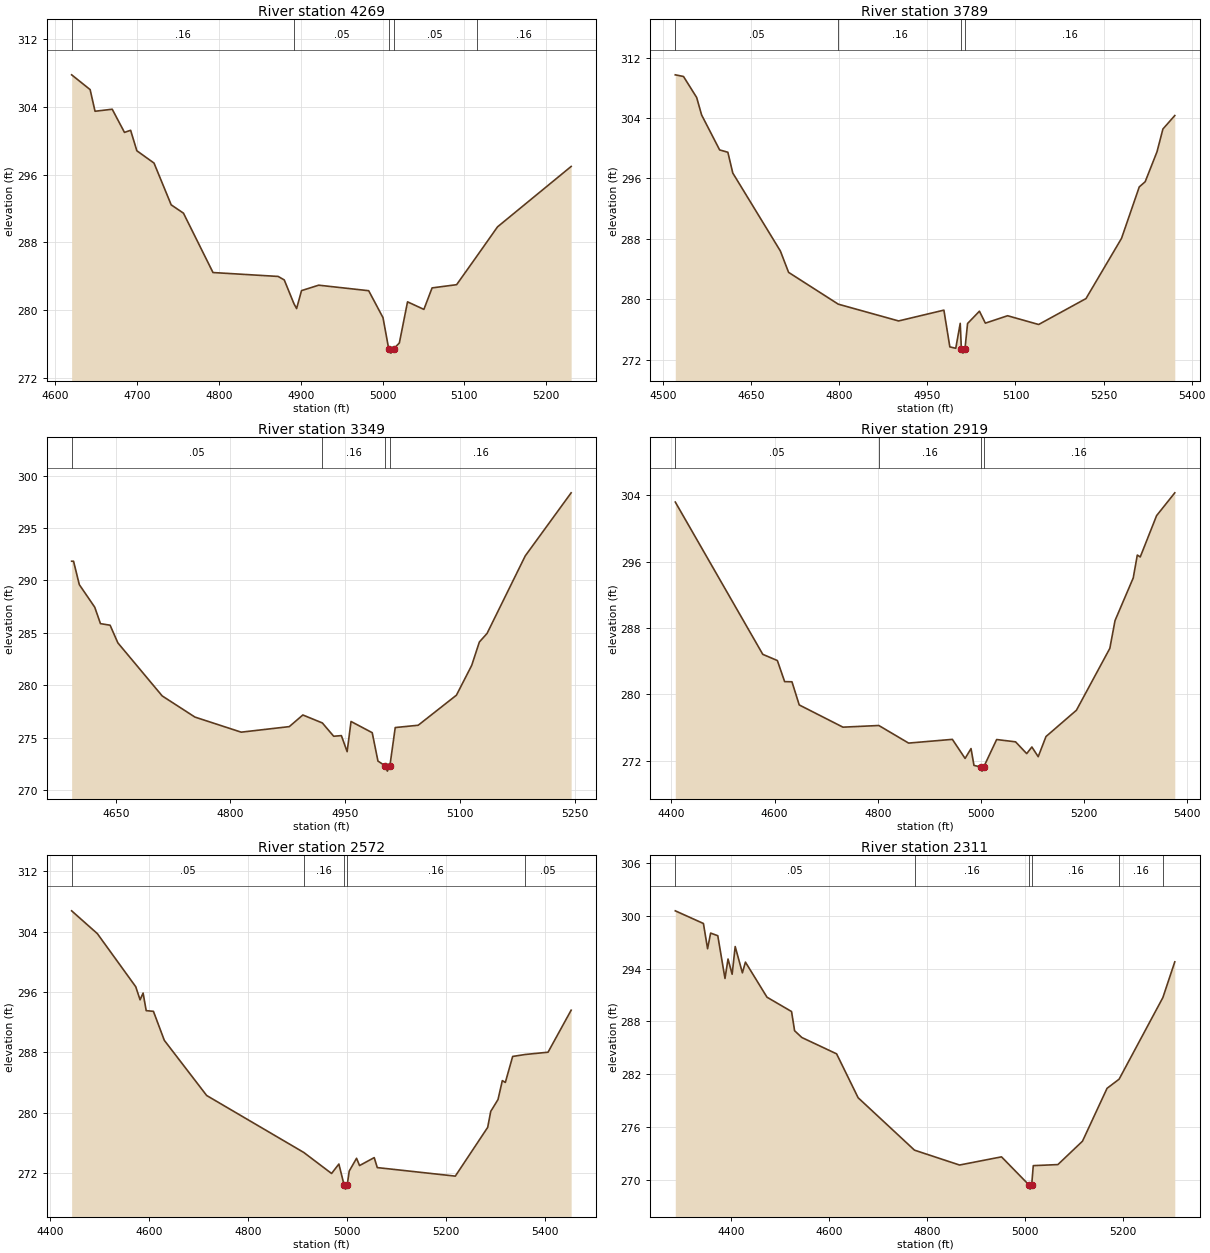
Type RM Length L Ch R = 1,4269,480,480,480
BEGIN DESCRIPTION:
UNT143 IN BECR 9.0
END DESCRIPTION:
XS GIS Cut Line= 3
      3780749.63     10516310.20      3780449.61     10516110.19
      3780199.59     10516110.19
#Sta/Elev= 30
  4620.0  307.74  4642.6  306.00  4648.6  303.45  4669.6  303.69  4684.6  300.96
  4692.1  301.21  4699.7  298.80  4720.7  297.35  4741.7  292.43  4756.7  291.45
  4792.8  284.46  4872.4  284.00  4879.9  283.59  4891.8  280.78  4895.0  280.22
  4901.0  282.33  4922.0  282.97  4983.1  282.32  5000.6  279.15  5007.6  275.47
  5010.3  274.97  5013.6  275.47  5020.6  276.17  5030.6  281.01  5050.6  280.12
  5060.6  282.65  5090.6  283.03  5115.3  286.38  5140.6  289.84  5230.6  296.95
#Mann=5,-1,0
  4620.0    0.16       0  4891.8    0.05       0  5007.6    0.04       0
  5013.6    0.05       0  5115.3    0.16       0
Bank Sta=5007.6,5013.6
Exp/Cntr=0.3,0.1

Type RM Length L Ch R = 1,3789,440,440,440
BEGIN DESCRIPTION:
UNT143 IN BECR 8.0
END DESCRIPTION:
XS GIS Cut Line= 3
      3780799.65     10515460.17      3780399.61     10515660.19
      3779999.58     10515610.19
#Sta/Elev= 30
  4520.9  309.71  4534.9  309.49  4557.3  306.71  4565.7  304.40  4596.4  299.77
  4610.4  299.46  4618.8  296.71  4699.8  286.39  4713.8  283.56  4798.4  279.35
  4901.1  277.13  4978.2  278.56  4988.3  273.70  4998.4  273.51  5006.0  276.81
  5008.0  273.37  5010.7  272.87  5014.0  273.37  5018.5  276.79  5038.7  278.42
  5048.8  276.84  5086.6  277.82  5139.5  276.66  5220.1  280.09  5280.6  288.06
  5310.8  294.87  5320.9  295.56  5341.0  299.52  5351.1  302.54  5371.3  304.32
#Mann=4,-1,0
  4520.9    0.05       0  4798.4    0.16       0  5008.0    0.07       0
  5014.0    0.16       0
Bank Sta=5008,5014
Exp/Cntr=0.3,0.1

Type RM Length L Ch R = 1,3349,430,430,430
BEGIN DESCRIPTION:
UNT143 IN BECR 7.0
END DESCRIPTION:
XS GIS Cut Line= 3
      3780649.56     10515360.18      3780249.61     10515310.19
      3779999.57     10515310.19
#Sta/Elev= 30
  4592.3  291.83  4594.8  291.83  4602.3  289.60  4622.5  287.44  4630.0  285.87
  4642.6  285.72  4652.7  284.04  4710.7  278.97  4753.5  276.95  4814.0  275.51
  4876.9  276.04  4894.6  277.15  4920.1  276.39  4934.9  275.12  4945.0  275.18
  4952.5  273.65  4957.6  276.53  4985.3  275.46  4992.8  272.75  5002.4  272.29
  5005.1  271.79  5008.4  272.29  5015.4  275.95  5045.4  276.17  5095.4  279.04
  5115.4  281.89  5125.4  284.12  5135.4  284.93  5185.4  292.34  5245.4  298.36
#Mann=4,-1,0
  4592.3    0.05       0  4920.1    0.16       0  5002.4    0.07       0
  5008.4    0.16       0
Bank Sta=5002.4,5008.4
Exp/Cntr=0.3,0.1

Type RM Length L Ch R = 1,2919,347,347,347
BEGIN DESCRIPTION:
UNT143 IN BECR 6.0
END DESCRIPTION:
XS GIS Cut Line= 3
      3780749.60     10515360.17      3780349.61     10514960.19
      3779999.59     10514760.18
#Sta/Elev= 30
  4407.4  303.18  4577.1  284.82  4605.4  284.07  4619.5  281.53  4633.7  281.51
  4647.8  278.72  4732.6  276.04  4802.2  276.24  4859.9  274.12  4944.8  274.57
  4969.5  272.27  4981.0  273.46  4986.7  271.43  4999.6  271.24  5002.3  270.74
  5005.6  271.24  5030.7  274.55  5067.4  274.27  5089.0  272.85  5099.0  273.65
  5111.3  272.48  5126.4  274.91  5185.4  278.08  5250.2  285.54  5260.3  288.89
  5295.6  294.03  5303.5  296.79  5309.2  296.56  5340.9  301.54  5376.2  304.29
#Mann=4,-1,0
  4407.4    0.05       0  4802.2    0.16       0  4999.6    0.07       0
  5005.6    0.16       0
Bank Sta=4999.6,5005.6
Exp/Cntr=0.3,0.1

Type RM Length L Ch R = 1,2572,261,261,261
BEGIN DESCRIPTION:
Mapping XS 589a8210
END DESCRIPTION:
XS GIS Cut Line= 2
      3780922.96     10515038.03      3780096.60     10514458.19
#Sta/Elev= 30
  4443.8  306.74  4495.8  303.72  4573.4  296.69  4582.1  294.96  4588.2  295.86
  4594.5  293.53  4609.1  293.44  4631.1  289.60  4716.7  282.30  4913.0  274.76
  4969.1  271.98  4983.9  273.23  4994.6  270.41  4997.4  269.91  5000.6  270.41
  5004.8  272.30  5019.6  273.99  5025.7  273.03  5055.3  274.08  5061.5  272.76
  5219.2  271.63  5284.6  278.08  5290.8  280.20  5305.5  281.77  5314.2  284.27
  5320.3  284.03  5335.1  287.47  5360.8  287.73  5406.6  288.03  5453.3  293.59
#Mann=5,-1,0
  4443.8    0.05       0  4913.0    0.16       0  4994.6    0.07       0
  5000.6    0.16       0  5360.8    0.05       0
Bank Sta=4994.6,5000.6
Exp/Cntr=0.3,0.1

Type RM Length L Ch R = 1,2311,385,385,385
BEGIN DESCRIPTION:
UNT143 IN BECR 5.0
END DESCRIPTION:
XS GIS Cut Line= 2
      3780964.59     10514916.48      3780143.20     10514313.43
#Sta/Elev= 30
  4285.9  300.58  4343.3  299.14  4351.8  296.27  4358.0  298.05  4372.6  297.75
  4387.3  292.89  4393.5  295.10  4401.9  293.37  4408.1  296.52  4422.8  293.53
  4429.0  294.75  4473.0  290.76  4523.1  289.13  4529.3  286.95  4544.0  286.18
  4615.0  284.32  4658.9  279.33  4773.9  273.37  4865.8  271.68  4951.4  272.61
  5007.0  269.44  5009.8  268.94  5013.0  269.44  5016.2  271.61  5066.4  271.73
  5116.6  274.39  5166.7  280.40  5191.3  281.44  5280.6  290.72  5304.9  294.78
#Mann=6,-1,0
  4285.9    0.05       0  4773.9    0.16       0  5007.0    0.07       0
  5013.0    0.16       0  5191.3    0.16       0  5280.6    0.05       0
Bank Sta=5007,5013
Exp/Cntr=0.3,0.1