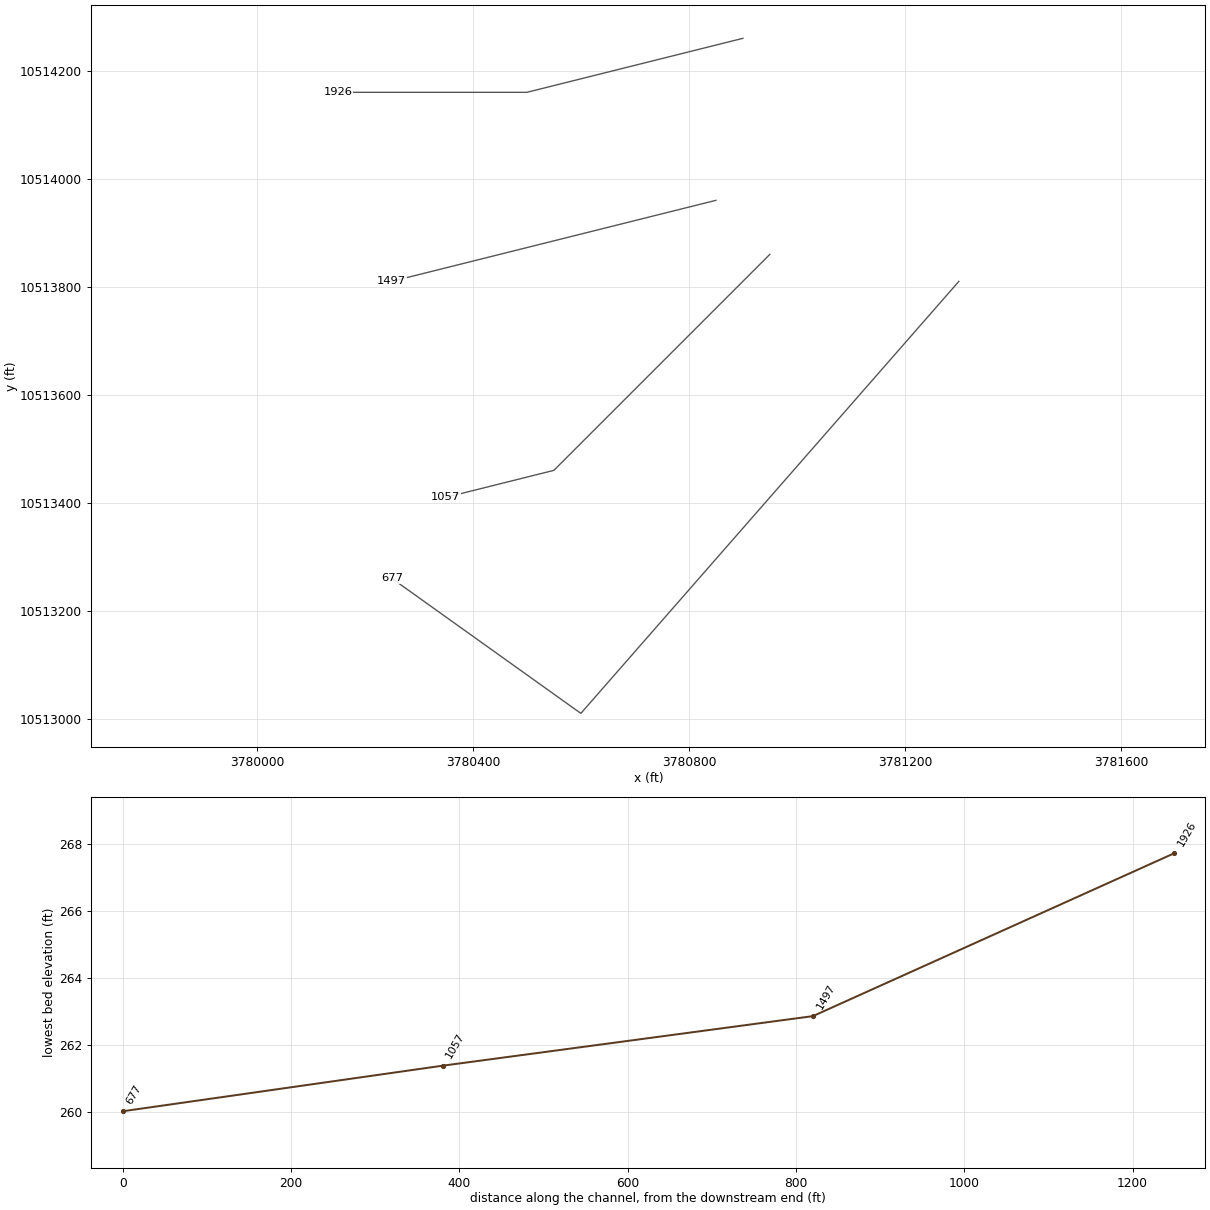
HEC-RAS study UNT143 IN BECR.prj: UNT143 IN BECR Base Level Engineering

--- UNT143 IN BECR.g01 (geometry) --- (continued)

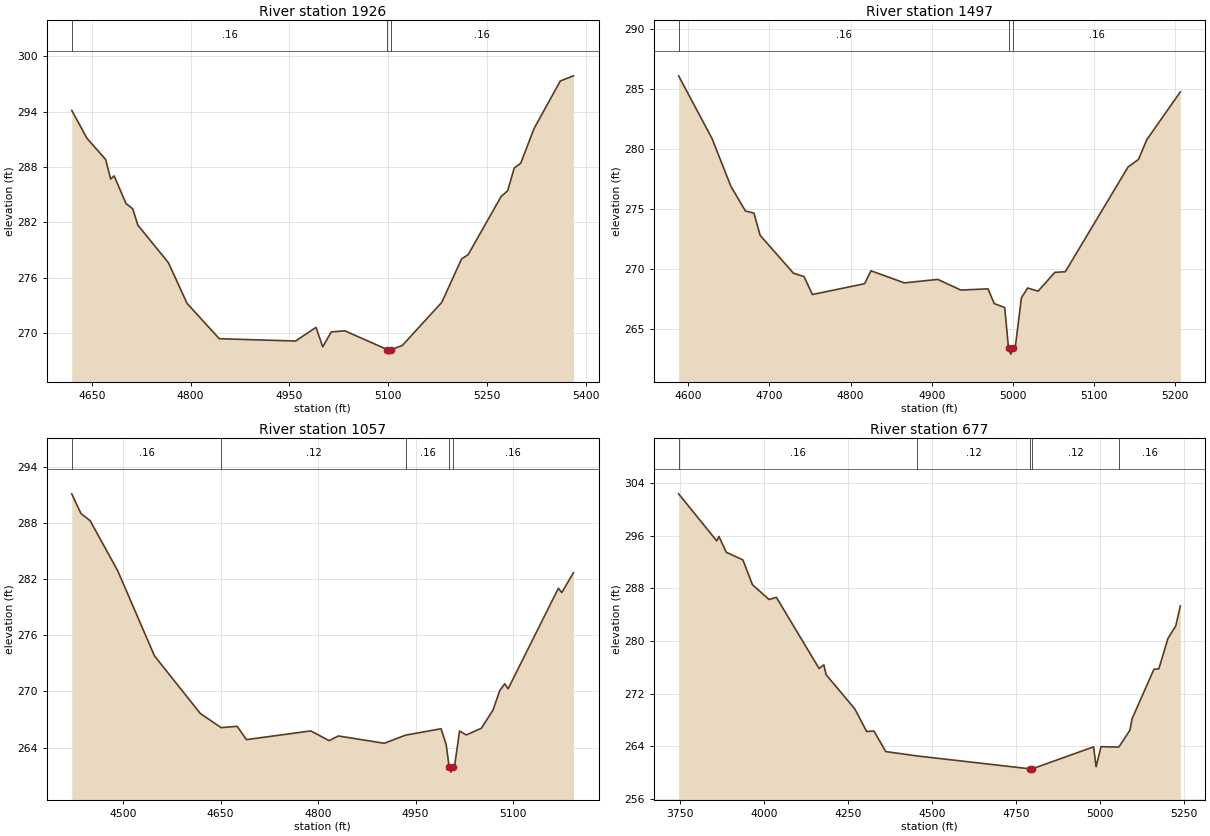
Type RM Length L Ch R = 1,1926,429,429,429
BEGIN DESCRIPTION:
UNT143 IN BECR 4.0
END DESCRIPTION:
XS GIS Cut Line= 3
      3780899.59     10514260.18      3780499.61     10514160.19
      3780149.60     10514160.19
#Sta/Elev= 30
  4619.3  294.15  4642.5  291.12  4670.8  288.83  4678.5  286.71  4683.7  287.05
  4701.7  284.06  4712.0  283.48  4719.8  281.71  4766.2  277.64  4794.5  273.23
  4843.5  269.40  4959.4  269.15  4990.4  270.63  5000.7  268.52  5013.5  270.13
  5034.1  270.26  5098.6  268.23  5101.3  267.73  5104.6  268.23  5121.6  268.67
  5181.6  273.35  5211.6  278.05  5221.6  278.51  5271.6  284.81  5281.6  285.44
  5291.6  287.90  5301.6  288.44  5321.6  292.17  5361.6  297.34  5381.6  297.90
#Mann=3,-1,0
  4619.3    0.16       0  5098.6    0.07       0  5104.6    0.16       0
Bank Sta=5098.6,5104.6
Exp/Cntr=0.3,0.1

Type RM Length L Ch R = 1,1497,440,440,440
BEGIN DESCRIPTION:
UNT143 IN BECR 3.0
END DESCRIPTION:
XS GIS Cut Line= 3
      3780849.60     10513960.19      3780449.61     10513860.19
      3780249.56     10513810.18
#Sta/Elev= 30
  4588.1  286.11  4629.3  280.87  4652.5  276.89  4670.5  274.82  4680.9  274.65
  4688.6  272.79  4729.8  269.62  4742.7  269.35  4753.0  267.85  4817.4  268.75
  4825.2  269.83  4866.4  268.82  4907.6  269.11  4936.0  268.22  4969.5  268.32
  4977.2  267.09  4990.1  266.76  4994.8  263.37  4997.6  262.87  5000.8  263.37
  5003.0  263.37  5010.7  267.58  5018.4  268.39  5031.3  268.13  5051.9  269.70
  5064.8  269.75  5142.1  278.49  5155.0  279.13  5165.3  280.78  5206.6  284.77
#Mann=3,-1,0
  4588.1    0.16       0  4994.8    0.07       0  5000.8    0.16       0
Bank Sta=4994.8,5000.8
Exp/Cntr=0.3,0.1

Type RM Length L Ch R = 1,1057,380,380,380
BEGIN DESCRIPTION:
UNT143 IN BECR 2.0
END DESCRIPTION:
XS GIS Cut Line= 3
      3780949.58     10513860.16      3780549.61     10513460.19
      3780349.61     10513410.19
#Sta/Elev= 30
  4421.1  291.10  4435.2  289.00  4449.3  288.24  4491.8  282.89  4548.3  273.81
  4619.0  267.64  4651.0  266.14  4675.6  266.28  4689.8  264.86  4788.8  265.79
  4817.0  264.75  4831.2  265.25  4901.9  264.47  4934.7  265.34  4989.3  266.02
  4997.1  264.34  5001.8  261.89  5004.5  261.39  5007.8  261.89  5009.9  261.98
  5017.7  265.78  5028.0  265.36  5051.2  266.07  5069.2  268.02  5079.5  270.10
  5087.2  270.82  5092.4  270.29  5169.7  281.02  5174.9  280.56  5192.9  282.68
#Mann=5,-1,0
  4421.1    0.16       0  4651.0    0.12       0  4934.7    0.16       0
  5001.8    0.07       0  5007.8    0.16       0
Bank Sta=5001.8,5007.8
Exp/Cntr=0.3,0.1

Type RM Length L Ch R = 1,677,0,0,0
BEGIN DESCRIPTION:
UNT143 IN BECR 1.0
END DESCRIPTION:
XS GIS Cut Line= 3
      3781299.58     10513810.16      3780599.61     10513010.19
      3780249.60     10513260.19
#Sta/Elev= 30
  3746.4  302.40  3859.8  295.24  3866.4  295.91  3888.3  293.50  3937.6  292.35
  3966.1  288.57  4015.4  286.31  4037.3  286.64  4164.4  275.81  4178.7  276.36
  4185.3  274.86  4270.7  269.66  4305.9  266.22  4327.7  266.29  4362.8  263.16
  4455.1  262.50  4792.6  260.53  4795.4  260.03  4798.6  260.53  4981.4  263.88
  4988.8  260.85  5003.5  263.90  5056.7  263.85  5089.6  266.42  5095.7  268.13
  5160.8  275.68  5175.6  275.77  5202.6  280.38  5226.0  282.30  5239.5  285.33
#Mann=5,-1,0
  3746.4    0.16       0  4455.1    0.12       0  4792.6    0.07       0
  4798.6    0.12       0  5056.7    0.16       0
Bank Sta=4792.6,4798.6
Exp/Cntr=0.3,0.1

Chan Stop Cuts=-1