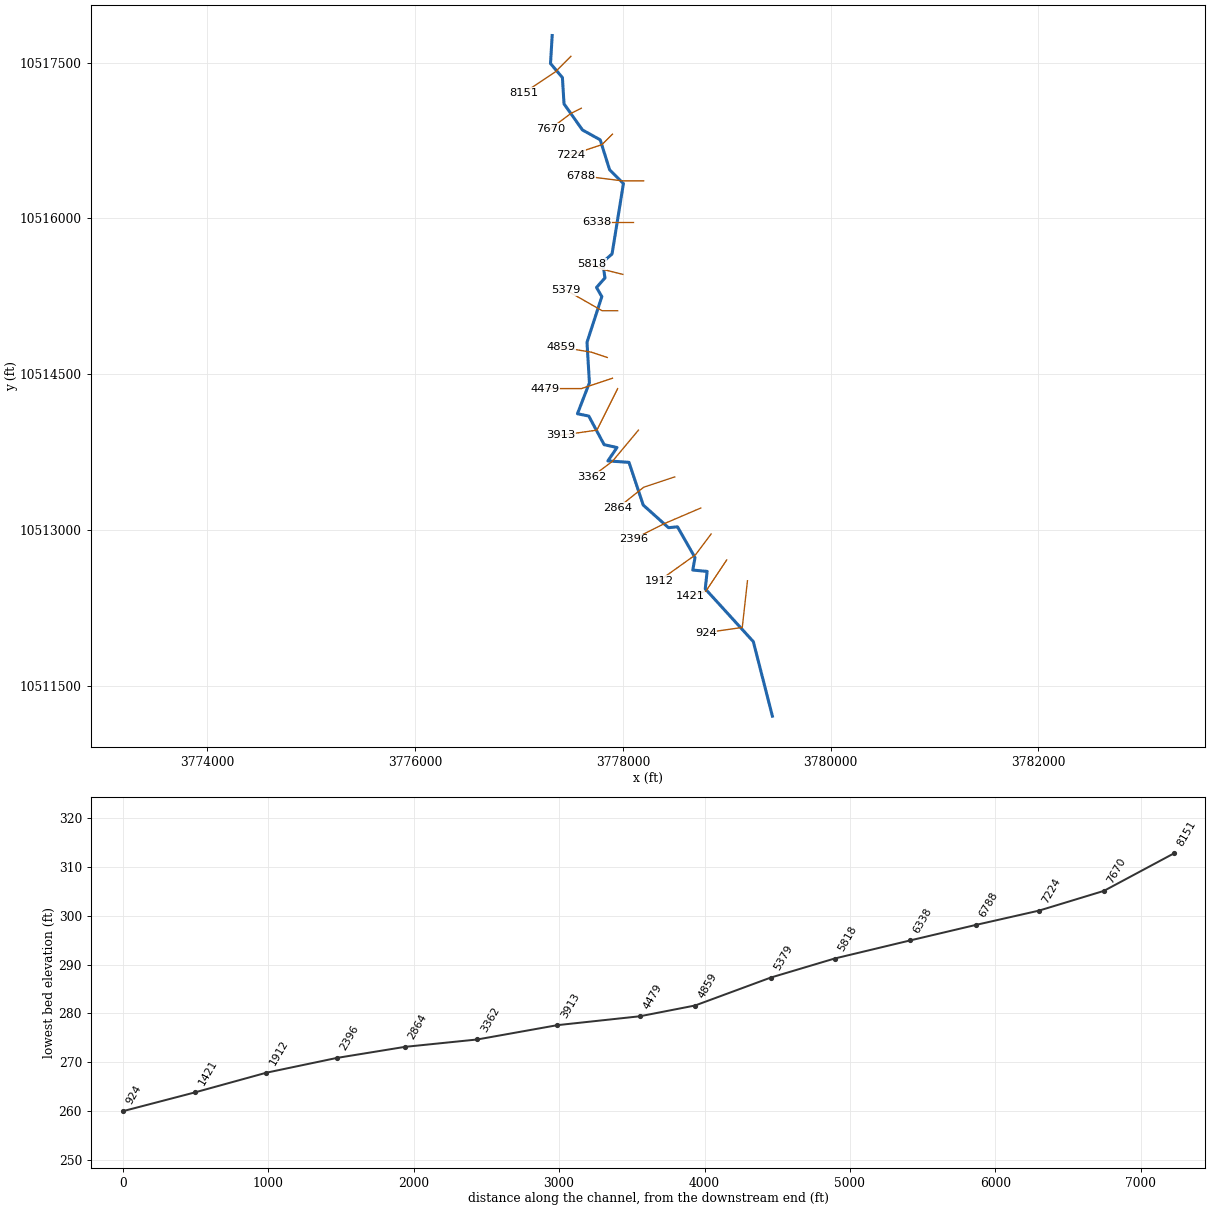
--- UNT144 IN BECR.prj (project) ---

Proj Title=UNT144 IN BECR Base Level Engineering
Current Plan=p01
Default Exp/Contr=0.3,0.1
English Units
Geom File=g01
Flow File=f01
Plan File=p01
BEGIN DESCRIPTION:
UNT144 IN BECR
END DESCRIPTION:

--- UNT144 IN BECR.p01 (plan) ---

Plan Title=Multiple Run
Short Identifier=Multiple
Geom File=g01
Flow File=f01
Subcritical Flow
K Sum by GR= 0
Std Step Tol= 0.01
Critical Tol= 0.01
Num of Std Step Trials= 20
Max Error Tol= 0.3
Flow Tol Ratio= 0.001
Split Flow NTrial= 30
Split Flow Tol= 0.02
Split Flow Ratio= 0.02
Log Output Level= 0
Friction Slope Method= 1
Unsteady Friction Slope Method= 2
Unsteady Bridges Friction Slope Method= 1
Parabolic Critical Depth
Global Vel Dist=  1 , 1 , 1
Global Log Level= 0
CheckData=True
Encroach Param= -1, 0, 0, 0
BEGIN DESCRIPTION:
Multiple Run
END DESCRIPTION:

--- UNT144 IN BECR.f01 (steady flow) ---

Flow Title=Multiple
Number of Profiles=7
Profile Names=10-year,25-year,50-year,1pct_min,100-year,1pct_plu,500-year
River Rch & RM= UNT144 IN BECR,Reach-1,8151
     546     733     886     788    1066    1442    1546
River Rch & RM= UNT144 IN BECR,Reach-1,6788
     629     850    1032     921    1246    1684    1820
Boundary for River Rch & Prof#=UNT144 IN BECR,Reach-1,1
Up Type=0
Dn Type=3
Dn Slope=0.005
Boundary for River Rch & Prof#=UNT144 IN BECR,Reach-1,2
Up Type=0
Dn Type=3
Dn Slope=0.005
Boundary for River Rch & Prof#=UNT144 IN BECR,Reach-1,3
Up Type=0
Dn Type=3
Dn Slope=0.005
Boundary for River Rch & Prof#=UNT144 IN BECR,Reach-1,4
Up Type=0
Dn Type=3
Dn Slope=0.005
Boundary for River Rch & Prof#=UNT144 IN BECR,Reach-1,5
Up Type=0
Dn Type=3
Dn Slope=0.005
Boundary for River Rch & Prof#=UNT144 IN BECR,Reach-1,6
Up Type=0
Dn Type=3
Dn Slope=0.005
Boundary for River Rch & Prof#=UNT144 IN BECR,Reach-1,7
Up Type=0
Dn Type=3
Dn Slope=0.005

--- UNT144 IN BECR.g01 (geometry) ---

Geom Title=Existing Conditions

River Reach=UNT144 IN BECR,Reach-1
Reach XY= 30
      3777319.25     10517760.00      3777303.00     10517491.00
      3777417.75     10517355.00      3777433.25     10517102.00
      3777610.50     10516851.00      3777781.50     10516756.00
      3777872.50     10516467.00      3778005.25     10516335.00
      3777895.75     10515657.00      3777805.25     10515577.00
      3777827.25     10515426.00      3777746.25     10515334.00
      3777797.25     10515246.00      3777654.50     10514806.00
      3777677.75     10514416.00      3777562.50     10514118.00
      3777671.50     10514096.00      3777819.75     10513820.00
      3777943.50     10513793.00      3777855.75     10513664.00
      3778058.75     10513650.00      3778195.75     10513239.00
      3778439.00     10513021.00      3778526.00     10513029.00
      3778694.50     10512733.00      3778673.00     10512613.00
      3778811.25     10512600.00      3778793.25     10512432.00
      3779256.00     10511924.00      3779439.75     10511206.00

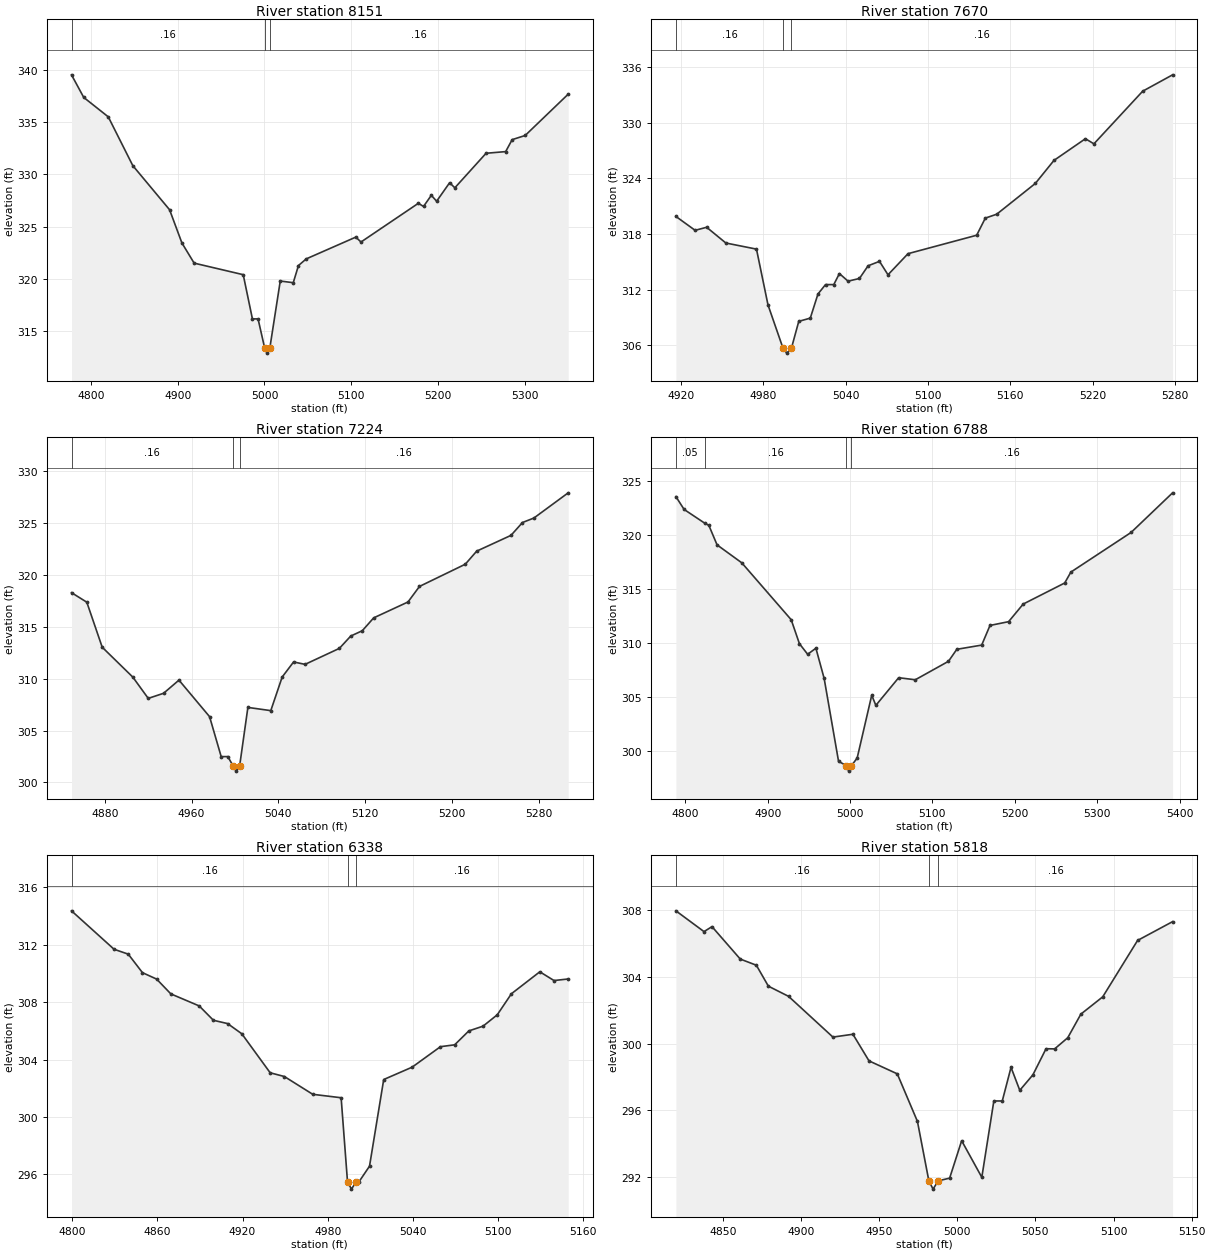
Type RM Length L Ch R = 1,8151,481,481,481
BEGIN DESCRIPTION:
UNT144 IN BECR 16.0
END DESCRIPTION:
XS GIS Cut Line= 3
      3777499.61     10517560.19      3777349.61     10517410.19
      3777049.60     10517210.18
#Sta/Elev= 30
  4777.5  339.58  4791.6  337.41  4819.9  335.54  4848.2  330.85  4890.6  326.61
  4904.8  323.42  4918.9  321.48  4975.5  320.37  4986.1  316.12  4992.6  316.12
  5000.2  313.33  5002.9  312.83  5006.2  313.33  5018.2  319.76  5033.2  319.60
  5039.2  321.25  5048.2  321.89  5105.3  323.98  5111.3  323.51  5177.4  327.23
  5183.4  326.93  5192.4  328.00  5198.5  327.43  5213.5  329.21  5219.5  328.72
  5255.5  332.04  5278.1  332.20  5285.6  333.35  5300.6  333.75  5350.2  337.72
#Mann=3,-1,0
  4777.5    0.16       0  5000.2    0.07       0  5006.2    0.16       0
Bank Sta=5000.2,5006.2
Exp/Cntr=0.3,0.1

Type RM Length L Ch R = 1,7670,446,446,446
BEGIN DESCRIPTION:
UNT144 IN BECR 15.0
END DESCRIPTION:
XS GIS Cut Line= 3
      3777599.64     10517060.20      3777499.61     10517010.19
      3777299.64     10516860.21
#Sta/Elev= 30
  4916.4  319.90  4930.4  318.40  4938.8  318.73  4952.8  317.03  4975.1  316.37
  4983.5  310.34  4994.5  305.64  4997.2  305.14  5000.5  305.64  5005.9  308.57
  5014.3  308.92  5019.9  311.53  5025.4  312.54  5031.4  312.54  5035.5  313.73
  5041.8  312.91  5050.1  313.20  5056.4  314.57  5064.7  315.05  5070.9  313.60
  5085.5  315.88  5135.5  317.87  5141.8  319.72  5150.1  320.14  5178.2  323.46
  5191.8  325.95  5214.7  328.29  5220.9  327.74  5256.4  333.42  5278.2  335.19
#Mann=3,-1,0
  4916.4    0.16       0  4994.5    0.07       0  5000.5    0.16       0
Bank Sta=4994.5,5000.5
Exp/Cntr=0.3,0.1

Type RM Length L Ch R = 1,7224,436,436,436
BEGIN DESCRIPTION:
UNT144 IN BECR 14.0
END DESCRIPTION:
XS GIS Cut Line= 3
      3777899.59     10516810.17      3777799.61     10516710.19
      3777499.63     10516610.19
#Sta/Elev= 30
  4849.4  318.29  4863.5  317.37  4877.7  313.03  4905.9  310.15  4920.1  308.10
  4934.2  308.59  4948.4  309.86  4976.6  306.34  4987.3  302.49  4993.4  302.49
  4998.3  301.59  5001.1  301.09  5004.3  301.59  5011.9  307.23  5033.0  306.92
  5043.5  310.16  5054.0  311.61  5064.6  311.38  5096.2  312.92  5106.7  314.11
  5117.3  314.62  5127.8  315.86  5159.4  317.39  5170.0  318.89  5212.2  321.03
  5222.7  322.29  5254.3  323.81  5264.9  325.05  5275.4  325.48  5307.0  327.91
#Mann=3,-1,0
  4849.4    0.16       0  4998.3    0.07       0  5004.3    0.16       0
Bank Sta=4998.3,5004.3
Exp/Cntr=0.3,0.1

Type RM Length L Ch R = 1,6788,450,450,450
BEGIN DESCRIPTION:
UNT144 IN BECR 13.0
END DESCRIPTION:
XS GIS Cut Line= 3
      3778199.58     10516360.19      3777999.61     10516360.19
      3777599.60     10516410.19
#Sta/Elev= 30
  4788.5  323.56  4798.5  322.37  4823.3  321.11  4828.5  320.90  4838.5  319.09
  4868.5  317.43  4928.5  312.16  4938.5  309.94  4948.5  308.96  4958.5  309.52
  4968.5  306.73  4986.0  299.05  4995.6  298.64  4998.3  298.14  5001.6  298.64
  5008.6  299.35  5026.3  305.17  5031.3  304.23  5059.0  306.79  5079.2  306.60
  5119.5  308.31  5129.6  309.42  5159.8  309.81  5169.9  311.63  5192.5  311.98
  5210.2  313.61  5260.6  315.56  5268.1  316.57  5341.2  320.24  5391.6  323.91
#Mann=4,-1,0
  4788.5    0.05       0  4823.3    0.16       0  4995.6    0.07       0
  5001.6    0.16       0
Bank Sta=4995.6,5001.6
Exp/Cntr=0.3,0.1

Type RM Length L Ch R = 1,6338,520,520,520
BEGIN DESCRIPTION:
UNT144 IN BECR 12.0
END DESCRIPTION:
XS GIS Cut Line= 3
      3778099.62     10515960.19      3777899.61     10515960.19
      3777749.62     10515960.19
#Sta/Elev= 30
  4799.5  314.37  4829.5  311.69  4839.5  311.35  4849.5  310.06  4859.5  309.61
  4869.5  308.58  4889.5  307.74  4899.5  306.74  4909.5  306.51  4919.5  305.80
  4939.5  303.08  4949.5  302.82  4969.5  301.58  4989.5  301.34  4994.0  295.47
  4996.8  294.97  5000.0  295.47  5002.0  295.47  5009.5  296.57  5019.5  302.61
  5039.5  303.47  5059.5  304.90  5069.5  305.03  5079.5  306.00  5089.5  306.33
  5099.5  307.12  5109.5  308.59  5129.5  310.12  5139.5  309.51  5149.5  309.62
#Mann=3,-1,0
  4799.5    0.16       0  4994.0    0.07       0  5000.0    0.16       0
Bank Sta=4994,5000
Exp/Cntr=0.3,0.1

Type RM Length L Ch R = 1,5818,439,439,439
BEGIN DESCRIPTION:
UNT144 IN BECR 11.0
END DESCRIPTION:
XS GIS Cut Line= 3
      3777999.56     10515460.20      3777799.61     10515510.19
      3777699.62     10515560.18
#Sta/Elev= 30
  4819.9  307.98  4837.9  306.73  4843.0  307.03  4861.1  305.08  4871.4  304.71
  4879.1  303.45  4892.0  302.84  4920.4  300.39  4933.2  300.56  4943.5  298.96
  4961.6  298.18  4974.5  295.32  4981.8  291.75  4984.5  291.25  4987.8  291.75
  4995.1  291.91  5002.8  294.16  5015.7  291.96  5023.4  296.55  5028.8  296.55
  5034.4  298.57  5040.0  297.19  5048.4  298.12  5056.8  299.69  5062.3  299.68
  5070.7  300.35  5079.1  301.77  5093.1  302.81  5115.4  306.20  5137.8  307.33
#Mann=3,-1,0
  4819.9    0.16       0  4981.8    0.07       0  4987.8    0.16       0
Bank Sta=4981.8,4987.8
Exp/Cntr=0.3,0.1

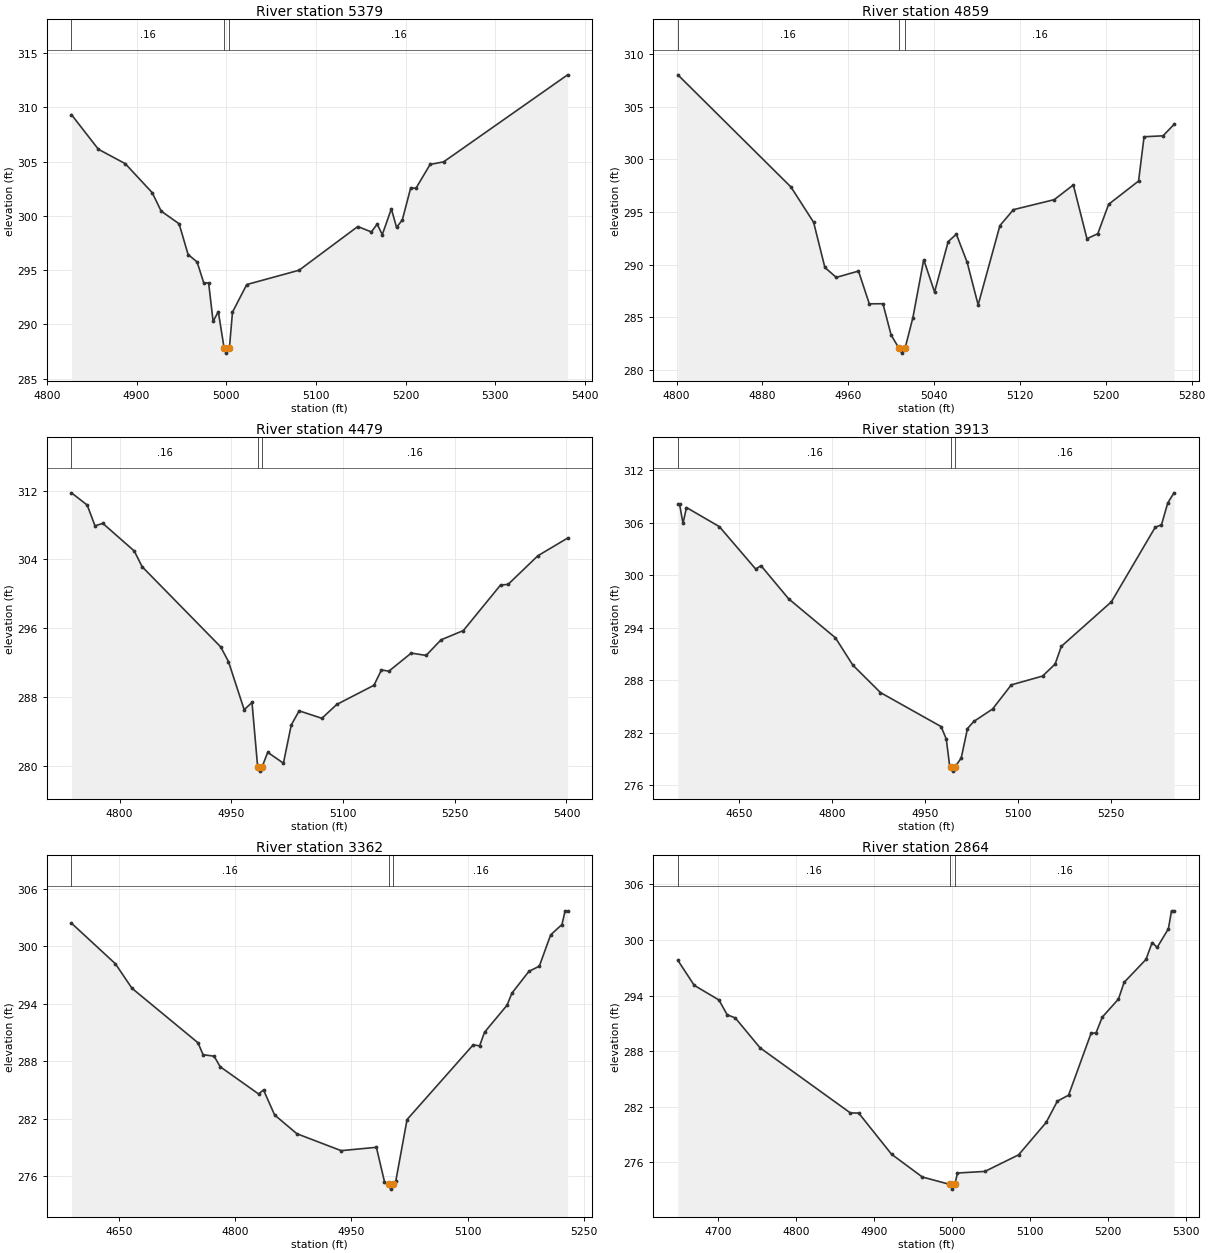
Type RM Length L Ch R = 1,5379,520,520,520
BEGIN DESCRIPTION:
UNT144 IN BECR 10.0
END DESCRIPTION:
XS GIS Cut Line= 3
      3777949.62     10515110.19      3777799.61     10515110.19
      3777449.63     10515310.17
#Sta/Elev= 30
  4827.4  309.32  4857.4  306.13  4887.4  304.80  4917.4  302.13  4927.4  300.43
  4947.4  299.26  4957.4  296.43  4967.4  295.75  4974.9  293.81  4980.3  293.81
  4985.3  290.27  4991.1  291.16  4997.5  287.84  5000.2  287.34  5003.5  287.84
  5006.9  291.12  5022.8  293.66  5081.1  294.98  5146.6  299.01  5161.7  298.51
  5168.2  299.23  5173.9  298.26  5184.0  300.64  5189.8  298.93  5196.2  299.61
  5205.6  302.58  5211.4  302.53  5227.2  304.73  5242.3  304.97  5380.5  312.99
#Mann=3,-1,0
  4827.4    0.16       0  4997.5    0.07       0  5003.5    0.16       0
Bank Sta=4997.5,5003.5
Exp/Cntr=0.3,0.1

Type RM Length L Ch R = 1,4859,380,380,380
BEGIN DESCRIPTION:
UNT144 IN BECR 9.0
END DESCRIPTION:
XS GIS Cut Line= 3
      3777849.62     10514660.18      3777699.61     10514710.19
      3777399.57     10514760.19
#Sta/Elev= 30
  4801.2  308.03  4906.6  297.38  4927.7  294.03  4938.2  289.74  4948.8  288.80
  4969.5  289.40  4979.6  286.29  4992.3  286.30  4999.9  283.33  5007.0  282.11
  5009.8  281.61  5013.0  282.11  5020.2  284.98  5030.3  290.48  5040.4  287.41
  5053.1  292.20  5060.7  292.90  5070.8  290.22  5081.0  286.19  5101.3  293.72
  5113.9  295.23  5151.9  296.18  5169.7  297.58  5182.4  292.47  5192.5  292.95
  5202.6  295.74  5230.5  297.95  5235.6  302.15  5253.3  302.24  5263.5  303.32
#Mann=3,-1,0
  4801.2    0.16       0  5007.0    0.07       0  5013.0    0.16       0
Bank Sta=5007,5013
Exp/Cntr=0.3,0.1

Type RM Length L Ch R = 1,4479,566,566,566
BEGIN DESCRIPTION:
UNT144 IN BECR 8.0
END DESCRIPTION:
XS GIS Cut Line= 3
      3777899.60     10514460.18      3777599.61     10514360.19
      3777249.62     10514360.19
#Sta/Elev= 30
  4735.3  311.75  4756.4  310.33  4766.9  307.91  4777.4  308.20  4819.6  304.99
  4830.2  303.16  4935.6  293.85  4946.1  292.14  4967.2  286.54  4977.7  287.38
  4985.3  279.90  4988.0  279.40  4991.3  279.90  4998.8  281.59  5019.9  280.32
  5030.4  284.76  5041.0  286.41  5071.5  285.54  5091.5  287.15  5141.5  289.38
  5151.5  291.16  5161.5  291.02  5191.5  293.12  5211.5  292.85  5231.5  294.66
  5261.5  295.74  5311.5  301.04  5321.5  301.10  5361.5  304.43  5401.5  306.49
#Mann=3,-1,0
  4735.3    0.16       0  4985.3    0.07       0  4991.3    0.16       0
Bank Sta=4985.3,4991.3
Exp/Cntr=0.3,0.1

Type RM Length L Ch R = 1,3913,551,551,551
BEGIN DESCRIPTION:
UNT144 IN BECR 7.0
END DESCRIPTION:
XS GIS Cut Line= 3
      3777949.59     10514360.15      3777749.61     10513960.19
      3777399.63     10513910.19
#Sta/Elev= 30
  4551.0  308.15  4553.7  308.15  4559.3  305.93  4564.9  307.75  4618.0  305.56
  4676.7  300.70  4685.1  301.10  4729.8  297.30  4805.3  292.84  4833.3  289.72
  4878.0  286.57  4975.8  282.68  4984.2  281.25  4989.8  278.08  4992.4  278.08
  4995.1  277.58  4998.4  278.08  5008.3  279.08  5018.4  282.45  5028.5  283.26
  5058.8  284.68  5089.1  287.45  5139.6  288.46  5159.8  289.83  5169.9  291.86
  5250.7  296.96  5321.4  305.49  5331.5  305.77  5341.6  308.27  5351.7  309.43
#Mann=3,-1,0
  4551.0    0.16       0  4992.4    0.07       0  4998.4    0.16       0
Bank Sta=4992.4,4998.4
Exp/Cntr=0.3,0.1

Type RM Length L Ch R = 1,3362,498,498,498
BEGIN DESCRIPTION:
UNT144 IN BECR 6.0
END DESCRIPTION:
XS GIS Cut Line= 3
      3778149.63     10513960.22      3777899.61     10513660.19
      3777699.57     10513510.16
#Sta/Elev= 30
  4588.5  302.43  4645.2  298.19  4666.6  295.63  4751.9  289.93  4758.4  288.69
  4772.7  288.53  4780.5  287.43  4830.0  284.59  4836.5  285.00  4850.8  282.39
  4879.5  280.43  4936.7  278.66  4982.2  279.01  4992.6  275.43  4997.9  275.14
  5000.7  274.64  5003.9  275.14  5007.2  275.46  5021.8  281.91  5107.2  289.72
  5115.5  289.61  5121.8  291.03  5150.9  293.86  5157.2  295.12  5179.1  297.39
  5192.6  297.94  5207.2  301.21  5221.8  302.29  5225.9  303.72  5229.1  303.72
#Mann=3,-1,0
  4588.5    0.16       0  4997.9    0.07       0  5003.9    0.16       0
Bank Sta=4997.9,5003.9
Exp/Cntr=0.3,0.1

Type RM Length L Ch R = 1,2864,468,468,468
BEGIN DESCRIPTION:
UNT144 IN BECR 5.0
END DESCRIPTION:
XS GIS Cut Line= 3
      3778499.56     10513510.17      3778199.61     10513410.19
      3777949.64     10513210.21
#Sta/Elev= 30
  4648.1  297.81  4669.1  295.11  4700.8  293.53  4711.3  291.94  4721.8  291.59
  4753.5  288.37  4869.4  281.34  4880.0  281.33  4922.1  276.89  4961.6  274.43
  4997.3  273.62  5000.0  273.12  5003.3  273.62  5006.7  274.86  5041.9  275.03
  5085.1  276.82  5120.4  280.31  5134.8  282.61  5149.2  283.26  5178.0  289.93
  5184.4  289.98  5192.4  291.68  5213.2  293.63  5220.4  295.43  5248.4  297.90
  5256.4  299.73  5262.8  299.20  5277.2  301.21  5281.2  303.15  5284.4  303.15
#Mann=3,-1,0
  4648.1    0.16       0  4997.3    0.07       0  5003.3    0.16       0
Bank Sta=4997.3,5003.3
Exp/Cntr=0.3,0.1

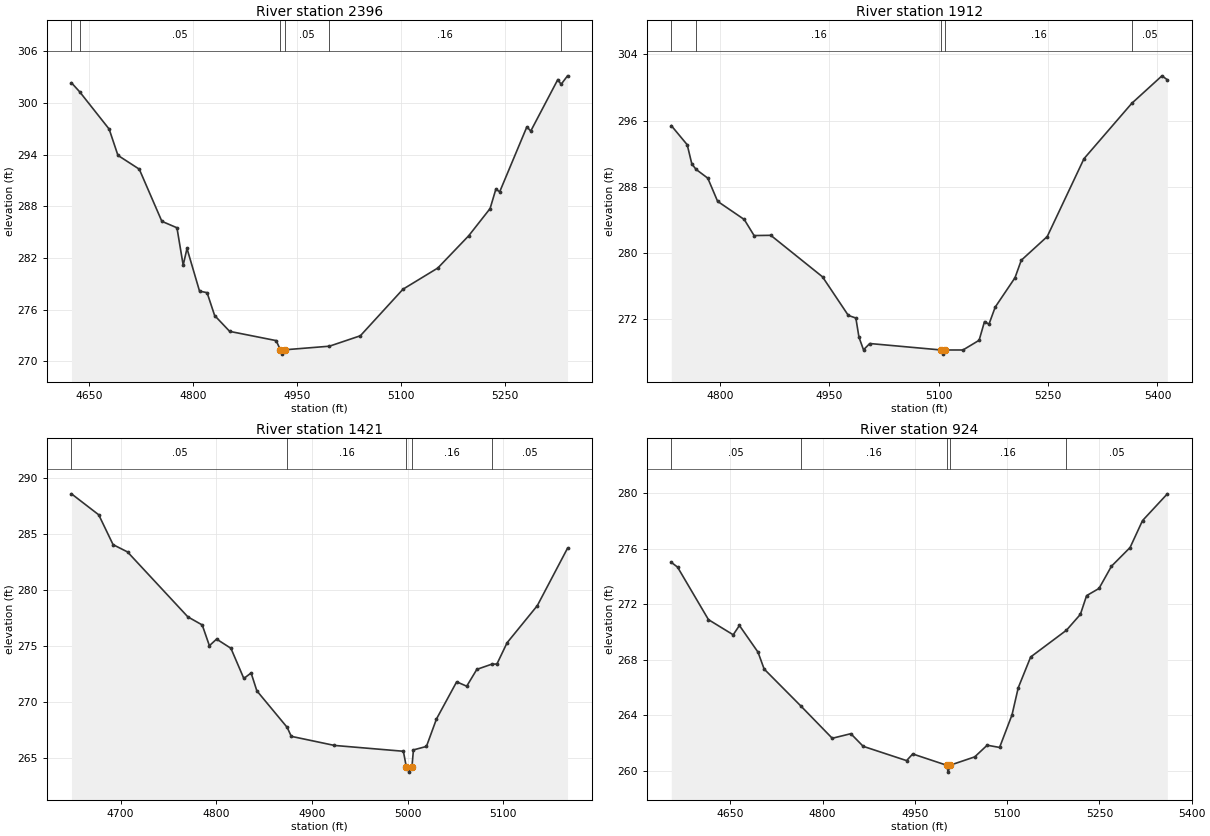
Type RM Length L Ch R = 1,2396,484,484,484
BEGIN DESCRIPTION:
UNT144 IN BECR 4.0
END DESCRIPTION:
XS GIS Cut Line= 3
      3778749.57     10513210.17      3778399.61     10513060.19
      3778099.57     10512910.17
#Sta/Elev= 30
  4624.3  302.33  4636.1  301.29  4678.7  296.96  4691.4  293.91  4722.2  292.31
  4754.8  286.26  4776.6  285.51  4785.6  281.17  4791.1  283.11  4809.2  278.16
  4820.1  277.98  4831.0  275.33  4852.7  273.49  4919.8  272.42  4925.9  271.35
  4928.6  270.85  4931.9  271.35  4996.7  271.77  5041.4  272.98  5102.9  278.38
  5153.2  280.84  5197.9  284.59  5228.7  287.74  5237.0  289.98  5242.6  289.69
  5281.8  297.22  5287.4  296.73  5326.5  302.71  5331.2  302.15  5340.5  303.14
#Mann=6,-1,0
  4624.3    0.16       0  4636.1    0.05       0  4925.9    0.07       0
  4931.9    0.05       0  4996.7    0.16       0  5331.2    0.05       0
Bank Sta=4925.9,4931.9
Exp/Cntr=0.3,0.1

Type RM Length L Ch R = 1,1912,491,491,491
BEGIN DESCRIPTION:
UNT144 IN BECR 3.0
END DESCRIPTION:
XS GIS Cut Line= 3
      3778849.59     10512960.16      3778699.61     10512760.19
      3778349.59     10512510.18
#Sta/Elev= 30
  4733.5  295.40  4755.3  293.09  4761.6  290.79  4767.4  290.12  4783.5  289.06
  4797.0  286.26  4833.5  284.07  4847.0  282.13  4869.9  282.16  4940.8  277.15
  4976.2  272.49  4986.5  272.18  4990.8  269.86  4997.0  268.34  5005.6  269.10
  5103.4  268.32  5106.1  267.82  5109.4  268.32  5133.4  268.32  5155.5  269.49
  5162.9  271.75  5169.0  271.43  5177.6  273.50  5204.7  277.04  5213.3  279.15
  5248.9  282.01  5299.3  291.41  5364.8  298.09  5406.2  301.41  5413.6  300.93
#Mann=5,-1,0
  4733.5    0.05       0  4767.4    0.16       0  5103.4    0.07       0
  5109.4    0.16       0  5364.8    0.05       0
Bank Sta=5103.4,5109.4
Exp/Cntr=0.3,0.1

Type RM Length L Ch R = 1,1421,497,497,497
BEGIN DESCRIPTION:
UNT144 IN BECR 2.0
END DESCRIPTION:
XS GIS Cut Line= 3
      3778999.59     10512710.16      3778799.61     10512410.19
      3778649.64     10512360.20
#Sta/Elev= 30
  4648.6  288.59  4677.1  286.72  4692.1  284.06  4707.2  283.41  4770.3  277.62
  4785.3  276.90  4792.8  275.05  4800.3  275.64  4815.3  274.82  4828.8  272.13
  4836.4  272.62  4842.4  271.03  4874.1  267.77  4878.4  266.97  4923.5  266.16
  4995.6  265.64  4998.6  264.28  5001.4  263.78  5004.6  264.28  5006.1  265.76
  5019.7  266.07  5030.2  268.52  5051.3  271.83  5061.8  271.44  5072.4  272.94
  5087.9  273.40  5093.4  273.42  5104.0  275.31  5135.6  278.62  5167.2  283.74
#Mann=5,-1,0
  4648.6    0.05       0  4874.1    0.16       0  4998.6    0.07       0
  5004.6    0.16       0  5087.9    0.05       0
Bank Sta=4998.6,5004.6
Exp/Cntr=0.3,0.1

Type RM Length L Ch R = 1,924,0,0,0
BEGIN DESCRIPTION:
UNT144 IN BECR 1.0
END DESCRIPTION:
XS GIS Cut Line= 3
      3779199.61     10512510.21      3779149.61     10512060.19
      3778799.65     10512010.19
#Sta/Elev= 30
  4554.2  275.03  4564.3  274.69  4614.6  270.90  4654.8  269.81  4664.9  270.48
  4695.1  268.56  4705.1  267.34  4764.7  264.68  4815.8  262.35  4846.0  262.68
  4866.1  261.77  4936.6  260.74  4946.6  261.22  5001.5  260.41  5004.2  259.91
  5007.5  260.41  5047.4  261.01  5067.6  261.85  5087.8  261.69  5108.0  264.04
  5118.1  265.99  5138.3  268.21  5196.5  270.14  5219.1  271.28  5229.2  272.63
  5249.4  273.15  5269.6  274.75  5299.9  276.10  5320.1  278.04  5360.5  279.97
#Mann=5,-1,0
  4554.2    0.05       0  4764.7    0.16       0  5001.5    0.07       0
  5007.5    0.16       0  5196.5    0.05       0
Bank Sta=5001.5,5007.5
Exp/Cntr=0.3,0.1

Chan Stop Cuts=-1