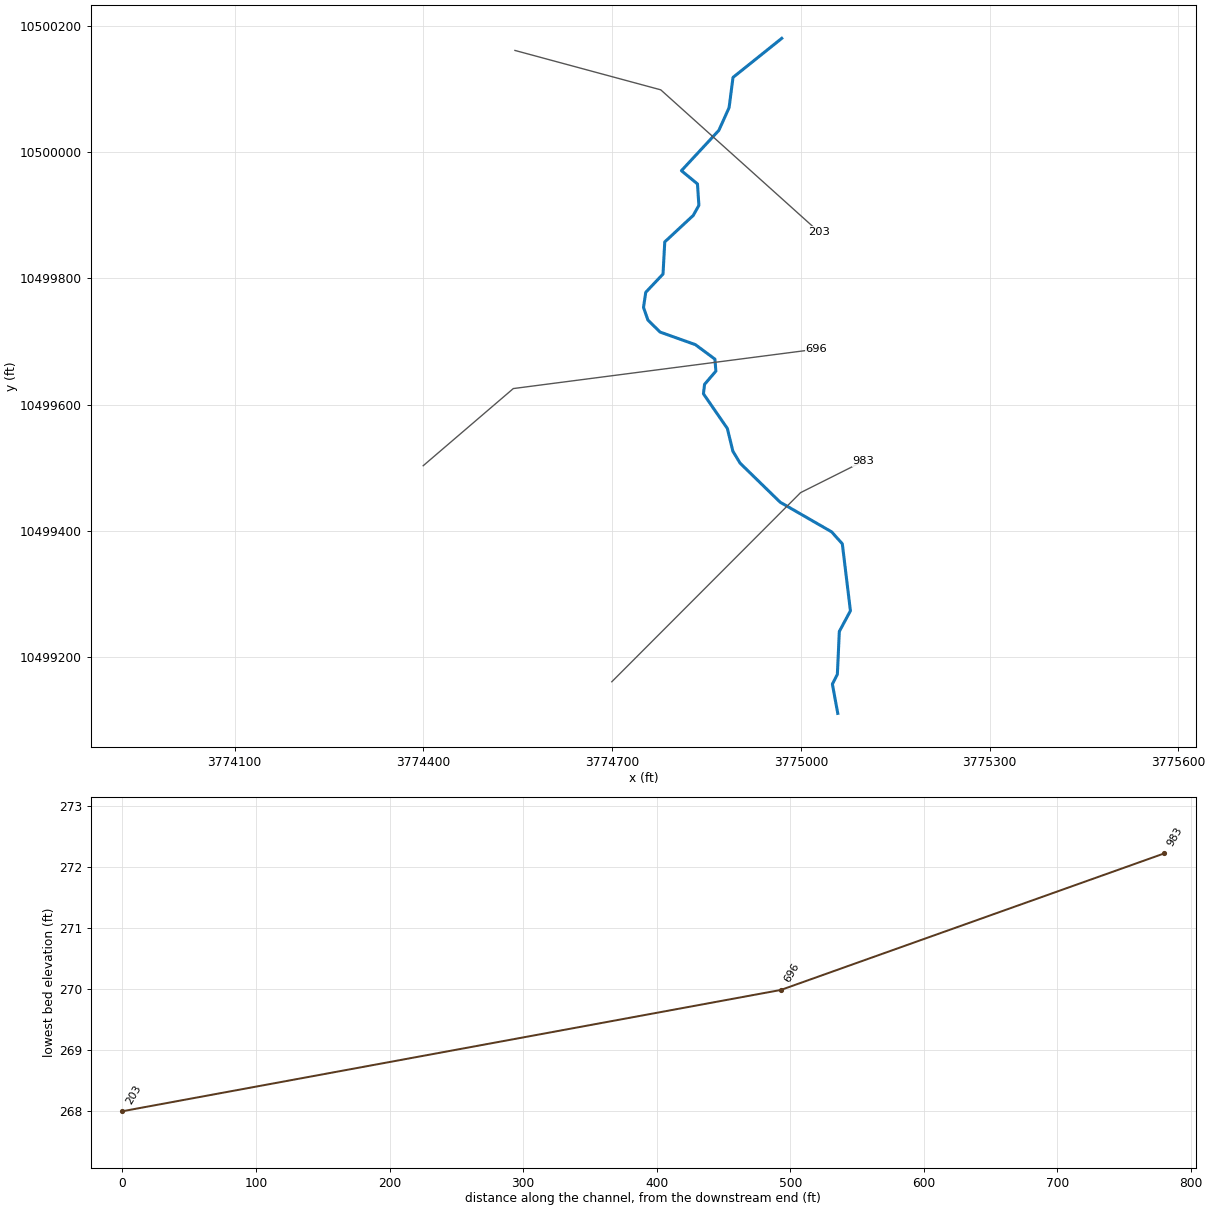
--- UNT147 IN BECR.prj (project) ---

Proj Title=UNT147 IN BECR Base Level Engineering
Current Plan=p01
Default Exp/Contr=0.3,0.1
English Units
Geom File=g01
Flow File=f01
Plan File=p01
BEGIN DESCRIPTION:
UNT147 IN BECR
END DESCRIPTION:

--- UNT147 IN BECR.p01 (plan) ---

Plan Title=Multiple Run
Short Identifier=Multiple
Geom File=g01
Flow File=f01
Subcritical Flow
K Sum by GR= 0
Std Step Tol= 0.01
Critical Tol= 0.01
Num of Std Step Trials= 20
Max Error Tol= 0.3
Flow Tol Ratio= 0.001
Split Flow NTrial= 30
Split Flow Tol= 0.02
Split Flow Ratio= 0.02
Log Output Level= 0
Friction Slope Method= 1
Unsteady Friction Slope Method= 2
Unsteady Bridges Friction Slope Method= 1
Parabolic Critical Depth
Global Vel Dist=  1 , 1 , 1
Global Log Level= 0
CheckData=True
Encroach Param= -1, 0, 0, 0
BEGIN DESCRIPTION:
Multiple Run
END DESCRIPTION:

--- UNT147 IN BECR.f01 (steady flow) ---

Flow Title=Multiple
Number of Profiles=7
Profile Names=10-year,25-year,50-year,1pct_min,100-year,1pct_plu,500-year
River Rch & RM= UNT147 IN BECR,Reach-1,983
     325     425     505     443     599     810     844
Boundary for River Rch & Prof#=UNT147 IN BECR,Reach-1,1
Up Type=0
Dn Type=3
Dn Slope=0.005
Boundary for River Rch & Prof#=UNT147 IN BECR,Reach-1,2
Up Type=0
Dn Type=3
Dn Slope=0.005
Boundary for River Rch & Prof#=UNT147 IN BECR,Reach-1,3
Up Type=0
Dn Type=3
Dn Slope=0.005
Boundary for River Rch & Prof#=UNT147 IN BECR,Reach-1,4
Up Type=0
Dn Type=3
Dn Slope=0.005
Boundary for River Rch & Prof#=UNT147 IN BECR,Reach-1,5
Up Type=0
Dn Type=3
Dn Slope=0.005
Boundary for River Rch & Prof#=UNT147 IN BECR,Reach-1,6
Up Type=0
Dn Type=3
Dn Slope=0.005
Boundary for River Rch & Prof#=UNT147 IN BECR,Reach-1,7
Up Type=0
Dn Type=3
Dn Slope=0.005

--- UNT147 IN BECR.g01 (geometry) ---

Geom Title=Existing Conditions

River Reach=UNT147 IN BECR,Reach-1
Reach XY= 30
      3775058.75     10499110.00      3775050.21     10499156.45
      3775058.12     10499171.91      3775061.25     10499240.00
      3775078.87     10499272.71      3775066.00     10499379.00
      3775049.00     10499398.00      3774967.25     10499445.00
      3774903.50     10499507.00      3774892.00     10499526.00
      3774883.25     10499562.00      3774845.25     10499617.00
      3774847.00     10499632.00      3774865.00     10499653.00
      3774863.50     10499672.00      3774832.50     10499695.00
      3774776.25     10499715.00      3774757.00     10499734.00
      3774750.00     10499754.00      3774753.50     10499778.00
      3774781.00     10499807.00      3774783.75     10499858.00
      3774829.00     10499900.00      3774838.00     10499916.00
      3774835.75     10499950.00      3774810.25     10499971.00
      3774869.75     10500035.00      3774886.00     10500071.00
      3774892.25     10500119.00      3774969.75     10500181.00

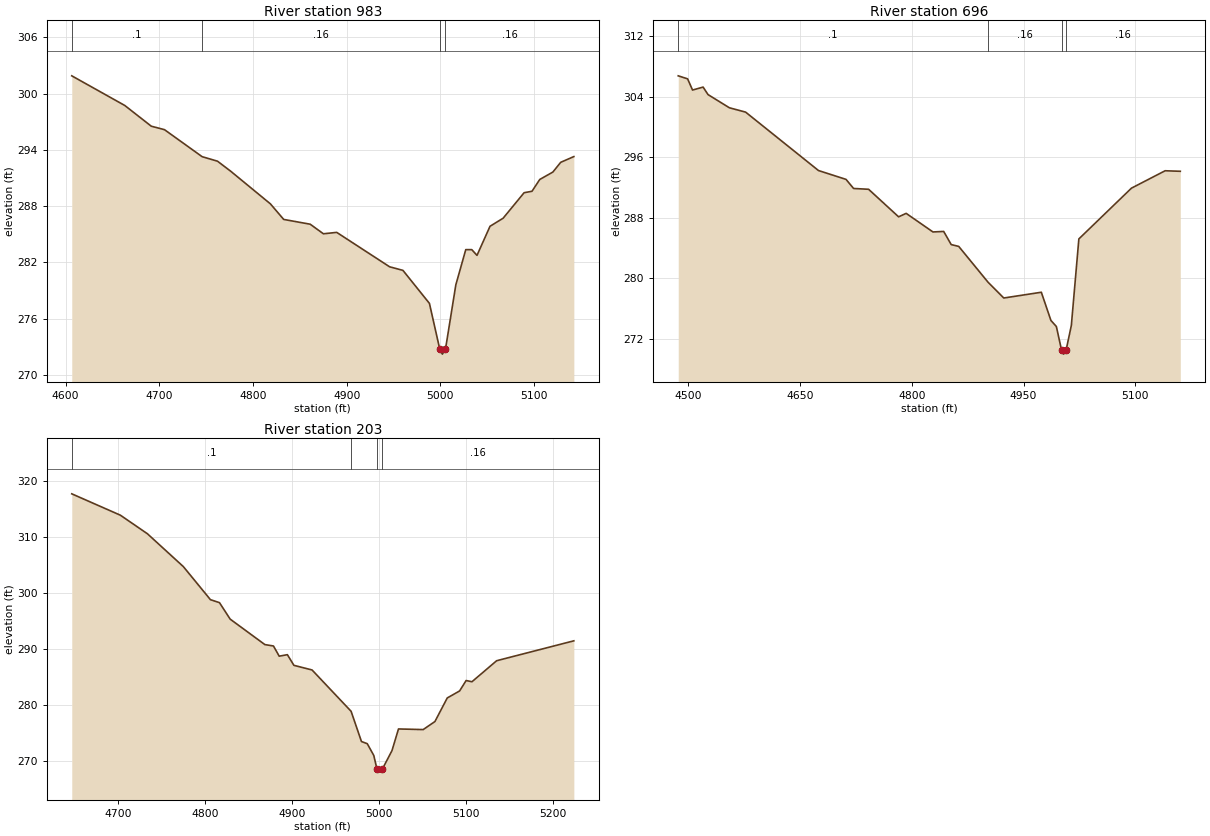
Type RM Length L Ch R = 1,983,287,287,287
BEGIN DESCRIPTION:
UNT147 IN BECR 2.0
END DESCRIPTION:
XS GIS Cut Line= 3
      3774699.60     10499160.18      3774999.61     10499460.19
      3775099.62     10499510.20
#Sta/Elev= 30
  4606.5  301.90  4663.1  298.74  4691.4  296.53  4705.5  296.16  4745.7  293.28
  4762.1  292.80  4776.2  291.73  4818.6  288.25  4832.8  286.59  4861.1  286.08
  4875.2  285.06  4889.4  285.21  4945.9  281.54  4960.1  281.16  4988.4  277.64
  4999.5  272.73  5002.2  272.23  5005.5  272.73  5016.6  279.62  5027.2  283.37
  5033.6  283.37  5039.2  282.76  5053.1  285.86  5067.1  286.72  5089.5  289.44
  5097.9  289.59  5106.2  290.85  5120.2  291.64  5128.6  292.68  5142.6  293.29
#Mann=4,-1,0
  4606.5     0.1       0  4745.7    0.16       0  4999.5    0.07       0
  5005.5    0.16       0
Bank Sta=4999.5,5005.5
Exp/Cntr=0.3,0.1

Type RM Length L Ch R = 1,696,493,493,493
BEGIN DESCRIPTION:
Mapping XS 73bd5b17
END DESCRIPTION:
XS GIS Cut Line= 3
      3774399.78     10499502.94      3774543.01     10499625.34
      3775024.67     10499687.83
#Sta/Elev= 30
  4486.4  306.78  4499.0  306.38  4505.6  304.90  4519.8  305.29  4526.4  304.30
  4555.0  302.56  4576.9  301.98  4674.7  294.26  4711.7  293.09  4721.8  291.89
  4742.0  291.78  4782.3  288.14  4792.4  288.60  4828.4  286.14  4842.8  286.21
  4852.9  284.47  4863.0  284.23  4902.5  279.48  4923.5  277.41  4973.9  278.17
  4986.8  274.44  4994.1  273.64  5001.1  270.49  5003.9  269.99  5007.1  270.49
  5014.2  273.78  5024.3  285.22  5094.9  291.93  5140.1  294.23  5160.5  294.16
#Mann=4,-1,0
  4486.4     0.1       0  4902.5    0.16       0  5001.1    0.07       0
  5007.1    0.16       0
Bank Sta=5001.1,5007.1
Exp/Cntr=0.3,0.1

Type RM Length L Ch R = 1,203,0,0,0
BEGIN DESCRIPTION:
UNT147 IN BECR 1.0
END DESCRIPTION:
XS GIS Cut Line= 3
      3774545.61     10500161.80      3774777.39     10500099.30
      3775028.59     10499873.99
#Sta/Elev= 30
  4646.7  317.64  4702.6  313.83  4733.7  310.52  4775.1  304.65  4806.2  298.76
  4816.6  298.23  4828.9  295.29  4868.8  290.75  4878.7  290.50  4885.3  288.68
  4894.7  288.95  4902.2  287.05  4923.1  286.22  4968.0  278.85  4979.9  273.46
  4986.6  273.07  4994.1  270.97  4997.8  268.50  5000.6  268.00  5003.8  268.50
  5015.0  271.83  5022.5  275.70  5050.9  275.59  5064.4  277.02  5078.6  281.23
  5092.8  282.48  5100.3  284.34  5107.0  284.12  5135.4  287.87  5224.2  291.42
#Mann=4,-1,0
  4646.7     0.1       0  4968.0    0.16       0  4997.8    0.07       0
  5003.8    0.16       0
Bank Sta=4997.8,5003.8
Exp/Cntr=0.3,0.1

Chan Stop Cuts=-1