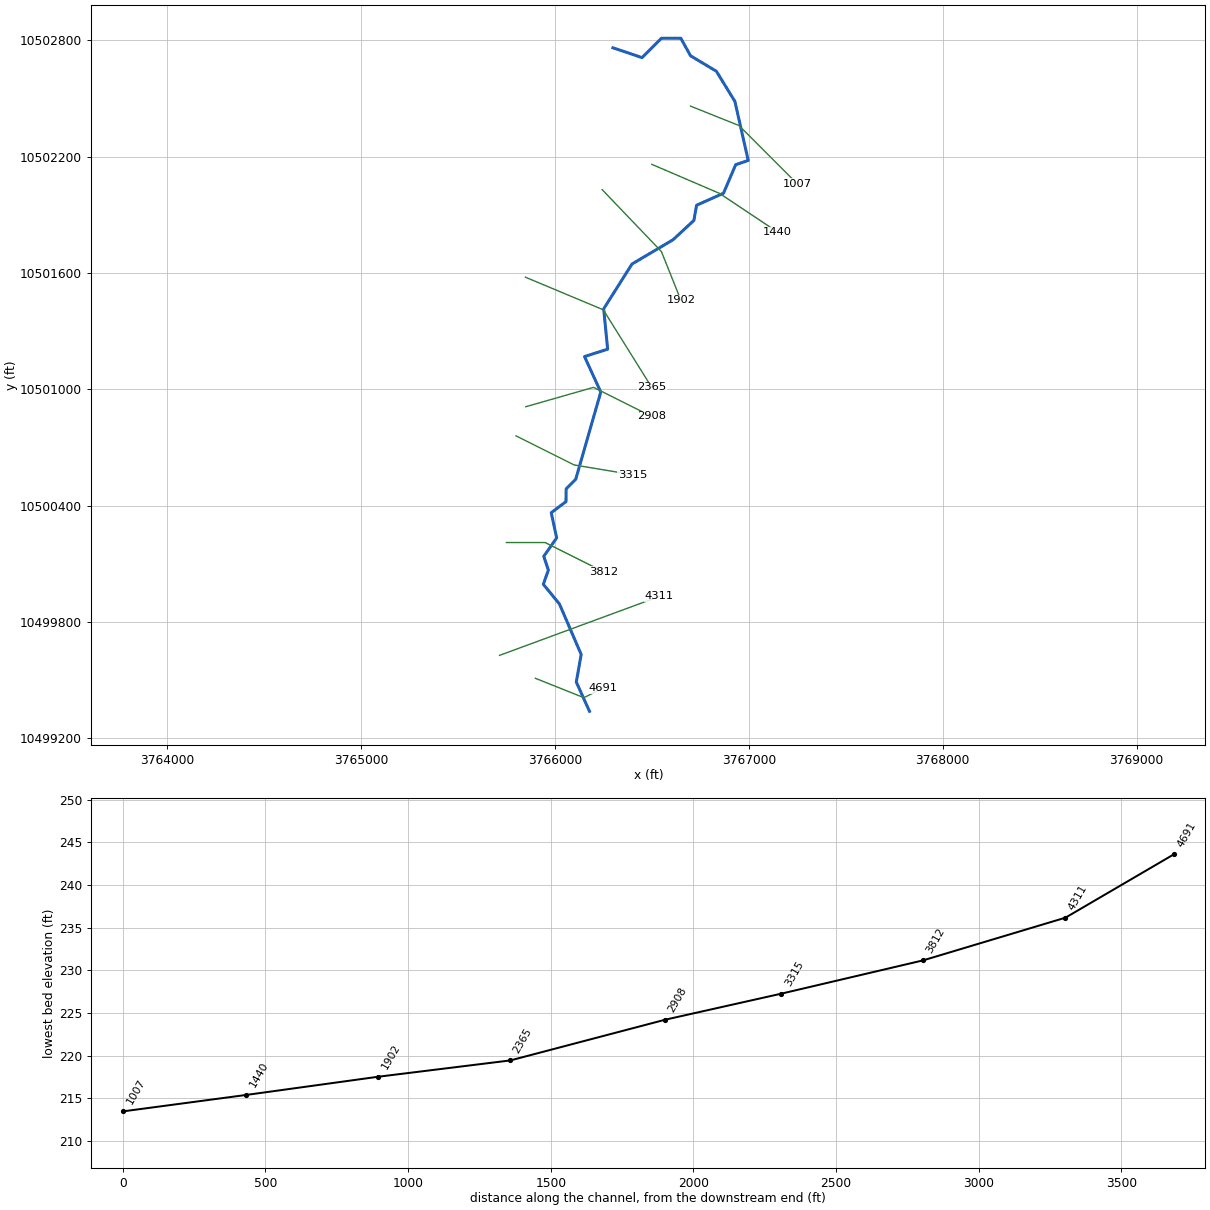
--- UNT149 IN BECR.prj (project) ---

Proj Title=UNT149 IN BECR Base Level Engineering
Current Plan=p01
Default Exp/Contr=0.3,0.1
English Units
Geom File=g01
Flow File=f01
Plan File=p01
Y Axis Title=Elevation
X Axis Title(PF)=Main Channel Distance
X Axis Title(XS)=Station
BEGIN DESCRIPTION:
UNT149 IN BECR
END DESCRIPTION:
DSS Export Rating Curves= 0
DSS Export Rating Curve Sorted= 0
DSS Export Volume Flow Curves= 0
DXF OffsetX= 0
DXF OffsetY= 0
DXF ScaleX= 1
DXF ScaleY= 10

--- UNT149 IN BECR.p01 (plan) ---

Plan Title=Multiple Run
Short Identifier=Multiple
Geom File=g01
Flow File=f01
Subcritical Flow
K Sum by GR= 0
Std Step Tol= 0.01
Critical Tol= 0.01
Num of Std Step Trials= 20
Max Error Tol= 0.3
Flow Tol Ratio= 0.001
Split Flow NTrial= 30
Split Flow Tol= 0.02
Split Flow Ratio= 0.02
Log Output Level= 0
Friction Slope Method= 1
Unsteady Friction Slope Method= 2
Unsteady Bridges Friction Slope Method= 1
Parabolic Critical Depth
Global Vel Dist=  1 , 1 , 1
Global Log Level= 0
CheckData=True
Encroach Param= -1, 0, 0, 0
BEGIN DESCRIPTION:
Multiple Run
END DESCRIPTION:

--- UNT149 IN BECR.f01 (steady flow) ---

Flow Title=Multiple
Program Version=4.10
Number of Profiles= 7
Profile Names=10-year,25-year,50-year,1pct_min,100-year,1pct_plu,500-year
River Rch & RM=UNT149 IN BECR,Reach-1         ,4691
     580     784     952     850    1150    1555    1682
Boundary for River Rch & Prof#=UNT149 IN BECR,Reach-1         , 1
Up Type= 0
Dn Type= 3
Dn Slope=0.006
Boundary for River Rch & Prof#=UNT149 IN BECR,Reach-1         , 2
Up Type= 0
Dn Type= 3
Dn Slope=0.006
Boundary for River Rch & Prof#=UNT149 IN BECR,Reach-1         , 3
Up Type= 0
Dn Type= 3
Dn Slope=0.006
Boundary for River Rch & Prof#=UNT149 IN BECR,Reach-1         , 4
Up Type= 0
Dn Type= 3
Dn Slope=0.006
Boundary for River Rch & Prof#=UNT149 IN BECR,Reach-1         , 5
Up Type= 0
Dn Type= 3
Dn Slope=0.006
Boundary for River Rch & Prof#=UNT149 IN BECR,Reach-1         , 6
Up Type= 0
Dn Type= 3
Dn Slope=0.006
Boundary for River Rch & Prof#=UNT149 IN BECR,Reach-1         , 7
Up Type= 0
Dn Type= 3
Dn Slope=0.006
DSS Import GetInterval= 0
DSS Import GetPeak= 0
DSS Import FillOption= 0

--- UNT149 IN BECR.g01 (geometry) ---

Geom Title=Existing Conditions
Program Version=4.10

River Reach=UNT149 IN BECR  ,Reach-1
Reach XY= 30
       3766178.5       10499340.       3766110.5       10499491.
      3766135.75       10499633.      3766023.75       10499893.
       3765940.5       10499995.       3765966.5       10500068.
      3765942.75       10500139.      3766009.25       10500234.
      3765981.25       10500364.      3766057.25       10500421.
      3766058.25       10500487.       3766107.5       10500536.
      3766236.75       10500986.        3766153.       10501169.
      3766272.25       10501207.      3766251.75       10501415.
      3766397.75       10501646.      3766609.25       10501771.
      3766717.25       10501871.      3766730.75       10501949.
      3766869.75       10502011.       3766932.5       10502158.
      3766997.25       10502180.      3766928.57     10502484.46
        3766833.       10502640.      3766699.61      10502719.9
      3766649.61     10502810.19      3766549.61     10502810.19
      3766449.61     10502710.19      3766299.61       10502761.

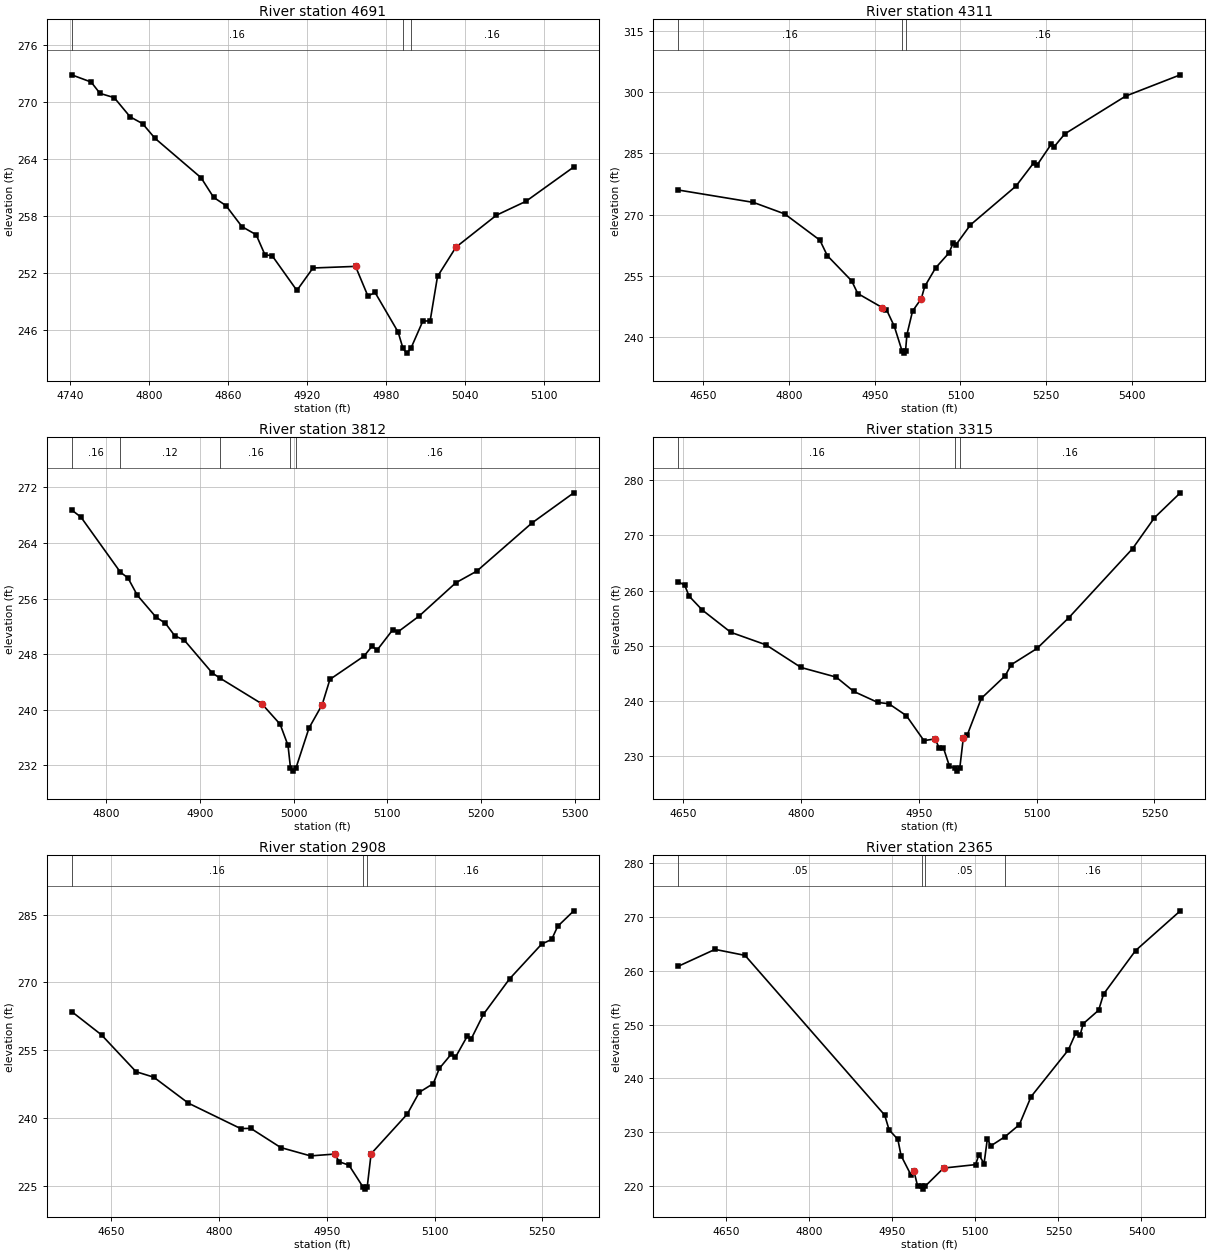
Type RM Length L Ch R = 1 ,4691    ,380,380,380
BEGIN DESCRIPTION:
UNT149 IN BECR 9.0
END DESCRIPTION:
XS GIS Cut Line= 3
      3765899.64     10499510.17      3766149.61     10499410.19
      3766249.59     10499460.18
#Sta/Elev= 30
  4741.3  272.84  4756.1  272.08  4762.8  270.89  4773.6  270.44  4785.7  268.42
  4795.1  267.71  4804.5  266.17  4839.5  262.02    4849  259.96  4858.4  259.09
  4870.5  256.88  4881.3  256.03    4888  253.91  4893.4  253.83  4912.2  250.17
  4924.4  252.53  4956.7   252.7  4966.1  249.58  4971.5  249.96    4989   245.8
  4992.7  244.08  4995.5  243.58  4998.7  244.08  5007.8  246.96  5013.3  246.96
  5018.9  251.64  5032.9  254.72  5063.6  258.08    5086  259.54  5122.3  263.15
#Mann= 3 ,-1 , 0
  4741.3     .16       0  4992.7     .07       0  4998.7     .16       0
Bank Sta=4956.7,5032.9
XS Rating Curve= 0 ,0
Exp/Cntr=0.3,0.1

Type RM Length L Ch R = 1 ,4311    ,499,499,499
BEGIN DESCRIPTION:
UNT149 IN BECR 8.0
END DESCRIPTION:
XS GIS Cut Line= 2
      3765714.74     10499628.39      3766539.36      10499932.2
#Sta/Elev= 30
    4606  276.06  4737.6  273.03  4792.4  270.21    4854  263.79    4867     260
  4909.6  253.84  4920.3  250.74  4962.9  247.32  4970.5  246.81  4984.2  242.74
  4997.9  236.66  5000.7  236.16  5003.9  236.66  5006.3  240.67  5016.2  246.45
  5031.4  249.46  5037.5  252.46  5056.5     257  5080.1  260.69    5087  263.04
  5092.3  262.68  5117.4  267.51  5197.3  277.03  5228.5  282.75  5233.9  282.11
    5259  287.29  5264.3  286.68  5282.6  289.78  5389.2  299.03  5484.8  304.23
#Mann= 3 ,-1 , 0
    4606     .16       0  4997.9     .07       0  5003.9     .16       0
Bank Sta=4962.9,5031.4
XS Rating Curve= 0 ,0
Exp/Cntr=0.3,0.1

Type RM Length L Ch R = 1 ,3812    ,497,497,497
BEGIN DESCRIPTION:
UNT149 IN BECR 7.0
END DESCRIPTION:
XS GIS Cut Line= 3
      3765749.63     10500210.19      3765949.61     10500210.19
      3766249.62     10500060.18
#Sta/Elev= 30
  4763.3  268.76  4773.3  267.71  4815.3  259.79  4823.3  258.98  4833.3  256.48
  4853.3  253.32  4863.3  252.44  4873.3  250.63  4883.3  250.03  4913.3  245.28
  4921.8  244.52  4966.1  240.85  4985.6  237.91    4994  234.86  4996.6  231.66
  4999.4  231.16  5002.6  231.66  5016.4  237.37  5030.4  240.72  5038.7  244.37
  5075.1  247.72  5083.5  249.13  5089.1   248.6  5105.8  251.53  5111.4  251.22
  5133.8  253.48  5172.9  258.27  5195.3  259.95    5254  266.87  5298.7  271.22
#Mann= 5 ,-1 , 0
  4763.3     .16       0  4815.3     .12       0  4921.8     .16       0
  4996.6     .07       0  5002.6     .16       0
Bank Sta=4966.1,5030.4
XS Rating Curve= 0 ,0
Exp/Cntr=0.3,0.1

Type RM Length L Ch R = 1 ,3315    ,407,407,407
BEGIN DESCRIPTION:
UNT149 IN BECR 6.0
END DESCRIPTION:
XS GIS Cut Line= 3
      3765799.65     10500760.17      3766099.61     10500610.19
       3766399.6     10500560.19
#Sta/Elev= 30
  4643.4  261.61  4651.7  260.97  4657.3  258.99  4674.1  256.47  4710.4  252.43
  4755.2  250.16  4799.9  246.05  4844.6  244.31    4867  241.71  4897.7  239.71
  4911.7  239.48    4934  237.32  4956.4  232.79  4970.4   233.1    4976  231.44
  4981.3  231.44  4988.9  228.16    4996  227.76  4998.8  227.26    5002  227.76
  5006.6  233.34  5011.7  233.86  5029.5  240.46  5059.9  244.55  5067.5  246.55
  5100.4   249.5    5141  255.09  5222.1   267.6    5250  273.21  5282.9  277.72
#Mann= 3 ,-1 , 0
  4643.4     .16       0    4996     .07       0    5002     .16       0
Bank Sta=4970.4,5006.6
XS Rating Curve= 0 ,0
Exp/Cntr=0.3,0.1

Type RM Length L Ch R = 1 ,2908    ,543,543,543
BEGIN DESCRIPTION:
UNT149 IN BECR 5.0
END DESCRIPTION:
XS GIS Cut Line= 3
      3765849.64      10500910.2      3766199.61     10501010.19
      3766499.62     10500860.18
#Sta/Elev= 30
  4594.5  263.54  4636.1  258.37  4684.2  250.22  4708.9     249    4757  243.26
  4829.8  237.63  4844.1  237.66  4885.7  233.42  4927.3  231.57  4961.3  231.98
  4966.9  230.29  4980.8  229.51  5000.2  224.71  5002.9  224.21  5006.2  224.71
  5011.6  232.04  5061.9  240.82  5078.7  245.66  5098.2  247.58  5106.6  250.93
  5123.4  254.14    5129   253.4  5145.7  258.13  5151.3  257.57  5168.1  262.94
  5204.4  270.77  5249.2  278.49  5263.1  279.52  5271.5  282.42  5293.9  285.85
#Mann= 3 ,-1 , 0
  4594.5     .16       0  5000.2     .07       0  5006.2     .16       0
Bank Sta=4961.3,5011.6
XS Rating Curve= 0 ,0
Exp/Cntr=0.3,0.1

Type RM Length L Ch R = 1 ,2365    ,463,463,463
BEGIN DESCRIPTION:
UNT149 IN BECR 4.0
END DESCRIPTION:
XS GIS Cut Line= 3
      3765848.27     10501578.12      3766249.61     10501410.19
      3766499.63     10501010.15
#Sta/Elev= 30
  4563.3  260.81  4629.8  263.95    4684  262.84  4936.2  233.19  4944.2  230.45
    4960  228.68  4965.8  225.67  4983.7  222.06  4989.2  222.72  4995.6  220.06
    5003  219.94  5005.8  219.44    5009  219.94  5042.6  223.35  5100.4  223.99
  5106.3  225.83  5115.7  224.18  5121.6  228.75  5128.1  227.48  5153.7  229.19
  5179.4   231.4  5200.6  236.61  5267.8  245.27  5281.4  248.44    5289     248
  5294.9  250.16  5322.6  252.66  5331.5  255.65  5389.3  263.73  5470.1  271.11
#Mann= 4 ,-1 , 0
  4563.3     .05       0    5003     .03       0    5009     .05       0
  5153.7     .16       0
Bank Sta=4989.2,5042.6
XS Rating Curve= 0 ,0
Exp/Cntr=0.3,0.1

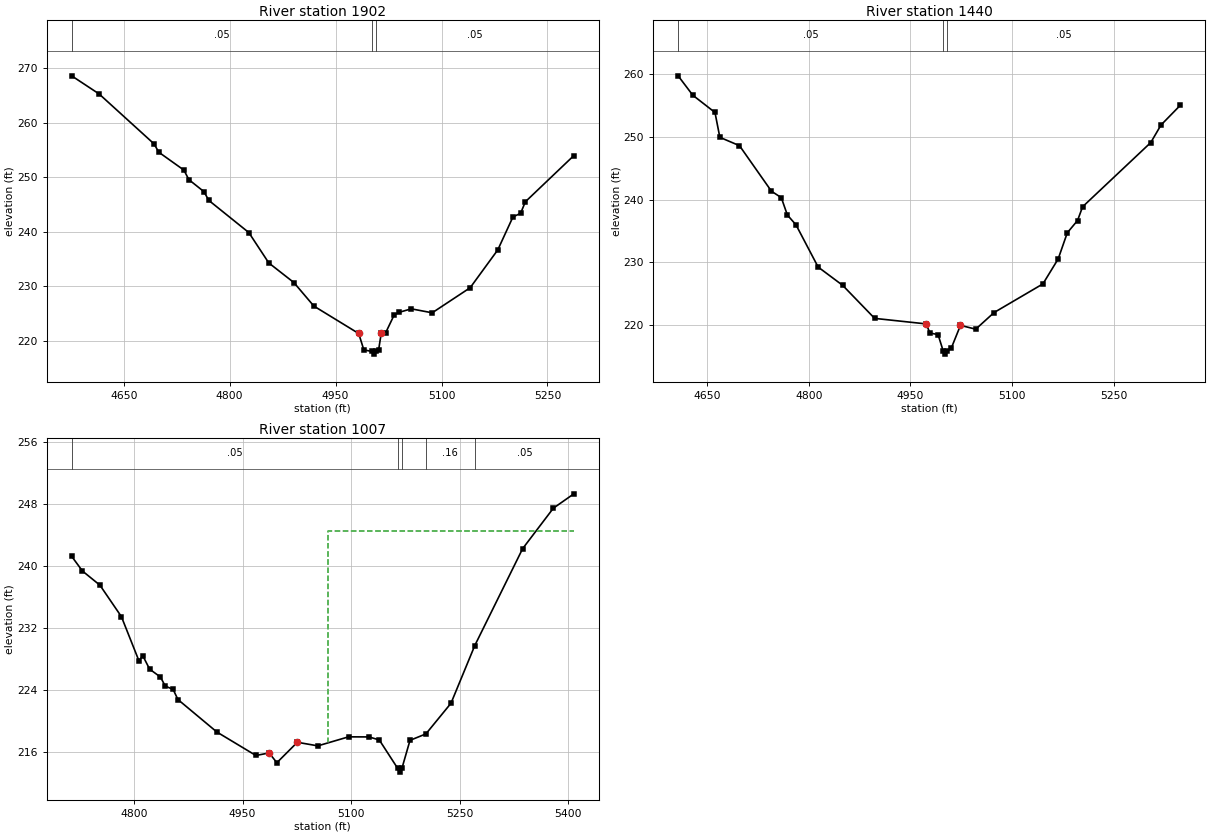
Type RM Length L Ch R = 1 ,1902    ,462,462,462
BEGIN DESCRIPTION:
UNT149 IN BECR 3.0
END DESCRIPTION:
XS GIS Cut Line= 3
      3766244.09     10502029.49      3766549.61     10501710.19
      3766649.62     10501460.17
#Sta/Elev= 30
  4576.2  268.65  4615.1  265.32  4692.7  256.17  4699.8   254.6  4735.2  251.33
  4742.2  249.58  4763.5  247.38  4770.5  245.76  4827.1  239.86  4855.4  234.28
  4890.9  230.68  4919.2  226.36  4982.7  221.32    4990  218.31  5001.1  218.03
  5003.9  217.53  5007.1  218.03    5011  218.36  5014.7  221.43  5020.8  221.43
  5032.9  224.71  5039.7   225.2  5057.2  225.85  5086.8  225.12  5140.6  229.73
  5179.7  236.68  5201.2  242.74    5212  243.39  5218.7  245.51  5287.4     254
#Mann= 3 ,-1 , 0
  4576.2     .05       0  5001.1     .03       0  5007.1     .05       0
Bank Sta=4982.7,5014.7
XS Rating Curve= 0 ,0
Exp/Cntr=0.3,0.1

Type RM Length L Ch R = 1 ,1440    ,433,433,433
BEGIN DESCRIPTION:
UNT149 IN BECR 2.0
END DESCRIPTION:
XS GIS Cut Line= 3
      3766499.65     10502160.17      3766849.61     10502010.19
      3767149.61     10501810.19
#Sta/Elev= 30
  4607.2   259.7  4628.9  256.61  4661.6  253.87  4668.8  249.91  4697.8  248.58
    4745  241.33  4759.5  240.31  4768.5  237.54  4781.2  235.98  4813.9  229.26
  4850.1  226.35  4897.3  221.09  4973.4  220.21  4978.9  218.76  4990.9  218.51
  4998.5   215.9  5001.2   215.4  5004.5   215.9  5010.5  216.37    5024  219.98
  5046.5  219.37  5073.6  222.02  5145.7  226.58  5168.2  230.55  5181.7  234.72
  5196.8  236.67  5204.3  238.86  5304.9  249.08    5320  251.87  5348.5  255.01
#Mann= 3 ,-1 , 0
  4607.2     .05       0  4998.5     .03       0  5004.5     .05       0
Bank Sta=4973.4,5024
XS Rating Curve= 0 ,0
Exp/Cntr=0.3,0.1

Type RM Length L Ch R = 1 ,1007    ,0,0,0
BEGIN DESCRIPTION:
UNT149 IN BECR 1.0
END DESCRIPTION:
XS GIS Cut Line= 3
      3766699.57     10502460.21      3766949.61     10502360.19
      3767249.63     10502060.17
#Sta/Elev= 30
  4713.9  241.24  4728.8  239.35    4753  237.52  4782.6  233.48  4806.8   227.8
  4812.2  228.44  4821.6  226.72  4836.5  225.71  4843.2  224.54    4854  224.12
  4860.7  222.81  4914.5  218.63  4968.4  215.61  4986.7  215.94  4997.3  214.68
  5025.6  217.31  5053.9  216.85  5096.3  218.01  5124.6     218  5138.8  217.61
  5164.1  213.97  5166.8  213.47  5170.1  213.97  5181.2  217.56  5203.2  218.39
  5237.8  222.33  5270.7  229.76  5336.8  242.23  5379.2  247.43  5407.5  249.28
#Mann= 5 ,-1 , 0
  4713.9     .05       0  5164.1     .03       0  5170.1     .05       0
  5203.2     .16       0  5270.7     .05       0
#XS Ineff= 2 , 0
                         5067.98          244.53
Permanent Ineff=
       F       F
Bank Sta=4986.7,5025.6
XS Rating Curve= 0 ,0
Exp/Cntr=0.3,0.1

Chan Stop Cuts=-1
Use User Specified Reach Order=0
Composite Channel Slope=5