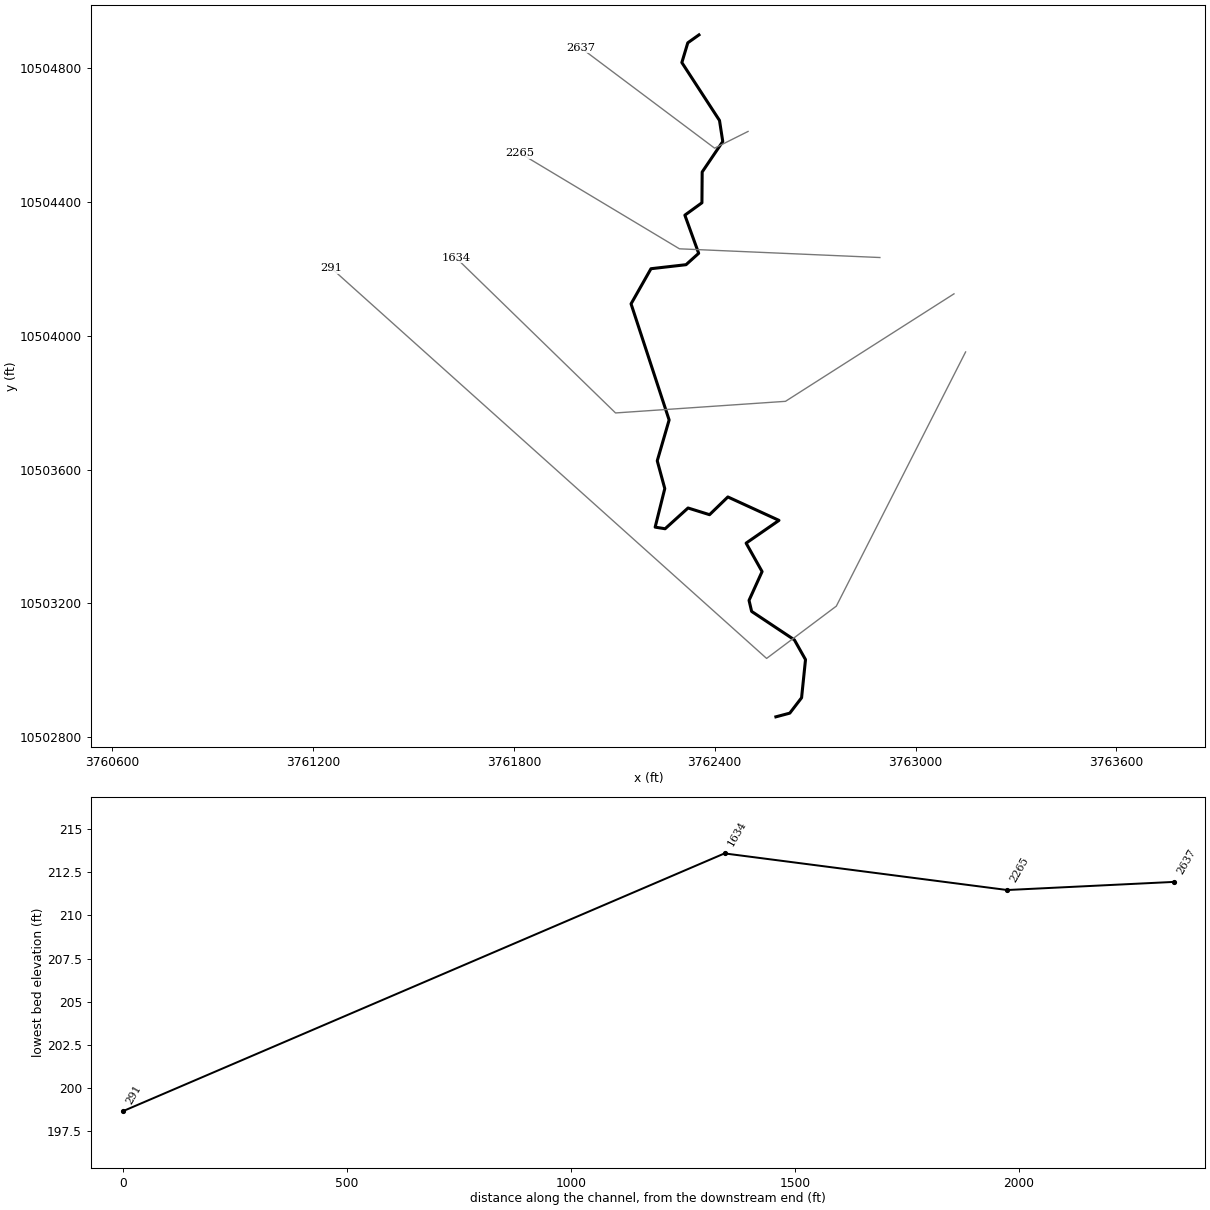
--- UNT150 IN BECR.prj (project) ---

Proj Title=UNT150 IN BECR Base Level Engineering
Current Plan=p01
Default Exp/Contr=0.3,0.1
English Units
Geom File=g01
Flow File=f01
Plan File=p01
BEGIN DESCRIPTION:
UNT150 IN BECR
END DESCRIPTION:

--- UNT150 IN BECR.p01 (plan) ---

Plan Title=Multiple Run
Short Identifier=Multiple
Geom File=g01
Flow File=f01
Subcritical Flow
K Sum by GR= 0
Std Step Tol= 0.01
Critical Tol= 0.01
Num of Std Step Trials= 20
Max Error Tol= 0.3
Flow Tol Ratio= 0.001
Split Flow NTrial= 30
Split Flow Tol= 0.02
Split Flow Ratio= 0.02
Log Output Level= 0
Friction Slope Method= 1
Unsteady Friction Slope Method= 2
Unsteady Bridges Friction Slope Method= 1
Parabolic Critical Depth
Global Vel Dist=  1 , 1 , 1
Global Log Level= 0
CheckData=True
Encroach Param= -1, 0, 0, 0
BEGIN DESCRIPTION:
Multiple Run
END DESCRIPTION:

--- UNT150 IN BECR.f01 (steady flow) ---

Flow Title=Multiple
Number of Profiles=7
Profile Names=10-year,25-year,50-year,1pct_min,100-year,1pct_plu,500-year
River Rch & RM= UNT150 IN BECR,Reach-1,2637
     584     791     961     859    1162    1571    1704
Boundary for River Rch & Prof#=UNT150 IN BECR,Reach-1,1
Up Type=0
Dn Type=3
Dn Slope=0.005
Boundary for River Rch & Prof#=UNT150 IN BECR,Reach-1,2
Up Type=0
Dn Type=3
Dn Slope=0.005
Boundary for River Rch & Prof#=UNT150 IN BECR,Reach-1,3
Up Type=0
Dn Type=3
Dn Slope=0.005
Boundary for River Rch & Prof#=UNT150 IN BECR,Reach-1,4
Up Type=0
Dn Type=3
Dn Slope=0.005
Boundary for River Rch & Prof#=UNT150 IN BECR,Reach-1,5
Up Type=0
Dn Type=3
Dn Slope=0.005
Boundary for River Rch & Prof#=UNT150 IN BECR,Reach-1,6
Up Type=0
Dn Type=3
Dn Slope=0.005
Boundary for River Rch & Prof#=UNT150 IN BECR,Reach-1,7
Up Type=0
Dn Type=3
Dn Slope=0.005

--- UNT150 IN BECR.g01 (geometry) ---

Geom Title=Existing Conditions

River Reach=UNT150 IN BECR,Reach-1
Reach XY= 30
      3762352.90     10504898.68      3762319.50     10504875.00
      3762301.75     10504816.00      3762414.25     10504643.00
      3762424.00     10504580.00      3762362.50     10504489.00
      3762361.75     10504397.00      3762310.75     10504360.00
      3762352.00     10504246.00      3762314.25     10504212.00
      3762209.50     10504200.00      3762150.00     10504095.00
      3762263.75     10503748.00      3762228.25     10503626.00
      3762250.75     10503543.00      3762221.97     10503427.79
      3762251.75     10503423.00      3762320.25     10503485.00
      3762384.50     10503465.00      3762439.25     10503518.00
      3762592.00     10503448.00      3762493.75     10503380.00
      3762541.50     10503295.00      3762502.50     10503209.00
      3762510.25     10503176.00      3762638.00     10503091.00
      3762671.25     10503032.00      3762659.50     10502918.00
      3762624.25     10502872.00      3762582.75     10502861.00

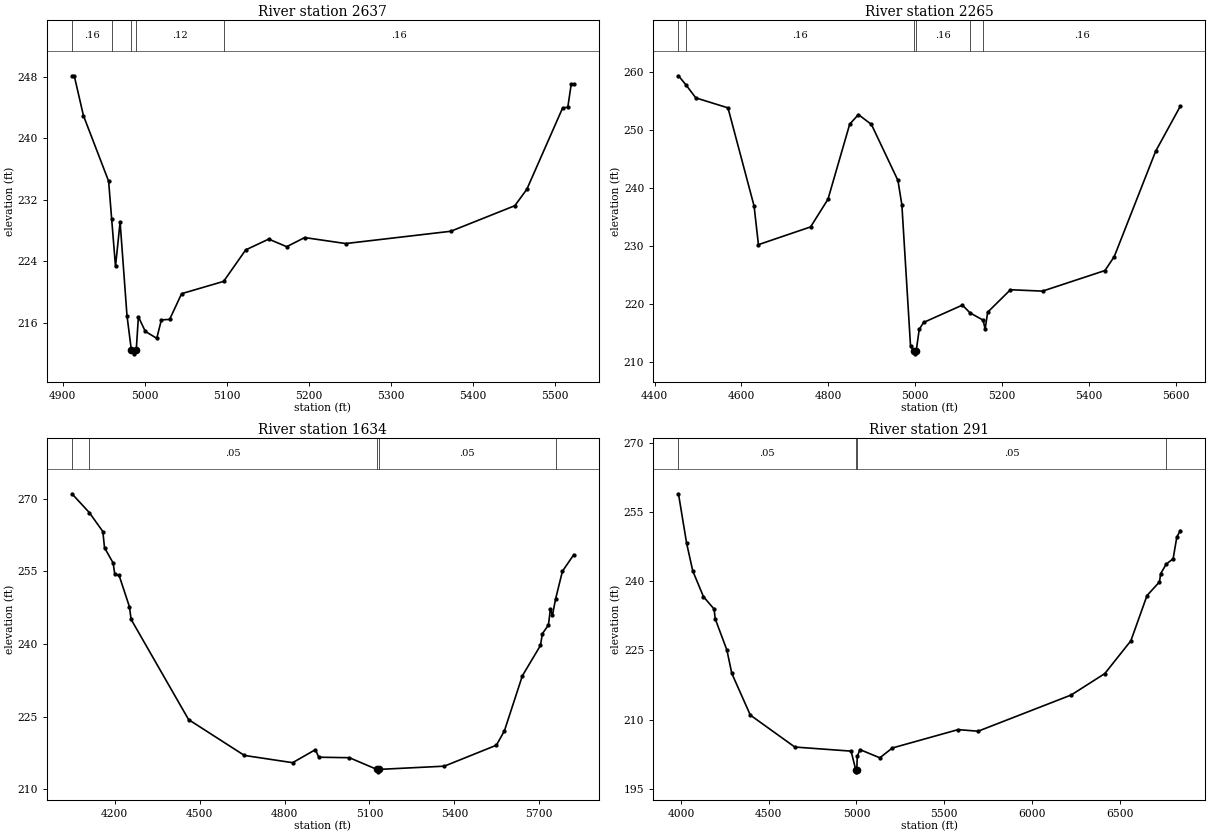
Type RM Length L Ch R = 1,2637,372,372,372
BEGIN DESCRIPTION:
UNT150 IN BECR 3.0
END DESCRIPTION:
XS GIS Cut Line= 3
      3762499.59     10504610.18      3762399.61     10504560.19
      3761999.60     10504860.20
#Sta/Elev= 30
  4911.2  248.17  4914.0  248.17  4925.2  242.98  4955.9  234.44  4959.6  229.54
  4964.3  223.32  4969.9  229.12  4978.3  216.92  4983.6  212.44  4986.4  211.94
  4989.6  212.44  4992.2  216.77  5000.6  214.87  5014.6  213.96  5020.2  216.36
  5030.3  216.43  5044.9  219.78  5096.1  221.38  5123.0  225.48  5151.1  226.89
  5173.0  225.90  5194.9  227.09  5244.9  226.31  5373.0  227.91  5451.1  231.24
  5465.7  233.37  5509.4  243.98  5515.7  244.08  5519.9  247.10  5523.0  247.10
#Mann=5,-1,0
  4911.2    0.16       0  4959.6    0.12       0  4983.6    0.07       0
  4989.6    0.12       0  5096.1    0.16       0
Bank Sta=4983.6,4989.6
Exp/Cntr=0.3,0.1

Type RM Length L Ch R = 1,2265,631,631,631
BEGIN DESCRIPTION:
UNT150 IN BECR 2.0
END DESCRIPTION:
XS GIS Cut Line= 3
      3762893.52     10504233.41      3762294.57     10504259.45
      3761817.73     10504545.56
#Sta/Elev= 30
  4455.2  259.40  4473.2  257.76  4495.1  255.59  4569.2  253.87  4629.3  236.95
  4639.3  230.29  4759.4  233.35  4799.4  238.11  4849.5  251.06  4869.5  252.71
  4899.5  251.01  4960.6  241.35  4969.6  237.15  4989.6  212.76  4996.6  211.97
  4999.4  211.47  5002.6  211.97  5009.6  215.69  5019.6  216.88  5108.9  219.87
  5126.6  218.53  5156.7  217.28  5161.3  215.72  5167.2  218.65  5219.6  222.52
  5293.5  222.28  5437.3  225.83  5458.7  228.24  5553.9  246.38  5610.8  254.16
#Mann=6,-1,0
  4455.2    0.05       0  4473.2    0.16       0  4996.6    0.07       0
  5002.6    0.16       0  5126.6    0.12       0  5156.7    0.16       0
Bank Sta=4996.6,5002.6
Exp/Cntr=0.3,0.1

Type RM Length L Ch R = 1,1634,1343,1343,1343
BEGIN DESCRIPTION:
Mapping XS 0df02e07
END DESCRIPTION:
XS GIS Cut Line= 4
      3763114.90     10504124.91      3762611.41     10503803.72
      3762103.60     10503769.00      3761626.14     10504233.45
#Sta/Elev= 30
  4049.3  271.05  4110.6  267.17  4158.4  263.25  4164.3  259.92  4194.8  256.74
  4200.7  254.39  4215.9  254.17  4252.3  247.71  4258.2  245.10  4461.3  224.38
  4658.3  216.98  4828.7  215.48  4908.9  218.17  4921.1  216.61  5029.2  216.51
  5126.4  214.09  5129.2  213.59  5132.4  214.09  5364.3  214.76  5548.2  219.09
  5576.5  222.05  5640.0  233.44  5703.8  239.70  5710.7  242.13  5732.1  243.95
  5739.0  247.22  5746.2  245.95  5757.5  249.36  5781.5  255.05  5821.6  258.47
#Mann=5,-1,0
  4049.3    0.16       0  4110.6    0.05       0  5126.4    0.03       0
  5132.4    0.05       0  5757.5    0.16       0
Bank Sta=5126.4,5132.4
Exp/Cntr=0.3,0.1

Type RM Length L Ch R = 1,291,0,0,0
BEGIN DESCRIPTION:
UNT150 IN BECR 1.0
END DESCRIPTION:
XS GIS Cut Line= 4
      3763149.60     10503951.28      3762763.32     10503191.75
      3762554.99     10503035.50      3761253.73     10504202.29
#Sta/Elev= 30
  3985.7  258.97  4031.8  248.30  4067.0  242.25  4128.1  236.65  4188.9  233.96
  4194.9  231.87  4261.6  225.07  4289.8  220.00  4395.1  210.97  4648.8  204.04
  4969.6  203.15  4995.7  199.16  4998.5  198.66  5001.7  199.16  5005.0  202.01
  5019.6  203.49  5133.4  201.70  5204.4  203.83  5579.7  207.82  5693.3  207.47
  6224.1  215.33  6415.5  219.97  6564.2  227.09  6656.2  236.90  6727.2  239.85
  6733.9  241.64  6765.9  243.72  6805.0  244.88  6825.9  249.56  6846.0  251.00
#Mann=4,-1,0
  3985.7    0.05       0  4995.7    0.03       0  5001.7    0.05       0
  6765.9    0.16       0
Bank Sta=4995.7,5001.7
Exp/Cntr=0.3,0.1

Chan Stop Cuts=-1