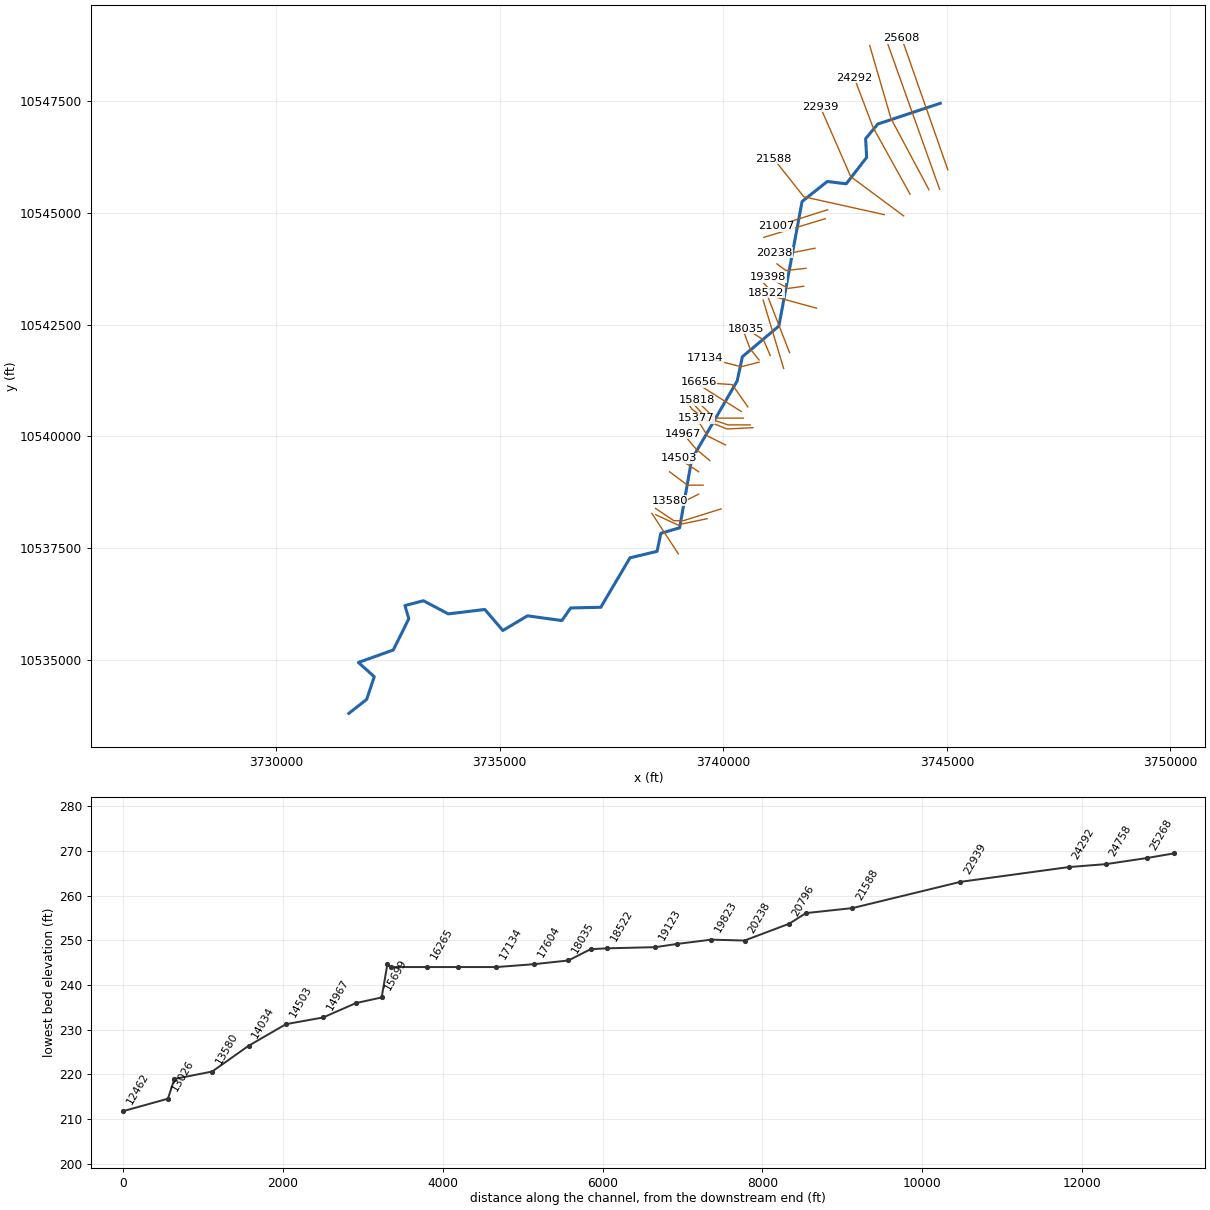
--- UNT151 IN BECR.prj (project) ---

Proj Title=UNT151 IN BECR Base Level Engineering
Current Plan=p01
Default Exp/Contr=0.3,0.1
English Units
Geom File=g01
Flow File=f01
Plan File=p01
Y Axis Title=Elevation
X Axis Title(PF)=Main Channel Distance
X Axis Title(XS)=Station
BEGIN DESCRIPTION:
UNT151 IN BECR
END DESCRIPTION:
DSS Export Rating Curves= 0
DSS Export Rating Curve Sorted= 0
DSS Export Volume Flow Curves= 0
DXF OffsetX= 0
DXF OffsetY= 0
DXF ScaleX= 1
DXF ScaleY= 10

--- UNT151 IN BECR.p01 (plan) ---

Plan Title=Multiple Run
Short Identifier=Multiple
Geom File=g01
Flow File=f01
Subcritical Flow
K Sum by GR= 0
Std Step Tol= 0.01
Critical Tol= 0.01
Num of Std Step Trials= 20
Max Error Tol= 0.3
Flow Tol Ratio= 0.001
Split Flow NTrial= 30
Split Flow Tol= 0.02
Split Flow Ratio= 0.02
Log Output Level= 0
Friction Slope Method= 1
Unsteady Friction Slope Method= 2
Unsteady Bridges Friction Slope Method= 1
Parabolic Critical Depth
Global Vel Dist=  1 , 1 , 1
Global Log Level= 0
CheckData=True
Encroach Param= -1, 0, 0, 0
BEGIN DESCRIPTION:
Multiple Run
END DESCRIPTION:

--- UNT151 IN BECR.f01 (steady flow) ---

Flow Title=Multiple
Program Version=4.10
Number of Profiles= 7
Profile Names=10-year,25-year,50-year,1pct_min,100-year,1pct_plu,500-year
River Rch & RM=UNT151 IN BECR,Reach-1         ,25608
     469     623     747     660     892    1206    1275
River Rch & RM=UNT151 IN BECR,Reach-1         ,24758
     779    1061    1294    1158    1566    2118    2304
River Rch & RM=UNT151 IN BECR,Reach-1         ,13107
    1004    1385    1704    1537    2079    2811    3106
River Rch & RM=UNT151 IN BECR,Reach-1         ,11550
    2685    3871    4907    4547    6149    8316    9705
Boundary for River Rch & Prof#=UNT151 IN BECR,Reach-1         , 1
Up Type= 0
Dn Type= 3
Dn Slope=0.007
Boundary for River Rch & Prof#=UNT151 IN BECR,Reach-1         , 2
Up Type= 0
Dn Type= 3
Dn Slope=0.007
Boundary for River Rch & Prof#=UNT151 IN BECR,Reach-1         , 3
Up Type= 0
Dn Type= 3
Dn Slope=0.007
Boundary for River Rch & Prof#=UNT151 IN BECR,Reach-1         , 4
Up Type= 0
Dn Type= 3
Dn Slope=0.007
Boundary for River Rch & Prof#=UNT151 IN BECR,Reach-1         , 5
Up Type= 0
Dn Type= 3
Dn Slope=0.007
Boundary for River Rch & Prof#=UNT151 IN BECR,Reach-1         , 6
Up Type= 0
Dn Type= 3
Dn Slope=0.007
Boundary for River Rch & Prof#=UNT151 IN BECR,Reach-1         , 7
Up Type= 0
Dn Type= 3
Dn Slope=0.007
DSS Import GetInterval= 0
DSS Import GetPeak= 0
DSS Import FillOption= 0

--- UNT151 IN BECR.g01 (geometry) ---

Geom Title=Existing Conditions
Program Version=4.10

River Reach=UNT151 IN BECR  ,Reach-1
Reach XY= 30
      3744851.03     10547449.67      3743456.25       10546987.
      3743182.25       10546659.      3743206.25       10546241.
        3742749.       10545650.      3742324.75       10545702.
       3741761.5       10545254.        3741243.       10542469.
        3740426.       10541782.      3740309.75       10541240.
        3739293.       10539487.      3739023.25       10537957.
        3738603.       10537834.        3738519.       10537431.
      3737912.75       10537285.        3737260.       10536180.
        3736587.       10536165.      3736389.25       10535883.
       3735619.5       10535989.       3735069.5       10535660.
      3734667.75       10536131.      3733849.75       10536032.
       3733294.5       10536326.       3732880.5       10536218.
      3732966.25       10535922.        3732620.       10535225.
      3731840.75       10534946.      3732194.25       10534628.
      3732024.75       10534120.      3731626.33     10533807.36

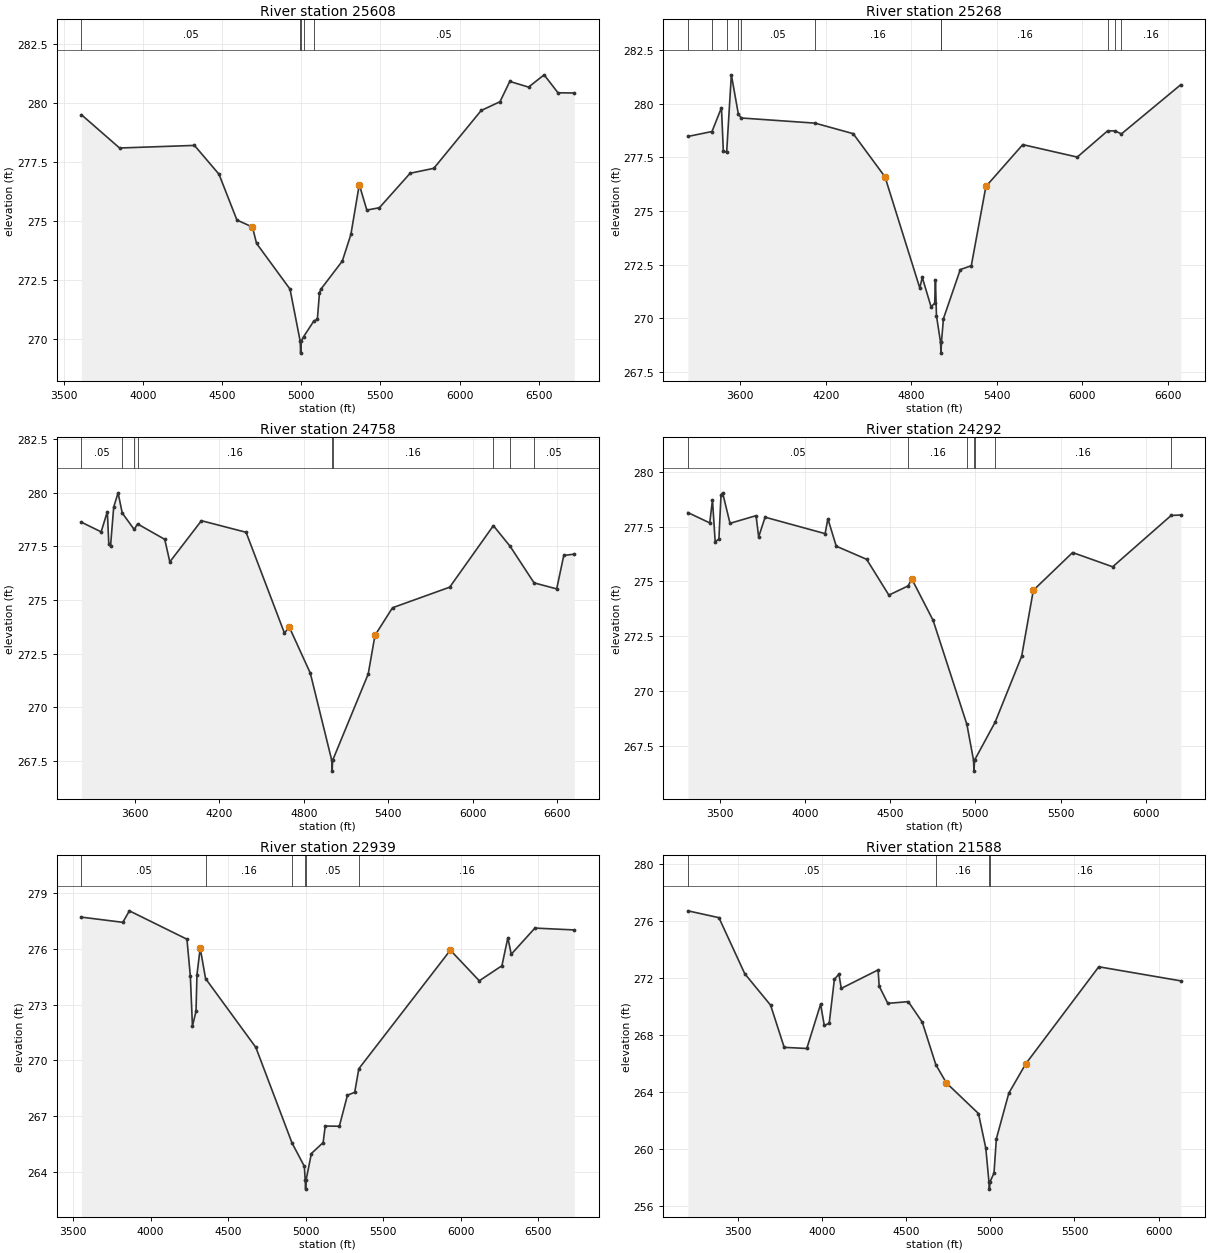
Type RM Length L Ch R = 1 ,25608   ,340,340,340
BEGIN DESCRIPTION:
UNT151 IN BECR 48.0
END DESCRIPTION:
XS GIS Cut Line= 2
      3745021.55     10545962.53      3743990.73     10548903.09
#Sta/Elev= 30
  3609.7  279.52  3850.9  278.11  4324.2  278.22  4479.3     277  4592.7  275.06
    4691  274.76  4716.7  274.07  4928.5  272.13  4992.8  269.92  4995.6  269.42
  4998.8  269.92  5014.7  270.12  5077.9  270.77  5101.3  270.86  5114.6  271.97
  5122.5  272.12    5259  273.32  5313.3  274.45  5366.3  276.56    5414  275.48
  5493.4  275.58  5687.8  277.04  5837.6  277.25  6137.1   279.7  6255.8  280.07
  6317.8  280.93  6436.5  280.69  6534.9  281.21  6622.6  280.45  6725.7  280.44
#Mann= 5 ,-1 , 0
  3609.7     .05       0  4992.8     .03       0  4998.8     .05       0
  5014.7     .16       0  5077.9     .05       0
Bank Sta=4691,5366.3
XS Rating Curve= 0 ,0
Exp/Cntr=0.3,0.1

Type RM Length L Ch R = 1 ,25268   ,510,510,510
BEGIN DESCRIPTION:
UNT151 IN BECR 47.0
END DESCRIPTION:
XS GIS Cut Line= 2
      3744837.09     10545528.51      3743676.05     10548783.75
#Sta/Elev= 30
  3233.9  278.47  3402.9   278.7  3469.3  279.81  3482.3   277.8  3505.6  277.73
  3538.6  281.34  3588.1   279.5  3608.4  279.33  4125.7  279.09  4392.9   278.6
  4615.9  276.59  4860.1  271.41  4877.2  271.91  4938.9  270.54  4964.4   270.7
  4969.7  271.79  4976.9  270.12  5005.7  268.88  5008.5  268.38  5011.7  268.88
    5026  269.99  5143.9  272.27  5221.1  272.45  5323.5  276.14    5582  278.09
  5964.3  277.51  6176.9  278.73  6227.6  278.73    6274  278.59    6690  280.88
#Mann= 11 ,-1 , 0
  3233.9     .05       0  3402.9     .08       0  3505.6     .05       0
  3588.1     .08       0  3608.4     .05       0  4125.7     .16       0
  5005.7     .07       0  5011.7     .16       0  6176.9     .05       0
  6227.6     .08       0    6274     .16       0
Bank Sta=4615.9,5323.5
XS Rating Curve= 0 ,0
Exp/Cntr=0.3,0.1

Type RM Length L Ch R = 1 ,24758   ,466,466,466
BEGIN DESCRIPTION:
UNT151 IN BECR 46.0
END DESCRIPTION:
XS GIS Cut Line= 3
      3744598.35     10545517.71      3743749.61     10547110.19
       3743274.6     10548740.26
#Sta/Elev= 30
  3219.6  278.63  3359.6  278.18  3403.7  279.12  3414.1  277.61  3426.4  277.52
    3449  279.34    3480     280  3509.5  279.06  3594.6  278.29  3618.4  278.55
  3811.6  277.83  3847.7  276.78  4072.3   278.7  4389.6  278.16  4661.5  273.47
  4697.9  273.72    4846  271.59  4998.5  267.52  5001.2  267.02  5004.5  267.52
  5257.5  271.55  5305.4  273.35  5430.2  274.64  5836.6   275.6  6147.1  278.47
  6266.6   277.5  6436.1   275.8  6596.9  275.52  6647.1  277.08    6722  277.14
#Mann= 9 ,-1 , 0
  3219.6     .05       0  3509.5     .08       0  3594.6     .05       0
  3618.4     .16       0  4998.5     .07       0  5004.5     .16       0
  6147.1     .08       0  6266.6     .16       0  6436.1     .05       0
Bank Sta=4697.9,5305.4
XS Rating Curve= 0 ,0
Exp/Cntr=0.3,0.1

Type RM Length L Ch R = 1 ,24292   ,1353,1353,1353
BEGIN DESCRIPTION:
UNT151 IN BECR 45.0
END DESCRIPTION:
XS GIS Cut Line= 3
      3744175.17     10545420.05      3743349.61     10546910.19
      3742927.35     10548024.21
#Sta/Elev= 30
  3311.5  278.14  3439.8  277.67  3455.8  278.71  3471.7  276.82  3493.6  276.93
    3506  278.94  3515.4  279.04  3558.9  277.65  3711.8     278  3727.1  277.03
  3764.9  277.93  4117.5  277.18  4133.6  277.86  4182.8  276.61  4361.4  276.01
  4491.9  274.38  4605.3   274.8  4626.3  275.12  4751.7  273.23  4950.1  268.49
  4989.2  266.86  4991.9  266.36  4995.2  266.86    5116  268.59  5271.7  271.59
  5340.4   274.6  5571.1  276.32  5806.4  275.67    6150  278.01  6206.4  278.03
#Mann= 7 ,-1 , 0
  3311.5     .05       0  4605.3     .16       0  4950.1     .05       0
  4989.2     .03       0  4995.2     .05       0    5116     .16       0
    6150     .08       0
Bank Sta=4626.3,5340.4
XS Rating Curve= 0 ,0
Exp/Cntr=0.3,0.1

Type RM Length L Ch R = 1 ,22939   ,1351,1351,1351
BEGIN DESCRIPTION:
UNT151 IN BECR 44.0
END DESCRIPTION:
XS GIS Cut Line= 3
      3744034.12     10544931.74      3742849.61     10545810.19
      3742167.81     10547373.15
#Sta/Elev= 30
  3553.7  277.72  3820.8  277.44    3863  278.06  4234.4  276.53  4256.5  274.53
  4269.9  271.84  4292.9  272.65  4299.1  274.62    4320  276.05  4354.5  274.41
  4678.9   270.7  4912.3  265.55  4991.9  264.29  4997.2  263.56    5000  263.06
  5003.2  263.56  5037.4  264.98  5113.1  265.57  5126.6  266.46  5217.7  266.45
  5269.9  268.12  5316.8  268.28  5343.4  269.55  5933.9  275.94  6120.6  274.29
  6266.5   275.1  6304.9  276.61  6326.7  275.72  6479.4  277.13  6733.6  277.03
#Mann= 6 ,-1 , 0
  3553.7     .05       0  4354.5     .16       0  4912.3     .05       0
  4997.2     .03       0  5003.2     .05       0  5343.4     .16       0
Bank Sta=4320,5933.9
XS Rating Curve= 0 ,0
Exp/Cntr=0.3,0.1

Type RM Length L Ch R = 1 ,21588   ,581,581,581
BEGIN DESCRIPTION:
UNT151 IN BECR 43.0
END DESCRIPTION:
XS GIS Cut Line= 3
      3743599.62     10544960.19      3741799.61     10545360.19
      3741126.14     10546212.13
#Sta/Elev= 30
  3202.2  276.74  3386.6  276.26  3540.3  272.32  3693.9  270.11  3774.6  267.15
    3909  267.07    3991  270.18  4012.8  268.69  4042.2  268.84  4072.9  271.92
  4099.8   272.3  4113.9  271.29  4332.9  272.59  4339.3  271.45  4390.5  270.24
  4512.2  270.36  4595.4  268.92  4676.1  265.93  4738.8  264.65  4929.6   262.5
  4973.1  260.07  4991.9  257.69  4994.6  257.19  4997.9  257.69  5021.8  258.32
  5035.9  260.73  5109.9  263.93  5210.4  265.99  5644.8  272.81  6132.1  271.82
#Mann= 4 ,-1 , 0
  3202.2     .05       0  4676.1     .16       0  4991.9     .07       0
  4997.9     .16       0
Bank Sta=4738.8,5210.4
XS Rating Curve= 0 ,0
Exp/Cntr=0.3,0.1

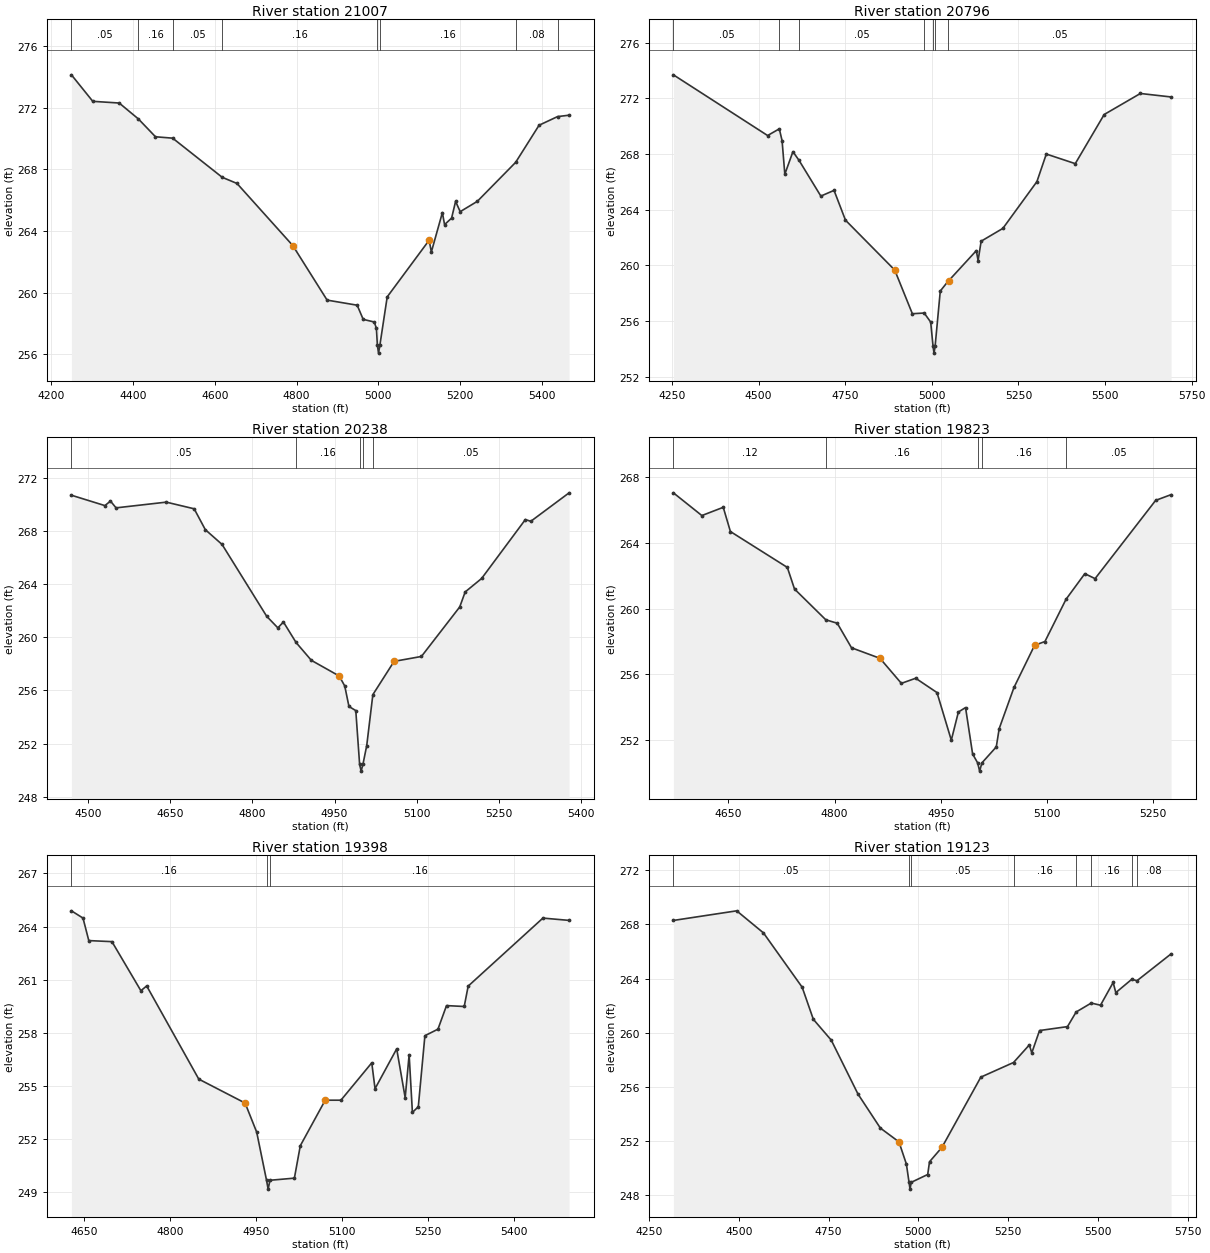
Type RM Length L Ch R = 1 ,21007   ,211,211,211
BEGIN DESCRIPTION:
UNT151 IN BECR 42.0
END DESCRIPTION:
XS GIS Cut Line= 2
      3742335.44     10545070.67      3741175.74     10544702.62
#Sta/Elev= 30
  4249.7  274.13  4301.9  272.41  4366.5   272.3  4413.3  271.27  4455.2  270.11
  4497.2  270.02  4618.3  267.48  4654.5  267.08  4790.9  263.05  4874.8  259.51
  4948.3  259.18    4963  258.26    4990  258.09  4995.3  257.68  4997.7  256.57
  5000.5  256.07  5003.7  256.57  5021.7  259.72  5124.3   263.4  5129.6  262.63
  5156.6  265.19  5161.9  264.41  5179.1  264.83  5188.9  265.92  5200.1  265.25
    5242  265.92  5335.7  268.45    5393  270.86  5438.2  271.42  5466.4  271.51
#Mann= 8 ,-1 , 0
  4249.7     .05       0  4413.3     .16       0  4497.2     .05       0
  4618.3     .16       0  4997.7     .07       0  5003.7     .16       0
  5335.7     .08       0  5438.2     .16       0
Bank Sta=4790.9,5124.3
XS Rating Curve= 0 ,0
Exp/Cntr=0.3,0.1

Type RM Length L Ch R = 1 ,20796   ,558,558,558
BEGIN DESCRIPTION:
UNT151 IN BECR 41.0
END DESCRIPTION:
XS GIS Cut Line= 2
       3742279.9     10544869.28      3740904.85      10544452.6
#Sta/Elev= 30
  4253.8  273.68  4525.8  269.32  4559.6   269.8  4567.6  268.95  4575.5  266.54
  4598.9  268.16  4616.7  267.53  4679.5  264.97  4717.6  265.38  4750.6  263.24
  4892.7  259.66  4943.7  256.52  4977.9  256.57  4996.6  255.92  5003.4  254.19
  5006.2  253.69  5009.4  254.19  5024.3  258.15  5046.4  258.84  5048.2  258.88
  5128.3  261.05  5133.5  260.34  5142.3  261.73    5205  262.65  5303.3  266.01
  5330.4  267.99    5414   267.3  5497.5  270.83    5602  272.34  5690.6  272.09
#Mann= 7 ,-1 , 0
  4253.8     .05       0  4559.6     .16       0  4616.7     .05       0
  4977.9     .16       0  5003.4     .07       0  5009.4     .16       0
  5046.4     .05       0
Bank Sta=4892.7,5048.2
XS Rating Curve= 0 ,0
Exp/Cntr=0.3,0.1

Type RM Length L Ch R = 1 ,20238   ,415,415,415
BEGIN DESCRIPTION:
UNT151 IN BECR 40.0
END DESCRIPTION:
XS GIS Cut Line= 3
      3742049.65      10544210.2      3741549.61     10544110.19
      3741149.66     10544110.19
#Sta/Elev= 30
    4469  270.67  4530.2  269.89  4540.4  270.23  4550.6  269.72  4642.4  270.15
  4693.4  269.65  4713.8  268.08  4744.4  266.97    4826  261.57  4846.4   260.7
  4856.6  261.14  4879.7   259.6  4907.6  258.26  4958.6  257.08  4968.7  256.33
  4976.4  254.79  4988.9  254.48  4995.9  250.43  4998.7  249.93  5001.9  250.43
  5008.9  251.85  5020.1  255.68  5058.9  258.18  5108.9  258.55  5178.9  262.27
  5188.9   263.4  5218.9  264.41  5298.9  268.84  5308.9  268.71  5378.9  270.85
#Mann= 5 ,-1 , 0
    4469     .05       0  4879.7     .16       0  4995.9     .07       0
  5001.9     .16       0  5020.1     .05       0
Bank Sta=4958.6,5058.9
XS Rating Curve= 0 ,0
Exp/Cntr=0.3,0.1

Type RM Length L Ch R = 1 ,19823   ,425,425,425
BEGIN DESCRIPTION:
UNT151 IN BECR 39.0
END DESCRIPTION:
XS GIS Cut Line= 3
      3741849.57     10543760.18      3741399.61     10543710.19
      3741199.63     10543860.17
#Sta/Elev= 30
  4572.3  267.03  4612.5  265.65  4642.7  266.15  4652.8  264.68  4733.2   262.5
  4743.3  261.19  4787.5  259.32  4803.7  259.11  4823.8  257.62    4864  256.98
  4894.2  255.46  4914.4  255.77  4944.5   254.9  4964.7  252.01  4974.7  253.72
  4984.8  253.99  4994.8  251.17  5001.9  250.63  5004.7  250.13  5007.9  250.63
  5028.2   251.6  5032.3  252.71  5053.2  255.21  5082.3  257.77  5096.9     258
  5126.6  260.56  5153.2  262.12  5167.7  261.82  5253.2  266.57    5275  266.92
#Mann= 5 ,-1 , 0
  4572.3     .12       0  4787.5     .16       0  5001.9     .07       0
  5007.9     .16       0  5126.6     .05       0
Bank Sta=4864,5082.3
XS Rating Curve= 0 ,0
Exp/Cntr=0.3,0.1

Type RM Length L Ch R = 1 ,19398   ,275,275,275
BEGIN DESCRIPTION:
UNT151 IN BECR 38.0
END DESCRIPTION:
XS GIS Cut Line= 3
       3741799.6     10543360.19      3741449.61     10543310.19
      3740999.63     10543560.18
#Sta/Elev= 30
  4627.7  264.89  4647.9  264.48    4658  263.21  4698.4  263.15  4748.9  260.38
    4759  260.65  4849.9  255.39  4930.7  254.04  4950.9   252.4  4968.1  249.68
  4970.9  249.18  4974.1  249.68  5016.7   249.8    5027  251.63  5070.5   254.2
  5097.9   254.2  5151.7  256.31  5157.4  254.85  5195.2   257.1    5210  254.34
  5216.9  256.77  5222.6  253.51  5232.9  253.83  5244.4  257.84  5267.2  258.21
  5282.1  259.54    5313  259.49  5319.9  260.64  5450.3  264.48    5496  264.35
#Mann= 3 ,-1 , 0
  4627.7     .16       0  4968.1     .07       0  4974.1     .16       0
Bank Sta=4930.7,5070.5
XS Rating Curve= 0 ,0
Exp/Cntr=0.3,0.1

Type RM Length L Ch R = 1 ,19123   ,601,601,601
BEGIN DESCRIPTION:
UNT151 IN BECR 37.0
END DESCRIPTION:
XS GIS Cut Line= 3
      3742085.48     10542869.26       3741189.6     10543112.33
      3740884.32     10543452.31
#Sta/Elev= 30
  4318.2  268.29  4494.4     269  4568.9  267.37  4676.6  263.36  4707.7  260.99
  4757.6  259.45    4832  255.47  4894.2  252.96    4946  251.94  4966.7   250.3
  4974.1  248.95  4976.8  248.45  4980.1  248.95    5026  249.53  5031.1  250.47
  5065.8  251.54  5173.9  256.72  5264.9   257.8  5308.9   259.1  5315.7  258.51
  5337.3  260.16  5415.1  260.45  5439.2  261.53  5481.2  262.19    5507  262.03
  5542.2  263.71  5549.6  262.96  5593.8  263.94  5608.6  263.84  5703.4  265.82
#Mann= 8 ,-1 , 0
  4318.2     .05       0  4974.1     .03       0  4980.1     .05       0
  5264.9     .16       0  5439.2     .05       0  5481.2     .16       0
  5593.8     .05       0  5608.6     .08       0
Bank Sta=4946,5065.8
XS Rating Curve= 0 ,0
Exp/Cntr=0.3,0.1

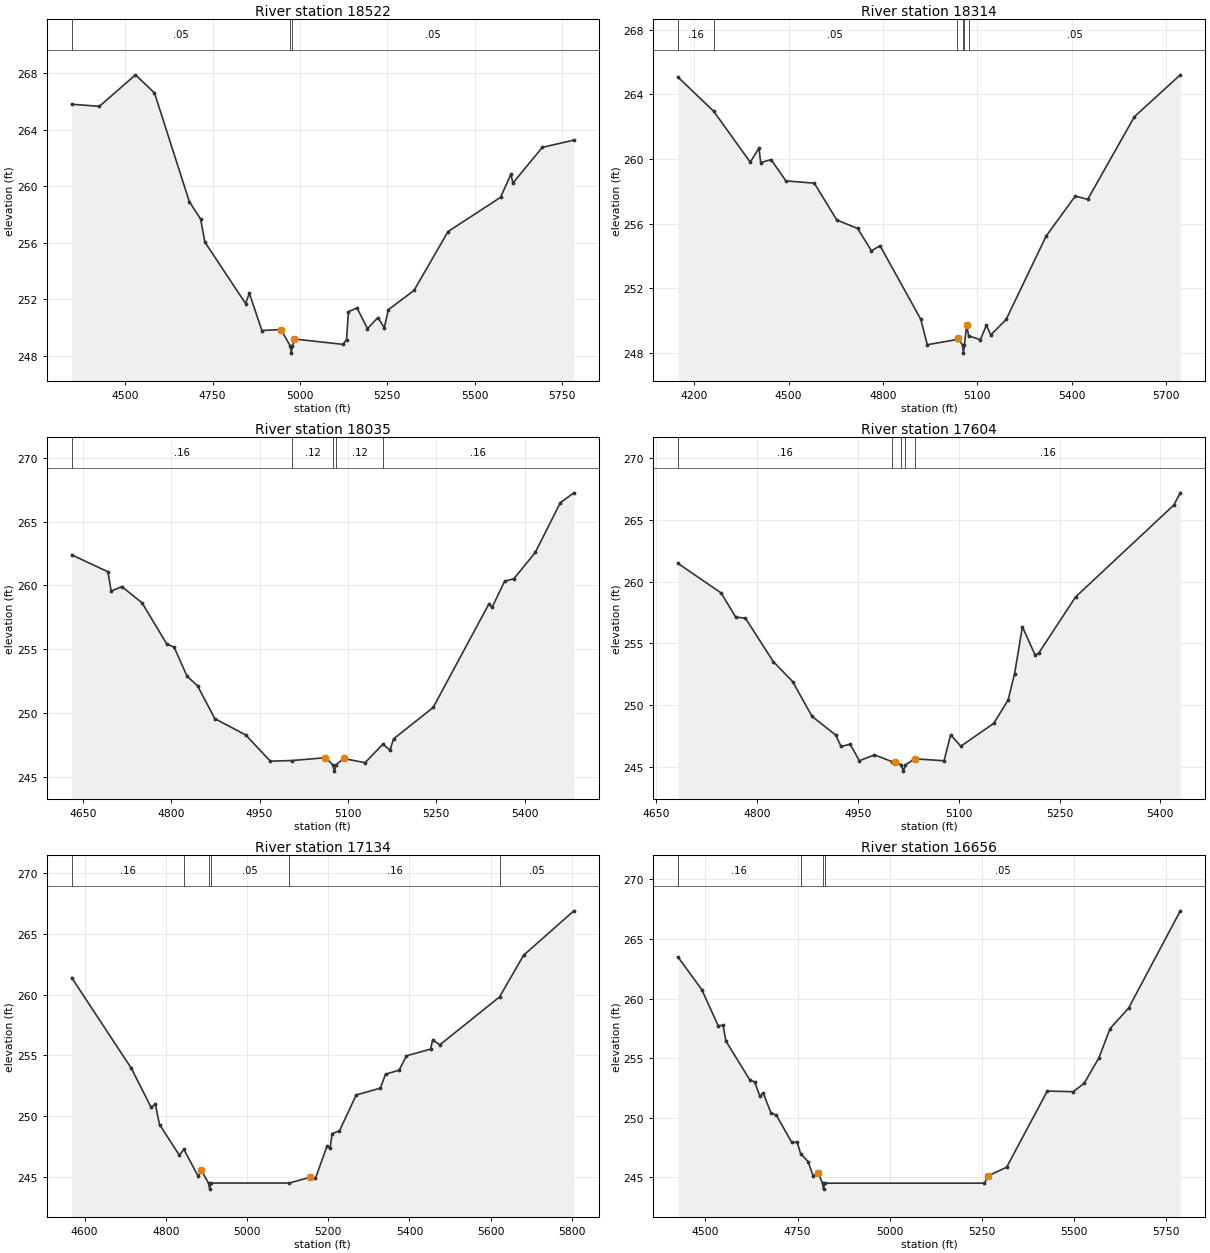
Type RM Length L Ch R = 1 ,18522   ,208,208,208
BEGIN DESCRIPTION:
UNT151 IN BECR 36.0
END DESCRIPTION:
XS GIS Cut Line= 2
      3741481.29     10541876.18      3740960.68     10543215.88
#Sta/Elev= 30
  4346.5   265.8  4425.9  265.65  4529.2  267.88  4583.6   266.6  4683.4   258.9
  4715.6  257.68  4727.8  256.05  4844.3   251.7    4855  252.43    4891  249.79
  4945.5  249.86  4972.4  248.69  4975.1  248.19  4978.4  248.69  4983.8  249.19
  5123.3  248.81  5133.3  249.15  5138.7  251.12  5163.2  251.39  5193.1  249.92
    5223  250.71  5241.3  249.98  5252.9  251.26  5326.5  252.63  5423.7  256.79
  5573.9  259.21    5604  260.86  5609.3  260.22  5693.7  262.75  5783.8  263.26
#Mann= 3 ,-1 , 0
  4346.5     .05       0  4972.4     .03       0  4978.4     .05       0
Bank Sta=4945.5,4983.8
XS Rating Curve= 0 ,0
Exp/Cntr=0.3,0.1

Type RM Length L Ch R = 1 ,18314   ,279,279,279
BEGIN DESCRIPTION:
Mapping XS 30f1678d
END DESCRIPTION:
XS GIS Cut Line= 2
      3741349.33     10541522.05      3740890.98     10543049.88
#Sta/Elev= 30
  4149.3  265.06  4262.2  262.96  4378.4  259.81  4406.2  260.68  4411.5  259.78
  4444.5  259.97  4491.9  258.65    4582  258.51  4653.3  256.23  4719.4  255.71
  4763.3  254.33  4790.8  254.64  4919.9   250.1  4940.8  248.52  5034.6  248.84
  5037.9  248.92  5052.7   248.5  5055.4     248  5058.7   248.5  5065.7  249.71
  5072.2  249.07  5109.2  248.83  5128.7  249.73  5142.3  249.12  5191.4  250.09
    5318  255.23  5410.6  257.71  5450.3  257.51  5598.6  262.62  5744.4  265.21
#Mann= 6 ,-1 , 0
  4149.3     .16       0  4262.2     .05       0  5034.6     .12       0
  5052.7     .04       0  5058.7     .12       0  5072.2     .05       0
Bank Sta=5037.9,5065.7
XS Rating Curve= 0 ,0
Exp/Cntr=0.3,0.1

Type RM Length L Ch R = 1 ,18035   ,431,431,431
BEGIN DESCRIPTION:
UNT151 IN BECR 35.0
END DESCRIPTION:
XS GIS Cut Line= 3
       3741049.6     10541810.21      3740899.61     10542160.19
      3740499.57     10542410.21
#Sta/Elev= 30
  4631.1   262.4  4692.7  261.07  4698.2  259.56  4716.3  259.91  4750.7  258.64
  4792.5  255.42  4805.1  255.17  4826.9  252.91    4845  252.13  4874.1  249.58
  4926.6   248.3  4968.3  246.25  5005.3   246.3    5062  246.52  5074.3  245.97
  5077.1  245.47  5080.3  245.97  5092.6  246.46  5129.2  246.13  5159.3  247.57
  5171.6  247.12  5177.5  247.99  5244.8  250.45  5339.1  258.53    5345   258.3
  5366.2  260.34  5381.6  260.52  5418.1  262.58  5460.6  266.47  5483.6  267.25
#Mann= 5 ,-1 , 0
  4631.1     .16       0  5005.3     .12       0  5074.3     .07       0
  5080.3     .12       0  5159.3     .16       0
Bank Sta=5062,5092.6
XS Rating Curve= 0 ,0
Exp/Cntr=0.3,0.1

Type RM Length L Ch R = 1 ,17604   ,470,470,470
BEGIN DESCRIPTION:
UNT151 IN BECR 34.0
END DESCRIPTION:
XS GIS Cut Line= 3
      3740799.62     10541710.18      3740599.61     10541960.19
       3740449.6     10542360.21
#Sta/Elev= 30
  4682.2  261.48  4746.2  259.09  4767.9  257.13  4782.3  257.05  4823.9  253.52
  4852.7   251.9  4881.5  249.08  4916.7  247.57  4924.7  246.64  4938.3  246.82
  4951.9  245.48  4974.4  245.96  5000.6  245.41    5005  245.41  5014.5  245.14
  5017.3  244.64  5020.5  245.14  5034.1  245.64    5078  245.48  5087.8  247.59
  5102.9  246.66  5151.9  248.51  5173.3   250.4    5183  252.55  5194.6  256.35
  5213.3  254.08  5218.6  254.19  5273.8  258.77  5419.8  266.21  5429.6  267.21
#Mann= 5 ,-1 , 0
  4682.2     .16       0  5000.6     .12       0  5014.5     .07       0
  5020.5     .12       0  5034.1     .16       0
Bank Sta=5005,5034.1
XS Rating Curve= 0 ,0
Exp/Cntr=0.3,0.1

Type RM Length L Ch R = 1 ,17134   ,478,478,478
BEGIN DESCRIPTION:
UNT151 IN BECR 33.0
END DESCRIPTION:
XS GIS Cut Line= 3
      3740799.58     10541660.18      3740399.61     10541560.19
      3739599.61     10541760.19
#Sta/Elev= 30
  4567.9  261.39  4714.8  253.94  4763.7  250.72    4774  250.99  4784.3  249.31
  4833.3  246.78  4844.2  247.28  4879.7  245.04  4887.4  245.54    4905   244.5
  4907.8     244    4911   244.5  5104.1   244.5  5155.4  244.98  5168.3  244.88
  5196.6  247.51  5204.4  247.37  5209.5  248.56  5227.6   248.8  5268.8  251.74
  5328.1   252.3    5341  253.45  5374.5  253.78  5392.5  254.96  5451.8  255.51
  5456.9  256.25    5475  255.87  5621.8   259.8  5681.1  263.23  5804.8  266.88
#Mann= 6 ,-1 , 0
  4567.9     .16       0  4844.2     .05       0    4905    .033       0
    4911     .05       0  5104.1     .16       0  5621.8     .05       0
Bank Sta=4887.4,5155.4
XS Rating Curve= 0 ,0
Exp/Cntr=0.3,0.1

Type RM Length L Ch R = 1 ,16656   ,391,391,391
BEGIN DESCRIPTION:
UNT151 IN BECR 32.0
END DESCRIPTION:
XS GIS Cut Line= 3
      3740549.62     10540660.17      3740199.61     10541160.19
      3739449.62     10541210.19
#Sta/Elev= 30
  4425.8  263.47  4489.9  260.75  4534.4  257.72  4547.9  257.75  4555.3  256.44
  4620.7  253.14  4633.3  253.01  4647.7  251.78  4656.4  252.08  4677.4  250.41
  4692.2  250.21    4734  247.92  4748.9  247.94  4757.8  246.99  4778.5   246.3
    4792   245.1  4805.5  245.39  4817.4   244.5  4820.1     244  4823.4   244.5
  5256.6   244.5  5266.7  245.11  5316.8  245.84    5427  252.23  5497.2  252.18
  5527.2  252.88  5567.3  255.04  5597.4  257.48  5647.5  259.19  5787.8  267.36
#Mann= 4 ,-1 , 0
  4425.8     .16       0  4757.8     .05       0  4817.4    .033       0
  4823.4     .05       0
Bank Sta=4805.5,5266.7
XS Rating Curve= 0 ,0
Exp/Cntr=0.3,0.1

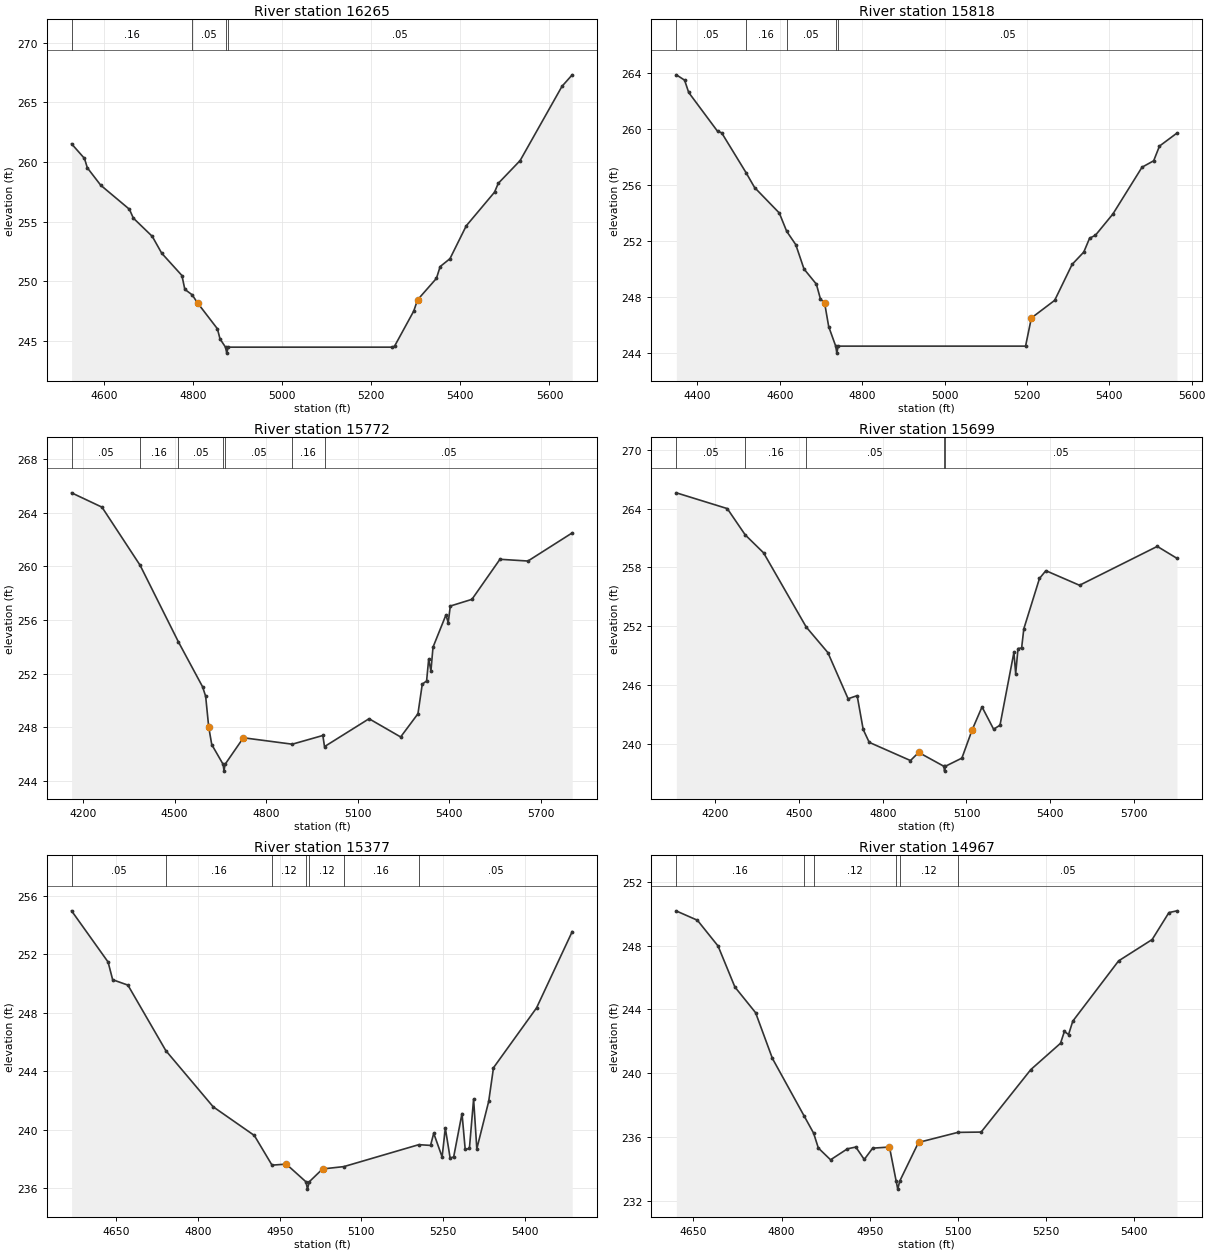
Type RM Length L Ch R = 1 ,16265   ,447,447,447
BEGIN DESCRIPTION:
UNT151 IN BECR 31.0
END DESCRIPTION:
XS GIS Cut Line= 3
      3740399.65     10540560.16      3739999.61     10540810.19
      3739449.58     10541160.21
#Sta/Elev= 30
  4527.3  261.53  4556.2  260.31  4562.7  259.52  4592.8  258.06  4657.1  256.05
  4665.9  255.31  4708.4  253.78  4729.6  252.37    4775   250.5  4781.5  249.34
  4797.8  248.89  4810.4  248.19  4854.6  246.04  4860.5  245.19  4872.8   244.5
  4875.6     244  4878.8   244.5  5246.3   244.5  5252.2  244.58  5295.4  247.53
  5303.8  248.46  5346.2  250.26  5354.6  251.25  5376.6  251.91  5413.1  254.66
  5476.6  257.48    5485  258.22  5534.1  260.13  5628.1  266.35    5651  267.31
#Mann= 4 ,-1 , 0
  4527.3     .16       0  4797.8     .05       0  4872.8    .033       0
  4878.8     .05       0
Bank Sta=4810.4,5303.8
XS Rating Curve= 0 ,0
Exp/Cntr=0.3,0.1

Type RM Length L Ch R = 1 ,15818   ,46,46,46
BEGIN DESCRIPTION:
UNT151 IN BECR 30.0
END DESCRIPTION:
XS GIS Cut Line= 3
      3740449.57     10540410.19      3739799.61     10540410.19
      3739399.57     10540810.22
#Sta/Elev= 30
  4348.7  263.88  4368.7   263.5  4378.7  262.62  4448.7  259.85  4458.7  259.74
  4517.8   256.9  4538.7  255.83  4598.7  254.01  4616.7   252.7  4638.7  251.75
  4658.7  250.01  4688.7  248.93  4698.7  247.86  4708.7  247.59  4718.7  245.89
  4735.7   244.5  4738.4     244  4741.7   244.5  5196.7   244.5  5210.8  246.51
  5267.4  247.77  5309.8  250.34  5338.1  251.22  5352.2  252.21  5366.4  252.42
  5408.8  253.94  5479.5  257.28  5507.8  257.74  5521.9  258.79  5564.4  259.72
#Mann= 5 ,-1 , 0
  4348.7     .05       0  4517.8     .16       0  4616.7     .05       0
  4735.7    .033       0  4741.7     .05       0
Bank Sta=4708.7,5210.8
XS Rating Curve= 0 ,0
Exp/Cntr=0.3,0.1

Type RM Length L Ch R = 1 ,15772   ,73,73,73
BEGIN DESCRIPTION:
Mapping XS 11908f3c
END DESCRIPTION:
XS GIS Cut Line= 5
       3740599.3     10540258.17      3740106.27     10540258.17
      3739738.21     10540383.17      3739571.55      10540466.5
      3739183.62     10540889.06
#Sta/Elev= 30
  4162.2  265.49  4261.9  264.42    4387  260.08  4512.2  254.38  4591.9  251.01
  4601.9   250.3  4611.9  248.01  4621.9   246.7  4659.3  245.22    4662  244.72
  4665.3  245.22  4725.6  247.21  4885.8  246.73  4986.2  247.38  4991.6  246.55
  5137.7  248.63  5241.3  247.27    5298     249  5312.2  251.21  5326.4  251.45
  5333.2  253.08  5340.6   252.2  5347.4  253.97  5389.9  256.38  5397.3  255.79
  5404.1  257.04    5475  257.54  5566.9  260.53  5658.7   260.4  5803.9   262.5
#Mann= 7 ,-1 , 0
  4162.2     .05       0    4387     .16       0  4512.2     .05       0
  4659.3     .03       0  4665.3     .05       0  4885.8     .16       0
  4991.6     .05       0
Bank Sta=4611.9,4725.6
XS Rating Curve= 0 ,0
Exp/Cntr=0.3,0.1

Type RM Length L Ch R = 1 ,15699   ,322,322,322
BEGIN DESCRIPTION:
Mapping XS 8bbfe6e4
END DESCRIPTION:
XS GIS Cut Line= 5
      3740661.87     10540195.67      3740078.49     10540167.89
      3739654.88      10540341.5      3739307.66     10540605.39
        3739114.     10540854.38
#Sta/Elev= 30
  4060.6  265.62  4243.1  264.01  4307.2  261.33  4373.2  259.49  4525.5  251.93
  4603.5   249.3  4675.9  244.59  4708.3  244.91  4729.9  241.46  4751.5  240.14
  4899.3  238.28  4928.7  239.11  5018.7   237.7  5021.4   237.2  5024.7   237.7
  5083.5  238.53  5120.2  241.41  5155.6  243.76  5197.2  241.48    5220  241.89
  5269.9  249.33  5276.2  247.15  5284.5  249.72  5297.5  249.78  5305.3  251.73
  5361.5  256.88  5384.3  257.67  5504.9  256.18  5783.4  260.15    5854  258.93
#Mann= 5 ,-1 , 0
  4060.6     .05       0  4307.2     .16       0  4525.5     .05       0
  5018.7     .03       0  5024.7     .05       0
Bank Sta=4928.7,5120.2
XS Rating Curve= 0 ,0
Exp/Cntr=0.3,0.1

Type RM Length L Ch R = 1 ,15377   ,410,410,410
BEGIN DESCRIPTION:
UNT151 IN BECR 29.0
END DESCRIPTION:
XS GIS Cut Line= 3
      3740049.58      10539810.2      3739649.61     10540010.19
       3739399.6     10540410.21
#Sta/Elev= 30
    4568  254.97    4635  251.47  4643.4  250.26  4671.4  249.89    4741  245.41
  4827.9  241.57  4903.4  239.61  4935.9  237.58  4962.1  237.65  4998.2  236.44
    5001  235.94  5004.2  236.44  5028.7  237.32  5067.8  237.48  5205.3  238.98
  5226.9  238.93  5232.7  239.76  5248.1  238.14    5254  240.11  5262.8  238.07
  5269.3  238.14  5284.6  241.11  5290.5  238.65  5298.2  238.72  5305.9   242.1
  5311.8   238.7  5333.6  241.94  5342.4  244.24  5421.4  248.33  5486.9  253.55
#Mann= 7 ,-1 , 0
    4568     .05       0    4741     .16       0  4935.9     .12       0
  4998.2     .07       0  5004.2     .12       0  5067.8     .16       0
  5205.3     .05       0
Bank Sta=4962.1,5028.7
XS Rating Curve= 0 ,0
Exp/Cntr=0.3,0.1

Type RM Length L Ch R = 1 ,14967   ,464,464,464
BEGIN DESCRIPTION:
UNT151 IN BECR 28.0
END DESCRIPTION:
XS GIS Cut Line= 3
      3739699.63     10539460.17      3739399.61     10539710.19
      3739099.62     10540060.18
#Sta/Elev= 30
  4621.1  250.17  4656.9  249.59  4692.1  247.97  4720.7   245.4  4755.9  243.79
  4784.5  240.92  4838.6   237.3  4854.6  236.23  4862.6   235.3  4883.4  234.56
  4912.1  235.25  4926.4  235.36  4940.7  234.58    4955  235.29  4983.6  235.36
    4995  233.22  4997.7  232.72    5001  233.22    5033  235.65  5099.9  236.28
  5139.5   236.3    5224  240.22  5274.5  241.87  5281.1  242.61  5288.2  242.42
  5295.4  243.26  5373.3  247.04  5430.4  248.38  5458.9  250.07  5472.6  250.18
#Mann= 6 ,-1 , 0
  4621.1     .16       0  4838.6     .05       0  4854.6     .12       0
    4995     .07       0    5001     .12       0  5099.9     .05       0
Bank Sta=4983.6,5033
XS Rating Curve= 0 ,0
Exp/Cntr=0.3,0.1

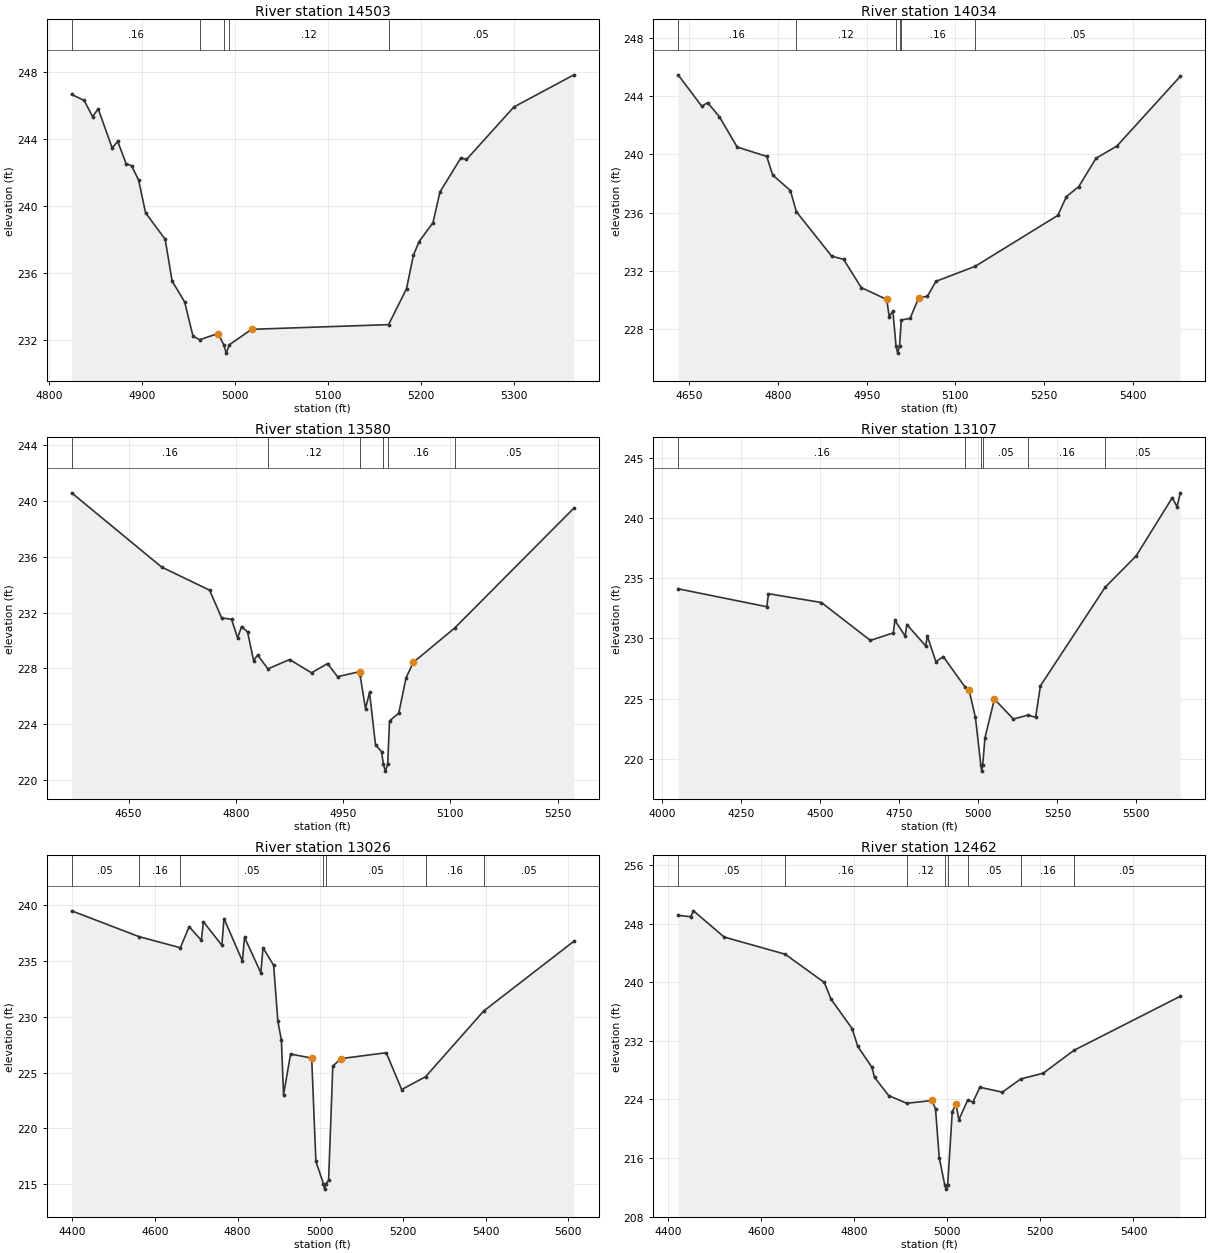
Type RM Length L Ch R = 1 ,14503   ,469,469,469
BEGIN DESCRIPTION:
UNT151 IN BECR 27.0
END DESCRIPTION:
XS GIS Cut Line= 3
      3739449.61     10539210.18      3739299.61     10539310.19
      3738999.64     10539510.17
#Sta/Elev= 30
    4824  246.66  4837.5   246.3  4846.5  245.34  4852.6   245.8  4867.6  243.47
  4873.6  243.86  4882.6  242.54  4888.6   242.4  4896.1  241.55  4903.6   239.6
  4924.7  238.02  4932.2  235.53  4945.7  234.28  4954.7  232.24  4961.9  232.03
  4981.7   232.4  4987.8  231.73  4990.5  231.23  4993.8  231.73  5017.8  232.65
  5165.3  232.93  5184.6  235.07  5192.1  237.08  5198.1  237.88  5213.1  239.01
  5220.6  240.84  5243.2  242.88  5249.2  242.78  5300.2  245.91  5364.8  247.83
#Mann= 5 ,-1 , 0
    4824     .16       0  4961.9     .12       0  4987.8     .07       0
  4993.8     .12       0  5165.3     .05       0
Bank Sta=4981.7,5017.8
XS Rating Curve= 0 ,0
Exp/Cntr=0.3,0.1

Type RM Length L Ch R = 1 ,14034   ,454,454,454
BEGIN DESCRIPTION:
UNT151 IN BECR 26.0
END DESCRIPTION:
XS GIS Cut Line= 3
      3739549.58     10538910.19      3739199.61     10538910.19
      3738799.59     10539210.21
#Sta/Elev= 30
  4630.8  245.45  4670.8   243.3  4680.8  243.54  4700.8  242.57  4730.8   240.5
  4780.8  239.86  4790.8  238.59  4820.8  237.52    4831  236.07  4890.8  233.02
  4910.8  232.81  4940.8  230.87  4983.9  230.06  4988.1  228.87  4994.3  229.28
  4999.6  226.88  5002.4  226.38  5005.6  226.88  5008.5  228.65  5023.5  228.76
  5038.1  230.19  5052.6  230.27  5067.2   231.3  5133.7  232.33  5273.5  235.82
  5288.1  237.11  5308.9  237.79  5338.1  239.73  5373.5  240.57  5480.8  245.35
#Mann= 6 ,-1 , 0
  4630.8     .16       0    4831     .12       0  4999.6     .07       0
  5005.6     .12       0  5008.5     .16       0  5133.7     .05       0
Bank Sta=4983.9,5038.1
XS Rating Curve= 0 ,0
Exp/Cntr=0.3,0.1

Type RM Length L Ch R = 1 ,13580   ,473,473,473
BEGIN DESCRIPTION:
UNT151 IN BECR 25.0
END DESCRIPTION:
XS GIS Cut Line= 3
      3739449.64     10538710.21      3739049.61     10538510.19
      3738799.61     10538560.19
#Sta/Elev= 30
  4570.4  240.58  4696.2  235.26  4763.3   233.6  4780.1  231.62    4794  231.51
  4802.4  230.18    4808  230.99  4816.4  230.61  4824.8  228.56  4830.4  228.95
  4844.9  227.96  4875.1  228.63  4905.8  227.68  4928.2  228.34  4942.2   227.4
  4972.9  227.76  4973.7  227.51  4981.3  225.11  4986.9  226.27  4995.3  222.51
  5003.7  222.03  5006.3  221.13    5009  220.63  5012.3  221.13  5014.9  224.23
  5027.8  224.79    5038  227.32  5048.2  228.43  5105.8  230.88  5272.6  239.48
#Mann= 6 ,-1 , 0
  4570.4     .16       0  4844.9     .12       0  4973.7     .16       0
  5006.3     .07       0  5012.3     .16       0  5105.8     .05       0
Bank Sta=4972.9,5048.2
XS Rating Curve= 0 ,0
Exp/Cntr=0.3,0.1

Type RM Length L Ch R = 1 ,13107   ,81,81,81
BEGIN DESCRIPTION:
Mapping XS 81ec5164
END DESCRIPTION:
XS GIS Cut Line= 4
      3739950.06     10538379.71      3739106.27     10538115.81
      3738894.46     10538115.81      3738484.71     10538390.13
#Sta/Elev= 30
  4049.9  234.13  4330.5  232.64  4335.8  233.72  4503.3  232.99  4658.1  229.84
  4730.6  230.46  4735.9   231.5  4768.3   230.2  4773.6  231.16  4833.3  229.38
  4838.5   230.2  4865.7  228.06  4888.6   228.5  4958.2  225.95  4970.7  225.68
  4990.7  223.43  5007.7  219.47  5010.4  218.97  5013.7  219.47  5020.7  221.73
  5050.7  224.96  5110.7   223.3  5156.8  223.63  5181.2  223.45  5196.2  226.06
  5401.1  234.26  5499.4  236.87  5613.5  241.71  5628.5  240.95  5638.9  242.11
#Mann= 6 ,-1 , 0
  4049.9     .16       0  4958.2     .05       0  5007.7     .03       0
  5013.7     .05       0  5156.8     .16       0  5401.1     .05       0
Bank Sta=4970.7,5050.7
XS Rating Curve= 0 ,0
Exp/Cntr=0.3,0.1

Type RM Length L Ch R = 1 ,13026   ,564,564,564
BEGIN DESCRIPTION:
UNT151 IN BECR 24.0
END DESCRIPTION:
XS GIS Cut Line= 3
      3739637.51     10538160.94      3738981.27     10538022.06
       3738488.2     10538251.23
#Sta/Elev= 30
  4398.8   239.5  4561.4  237.19  4661.7  236.19  4682.9  238.08  4712.4  236.86
  4717.5  238.52  4762.1  236.41  4767.2  238.81  4811.8     235  4816.9  237.13
  4856.4  233.94  4861.5  236.19  4887.3  234.62  4897.5   229.6  4906.1   227.9
  4911.2  222.99  4928.2  226.66  4979.3   226.3  4989.5  217.04  5007.6  215.05
  5010.3  214.55  5013.6  215.05  5020.2  215.34  5030.4  225.58  5050.1  226.25
  5159.6  226.78  5196.9  223.48  5254.8  224.63    5395  230.51  5613.3  236.77
#Mann= 7 ,-1 , 0
  4398.8     .05       0  4561.4     .16       0  4661.7     .05       0
  5007.6     .04       0  5013.6     .05       0  5254.8     .16       0
    5395     .05       0
Bank Sta=4979.3,5050.1
XS Rating Curve= 0 ,0
Exp/Cntr=0.3,0.1

Type RM Length L Ch R = 1 ,12462   ,340,340,340
BEGIN DESCRIPTION:
UNT151 IN BECR 23.0
END DESCRIPTION:
XS GIS Cut Line= 2
      3738992.59     10537377.42      3738402.32     10538280.17
#Sta/Elev= 30
    4422  249.12    4449  248.94    4455  249.74  4520.9  246.16  4651.9  243.82
    4736  239.96  4750.6  237.66  4795.7  233.67  4807.8  231.25  4838.1   228.4
    4844     227  4874.2  224.52  4912.9  223.47  4967.7  223.85  4974.9  222.66
  4982.8  216.05  4994.9  212.25  4997.7  211.75  5000.9  212.25  5010.8  222.34
    5019  223.31    5025  221.21  5043.7  223.87  5055.2  223.65  5070.3  225.65
  5118.5  224.99    5158  226.79    5206  227.57  5272.3   230.7  5500.6  238.08
#Mann= 8 ,-1 , 0
    4422     .05       0  4651.9     .16       0  4912.9     .12       0
  4994.9     .07       0  5000.9     .12       0  5043.7     .05       0
    5158     .16       0  5272.3     .05       0
Bank Sta=4967.7,5019
XS Rating Curve= 0 ,0
Exp/Cntr=0.3,0.1