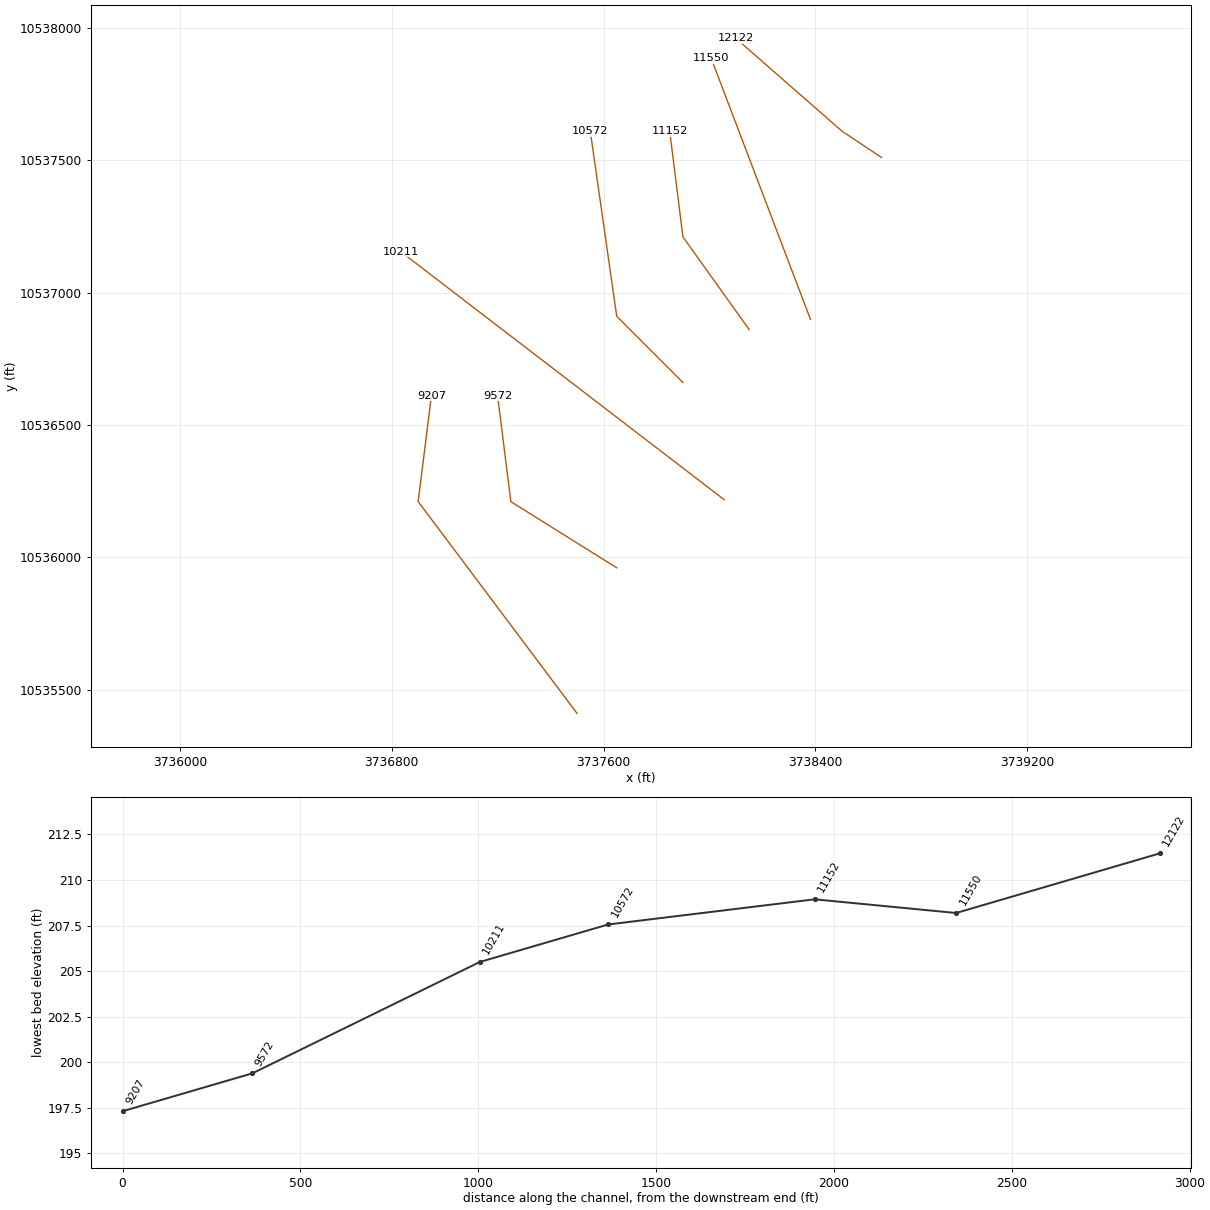
HEC-RAS study UNT151 IN BECR.prj: UNT151 IN BECR Base Level Engineering

--- UNT151 IN BECR.g01 (geometry) --- (continued)

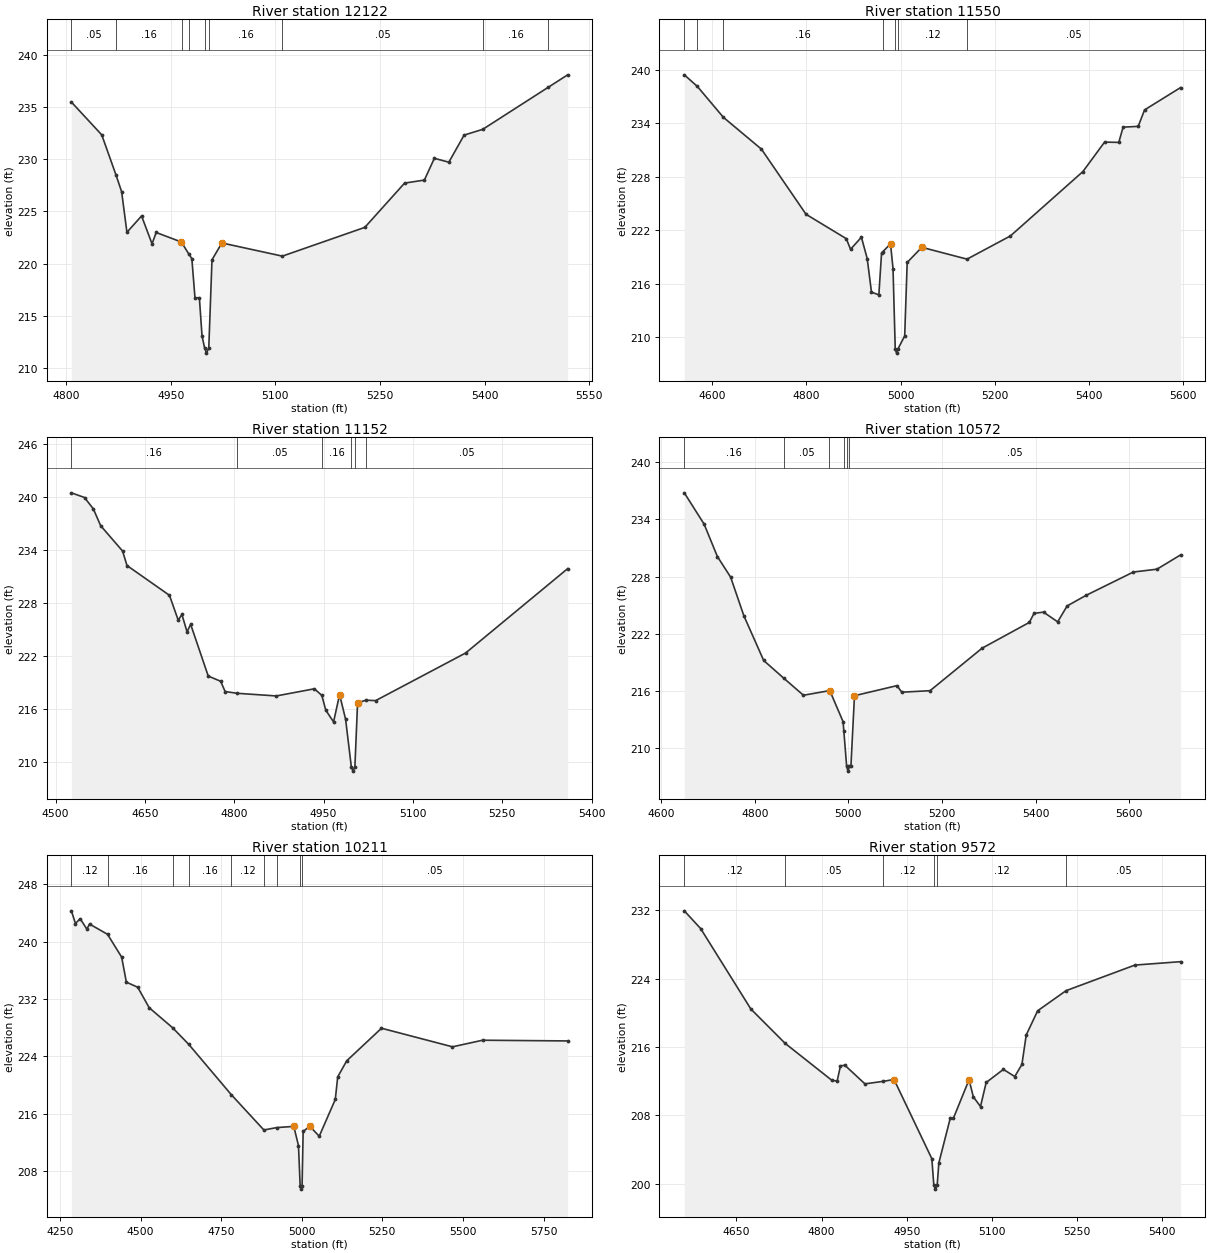
Type RM Length L Ch R = 1 ,12122   ,572,572,572
BEGIN DESCRIPTION:
UNT151 IN BECR 22.0
END DESCRIPTION:
XS GIS Cut Line= 3
      3738649.63     10537510.17      3738499.61     10537610.19
      3738099.62     10537960.18
#Sta/Elev= 30
  4807.4  235.46    4851  232.32  4871.3  228.51  4879.5  226.89  4887.1  223.01
  4908.1  224.57  4923.1  221.91  4929.1  222.99  4965.2  222.08  4966.2  221.97
  4975.5  220.97  4980.2  220.49  4984.7  216.75    4991  216.75  4994.8  213.11
  4998.5  211.96  5001.2  211.46  5004.5  211.96  5009.1  220.38  5023.3  221.99
    5110  220.73  5228.3  223.48  5285.3  227.71  5313.7     228    5328  230.08
  5348.8  229.71  5370.7   232.3  5397.4  232.85  5491.6  236.88  5519.2  238.06
#Mann= 9 ,-1 , 0
  4807.4     .05       0  4871.3     .16       0  4966.2     .12       0
  4975.5     .16       0  4998.5     .07       0  5004.5     .16       0
    5110     .05       0  5397.4     .16       0  5491.6     .05       0
Bank Sta=4965.2,5023.3
XS Rating Curve= 0 ,0
Exp/Cntr=0.3,0.1

Type RM Length L Ch R = 1 ,11550   ,398,398,398
BEGIN DESCRIPTION:
UNT151 IN BECR 21.0
END DESCRIPTION:
XS GIS Cut Line= 2
      3738381.48     10536898.26      3738006.49     10537884.36
#Sta/Elev= 30
  4540.3  239.46    4568  238.16  4623.3  234.69  4704.3  231.11  4799.1  223.79
  4884.7  221.05  4893.7  219.86  4916.8  221.21  4929.1  218.82  4938.2  215.04
  4953.9  214.74  4959.6  219.41  4962.5   219.6  4978.7  220.47    4984  217.69
  4988.7  208.69  4991.5  208.19  4994.7  208.69  5008.8  210.12  5014.1  218.38
  5045.2  220.08  5141.3  218.75  5233.6  221.36  5387.6  228.59  5433.7   231.9
  5463.9  231.87  5473.1  233.58  5505.2  233.67  5518.7  235.52  5595.3  238.03
#Mann= 7 ,-1 , 0
  4540.3     .16       0    4568     .12       0  4623.3     .16       0
  4962.5     .12       0  4988.7     .07       0  4994.7     .12       0
  5141.3     .05       0
Bank Sta=4978.7,5045.2
XS Rating Curve= 0 ,0
Exp/Cntr=0.3,0.1

Type RM Length L Ch R = 1 ,11152   ,580,580,580
BEGIN DESCRIPTION:
UNT151 IN BECR 20.0
END DESCRIPTION:
XS GIS Cut Line= 3
      3738149.62     10536860.18      3737899.61     10537210.19
      3737849.61     10537610.15
#Sta/Elev= 30
  4526.5  240.44  4548.6  239.91  4563.4  238.62  4575.7  236.72  4612.5  233.85
  4619.9  232.21  4691.2  228.84  4705.9  226.03  4712.1  226.67  4720.7  224.71
  4726.8  225.55  4756.3   219.7  4777.2  219.11  4784.6  217.95  4804.8  217.75
  4870.6  217.45  4934.5  218.26    4947  217.51  4953.6  215.84  4966.7  214.51
  4976.8   217.6  4986.9  214.81  4996.5  209.44  4999.2  208.94  5002.5  209.44
    5007  216.67    5021  216.97  5037.3  216.92  5188.4  222.31  5359.7  231.86
#Mann= 6 ,-1 , 0
  4526.5     .16       0  4804.8     .05       0    4947     .16       0
  4996.5     .07       0  5002.5     .16       0    5021     .05       0
Bank Sta=4976.8,5007
XS Rating Curve= 0 ,0
Exp/Cntr=0.3,0.1

Type RM Length L Ch R = 1 ,10572   ,361,361,361
BEGIN DESCRIPTION:
UNT151 IN BECR 19.0
END DESCRIPTION:
XS GIS Cut Line= 3
      3737899.62     10536660.18      3737649.61     10536910.19
      3737549.61     10537610.21
#Sta/Elev= 30
  4649.2  236.79  4691.6   233.5  4719.9   230.1  4748.2  227.94  4776.5  223.88
  4818.9  219.18  4861.8  217.32  4903.8  215.53    4959  216.01  4960.3     216
  4988.6  212.75  4990.2  211.76  4996.2  208.06    4999  207.56  5002.2  208.06
  5005.3  208.06  5012.9  215.48  5103.8  216.54  5113.9  215.85  5174.5  216.01
  5285.6  220.47  5386.6  223.18  5396.7  224.13  5416.9  224.26  5447.2  223.24
  5467.4  224.91  5507.8  226.02  5608.9  228.47  5659.4  228.77  5709.9  230.27
#Mann= 6 ,-1 , 0
  4649.2     .16       0  4861.8     .05       0    4959     .16       0
  4990.2     .05       0  4996.2     .03       0  5002.2     .05       0
Bank Sta=4960.3,5012.9
XS Rating Curve= 0 ,0
Exp/Cntr=0.3,0.1

Type RM Length L Ch R = 1 ,10211   ,639,639,639
BEGIN DESCRIPTION:
UNT151 IN BECR 18.0
END DESCRIPTION:
XS GIS Cut Line= 2
      3738055.09     10536217.67      3736833.72     10537154.52
#Sta/Elev= 30
  4285.5  244.28  4298.3  242.51  4312.8  243.19  4333.6  241.73  4341.8  242.44
  4397.7  241.01  4441.5  237.83  4456.1  234.34  4491.4  233.63  4526.7  230.79
  4599.7  227.98  4649.3  225.69  4781.4  218.67  4882.6  213.74    4923  214.08
  4975.4  214.24  4989.9  211.57  4995.1     206  4997.9   205.5  5001.1     206
  5004.4  213.54  5025.2  214.25  5054.3  212.87  5104.1     218  5111.6  221.14
  5139.5  223.38  5247.4  227.92  5467.6  225.33    5561  226.25  5824.8  226.15
#Mann= 9 ,-1 , 0
  4285.5     .12       0  4397.7     .16       0  4599.7     .05       0
  4649.3     .16       0  4781.4     .12       0  4882.6     .05       0
    4923     .16       0  4995.1     .03       0  5001.1     .05       0
Bank Sta=4975.4,5025.2
XS Rating Curve= 0 ,0
Exp/Cntr=0.3,0.1

Type RM Length L Ch R = 1 ,9572    ,365,365,365
BEGIN DESCRIPTION:
UNT151 IN BECR 17.0
END DESCRIPTION:
XS GIS Cut Line= 3
      3737649.59      10535960.2      3737249.61     10536210.19
      3737199.61      10536610.2
#Sta/Elev= 30
  4558.1  231.91    4587  229.83  4675.4  220.44  4736.1  216.41  4818.1  212.11
  4827.5  212.02  4833.4  213.79  4841.1  213.87  4876.5  211.69  4908.1  211.98
  4927.8   212.2  4994.4  202.95  4997.9  199.89  5000.6  199.39  5003.9  199.89
  5006.8  202.46  5026.8  207.65  5032.3  207.65    5060  212.17  5067.6  210.17
  5080.2  209.04  5090.2  211.85  5120.5  213.38  5140.6  212.55  5153.2  213.96
  5160.8   217.4  5180.9  220.23    5231  222.58  5352.3  225.57  5432.9  225.97
#Mann= 6 ,-1 , 0
  4558.1     .12       0  4736.1     .05       0  4908.1     .12       0
  4997.9     .07       0  5003.9     .12       0    5231     .05       0
Bank Sta=4927.8,5060
XS Rating Curve= 0 ,0
Exp/Cntr=0.3,0.1

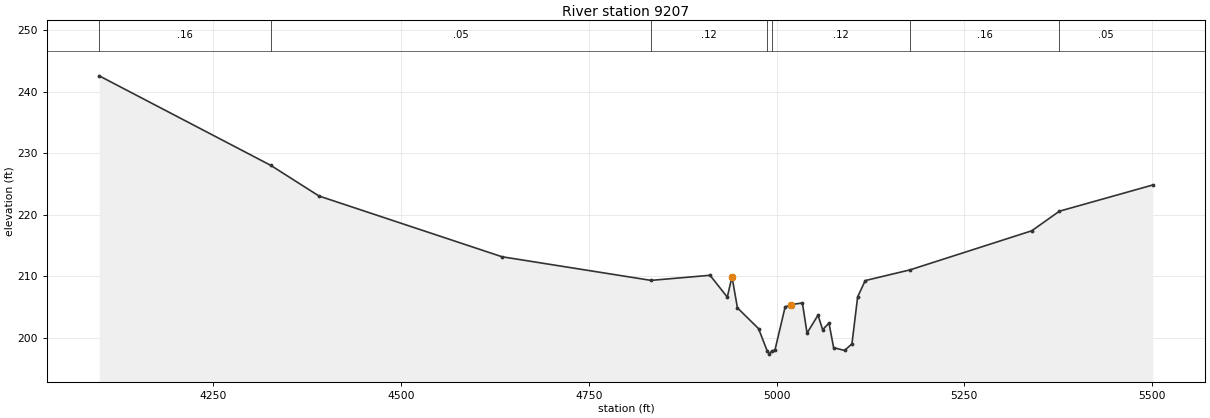
Type RM Length L Ch R = 1 ,9207    ,0,0,0
BEGIN DESCRIPTION:
UNT151 IN BECR 16.0
END DESCRIPTION:
XS GIS Cut Line= 3
      3737499.61     10535410.19      3736899.61     10536210.19
      3736949.61     10536610.18
#Sta/Elev= 30
  4097.9  242.56  4326.4     228  4390.6  223.02  4634.4  213.14  4832.8   209.3
  4911.4  210.13  4934.4  206.58  4940.6   209.9  4947.9  204.83    4976  201.46
  4987.6  197.81  4990.4  197.31  4993.6  197.81  4997.9  197.99  5011.4  204.98
  5019.8  205.37  5034.4  205.63  5040.6  200.73  5055.2  203.65  5061.4  201.27
  5069.8  202.37    5076  198.36  5090.6  197.91  5100.4  198.98    5108  206.62
  5118.1  209.27  5177.7  211.01  5339.8  217.36  5376.7  220.55    5501  224.81
#Mann= 7 ,-1 , 0
  4097.9     .16       0  4326.4     .05       0  4832.8     .12       0
  4987.6     .07       0  4993.6     .12       0  5177.7     .16       0
  5376.7     .05       0
Bank Sta=4940.6,5019.8
XS Rating Curve= 0 ,0
Exp/Cntr=0.3,0.1

Chan Stop Cuts=-1
Use User Specified Reach Order=0
Composite Channel Slope=5