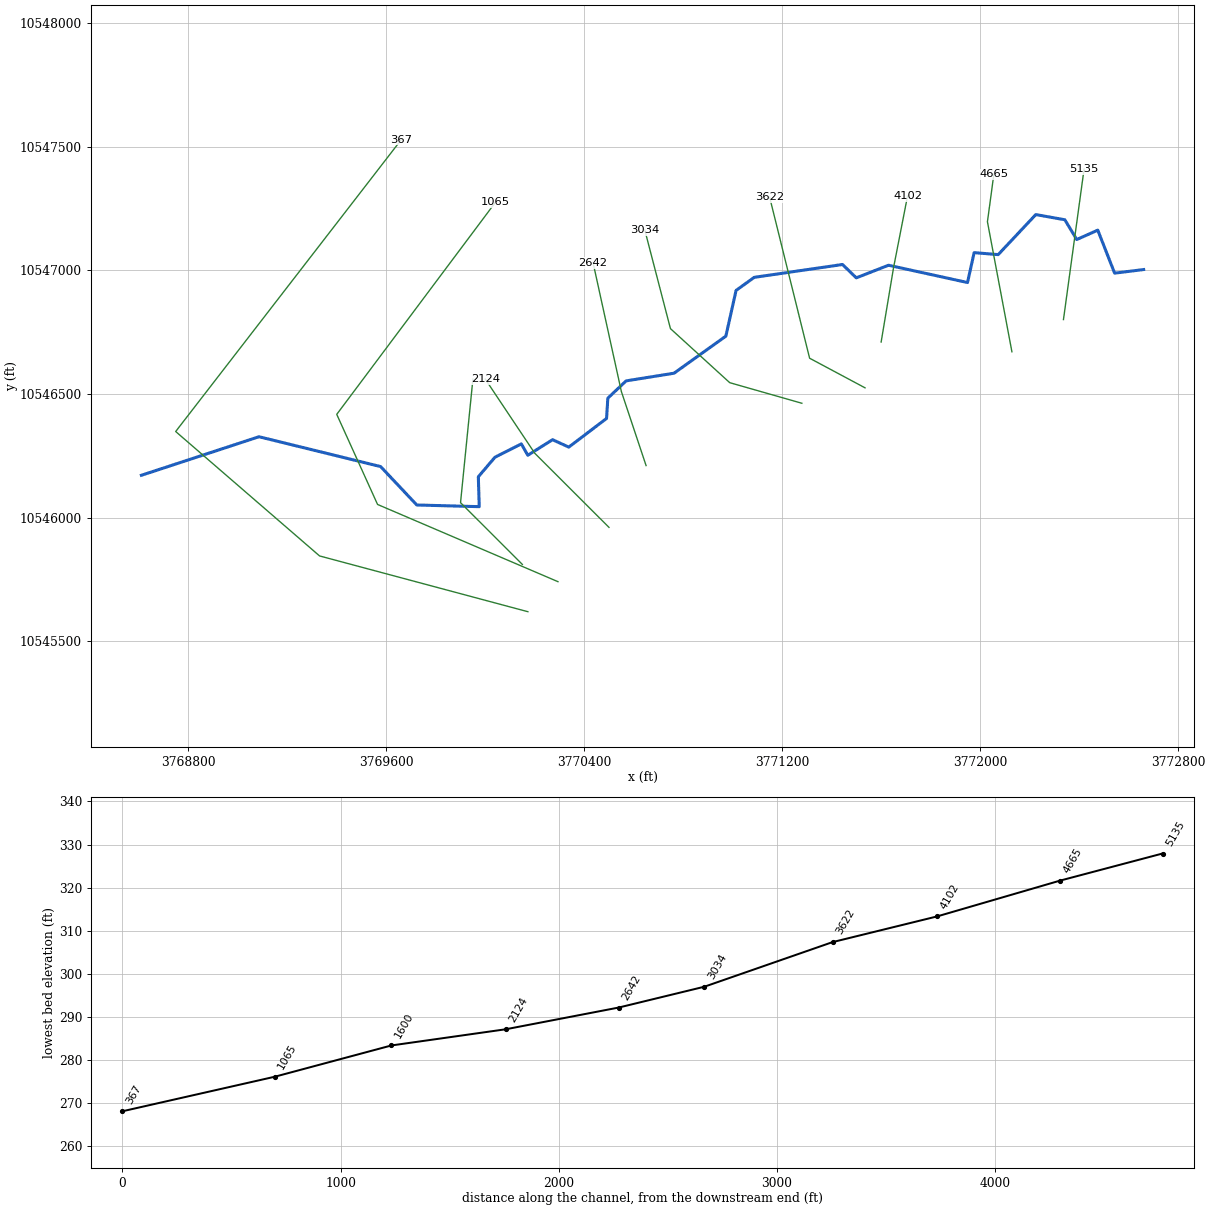
--- UNT152 IN BECR.prj (project) ---

Proj Title=UNT152 IN BECR Base Level Engineering
Current Plan=p01
Default Exp/Contr=0.3,0.1
English Units
Geom File=g01
Flow File=f01
Plan File=p01
BEGIN DESCRIPTION:
UNT152 IN BECR
END DESCRIPTION:

--- UNT152 IN BECR.p01 (plan) ---

Plan Title=Multiple Run
Short Identifier=Multiple
Geom File=g01
Flow File=f01
Subcritical Flow
K Sum by GR= 0
Std Step Tol= 0.01
Critical Tol= 0.01
Num of Std Step Trials= 20
Max Error Tol= 0.3
Flow Tol Ratio= 0.001
Split Flow NTrial= 30
Split Flow Tol= 0.02
Split Flow Ratio= 0.02
Log Output Level= 0
Friction Slope Method= 1
Unsteady Friction Slope Method= 2
Unsteady Bridges Friction Slope Method= 1
Parabolic Critical Depth
Global Vel Dist=  1 , 1 , 1
Global Log Level= 0
CheckData=True
Encroach Param= -1, 0, 0, 0
BEGIN DESCRIPTION:
Multiple Run
END DESCRIPTION:

--- UNT152 IN BECR.f01 (steady flow) ---

Flow Title=Multiple
Number of Profiles=7
Profile Names=10-year,25-year,50-year,1pct_min,100-year,1pct_plu,500-year
River Rch & RM= UNT152 IN BECR,Reach-1,5135
     601     821    1006     907    1226    1659    1828
Boundary for River Rch & Prof#=UNT152 IN BECR,Reach-1,1
Up Type=0
Dn Type=3
Dn Slope=0.005
Boundary for River Rch & Prof#=UNT152 IN BECR,Reach-1,2
Up Type=0
Dn Type=3
Dn Slope=0.005
Boundary for River Rch & Prof#=UNT152 IN BECR,Reach-1,3
Up Type=0
Dn Type=3
Dn Slope=0.005
Boundary for River Rch & Prof#=UNT152 IN BECR,Reach-1,4
Up Type=0
Dn Type=3
Dn Slope=0.005
Boundary for River Rch & Prof#=UNT152 IN BECR,Reach-1,5
Up Type=0
Dn Type=3
Dn Slope=0.005
Boundary for River Rch & Prof#=UNT152 IN BECR,Reach-1,6
Up Type=0
Dn Type=3
Dn Slope=0.005
Boundary for River Rch & Prof#=UNT152 IN BECR,Reach-1,7
Up Type=0
Dn Type=3
Dn Slope=0.005

--- UNT152 IN BECR.g01 (geometry) ---

Geom Title=Existing Conditions

River Reach=UNT152 IN BECR,Reach-1
Reach XY= 30
      3772660.69     10547003.56      3772543.25     10546989.00
      3772475.25     10547163.00      3772390.25     10547125.00
      3772342.00     10547205.00      3772224.75     10547226.00
      3772072.75     10547064.00      3771975.50     10547072.00
      3771948.75     10546951.00      3771629.50     10547021.00
      3771499.25     10546970.00      3771443.50     10547024.00
      3771086.75     10546972.00      3771013.25     10546919.00
      3770972.00     10546734.00      3770762.50     10546584.00
      3770568.75     10546553.00      3770495.00     10546483.00
      3770489.75     10546401.00      3770337.25     10546285.00
      3770271.50     10546315.00      3770171.50     10546252.00
      3770145.50     10546298.00      3770038.75     10546244.00
      3769971.50     10546165.00      3769975.25     10546044.00
      3769722.92     10546050.75      3769576.62     10546206.19
      3769085.00     10546327.00      3768609.75     10546171.00

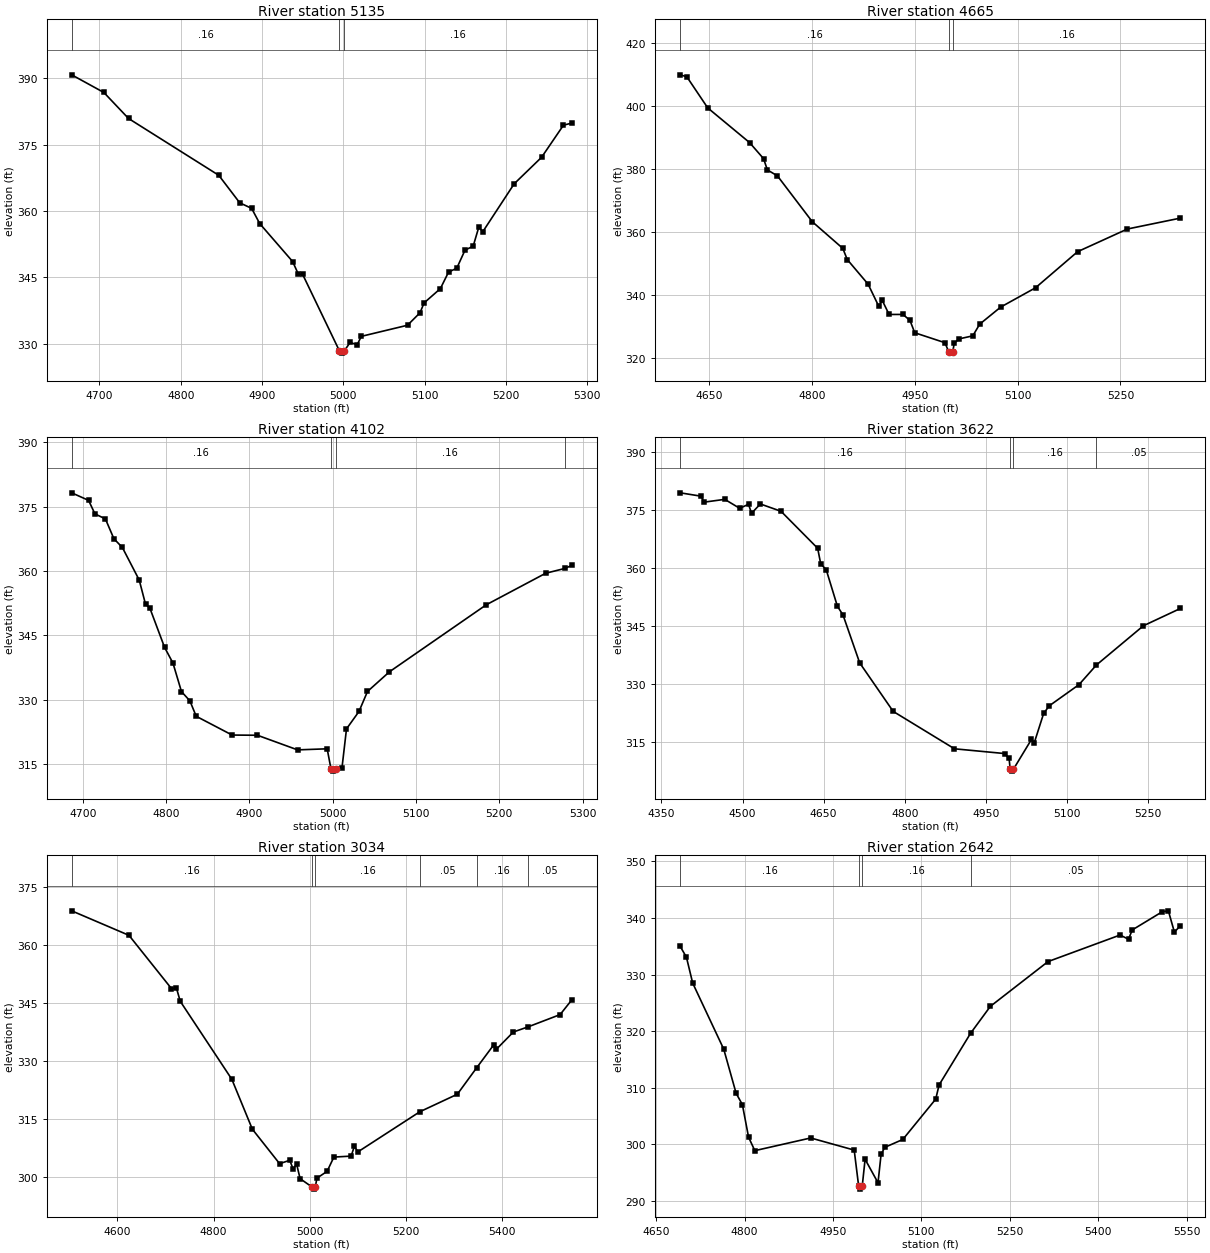
Type RM Length L Ch R = 1,5135,470,470,470
BEGIN DESCRIPTION:
UNT152 IN BECR 9.0
END DESCRIPTION:
XS GIS Cut Line= 2
      3772336.53     10546800.97      3772419.88     10547410.40
#Sta/Elev= 30
  4665.9  390.79  4705.5  386.80  4735.8  380.93  4846.8  368.09  4872.6  361.87
  4887.2  360.62  4897.2  357.17  4937.6  348.61  4944.8  345.70  4949.8  345.76
  4995.2  328.41  4997.9  327.91  5001.2  328.41  5008.3  330.33  5017.0  329.80
  5022.1  331.70  5078.9  334.21  5094.3  337.03  5099.3  339.26  5119.3  342.48
  5129.4  346.22  5139.5  347.10  5149.6  351.17  5159.7  352.09  5166.5  356.33
  5171.6  355.37  5210.1  366.17  5243.8  372.16  5270.7  379.41  5281.0  379.89
#Mann=3,-1,0
  4665.9    0.16       0  4995.2    0.07       0  5001.2    0.16       0
Bank Sta=4995.2,5001.2
Exp/Cntr=0.3,0.1

Type RM Length L Ch R = 1,4665,563,563,563
BEGIN DESCRIPTION:
UNT152 IN BECR 8.0
END DESCRIPTION:
XS GIS Cut Line= 3
      3772128.20     10546670.79      3772029.25     10547196.82
      3772055.28     10547389.51
#Sta/Elev= 30
  4607.8  409.87  4617.4  409.25  4647.9  399.38  4708.9  388.39  4729.3  383.30
  4734.9  379.72  4749.6  377.82  4800.5  363.27  4845.0  354.82  4851.4  351.30
  4881.9  343.47  4897.4  336.47  4902.5  338.33  4912.5  333.87  4932.8  333.88
  4943.0  331.96  4949.9  328.07  4993.9  324.92  4999.4  322.11  5002.2  321.61
  5005.4  322.11  5007.5  324.68  5014.2  326.11  5034.6  327.09  5044.7  330.80
  5075.3  336.21  5126.1  342.33  5187.5  353.78  5260.1  360.97  5337.5  364.43
#Mann=3,-1,0
  4607.8    0.16       0  4999.4    0.07       0  5005.4    0.16       0
Bank Sta=4999.4,5005.4
Exp/Cntr=0.3,0.1

Type RM Length L Ch R = 1,4102,480,480,480
BEGIN DESCRIPTION:
UNT152 IN BECR 7.0
END DESCRIPTION:
XS GIS Cut Line= 3
      3771599.61     10546710.20      3771649.61     10547010.19
      3771706.33     10547300.99
#Sta/Elev= 30
  4686.7  378.25  4707.0  376.49  4714.6  373.34  4727.2  372.16  4737.4  367.53
  4747.5  365.51  4767.8  357.89  4775.4  352.21  4780.5  351.37  4798.2  342.19
  4808.3  338.51  4818.5  331.86  4828.6  329.70  4836.2  326.10  4879.3  321.72
  4909.7  321.67  4957.9  318.26  4993.4  318.51  4998.0  313.80  5000.8  313.30
  5004.0  313.80  5011.2  314.09  5016.6  323.16  5031.6  327.23  5041.8  331.89
  5068.2  336.49  5184.4  352.12  5255.7  359.48  5278.4  360.59  5287.1  361.31
#Mann=4,-1,0
  4686.7    0.16       0  4998.0    0.07       0  5004.0    0.16       0
  5278.4    0.05       0
Bank Sta=4998,5004
Exp/Cntr=0.3,0.1

Type RM Length L Ch R = 1,3622,588,588,588
BEGIN DESCRIPTION:
UNT152 IN BECR 6.0
END DESCRIPTION:
XS GIS Cut Line= 3
      3771534.47     10546524.94      3771310.50     10546644.74
      3771149.10     10547295.53
#Sta/Elev= 30
  4384.9  379.50  4423.3  378.63  4429.0  377.08  4467.2  377.81  4494.8  375.48
  4511.1  376.53  4516.7  374.20  4533.0  376.61  4571.2  374.71  4638.9  365.12
  4644.5  361.12  4654.8  359.52  4675.4  350.07  4685.7  347.84  4716.6  335.39
  4778.5  322.81  4891.8  313.11  4984.5  311.88  4992.7  310.62  4994.8  307.82
  4997.6  307.32  5000.8  307.82  5034.1  315.54  5039.2  314.64  5056.6  322.28
  5066.9  324.25  5122.0  329.76  5154.2  334.85  5240.9  345.01  5309.4  349.51
#Mann=4,-1,0
  4384.9    0.16       0  4994.8    0.07       0  5000.8    0.16       0
  5154.2    0.05       0
Bank Sta=4994.8,5000.8
Exp/Cntr=0.3,0.1

Type RM Length L Ch R = 1,3034,392,392,392
BEGIN DESCRIPTION:
UNT152 IN BECR 5.0
END DESCRIPTION:
XS GIS Cut Line= 4
      3771279.21     10546462.46      3770987.58     10546545.78
      3770748.00     10546764.53      3770644.28     10547163.85
#Sta/Elev= 30
  4504.9  368.93  4624.1  362.59  4712.5  348.81  4722.9  348.92  4730.7  345.54
  4838.1  325.34  4880.7  312.45  4937.4  303.53  4958.4  304.41  4965.8  302.08
  4972.6  303.51  4980.0  299.66  5005.4  297.45  5008.1  296.95  5011.4  297.45
  5015.1  299.80  5036.1  301.54  5050.3  305.24  5086.1  305.49  5092.9  308.01
  5100.3  306.59  5229.0  316.96  5307.1  321.50  5347.1  328.31  5383.0  334.31
  5388.2  333.12  5423.6  337.59  5454.0  338.91  5520.8  342.09  5545.2  345.91
#Mann=6,-1,0
  4504.9    0.16       0  5005.4    0.07       0  5011.4    0.16       0
  5229.0    0.05       0  5347.1    0.16       0  5454.0    0.05       0
Bank Sta=5005.4,5011.4
Exp/Cntr=0.3,0.1

Type RM Length L Ch R = 1,2642,518,518,518
BEGIN DESCRIPTION:
UNT152 IN BECR 4.0
END DESCRIPTION:
XS GIS Cut Line= 3
      3770649.60     10546210.21      3770549.61     10546510.19
      3770435.51     10547030.11
#Sta/Elev= 30
  4690.9  334.95  4701.4  333.05  4712.0  328.49  4764.7  316.82  4785.7  309.03
  4796.3  307.04  4806.8  301.29  4817.4  298.91  4912.2  301.15  4986.0  299.01
  4993.6  292.62  4996.3  292.12  4999.6  292.62  5004.5  297.39  5026.4  293.24
  5031.6  298.25  5037.8  299.49  5068.5  300.89  5124.3  308.01  5130.0  310.51
  5183.4  319.62  5217.0  324.38  5314.8  332.28  5437.1  336.97  5451.4  336.22
  5457.6  337.86  5508.8  341.09  5519.0  341.24  5529.2  337.48  5539.4  338.63
#Mann=4,-1,0
  4690.9    0.16       0  4993.6    0.07       0  4999.6    0.16       0
  5183.4    0.05       0
Bank Sta=4993.6,4999.6
Exp/Cntr=0.3,0.1

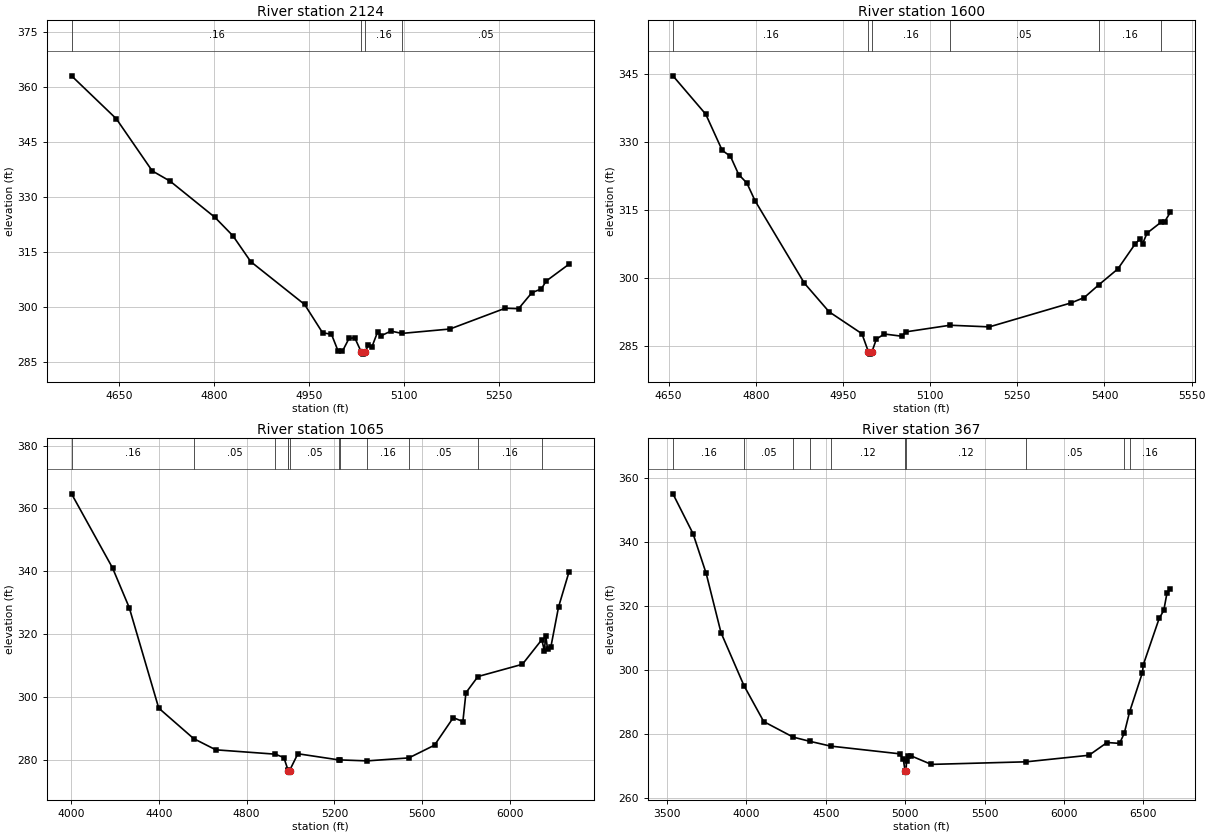
Type RM Length L Ch R = 1,2124,524,524,524
BEGIN DESCRIPTION:
UNT152 IN BECR 3.0
END DESCRIPTION:
XS GIS Cut Line= 3
      3770499.61     10545960.19      3770199.61     10546260.19
      3769999.62     10546560.18
#Sta/Elev= 30
  4575.1  362.97  4645.8  351.24  4702.4  337.04  4730.7  334.23  4801.4  324.36
  4829.7  319.34  4857.9  312.28  4942.8  300.61  4971.1  292.91  4985.2  292.47
  4995.8  287.84  5002.4  287.84  5012.9  291.37  5021.9  291.53  5032.4  287.57
  5035.2  287.07  5038.4  287.57  5042.9  289.43  5048.9  289.01  5057.9  293.09
  5064.0  292.12  5079.0  293.36  5096.2  292.72  5172.1  293.92  5259.3  299.59
  5280.3  299.46  5301.3  303.82  5316.3  304.86  5323.9  307.00  5359.9  311.60
#Mann=4,-1,0
  4575.1    0.16       0  5032.4    0.07       0  5038.4    0.16       0
  5096.2    0.05       0
Bank Sta=5032.4,5038.4
Exp/Cntr=0.3,0.1

Type RM Length L Ch R = 1,1600,535,535,535
BEGIN DESCRIPTION:
UNT152 IN BECR 2.0
END DESCRIPTION:
XS GIS Cut Line= 3
      3770149.59     10545810.21      3769899.61     10546060.19
      3769949.61     10546560.17
#Sta/Elev= 30
  4657.4  344.68  4713.9  336.21  4742.2  328.24  4756.4  326.93  4770.5  322.92
  4784.6  321.04  4798.8  317.11  4883.6  298.95  4926.1  292.65  4982.6  287.81
  4993.8  283.81  4996.5  283.31  4999.8  283.81  5007.4  286.61  5021.0  287.75
  5051.1  287.26  5058.7  288.23  5134.2  289.68  5201.9  289.32  5342.6  294.61
  5365.2  295.79  5389.8  298.55  5423.0  302.10  5453.1  307.67  5460.7  308.63
  5465.7  307.69  5473.2  309.99  5497.3  312.40  5503.4  312.50  5513.4  314.60
#Mann=6,-1,0
  4657.4    0.16       0  4993.8    0.07       0  4999.8    0.16       0
  5134.2    0.05       0  5389.8    0.16       0  5497.3    0.05       0
Bank Sta=4993.8,4999.8
Exp/Cntr=0.3,0.1

Type RM Length L Ch R = 1,1065,698,698,698
BEGIN DESCRIPTION:
Mapping XS ddb53ae4
END DESCRIPTION:
XS GIS Cut Line= 4
      3770293.36     10545740.47      3769564.22     10546052.96
      3769399.29     10546417.54      3770041.02     10547276.07
#Sta/Elev= 30
  4002.7  364.63  4189.3  341.06  4265.5  328.40  4399.7  296.42  4558.6  286.72
  4659.6  283.14  4929.9  281.76  4969.5  280.68  4988.7  276.65  4989.6  276.54
  4992.3  276.04  4995.6  276.54  5033.3  281.89  5222.8  279.90  5224.6  279.93
  5348.9  279.62  5538.8  280.57  5655.6  284.62  5741.0  293.38  5784.8  292.15
  5798.7  301.31  5853.4  306.47  6055.8  310.37  6144.2  318.20  6155.8  314.67
  6162.0  319.49  6170.4  315.19  6185.0  315.73  6220.4  328.61  6268.0  339.77
#Mann=12,-1,0
  4002.7    0.16       0  4558.6    0.05       0  4929.9    0.12       0
  4988.7    0.05       0  4989.6    0.03       0  4995.6    0.05       0
  5222.8    0.16       0  5224.6    0.05       0  5348.9    0.16       0
  5538.8    0.05       0  5853.4    0.16       0  6144.2    0.05       0
Bank Sta=4989.6,4995.6
Exp/Cntr=0.3,0.1

Type RM Length L Ch R = 1,367,0,0,0
BEGIN DESCRIPTION:
UNT152 IN BECR 1.0
END DESCRIPTION:
XS GIS Cut Line= 4
      3770171.88     10545618.92      3769329.84     10545844.62
      3768748.25     10546348.10      3769659.72     10547528.67
#Sta/Elev= 30
  3537.8  355.14  3664.4  342.67  3747.2  330.21  3840.4  311.70  3984.9  295.12
  4109.6  283.84  4295.2  278.97  4398.6  277.68  4530.5  276.17  4966.2  273.75
  4988.1  272.09  4999.4  268.52  5002.1  268.02  5005.4  268.52  5009.0  271.43
  5016.6  273.00  5037.5  273.11  5164.7  270.44  5762.7  271.25  6157.6  273.30
  6271.7  277.29  6350.5  277.02  6380.0  280.21  6413.2  286.85  6493.7  299.10
  6500.0  301.68  6599.6  316.13  6628.6  318.64  6649.4  324.24  6670.3  325.24
#Mann=10,-1,0
  3537.8    0.16       0  3984.9    0.05       0  4295.2    0.12       0
  4398.6    0.16       0  4530.5    0.12       0  4999.4    0.07       0
  5005.4    0.12       0  5762.7    0.05       0  6380.0    0.12       0
  6413.2    0.16       0
Bank Sta=4999.4,5005.4
Exp/Cntr=0.3,0.1

Chan Stop Cuts=-1