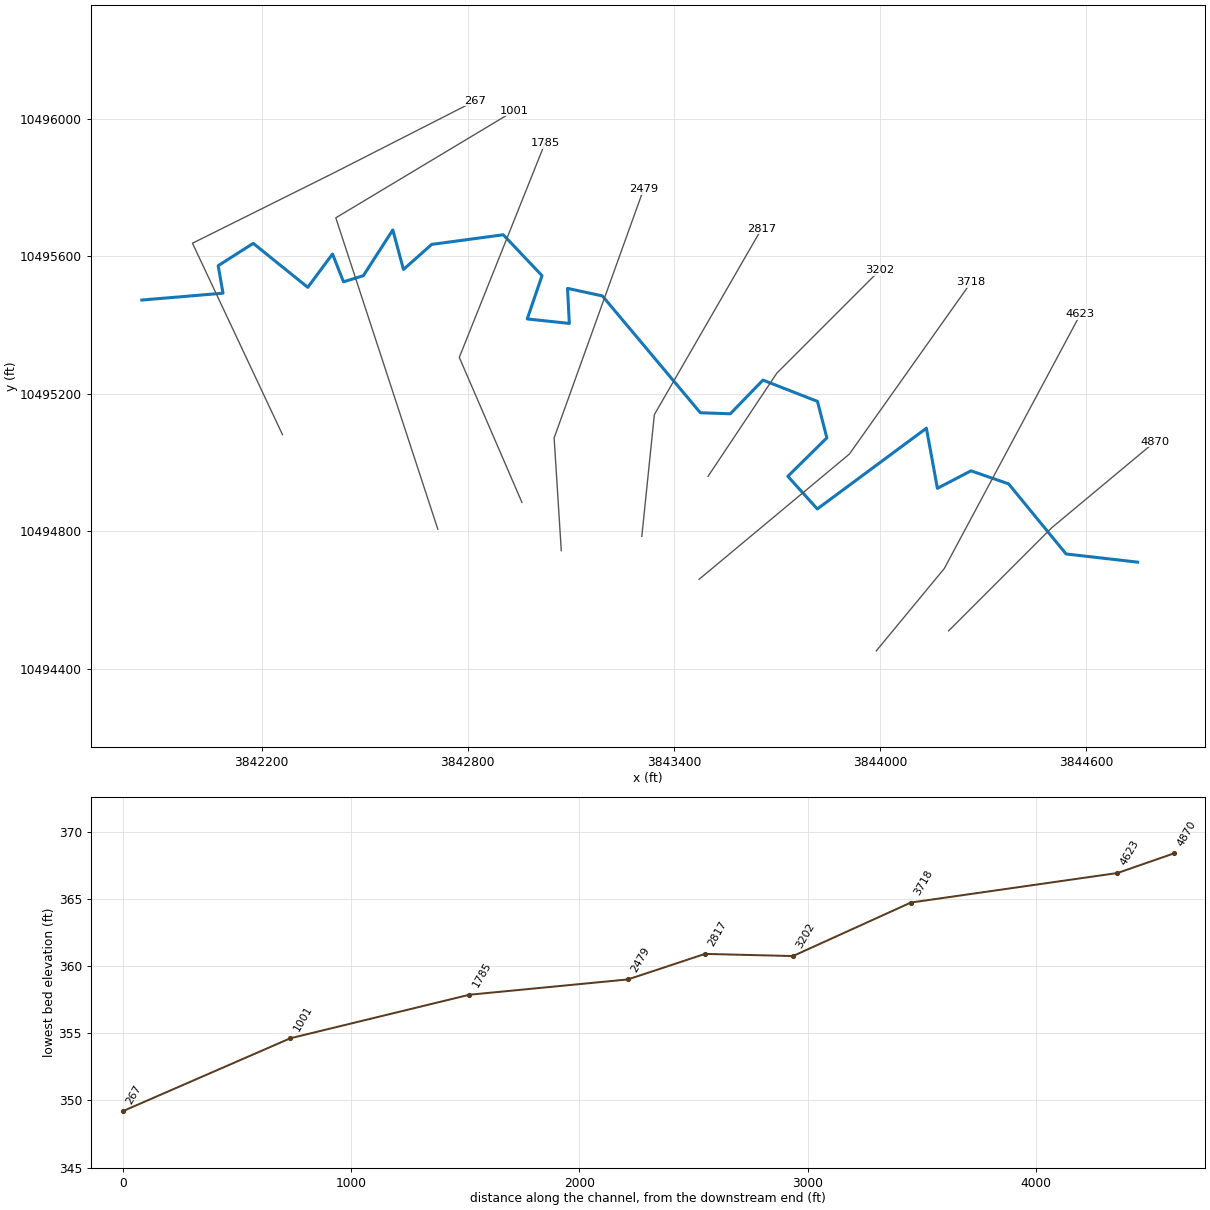
--- UNT154 IN BECR.prj (project) ---

Proj Title=UNT154 IN BECR Base Level Engineering
Current Plan=p01
Default Exp/Contr=0.3,0.1
English Units
Geom File=g01
Flow File=f01
Plan File=p01
BEGIN DESCRIPTION:
UNT154 IN BECR
END DESCRIPTION:

--- UNT154 IN BECR.p01 (plan) ---

Plan Title=Multiple Run
Short Identifier=Multiple
Geom File=g01
Flow File=f01
Subcritical Flow
K Sum by GR= 0
Std Step Tol= 0.01
Critical Tol= 0.01
Num of Std Step Trials= 20
Max Error Tol= 0.3
Flow Tol Ratio= 0.001
Split Flow NTrial= 30
Split Flow Tol= 0.02
Split Flow Ratio= 0.02
Log Output Level= 0
Friction Slope Method= 1
Unsteady Friction Slope Method= 2
Unsteady Bridges Friction Slope Method= 1
Parabolic Critical Depth
Global Vel Dist=  1 , 1 , 1
Global Log Level= 0
CheckData=True
Encroach Param= -1, 0, 0, 0
BEGIN DESCRIPTION:
Multiple Run
END DESCRIPTION:

--- UNT154 IN BECR.f01 (steady flow) ---

Flow Title=Multiple
Number of Profiles=7
Profile Names=10-year,25-year,50-year,1pct_min,100-year,1pct_plu,500-year
River Rch & RM= UNT154 IN BECR,Reach-1,4870
     399     522     621     543     734     993    1030
Boundary for River Rch & Prof#=UNT154 IN BECR,Reach-1,1
Up Type=0
Dn Type=3
Dn Slope=0.005
Boundary for River Rch & Prof#=UNT154 IN BECR,Reach-1,2
Up Type=0
Dn Type=3
Dn Slope=0.005
Boundary for River Rch & Prof#=UNT154 IN BECR,Reach-1,3
Up Type=0
Dn Type=3
Dn Slope=0.005
Boundary for River Rch & Prof#=UNT154 IN BECR,Reach-1,4
Up Type=0
Dn Type=3
Dn Slope=0.005
Boundary for River Rch & Prof#=UNT154 IN BECR,Reach-1,5
Up Type=0
Dn Type=3
Dn Slope=0.005
Boundary for River Rch & Prof#=UNT154 IN BECR,Reach-1,6
Up Type=0
Dn Type=3
Dn Slope=0.005
Boundary for River Rch & Prof#=UNT154 IN BECR,Reach-1,7
Up Type=0
Dn Type=3
Dn Slope=0.005

--- UNT154 IN BECR.g01 (geometry) ---

Geom Title=Existing Conditions

River Reach=UNT154 IN BECR,Reach-1
Reach XY= 30
      3844749.61     10494710.19      3844541.50     10494734.00
      3844374.25     10494938.00      3844264.75     10494976.00
      3844167.00     10494925.00      3844135.00     10495100.00
      3843817.50     10494865.00      3843731.75     10494960.00
      3843845.25     10495072.00      3843818.00     10495178.00
      3843659.25     10495240.00      3843564.25     10495142.00
      3843477.00     10495145.00      3843192.00     10495485.00
      3843090.50     10495507.00      3843095.75     10495405.00
      3842973.25     10495418.00      3843016.25     10495544.00
      3842903.50     10495663.00      3842695.25     10495635.00
      3842613.00     10495562.00      3842582.00     10495677.00
      3842496.25     10495544.00      3842438.50     10495526.00
      3842406.50     10495607.00      3842334.50     10495510.00
      3842175.75     10495638.00      3842073.75     10495573.00
      3842087.75     10495493.00      3841851.50     10495473.00

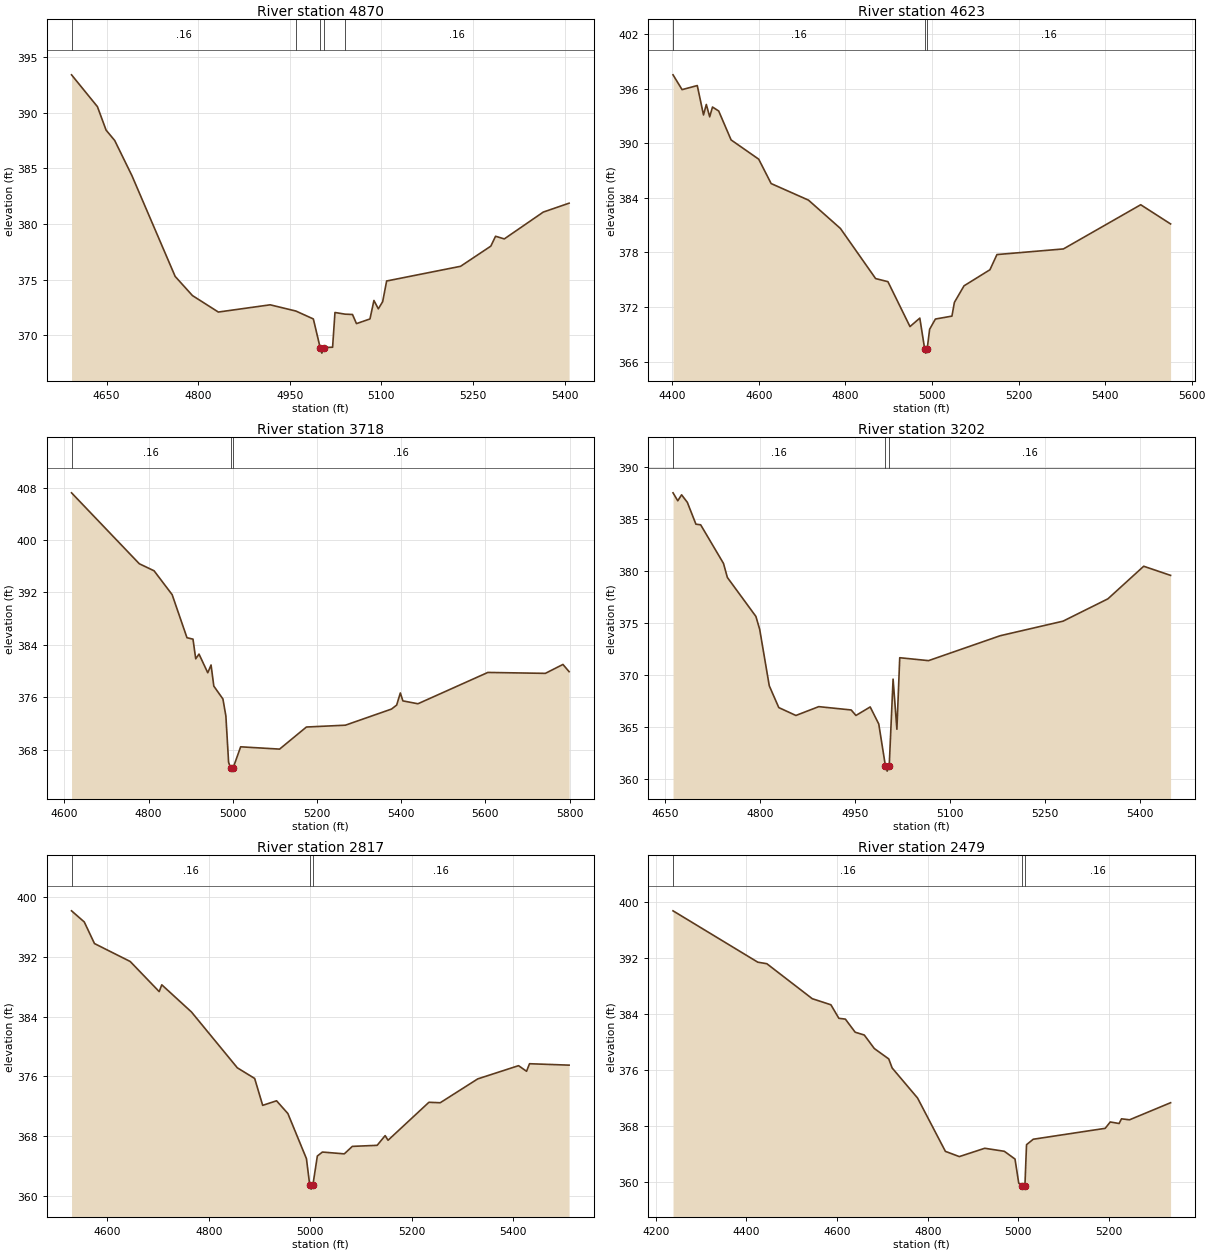
Type RM Length L Ch R = 1,4870,247,247,247
BEGIN DESCRIPTION:
UNT154 IN BECR 6.0
END DESCRIPTION:
XS GIS Cut Line= 3
      3844199.61     10494510.19      3844499.61     10494810.19
      3844799.63     10495060.21
#Sta/Elev= 30
  4592.7  393.39  4635.1  390.53  4649.3  388.42  4663.4  387.49  4691.7  384.32
  4762.4  375.28  4790.7  373.56  4833.1  372.08  4918.0  372.73  4960.1  372.17
  4988.7  371.46  4999.8  368.89  5002.6  368.39  5005.8  368.89  5020.2  368.92
  5024.1  372.04  5040.7  371.89  5052.8  371.86  5059.3  371.04  5081.4  371.46
  5087.9  373.12  5095.1  372.37  5102.2  373.01  5108.7  374.87  5229.8  376.19
  5279.3  378.00  5287.1  378.89  5301.4  378.65  5365.2  381.06  5407.5  381.86
#Mann=5,-1,0
  4592.7    0.16       0  4960.1    0.12       0  4999.8    0.07       0
  5005.8    0.12       0  5040.7    0.16       0
Bank Sta=4999.8,5005.8
Exp/Cntr=0.3,0.1

Type RM Length L Ch R = 1,4623,905,905,905
BEGIN DESCRIPTION:
UNT154 IN BECR 5.0
END DESCRIPTION:
XS GIS Cut Line= 3
      3843989.01     10494451.88      3844186.94     10494691.47
      3844582.76     10495431.04
#Sta/Elev= 30
  4401.7  397.54  4422.6  395.91  4457.7  396.36  4472.1  393.13  4478.6  394.28
  4486.4  392.92  4492.9  394.00  4507.2  393.56  4535.9  390.38  4599.7  388.26
  4628.4  385.58  4714.6  383.76  4788.5  380.64  4869.8  375.13  4898.2  374.79
  4949.2  369.85  4971.9  370.78  4983.0  367.43  4985.7  366.93  4989.0  367.43
  4994.6  369.56  5007.9  370.68  5046.1  371.00  5051.8  372.51  5074.0  374.33
  5133.9  376.10  5150.1  377.77  5303.7  378.39  5482.3  383.25  5551.3  381.14
#Mann=3,-1,0
  4401.7    0.16       0  4983.0    0.07       0  4989.0    0.16       0
Bank Sta=4983,4989
Exp/Cntr=0.3,0.1

Type RM Length L Ch R = 1,3718,516,516,516
BEGIN DESCRIPTION:
UNT154 IN BECR 4.0
END DESCRIPTION:
XS GIS Cut Line= 3
      3843473.36     10494660.19      3843910.89     10495024.81
      3844264.85     10495524.50
#Sta/Elev= 30
  4617.1  407.20  4778.0  396.38  4813.2  395.30  4856.1  391.66  4891.3  385.09
  4905.6  384.87  4912.1  381.87  4919.9  382.59  4940.7  379.74  4948.5  380.93
  4955.1  377.70  4976.7  375.74  4983.7  373.15  4990.2  366.07  4995.0  365.23
  4997.8  364.73  5001.0  365.23  5018.8  368.44  5111.3  368.09  5175.0  371.46
  5267.6  371.74  5377.1  374.20  5389.4  374.81  5398.1  376.66  5404.2  375.45
  5439.9  375.01  5606.0  379.79  5742.6  379.65  5784.4  381.01  5799.0  379.91
#Mann=3,-1,0
  4617.1    0.16       0  4995.0    0.07       0  5001.0    0.16       0
Bank Sta=4995,5001
Exp/Cntr=0.3,0.1

Type RM Length L Ch R = 1,3202,385,385,385
BEGIN DESCRIPTION:
UNT154 IN BECR 3.0
END DESCRIPTION:
XS GIS Cut Line= 3
      3843499.59     10494960.17      3843699.61     10495260.19
      3843999.58     10495560.16
#Sta/Elev= 30
  4662.9  387.55  4670.4  386.78  4676.4  387.36  4685.5  386.63  4699.0  384.53
  4706.5  384.47  4742.5  380.75  4748.6  379.40  4793.6  375.65  4799.6  374.40
  4814.7  368.97  4829.7  366.87  4856.7  366.11  4892.8  366.96  4943.9  366.64
  4951.4  366.11  4973.9  366.93  4987.4  365.29  4997.9  361.25  5000.7  360.75
  5003.9  361.25  5010.0  369.61  5016.0  364.78  5020.5  371.67  5065.9  371.39
  5179.0  373.79  5278.0  375.19  5348.8  377.34  5405.3  380.48  5447.7  379.60
#Mann=3,-1,0
  4662.9    0.16       0  4997.9    0.07       0  5003.9    0.16       0
Bank Sta=4997.9,5003.9
Exp/Cntr=0.3,0.1

Type RM Length L Ch R = 1,2817,338,338,338
BEGIN DESCRIPTION:
UNT154 IN BECR 2.0
END DESCRIPTION:
XS GIS Cut Line= 3
      3843306.73     10494785.23      3843343.19     10495139.39
      3843655.15     10495680.12
#Sta/Elev= 30
  4529.6  398.15  4554.7  396.66  4574.8  393.77  4645.2  391.37  4702.3  387.34
  4707.4  388.25  4765.8  384.62  4856.3  377.14  4890.4  375.72  4906.2  372.12
  4933.5  372.73  4955.8  371.03  4992.4  364.99  4999.0  361.41  5001.8  360.91
  5005.0  361.41  5013.9  365.34  5023.9  365.87  5067.0  365.63  5082.8  366.63
  5131.7  366.77  5147.5  368.07  5153.2  367.45  5233.7  372.53  5256.0  372.47
  5329.9  375.66  5410.3  377.43  5426.1  376.68  5431.9  377.69  5509.9  377.50
#Mann=3,-1,0
  4529.6    0.16       0  4999.0    0.07       0  5005.0    0.16       0
Bank Sta=4999,5005
Exp/Cntr=0.3,0.1

Type RM Length L Ch R = 1,2479,694,694,694
BEGIN DESCRIPTION:
Mapping XS 3076a1b9
END DESCRIPTION:
XS GIS Cut Line= 3
      3843072.35     10494743.57      3843051.52     10495071.68
      3843311.85     10495795.41
#Sta/Elev= 30
  4237.9  398.79  4424.9  391.45  4444.9  391.23  4545.1  386.23  4586.3  385.36
  4603.8  383.43  4618.2  383.31  4639.8  381.44  4659.9  381.04  4682.0  379.11
  4713.9  377.62  4721.4  376.33  4777.5  372.03  4838.9  364.41  4869.6  363.66
  4925.7  364.85  4968.9  364.42  4992.5  363.31  5000.8  359.85  5008.4  359.51
  5011.2  359.01  5014.4  359.51  5017.9  365.36  5032.7  366.14  5191.5  367.70
  5202.7  368.61  5222.2  368.39  5227.5  369.06  5245.2  368.92  5335.8  371.36
#Mann=3,-1,0
  4237.9    0.16       0  5008.4    0.07       0  5014.4    0.16       0
Bank Sta=5008.4,5014.4
Exp/Cntr=0.3,0.1

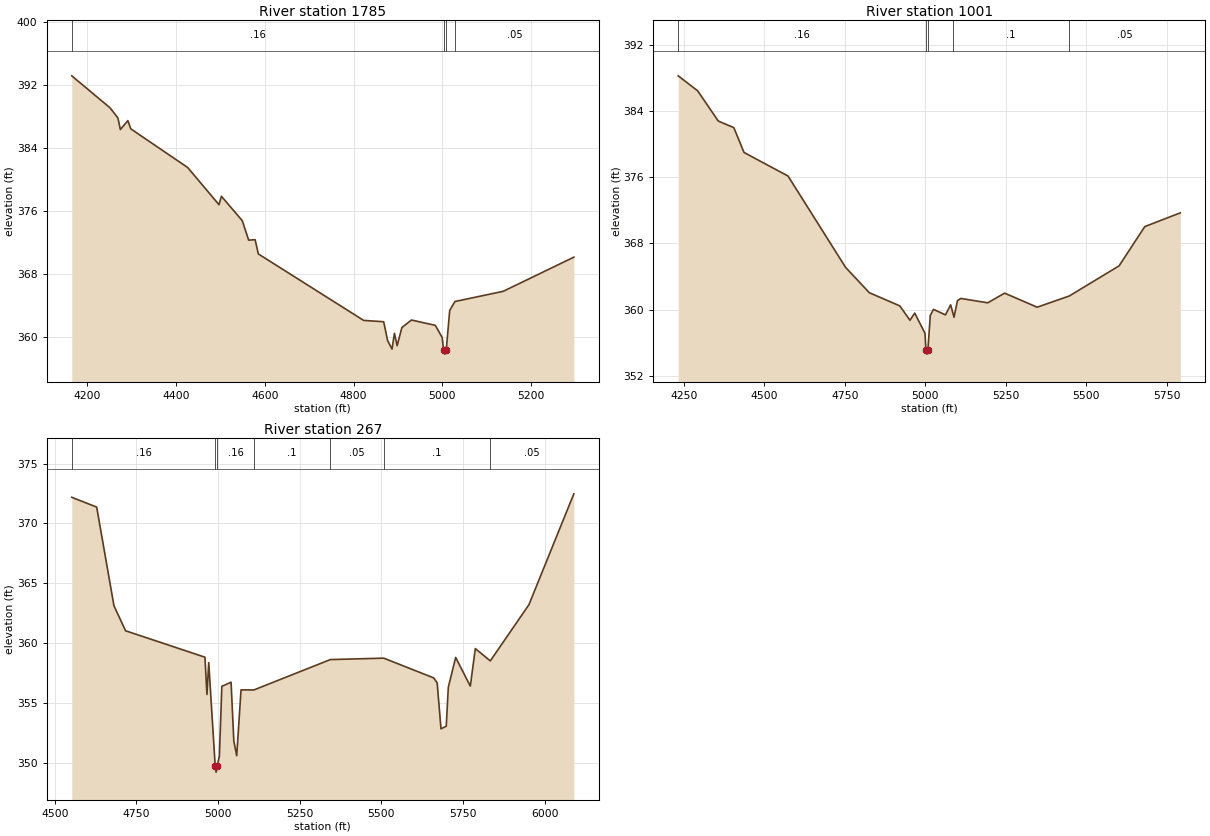
Type RM Length L Ch R = 1,1785,784,784,784
BEGIN DESCRIPTION:
Mapping XS 164ceb78
END DESCRIPTION:
XS GIS Cut Line= 3
      3842957.78     10494884.15      3842775.48     10495306.06
      3843025.05     10495929.99
#Sta/Elev= 30
  4164.7  393.20  4250.7  389.15  4268.7  387.86  4274.2  386.38  4291.1  387.51
  4297.7  386.47  4426.0  381.56  4496.5  376.84  4502.0  377.91  4549.0  374.81
  4563.4  372.34  4577.9  372.40  4585.2  370.59  4822.6  362.15  4867.7  361.98
  4876.5  359.61  4886.5  358.51  4891.9  360.51  4898.0  358.94  4908.8  361.25
  4930.3  362.20  4984.2  361.52  4999.6  359.98  5002.7  358.37  5005.5  357.87
  5008.7  358.37  5016.5  363.41  5028.3  364.55  5137.0  365.84  5296.3  370.18
#Mann=4,-1,0
  4164.7    0.16       0  5002.7    0.07       0  5008.7    0.16       0
  5028.3    0.05       0
Bank Sta=5002.7,5008.7
Exp/Cntr=0.3,0.1

Type RM Length L Ch R = 1,1001,734,734,734
BEGIN DESCRIPTION:
UNT154 IN BECR 1.0
END DESCRIPTION:
XS GIS Cut Line= 3
      3842712.97     10494806.08      3842416.10     10495712.31
      3842935.73     10496024.08
#Sta/Elev= 30
  4232.2  388.26  4292.8  386.44  4356.5  382.80  4404.9  382.00  4436.5  379.00
  4573.3  376.15  4752.1  365.11  4825.8  362.05  4920.5  360.46  4952.1  358.72
  4966.8  359.59  4998.7  357.15  5001.7  355.13  5004.4  354.63  5007.7  355.13
  5015.2  359.31  5025.2  360.04  5062.3  359.37  5078.4  360.59  5084.2  359.76
  5088.9  359.09  5099.5  361.09  5109.9  361.36  5193.6  360.83  5246.1  362.00
  5347.1  360.30  5447.2  361.66  5601.7  365.30  5681.4  370.04  5791.8  371.70
#Mann=5,-1,0
  4232.2    0.16       0  5001.7    0.07       0  5007.7    0.16       0
  5084.2     0.1       0  5447.2    0.05       0
Bank Sta=5001.7,5007.7
Exp/Cntr=0.3,0.1

Type RM Length L Ch R = 1,267,0,0,0
BEGIN DESCRIPTION:
Mapping XS be269f37
END DESCRIPTION:
XS GIS Cut Line= 4
      3842260.96     10495081.12      3841998.95     10495638.38
      3842411.50     10495843.68      3842822.08     10496052.88
#Sta/Elev= 30
  4552.0  372.18  4628.3  371.36  4681.2  363.11  4716.7  361.02  4959.8  358.81
  4965.9  355.69  4971.4  358.36  4991.2  349.70  4994.0  349.20  4997.2  349.70
  5004.0  350.54  5011.5  356.37  5039.8  356.72  5048.2  351.81  5057.1  350.57
  5070.3  356.08  5109.6  356.07  5343.8  358.61  5507.4  358.73  5660.1  357.08
  5670.9  356.67  5682.6  352.82  5698.7  353.04  5705.0  356.29  5727.5  358.79
  5772.4  356.39  5787.7  359.53  5833.6  358.50  5951.9  363.20  6089.4  372.47
#Mann=7,-1,0
  4552.0    0.16       0  4991.2    0.07       0  4997.2    0.16       0
  5109.6     0.1       0  5343.8    0.05       0  5507.4     0.1       0
  5833.6    0.05       0
Bank Sta=4991.2,4997.2
Exp/Cntr=0.3,0.1

Chan Stop Cuts=-1