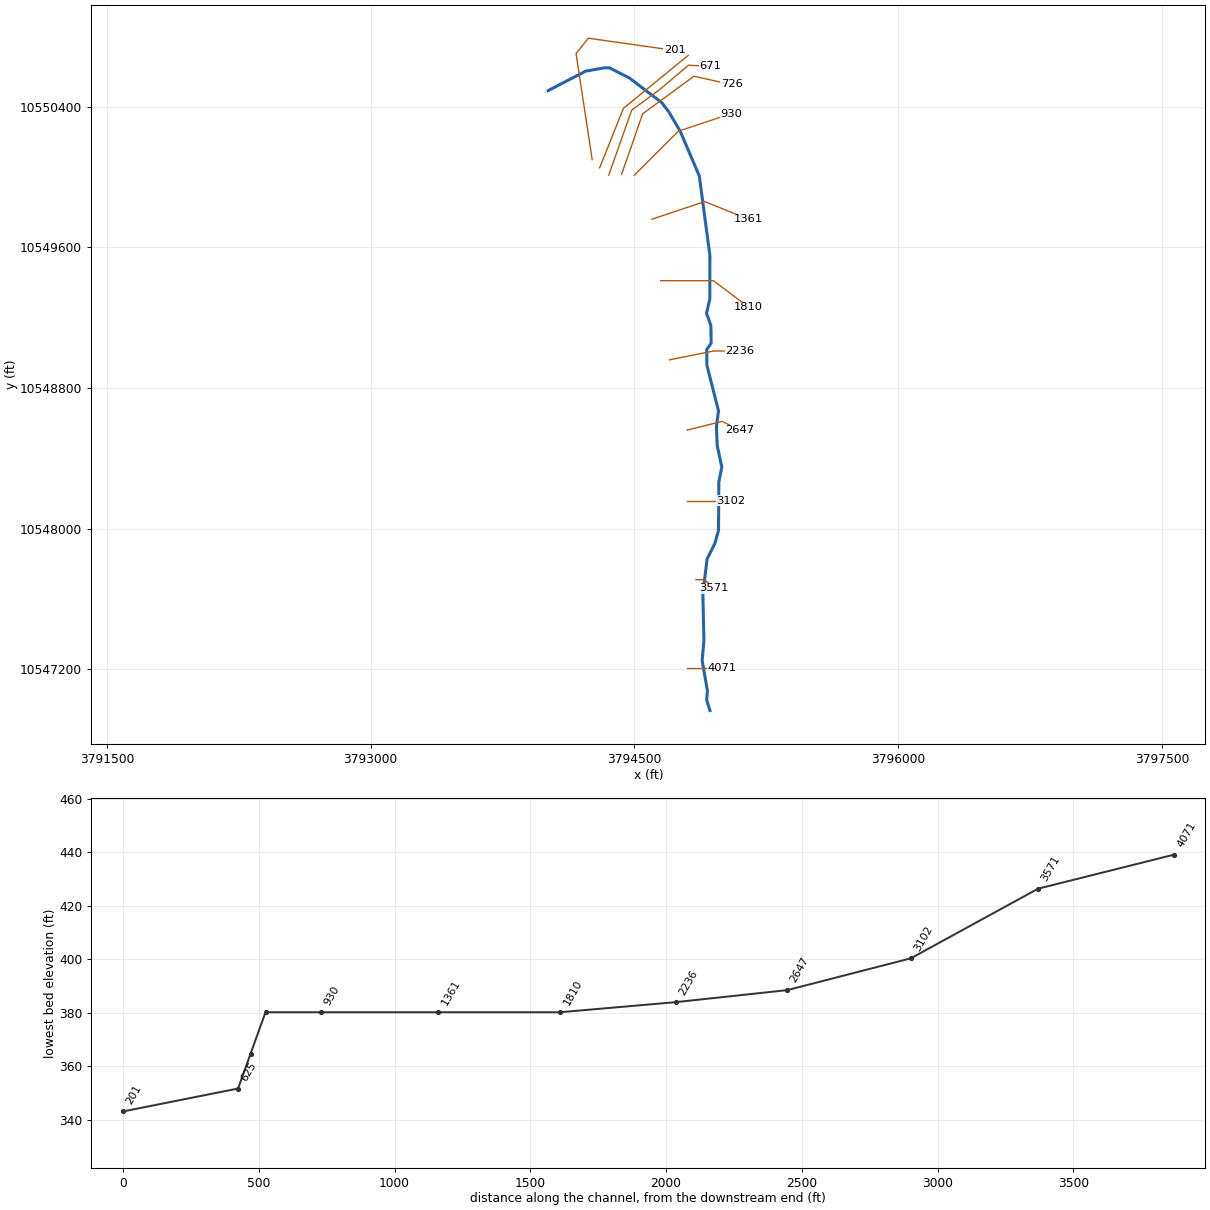
--- UNT155 IN BECR.prj (project) ---

Proj Title=UNT155 IN BECR Base Level Engineering
Current Plan=p01
Default Exp/Contr=0.3,0.1
English Units
Geom File=g01
Flow File=f01
Plan File=p01
BEGIN DESCRIPTION:
UNT155 IN BECR
END DESCRIPTION:

--- UNT155 IN BECR.p01 (plan) ---

Plan Title=Multiple Run
Short Identifier=Multiple
Geom File=g01
Flow File=f01
Subcritical Flow
K Sum by GR= 0
Std Step Tol= 0.01
Critical Tol= 0.01
Num of Std Step Trials= 20
Max Error Tol= 0.3
Flow Tol Ratio= 0.001
Split Flow NTrial= 30
Split Flow Tol= 0.02
Split Flow Ratio= 0.02
Log Output Level= 0
Friction Slope Method= 1
Unsteady Friction Slope Method= 2
Unsteady Bridges Friction Slope Method= 1
Parabolic Critical Depth
Global Vel Dist=  1 , 1 , 1
Global Log Level= 0
CheckData=True
Encroach Param= -1, 0, 0, 0
BEGIN DESCRIPTION:
Multiple Run
END DESCRIPTION:

--- UNT155 IN BECR.f01 (steady flow) ---

Flow Title=Multiple
Number of Profiles=7
Profile Names=10-year,25-year,50-year,1pct_min,100-year,1pct_plu,500-year
River Rch & RM= UNT155 IN BECR,Reach-1,4071
     278     362     428     375     507     686     710
Boundary for River Rch & Prof#=UNT155 IN BECR,Reach-1,1
Up Type=0
Dn Type=3
Dn Slope=0.005
Boundary for River Rch & Prof#=UNT155 IN BECR,Reach-1,2
Up Type=0
Dn Type=3
Dn Slope=0.005
Boundary for River Rch & Prof#=UNT155 IN BECR,Reach-1,3
Up Type=0
Dn Type=3
Dn Slope=0.005
Boundary for River Rch & Prof#=UNT155 IN BECR,Reach-1,4
Up Type=0
Dn Type=3
Dn Slope=0.005
Boundary for River Rch & Prof#=UNT155 IN BECR,Reach-1,5
Up Type=0
Dn Type=3
Dn Slope=0.005
Boundary for River Rch & Prof#=UNT155 IN BECR,Reach-1,6
Up Type=0
Dn Type=3
Dn Slope=0.005
Boundary for River Rch & Prof#=UNT155 IN BECR,Reach-1,7
Up Type=0
Dn Type=3
Dn Slope=0.005

--- UNT155 IN BECR.g01 (geometry) ---

Geom Title=Existing Conditions

River Reach=UNT155 IN BECR,Reach-1
Reach XY= 30
      3794929.75     10546966.00      3794911.25     10547026.00
      3794915.25     10547079.00      3794885.50     10547250.00
      3794895.50     10547365.00      3794889.50     10547631.00
      3794913.75     10547829.00      3794958.00     10547916.00
      3794978.50     10547991.00      3794980.25     10548265.00
      3794997.25     10548350.00      3794971.00     10548473.00
      3794966.75     10548580.00      3794978.50     10548670.00
      3794912.25     10548930.00      3794911.50     10549018.00
      3794936.50     10549055.00      3794935.25     10549155.00
      3794910.25     10549225.00      3794929.00     10549305.00
      3794929.50     10549553.00      3794869.25     10550006.00
      3794760.75     10550260.00      3794696.75     10550369.00
      3794655.75     10550423.00      3794471.75     10550563.00
      3794357.75     10550621.00      3794328.50     10550621.00
      3794222.50     10550602.00      3794010.01     10550491.66

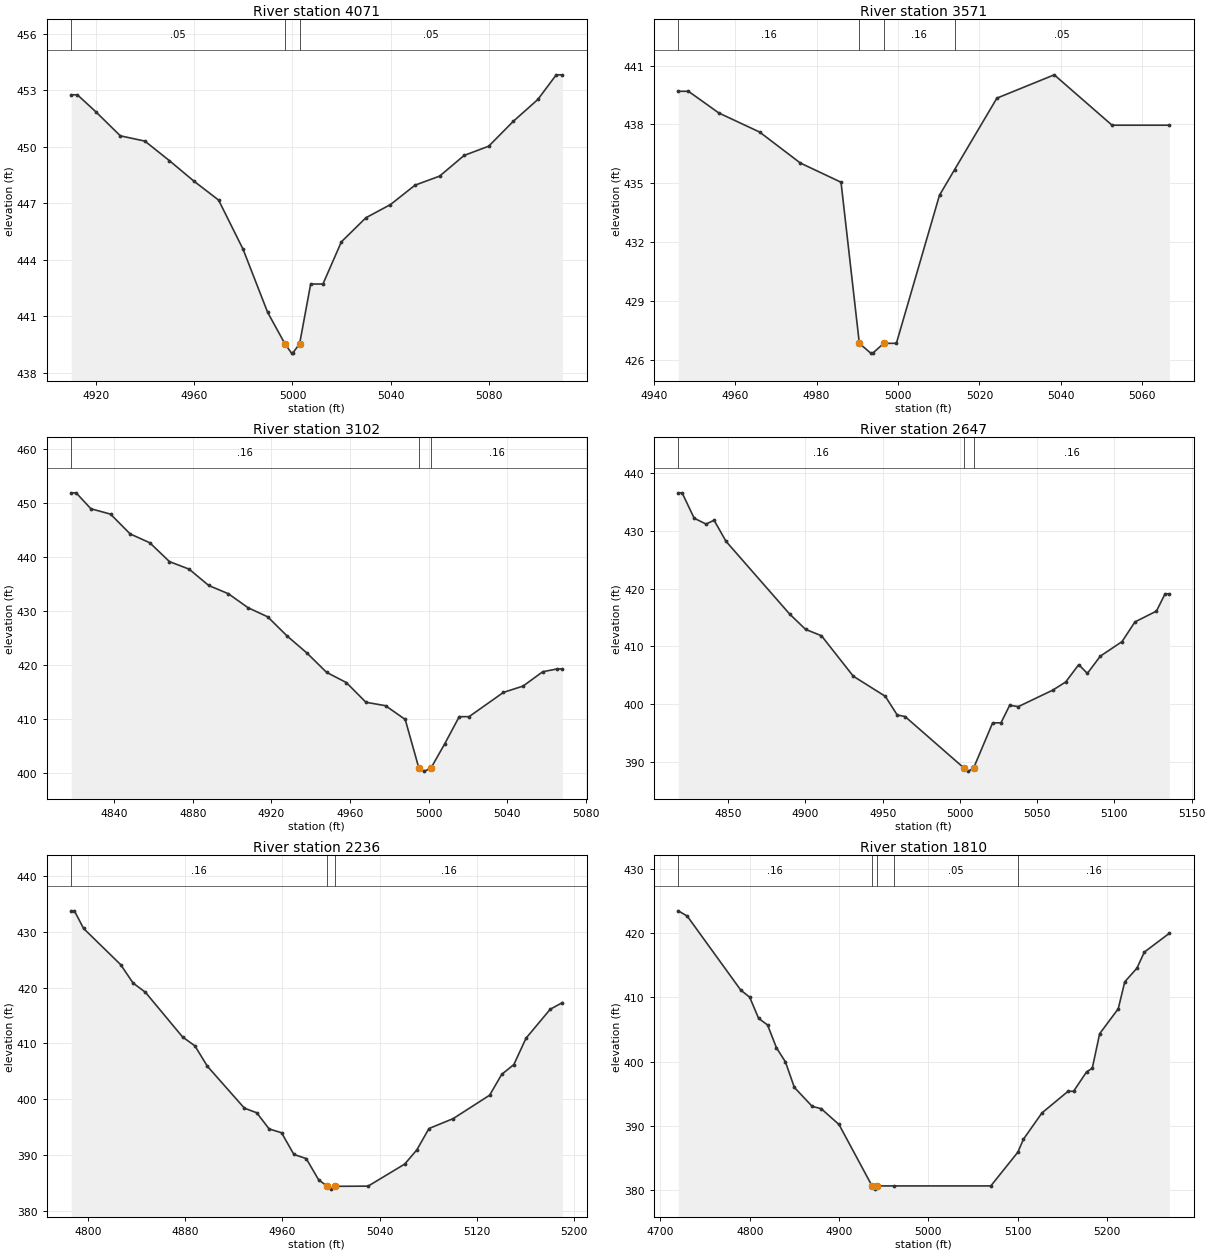
Type RM Length L Ch R = 1,4071,500,500,500
BEGIN DESCRIPTION:
UNT155 IN BECR 9.0
END DESCRIPTION:
XS GIS Cut Line= 3
      3794799.64     10547210.19      3794899.61     10547210.19
      3794999.64     10547210.19
#Sta/Elev= 27
  4909.9  452.77  4912.4  452.77  4919.9  451.87  4929.9  450.59  4939.9  450.31
  4949.9  449.27  4959.9  448.18  4969.9  447.18  4979.9  444.56  4989.9  441.21
  4996.9  439.55  4999.6  439.05  5000.1  439.05  5002.9  439.55  5007.4  442.72
  5012.4  442.72  5019.9  444.96  5029.9  446.24  5039.9  446.94  5049.9  447.97
  5059.9  448.45  5069.9  449.55  5079.9  450.04  5089.9  451.36  5099.9  452.52
  5107.4  453.83  5109.9  453.83
#Mann=3,-1,0
  4909.9    0.05       0  4996.9    0.03       0  5002.9    0.05       0
Bank Sta=4996.9,5002.9
Exp/Cntr=0.3,0.1

Type RM Length L Ch R = 1,3571,469,469,469
BEGIN DESCRIPTION:
UNT155 IN BECR 8.0
END DESCRIPTION:
XS GIS Cut Line= 3
      3794849.59     10547710.19      3794899.61     10547710.19
      3794949.59     10547660.21
#Sta/Elev= 17
  4946.0  439.69  4948.5  439.69  4956.0  438.58  4966.0  437.61  4976.0  436.03
  4986.0  435.05  4990.5  426.83  4993.3  426.33  4993.8  426.33  4996.5  426.83
  4999.6  426.83  5010.2  434.39  5013.9  435.69  5024.3  439.34  5038.4  440.53
  5052.6  437.96  5066.7  437.96
#Mann=4,-1,0
  4946.0    0.16       0  4990.5    0.07       0  4996.5    0.16       0
  5013.9    0.05       0
Bank Sta=4990.5,4996.5
Exp/Cntr=0.3,0.1

Type RM Length L Ch R = 1,3102,455,455,455
BEGIN DESCRIPTION:
UNT155 IN BECR 7.0
END DESCRIPTION:
XS GIS Cut Line= 3
      3794799.62     10548160.19      3794999.61     10548160.19
      3795049.62     10548160.19
#Sta/Elev= 30
  4818.1  451.88  4820.6  451.88  4828.1  448.93  4838.1  447.93  4848.1  444.26
  4858.1  442.62  4868.1  439.13  4878.1  437.73  4888.1  434.70  4898.1  433.17
  4908.1  430.58  4918.1  428.89  4928.1  425.30  4938.1  422.17  4948.1  418.59
  4958.1  416.71  4968.1  413.05  4978.1  412.41  4988.1  409.86  4995.1  400.78
  4997.8  400.28  5001.1  400.78  5008.1  405.27  5015.6  410.38  5020.6  410.38
  5038.1  414.88  5048.1  416.05  5058.1  418.71  5065.6  419.24  5068.1  419.24
#Mann=3,-1,0
  4818.1    0.16       0  4995.1    0.07       0  5001.1    0.16       0
Bank Sta=4995.1,5001.1
Exp/Cntr=0.3,0.1

Type RM Length L Ch R = 1,2647,411,411,411
BEGIN DESCRIPTION:
UNT155 IN BECR 6.0
END DESCRIPTION:
XS GIS Cut Line= 3
      3794799.65     10548560.20      3794999.61     10548610.19
      3795099.59     10548560.20
#Sta/Elev= 30
  4817.7  436.62  4820.2  436.62  4828.0  432.22  4835.7  431.21  4840.9  431.87
  4848.6  428.22  4889.8  415.61  4900.1  412.96  4910.4  411.85  4931.0  404.84
  4951.7  401.36  4959.4  398.13  4964.5  397.85  5002.8  388.89  5005.5  388.39
  5008.8  388.89  5021.2  396.76  5026.6  396.76  5032.2  399.80  5037.8  399.57
  5060.2  402.44  5068.5  403.85  5076.9  406.84  5082.5  405.33  5090.9  408.32
  5104.9  410.83  5113.3  414.25  5127.2  416.12  5132.8  419.12  5135.6  419.12
#Mann=3,-1,0
  4817.7    0.16       0  5002.8    0.07       0  5008.8    0.16       0
Bank Sta=5002.8,5008.8
Exp/Cntr=0.3,0.1

Type RM Length L Ch R = 1,2236,426,426,426
BEGIN DESCRIPTION:
UNT155 IN BECR 5.0
END DESCRIPTION:
XS GIS Cut Line= 3
      3794699.57     10548960.18      3794949.61     10549010.19
      3795099.62     10549010.19
#Sta/Elev= 30
  4785.8  433.76  4788.4  433.76  4796.0  430.60  4826.6  424.11  4836.8  420.82
  4847.0  419.16  4877.6  411.16  4887.8  409.56  4898.0  405.93  4928.6  398.40
  4938.8  397.57  4949.0  394.67  4959.2  394.00  4969.4  390.11  4979.6  389.36
  4989.8  385.56  4997.0  384.39  4999.7  383.89  5003.0  384.39  5030.6  384.43
  5060.8  388.38  5070.8  390.93  5080.8  394.75  5100.8  396.53  5130.8  400.72
  5140.8  404.46  5150.8  406.22  5160.8  410.93  5180.8  416.13  5190.8  417.31
#Mann=3,-1,0
  4785.8    0.16       0  4997.0    0.07       0  5003.0    0.16       0
Bank Sta=4997,5003
Exp/Cntr=0.3,0.1

Type RM Length L Ch R = 1,1810,449,449,449
BEGIN DESCRIPTION:
UNT155 IN BECR 4.0
END DESCRIPTION:
XS GIS Cut Line= 3
      3794649.59     10549410.19      3794949.61     10549410.19
      3795149.59     10549260.20
#Sta/Elev= 30
  4719.9  423.48  4729.9  422.67  4789.9  411.13  4799.9  410.02  4809.9  406.72
  4819.9  405.70  4829.9  402.13  4839.9  399.95  4849.9  395.97  4869.9  393.01
  4879.9  392.66  4899.9  390.19  4936.9  380.62  4939.7  380.12  4942.9  380.62
  4961.4  380.62  5069.9  380.62  5100.2  385.88  5106.4  387.89  5127.2  392.00
  5156.4  395.36  5162.6  395.37  5177.2  398.40  5183.5  398.95  5191.8  404.34
  5212.6  408.22  5219.9  412.42  5233.5  414.54  5241.8  417.05  5269.9  419.99
#Mann=5,-1,0
  4719.9    0.16       0  4936.9   0.033       0  4942.9    0.16       0
  4961.4    0.05       0  5100.2    0.16       0
Bank Sta=4936.9,4942.9
Exp/Cntr=0.3,0.1

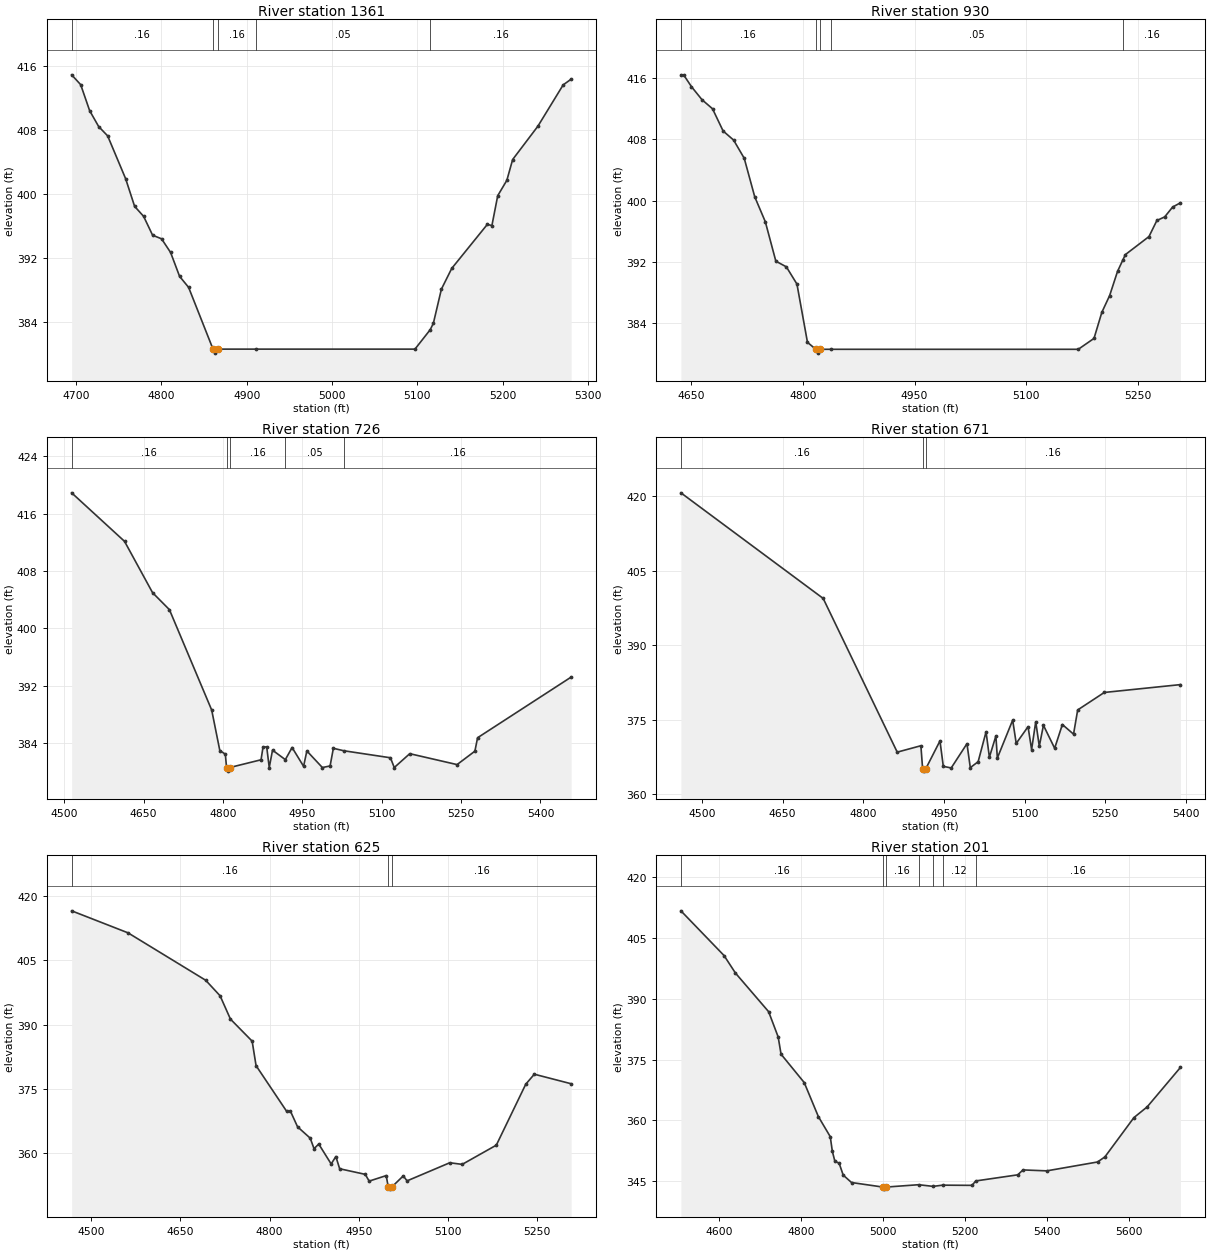
Type RM Length L Ch R = 1,1361,431,431,431
BEGIN DESCRIPTION:
UNT155 IN BECR 3.0
END DESCRIPTION:
XS GIS Cut Line= 3
      3794599.57     10549760.18      3794899.61     10549860.19
      3795149.58     10549760.20
#Sta/Elev= 30
  4694.8  414.91  4705.4  413.68  4715.9  410.43  4726.5  408.44  4737.0  407.28
  4758.1  401.92  4768.6  398.47  4779.2  397.21  4789.7  394.86  4800.2  394.41
  4810.8  392.70  4821.3  389.72  4831.9  388.34  4860.5  380.62  4863.2  380.12
  4866.5  380.62  4910.6  380.62  5097.2  380.62  5115.1  383.05  5118.8  383.86
  5128.2  388.12  5140.3  390.71  5182.0  396.21  5187.4  396.07  5194.2  399.80
  5204.9  401.72  5211.7  404.32  5241.3  408.49  5270.9  413.65  5280.3  414.37
#Mann=5,-1,0
  4694.8    0.16       0  4860.5   0.033       0  4866.5    0.16       0
  4910.6    0.05       0  5115.1    0.16       0
Bank Sta=4860.5,4866.5
Exp/Cntr=0.3,0.1

Type RM Length L Ch R = 1,930,204,204,204
BEGIN DESCRIPTION:
UNT155 IN BECR 2.0
END DESCRIPTION:
XS GIS Cut Line= 3
      3794499.59     10550010.17      3794749.61     10550260.19
      3795049.61     10550360.19
#Sta/Elev= 30
  4636.7  416.44  4640.3  416.44  4650.9  414.89  4665.0  413.19  4679.1  412.01
  4693.3  409.11  4707.4  407.92  4721.6  405.55  4735.7  400.52  4749.9  397.26
  4764.0  392.12  4778.1  391.38  4792.3  389.13  4806.4  381.53  4817.6  380.62
  4820.3  380.12  4823.6  380.62  4838.6  380.62  5169.5  380.62  5190.6  382.04
  5201.1  385.44  5211.6  387.64  5222.2  390.80  5229.5  392.32  5232.7  392.98
  5264.3  395.33  5274.9  397.43  5285.4  397.90  5296.0  399.18  5306.5  399.74
#Mann=5,-1,0
  4636.7    0.16       0  4817.6   0.033       0  4823.6    0.16       0
  4838.6    0.05       0  5229.5    0.16       0
Bank Sta=4817.6,4823.6
Exp/Cntr=0.3,0.1

Type RM Length L Ch R = 1,726,55,55,55
BEGIN DESCRIPTION:
Mapping XS 335f7088
END DESCRIPTION:
XS GIS Cut Line= 4
      3794427.31     10550015.73      3794547.10     10550359.50
      3794838.77     10550573.04      3795052.36     10550526.15
#Sta/Elev= 30
  4513.9  418.88  4613.9  412.12  4666.9  404.97  4698.7  402.61  4778.6  388.63
  4794.0  382.98  4804.4  382.48  4806.7  380.62  4809.5  380.12  4812.7  380.62
  4871.9  381.70  4875.7  383.49  4882.6  383.49  4887.4  380.62  4893.6  383.04
  4917.8  381.72  4930.6  383.41  4952.3  380.79  4958.5  382.93  4987.8  380.62
  5002.4  380.84  5008.6  383.30  5028.1  382.96  5116.5  381.98  5123.7  380.62
  5153.0  382.55  5242.4  381.03  5276.1  382.90  5281.2  384.77  5458.1  393.22
#Mann=5,-1,0
  4513.9    0.16       0  4806.7   0.033       0  4812.7    0.16       0
  4917.8    0.05       0  5028.1    0.16       0
Bank Sta=4806.7,4812.7
Exp/Cntr=0.3,0.1

Type RM Length L Ch R = 1,671,46,46,46
BEGIN DESCRIPTION:
Mapping XS 93da074d
END DESCRIPTION:
XS GIS Cut Line= 5
      3794354.40     10550010.56      3794484.60     10550380.33
      3794640.85     10550494.91      3794807.52     10550635.54
      3794932.56     10550630.33
#Sta/Elev= 30
  4460.8  420.63  4725.4  399.38  4863.1  368.45  4907.1  369.74  4910.3  365.13
  4913.0  364.63  4916.3  365.13  4942.6  370.71  4948.8  365.59  4963.5  365.27
  4992.8  370.15  4999.0  365.33  5013.6  366.53  5028.3  372.54  5034.5  367.43
  5046.6  371.71  5049.3  367.27  5077.8  374.89  5084.4  370.21  5106.4  373.57
  5113.0  368.97  5120.7  374.57  5127.3  369.64  5135.0  373.85  5155.9  369.23
  5170.2  374.01  5191.0  372.07  5198.7  376.94  5248.2  380.46  5389.8  382.04
#Mann=3,-1,0
  4460.8    0.16       0  4910.3    0.07       0  4916.3    0.16       0
Bank Sta=4910.3,4916.3
Exp/Cntr=0.3,0.1

Type RM Length L Ch R = 1,625,424,424,424
BEGIN DESCRIPTION:
Mapping XS b169d68d
END DESCRIPTION:
XS GIS Cut Line= 3
      3794302.32     10550052.21      3794437.73     10550390.75
      3794806.04     10550691.62
#Sta/Elev= 30
  4467.2  416.59  4562.0  411.45  4692.7  400.37  4716.9  396.74  4734.3  391.30
  4770.8  386.15  4777.4  380.43  4828.8  369.77  4835.3  369.77  4847.2  366.14
  4868.5  363.49  4874.9  361.03  4882.8  362.12  4903.7  357.47  4911.6  359.20
  4918.0  356.35  4961.1  355.04  4967.6  353.46  4996.3  354.75  4999.7  352.09
  5002.5  351.59  5005.7  352.09  5025.0  354.68  5031.4  353.52  5103.2  357.75
  5124.1  357.37  5181.5  361.86  5231.0  376.09  5245.4  378.43  5307.4  376.20
#Mann=3,-1,0
  4467.2    0.16       0  4999.7    0.07       0  5005.7    0.16       0
Bank Sta=4999.7,5005.7
Exp/Cntr=0.3,0.1

Type RM Length L Ch R = 1,201,0,0,0
BEGIN DESCRIPTION:
UNT155 IN BECR 1.0
END DESCRIPTION:
XS GIS Cut Line= 4
      3794260.09     10550098.58      3794168.13     10550701.99
      3794238.46     10550789.47      3794730.00     10550719.67
#Sta/Elev= 30
  4506.8  411.71  4612.1  400.67  4639.9  396.35  4720.9  386.81  4744.2  380.57
  4751.2  376.32  4807.8  369.31  4842.2  360.93  4871.3  355.96  4876.4  352.33
  4882.7  349.84  4892.8  349.45  4902.9  346.47  4923.2  344.64  5000.4  343.51
  5003.2  343.01  5006.4  343.51  5086.9  344.10  5122.4  343.69  5145.4  343.99
  5217.2  343.94  5226.4  345.03  5328.8  346.54  5341.7  347.75  5399.7  347.52
  5523.5  349.71  5541.5  350.96  5612.4  360.67  5644.7  363.31  5725.9  373.05
#Mann=7,-1,0
  4506.8    0.16       0  5000.4    0.07       0  5006.4    0.16       0
  5086.9    0.12       0  5122.4    0.16       0  5145.4    0.12       0
  5226.4    0.16       0
Bank Sta=5000.4,5006.4
Exp/Cntr=0.3,0.1

Chan Stop Cuts=-1