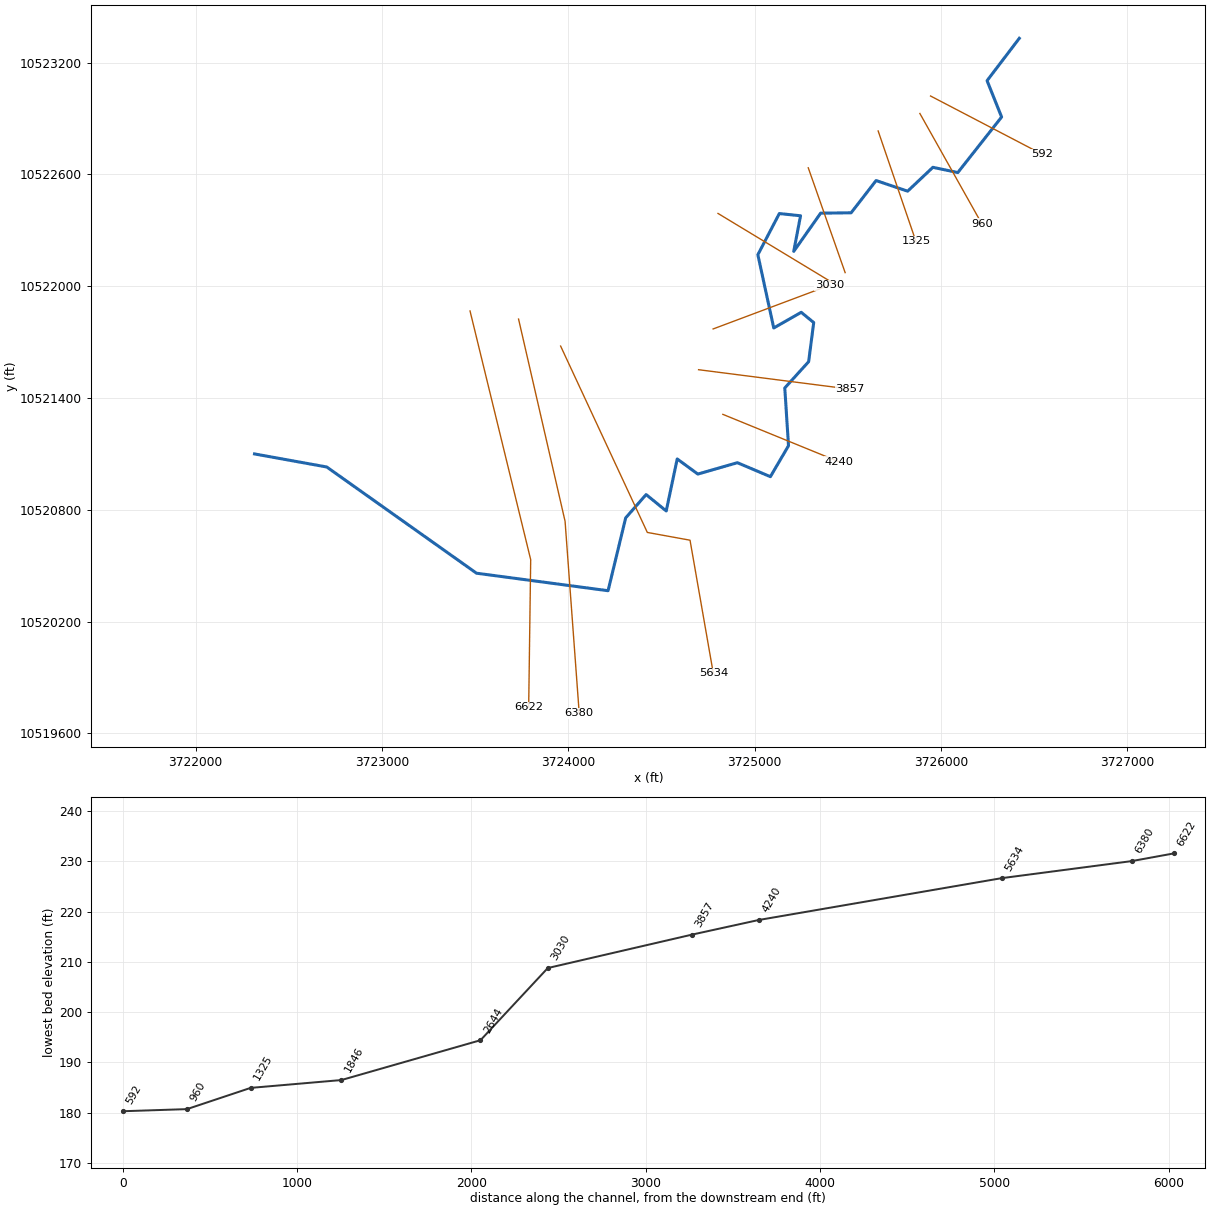
--- UNT157 IN BECR.prj (project) ---

Proj Title=UNT157 IN BECR Base Level Engineering
Current Plan=p01
Default Exp/Contr=0.3,0.1
English Units
Geom File=g01
Flow File=f01
Plan File=p01
BEGIN DESCRIPTION:
UNT157 IN BECR
END DESCRIPTION:

--- UNT157 IN BECR.p01 (plan) ---

Plan Title=Multiple Run
Short Identifier=Multiple
Geom File=g01
Flow File=f01
Subcritical Flow
K Sum by GR= 0
Std Step Tol= 0.01
Critical Tol= 0.01
Num of Std Step Trials= 20
Max Error Tol= 0.3
Flow Tol Ratio= 0.001
Split Flow NTrial= 30
Split Flow Tol= 0.02
Split Flow Ratio= 0.02
Log Output Level= 0
Friction Slope Method= 1
Unsteady Friction Slope Method= 2
Unsteady Bridges Friction Slope Method= 1
Parabolic Critical Depth
Global Vel Dist=  1 , 1 , 1
Global Log Level= 0
CheckData=True
Encroach Param= -1, 0, 0, 0
BEGIN DESCRIPTION:
Multiple Run
END DESCRIPTION:

--- UNT157 IN BECR.f01 (steady flow) ---

Flow Title=Multiple
Number of Profiles=7
Profile Names=10-year,25-year,50-year,1pct_min,100-year,1pct_plu,500-year
River Rch & RM= UNT157 IN BECR,Reach-1,6622
     720     986    1207    1086    1469    1986    2182
Boundary for River Rch & Prof#=UNT157 IN BECR,Reach-1,1
Up Type=0
Dn Type=3
Dn Slope=0.005
Boundary for River Rch & Prof#=UNT157 IN BECR,Reach-1,2
Up Type=0
Dn Type=3
Dn Slope=0.005
Boundary for River Rch & Prof#=UNT157 IN BECR,Reach-1,3
Up Type=0
Dn Type=3
Dn Slope=0.005
Boundary for River Rch & Prof#=UNT157 IN BECR,Reach-1,4
Up Type=0
Dn Type=3
Dn Slope=0.005
Boundary for River Rch & Prof#=UNT157 IN BECR,Reach-1,5
Up Type=0
Dn Type=3
Dn Slope=0.005
Boundary for River Rch & Prof#=UNT157 IN BECR,Reach-1,6
Up Type=0
Dn Type=3
Dn Slope=0.005
Boundary for River Rch & Prof#=UNT157 IN BECR,Reach-1,7
Up Type=0
Dn Type=3
Dn Slope=0.005

--- UNT157 IN BECR.g01 (geometry) ---

Geom Title=Existing Conditions

River Reach=UNT157 IN BECR,Reach-1
Reach XY= 30
      3722315.75     10521100.00      3722703.25     10521030.00
      3723507.00     10520460.00      3724213.00     10520366.00
      3724307.50     10520757.00      3724417.25     10520882.00
      3724525.00     10520794.00      3724584.00     10521073.00
      3724694.75     10520992.00      3724907.00     10521053.00
      3725084.00     10520978.00      3725181.25     10521144.00
      3725161.25     10521454.00      3725289.25     10521595.00
      3725316.50     10521805.00      3725249.50     10521860.00
      3725102.00     10521776.00      3725016.75     10522169.00
      3725132.00     10522390.00      3725245.75     10522378.00
      3725209.25     10522187.00      3725353.75     10522392.00
      3725517.25     10522394.00      3725651.25     10522567.00
      3725820.50     10522510.00      3725956.00     10522638.00
      3726089.75     10522610.00      3726324.75     10522908.00
      3726246.75     10523103.00      3726419.61     10523330.19

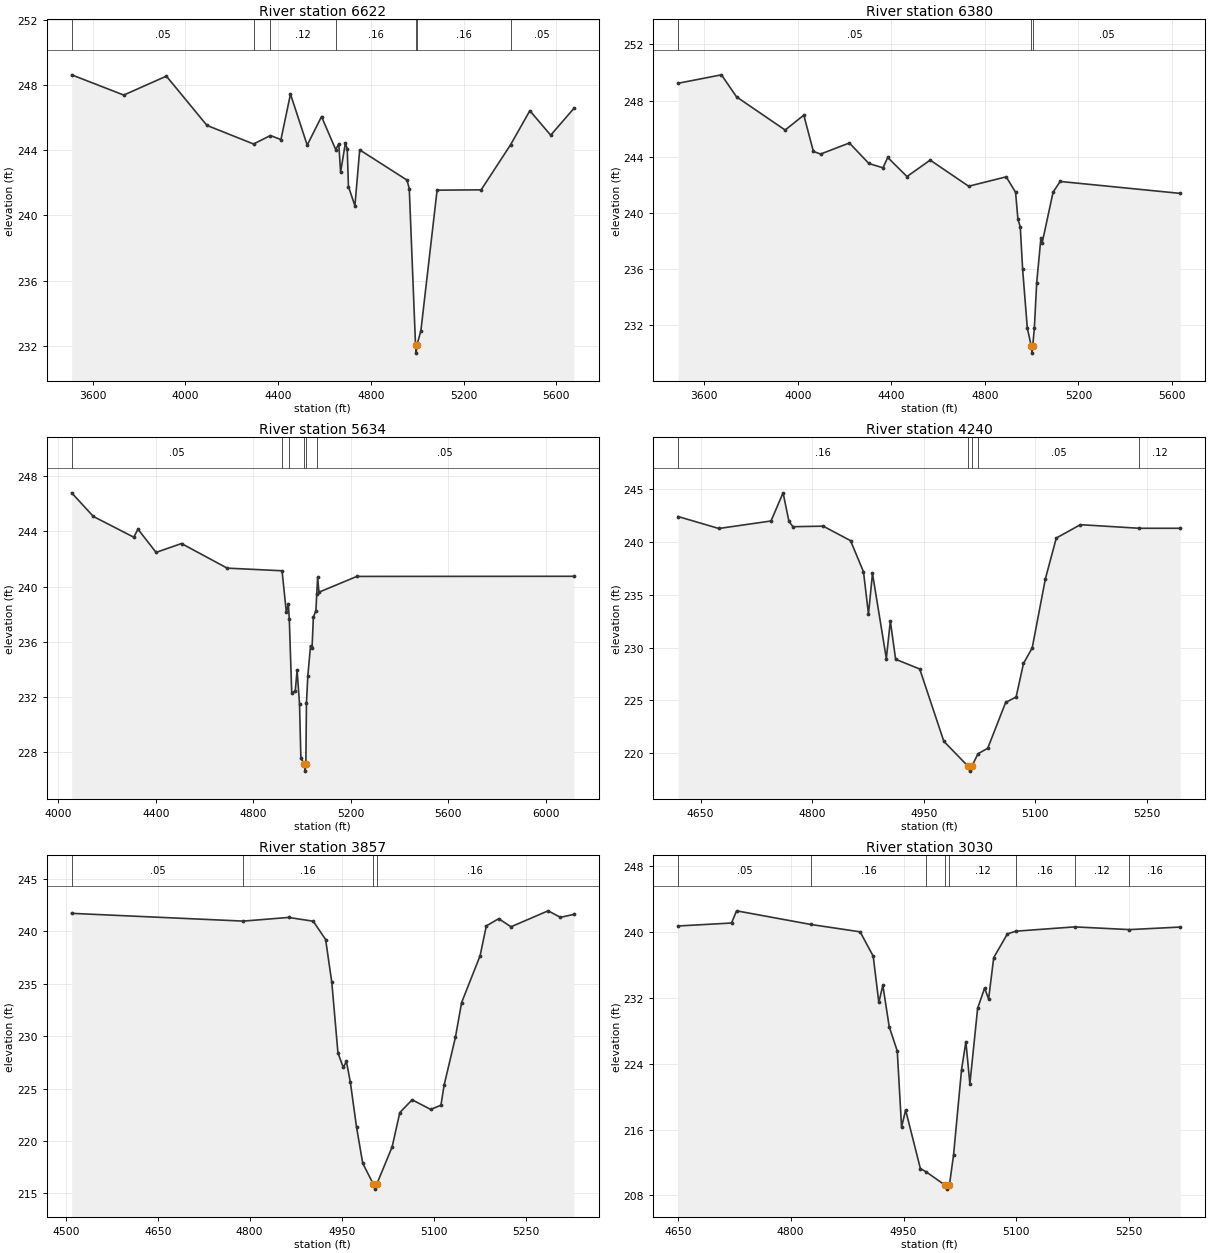
Type RM Length L Ch R = 1,6622,242,242,242
BEGIN DESCRIPTION:
UNT157 IN BECR 11.0
END DESCRIPTION:
XS GIS Cut Line= 3
      3723472.25     10521867.11      3723797.77     10520532.50
      3723786.91     10519740.41
#Sta/Elev= 30
  3509.4  248.62  3734.1  247.38  3918.0  248.54  4092.9  245.52  4293.9  244.38
  4366.7  244.90  4412.0  244.65  4453.2  247.44  4525.3  244.31  4587.0  246.06
  4648.2  244.04  4661.5  244.39  4669.4  242.65  4689.9  244.44  4698.0  244.08
  4703.2  241.77  4731.1  240.59  4751.7  244.02  4955.5  242.17  4965.5  241.65
  4992.5  232.06  4995.2  231.56  4998.5  232.06  5015.5  232.92  5085.5  241.55
  5275.5  241.57  5402.7  244.34  5485.5  246.42  5575.5  244.92  5675.3  246.56
#Mann=7,-1,0
  3509.4    0.05       0  4293.9    0.08       0  4366.7    0.12       0
  4648.2    0.16       0  4992.5    0.07       0  4998.5    0.16       0
  5402.7    0.05       0
Bank Sta=4992.5,4998.5
Exp/Cntr=0.3,0.1

Type RM Length L Ch R = 1,6380,746,746,746
BEGIN DESCRIPTION:
UNT157 IN BECR 10.0
END DESCRIPTION:
XS GIS Cut Line= 3
      3723732.65     10521823.78      3723982.23     10520738.67
      3724058.19     10519707.80
#Sta/Elev= 30
  3488.6  249.24  3673.8  249.84  3738.5  248.27  3946.2  245.91  4025.9  246.97
  4066.9  244.39  4097.7  244.20  4220.8  244.99  4304.2  243.53  4364.5  243.22
  4384.7  243.96  4467.1  242.60  4566.3  243.77  4730.9  241.91  4891.3  242.58
  4931.4  241.48  4941.4  239.57  4951.5  239.01  4961.5  236.02  4981.5  231.82
  4998.6  230.53  5001.4  230.03  5004.6  230.53  5011.6  231.79  5021.7  235.05
  5039.7  238.21  5044.7  237.85  5091.8  241.49  5121.9  242.25  5635.7  241.40
#Mann=3,-1,0
  3488.6    0.05       0  4998.6    0.03       0  5004.6    0.05       0
Bank Sta=4998.6,5004.6
Exp/Cntr=0.3,0.1

Type RM Length L Ch R = 1,5634,1394,1394,1394
BEGIN DESCRIPTION:
UNT157 IN BECR 9.0
END DESCRIPTION:
XS GIS Cut Line= 4
      3723958.35     10521678.79      3724423.63     10520678.77
      3724652.80     10520637.10      3724777.51     10519923.51
#Sta/Elev= 30
  4055.0  246.78  4144.1  245.07  4309.8  243.57  4327.1  244.15  4401.3  242.47
  4505.7  243.11  4693.2  241.33  4918.2  241.14  4935.8  238.14  4944.1  238.72
  4947.9  237.65  4957.9  232.30  4972.5  232.45  4979.9  233.95  4989.9  231.50
  4995.4  227.59  5009.8  227.14  5012.5  226.64  5015.8  227.14  5018.3  231.56
  5024.0  233.55  5035.1  235.71  5041.2  235.53  5046.7  237.78  5057.1  238.26
  5060.5  239.43  5064.1  240.67  5069.6  239.59  5225.0  240.73  6115.3  240.74
#Mann=6,-1,0
  4055.0    0.05       0  4918.2    0.16       0  4947.9    0.12       0
  5009.8    0.07       0  5015.8    0.12       0  5060.5    0.05       0
Bank Sta=5009.8,5015.8
Exp/Cntr=0.3,0.1

Type RM Length L Ch R = 1,4240,383,383,383
BEGIN DESCRIPTION:
UNT157 IN BECR 8.0
END DESCRIPTION:
XS GIS Cut Line= 2
      3724828.94     10521312.41      3725453.95     10521057.20
#Sta/Elev= 30
  4619.9  242.38  4674.6  241.25  4744.8  241.96  4761.0  244.62  4768.9  241.92
  4774.3  241.42  4815.0  241.47  4851.7  240.10  4869.1  237.16  4875.8  233.16
  4881.2  237.00  4899.8  228.96  4905.2  232.50  4912.3  228.89  4944.7  227.97
  4977.1  221.14  5009.1  218.82  5011.9  218.32  5015.1  218.82  5023.0  219.96
  5036.1  220.48  5060.2  224.81  5074.3  225.33  5084.2  228.50  5095.9  229.96
  5113.6  236.49  5128.3  240.35  5160.7  241.61  5240.0  241.27  5295.0  241.27
#Mann=5,-1,0
  4619.9    0.16       0  5009.1    0.07       0  5015.1    0.16       0
  5023.0    0.05       0  5240.0    0.12       0
Bank Sta=5009.1,5015.1
Exp/Cntr=0.3,0.1

Type RM Length L Ch R = 1,3857,827,827,827
BEGIN DESCRIPTION:
UNT157 IN BECR 7.0
END DESCRIPTION:
XS GIS Cut Line= 2
      3724698.70     10521552.01      3725511.25     10521447.83
#Sta/Elev= 30
  4509.6  241.71  4789.6  240.97  4863.4  241.32  4903.7  240.96  4923.9  239.21
  4934.0  235.12  4944.0  228.40  4952.7  227.01  4957.8  227.59  4964.2  225.62
  4974.3  221.33  4984.4  217.88  5001.5  215.91  5004.3  215.41  5007.5  215.91
  5032.4  219.44  5044.9  222.71  5065.0  223.93  5095.3  223.01  5112.0  223.41
  5117.1  225.30  5135.6  229.88  5145.7  233.20  5175.9  237.67  5186.0  240.51
  5206.2  241.20  5226.3  240.43  5286.8  241.95  5307.0  241.33  5328.8  241.61
#Mann=4,-1,0
  4509.6    0.05       0  4789.6    0.16       0  5001.5    0.07       0
  5007.5    0.16       0
Bank Sta=5001.5,5007.5
Exp/Cntr=0.3,0.1

Type RM Length L Ch R = 1,3030,386,386,386
BEGIN DESCRIPTION:
UNT157 IN BECR 6.0
END DESCRIPTION:
XS GIS Cut Line= 2
      3724776.85     10521770.76      3725401.85     10522005.13
#Sta/Elev= 30
  4650.4  240.73  4721.4  241.09  4728.1  242.57  4827.1  240.91  4892.3  240.02
  4909.7  237.07  4917.2  231.44  4922.5  233.54  4931.0  228.49  4941.7  225.54
  4947.4  216.31  4952.8  218.37  4972.4  211.27  4979.9  210.88  5005.0  209.27
  5007.7  208.77  5011.0  209.27  5016.5  212.91  5027.1  223.25  5032.9  226.68
  5038.2  221.55  5048.5  230.72  5057.8  233.19  5063.1  231.86  5069.9  236.89
  5088.1  239.77  5099.4  240.10  5177.4  240.62  5250.3  240.29  5317.9  240.60
#Mann=8,-1,0
  4650.4    0.05       0  4827.1    0.16       0  4979.9    0.12       0
  5005.0    0.07       0  5011.0    0.12       0  5099.4    0.16       0
  5177.4    0.12       0  5250.3    0.16       0
Bank Sta=5005,5011
Exp/Cntr=0.3,0.1

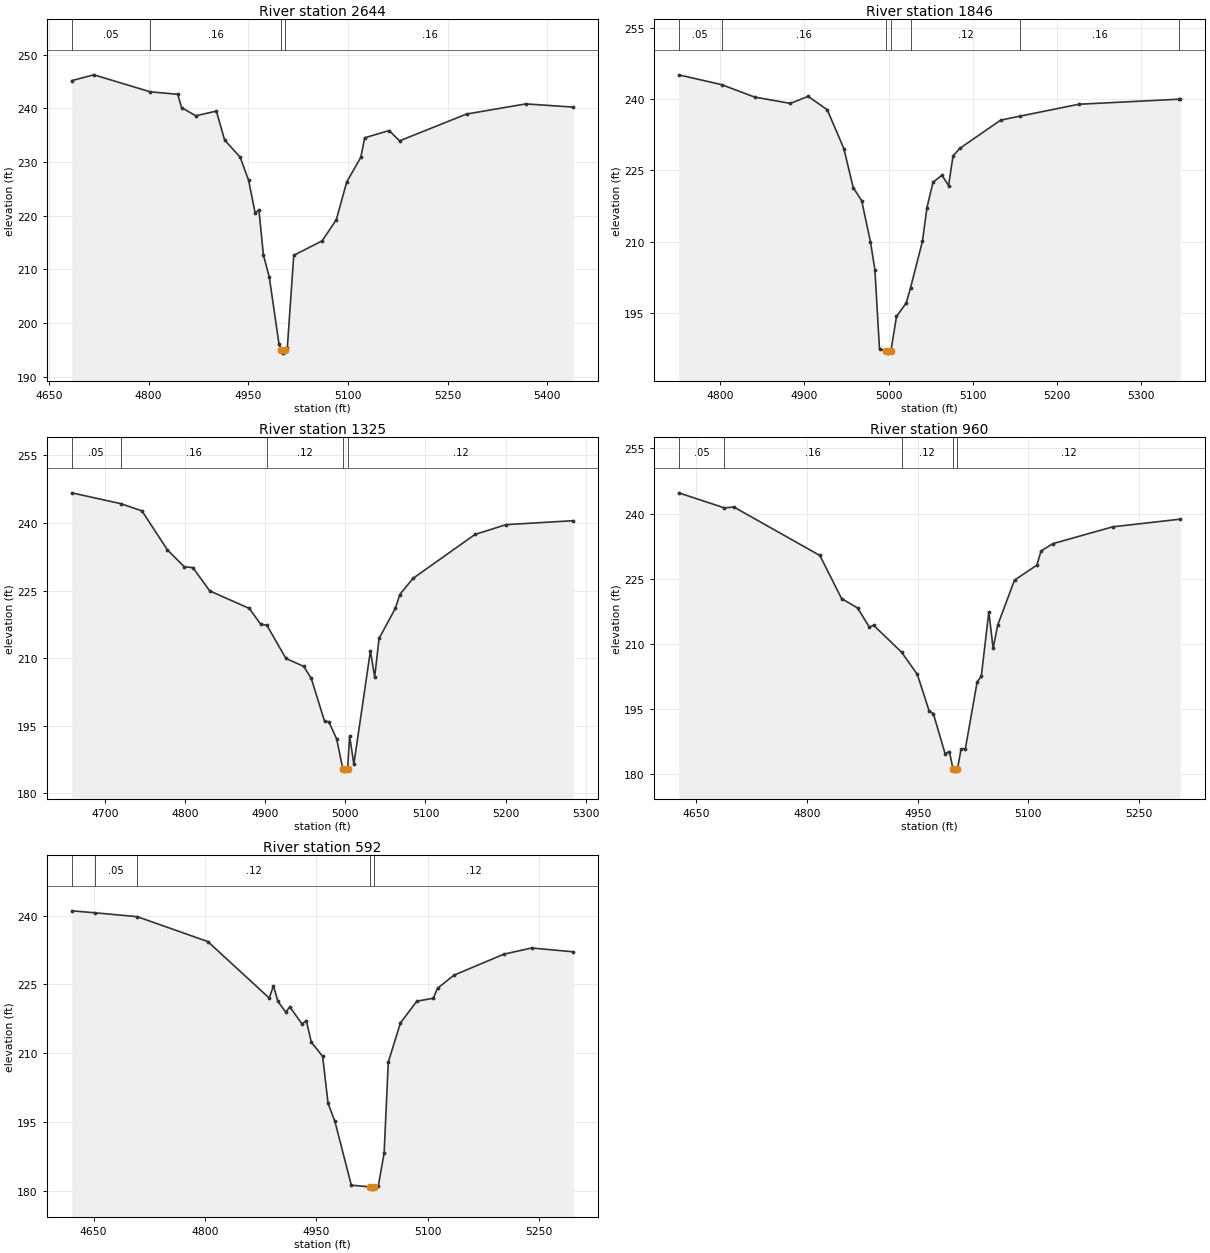
Type RM Length L Ch R = 1,2644,798,798,798
BEGIN DESCRIPTION:
UNT157 IN BECR 5.0
END DESCRIPTION:
XS GIS Cut Line= 2
      3724802.91     10522390.53      3725448.68     10521999.94
#Sta/Elev= 30
  4684.5  245.14  4717.8  246.22  4802.8  243.05  4843.9  242.60  4849.7  240.13
  4871.1  238.60  4902.1  239.47  4914.4  234.11  4937.8  230.90  4950.6  226.57
  4960.3  220.58  4966.1  221.03  4972.8  212.74  4981.7  208.56  4996.2  196.21
  5000.0  194.92  5002.8  194.42  5006.0  194.92  5008.8  195.37  5018.5  212.62
  5061.2  215.32  5082.6  219.26  5098.1  226.26  5119.4  230.87  5125.2  234.50
  5162.1  235.85  5177.6  233.93  5278.5  238.92  5367.7  240.81  5439.2  240.21
#Mann=4,-1,0
  4684.5    0.05       0  4802.8    0.16       0  5000.0    0.07       0
  5006.0    0.16       0
Bank Sta=5000,5006
Exp/Cntr=0.3,0.1

Type RM Length L Ch R = 1,1846,521,521,521
BEGIN DESCRIPTION:
UNT157 IN BECR 4.0
END DESCRIPTION:
XS GIS Cut Line= 2
      3725287.26     10522635.33      3725485.18     10522072.83
#Sta/Elev= 30
  4750.6  245.14  4801.7  243.07  4840.9  240.45  4883.3  239.12  4904.5  240.60
  4927.2  237.78  4946.9  229.61  4958.1  221.36  4968.1  218.63  4978.5  210.00
  4983.8  204.09  4989.3  187.36  4996.9  187.00  4999.6  186.50  5002.9  187.00
  5009.5  194.22  5021.1  197.07  5026.2  200.26  5040.4  210.11  5045.7  217.17
  5052.9  222.49  5063.5  224.00  5071.4  221.80  5076.7  228.04  5084.7  229.64
  5133.3  235.59  5156.7  236.45  5226.2  238.94  5344.8  240.00  5346.9  240.02
#Mann=7,-1,0
  4750.6    0.05       0  4801.7    0.16       0  4996.9    0.07       0
  5002.9    0.16       0  5026.2    0.12       0  5156.7    0.16       0
  5344.8    0.12       0
Bank Sta=4996.9,5002.9
Exp/Cntr=0.3,0.1

Type RM Length L Ch R = 1,1325,365,365,365
BEGIN DESCRIPTION:
UNT157 IN BECR 3.0
END DESCRIPTION:
XS GIS Cut Line= 2
      3725662.27     10522833.21      3725865.00     10522240.63
#Sta/Elev= 30
  4658.4  246.68  4719.6  244.28  4746.1  242.66  4777.9  234.01  4799.0  230.26
  4809.6  230.10  4830.7  224.92  4880.1  221.03  4894.1  217.58  4902.2  217.25
  4925.8  209.93  4948.0  208.19  4957.5  205.49  4974.0  196.01  4979.3  195.90
  4989.2  192.06  4996.8  185.44  4999.6  184.94  5002.8  185.44  5005.3  192.78
  5010.6  186.48  5031.3  211.64  5036.6  205.85  5042.1  214.38  5062.6  221.11
  5067.9  224.11  5084.4  227.69  5161.8  237.44  5200.6  239.62  5284.7  240.50
#Mann=5,-1,0
  4658.4    0.05       0  4719.6    0.16       0  4902.2    0.12       0
  4996.8    0.07       0  5002.8    0.12       0
Bank Sta=4996.8,5002.8
Exp/Cntr=0.3,0.1

Type RM Length L Ch R = 1,960,368,368,368
BEGIN DESCRIPTION:
UNT157 IN BECR 2.0
END DESCRIPTION:
XS GIS Cut Line= 2
      3725886.20     10522927.03      3726218.99     10522334.26
#Sta/Elev= 30
  4626.1  244.79  4688.1  241.32  4700.8  241.53  4817.4  230.37  4846.8  220.46
  4868.5  218.29  4884.5  213.87  4890.2  214.30  4928.2  208.10  4949.5  202.98
  4965.5  194.59  4971.2  193.96  4987.1  184.74  4992.9  185.23  4997.9  181.22
  5000.7  180.72  5003.9  181.22  5008.8  185.82  5014.6  185.88  5030.5  201.22
  5036.2  202.60  5046.4  217.41  5052.2  208.97  5058.3  214.30  5081.2  224.69
  5111.5  228.15  5117.2  231.41  5133.2  233.09  5214.2  236.96  5305.9  238.73
#Mann=5,-1,0
  4626.1    0.05       0  4688.1    0.16       0  4928.2    0.12       0
  4997.9    0.07       0  5003.9    0.12       0
Bank Sta=4997.9,5003.9
Exp/Cntr=0.3,0.1

Type RM Length L Ch R = 1,592,0,0,0
BEGIN DESCRIPTION:
UNT157 IN BECR 1.0
END DESCRIPTION:
XS GIS Cut Line= 2
      3725943.53     10523020.74      3726542.51     10522708.23
#Sta/Elev= 30
  4620.6  241.09  4652.1  240.66  4708.9  239.81  4803.9  234.37  4886.6  222.03
  4892.3  224.72  4898.2  221.32  4908.7  219.00  4914.4  220.09  4930.8  216.36
  4936.4  217.12  4943.3  212.39  4958.5  209.30  4965.8  199.03  4975.0  195.11
  4997.1  181.16  5021.8  180.80  5024.6  180.30  5027.8  180.80  5033.5  181.05
  5041.3  188.14  5046.9  208.03  5063.3  216.61  5085.4  221.35  5107.5  222.00
  5113.2  224.16  5135.2  227.02  5202.7  231.63  5240.0  232.97  5296.2  232.14
#Mann=5,-1,0
  4620.6    0.16       0  4652.1    0.05       0  4708.9    0.12       0
  5021.8    0.07       0  5027.8    0.12       0
Bank Sta=5021.8,5027.8
Exp/Cntr=0.3,0.1

Chan Stop Cuts=-1