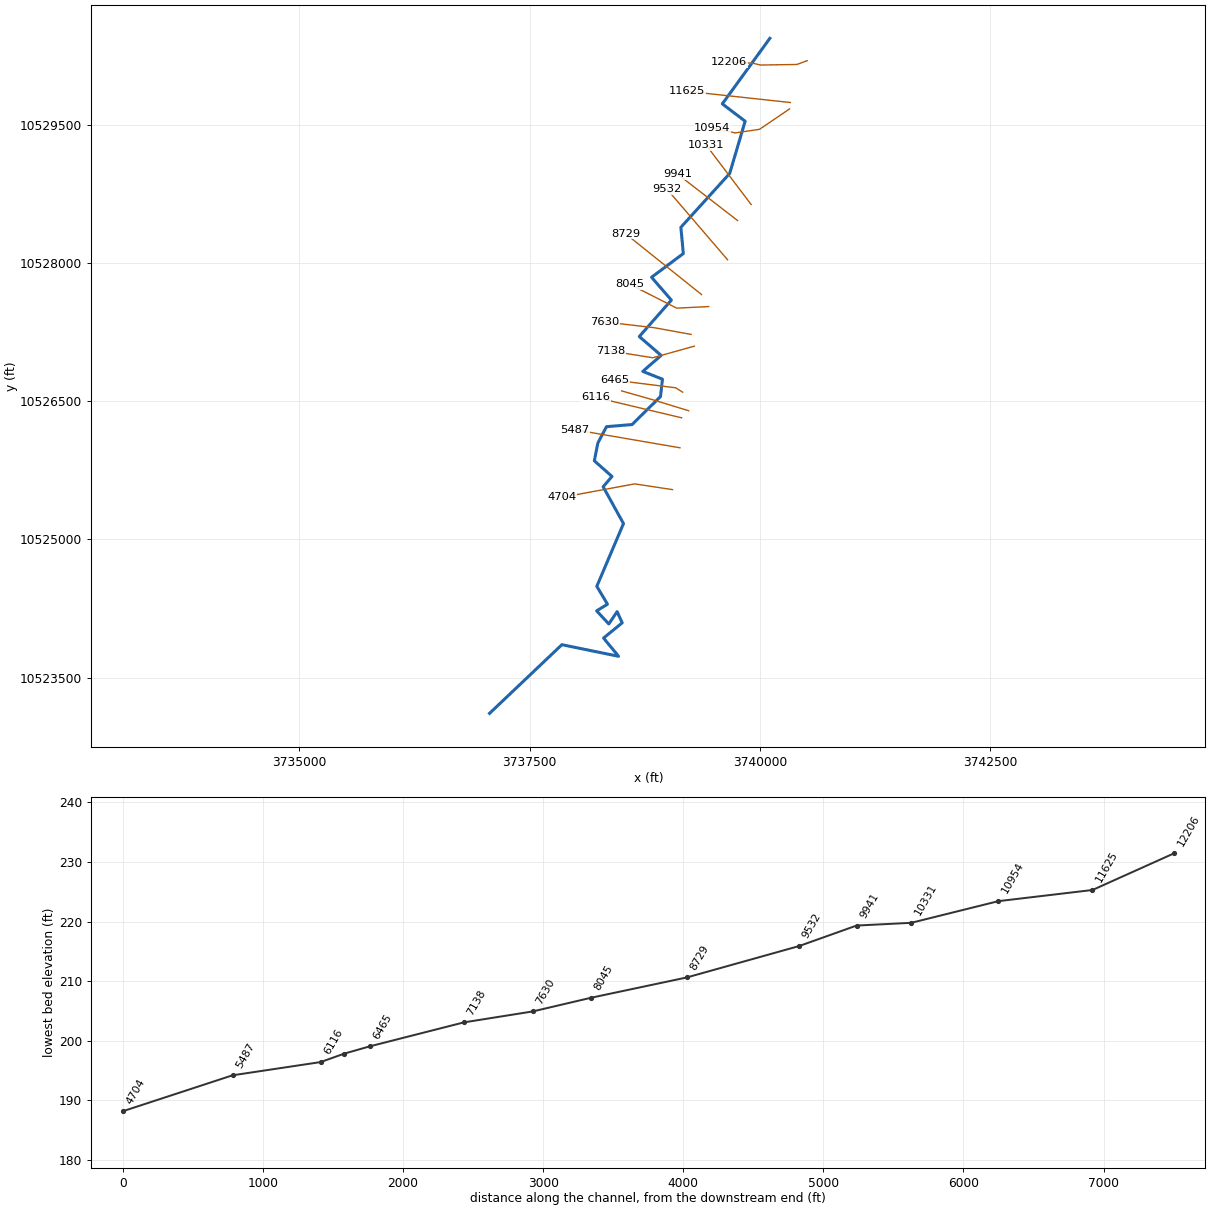
--- UNT158 IN BECR.prj (project) ---

Proj Title=UNT158 IN BECR Base Level Engineering
Current Plan=p01
Default Exp/Contr=0.3,0.1
English Units
Geom File=g01
Flow File=f01
Plan File=p01
Y Axis Title=Elevation
X Axis Title(PF)=Main Channel Distance
X Axis Title(XS)=Station
BEGIN DESCRIPTION:
UNT158 IN BECR
END DESCRIPTION:
DSS Export Rating Curves= 0
DSS Export Rating Curve Sorted= 0
DSS Export Volume Flow Curves= 0
DXF OffsetX= 0
DXF OffsetY= 0
DXF ScaleX= 1
DXF ScaleY= 10

--- UNT158 IN BECR.p01 (plan) ---

Plan Title=Multiple Run
Short Identifier=Multiple
Geom File=g01
Flow File=f01
Subcritical Flow
K Sum by GR= 0
Std Step Tol= 0.01
Critical Tol= 0.01
Num of Std Step Trials= 20
Max Error Tol= 0.3
Flow Tol Ratio= 0.001
Split Flow NTrial= 30
Split Flow Tol= 0.02
Split Flow Ratio= 0.02
Log Output Level= 0
Friction Slope Method= 1
Unsteady Friction Slope Method= 2
Unsteady Bridges Friction Slope Method= 1
Parabolic Critical Depth
Global Vel Dist=  1 , 1 , 1
Global Log Level= 0
CheckData=True
Encroach Param= -1, 0, 0, 0
BEGIN DESCRIPTION:
Multiple Run
END DESCRIPTION:

--- UNT158 IN BECR.f01 (steady flow) ---

Flow Title=Multiple
Program Version=4.10
Number of Profiles= 7
Profile Names=10-year,25-year,50-year,1pct_min,100-year,1pct_plu,500-year
River Rch & RM=UNT158 IN BECR,Reach-1         ,12206
     494     643     758     517     877    1236    1164
River Rch & RM=UNT158 IN BECR,Reach-1         ,11625
     534     708     848     745    1008    1363    1430
Boundary for River Rch & Prof#=UNT158 IN BECR,Reach-1         , 1
Up Type= 0
Dn Type= 3
Dn Slope=0.005
Boundary for River Rch & Prof#=UNT158 IN BECR,Reach-1         , 2
Up Type= 0
Dn Type= 3
Dn Slope=0.005
Boundary for River Rch & Prof#=UNT158 IN BECR,Reach-1         , 3
Up Type= 0
Dn Type= 3
Dn Slope=0.005
Boundary for River Rch & Prof#=UNT158 IN BECR,Reach-1         , 4
Up Type= 0
Dn Type= 3
Dn Slope=0.005
Boundary for River Rch & Prof#=UNT158 IN BECR,Reach-1         , 5
Up Type= 0
Dn Type= 3
Dn Slope=0.005
Boundary for River Rch & Prof#=UNT158 IN BECR,Reach-1         , 6
Up Type= 0
Dn Type= 3
Dn Slope=0.005
Boundary for River Rch & Prof#=UNT158 IN BECR,Reach-1         , 7
Up Type= 0
Dn Type= 3
Dn Slope=0.005
DSS Import GetInterval= 0
DSS Import GetPeak= 0
DSS Import FillOption= 0

--- UNT158 IN BECR.g01 (geometry) ---

Geom Title=Existing Conditions
Program Version=4.10

River Reach=UNT158 IN BECR  ,Reach-1
Reach XY= 30
      3740107.25       10530435.       3739591.5       10529724.
      3739839.25       10529536.       3739671.5       10528969.
        3739142.       10528385.       3739168.5       10528100.
        3738824.       10527843.      3739038.75       10527595.
        3738691.       10527200.      3738927.75       10526995.
        3738729.       10526822.      3738942.25       10526737.
        3738921.       10526549.      3738612.25       10526245.
        3738335.       10526222.       3738241.5       10526045.
      3738203.25       10525852.      3738394.75       10525682.
      3738298.75       10525570.       3738519.5       10525171.
        3738230.       10524490.        3738346.       10524296.
      3738228.25       10524224.        3738360.       10524082.
       3738450.5       10524215.       3738505.5       10524094.
      3738303.25       10523929.      3738466.25       10523731.
      3737851.25       10523857.      3737066.47      10523111.8

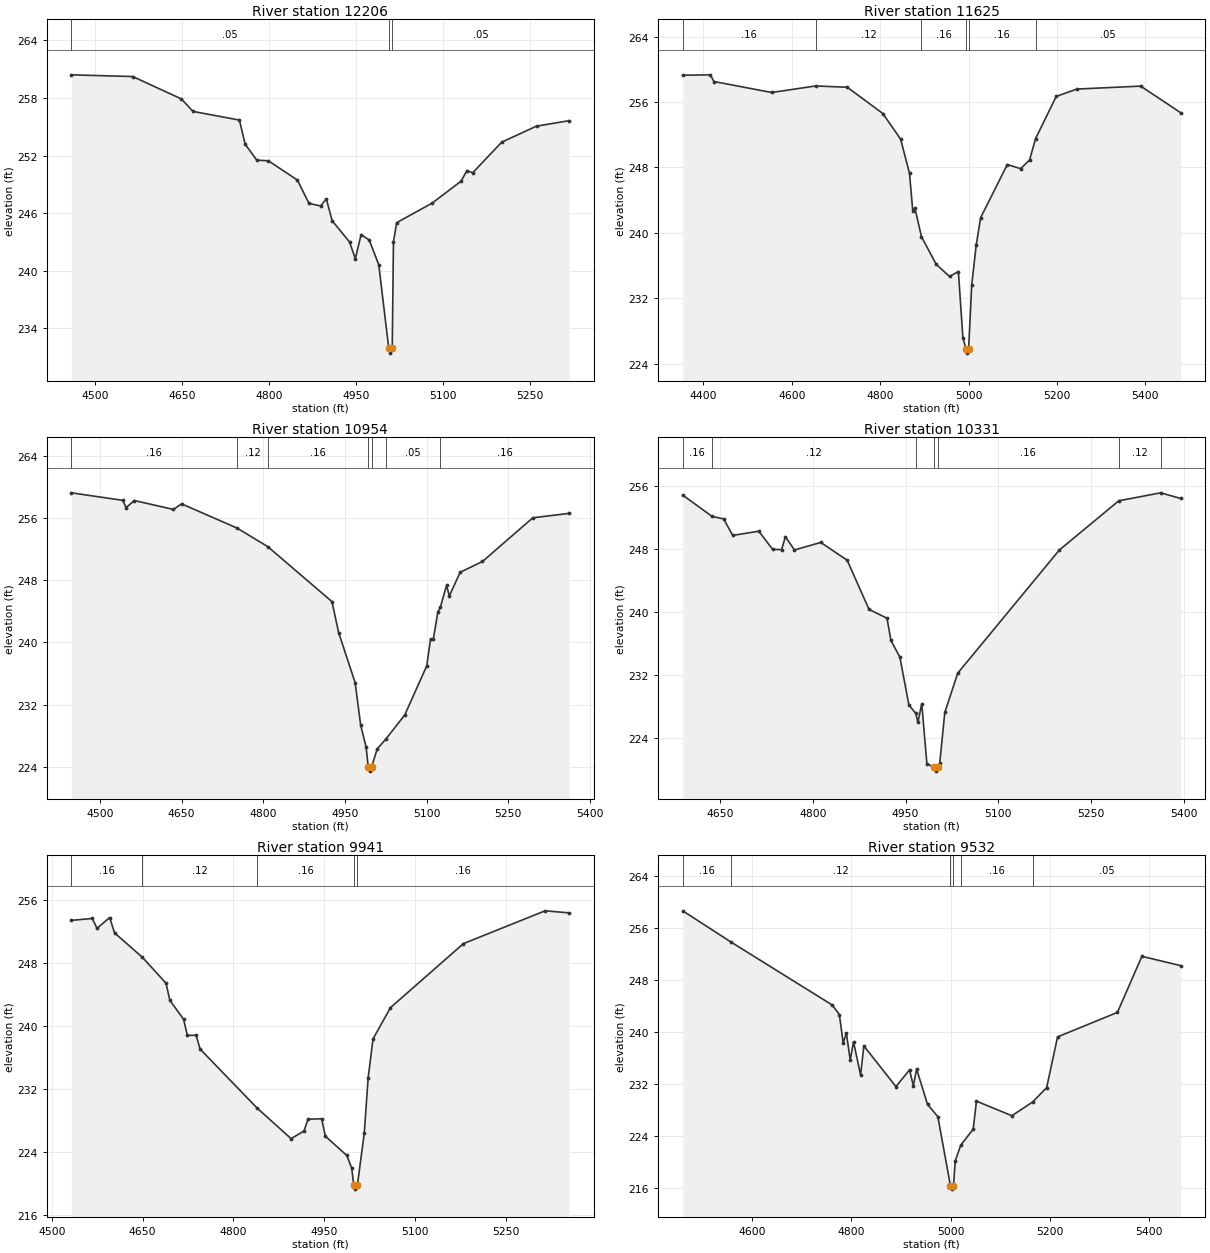
Type RM Length L Ch R = 1 ,12206   ,581,581,581
BEGIN DESCRIPTION:
Mapping XS 25d938cb
END DESCRIPTION:
XS GIS Cut Line= 5
      3740511.97     10530192.69      3740401.34     10530151.55
      3740005.66     10530145.43      3739922.85     10530165.44
      3739663.16     10530177.04
#Sta/Elev= 30
  4458.5   260.4  4564.2  260.22  4648.3  257.89  4668.3  256.59  4748.3  255.69
  4758.3  253.17  4778.3  251.52  4798.3  251.45  4848.3  249.45  4868.3  247.02
  4888.3  246.75  4898.3  247.48  4908.3  245.22  4938.3     243  4948.3  241.27
  4958.3  243.76  4972.3  243.21  4988.8  240.62    5006  231.93  5008.7  231.43
    5012  231.93  5014.1  243.02  5019.6  245.01  5080.7  247.04  5130.8  249.33
  5140.8  250.43  5150.8   250.2  5200.8  253.39  5260.9  255.06  5317.4  255.63
#Mann= 3 ,-1 , 0
  4458.5     .05       0    5006     .04       0    5012     .05       0
Bank Sta=5006,5012
XS Rating Curve= 0 ,0
Exp/Cntr=0.3,0.1

Type RM Length L Ch R = 1 ,11625   ,671,671,671
BEGIN DESCRIPTION:
UNT158 IN BECR 22.0
END DESCRIPTION:
XS GIS Cut Line= 2
      3740329.79     10529738.78      3739209.96     10529860.31
#Sta/Elev= 30
  4353.3  259.27  4415.8  259.32  4423.9   258.5  4554.7  257.16  4654.3  257.96
  4725.7   257.8  4806.1  254.59  4846.4  251.45  4866.5  247.27  4873.8  242.72
  4878.8  243.01  4893.5  239.53  4926.8  236.16    4957  234.66  4977.1  235.27
  4987.2   227.2  4994.2  225.79    4997  225.29  5000.2  225.79  5007.3  233.66
  5017.4   238.5  5027.4  241.85  5087.8  248.35  5117.9  247.85  5138.1   248.9
  5151.7  251.51  5198.4  256.68  5245.3  257.58  5389.5  257.94  5479.7   254.7
#Mann= 6 ,-1 , 0
  4353.3     .16       0  4654.3     .12       0  4893.5     .16       0
  4994.2     .07       0  5000.2     .16       0  5151.7     .05       0
Bank Sta=4994.2,5000.2
XS Rating Curve= 0 ,0
Exp/Cntr=0.3,0.1

Type RM Length L Ch R = 1 ,10954   ,623,623,623
BEGIN DESCRIPTION:
UNT158 IN BECR 21.0
END DESCRIPTION:
XS GIS Cut Line= 4
      3740321.11     10529669.33      3739995.59     10529447.98
      3739730.84     10529408.92      3739484.33     10529465.14
#Sta/Elev= 30
  4447.8  259.26  4542.2  258.29  4548.2  257.35  4563.2  258.27    4635  257.12
    4650  257.84    4752  254.72  4808.5  252.32  4926.2  245.25  4938.5  241.24
  4968.8   234.8  4978.9  229.34    4989  226.48  4992.8  223.92  4995.6  223.42
  4998.8  223.92  5009.2  226.27  5025.5  227.58  5059.8  230.65  5100.2  236.97
  5107.2  240.42  5112.3  240.42  5120.6  243.89  5125.3  244.54  5136.6  247.35
  5141.7  245.98  5161.6  249.03  5202.6  250.42  5294.9  256.04  5361.9  256.62
#Mann= 7 ,-1 , 0
  4447.8     .16       0    4752     .12       0  4808.5     .16       0
  4992.8     .07       0  4998.8     .16       0  5025.5     .05       0
  5125.3     .16       0
Bank Sta=4992.8,4998.8
XS Rating Curve= 0 ,0
Exp/Cntr=0.3,0.1

Type RM Length L Ch R = 1 ,10331   ,390,390,390
BEGIN DESCRIPTION:
UNT158 IN BECR 20.0
END DESCRIPTION:
XS GIS Cut Line= 2
      3739904.44     10528632.02      3739418.36     10529274.33
#Sta/Elev= 30
  4589.4  254.86  4636.8  252.16  4655.7  251.83  4670.3  249.74  4712.5  250.27
  4734.8  247.98  4749.3  247.92  4755.6  249.57  4770.2  247.89  4812.8  248.84
  4855.5  246.59  4890.9  240.33    4920  239.21  4926.3  236.39  4940.8  234.27
  4955.4  228.18  4966.6  227.11  4969.9  225.97  4976.2  228.35  4984.5  220.73
    4996  220.28  4998.8  219.78    5002  220.28  5005.3   220.8  5013.5  227.24
  5034.4  232.23  5198.8  247.88    5295  254.14  5362.9  255.15  5394.9  254.44
#Mann= 7 ,-1 , 0
  4589.4     .16       0  4636.8     .12       0  4966.6     .16       0
    4996     .07       0    5002     .16       0    5295     .12       0
  5362.9     .16       0
Bank Sta=4996,5002
XS Rating Curve= 0 ,0
Exp/Cntr=0.3,0.1

Type RM Length L Ch R = 1 ,9941    ,409,409,409
BEGIN DESCRIPTION:
UNT158 IN BECR 19.0
END DESCRIPTION:
XS GIS Cut Line= 2
      3739756.92     10528458.37       3739105.8      10528961.9
#Sta/Elev= 30
  4532.2  253.41  4566.7  253.65  4574.5  252.39  4595.4  253.77  4603.5  251.82
  4649.2  248.75  4688.6  245.44    4695  243.26  4717.6  240.87  4723.9  238.82
  4738.4  238.84  4744.8   237.1  4839.1  229.61  4895.4  225.72  4916.8   226.7
  4923.2  228.18  4945.8  228.25  4952.1  226.03  4987.5  223.59  4995.6  221.98
    4999  219.82  5001.7  219.32    5005  219.82  5016.4  226.43  5022.8  233.44
  5030.9  238.38  5059.7  242.34  5180.3  250.46  5315.3  254.62  5355.3  254.36
#Mann= 5 ,-1 , 0
  4532.2     .16       0  4649.2     .12       0  4839.1     .16       0
    4999     .07       0    5005     .16       0
Bank Sta=4999,5005
XS Rating Curve= 0 ,0
Exp/Cntr=0.3,0.1

Type RM Length L Ch R = 1 ,9532    ,803,803,803
BEGIN DESCRIPTION:
UNT158 IN BECR 18.0
END DESCRIPTION:
XS GIS Cut Line= 2
      3739648.36     10528033.06      3738994.54     10528795.13
#Sta/Elev= 30
  4459.7  258.63  4558.1  253.79  4761.4  244.16  4775.7   242.7  4783.3  238.36
  4789.9  239.81  4797.6   235.7  4804.2  238.51  4818.5  233.41  4825.1  237.89
  4889.8  231.63  4917.2  234.21  4924.9  231.77  4931.5  234.33  4953.5   228.9
  4974.3  227.02  4999.8  216.39  5002.6  215.89  5005.8  216.39  5009.4  220.23
  5020.6  222.65  5045.6  225.09  5052.2   229.4  5123.6  227.16  5165.8  229.29
  5193.8  231.49  5215.8  239.27  5336.5  243.03  5385.9  251.64  5463.8  250.22
#Mann= 6 ,-1 , 0
  4459.7     .16       0  4558.1     .12       0  4999.8     .07       0
  5005.8     .12       0  5020.6     .16       0  5165.8     .05       0
Bank Sta=4999.8,5005.8
XS Rating Curve= 0 ,0
Exp/Cntr=0.3,0.1

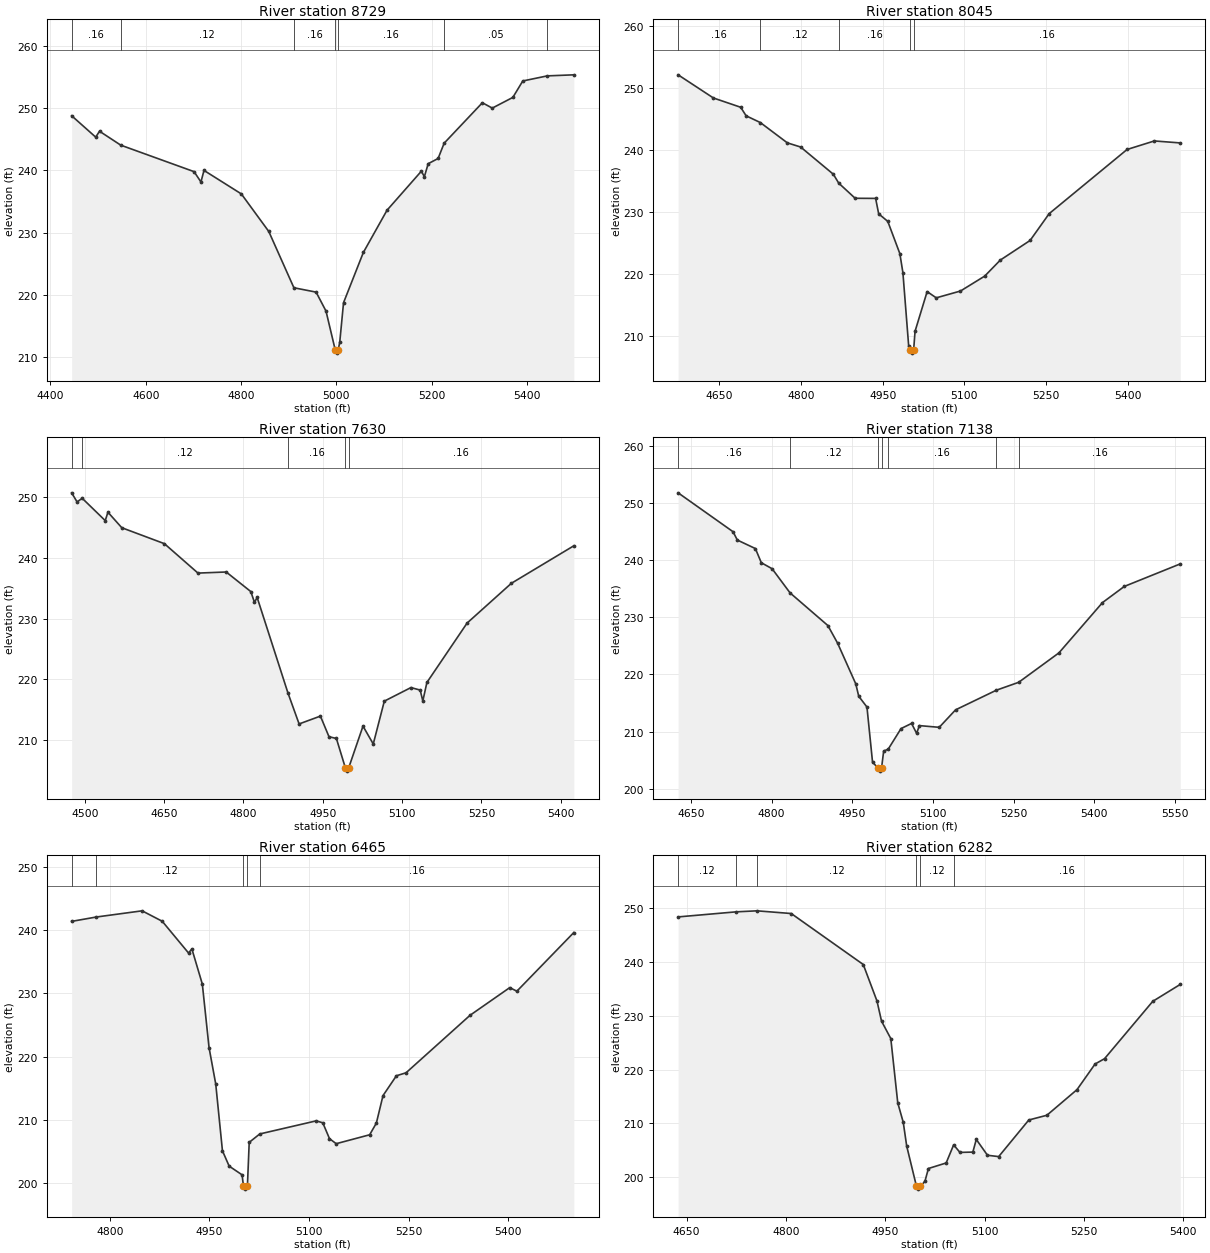
Type RM Length L Ch R = 1 ,8729    ,684,684,684
BEGIN DESCRIPTION:
UNT158 IN BECR 17.0
END DESCRIPTION:
XS GIS Cut Line= 2
      3739366.25     10527655.44      3738543.14     10528313.94
#Sta/Elev= 30
  4444.5  248.78    4495  245.34    4503  246.29  4547.6  244.05  4701.5  239.79
  4715.9  238.13  4722.3  239.99  4800.7  236.21  4858.3  230.17    4911  221.12
  4957.6  220.42  4978.4  217.37  4997.8  211.11  5000.6  210.61  5003.8  211.11
  5007.2  212.33  5015.2  218.72  5056.8   226.8  5106.5  233.59  5178.5  239.86
  5184.9  238.99  5192.9  241.07  5213.7  241.91  5226.4  244.37  5306.6  250.87
  5327.4  250.01  5370.6  251.73  5391.4  254.37  5442.8  255.19  5498.6  255.36
#Mann= 7 ,-1 , 0
  4444.5     .16       0  4547.6     .12       0    4911     .16       0
  4997.8     .07       0  5003.8     .16       0  5226.4     .05       0
  5442.8     .16       0
Bank Sta=4997.8,5003.8
XS Rating Curve= 0 ,0
Exp/Cntr=0.3,0.1

Type RM Length L Ch R = 1 ,8045    ,415,415,415
BEGIN DESCRIPTION:
UNT158 IN BECR 16.0
END DESCRIPTION:
XS GIS Cut Line= 3
      3739444.34     10527525.24      3739097.16     10527507.88
      3738584.98     10527768.31
#Sta/Elev= 30
  4574.4  252.15  4639.2  248.41  4689.3  246.91  4699.3  245.53  4725.4  244.44
    4775  241.16  4799.4  240.49  4859.5  236.09  4869.3  234.66  4899.5  232.21
  4937.1  232.19  4942.7   229.7  4959.4  228.48  4981.6  223.27  4987.2  220.19
  4997.8  208.35  5000.9   207.7  5003.6   207.2  5006.9   207.7  5009.5  210.73
  5031.7  217.14  5048.4  216.13  5092.9  217.23  5137.4  219.64  5166.1  222.23
  5220.8   225.4  5255.8  229.73  5398.8  240.09  5448.9  241.47  5496.6  241.15
#Mann= 5 ,-1 , 0
  4574.4     .16       0  4725.4     .12       0  4869.3     .16       0
  5000.9     .07       0  5006.9     .16       0
Bank Sta=5000.9,5006.9
XS Rating Curve= 0 ,0
Exp/Cntr=0.3,0.1

Type RM Length L Ch R = 1 ,7630    ,492,492,492
BEGIN DESCRIPTION:
UNT158 IN BECR 15.0
END DESCRIPTION:
XS GIS Cut Line= 3
      3739252.87     10527223.06      3738851.84     10527295.97
      3738313.65     10527358.37
#Sta/Elev= 30
  4475.3  250.68  4485.5  249.19  4495.3  249.78  4538.8  246.11  4543.9  247.49
  4570.1  244.94  4650.6  242.32  4714.1  237.48  4767.5  237.66    4814  234.44
  4820.9  232.67    4826  233.47  4884.2  217.77  4905.3  212.67  4945.6  213.96
  4961.8  210.57  4975.8  210.28  4992.9  205.41  4995.6  204.91  4998.9  205.41
  5026.1  212.31  5045.5  209.37  5066.4  216.42  5116.7  218.65  5134.2  218.24
  5139.2  216.45  5146.9  219.49  5222.9  229.26  5306.6   235.8  5424.7  241.97
#Mann= 5 ,-1 , 0
  4475.3     .16       0  4495.3     .12       0  4884.2     .16       0
  4992.9     .07       0  4998.9     .16       0
Bank Sta=4992.9,4998.9
XS Rating Curve= 0 ,0
Exp/Cntr=0.3,0.1

Type RM Length L Ch R = 1 ,7138    ,673,673,673
BEGIN DESCRIPTION:
UNT158 IN BECR 14.0
END DESCRIPTION:
XS GIS Cut Line= 3
      3739288.08     10527095.54      3738836.74     10526969.68
      3738376.68     10527043.47
#Sta/Elev= 30
  4625.9   251.8  4728.1  244.99  4736.1  243.53  4769.7  242.04  4780.7  239.56
  4800.8  238.51  4834.2  234.28  4904.6  228.56  4922.6  225.49  4956.5  218.35
    4962  216.18  4977.3  214.29  4987.7  204.64  4998.4  203.57  5001.1  203.07
  5004.4  203.57  5008.4  206.58  5016.8  206.91  5040.7  210.52  5060.3  211.42
  5069.7  209.69  5074.9  211.04  5111.8  210.74  5142.2   213.8  5218.1  217.24
  5259.6  218.62  5334.6  223.78  5415.6  232.58  5456.2  235.41  5560.4  239.36
#Mann= 7 ,-1 , 0
  4625.9     .16       0  4834.2     .12       0  4998.4     .07       0
  5004.4     .12       0  5016.8     .16       0  5218.1     .12       0
  5259.6     .16       0
Bank Sta=4998.4,5004.4
XS Rating Curve= 0 ,0
Exp/Cntr=0.3,0.1

Type RM Length L Ch R = 1 ,6465    ,183,183,183
BEGIN DESCRIPTION:
UNT158 IN BECR 13.0
END DESCRIPTION:
XS GIS Cut Line= 3
      3739162.22     10526596.44      3739084.13     10526644.16
      3738424.48     10526726.62
#Sta/Elev= 30
  4742.7  241.41  4779.8   242.1  4848.8  243.08  4879.1  241.43  4918.7  236.41
  4923.8  237.04  4939.5  231.49  4949.6  221.45  4959.7  215.67  4969.8  205.11
  4979.9  202.68  4999.4   201.3  5001.4  199.54  5004.1  199.04  5007.4  199.54
  5010.1  206.44    5026  207.77  5110.9  209.84  5120.9  209.54    5131  207.03
  5141.1  206.23  5191.5  207.64  5201.6  209.49  5211.6  213.84  5231.8  216.98
  5246.3  217.45  5342.7  226.55  5402.5  230.93  5413.2  230.36    5499  239.65
#Mann= 5 ,-1 , 0
  4742.7     .16       0  4779.8     .12       0  5001.4     .07       0
  5007.4     .12       0    5026     .16       0
Bank Sta=5001.4,5007.4
XS Rating Curve= 0 ,0
Exp/Cntr=0.3,0.1

Type RM Length L Ch R = 1 ,6282    ,166,166,166
BEGIN DESCRIPTION:
UNT158 IN BECR 12.0
END DESCRIPTION:
XS GIS Cut Line= 3
      3739226.79     10526394.94      3738849.61     10526510.19
      3738499.61     10526610.19
#Sta/Elev= 30
  4637.1  248.37  4724.6  249.31  4756.2   249.5  4807.9     249  4916.7  239.53
  4937.4  232.76  4944.3  229.01  4958.3  225.77  4968.8  213.83  4977.1  210.22
  4982.3  205.81  4997.1  198.31  4999.9  197.81  5003.1  198.31  5009.9  199.29
  5015.1  201.64  5041.9  202.67  5053.2  206.03  5062.7  204.63  5082.2  204.69
  5087.4  207.04  5104.3   204.1  5121.2  203.85  5166.7  210.65    5194  211.53
  5239.5  216.29  5266.8  221.05  5281.1  222.04  5353.9  232.69  5395.5  235.84
#Mann= 6 ,-1 , 0
  4637.1     .12       0  4724.6     .16       0  4756.2     .12       0
  4997.1     .07       0  5003.1     .12       0  5053.2     .16       0
Bank Sta=4997.1,5003.1
XS Rating Curve= 0 ,0
Exp/Cntr=0.3,0.1

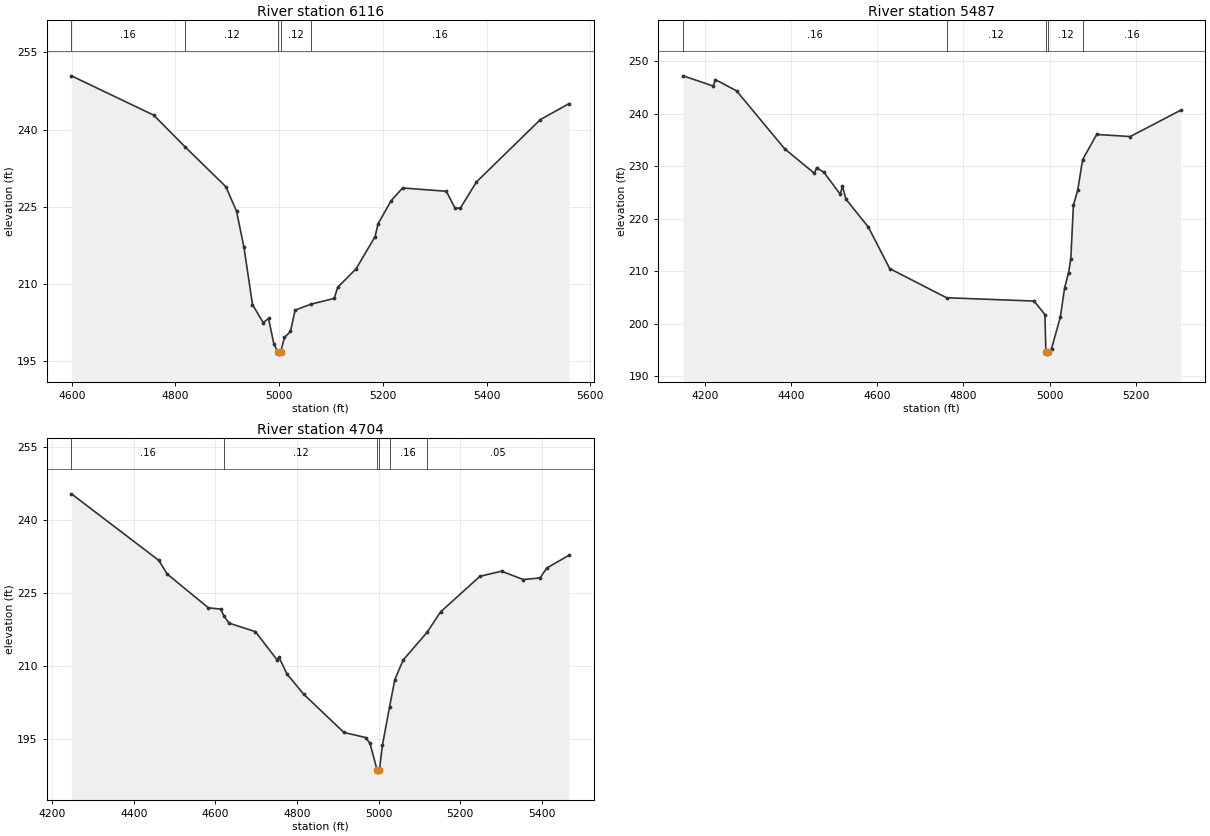
Type RM Length L Ch R = 1 ,6116    ,629,629,629
BEGIN DESCRIPTION:
UNT158 IN BECR 11.0
END DESCRIPTION:
XS GIS Cut Line= 2
      3739149.28     10526318.63      3738216.08     10526539.99
#Sta/Elev= 30
  4599.4  250.46  4758.1  242.82  4818.9  236.63  4897.1  228.94  4917.7  224.19
  4932.1  217.14  4948.5  206.04  4969.1  202.53  4979.5  203.33  4989.6  198.45
  4996.9  196.91  4999.6  196.41  5002.9  196.91  5010.2  199.66  5021.7  200.81
  5030.7  204.96  5061.8  206.13  5106.1  207.23  5112.9   209.4  5148.3  212.99
  5184.9  219.24  5190.5  221.69  5215.7   226.2  5237.9  228.68  5322.3  228.04
    5339  224.76  5349.3  224.76  5380.2  229.84  5503.5  241.96  5558.5  245.04
#Mann= 5 ,-1 , 0
  4599.4     .16       0  4818.9     .12       0  4996.9     .07       0
  5002.9     .12       0  5061.8     .16       0
Bank Sta=4996.9,5002.9
XS Rating Curve= 0 ,0
Exp/Cntr=0.3,0.1

Type RM Length L Ch R = 1 ,5487    ,783,783,783
BEGIN DESCRIPTION:
UNT158 IN BECR 10.0
END DESCRIPTION:
XS GIS Cut Line= 2
      3739131.86     10525993.12      3737994.71     10526188.43
#Sta/Elev= 30
    4150   247.2  4219.8  245.26  4224.8  246.48    4274  244.34  4385.7  233.29
  4454.6  228.63  4459.7  229.71    4477   228.8  4514.6  224.63  4519.6   226.2
  4527.7  223.71  4579.6  218.41  4629.2  210.48  4761.1  204.93    4964   204.3
  4989.3  201.73  4991.4  194.69  4994.2  194.19  4997.4  194.69  5004.6  195.25
  5024.9   201.2    5035  206.85  5044.2  209.73  5049.3  212.37  5055.3  222.54
  5065.5  225.48  5076.6  231.23  5109.3  236.03  5187.2  235.64  5303.8  240.63
#Mann= 5 ,-1 , 0
    4150     .16       0  4761.1     .12       0  4991.4     .07       0
  4997.4     .12       0  5076.6     .16       0
Bank Sta=4991.4,4997.4
XS Rating Curve= 0 ,0
Exp/Cntr=0.3,0.1

Type RM Length L Ch R = 1 ,4704    ,0,0,0
BEGIN DESCRIPTION:
UNT158 IN BECR 9.0
END DESCRIPTION:
XS GIS Cut Line= 3
      3739051.52     10525539.02      3738641.77     10525601.53
      3737850.08     10525455.69
#Sta/Elev= 30
  4247.1  245.41  4461.5  231.71  4481.7  228.93  4582.9  221.96  4613.2  221.69
  4620.7  220.34  4633.4  218.81    4698  217.07    4751   211.3  4756.1  211.76
  4775.6  208.34  4816.3  204.21  4915.1  196.32  4968.2  195.28    4979   194.1
  4996.3  188.66  4999.1  188.16  5002.3  188.66  5009.5  193.67  5027.1  201.63
    5040  207.21  5060.3  211.22    5119  216.92  5151.9  221.11  5248.5  228.44
  5301.5   229.5  5354.6  227.78  5395.9  228.11  5412.7  230.16  5466.6  232.76
#Mann= 6 ,-1 , 0
  4247.1     .16       0  4620.7     .12       0  4996.3     .07       0
  5002.3     .12       0  5027.1     .16       0    5119     .05       0
Bank Sta=4996.3,5002.3
XS Rating Curve= 0 ,0
Exp/Cntr=0.3,0.1

Chan Stop Cuts=-1
Use User Specified Reach Order=0
Composite Channel Slope=5