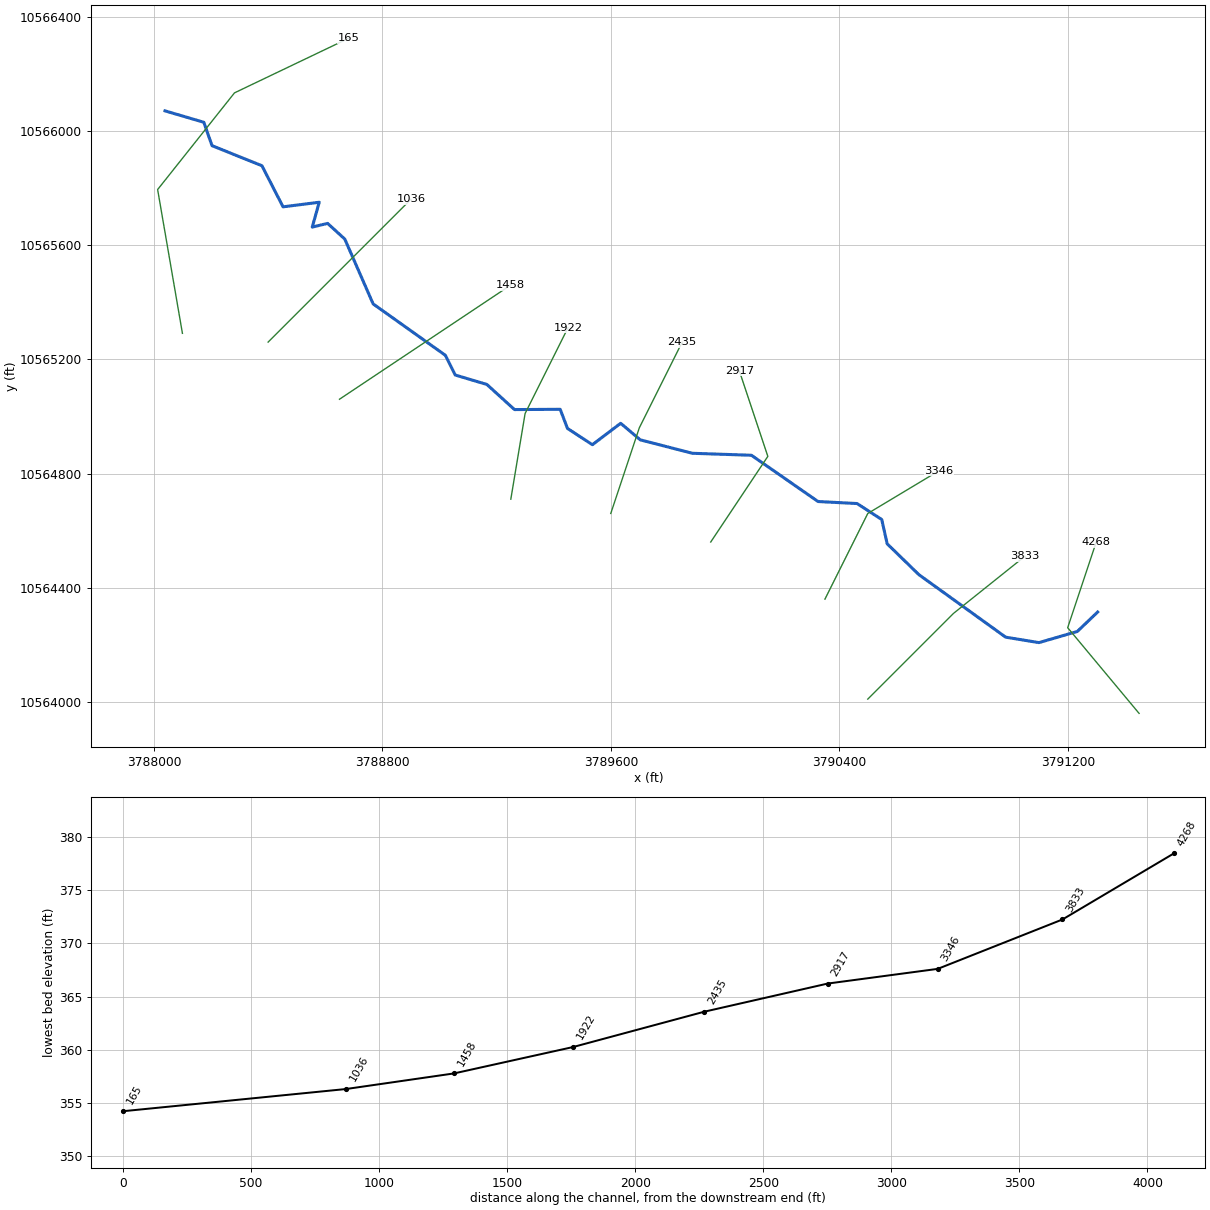
--- UNT159 IN BECR.prj (project) ---

Proj Title=UNT159 IN BECR Base Level Engineering
Current Plan=p01
Default Exp/Contr=0.3,0.1
English Units
Geom File=g01
Flow File=f01
Plan File=p01
BEGIN DESCRIPTION:
UNT159 IN BECR
END DESCRIPTION:

--- UNT159 IN BECR.p01 (plan) ---

Plan Title=Multiple Run
Short Identifier=Multiple
Geom File=g01
Flow File=f01
Subcritical Flow
K Sum by GR= 0
Std Step Tol= 0.01
Critical Tol= 0.01
Num of Std Step Trials= 20
Max Error Tol= 0.3
Flow Tol Ratio= 0.001
Split Flow NTrial= 30
Split Flow Tol= 0.02
Split Flow Ratio= 0.02
Log Output Level= 0
Friction Slope Method= 1
Unsteady Friction Slope Method= 2
Unsteady Bridges Friction Slope Method= 1
Parabolic Critical Depth
Global Vel Dist=  1 , 1 , 1
Global Log Level= 0
CheckData=True
Encroach Param= -1, 0, 0, 0
BEGIN DESCRIPTION:
Multiple Run
END DESCRIPTION:

--- UNT159 IN BECR.f01 (steady flow) ---

Flow Title=Multiple
Number of Profiles=7
Profile Names=10-year,25-year,50-year,1pct_min,100-year,1pct_plu,500-year
River Rch & RM= UNT159 IN BECR,Reach-1,4268
     463     617     742     657     889    1202    1278
Boundary for River Rch & Prof#=UNT159 IN BECR,Reach-1,1
Up Type=0
Dn Type=3
Dn Slope=0.005
Boundary for River Rch & Prof#=UNT159 IN BECR,Reach-1,2
Up Type=0
Dn Type=3
Dn Slope=0.005
Boundary for River Rch & Prof#=UNT159 IN BECR,Reach-1,3
Up Type=0
Dn Type=3
Dn Slope=0.005
Boundary for River Rch & Prof#=UNT159 IN BECR,Reach-1,4
Up Type=0
Dn Type=3
Dn Slope=0.005
Boundary for River Rch & Prof#=UNT159 IN BECR,Reach-1,5
Up Type=0
Dn Type=3
Dn Slope=0.005
Boundary for River Rch & Prof#=UNT159 IN BECR,Reach-1,6
Up Type=0
Dn Type=3
Dn Slope=0.005
Boundary for River Rch & Prof#=UNT159 IN BECR,Reach-1,7
Up Type=0
Dn Type=3
Dn Slope=0.005

--- UNT159 IN BECR.g01 (geometry) ---

Geom Title=Existing Conditions

River Reach=UNT159 IN BECR,Reach-1
Reach XY= 30
      3791304.50     10564315.00      3791233.25     10564247.00
      3791099.00     10564208.00      3790982.50     10564227.00
      3790678.50     10564446.00      3790567.50     10564554.00
      3790548.50     10564639.00      3790462.00     10564695.00
      3790325.50     10564702.00      3790092.25     10564864.00
      3789885.25     10564871.00      3789703.00     10564918.00
      3789634.25     10564976.00      3789535.25     10564901.00
      3789448.00     10564958.00      3789422.50     10565025.00
      3789262.50     10565024.00      3789165.75     10565112.00
      3789055.00     10565145.00      3789020.50     10565214.00
      3788767.50     10565394.00      3788668.25     10565621.00
      3788608.00     10565676.00      3788554.25     10565663.00
      3788578.75     10565750.00      3788452.00     10565734.00
      3788378.00     10565878.00      3788203.50     10565948.00
      3788174.50     10566030.00      3788038.75     10566070.00

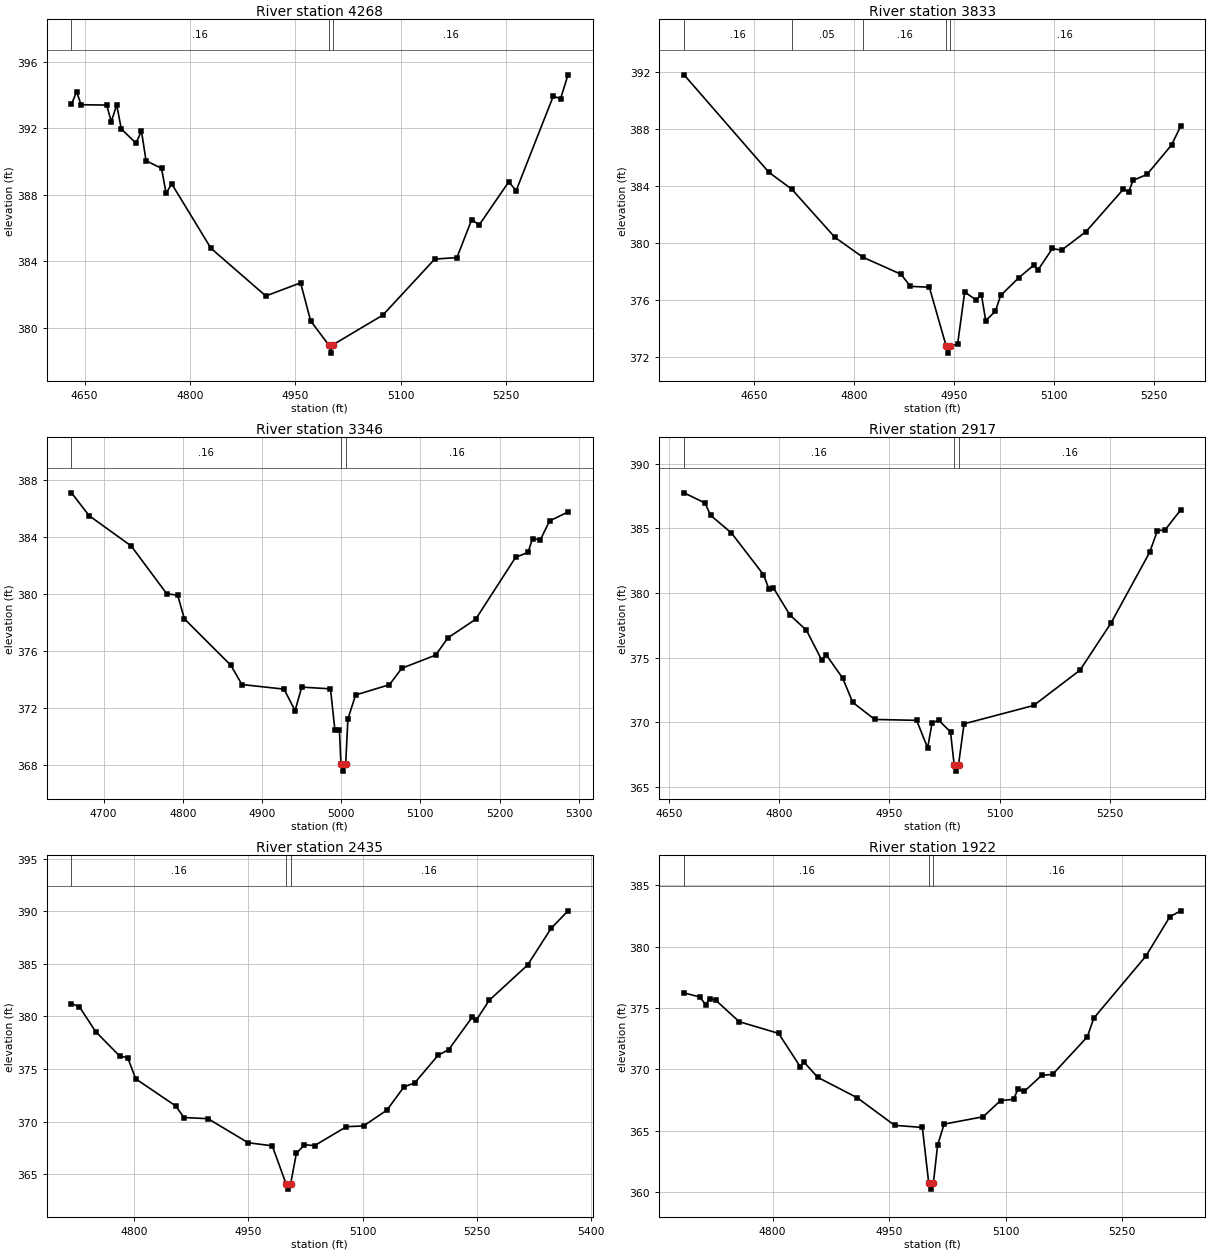
Type RM Length L Ch R = 1,4268,435,435,435
BEGIN DESCRIPTION:
UNT159 IN BECR 9.0
END DESCRIPTION:
XS GIS Cut Line= 3
      3791449.60     10563960.19      3791199.61     10564260.19
      3791299.60     10564560.16
#Sta/Elev= 30
  4631.3  393.44  4638.5  394.21  4645.0  393.42  4681.4  393.40  4687.9  392.40
  4695.7  393.41  4702.2  391.96  4723.1  391.11  4730.9  391.84  4737.4  390.05
  4759.5  389.59  4766.0  388.08  4773.8  388.67  4829.8  384.78  4907.9  381.91
  4957.4  382.70  4971.7  380.41  4997.3  378.97  5000.1  378.47  5003.3  378.97
  5074.5  380.76  5148.3  384.13  5179.9  384.22  5201.0  386.51  5211.5  386.18
  5253.7  388.78  5264.2  388.25  5317.0  393.93  5327.5  393.79  5338.0  395.22
#Mann=3,-1,0
  4631.3    0.16       0  4997.3    0.07       0  5003.3    0.16       0
Bank Sta=4997.3,5003.3
Exp/Cntr=0.3,0.1

Type RM Length L Ch R = 1,3833,487,487,487
BEGIN DESCRIPTION:
UNT159 IN BECR 8.0
END DESCRIPTION:
XS GIS Cut Line= 3
      3790499.64     10564010.22      3790799.61     10564310.19
      3791049.63     10564510.20
#Sta/Elev= 30
  4545.4  391.80  4672.6  384.95  4706.8  383.77  4771.6  380.38  4813.4  378.99
  4870.6  377.79  4884.8  376.94  4913.1  376.88  4938.3  372.75  4941.1  372.25
  4944.3  372.75  4955.5  372.88  4966.1  376.54  4983.2  375.99  4991.2  376.35
  4997.6  374.54  5012.0  375.18  5020.0  376.30  5047.3  377.55  5069.7  378.43
  5076.1  378.10  5097.7  379.60  5111.3  379.48  5148.1  380.79  5204.1  383.77
  5212.1  383.58  5218.5  384.39  5239.4  384.80  5276.2  386.87  5289.8  388.18
#Mann=5,-1,0
  4545.4    0.16       0  4706.8    0.05       0  4813.4    0.16       0
  4938.3    0.07       0  4944.3    0.16       0
Bank Sta=4938.3,4944.3
Exp/Cntr=0.3,0.1

Type RM Length L Ch R = 1,3346,429,429,429
BEGIN DESCRIPTION:
UNT159 IN BECR 7.0
END DESCRIPTION:
XS GIS Cut Line= 3
      3790349.62     10564360.22      3790499.61     10564660.19
      3790749.59     10564810.17
#Sta/Elev= 30
  4659.5  387.08  4681.8  385.48  4734.9  383.36  4779.7  380.02  4793.6  379.91
  4802.0  378.26  4860.7  375.01  4874.7  373.66  4927.8  373.34  4941.8  371.84
  4950.2  373.48  4986.5  373.36  4992.1  370.47  4997.8  370.47  4999.7  368.10
  5002.4  367.60  5005.7  368.10  5008.5  371.25  5018.2  372.93  5061.0  373.65
  5076.5  374.80  5119.3  375.72  5134.8  376.93  5169.8  378.23  5220.3  382.57
  5235.9  382.91  5241.7  383.88  5251.4  383.78  5263.1  385.11  5286.4  385.74
#Mann=3,-1,0
  4659.5    0.16       0  4999.7    0.07       0  5005.7    0.16       0
Bank Sta=4999.7,5005.7
Exp/Cntr=0.3,0.1

Type RM Length L Ch R = 1,2917,482,482,482
BEGIN DESCRIPTION:
UNT159 IN BECR 6.0
END DESCRIPTION:
XS GIS Cut Line= 3
      3789949.61     10564560.19      3790149.61     10564860.19
      3790049.60     10565160.21
#Sta/Elev= 30
  4670.0  387.76  4698.5  386.97  4706.1  386.02  4734.6  384.65  4778.2  381.43
  4785.7  380.31  4791.7  380.41  4814.2  378.31  4836.8  377.12  4857.8  374.80
  4863.8  375.22  4886.3  373.41  4899.9  371.54  4929.9  370.22  4987.0  370.15
  5002.0  368.02  5008.0  369.94  5017.0  370.17  5033.2  369.25  5038.1  366.72
  5040.8  366.22  5044.1  366.72  5051.6  369.88  5146.5  371.30  5209.8  374.04
  5251.9  377.68  5304.6  383.15  5315.2  384.83  5325.7  384.89  5346.8  386.43
#Mann=3,-1,0
  4670.0    0.16       0  5038.1    0.07       0  5044.1    0.16       0
Bank Sta=5038.1,5044.1
Exp/Cntr=0.3,0.1

Type RM Length L Ch R = 1,2435,513,513,513
BEGIN DESCRIPTION:
UNT159 IN BECR 5.0
END DESCRIPTION:
XS GIS Cut Line= 3
      3789599.62     10564660.21      3789699.61     10564960.19
      3789849.60     10565260.18
#Sta/Elev= 30
  4717.8  381.22  4728.3  380.90  4749.4  378.56  4781.0  376.23  4791.6  376.07
  4802.1  374.06  4854.8  371.47  4865.3  370.38  4897.0  370.27  4949.7  367.98
  4981.3  367.69  4999.4  364.07  5002.1  363.57  5005.4  364.07  5012.9  366.96
  5023.5  367.79  5036.8  367.71  5078.7  369.51  5101.1  369.58  5131.8  371.09
  5154.2  373.30  5168.2  373.67  5198.9  376.30  5212.9  376.84  5243.6  379.92
  5249.2  379.66  5266.0  381.53  5316.3  384.88  5347.1  388.36  5369.4  390.04
#Mann=3,-1,0
  4717.8    0.16       0  4999.4    0.07       0  5005.4    0.16       0
Bank Sta=4999.4,5005.4
Exp/Cntr=0.3,0.1

Type RM Length L Ch R = 1,1922,464,464,464
BEGIN DESCRIPTION:
UNT159 IN BECR 4.0
END DESCRIPTION:
XS GIS Cut Line= 3
      3789249.61     10564710.19      3789299.61     10565010.19
      3789449.59     10565310.15
#Sta/Elev= 30
  4686.0  376.24  4706.3  375.90  4713.9  375.27  4718.9  375.78  4726.5  375.66
  4757.0  373.89  4807.7  372.94  4835.5  370.23  4840.6  370.58  4858.3  369.35
  4909.0  367.69  4957.2  365.44  4992.9  365.27  5001.1  360.74  5003.9  360.24
  5007.1  360.74  5012.5  363.81  5020.9  365.54  5071.2  366.14  5093.6  367.46
  5110.3  367.56  5115.9  368.37  5124.3  368.22  5146.7  369.52  5160.6  369.59
  5205.4  372.66  5213.7  374.18  5280.8  379.24  5311.6  382.44  5325.5  382.93
#Mann=3,-1,0
  4686.0    0.16       0  5001.1    0.07       0  5007.1    0.16       0
Bank Sta=5001.1,5007.1
Exp/Cntr=0.3,0.1

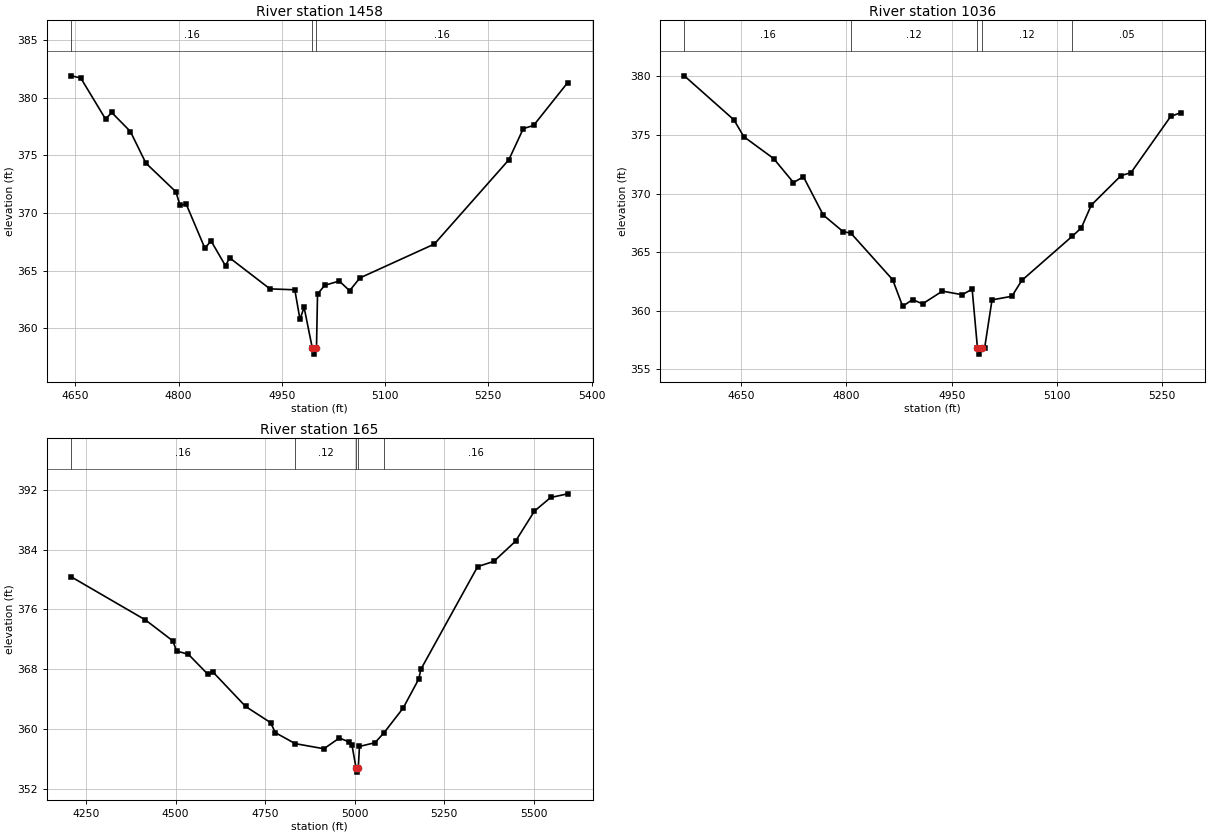
Type RM Length L Ch R = 1,1458,422,422,422
BEGIN DESCRIPTION:
UNT159 IN BECR 3.0
END DESCRIPTION:
XS GIS Cut Line= 3
      3788649.64     10565060.21      3788949.61     10565260.19
      3789249.63     10565460.21
#Sta/Elev= 30
  4644.3  381.90  4657.8  381.71  4693.8  378.15  4702.8  378.72  4729.9  377.07
  4752.4  374.33  4796.0  371.84  4802.0  370.68  4811.0  370.77  4838.1  366.95
  4847.1  367.58  4868.1  365.42  4874.1  366.11  4932.7  363.42  4968.8  363.34
  4976.3  360.78  4982.3  361.82  4994.3  358.26  4997.1  357.76  5000.3  358.26
  5001.8  362.97  5012.3  363.73  5033.4  364.10  5048.4  363.26  5063.4  364.37
  5171.6  367.31  5279.7  374.61  5300.8  377.32  5315.8  377.60  5365.4  381.32
#Mann=3,-1,0
  4644.3    0.16       0  4994.3    0.07       0  5000.3    0.16       0
Bank Sta=4994.3,5000.3
Exp/Cntr=0.3,0.1

Type RM Length L Ch R = 1,1036,871,871,871
BEGIN DESCRIPTION:
UNT159 IN BECR 2.0
END DESCRIPTION:
XS GIS Cut Line= 3
      3788399.64     10565260.22      3788699.61     10565560.19
      3788899.63     10565760.21
#Sta/Elev= 30
  4569.1  380.05  4639.8  376.29  4653.9  374.85  4696.3  372.99  4724.6  370.94
  4738.8  371.43  4767.0  368.17  4795.3  366.75  4806.4  366.62  4866.0  362.64
  4880.2  360.37  4894.3  360.95  4908.5  360.58  4936.8  361.67  4965.0  361.36
  4979.2  361.84  4986.8  356.79  4989.5  356.29  4992.8  356.79  4996.9  356.79
  5007.5  360.92  5035.8  361.23  5049.9  362.58  5121.9  366.36  5134.7  367.06
  5148.9  369.01  5191.3  371.53  5205.5  371.78  5262.0  376.58  5276.2  376.90
#Mann=5,-1,0
  4569.1    0.16       0  4806.4    0.12       0  4986.8    0.07       0
  4992.8    0.12       0  5121.9    0.05       0
Bank Sta=4986.8,4992.8
Exp/Cntr=0.3,0.1

Type RM Length L Ch R = 1,165,0,0,0
BEGIN DESCRIPTION:
UNT159 IN BECR 1.0
END DESCRIPTION:
XS GIS Cut Line= 4
      3788099.65     10565291.01      3788012.85     10565794.48
      3788281.94     10566133.02      3788681.26     10566324.00
#Sta/Elev= 30
  4209.2  380.34  4415.9  374.58  4492.5  371.77  4502.6  370.43  4535.7  369.98
  4590.5  367.29  4604.1  367.62  4695.4  363.00  4765.2  360.83  4778.5  359.49
  4833.8  358.02  4914.2  357.33  4957.3  358.77  4984.7  358.24  4992.7  357.79
  5004.1  354.70  5006.9  354.20  5010.1  354.70  5013.5  357.64  5056.8  358.14
  5082.5  359.50  5135.3  362.77  5179.2  366.68  5184.8  367.96  5343.5  381.73
  5388.8  382.43  5449.3  385.13  5502.2  389.17  5547.5  390.99  5595.2  391.48
#Mann=5,-1,0
  4209.2    0.16       0  4833.8    0.12       0  5004.1    0.07       0
  5010.1    0.12       0  5082.5    0.16       0
Bank Sta=5004.1,5010.1
Exp/Cntr=0.3,0.1

Chan Stop Cuts=-1