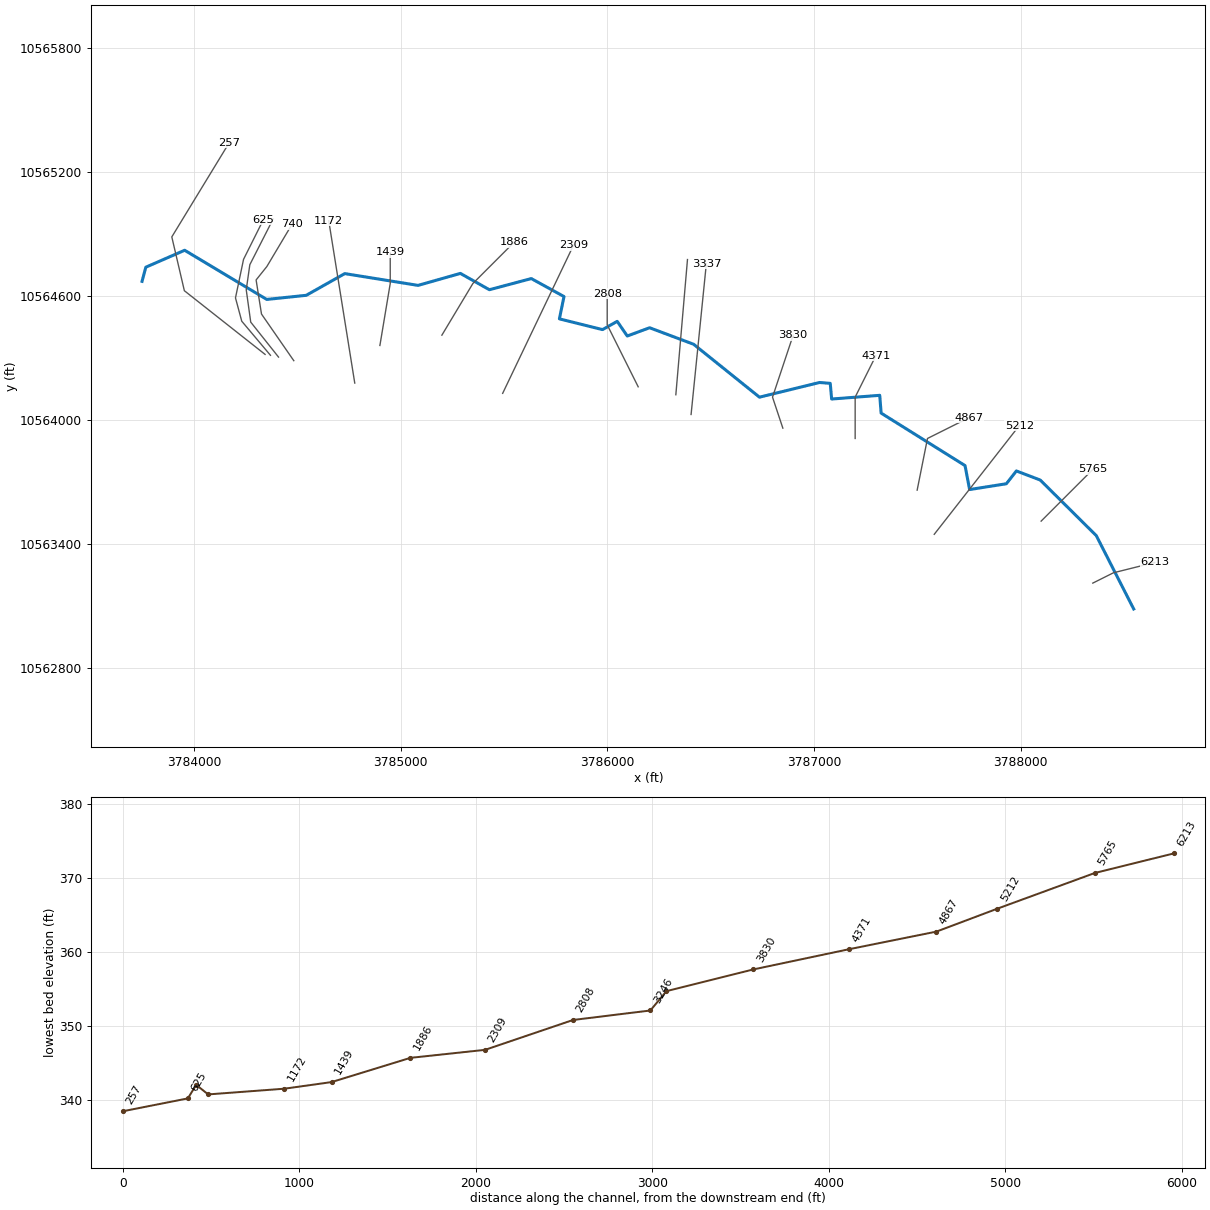
--- UNT160 IN BECR.prj (project) ---

Proj Title=UNT160 IN BECR Base Level Engineering
Current Plan=p01
Default Exp/Contr=0.3,0.1
English Units
Geom File=g01
Flow File=f01
Plan File=p01
BEGIN DESCRIPTION:
UNT160 IN BECR
END DESCRIPTION:

--- UNT160 IN BECR.p01 (plan) ---

Plan Title=Multiple Run
Short Identifier=Multiple
Geom File=g01
Flow File=f01
Subcritical Flow
K Sum by GR= 0
Std Step Tol= 0.01
Critical Tol= 0.01
Num of Std Step Trials= 20
Max Error Tol= 0.3
Flow Tol Ratio= 0.001
Split Flow NTrial= 30
Split Flow Tol= 0.02
Split Flow Ratio= 0.02
Log Output Level= 0
Friction Slope Method= 1
Unsteady Friction Slope Method= 2
Unsteady Bridges Friction Slope Method= 1
Parabolic Critical Depth
Global Vel Dist=  1 , 1 , 1
Global Log Level= 0
CheckData=True
Encroach Param= -1, 0, 0, 0
BEGIN DESCRIPTION:
Multiple Run
END DESCRIPTION:

--- UNT160 IN BECR.f01 (steady flow) ---

Flow Title=Multiple
Number of Profiles=7
Profile Names=10-year,25-year,50-year,1pct_min,100-year,1pct_plu,500-year
River Rch & RM= UNT160 IN BECR,Reach-1,6213
     425     560     670     590     797    1078    1132
Boundary for River Rch & Prof#=UNT160 IN BECR,Reach-1,1
Up Type=0
Dn Type=3
Dn Slope=0.005
Boundary for River Rch & Prof#=UNT160 IN BECR,Reach-1,2
Up Type=0
Dn Type=3
Dn Slope=0.005
Boundary for River Rch & Prof#=UNT160 IN BECR,Reach-1,3
Up Type=0
Dn Type=3
Dn Slope=0.005
Boundary for River Rch & Prof#=UNT160 IN BECR,Reach-1,4
Up Type=0
Dn Type=3
Dn Slope=0.005
Boundary for River Rch & Prof#=UNT160 IN BECR,Reach-1,5
Up Type=0
Dn Type=3
Dn Slope=0.005
Boundary for River Rch & Prof#=UNT160 IN BECR,Reach-1,6
Up Type=0
Dn Type=3
Dn Slope=0.005
Boundary for River Rch & Prof#=UNT160 IN BECR,Reach-1,7
Up Type=0
Dn Type=3
Dn Slope=0.005

--- UNT160 IN BECR.g01 (geometry) ---

Geom Title=Existing Conditions

River Reach=UNT160 IN BECR,Reach-1
Reach XY= 30
      3788547.50     10563085.00      3788366.50     10563440.00
      3788095.25     10563709.00      3787979.75     10563753.00
      3787931.25     10563691.00      3787753.50     10563663.00
      3787731.25     10563779.00      3787325.25     10564033.00
      3787318.50     10564119.00      3787085.75     10564101.00
      3787079.00     10564177.00      3787027.00     10564181.00
      3786736.50     10564110.00      3786418.00     10564366.00
      3786204.75     10564446.00      3786096.75     10564406.00
      3786048.00     10564477.00      3785977.00     10564437.00
      3785768.25     10564489.00      3785790.50     10564597.00
      3785632.25     10564684.00      3785429.50     10564630.00
      3785289.00     10564709.00      3785084.25     10564651.00
      3784729.50     10564708.00      3784543.25     10564603.00
      3784352.00     10564583.00      3783954.75     10564821.00
      3783766.75     10564739.00      3783748.56     10564670.52

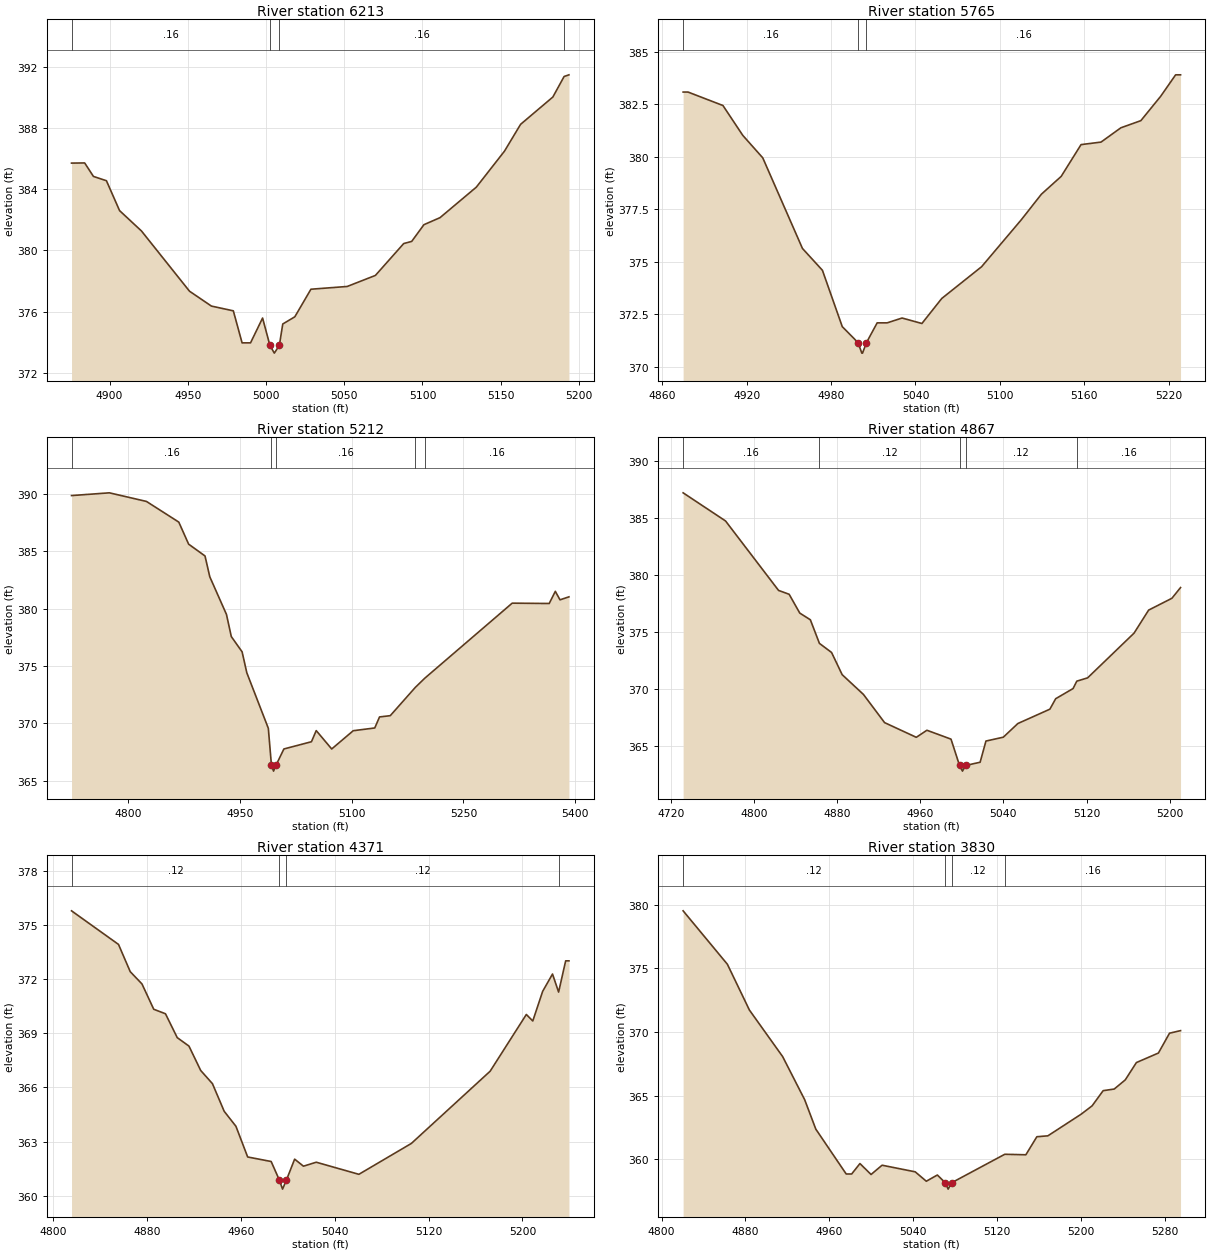
Type RM Length L Ch R = 1,6213,448,448,448
BEGIN DESCRIPTION:
UNT160 IN BECR 13.0
END DESCRIPTION:
XS GIS Cut Line= 3
      3788349.63     10563210.20      3788449.61     10563260.19
      3788649.57     10563310.18
#Sta/Elev= 30
  4875.7  385.70  4884.1  385.71  4889.7  384.83  4898.0  384.55  4906.4  382.60
  4920.4  381.27  4951.1  377.34  4965.1  376.37  4979.1  376.06  4984.7  373.97
  4990.1  373.97  4997.8  375.59  5002.5  373.80  5005.3  373.30  5008.5  373.80
  5010.7  375.20  5018.4  375.67  5028.7  377.47  5051.9  377.65  5069.9  378.37
  5088.0  380.45  5093.1  380.59  5100.9  381.68  5111.2  382.14  5134.4  384.13
  5152.4  386.48  5162.7  388.23  5183.3  390.01  5190.5  391.35  5193.6  391.46
#Mann=4,-1,0
  4875.7    0.16       0  5002.5    0.07       0  5008.5    0.16       0
  5190.5    0.05       0
Bank Sta=5002.5,5008.5
Exp/Cntr=0.3,0.1

Type RM Length L Ch R = 1,5765,553,553,553
BEGIN DESCRIPTION:
UNT160 IN BECR 12.0
END DESCRIPTION:
XS GIS Cut Line= 3
      3788099.61     10563510.19      3788199.61     10563610.19
      3788349.57     10563760.15
#Sta/Elev= 28
  4874.9  383.08  4878.4  383.08  4903.2  382.44  4917.3  381.02  4931.5  379.95
  4959.7  375.64  4973.9  374.60  4988.0  371.92  4999.2  371.16  5001.9  370.66
  5002.4  370.66  5005.2  371.16  5012.8  372.10  5019.9  372.10  5030.5  372.33
  5044.6  372.07  5058.7  373.26  5087.0  374.77  5115.3  377.01  5129.5  378.22
  5143.6  379.07  5157.7  380.58  5171.9  380.70  5186.0  381.38  5200.2  381.72
  5214.3  382.88  5224.9  383.90  5228.4  383.90
#Mann=3,-1,0
  4874.9    0.16       0  4999.2    0.07       0  5005.2    0.16       0
Bank Sta=4999.2,5005.2
Exp/Cntr=0.3,0.1

Type RM Length L Ch R = 1,5212,345,345,345
BEGIN DESCRIPTION:
UNT160 IN BECR 11.0
END DESCRIPTION:
XS GIS Cut Line= 2
      3787582.33     10563446.38      3787993.76     10563972.38
#Sta/Elev= 30
  4723.9  389.84  4774.7  390.08  4824.5  389.33  4867.9  387.53  4881.1  385.61
  4903.1  384.58  4909.5  382.77  4931.9  379.49  4938.4  377.56  4952.9  376.23
  4959.2  374.41  4988.1  369.57  4992.3  366.34  4995.1  365.84  4998.3  366.34
  5009.0  367.77  5046.0  368.40  5052.4  369.37  5073.2  367.77  5102.1  369.36
  5131.0  369.60  5137.4  370.56  5151.8  370.67  5185.4  373.13  5198.1  373.93
  5315.5  380.47  5365.2  380.44  5373.4  381.50  5379.7  380.76  5391.7  381.02
#Mann=5,-1,0
  4723.9    0.16       0  4992.3    0.07       0  4998.3    0.16       0
  5185.4    0.12       0  5198.1    0.16       0
Bank Sta=4992.3,4998.3
Exp/Cntr=0.3,0.1

Type RM Length L Ch R = 1,4867,496,496,496
BEGIN DESCRIPTION:
UNT160 IN BECR 10.0
END DESCRIPTION:
XS GIS Cut Line= 3
      3787499.61     10563660.20      3787549.61     10563910.19
      3787749.56     10564010.17
#Sta/Elev= 30
  4731.9  387.19  4772.7  384.72  4823.7  378.62  4833.9  378.28  4844.1  376.63
  4854.3  376.04  4863.0  373.97  4874.7  373.17  4884.9  371.22  4905.3  369.49
  4925.7  367.01  4956.2  365.72  4966.4  366.34  4989.6  365.56  4997.8  363.25
  5000.6  362.75  5003.8  363.25  5017.6  363.53  5023.2  365.39  5039.9  365.73
  5053.9  366.93  5084.7  368.19  5090.3  369.11  5107.0  370.00  5110.6  370.65
  5121.0  370.94  5165.7  374.87  5179.7  376.89  5202.1  377.93  5210.4  378.87
#Mann=5,-1,0
  4731.9    0.16       0  4863.0    0.12       0  4997.8    0.07       0
  5003.8    0.12       0  5110.6    0.16       0
Bank Sta=4997.8,5003.8
Exp/Cntr=0.3,0.1

Type RM Length L Ch R = 1,4371,541,541,541
BEGIN DESCRIPTION:
UNT160 IN BECR 9.0
END DESCRIPTION:
XS GIS Cut Line= 3
      3787199.61     10563910.20      3787199.61     10564110.19
      3787299.61     10564310.20
#Sta/Elev= 30
  4816.0  375.78  4856.0  373.92  4866.0  372.41  4876.0  371.73  4886.0  370.33
  4896.0  370.08  4906.0  368.76  4916.0  368.29  4926.0  366.94  4936.0  366.21
  4946.0  364.68  4956.0  363.85  4966.0  362.15  4986.0  361.90  4993.0  360.87
  4995.7  360.37  4999.0  360.87  5006.0  362.03  5013.5  361.64  5024.4  361.86
  5060.7  361.19  5105.4  362.90  5172.5  366.90  5203.3  370.04  5208.8  369.68
  5217.2  371.32  5225.6  372.28  5230.8  371.28  5236.8  373.01  5239.6  373.01
#Mann=4,-1,0
  4816.0    0.12       0  4993.0    0.07       0  4999.0    0.12       0
  5230.8    0.16       0
Bank Sta=4993,4999
Exp/Cntr=0.3,0.1

Type RM Length L Ch R = 1,3830,493,493,493
BEGIN DESCRIPTION:
UNT160 IN BECR 8.0
END DESCRIPTION:
XS GIS Cut Line= 3
      3786849.61     10563960.20      3786799.61     10564110.19
      3786899.60     10564410.16
#Sta/Elev= 30
  4820.6  379.53  4862.8  375.33  4883.8  371.73  4915.5  368.07  4936.5  364.68
  4947.1  362.37  4976.1  358.84  4981.3  358.84  4989.2  359.66  4999.8  358.80
  5010.3  359.53  5041.9  359.01  5052.5  358.27  5063.0  358.76  5070.6  358.15
  5073.3  357.65  5076.6  358.15  5127.3  360.39  5147.4  360.35  5157.9  361.77
  5168.4  361.84  5200.1  363.54  5210.6  364.20  5221.1  365.39  5231.7  365.52
  5242.2  366.24  5252.8  367.60  5273.8  368.35  5284.4  369.91  5294.9  370.11
#Mann=4,-1,0
  4820.6    0.12       0  5070.6    0.07       0  5076.6    0.12       0
  5127.3    0.16       0
Bank Sta=5070.6,5076.6
Exp/Cntr=0.3,0.1

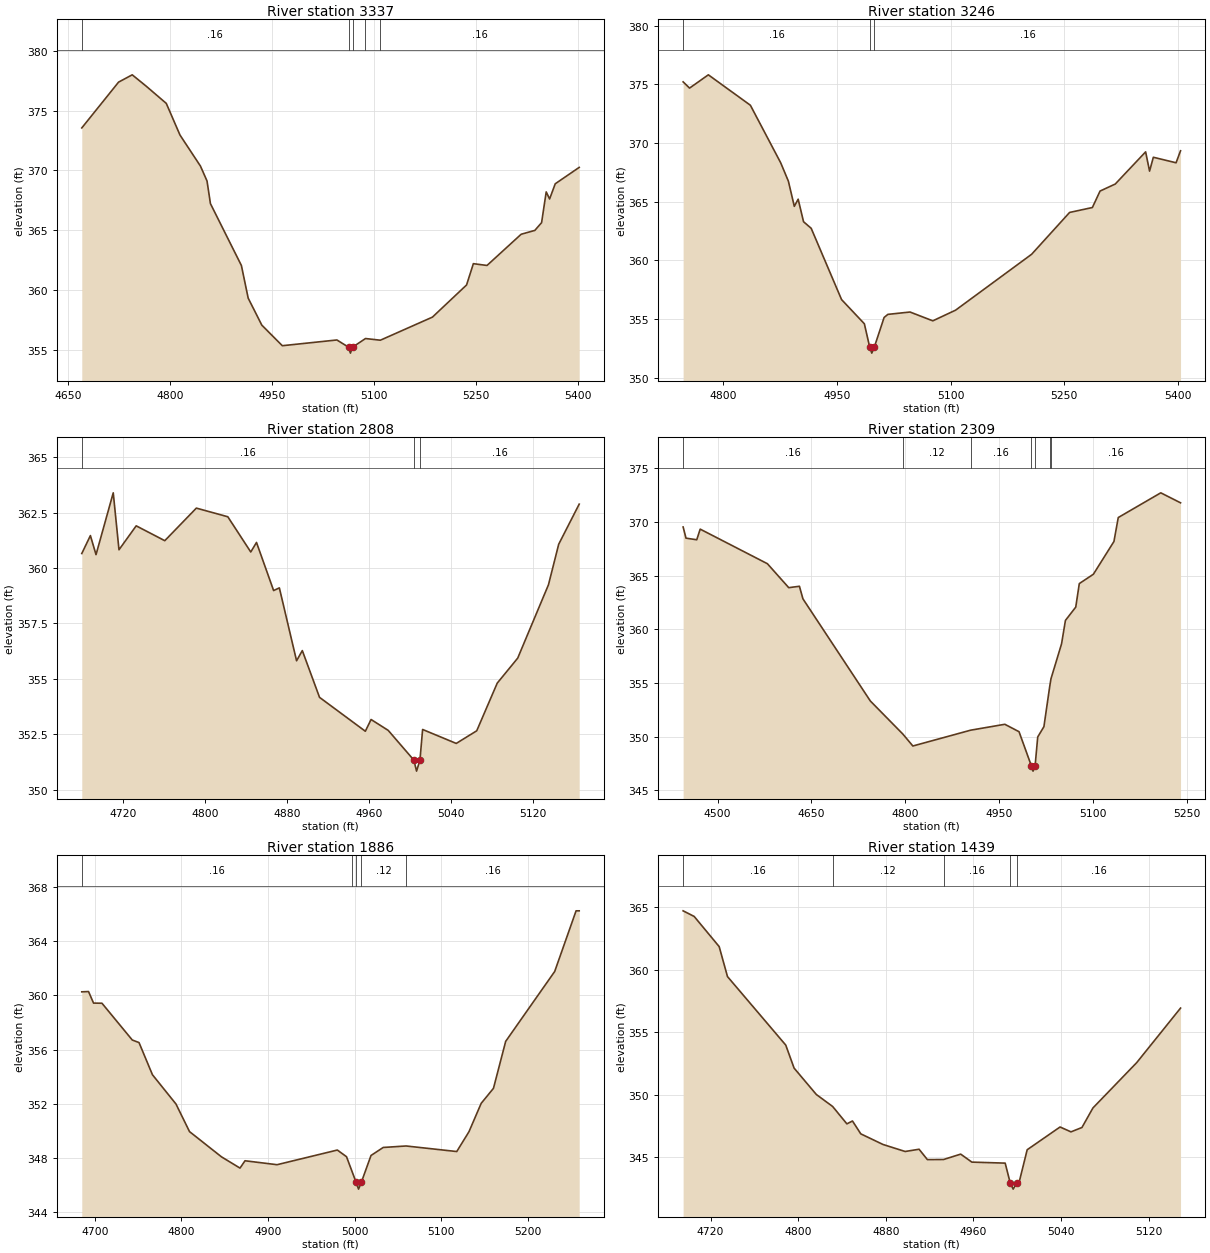
Type RM Length L Ch R = 1,3337,91,91,91
BEGIN DESCRIPTION:
UNT160 IN BECR 7.0
END DESCRIPTION:
XS GIS Cut Line= 2
      3786405.56     10564026.29      3786479.32     10564755.27
#Sta/Elev= 30
  4669.7  373.55  4723.9  377.38  4744.0  377.99  4764.4  377.05  4794.2  375.60
  4814.3  372.96  4844.5  370.36  4854.2  369.11  4859.2  367.22  4904.8  362.05
  4914.8  359.32  4934.9  357.06  4965.1  355.34  5045.5  355.82  5062.6  355.22
  5065.4  354.72  5068.6  355.22  5087.6  355.94  5109.5  355.80  5186.2  357.73
  5236.5  360.42  5246.5  362.20  5266.6  362.05  5316.9  364.66  5337.0  364.98
  5347.0  365.63  5353.8  368.20  5358.8  367.61  5367.1  368.88  5402.4  370.25
#Mann=5,-1,0
  4669.7    0.16       0  5062.6    0.07       0  5068.6    0.16       0
  5087.6    0.12       0  5109.5    0.16       0
Bank Sta=5062.6,5068.6
Exp/Cntr=0.3,0.1

Type RM Length L Ch R = 1,3246,438,438,438
BEGIN DESCRIPTION:
Mapping XS 45f2f9a0
END DESCRIPTION:
XS GIS Cut Line= 2
      3786331.77     10564121.73      3786388.11     10564776.11
#Sta/Elev= 30
  4746.8  375.21  4755.3  374.68  4780.1  375.81  4835.6  373.22  4875.7  368.31
  4885.8  366.75  4893.6  364.61  4898.7  365.22  4905.8  363.30  4915.9  362.74
  4956.0  356.67  4986.1  354.61  4993.2  352.61  4995.9  352.11  4999.2  352.61
  5012.2  355.15  5017.2  355.41  5046.4  355.61  5076.5  354.86  5106.6  355.77
  5207.0  360.53  5257.1  364.09  5287.2  364.51  5297.3  365.91  5317.4  366.51
  5357.5  369.25  5362.7  367.61  5367.7  368.79  5397.7  368.32  5403.6  369.34
#Mann=3,-1,0
  4746.8    0.16       0  4993.2    0.07       0  4999.2    0.16       0
Bank Sta=4993.2,4999.2
Exp/Cntr=0.3,0.1

Type RM Length L Ch R = 1,2808,499,499,499
BEGIN DESCRIPTION:
UNT160 IN BECR 6.0
END DESCRIPTION:
XS GIS Cut Line= 3
      3786149.60     10564160.21      3785999.61     10564460.19
      3785999.61     10564610.20
#Sta/Elev= 30
  4679.5  360.65  4687.9  361.46  4693.4  360.60  4710.2  363.39  4715.8  360.82
  4732.6  361.90  4760.5  361.23  4791.3  362.70  4822.0  362.31  4844.4  360.72
  4850.0  361.15  4866.7  358.98  4872.3  359.10  4889.1  355.81  4894.7  356.27
  4911.5  354.16  4956.2  352.63  4961.8  353.16  4978.5  352.67  5003.5  351.33
  5006.2  350.83  5009.5  351.33  5012.1  352.71  5044.9  352.08  5064.9  352.65
  5084.9  354.80  5104.9  355.93  5134.9  359.24  5144.9  361.07  5164.9  362.88
#Mann=3,-1,0
  4679.5    0.16       0  5003.5    0.07       0  5009.5    0.16       0
Bank Sta=5003.5,5009.5
Exp/Cntr=0.3,0.1

Type RM Length L Ch R = 1,2309,423,423,423
BEGIN DESCRIPTION:
UNT160 IN BECR 5.0
END DESCRIPTION:
XS GIS Cut Line= 2
      3785493.76     10564128.62      3785836.98     10564846.27
#Sta/Elev= 30
  4444.9  369.53  4449.5  368.49  4466.7  368.34  4472.2  369.33  4579.7  366.11
  4613.8  363.88  4630.9  364.01  4636.5  362.84  4744.3  353.33  4796.3  350.25
  4812.3  349.14  4904.6  350.61  4959.4  351.16  4982.1  350.47  5001.8  347.30
  5004.5  346.80  5007.8  347.30  5012.0  349.98  5021.9  350.94  5031.1  354.65
  5033.2  355.40  5050.1  358.65  5056.3  360.83  5072.8  362.07  5078.5  364.26
  5101.0  365.13  5133.9  368.18  5140.8  370.41  5208.8  372.71  5240.4  371.78
#Mann=7,-1,0
  4444.9    0.16       0  4796.3    0.12       0  4904.6    0.16       0
  5001.8    0.07       0  5007.8    0.16       0  5031.1    0.12       0
  5033.2    0.16       0
Bank Sta=5001.8,5007.8
Exp/Cntr=0.3,0.1

Type RM Length L Ch R = 1,1886,447,447,447
BEGIN DESCRIPTION:
UNT160 IN BECR 4.0
END DESCRIPTION:
XS GIS Cut Line= 3
      3785199.61     10564410.19      3785349.61     10564660.19
      3785549.62     10564860.20
#Sta/Elev= 30
  4685.0  360.26  4692.8  360.28  4698.6  359.43  4708.3  359.42  4743.3  356.71
  4751.1  356.52  4766.6  354.15  4793.8  351.99  4809.4  349.96  4846.3  348.10
  4867.7  347.27  4873.5  347.81  4910.5  347.52  4980.1  348.60  4990.7  348.11
  4997.1  347.02  5001.8  346.22  5004.6  345.72  5007.8  346.22  5019.0  348.20
  5033.1  348.79  5059.5  348.90  5118.0  348.49  5132.1  349.95  5146.2  352.04
  5160.4  353.15  5174.5  356.61  5231.1  361.76  5255.8  366.23  5259.4  366.23
#Mann=5,-1,0
  4685.0    0.16       0  4997.1    0.12       0  5001.8    0.07       0
  5007.8    0.12       0  5059.5    0.16       0
Bank Sta=5001.8,5007.8
Exp/Cntr=0.3,0.1

Type RM Length L Ch R = 1,1439,267,267,267
BEGIN DESCRIPTION:
UNT160 IN BECR 3.0
END DESCRIPTION:
XS GIS Cut Line= 3
      3784899.61     10564360.22      3784949.61     10564660.19
      3784949.61     10564810.18
#Sta/Elev= 30
  4695.0  364.71  4705.1  364.26  4727.9  361.85  4735.5  359.45  4788.7  353.97
  4796.3  352.13  4816.6  350.02  4831.5  349.06  4844.5  347.67  4849.6  347.90
  4857.2  346.87  4877.5  346.02  4897.7  345.46  4910.4  345.64  4918.0  344.81
  4932.8  344.82  4948.4  345.25  4958.6  344.61  4989.0  344.53  4993.6  342.95
  4996.3  342.45  4999.6  342.95  5001.6  342.95  5009.1  345.60  5039.1  347.42
  5049.1  347.03  5059.1  347.38  5069.1  348.94  5109.1  352.57  5149.1  356.93
#Mann=5,-1,0
  4695.0    0.16       0  4831.5    0.12       0  4932.8    0.16       0
  4993.6    0.07       0  4999.6    0.16       0
Bank Sta=4993.6,4999.6
Exp/Cntr=0.3,0.1

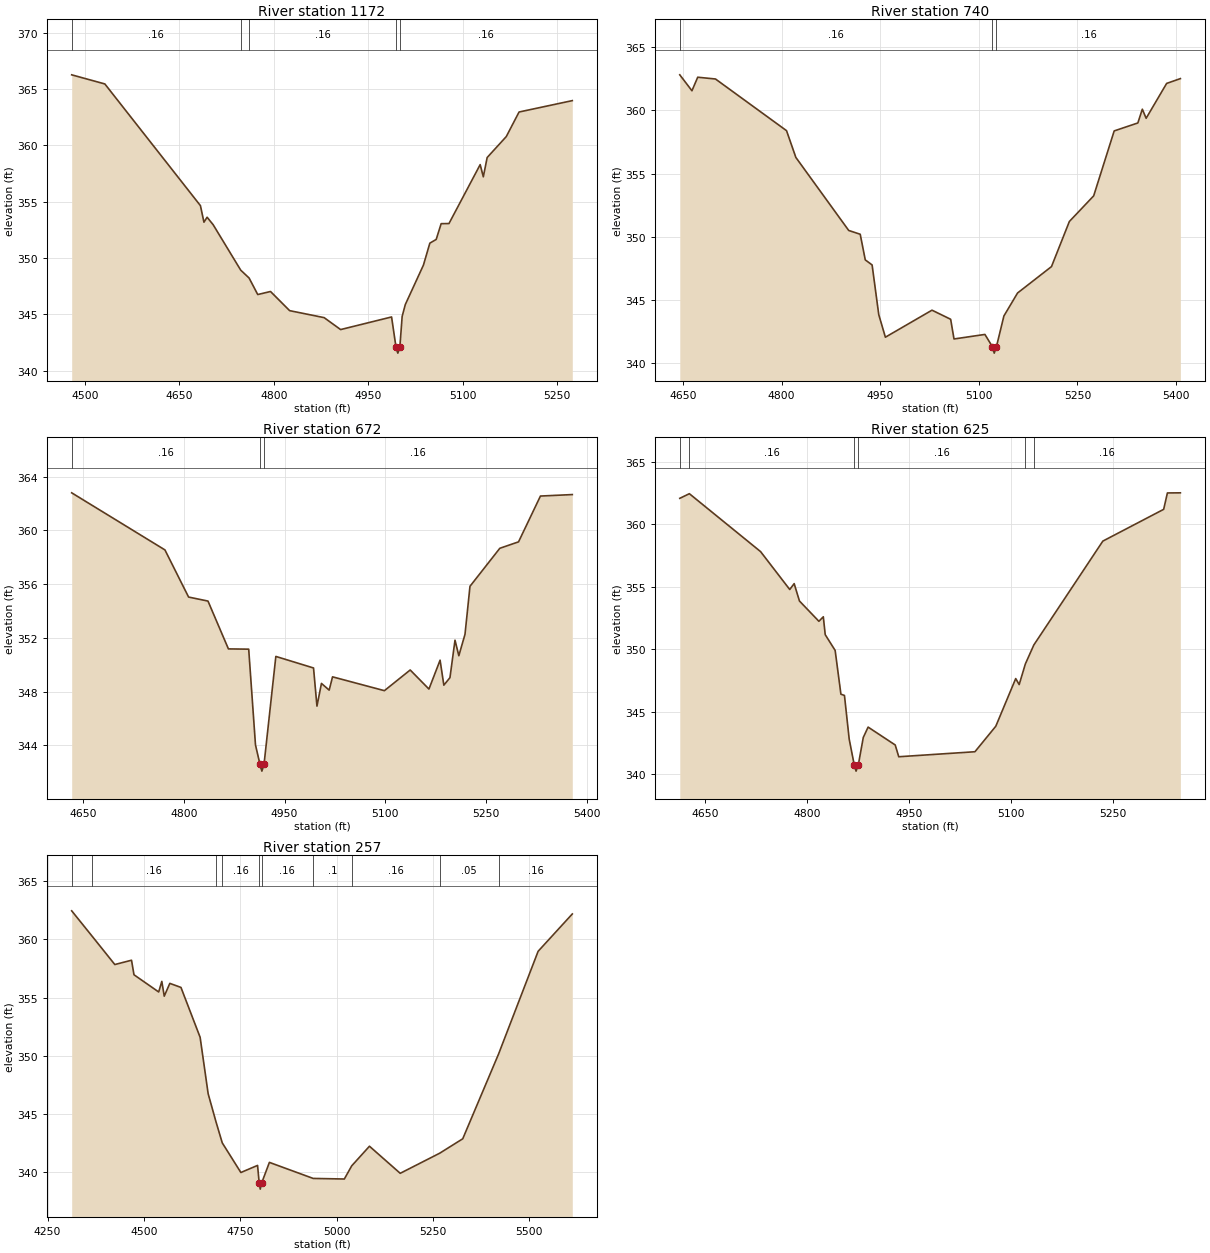
Type RM Length L Ch R = 1,1172,432,432,432
BEGIN DESCRIPTION:
UNT160 IN BECR 2.0
END DESCRIPTION:
XS GIS Cut Line= 2
      3784777.95     10564178.18      3784652.08     10564963.76
#Sta/Elev= 30
  4478.8  366.26  4531.5  365.45  4683.4  354.65  4689.0  353.18  4694.0  353.62
  4703.6  352.96  4747.5  348.92  4760.7  348.23  4774.5  346.76  4794.8  347.03
  4825.2  345.33  4880.0  344.71  4906.2  343.65  4987.2  344.77  4994.3  342.06
  4997.1  341.56  5000.3  342.06  5004.0  344.82  5009.0  345.87  5037.8  349.37
  5048.0  351.32  5058.1  351.65  5066.0  353.05  5078.4  353.06  5128.0  358.29
  5133.0  357.21  5139.1  358.92  5169.5  360.78  5189.8  362.96  5274.4  363.97
#Mann=5,-1,0
  4478.8    0.16       0  4747.5    0.12       0  4760.7    0.16       0
  4994.3    0.07       0  5000.3    0.16       0
Bank Sta=4994.3,5000.3
Exp/Cntr=0.3,0.1

Type RM Length L Ch R = 1,740,68,68,68
BEGIN DESCRIPTION:
Mapping XS 2fa58265
END DESCRIPTION:
XS GIS Cut Line= 5
      3784482.83     10564286.64      3784326.56     10564512.36
      3784300.52     10564677.29      3784352.60     10564742.40
      3784473.76     10564945.76
#Sta/Elev= 30
  4645.1  362.82  4663.6  361.56  4672.4  362.63  4699.4  362.49  4807.5  358.40
  4821.7  356.28  4902.1  350.50  4919.6  350.20  4927.3  348.17  4937.7  347.77
  4947.8  343.84  4957.9  342.05  5028.8  344.19  5057.2  343.47  5062.3  341.91
  5109.3  342.27  5120.8  341.29  5123.5  340.79  5126.8  341.29  5138.2  343.73
  5159.0  345.55  5210.6  347.64  5237.8  351.21  5274.8  353.24  5306.0  358.38
  5342.0  359.01  5348.8  360.10  5354.6  359.38  5385.8  362.14  5406.7  362.52
#Mann=3,-1,0
  4645.1    0.16       0  5120.8    0.07       0  5126.8    0.16       0
Bank Sta=5120.8,5126.8
Exp/Cntr=0.3,0.1

Type RM Length L Ch R = 1,672,47,47,47
BEGIN DESCRIPTION:
Mapping XS 42b142df
END DESCRIPTION:
XS GIS Cut Line= 5
      3784409.01     10564304.05      3784274.48     10564473.30
      3784252.78     10564629.55      3784270.14     10564751.08
      3784383.00     10564972.46
#Sta/Elev= 30
  4633.2  362.80  4772.0  358.55  4807.2  355.04  4836.1  354.74  4866.5  351.18
  4896.7  351.16  4906.8  344.03  4913.5  342.58  4916.3  342.08  4919.5  342.58
  4937.1  350.62  4993.2  349.76  4998.3  346.92  5005.0  348.61  5016.5  348.11
  5021.5  349.10  5098.7  348.07  5137.1  349.61  5165.0  348.19  5181.6  350.34
  5187.2  348.48  5196.3  349.04  5203.8  351.83  5209.5  350.67  5218.7  352.27
  5226.1  355.84  5270.5  358.67  5298.4  359.15  5331.0  362.56  5378.4  362.67
#Mann=3,-1,0
  4633.2    0.16       0  4913.5    0.07       0  4919.5    0.16       0
Bank Sta=4913.5,4919.5
Exp/Cntr=0.3,0.1

Type RM Length L Ch R = 1,625,368,368,368
BEGIN DESCRIPTION:
Mapping XS 6acefd91
END DESCRIPTION:
XS GIS Cut Line= 5
      3784369.94     10564312.73      3784231.07     10564477.64
      3784200.69     10564590.49      3784239.75     10564777.12
      3784335.22     10564968.05
#Sta/Elev= 30
  4612.5  362.06  4626.6  362.43  4731.4  357.80  4774.3  354.77  4780.8  355.24
  4788.6  353.85  4817.2  352.23  4823.7  352.59  4826.5  351.16  4841.1  349.90
  4849.6  346.40  4854.8  346.30  4861.8  342.80  4869.2  340.75  4871.9  340.25
  4875.2  340.75  4882.5  342.94  4889.6  343.77  4929.5  342.34  4934.7  341.40
  5046.8  341.80  5077.5  343.84  5106.8  347.65  5111.9  347.17  5121.0  348.82
  5133.5  350.34  5235.0  358.64  5324.5  361.18  5330.0  362.49  5349.1  362.50
#Mann=6,-1,0
  4612.5    0.05       0  4626.6    0.16       0  4869.2    0.07       0
  4875.2    0.16       0  5121.0    0.05       0  5133.5    0.16       0
Bank Sta=4869.2,4875.2
Exp/Cntr=0.3,0.1

Type RM Length L Ch R = 1,257,0,0,0
BEGIN DESCRIPTION:
UNT160 IN BECR 1.0
END DESCRIPTION:
XS GIS Cut Line= 4
      3784343.91     10564317.06      3783953.30     10564625.21
      3783892.53     10564885.63      3784170.33     10565341.39
#Sta/Elev= 30
  4312.5  362.46  4365.2  360.29  4424.4  357.84  4467.7  358.21  4474.1  356.96
  4538.2  355.48  4546.3  356.39  4552.6  355.12  4567.1  356.22  4596.0  355.87
  4645.7  351.58  4666.5  346.73  4686.6  344.34  4703.1  342.50  4751.4  339.95
  4794.7  340.56  4799.0  339.02  4801.7  338.52  4805.0  339.02  4825.4  340.82
  4939.0  339.44  5019.8  339.39  5038.9  340.52  5085.0  342.21  5164.8  339.88
  5267.2  341.61  5327.0  342.85  5419.8  350.13  5522.6  358.98  5611.2  362.19
#Mann=10,-1,0
  4312.5    0.05       0  4365.2    0.16       0  4686.6    0.05       0
  4703.1    0.16       0  4799.0    0.07       0  4805.0    0.16       0
  4939.0     0.1       0  5038.9    0.16       0  5267.2    0.05       0
  5419.8    0.16       0
Bank Sta=4799,4805
Exp/Cntr=0.3,0.1

Chan Stop Cuts=-1