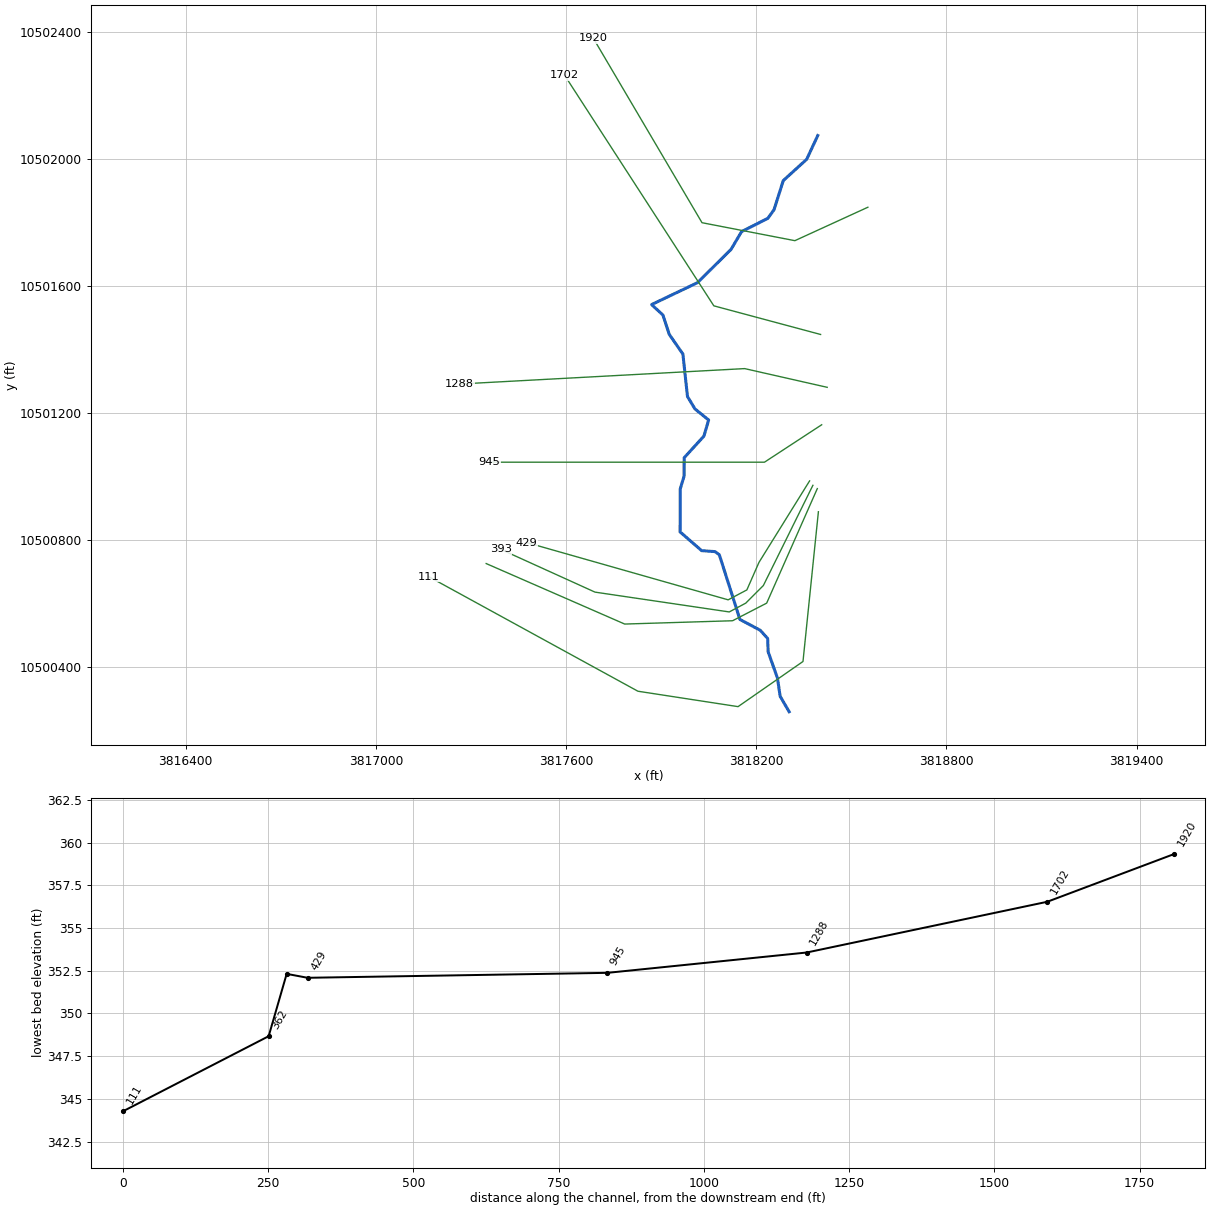
--- UNT161 IN BECR.prj (project) ---

Proj Title=UNT161 IN BECR Base Level Engineering
Current Plan=p01
Default Exp/Contr=0.3,0.1
English Units
Geom File=g01
Flow File=f01
Plan File=p01
Y Axis Title=Elevation
X Axis Title(PF)=Main Channel Distance
X Axis Title(XS)=Station
BEGIN DESCRIPTION:
UNT161 IN BECR
END DESCRIPTION:
DSS Export Rating Curves= 0
DSS Export Rating Curve Sorted= 0
DSS Export Volume Flow Curves= 0
DXF OffsetX= 0
DXF OffsetY= 0
DXF ScaleX= 1
DXF ScaleY= 10

--- UNT161 IN BECR.p01 (plan) ---

Plan Title=Multiple Run
Short Identifier=Multiple
Geom File=g01
Flow File=f01
Subcritical Flow
K Sum by GR= 0
Std Step Tol= 0.01
Critical Tol= 0.01
Num of Std Step Trials= 20
Max Error Tol= 0.3
Flow Tol Ratio= 0.001
Split Flow NTrial= 30
Split Flow Tol= 0.02
Split Flow Ratio= 0.02
Log Output Level= 0
Friction Slope Method= 1
Unsteady Friction Slope Method= 2
Unsteady Bridges Friction Slope Method= 1
Parabolic Critical Depth
Global Vel Dist=  1 , 1 , 1
Global Log Level= 0
CheckData=True
Encroach Param= -1, 0, 0, 0
BEGIN DESCRIPTION:
Multiple Run
END DESCRIPTION:

--- UNT161 IN BECR.f01 (steady flow) ---

Flow Title=Multiple
Number of Profiles=7
Profile Names=10-year,25-year,50-year,1pct_min,100-year,1pct_plu,500-year
River Rch & RM= UNT161 IN BECR,Reach-1,1920
     279     360     423     367     496     670     683
Boundary for River Rch & Prof#=UNT161 IN BECR,Reach-1,1
Up Type=0
Dn Type=3
Dn Slope=0.005
Boundary for River Rch & Prof#=UNT161 IN BECR,Reach-1,2
Up Type=0
Dn Type=3
Dn Slope=0.005
Boundary for River Rch & Prof#=UNT161 IN BECR,Reach-1,3
Up Type=0
Dn Type=3
Dn Slope=0.005
Boundary for River Rch & Prof#=UNT161 IN BECR,Reach-1,4
Up Type=0
Dn Type=3
Dn Slope=0.005
Boundary for River Rch & Prof#=UNT161 IN BECR,Reach-1,5
Up Type=0
Dn Type=3
Dn Slope=0.005
Boundary for River Rch & Prof#=UNT161 IN BECR,Reach-1,6
Up Type=0
Dn Type=3
Dn Slope=0.005
Boundary for River Rch & Prof#=UNT161 IN BECR,Reach-1,7
Up Type=0
Dn Type=3
Dn Slope=0.005

--- UNT161 IN BECR.g01 (geometry) ---

Geom Title=Existing Conditions
Program Version=4.10

River Reach=UNT161 IN BECR  ,Reach-1
Reach XY= 30
        3818394.       10502075.        3818359.       10502000.
      3818285.25       10501933.        3818256.       10501841.
       3818236.5       10501814.       3818153.5       10501772.
       3818120.5       10501716.       3818014.5       10501611.
      3817869.75       10501542.       3817905.5       10501509.
       3817925.5       10501448.       3817968.5       10501386.
        3817983.       10501252.       3818006.5       10501213.
      3818049.75       10501178.      3818034.75       10501127.
       3817972.5       10501059.      3817972.25       10501001.
      3817960.25       10500961.      3817959.75       10500825.
      3818027.75       10500766.      3818069.75       10500763.
       3818083.5       10500753.       3818148.5       10500549.
       3818212.5       10500515.        3818236.       10500489.
       3818237.5       10500447.        3818267.       10500364.
      3818275.25       10500307.      3818303.75       10500258.

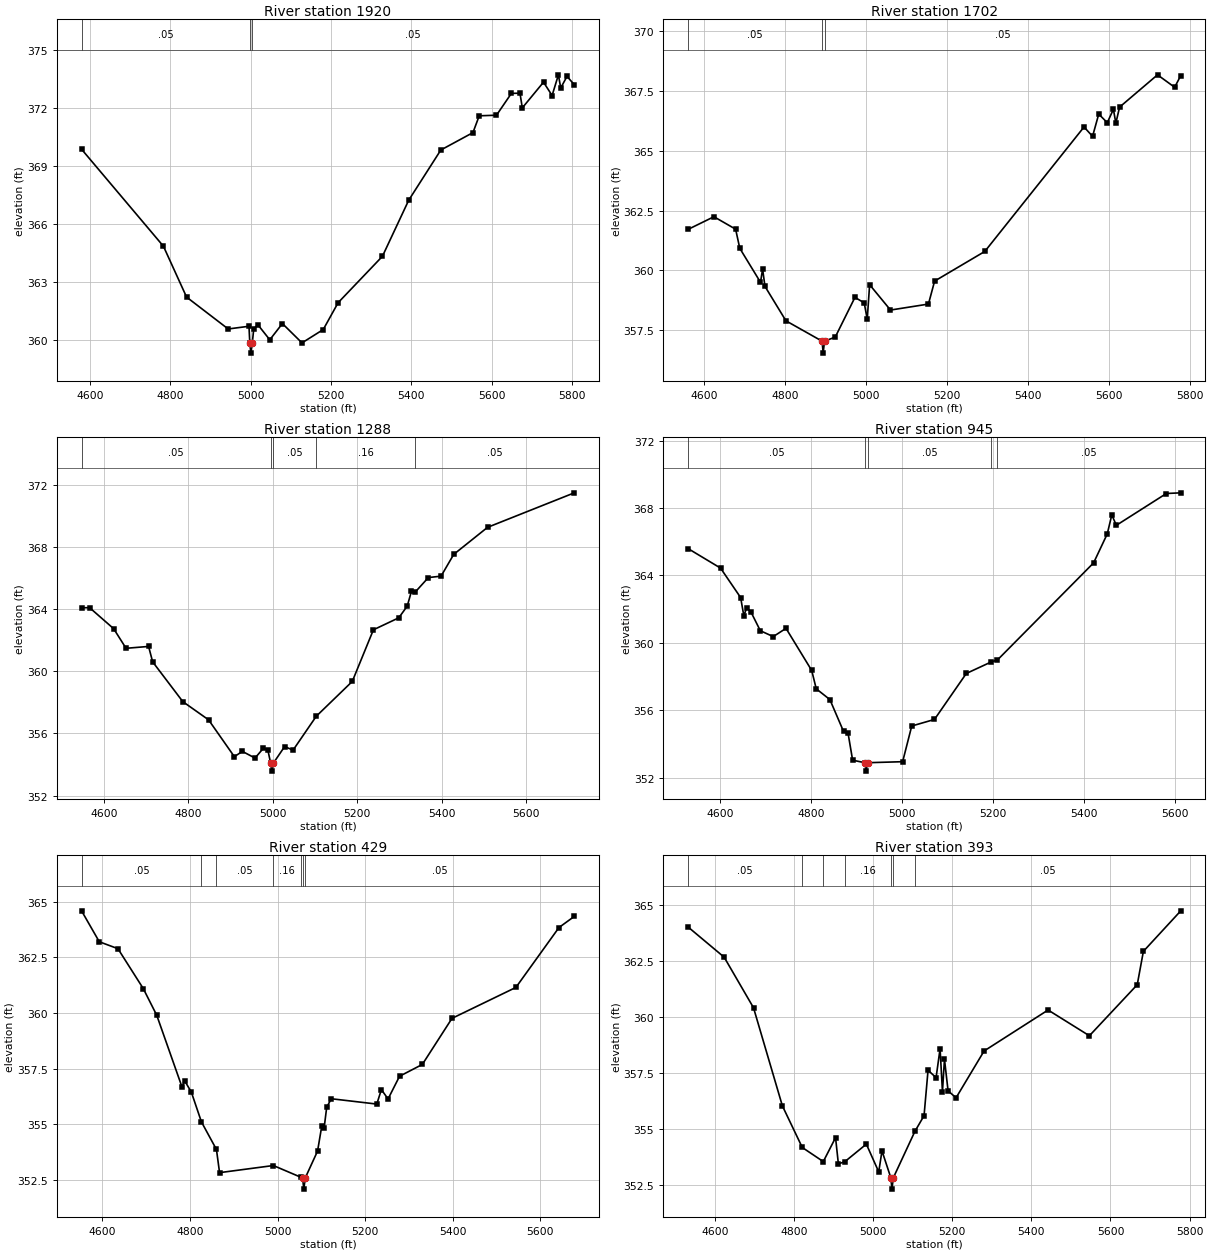
Type RM Length L Ch R = 1 ,1920    ,218,218,218
BEGIN DESCRIPTION:
UNT161 IN BECR 2.0
END DESCRIPTION:
XS GIS Cut Line= 4
      3818552.25     10501848.98      3818321.82     10501743.53
      3818028.85     10501800.17      3817685.94     10502381.81
#Sta/Elev= 30
  4579.1  369.88    4783  364.86  4840.6  362.23  4944.2  360.58    4996  360.72
  4998.1  359.83  5000.8  359.33  5004.1  359.83  5007.9  360.59  5018.1   360.8
  5047.8  360.02  5079.2  360.86    5128  359.86  5180.9  360.55    5218  361.94
  5328.3  364.34  5393.7  367.24  5473.7  369.84  5553.7  370.74  5569.3  371.61
  5612.3  371.64  5649.4  372.77  5670.8  372.78  5676.6  372.02  5729.4  373.35
  5750.8  372.66  5766.5  373.73  5772.3  373.05  5787.9  373.65  5806.1  373.22
#Mann= 3 ,-1 , 0
  4579.1     .05       0  4998.1     .03       0  5004.1     .05       0
Bank Sta=4998.1,5004.1
XS Rating Curve= 0 ,0
Exp/Cntr=0.3,0.1

Type RM Length L Ch R = 1 ,1702    ,414,414,414
BEGIN DESCRIPTION:
Mapping XS 224fdb48
END DESCRIPTION:
XS GIS Cut Line= 3
      3818402.97     10501447.74      3818066.18     10501538.01
      3817594.94     10502265.66
#Sta/Elev= 30
  4560.6  361.71  4624.5  362.24    4678  361.72  4688.3  360.92  4739.4   359.5
  4744.6  360.05  4750.4  359.33  4802.2  357.89  4891.3  357.04    4894  356.54
  4897.3  357.04  4923.8  357.21  4972.4  358.87  4995.3  358.64  5002.7  357.95
  5008.6   359.4  5060.1  358.34  5153.7  358.59  5168.9  359.55  5292.8  360.79
  5537.5  365.99  5558.6   365.6  5573.8  366.53  5594.9  366.17    5610  366.73
    5616  366.15  5625.2  366.82  5718.8  368.17  5761.1  367.65  5776.2  368.14
#Mann= 3 ,-1 , 0
  4560.6     .05       0  4891.3     .03       0  4897.3     .05       0
Bank Sta=4891.3,4897.3
XS Rating Curve= 0 ,0
Exp/Cntr=0.3,0.1

Type RM Length L Ch R = 1 ,1288    ,343,343,343
BEGIN DESCRIPTION:
Mapping XS f9963218
END DESCRIPTION:
XS GIS Cut Line= 3
      3818423.81     10501281.07       3818163.4      10501340.1
      3817264.33      10501291.5
#Sta/Elev= 30
  4547.2  364.08  4566.4  364.08  4623.3  362.73  4652.6  361.47    4706  361.59
  4715.6   360.6  4787.1  358.04  4848.1  356.87  4909.2   354.5  4928.2  354.84
  4958.2  354.41  4978.2  355.05  4988.3  354.96  4995.3  354.07    4998  353.57
  5001.3  354.07  5028.3  355.15  5048.3  354.92  5103.3   357.1  5188.6  359.34
  5238.6  362.66  5298.7  363.43  5318.7  364.18  5328.8  365.14  5337.5  365.08
  5368.8  366.02  5398.9  366.11  5428.9  367.51    5509  369.25  5714.6  371.47
#Mann= 5 ,-1 , 0
  4547.2     .05       0  4995.3     .03       0  5001.3     .05       0
  5103.3     .16       0  5337.5     .05       0
Bank Sta=4995.3,5001.3
XS Rating Curve= 0 ,0
Exp/Cntr=0.3,0.1

Type RM Length L Ch R = 1 ,945     ,516,516,516
BEGIN DESCRIPTION:
Mapping XS a9bcea8a
END DESCRIPTION:
XS GIS Cut Line= 3
      3818406.42     10501162.99       3818225.9     10501044.96
      3817357.88     10501044.96
#Sta/Elev= 30
  4528.6   365.6  4600.1  364.44  4644.3  362.69  4651.4   361.6  4657.3  362.07
  4666.5  361.86  4687.6  360.72    4716  360.37  4744.1  360.86  4800.6  358.36
  4810.6  357.27  4840.6  356.63  4870.6  354.74  4880.6  354.63  4890.6  353.03
  4917.6  352.88  4920.3  352.38  4923.6  352.88  5000.6  352.94  5020.6  355.06
  5070.6  355.45  5140.6  358.18  5195.8  358.87    5209  358.98  5420.6  364.75
  5450.6  366.47  5460.6   367.6  5470.6  366.98  5580.6  368.87  5612.3  368.91
#Mann= 5 ,-1 , 0
  4528.6     .05       0  4917.6     .03       0  4923.6     .05       0
  5195.8     .16       0    5209     .05       0
Bank Sta=4917.6,4923.6
XS Rating Curve= 0 ,0
Exp/Cntr=0.3,0.1

Type RM Length L Ch R = 1 ,429     ,36,36,36
BEGIN DESCRIPTION:
Mapping XS 0bb70227
END DESCRIPTION:
XS GIS Cut Line= 5
      3818368.26     10500985.93      3818208.54     10500728.99
      3818170.34     10500642.18      3818111.31     10500610.93
      3817475.94     10500791.47
#Sta/Elev= 30
  4552.7  364.59  4593.2   363.2  4635.7  362.89  4693.5   361.1  4724.3   359.9
  4782.1  356.67    4788  356.96  4803.4  356.44  4826.3  355.11  4860.6  353.87
  4867.7  352.83  4990.5  353.15  5053.7  352.62  5057.2  352.59    5060  352.09
  5063.2  352.59  5091.4   353.8  5101.1  354.94  5106.3  354.83  5112.2  355.76
  5122.6  356.15  5226.6  355.91    5237  356.56  5252.3  356.14  5278.5  357.16
  5330.5  357.69  5398.2  359.76  5544.1  361.15  5642.4  363.84  5677.4  364.34
#Mann= 7 ,-1 , 0
  4552.7     .05       0  4826.3     .16       0  4860.6     .05       0
  4990.5     .16       0  5053.7     .05       0  5057.2     .07       0
  5063.2     .05       0
Bank Sta=5057.2,5063.2
XS Rating Curve= 0 ,0
Exp/Cntr=0.3,0.1

Type RM Length L Ch R = 1 ,393     ,31,31,31
BEGIN DESCRIPTION:
Mapping XS c9ffc01e
END DESCRIPTION:
XS GIS Cut Line= 6
      3818378.69     10500972.06      3818222.43     10500656.07
      3818166.87     10500600.51      3818114.79     10500572.74
      3817691.18     10500635.24      3817393.56      10500770.2
#Sta/Elev= 30
  4532.5  364.03  4623.8  362.68    4698  360.42  4770.9  356.04  4821.2  354.18
  4874.3  353.55  4905.3  354.62  4912.4  353.45  4928.3  353.54  4983.1  354.33
  5014.4  353.09  5022.6  354.03  5045.1  352.82  5047.8  352.32  5051.1  352.82
  5105.8   354.9  5128.9   355.6    5139  357.63  5159.3   357.3  5169.4  358.59
  5175.4  356.68  5180.5  358.12  5189.6  356.71  5209.8   356.4  5280.6  358.49
  5442.3  360.32  5546.7  359.17  5667.6  361.45  5683.1  362.94  5777.6  364.75
#Mann= 7 ,-1 , 0
  4532.5     .05       0  4821.2     .16       0  4874.3     .05       0
  4928.3     .16       0  5045.1     .07       0  5051.1     .16       0
  5105.8     .05       0
Bank Sta=5045.1,5051.1
XS Rating Curve= 0 ,0
Exp/Cntr=0.3,0.1

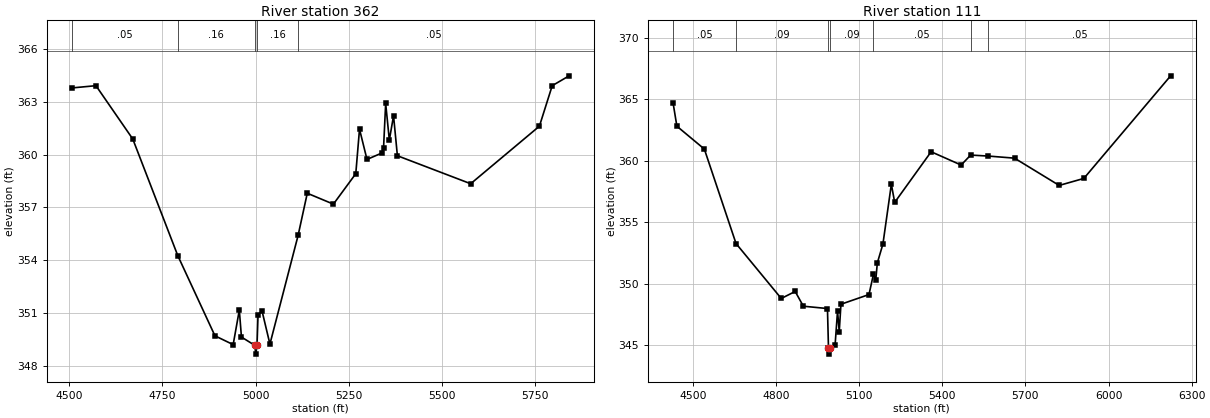
Type RM Length L Ch R = 1 ,362     ,251,251,251
BEGIN DESCRIPTION:
Mapping XS 7273bbdf
END DESCRIPTION:
XS GIS Cut Line= 5
      3818392.58     10500961.66      3818232.84     10500600.51
       3818125.2     10500544.96      3817784.93     10500534.54
      3817347.82     10500725.34
#Sta/Elev= 30
  4506.9  363.79  4572.3  363.92    4671  360.89  4791.5  354.27  4891.2  349.71
    4940  349.21  4956.5  351.17  4962.2  349.64  4997.9  349.17  5000.6  348.67
  5003.9  349.17  5006.7  350.91  5017.4  351.12  5038.5  349.24    5114  355.41
  5138.6  357.81  5208.6  357.19  5268.6  358.92  5278.6  361.45  5298.6  359.73
  5337.9  360.09    5343  360.38  5348.7  362.91  5358.5  360.83  5369.8  362.21
  5380.1  359.94  5576.5  358.35  5760.7  361.62    5795  363.92  5840.3  364.48
#Mann= 5 ,-1 , 0
  4506.9     .05       0  4791.5     .16       0  4997.9     .07       0
  5003.9     .16       0    5114     .05       0
Bank Sta=4997.9,5003.9
XS Rating Curve= 0 ,0
Exp/Cntr=0.3,0.1

Type RM Length L Ch R = 1 ,111     ,0,0,0
BEGIN DESCRIPTION:
UNT161 IN BECR 1.0
END DESCRIPTION:
XS GIS Cut Line= 5
      3818396.04     10500888.71      3818347.43     10500416.49
      3818142.56     10500274.13      3817826.59     10500322.74
      3817166.84     10500683.87
#Sta/Elev= 30
  4428.1  364.72  4441.9  362.82    4541  360.96  4655.4  353.27  4818.7   348.8
  4868.9  349.37  4898.4  348.17  4985.4  347.98  4989.1  344.77  4991.8  344.27
  4995.1  344.77    5013  345.02  5021.8  347.78  5027.9  346.09  5034.1  348.33
  5135.3  349.12  5151.5  350.78  5159.8  350.32  5165.4  351.69  5185.6  353.23
    5216  358.09  5228.1  356.62  5359.6  360.74  5467.9  359.66  5502.3  360.47
  5565.9  360.39  5660.6  360.22  5821.9     358  5910.9  358.57  6224.1  366.92
#Mann= 7 ,-1 , 0
  4428.1     .05       0  4655.4     .09       0  4989.1     .05       0
  4995.1     .09       0  5151.5     .05       0  5502.3     .16       0
  5565.9     .05       0
Bank Sta=4989.1,4995.1
XS Rating Curve= 0 ,0
Exp/Cntr=0.3,0.1

Chan Stop Cuts=-1
Use User Specified Reach Order=0
Composite Channel Slope=5