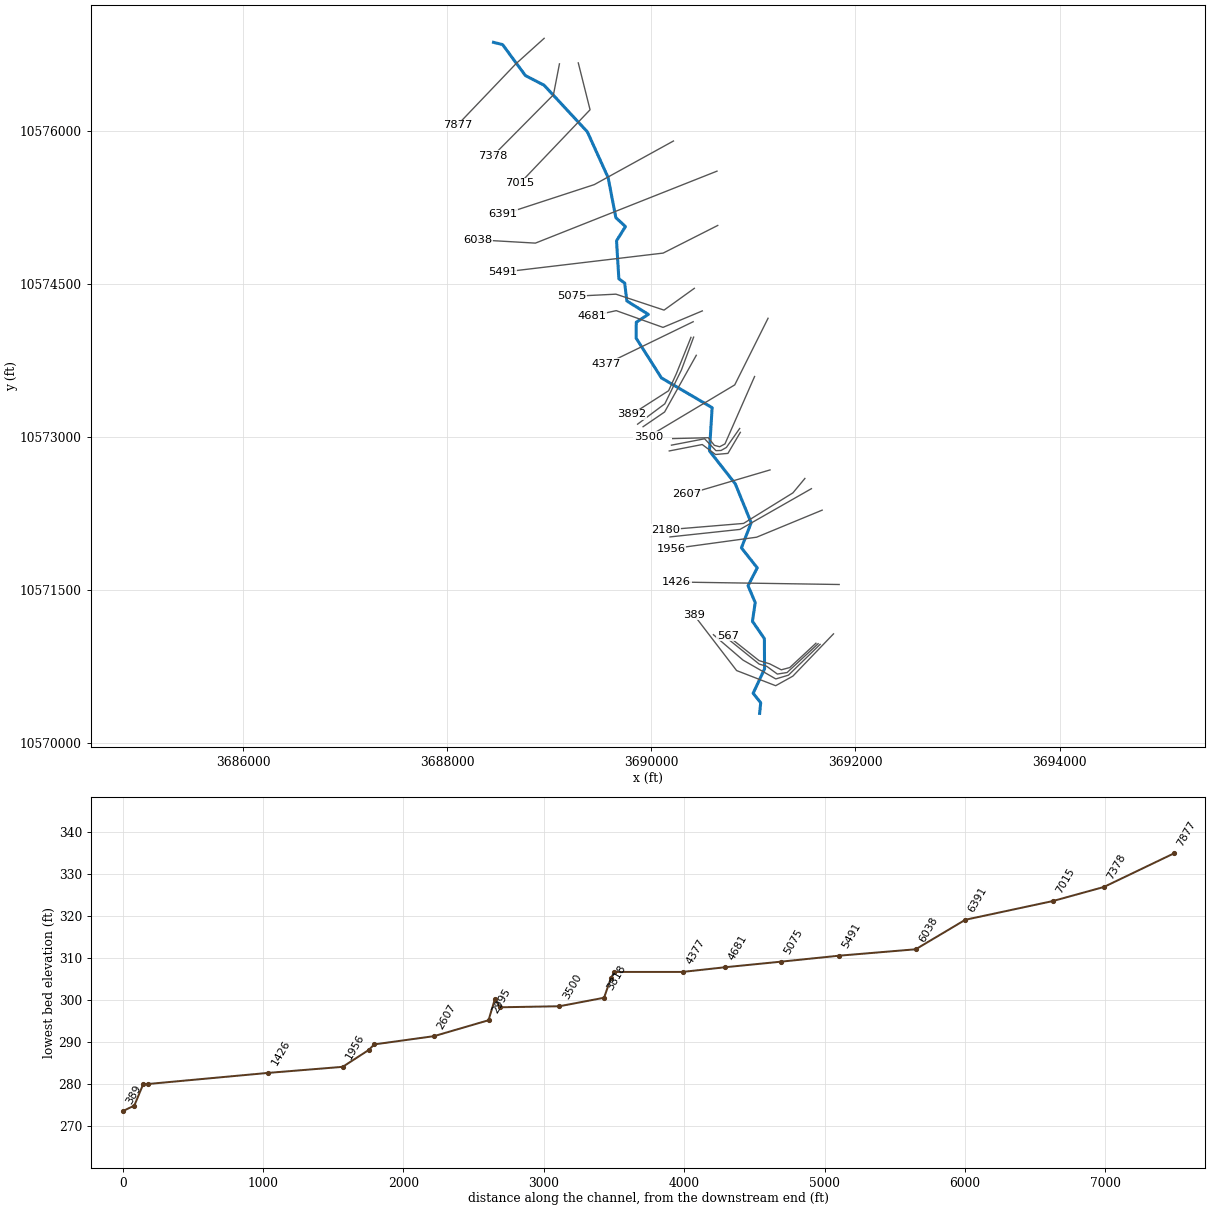
--- UNT162 IN BECR.prj (project) ---

Proj Title=UNT162 IN BECR Base Level Engineering
Current Plan=p01
Default Exp/Contr=0.3,0.1
English Units
Geom File=g01
Flow File=f01
Plan File=p01
Y Axis Title=Elevation
X Axis Title(PF)=Main Channel Distance
X Axis Title(XS)=Station
BEGIN DESCRIPTION:
UNT162 IN BECR
END DESCRIPTION:
DSS Export Rating Curves= 0
DSS Export Rating Curve Sorted= 0
DSS Export Volume Flow Curves= 0
DXF OffsetX= 0
DXF OffsetY= 0
DXF ScaleX= 1
DXF ScaleY= 10

--- UNT162 IN BECR.p01 (plan) ---

Plan Title=Multiple Run
Short Identifier=Multiple
Geom File=g01
Flow File=f01
Subcritical Flow
K Sum by GR= 0
Std Step Tol= 0.01
Critical Tol= 0.01
Num of Std Step Trials= 20
Max Error Tol= 0.3
Flow Tol Ratio= 0.001
Split Flow NTrial= 30
Split Flow Tol= 0.02
Split Flow Ratio= 0.02
Log Output Level= 0
Friction Slope Method= 1
Unsteady Friction Slope Method= 2
Unsteady Bridges Friction Slope Method= 1
Parabolic Critical Depth
Global Vel Dist=  1 , 1 , 1
Global Log Level= 0
CheckData=True
Encroach Param= -1, 0, 0, 0
BEGIN DESCRIPTION:
Multiple Run
END DESCRIPTION:

--- UNT162 IN BECR.f01 (steady flow) ---

Flow Title=Multiple
Program Version=4.10
Number of Profiles= 7
Profile Names=10-year,25-year,50-year,1pct_min,100-year,1pct_plu,500-year
River Rch & RM=UNT162 IN BECR,Reach-1         ,7877
     478     644     780     695     940    1271    1371
Boundary for River Rch & Prof#=UNT162 IN BECR,Reach-1         , 1
Up Type= 0
Dn Type= 3
Dn Slope=0.025
Boundary for River Rch & Prof#=UNT162 IN BECR,Reach-1         , 2
Up Type= 0
Dn Type= 3
Dn Slope=0.025
Boundary for River Rch & Prof#=UNT162 IN BECR,Reach-1         , 3
Up Type= 0
Dn Type= 3
Dn Slope=0.025
Boundary for River Rch & Prof#=UNT162 IN BECR,Reach-1         , 4
Up Type= 0
Dn Type= 3
Dn Slope=0.025
Boundary for River Rch & Prof#=UNT162 IN BECR,Reach-1         , 5
Up Type= 0
Dn Type= 3
Dn Slope=0.025
Boundary for River Rch & Prof#=UNT162 IN BECR,Reach-1         , 6
Up Type= 0
Dn Type= 3
Dn Slope=0.025
Boundary for River Rch & Prof#=UNT162 IN BECR,Reach-1         , 7
Up Type= 0
Dn Type= 3
Dn Slope=0.025
DSS Import GetInterval= 0
DSS Import GetPeak= 0
DSS Import FillOption= 0

--- UNT162 IN BECR.g01 (geometry) ---

Geom Title=Existing Conditions
Program Version=4.10

River Reach=UNT162 IN BECR  ,Reach-1
Reach XY= 30
       3688453.5       10576871.      3688542.25       10576849.
      3688766.25       10576545.      3688948.75       10576451.
        3689373.       10575994.       3689576.5       10575546.
      3689652.25       10575153.       3689746.5       10575066.
        3689659.       10574926.      3689681.75       10574553.
        3689739.       10574512.      3689759.75       10574337.
      3689970.75       10574205.       3689852.5       10574128.
      3689851.25       10573972.      3690099.25       10573582.
      3690595.75       10573291.      3690569.75       10572867.
        3690823.       10572544.      3690978.25       10572163.
        3690883.       10571917.        3691038.       10571721.
        3690948.       10571546.      3691017.75       10571381.
        3690991.       10571197.      3691107.75       10571028.
      3691109.75       10570731.      3690997.75       10570492.
        3691072.       10570399.      3691061.41       10570295.

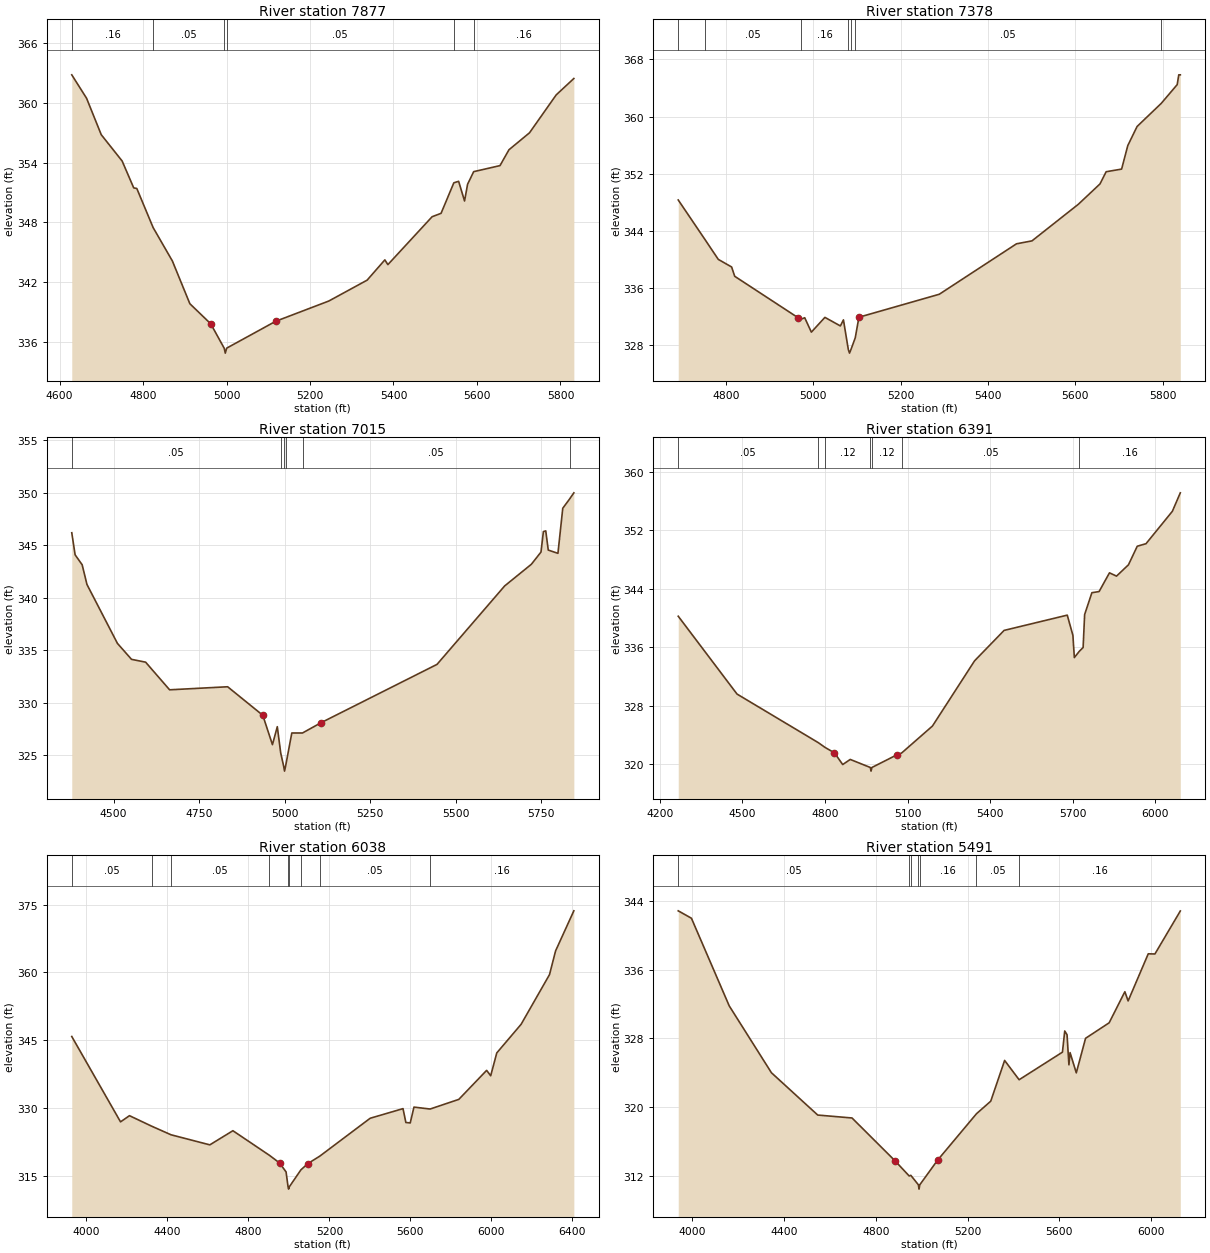
Type RM Length L Ch R = 1 ,7877    ,499,499,499
BEGIN DESCRIPTION:
UNT162 IN BECR 13.0
END DESCRIPTION:
XS GIS Cut Line= 3
      3688949.61     10576910.19      3688674.25       10576662.
      3688099.61     10576060.19
#Sta/Elev= 30
  4629.3  362.83  4664.8  360.47  4699.9  356.81    4750  354.16  4777.7  351.46
  4785.1   351.4  4824.2  347.47  4870.3  344.11  4912.2  339.81  4962.2  337.79
  4994.4  335.34  4997.1  334.84  5000.4  335.34  5117.7  338.04  5245.1  340.08
  5336.9  342.18  5379.4  344.22  5386.6  343.74  5492.6  348.56    5514   348.9
  5544.6  351.97  5556.1  352.12  5570.3  350.14  5577.5  351.82  5592.1  353.09
  5655.2   353.7  5676.6  355.29  5725.9     357  5789.8  360.81  5832.1  362.46
#Mann= 6 ,-1 , 0
  4629.3     .16       0  4824.2     .05       0  4994.4     .03       0
  5000.4     .05       0  5544.6     .08       0  5592.1     .16       0
Bank Sta=4962.2,5117.7
XS Rating Curve= 0 ,0
Exp/Cntr=0.3,0.1

Type RM Length L Ch R = 1 ,7378    ,363,363,363
BEGIN DESCRIPTION:
UNT162 IN BECR 12.0
END DESCRIPTION:
XS GIS Cut Line= 3
       3689099.6     10576660.14      3689040.75       10576357.
      3688449.62      10575760.2
#Sta/Elev= 30
  4691.2  348.31  4752.4  342.77  4782.8  339.99  4813.4  338.92  4820.4  337.62
  4966.2  331.78  4972.4  331.61  4980.6  331.81  4995.8  329.79  5026.8  331.86
  5062.2  330.66  5069.2  331.51  5080.4  327.35  5083.1  326.85  5086.4  327.35
  5096.3  329.01  5104.6  331.88  5288.5   335.1  5465.2  342.17  5500.6  342.58
  5606.7  347.71  5656.2  350.56  5670.3  352.27  5705.7  352.64  5719.8  355.93
  5741.1  358.61  5796.4  361.85  5832.9  364.48  5836.5  365.85    5840  365.85
#Mann= 7 ,-1 , 0
  4691.2     .16       0  4752.4     .05       0  4972.4     .16       0
  5080.4     .07       0  5086.4     .16       0  5096.3     .05       0
  5796.4     .16       0
Bank Sta=4966.2,5104.6
XS Rating Curve= 0 ,0
Exp/Cntr=0.3,0.1

Type RM Length L Ch R = 1 ,7015    ,624,624,624
BEGIN DESCRIPTION:
UNT162 IN BECR 11.0
END DESCRIPTION:
XS GIS Cut Line= 3
      3689284.15     10576669.66      3689399.61     10576210.19
       3688713.3     10575490.67
#Sta/Elev= 30
  4377.5   346.2  4387.3   344.1  4407.9  343.15  4421.9  341.28    4511  335.67
  4552.2  334.15  4593.5  333.88  4663.6  331.25  4833.3  331.54    4936  328.83
  4964.3  326.03  4978.5  327.74  4988.4  325.25  4996.9  324.01  4999.6  323.51
  5002.9  324.01  5020.9  327.14  5052.2  327.14  5105.9  328.11  5445.5  333.67
  5643.4  341.14  5721.4   343.2  5749.5  344.36  5756.6  346.31  5763.5  346.38
  5770.8  344.55  5799.1  344.24  5813.2  348.53  5832.9   349.4  5845.6     350
#Mann= 6 ,-1 , 0
  4377.5     .05       0  4988.4     .12       0  4996.9     .07       0
  5002.9     .12       0  5052.2     .05       0  5832.9     .16       0
Bank Sta=4936,5105.9
XS Rating Curve= 0 ,0
Exp/Cntr=0.3,0.1

Type RM Length L Ch R = 1 ,6391    ,353,353,353
BEGIN DESCRIPTION:
UNT162 IN BECR 10.0
END DESCRIPTION:
XS GIS Cut Line= 3
      3690216.65     10575904.06      3689440.67     10575476.63
      3688549.31     10575185.53
#Sta/Elev= 30
  4267.2  340.25  4480.7   329.6  4775.8  322.95  4801.1  322.28  4834.7  321.55
  4864.6  319.95    4892  320.65  4964.7  319.55  4967.5  319.05  4970.7  319.55
    5063  321.31  5078.6  321.53  5190.5  325.22  5343.6  334.15  5450.8  338.31
  5680.2   340.4  5700.7  337.63  5705.9  334.59  5724.2  335.46  5737.8  335.97
  5743.3  340.48  5769.7  343.47  5795.9  343.63  5833.5  346.19  5859.1  345.74
  5902.5  347.29  5934.4  349.83  5966.3  350.18  6061.9  354.61  6090.8  357.14
#Mann= 7 ,-1 , 0
  4267.2     .05       0  4775.8     .16       0  4801.1     .12       0
  4964.7     .07       0  4970.7     .12       0  5078.6     .05       0
  5724.2     .16       0
Bank Sta=4834.7,5063
XS Rating Curve= 0 ,0
Exp/Cntr=0.3,0.1

Type RM Length L Ch R = 1 ,6038    ,547,547,547
BEGIN DESCRIPTION:
UNT162 IN BECR 9.0
END DESCRIPTION:
XS GIS Cut Line= 3
      3690643.44     10575608.69      3688863.93     10574903.39
      3688299.65     10574935.95
#Sta/Elev= 30
  3927.6  345.83  4168.4  326.93  4212.6   328.3  4321.8  325.98  4417.8  324.07
  4609.4  321.84  4723.3  324.97  4903.9  319.52  4953.6  317.84  4985.9  315.85
  4995.8  312.54  4998.5  312.04  5001.8  312.54  5059.2  316.31  5093.5  317.69
  5152.6  319.35  5401.3  327.73  5563.4  329.86  5577.5  326.79    5599  326.69
  5617.5   330.2  5697.1  329.77    5839  331.91  5976.3  338.33  5996.4  337.14
  6026.4  342.19  6146.6  348.53  6286.8  359.52  6316.9  364.79    6407  373.65
#Mann= 9 ,-1 , 0
  3927.6     .05       0  4321.8     .16       0  4417.8     .05       0
  4903.9     .12       0  4995.8     .07       0  5001.8     .12       0
  5059.2     .16       0  5152.6     .05       0  5697.1     .16       0
Bank Sta=4953.6,5093.5
XS Rating Curve= 0 ,0
Exp/Cntr=0.3,0.1

Type RM Length L Ch R = 1 ,5491    ,416,416,416
BEGIN DESCRIPTION:
UNT162 IN BECR 8.0
END DESCRIPTION:
XS GIS Cut Line= 3
      3690650.86     10575076.59       3690116.1     10574805.74
      3688539.76     10574618.24
#Sta/Elev= 30
  3939.7  342.82  3997.2  341.96  4161.9  331.78  4345.7  324.02  4547.3  319.11
  4696.7  318.77  4882.8  313.83  4945.6  312.04  4952.8  312.11  4985.8  311.01
  4988.5  310.51  4991.8  311.01  5069.3  313.87  5238.7  319.26  5300.9  320.72
  5361.4  325.45  5424.5  323.21  5613.2  326.41  5623.2  328.87  5633.3  328.43
  5641.4  324.94  5646.4  326.36  5673.6  324.01  5713.9  328.02  5816.7  329.82
  5885.1  333.43  5899.3  332.36    5987  337.83    6016  337.81  6126.6   342.8
#Mann= 7 ,-1 , 0
  3939.7     .05       0  4945.6     .12       0  4952.8     .16       0
  4985.8     .07       0  4991.8     .16       0  5238.7     .05       0
  5424.5     .16       0
Bank Sta=4882.8,5069.3
XS Rating Curve= 0 ,0
Exp/Cntr=0.3,0.1

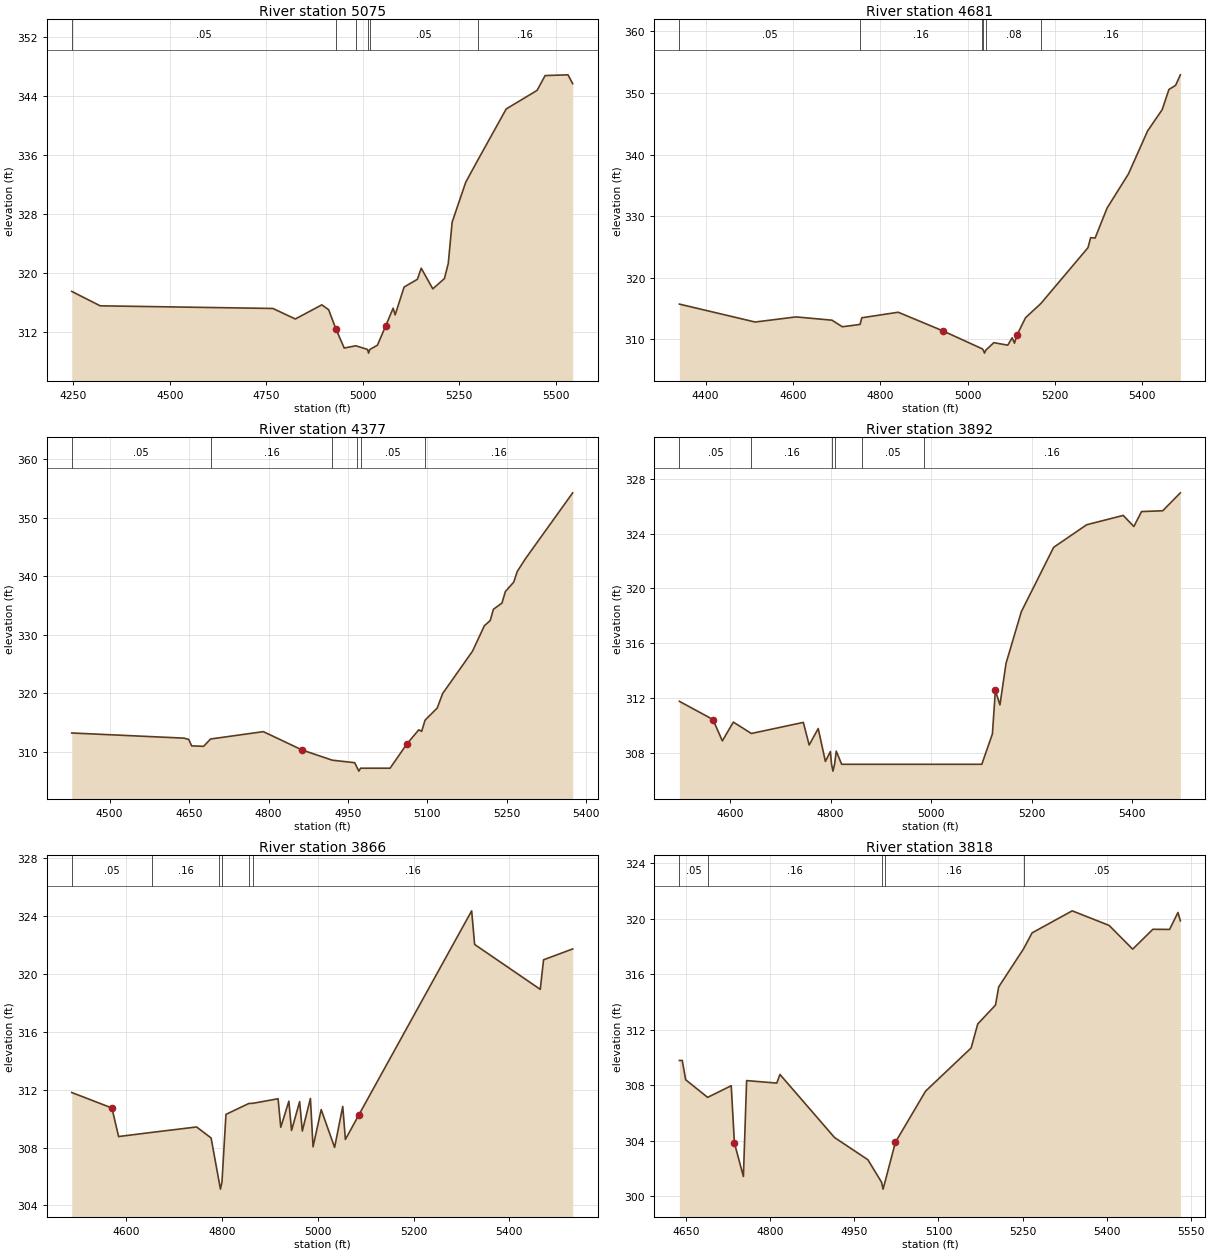
Type RM Length L Ch R = 1 ,5075    ,394,394,394
BEGIN DESCRIPTION:
Mapping XS 2f58e184
END DESCRIPTION:
XS GIS Cut Line= 4
       3690421.5      10574460.4      3690124.63     10574246.87
      3689653.28     10574403.12      3689217.48     10574381.42
#Sta/Elev= 30
  4245.9  317.47  4319.7  315.51  4767.4  315.15  4825.5  313.72  4894.2  315.64
  4911.9  314.98  4930.4  312.41  4952.3  309.77  4982.3  310.08  5012.7  309.58
  5015.4  309.08  5018.7  309.58  5038.3  310.15  5059.4  312.73  5079.1  315.19
  5084.3  314.28  5107.5  318.06  5141.9  319.11  5151.9  320.62  5181.9  317.82
    5212  319.21    5222  321.27    5232  326.88  5267.3  332.31  5298.1  335.27
  5372.2  342.26  5452.3  344.79    5473   346.8  5532.4   346.9  5544.5   345.7
#Mann= 6 ,-1 , 0
  4245.9     .05       0  4930.4      .1       0  4982.3     .05       0
  5012.7     .03       0  5018.7     .05       0  5298.1     .16       0
Bank Sta=4930.4,5059.4
XS Rating Curve= 0 ,0
Exp/Cntr=0.3,0.1

Type RM Length L Ch R = 1 ,4681    ,304,304,304
BEGIN DESCRIPTION:
Mapping XS 4933c44f
END DESCRIPTION:
XS GIS Cut Line= 4
      3690499.64     10574239.06      3690114.22      10574077.6
      3689655.88     10574241.66      3689418.93     10574189.58
#Sta/Elev= 30
  4339.9  315.73  4513.4  312.82  4607.1  313.65  4689.3  313.12  4713.1  312.05
  4753.7  312.43  4757.6  313.51    4841  314.41  4943.2  311.39  5033.5  308.47
  5035.8  308.27  5038.6  307.77  5041.8  308.27  5060.1  309.47  5091.9  309.06
    5102  310.26  5107.3  309.39  5113.2  310.74  5132.7  313.53  5167.8  315.83
  5275.7   324.9  5281.7  326.52    5292  326.46  5319.4  331.33  5368.3  336.87
  5412.1  343.84  5445.5   347.3    5461  350.58  5476.3  351.25  5487.2  352.96
#Mann= 6 ,-1 , 0
  4339.9     .05       0  4753.7     .16       0  5033.5     .08       0
  5035.8     .07       0  5041.8     .08       0  5167.8     .16       0
Bank Sta=4943.2,5113.2
XS Rating Curve= 0 ,0
Exp/Cntr=0.3,0.1

Type RM Length L Ch R = 1 ,4377    ,485,485,485
BEGIN DESCRIPTION:
Mapping XS 4ddefaa7
END DESCRIPTION:
XS GIS Cut Line= 2
      3690410.23     10574133.16      3689559.56     10573719.98
#Sta/Elev= 30
  4428.5  313.17  4640.4  312.29  4649.4  312.07  4654.9  310.97  4677.5  310.89
  4690.6  312.14  4790.3   313.4  4863.5  310.26  4920.4  308.52  4962.8  308.09
  4967.8  307.15  4970.5  306.65  4973.8  307.15  5029.5  307.15    5061  311.27
  5083.6  313.71  5089.1  313.45  5095.5  315.36  5118.5  317.44  5128.7  319.91
  5185.2  327.17  5207.5   331.5  5218.5  332.39  5224.5  334.31  5240.7  335.38
  5247.1  337.34    5263  338.97  5269.6  340.79  5285.2  342.98  5374.2  354.22
#Mann= 6 ,-1 , 0
  4428.5     .05       0  4690.6     .16       0  4920.4     .05       0
  4967.8    .035       0  4973.8     .05       0  5095.5     .16       0
Bank Sta=4863.5,5061
XS Rating Curve= 0 ,0
Exp/Cntr=0.3,0.1

Type RM Length L Ch R = 1 ,3892    ,26,26,26
BEGIN DESCRIPTION:
Mapping XS 842553f4
END DESCRIPTION:
XS GIS Cut Line= 4
      3690388.45      10573979.8      3690245.22      10573623.9
      3690169.27     10573456.79      3689807.29     10573224.87
#Sta/Elev= 30
  4498.9  311.75  4565.7  310.42  4584.4  308.86  4606.3  310.23  4642.2   309.4
  4745.6  310.21  4757.2  308.56  4775.2  309.76  4789.5  307.36  4799.4  308.08
  4801.8  307.15  4804.5  306.65  4807.8  307.15  4811.1  308.11  4821.9  307.15
  4861.8  307.15  4985.6  307.15  5100.8  307.15  5121.9  309.37  5127.8  312.54
  5136.9  311.49    5149  314.52  5179.4  318.29  5243.8     323  5309.6  324.65
  5382.3  325.33  5403.4  324.52  5418.7  325.61  5460.9  325.67    5496  326.98
#Mann= 6 ,-1 , 0
  4498.9     .05       0  4642.2     .16       0  4801.8     .07       0
  4807.8     .16       0  4861.8     .05       0  4985.6     .16       0
Bank Sta=4565.7,5127.8
XS Rating Curve= 0 ,0
Exp/Cntr=0.3,0.1

Type RM Length L Ch R = 1 ,3866    ,48,48,48
BEGIN DESCRIPTION:
Mapping XS b92bb682
END DESCRIPTION:
XS GIS Cut Line= 4
       3690414.5     10573981.98      3690295.13     10573660.79
      3690132.37     10573328.76      3689865.42     10573129.09
#Sta/Elev= 30
  4486.4   311.8  4570.3  310.73  4584.3  308.76  4654.5  309.05  4747.1  309.42
  4777.4  308.66  4794.1  305.63  4796.9  305.13  4800.1  305.63  4808.4  310.29
    4856  311.04  4865.8  311.06  4917.2  311.37  4922.8   309.4  4939.7   311.2
  4945.3  309.18  4962.2  311.17  4967.8  309.14  4984.7  311.39  4990.2  308.05
  5007.2  310.62  5035.2  308.01  5052.2  310.84  5057.7  308.56  5085.9  310.26
  5321.3  324.34  5327.5  322.02  5464.5  318.92  5471.4  320.96  5532.2  321.71
#Mann= 6 ,-1 , 0
  4486.4     .05       0  4654.5     .16       0  4794.1     .07       0
  4800.1     .16       0    4856     .05       0  4865.8     .16       0
Bank Sta=4570.3,5085.9
XS Rating Curve= 0 ,0
Exp/Cntr=0.3,0.1

Type RM Length L Ch R = 1 ,3818    ,318,318,318
BEGIN DESCRIPTION:
Mapping XS 04264fce
END DESCRIPTION:
XS GIS Cut Line= 3
      3690440.54     10573804.04       3690130.2     10573248.46
       3689919.1     10573104.14
#Sta/Elev= 30
  4638.7  309.78  4643.8  309.78  4649.9  308.39    4689  307.12    4731  307.96
  4736.7  303.83  4752.7  301.42  4758.4  308.33  4812.1  308.15  4817.8  308.77
  4914.9  304.23  4974.3  302.63  4998.7  301.01  5001.4  300.51  5004.7  301.01
  5023.4  303.89  5077.1  307.57  5158.2  310.68    5170  312.41  5201.6  313.77
  5207.3  315.08  5251.7  317.83  5266.7  318.97  5338.2  320.56  5403.9  319.51
  5445.9   317.8  5481.8  319.23  5511.6  319.22  5526.5  320.44  5530.8  319.84
#Mann= 5 ,-1 , 0
  4638.7     .05       0    4689     .16       0  4998.7     .07       0
  5004.7     .16       0  5251.7     .05       0
Bank Sta=4736.7,5023.4
XS Rating Curve= 0 ,0
Exp/Cntr=0.3,0.1

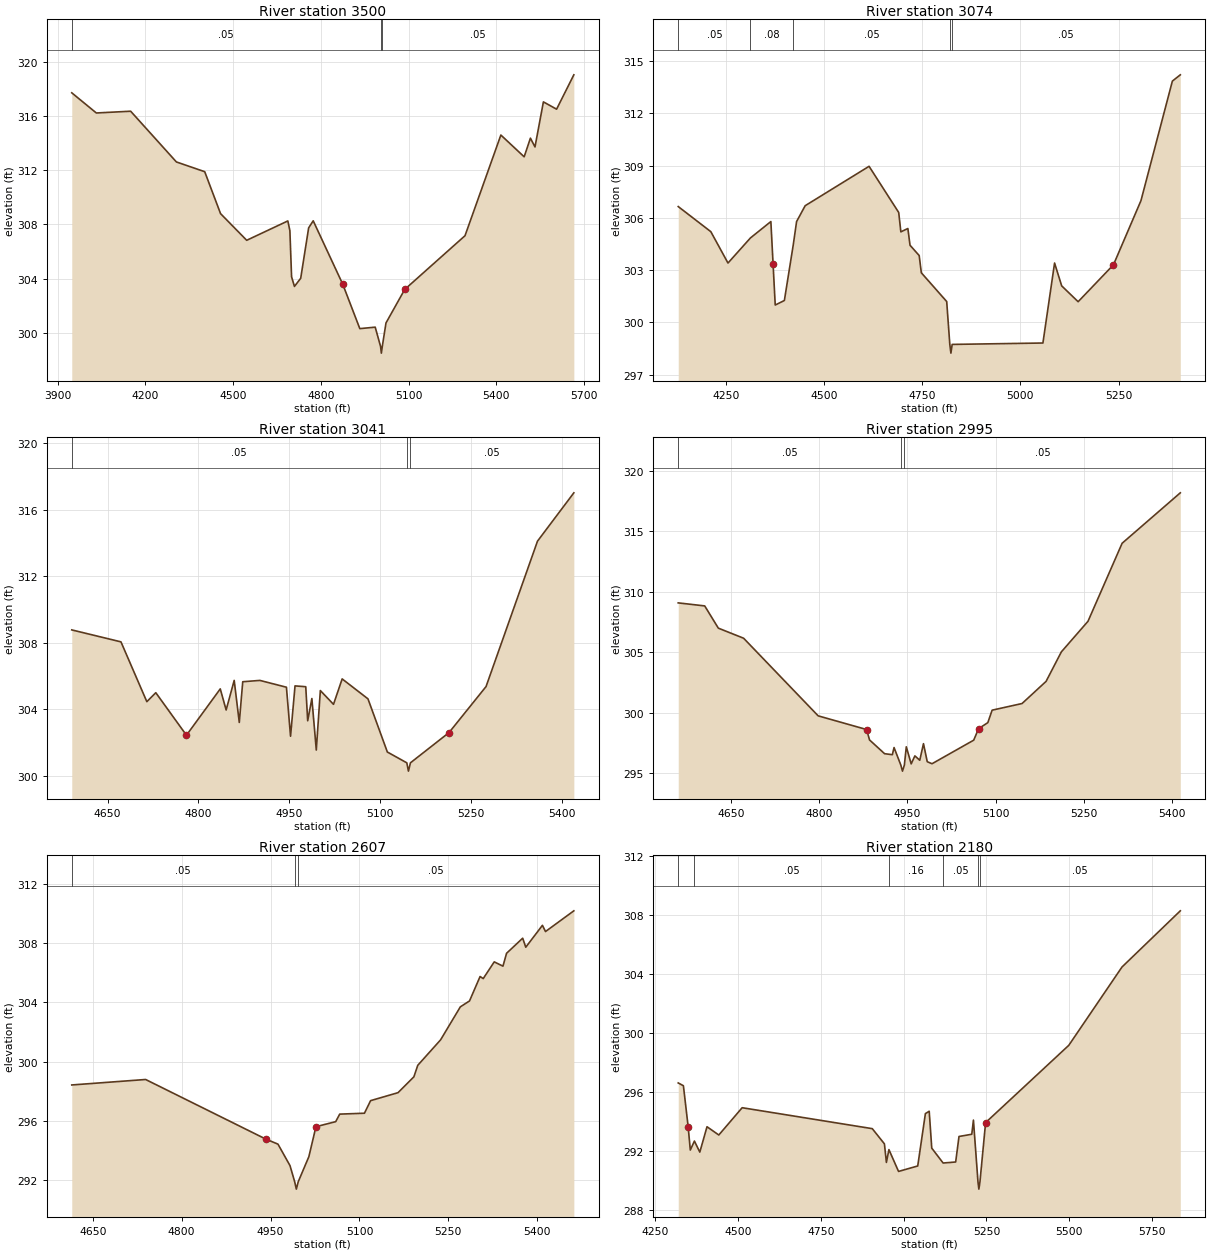
Type RM Length L Ch R = 1 ,3500    ,426,426,426
BEGIN DESCRIPTION:
UNT162 IN BECR 4.0
END DESCRIPTION:
XS GIS Cut Line= 3
       3691143.9     10574166.88      3690817.49     10573514.07
      3689970.24     10573007.11
#Sta/Elev= 30
    3948  317.73    4032  316.24  4149.4  316.37  4305.9  312.62  4402.7   311.9
  4456.9   308.8  4546.3  306.83    4687  308.26    4694  307.54  4699.8  304.13
  4709.6  303.42    4731  304.02  4758.2  307.75  4773.8  308.27  4874.9  303.58
  4933.2   300.3  4985.8  300.41  5004.1  298.99  5006.9  298.49  5010.1  298.99
  5022.7  300.72  5086.9   303.2    5293  307.17  5415.6  314.61  5495.3     313
  5516.7  314.38  5532.3  313.73  5561.1  317.06  5606.2  316.52  5665.2  319.06
#Mann= 3 ,-1 , 0
    3948     .05       0  5004.1     .03       0  5010.1     .05       0
Bank Sta=4874.9,5086.9
XS Rating Curve= 0 ,0
Exp/Cntr=0.3,0.1

Type RM Length L Ch R = 1 ,3074    ,33,33,33
BEGIN DESCRIPTION:
Mapping XS 458b5487
END DESCRIPTION:
XS GIS Cut Line= 6
      3691011.83     10573596.14      3690721.64     10572935.67
      3690669.55     10572907.89      3690617.47     10572921.78
      3690558.44     10572996.44      3690209.46     10572987.75
#Sta/Elev= 30
  4128.8  306.65  4211.8  305.21  4255.5  303.41  4312.7  304.85  4364.7  305.79
  4370.3  303.37  4375.8     301  4399.1  301.26  4421.7  304.45  4430.2  305.79
  4452.1   306.7  4614.8  308.96  4690.3  306.31  4695.7   305.2  4713.6  305.39
  4719.1  304.43  4742.4  303.84  4747.9  302.85  4812.5   301.2  4820.4  298.74
  4823.2  298.24  4826.4  298.74  5057.5  298.82  5087.2  303.41  5105.3   302.1
  5147.2  301.19  5237.2  303.31  5307.2  306.99  5387.2  313.85  5407.4  314.21
#Mann= 5 ,-1 , 0
  4128.8     .05       0  4312.7     .08       0  4421.7     .05       0
  4820.4     .03       0  4826.4     .05       0
Bank Sta=4370.3,5237.2
XS Rating Curve= 0 ,0
Exp/Cntr=0.3,0.1

Type RM Length L Ch R = 1 ,3041    ,46,46,46
BEGIN DESCRIPTION:
Mapping XS d090b110
END DESCRIPTION:
XS GIS Cut Line= 6
      3690865.72     10573086.69      3690735.53     10572900.95
      3690683.44     10572871.44       3690633.1      10572869.7
      3690521.99     10572986.02      3690197.36     10572923.52
#Sta/Elev= 30
  4590.9  308.78  4672.1  308.06  4714.8  304.46  4729.6     305  4780.2  302.44
    4836  305.23  4845.7  303.96    4859  305.74  4867.4  303.21  4873.1  305.66
  4901.4  305.74  4945.2  305.33    4952  302.38  4959.4  305.41  4977.1  305.36
  4980.3  303.31  4987.2  304.65  4994.5  301.55  5001.2  305.13  5022.9   304.3
  5037.2  305.83  5079.8  304.63  5111.8  301.43  5143.9  300.78  5146.6  300.28
  5149.9  300.78  5213.6   302.6  5274.7  305.37  5359.6  314.12  5419.6  317.03
#Mann= 3 ,-1 , 0
  4590.9     .05       0  5143.9     .03       0  5149.9     .05       0
Bank Sta=4780.2,5213.6
XS Rating Curve= 0 ,0
Exp/Cntr=0.3,0.1

Type RM Length L Ch R = 1 ,2995    ,388,388,388
BEGIN DESCRIPTION:
Mapping XS 2171d643
END DESCRIPTION:
XS GIS Cut Line= 5
      3690872.23     10573048.92      3690750.72     10572842.79
      3690629.19     10572831.94      3690498.98      10572929.6
       3690175.6     10572866.66
#Sta/Elev= 30
  4560.5  309.07  4605.5  308.82  4628.7  306.98  4671.6  306.15  4798.4  299.73
  4880.7   298.6  4885.7  297.74  4911.3   296.6  4924.5  296.52  4927.4  297.11
  4938.9  295.66  4941.7  295.16  4944.9  295.66  4948.2  297.17  4956.5  295.76
  4962.8  296.42  4971.1  296.06  4977.4  297.43  4983.8  295.94  4991.9  295.77
  5062.8  297.72  5071.1  298.67  5086.8  299.17  5094.1   300.2    5145  300.75
  5185.8  302.58  5211.8  305.02  5257.1  307.55  5315.1     314    5414  318.17
#Mann= 3 ,-1 , 0
  4560.5     .05       0  4938.9     .03       0  4944.9     .05       0
Bank Sta=4880.7,5071.1
XS Rating Curve= 0 ,0
Exp/Cntr=0.3,0.1

Type RM Length L Ch R = 1 ,2607    ,427,427,427
BEGIN DESCRIPTION:
Mapping XS 17224013
END DESCRIPTION:
XS GIS Cut Line= 2
      3691163.26     10572680.68      3690350.75     10572441.09
#Sta/Elev= 30
  4614.6  298.42  4739.2  298.79  4941.6  294.77  4962.5  294.42  4982.8  292.97
  4990.7  291.88  4993.5  291.38  4996.7  291.88  5014.6  293.57  5026.6   295.6
  5059.9  295.94  5066.7  296.45  5108.4  296.51  5118.8  297.36  5165.1   297.9
  5191.8  298.97  5198.4  299.75  5236.9  301.47  5270.2   303.7  5285.7   304.1
  5303.5  305.75  5308.8  305.61  5327.4  306.74  5342.1  306.45  5348.2  307.32
  5375.4  308.34  5380.6  307.73  5408.7  309.21  5413.9  308.79  5461.7  310.19
#Mann= 3 ,-1 , 0
  4614.6     .05       0  4990.7     .03       0  4996.7     .05       0
Bank Sta=4941.6,5026.6
XS Rating Curve= 0 ,0
Exp/Cntr=0.3,0.1

Type RM Length L Ch R = 1 ,2180    ,37,37,37
BEGIN DESCRIPTION:
Mapping XS 6855ffe3
END DESCRIPTION:
XS GIS Cut Line= 4
      3691504.77     10572596.99      3691387.58     10572455.93
      3690903.64     10572156.45      3690144.34     10572093.53
#Sta/Elev= 30
  4320.3  296.61  4335.9  296.42  4350.2  293.65  4356.7  292.06  4369.1  292.67
  4385.4  291.92  4407.1  293.64  4442.7  293.08  4513.1  294.93  4905.6  293.51
  4942.2  292.48  4948.2  291.22  4955.8  292.09  4984.8  290.61  5042.7  290.98
  5065.8  294.53  5077.3  294.69    5085  292.19  5119.3  291.18  5157.1  291.25
  5167.2  292.98  5205.7  293.13  5210.7  294.09  5224.4  289.91  5227.1  289.41
  5230.4  289.91  5247.4  293.92  5498.3  299.16  5658.8  304.47  5834.7  308.28
#Mann= 6 ,-1 , 0
  4320.3     .08       0  4369.1     .05       0  4955.8     .16       0
  5119.3     .05       0  5224.4     .07       0  5230.4     .05       0
Bank Sta=4350.2,5247.4
XS Rating Curve= 0 ,0
Exp/Cntr=0.3,0.1

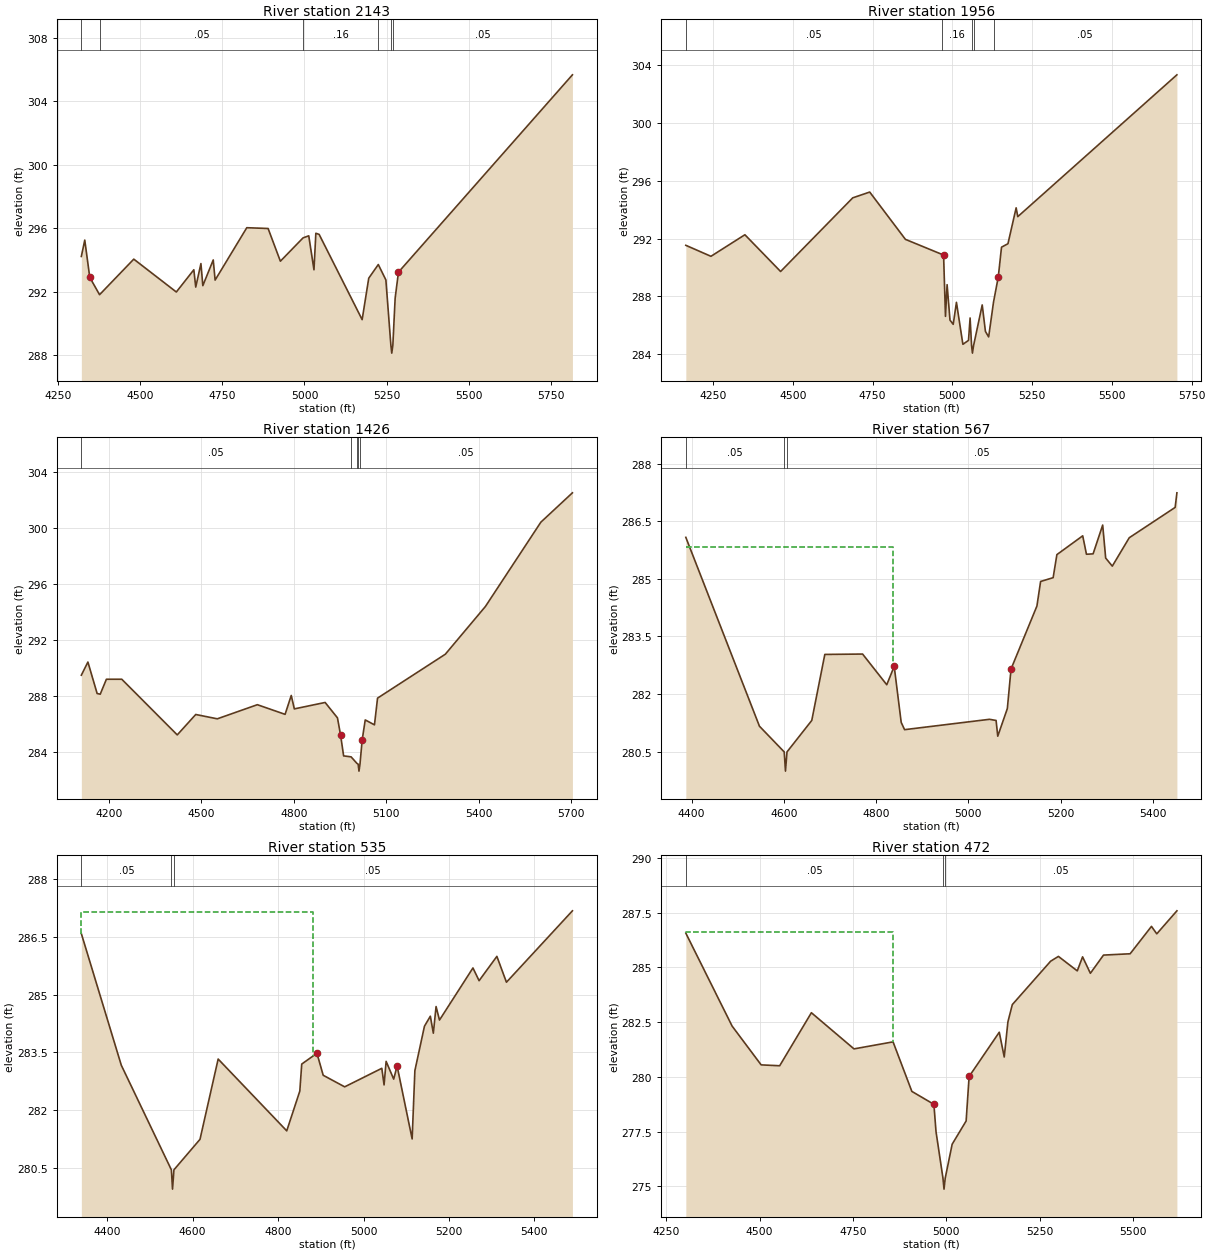
Type RM Length L Ch R = 1 ,2143    ,187,187,187
BEGIN DESCRIPTION:
Mapping XS e79e5065
END DESCRIPTION:
XS GIS Cut Line= 3
      3691568.65     10572496.99      3690868.92     10572097.85
      3690182.81     10572024.27
#Sta/Elev= 30
  4320.4  294.21  4330.8  295.24  4346.1  292.89  4375.9   291.8  4480.1  294.04
  4609.7  291.97    4663  293.37  4668.8  292.28  4684.6  293.76  4690.4  292.37
  4722.1  293.99  4727.8  292.72  4824.3  296.02  4889.2  295.97  4926.6  293.91
  4995.7  295.38    5013  295.51  5028.9  293.37  5034.6  295.67  5044.6   295.6
  5175.6  290.23  5195.7  292.84  5224.8   293.7  5247.9  292.73  5263.1  288.62
  5265.8  288.12  5269.1  288.62  5276.1  291.58  5286.2  293.22    5816  305.65
#Mann= 6 ,-1 , 0
  4320.4     .08       0  4375.9     .05       0  4995.7     .16       0
  5224.8     .05       0  5263.1     .07       0  5269.1     .05       0
Bank Sta=4346.1,5286.2
XS Rating Curve= 0 ,0
Exp/Cntr=0.3,0.1

Type RM Length L Ch R = 1 ,1956    ,530,530,530
BEGIN DESCRIPTION:
Mapping XS 0f2debc5
END DESCRIPTION:
XS GIS Cut Line= 3
      3691674.08     10572286.55      3691031.68     10572021.46
      3690194.83     10571906.88
#Sta/Elev= 30
  4164.2  291.53  4242.9  290.77  4349.4  292.26  4461.3  289.72  4687.5  294.81
  4740.7  295.21  4852.7  291.94  4968.7  290.89  4972.3  290.85  4978.2  286.62
  4983.3  288.81  4992.4  286.36  5002.5  286.07  5012.6  287.59  5032.8  284.69
  5050.4  284.96  5055.4  286.51  5060.1  284.58  5062.8  284.08  5066.1  284.58
  5093.4  287.41  5103.5  285.58  5113.6   285.2  5128.8   287.6  5143.8  289.35
  5153.9   291.4  5174.1  291.64  5199.8  294.12  5204.9  293.51  5703.8  303.31
#Mann= 5 ,-1 , 0
  4164.2     .05       0  4968.7     .16       0  5060.1     .07       0
  5066.1     .16       0  5128.8     .05       0
Bank Sta=4972.3,5143.8
XS Rating Curve= 0 ,0
Exp/Cntr=0.3,0.1

Type RM Length L Ch R = 1 ,1426    ,859,859,859
BEGIN DESCRIPTION:
UNT162 IN BECR 2.0
END DESCRIPTION:
XS GIS Cut Line= 2
      3691840.86     10571557.94      3690247.14     10571582.24
#Sta/Elev= 30
  4110.6   289.5  4131.9  290.44  4161.9  288.19  4171.9  288.14  4191.9  289.21
  4241.9  289.21  4421.9  285.23  4481.9  286.69  4551.9  286.38  4681.9  287.39
  4771.9   286.7  4791.9  288.05  4801.9  287.09  4901.9  287.55  4941.9  286.45
  4951.9  285.23  4961.9  283.73  4986.2  283.66  5004.8   283.2    5009  283.14
  5011.7  282.64    5015  283.14    5022  284.85    5032   286.3    5062  285.95
    5072  287.86    5292     291    5422  294.41    5602  300.44  5704.5  302.54
#Mann= 5 ,-1 , 0
  4110.6     .05       0  4986.2     .16       0  5004.8     .05       0
    5009     .07       0    5015     .05       0
Bank Sta=4951.9,5022
XS Rating Curve= 0 ,0
Exp/Cntr=0.3,0.1

Type RM Length L Ch R = 1 ,567     ,32,32,32
BEGIN DESCRIPTION:
Mapping XS 40655c8f
END DESCRIPTION:
XS GIS Cut Line= 6
      3691613.13     10570982.33      3691356.62     10570744.05
      3691273.29     10570721.91      3691160.01     10570780.51
      3691055.84     10570811.76      3690748.62     10571055.19
#Sta/Elev= 30
  4387.6  286.08  4547.2  281.16  4600.9  280.49  4603.6  279.99  4606.9  280.49
  4660.6  281.31  4688.9  283.03  4770.8  283.04  4823.2  282.24  4839.3  282.72
  4854.5  281.26  4861.8  281.07  5045.8  281.34  5060.2  281.31  5063.8   280.9
  5084.6  281.62  5092.6  282.65  5148.7  284.29  5156.7  284.93  5183.9  285.03
    5192  285.63    5248  286.12  5256.1  285.64  5270.5  285.65  5291.3   286.4
  5297.8  285.54  5312.1  285.33  5348.9  286.07  5448.4  286.86  5452.2  287.24
#Mann= 3 ,-1 , 0
  4387.6     .05       0  4600.9     .03       0  4606.9     .05       0
#XS Ineff= 2 , 0
         4835.78  285.83
Permanent Ineff=
       F       F
Bank Sta=4839.3,5092.6
XS Rating Curve= 0 ,0
Exp/Cntr=0.3,0.1

Type RM Length L Ch R = 1 ,535     ,63,63,63
BEGIN DESCRIPTION:
Mapping XS 06f3d0bb
END DESCRIPTION:
XS GIS Cut Line= 6
      3691634.43     10570977.58      3691330.58     10570695.44
      3691235.09     10570680.25      3691130.93      10570756.2
      3691057.14      10570777.9      3690720.76     10571049.18
#Sta/Elev= 30
  4339.6  286.58  4433.1  283.17  4550.3  280.46    4553  279.96  4556.3  280.46
  4617.3  281.25  4659.8  283.33  4820.3  281.47  4850.9   282.5  4855.4   283.2
    4891  283.48  4905.6  282.91  4955.9  282.61  5042.8  283.09  5048.1  282.66
  5052.9  283.27  5070.6  282.81  5078.6  283.15  5113.8  281.26  5120.2  283.03
  5142.6  284.18  5156.4  284.44  5163.4     284  5169.8  284.69  5177.8  284.34
  5256.1  285.69  5270.5  285.36  5312.1  285.99  5334.5  285.32  5488.9  287.17
#Mann= 3 ,-1 , 0
  4339.6     .05       0  4550.3     .03       0  4556.3     .05       0
#XS Ineff= 2 , 0
         4881.65  287.15
Permanent Ineff=
       F       F
Bank Sta=4891,5078.6
XS Rating Curve= 0 ,0
Exp/Cntr=0.3,0.1

Type RM Length L Ch R = 1 ,472     ,83,83,83
BEGIN DESCRIPTION:
Mapping XS 566100cf
END DESCRIPTION:
XS GIS Cut Line= 5
      3691653.95     10570971.07       3691343.6      10570669.4
       3691219.9      10570632.5      3690898.72     10570816.97
      3690608.67     10571065.89
#Sta/Elev= 30
  4302.8  286.56  4426.7  282.32  4504.4  280.55    4554  280.51  4638.9  282.93
  4752.9  281.28  4857.5   281.6  4907.8  279.34  4966.8  278.75  4972.5   277.5
  4991.1  275.38  4993.9  274.88  4997.1  275.38  5015.7  276.93  5053.1  277.99
  5061.1  280.02  5141.8  282.04  5155.1  280.91  5164.9  282.51  5176.7   283.3
  5279.2  285.28  5300.1   285.5  5350.6  284.84  5364.8  285.48  5385.7  284.73
  5420.8  285.56  5492.1  285.62  5549.2  286.87  5563.4  286.53  5617.3  287.58
#Mann= 3 ,-1 , 0
  4302.8     .05       0  4991.1     .03       0  4997.1     .05       0
#XS Ineff= 2 , 0
          4857.4  286.63
Permanent Ineff=
       F       F
Bank Sta=4966.8,5061.1
XS Rating Curve= 0 ,0
Exp/Cntr=0.3,0.1

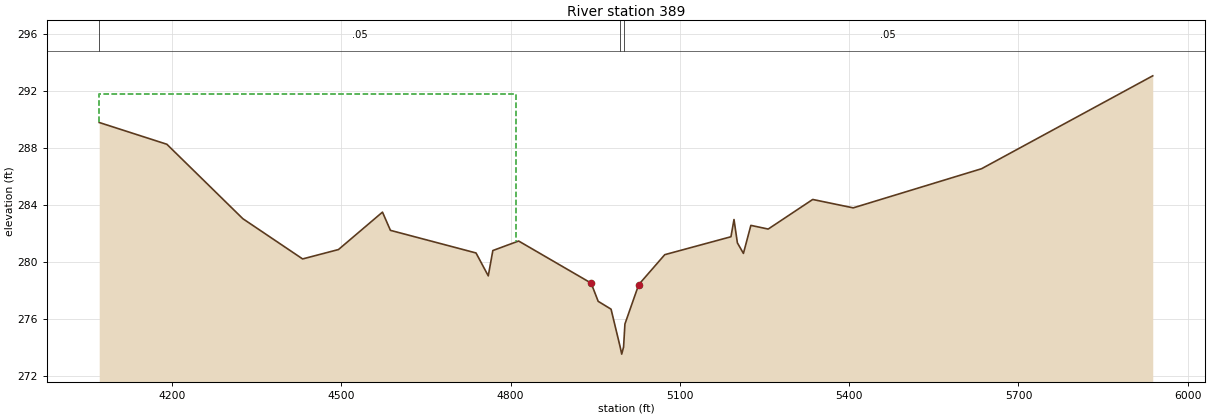
Type RM Length L Ch R = 1 ,389     ,0,0,0
BEGIN DESCRIPTION:
UNT162 IN BECR 1.0
END DESCRIPTION:
XS GIS Cut Line= 5
      3691785.24     10571074.23      3691386.94     10570659.91
      3691218.53     10570566.16      3690835.72     10570714.59
      3690416.48     10571261.43
#Sta/Elev= 30
  4070.9   289.8  4190.8  288.27  4325.4  283.04  4431.4  280.21  4494.9  280.87
  4572.9   283.5    4587  282.22  4738.7  280.63  4760.4  279.02  4768.5   280.8
  4814.2  281.47  4942.7  278.51  4955.2  277.23    4978  276.68  4994.2  274.02
  4996.9  273.52  5000.2  274.02  5002.6  275.64  5027.1  278.41  5073.2  280.51
  5190.5  281.77  5195.9  282.98  5201.9  281.34  5212.6   280.6  5225.8  282.57
  5256.5  282.31  5335.4  284.39  5407.2   283.8  5634.6  286.55    5938  293.08
#Mann= 3 ,-1 , 0
  4070.9     .05       0  4994.2     .03       0  5000.2     .05       0
#XS Ineff= 2 , 0
         4809.96  291.77
Permanent Ineff=
       F       F
Bank Sta=4942.7,5027.1
XS Rating Curve= 0 ,0
Exp/Cntr=0.3,0.1

Chan Stop Cuts=-1
Use User Specified Reach Order=0
Composite Channel Slope=5