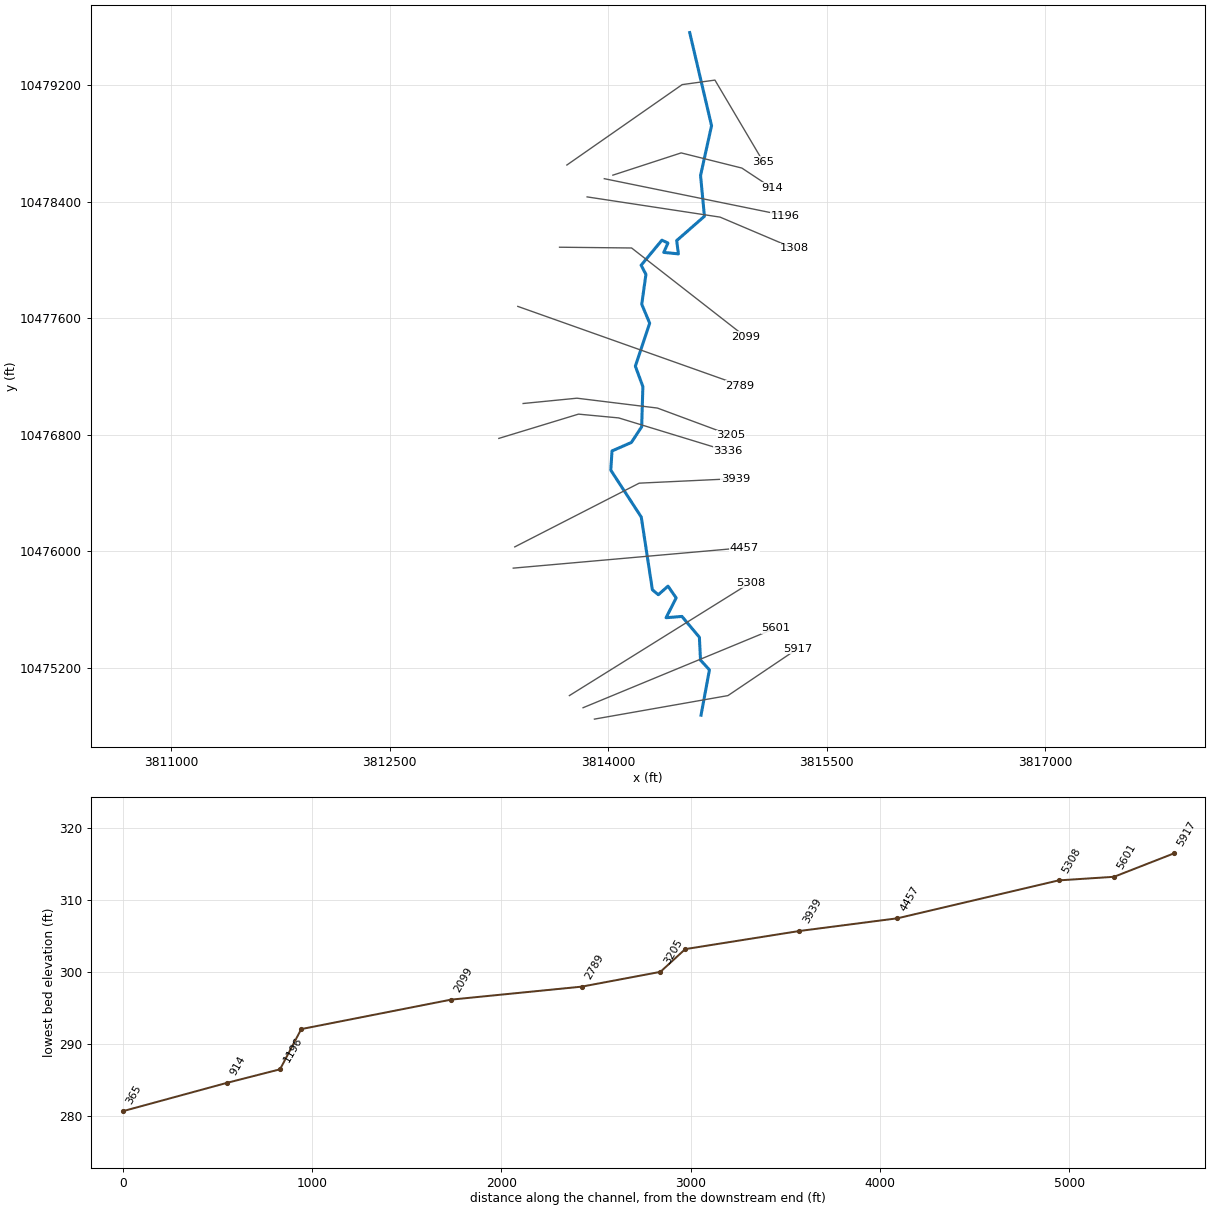
--- UNT163 IN BECR.prj (project) ---

Proj Title=UNT163 IN BECR Base Level Engineering
Current Plan=p01
Default Exp/Contr=0.3,0.1
English Units
Geom File=g01
Flow File=f01
Plan File=p01
BEGIN DESCRIPTION:
UNT163 IN BECR
END DESCRIPTION:

--- UNT163 IN BECR.p01 (plan) ---

Plan Title=Multiple Run
Short Identifier=Multiple
Geom File=g01
Flow File=f01
Subcritical Flow
K Sum by GR= 0
Std Step Tol= 0.01
Critical Tol= 0.01
Num of Std Step Trials= 20
Max Error Tol= 0.3
Flow Tol Ratio= 0.001
Split Flow NTrial= 30
Split Flow Tol= 0.02
Split Flow Ratio= 0.02
Log Output Level= 0
Friction Slope Method= 1
Unsteady Friction Slope Method= 2
Unsteady Bridges Friction Slope Method= 1
Parabolic Critical Depth
Global Vel Dist=  1 , 1 , 1
Global Log Level= 0
CheckData=True
Encroach Param= -1, 0, 0, 0
BEGIN DESCRIPTION:
Multiple Run
END DESCRIPTION:

--- UNT163 IN BECR.f01 (steady flow) ---

Flow Title=Multiple
Number of Profiles=7
Profile Names=10-year,25-year,50-year,1pct_min,100-year,1pct_plu,500-year
River Rch & RM= UNT163 IN BECR,Reach-1,5917
     424     558     665     584     789    1068    1114
Boundary for River Rch & Prof#=UNT163 IN BECR,Reach-1,1
Up Type=0
Dn Type=3
Dn Slope=0.005
Boundary for River Rch & Prof#=UNT163 IN BECR,Reach-1,2
Up Type=0
Dn Type=3
Dn Slope=0.005
Boundary for River Rch & Prof#=UNT163 IN BECR,Reach-1,3
Up Type=0
Dn Type=3
Dn Slope=0.005
Boundary for River Rch & Prof#=UNT163 IN BECR,Reach-1,4
Up Type=0
Dn Type=3
Dn Slope=0.005
Boundary for River Rch & Prof#=UNT163 IN BECR,Reach-1,5
Up Type=0
Dn Type=3
Dn Slope=0.005
Boundary for River Rch & Prof#=UNT163 IN BECR,Reach-1,6
Up Type=0
Dn Type=3
Dn Slope=0.005
Boundary for River Rch & Prof#=UNT163 IN BECR,Reach-1,7
Up Type=0
Dn Type=3
Dn Slope=0.005

--- UNT163 IN BECR.g01 (geometry) ---

Geom Title=Existing Conditions

River Reach=UNT163 IN BECR,Reach-1
Reach XY= 30
      3814637.25     10474874.00      3814695.00     10475185.00
      3814633.75     10475252.00      3814626.00     10475409.00
      3814506.00     10475552.00      3814397.25     10475543.00
      3814466.50     10475679.00      3814410.50     10475760.00
      3814344.00     10475701.00      3814303.25     10475735.00
      3814227.00     10476234.00      3814017.75     10476556.00
      3814026.00     10476688.00      3814158.75     10476746.00
      3814229.75     10476854.00      3814238.00     10477130.00
      3814186.25     10477270.00      3814284.75     10477565.00
      3814230.25     10477695.00      3814259.00     10477900.00
      3814226.00     10477963.00      3814368.75     10478135.00
      3814410.00     10478115.00      3814381.25     10478051.00
      3814482.00     10478041.00      3814470.00     10478132.00
      3814660.50     10478299.00      3814634.00     10478579.00
      3814709.50     10478921.00      3814559.50     10479560.00

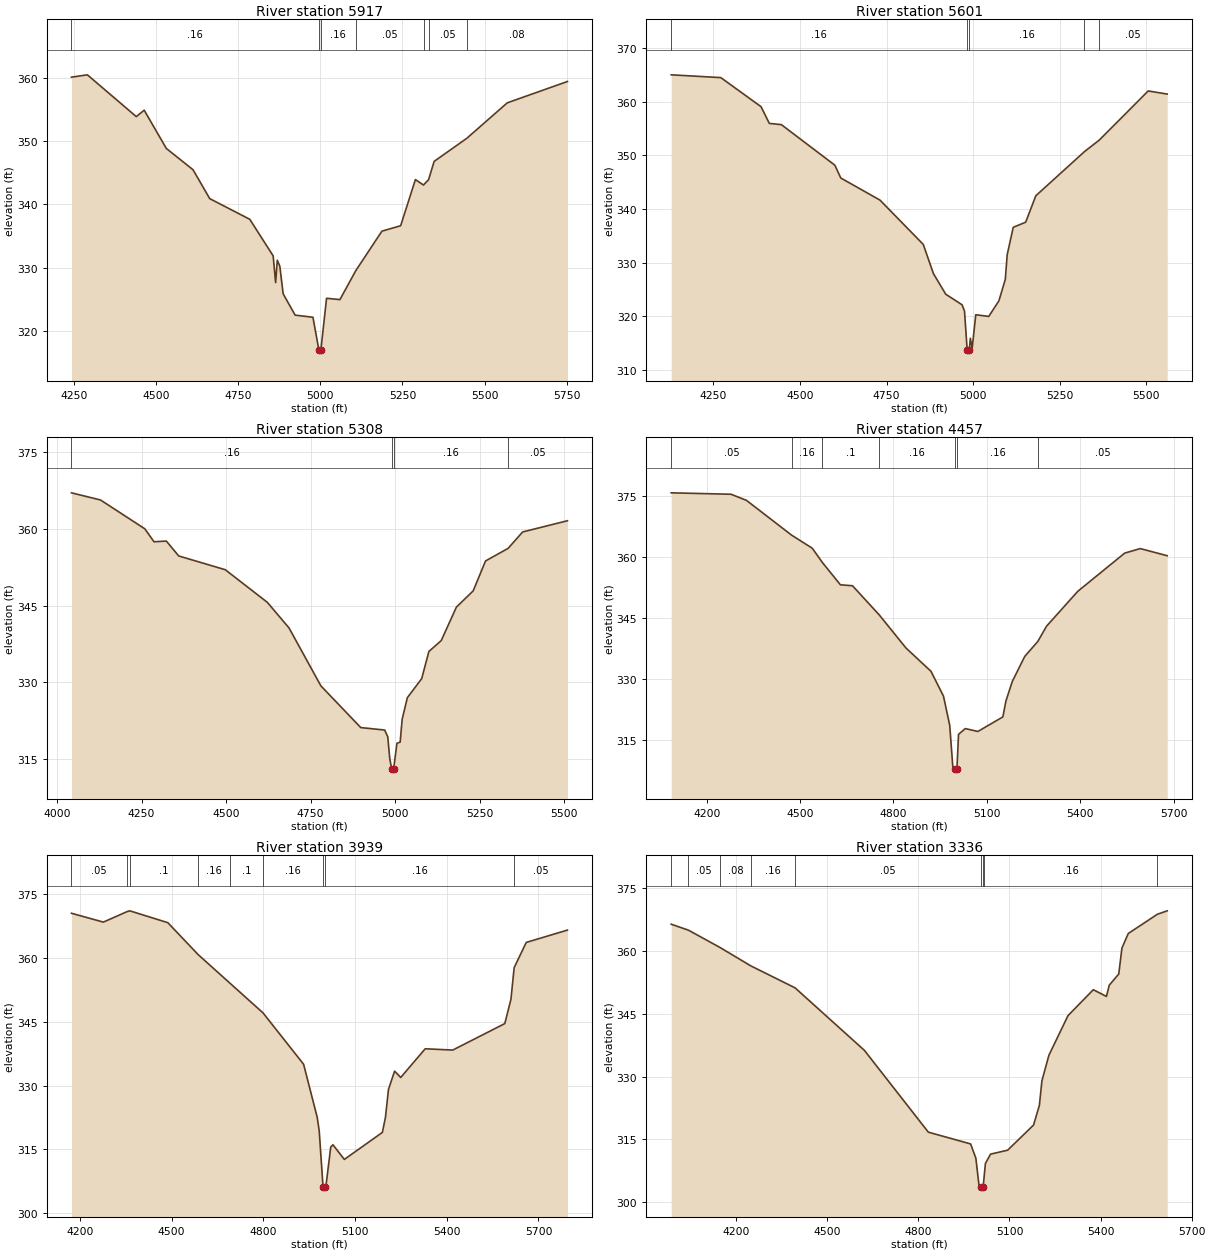
Type RM Length L Ch R = 1,5917,316,316,316
BEGIN DESCRIPTION:
UNT163 IN BECR 11.0
END DESCRIPTION:
XS GIS Cut Line= 3
      3813905.43     10474847.05      3814822.07     10475008.50
      3815301.26     10475331.43
#Sta/Elev= 30
  4243.1  360.20  4291.5  360.57  4440.3  353.94  4464.3  354.96  4531.7  348.89
  4612.9  345.51  4663.7  340.93  4785.5  337.65  4856.6  331.85  4864.1  327.61
  4869.2  331.16  4876.9  330.20  4887.0  325.83  4923.4  322.45  4977.6  322.11
  4995.7  316.92  4998.5  316.42  5001.7  316.92  5019.0  325.12  5059.7  324.91
  5107.9  329.50  5187.4  335.77  5244.4  336.63  5289.3  343.95  5313.9  343.09
  5329.4  343.94  5346.3  346.84  5445.6  350.50  5568.8  356.13  5751.7  359.51
#Mann=7,-1,0
  4243.1    0.16       0  4995.7    0.07       0  5001.7    0.16       0
  5107.9    0.05       0  5313.9    0.16       0  5329.4    0.05       0
  5445.6    0.08       0
Bank Sta=4995.7,5001.7
Exp/Cntr=0.3,0.1

Type RM Length L Ch R = 1,5601,293,293,293
BEGIN DESCRIPTION:
UNT163 IN BECR 10.0
END DESCRIPTION:
XS GIS Cut Line= 2
      3813827.32     10474925.18      3815150.24     10475472.06
#Sta/Elev= 30
  4128.6  364.97  4271.8  364.45  4387.9  359.04  4411.8  355.93  4446.5  355.70
  4600.8  348.16  4618.0  345.77  4731.1  341.66  4856.1  333.41  4885.4  327.98
  4921.0  324.14  4968.0  322.18  4975.1  321.01  4982.9  313.68  4985.7  313.18
  4988.9  313.68  4991.9  315.95  4997.3  314.12  5007.6  320.32  5045.1  320.01
  5074.4  322.91  5092.9  326.91  5098.3  331.49  5115.8  336.60  5151.6  337.54
  5180.9  342.46  5321.3  350.68  5364.0  352.82  5505.3  361.97  5560.1  361.39
#Mann=5,-1,0
  4128.6    0.16       0  4982.9    0.07       0  4988.9    0.16       0
  5321.3    0.08       0  5364.0    0.05       0
Bank Sta=4982.9,4988.9
Exp/Cntr=0.3,0.1

Type RM Length L Ch R = 1,5308,851,851,851
BEGIN DESCRIPTION:
UNT163 IN BECR 9.0
END DESCRIPTION:
XS GIS Cut Line= 2
      3813733.56     10475008.52      3814978.28     10475784.52
#Sta/Elev= 30
  4042.8  367.00  4128.8  365.60  4259.7  359.98  4286.9  357.45  4323.4  357.58
  4360.0  354.68  4497.7  351.99  4622.0  345.63  4686.3  340.62  4780.5  329.32
  4898.4  321.18  4969.1  320.70  4978.3  319.37  4984.2  315.09  4989.7  313.18
  4992.4  312.68  4995.7  313.18  5005.4  318.11  5014.9  318.34  5020.8  322.79
  5036.1  327.01  5078.6  330.73  5099.8  336.03  5136.4  338.16  5181.2  344.69
  5230.8  347.86  5267.4  353.70  5334.2  356.16  5377.1  359.36  5509.6  361.55
#Mann=4,-1,0
  4042.8    0.16       0  4989.7    0.07       0  4995.7    0.16       0
  5334.2    0.05       0
Bank Sta=4989.7,4995.7
Exp/Cntr=0.3,0.1

Type RM Length L Ch R = 1,4457,518,518,518
BEGIN DESCRIPTION:
UNT163 IN BECR 8.0
END DESCRIPTION:
XS GIS Cut Line= 2
      3813348.07     10475883.50      3814935.66     10476024.04
#Sta/Elev= 30
  4085.8  375.66  4278.1  375.31  4327.5  373.82  4472.8  365.28  4539.1  362.08
  4571.7  358.57  4629.5  353.11  4668.3  352.88  4754.0  345.76  4840.3  337.61
  4920.6  331.90  4960.7  325.82  4980.8  318.65  4990.9  308.30  4997.9  307.93
  5000.7  307.43  5003.9  307.93  5009.1  316.46  5031.0  317.86  5071.2  317.15
  5151.5  320.72  5161.5  324.66  5181.6  329.37  5221.8  335.54  5264.0  339.24
  5292.0  342.97  5392.4  351.52  5543.0  360.88  5593.2  361.99  5679.6  360.24
#Mann=7,-1,0
  4085.8    0.05       0  4472.8    0.16       0  4571.7     0.1       0
  4754.0    0.16       0  4997.9    0.07       0  5003.9    0.16       0
  5264.0    0.05       0
Bank Sta=4997.9,5003.9
Exp/Cntr=0.3,0.1

Type RM Length L Ch R = 1,3939,603,603,603
BEGIN DESCRIPTION:
UNT163 IN BECR 7.0
END DESCRIPTION:
XS GIS Cut Line= 3
      3813358.53     10476029.34      3814212.70     10476466.83
      3814874.17     10476498.08
#Sta/Elev= 30
  4172.8  370.48  4277.1  368.40  4354.2  370.85  4363.5  371.05  4487.9  368.27
  4586.8  360.79  4690.3  354.10  4799.3  347.07  4931.9  335.01  4976.3  322.59
  4983.0  319.35  4995.5  306.17  4998.3  305.67  5001.5  306.17  5005.4  306.62
  5020.7  315.57  5027.9  316.09  5065.1  312.65  5189.5  318.99  5199.5  322.49
  5209.5  329.09  5229.5  333.39  5249.5  331.90  5329.6  338.64  5419.7  338.34
  5589.9  344.56  5609.9  350.24  5620.5  357.70  5660.0  363.63  5794.7  366.52
#Mann=9,-1,0
  4172.8    0.05       0  4354.2    0.16       0  4363.5     0.1       0
  4586.8    0.16       0  4690.3     0.1       0  4799.3    0.16       0
  4995.5    0.07       0  5001.5    0.16       0  5620.5    0.05       0
Bank Sta=4995.5,5001.5
Exp/Cntr=0.3,0.1

Type RM Length L Ch R = 1,3336,131,131,131
BEGIN DESCRIPTION:
UNT163 IN BECR 6.0
END DESCRIPTION:
XS GIS Cut Line= 4
      3813249.11     10476774.11      3813796.03     10476940.79
      3814072.07     10476914.75      3814822.11     10476685.57
#Sta/Elev= 30
  3986.1  366.30  4042.9  364.88  4146.6  360.76  4248.7  356.35  4393.8  351.14
  4622.1  336.25  4832.8  316.74  4972.1  313.93  4989.4  310.52  4999.7  304.04
  5007.3  303.66  5010.1  303.16  5013.3  303.66  5016.5  306.06  5020.8  309.28
  5037.7  311.50  5094.0  312.44  5179.3  318.43  5198.5  323.13  5206.9  328.98
  5229.9  335.07  5292.6  344.49  5376.1  350.69  5419.4  349.09  5428.6  351.76
  5459.9  354.43  5470.4  360.62  5491.3  364.09  5587.1  368.67  5619.4  369.49
#Mann=9,-1,0
  3986.1    0.08       0  4042.9    0.05       0  4146.6    0.08       0
  4248.7    0.16       0  4393.8    0.05       0  5007.3    0.04       0
  5013.3    0.05       0  5016.5    0.16       0  5587.1    0.08       0
Bank Sta=5007.3,5013.3
Exp/Cntr=0.3,0.1

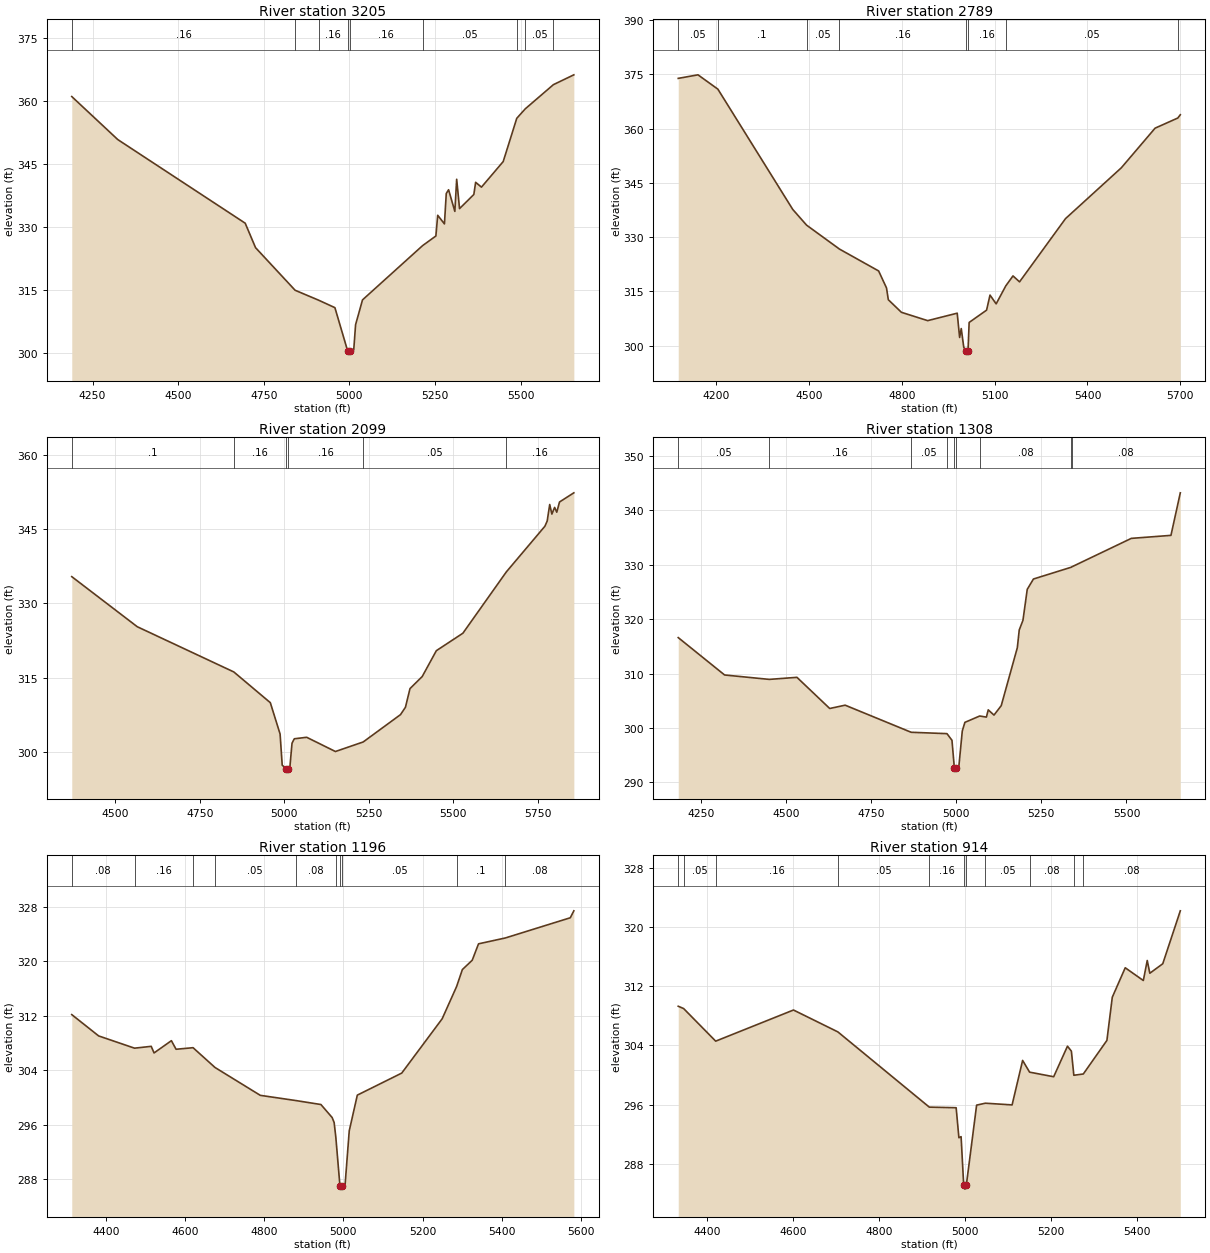
Type RM Length L Ch R = 1,3205,416,416,416
BEGIN DESCRIPTION:
UNT163 IN BECR 5.0
END DESCRIPTION:
XS GIS Cut Line= 4
      3813415.87     10477013.71      3813785.61     10477050.17
      3814337.70     10476982.46      3814842.59     10476795.08
#Sta/Elev= 30
  4189.2  361.07  4323.6  350.83  4695.7  330.93  4726.0  325.10  4841.5  314.97
  4909.8  312.62  4957.7  310.83  4995.0  300.51  4997.7  300.01  5001.0  300.51
  5012.7  300.81  5018.1  306.78  5038.3  312.68  5213.9  325.60  5252.6  327.89
  5257.9  332.82  5277.6  330.76  5282.9  337.99  5289.7  338.89  5308.0  333.74
  5313.3  341.39  5321.7  334.40  5363.4  337.76  5368.7  340.66  5385.7  339.51
  5449.2  345.60  5488.8  355.89  5513.8  358.16  5595.8  363.90  5655.5  366.24
#Mann=9,-1,0
  4189.2    0.16       0  4841.5    0.05       0  4909.8    0.16       0
  4995.0    0.07       0  5001.0    0.16       0  5213.9    0.05       0
  5488.8    0.16       0  5513.8    0.05       0  5595.8    0.08       0
Bank Sta=4995,5001
Exp/Cntr=0.3,0.1

Type RM Length L Ch R = 1,2789,690,690,690
BEGIN DESCRIPTION:
UNT163 IN BECR 4.0
END DESCRIPTION:
XS GIS Cut Line= 3
      3813379.35     10477680.38      3814905.40     10477138.71
      3814905.40     10477134.34
#Sta/Elev= 30
  4076.6  373.90  4140.5  374.88  4204.8  370.92  4446.9  337.68  4491.7  333.33
  4598.0  326.72  4724.7  320.67  4750.2  315.96  4756.0  312.72  4798.4  309.24
  4883.3  306.94  4978.8  309.00  4986.6  302.29  4991.9  304.75  5000.0  299.57
  5007.7  298.46  5010.4  297.96  5013.7  298.46  5017.4  306.44  5073.8  309.84
  5084.9  314.01  5104.7  311.57  5136.0  316.56  5159.2  319.30  5180.4  317.66
  5329.0  335.13  5509.4  349.17  5618.8  360.14  5692.2  362.94  5700.3  363.84
#Mann=8,-1,0
  4076.6    0.05       0  4204.8     0.1       0  4491.7    0.05       0
  4598.0    0.16       0  5007.7    0.07       0  5013.7    0.16       0
  5136.0    0.05       0  5692.2    0.08       0
Bank Sta=5007.7,5013.7
Exp/Cntr=0.3,0.1

Type RM Length L Ch R = 1,2099,791,791,791
BEGIN DESCRIPTION:
UNT163 IN BECR 3.0
END DESCRIPTION:
XS GIS Cut Line= 3
      3813665.82     10478086.63      3814160.61     10478081.42
      3814941.84     10477472.06
#Sta/Elev= 30
  4370.9  335.42  4564.7  325.31  4850.4  316.18  4958.4  309.98  4987.3  303.65
  4993.6  297.36  5005.1  296.66  5007.9  296.16  5011.1  296.66  5016.2  296.90
  5022.6  301.79  5029.3  302.69  5066.0  302.99  5151.0  300.12  5233.3  302.05
  5343.7  307.57  5358.2  309.05  5371.7  312.82  5407.9  315.26  5449.6  320.47
  5528.2  324.00  5656.9  336.39  5770.7  345.58  5777.6  346.63  5785.1  349.98
  5791.5  348.05  5799.6  349.40  5806.0  348.43  5814.1  350.49  5856.5  352.34
#Mann=6,-1,0
  4370.9     0.1       0  4850.4    0.16       0  5005.1    0.07       0
  5011.1    0.16       0  5233.3    0.05       0  5656.9    0.16       0
Bank Sta=5005.1,5011.1
Exp/Cntr=0.3,0.1

Type RM Length L Ch R = 1,1308,112,112,112
BEGIN DESCRIPTION:
UNT163 IN BECR 2.0
END DESCRIPTION:
XS GIS Cut Line= 3
      3813855.08     10478432.11      3814768.25     10478293.22
      3815274.89     10478078.08
#Sta/Elev= 30
  4184.0  316.62  4320.1  309.75  4451.4  308.94  4532.5  309.32  4628.8  303.59
  4674.1  304.20  4867.9  299.22  4973.0  298.97  4987.7  297.74  4994.8  292.58
  4997.5  292.08  5000.8  292.58  5007.9  292.94  5018.0  299.47  5025.6  301.04
  5069.1  302.21  5088.8  302.01  5094.2  303.34  5111.1  302.38  5132.3  304.11
  5179.6  314.77  5185.2  318.03  5196.1  319.79  5208.7  325.49  5226.9  327.39
  5337.6  329.55  5339.4  329.62  5514.3  334.86  5630.6  335.41  5658.1  343.23
#Mann=9,-1,0
  4184.0    0.05       0  4451.4    0.16       0  4867.9    0.05       0
  4973.0    0.16       0  4994.8    0.07       0  5000.8    0.16       0
  5069.1    0.08       0  5337.6    0.05       0  5339.4    0.08       0
Bank Sta=4994.8,5000.8
Exp/Cntr=0.3,0.1

Type RM Length L Ch R = 1,1196,282,282,282
BEGIN DESCRIPTION:
Mapping XS 88a63289
END DESCRIPTION:
XS GIS Cut Line= 2
      3813973.08     10478557.12      3815215.42     10478303.79
#Sta/Elev= 30
  4314.2  312.15  4382.1  309.02  4472.7  307.22  4514.8  307.49  4522.0  306.52
  4565.8  308.32  4577.6  307.06  4620.5  307.29  4676.0  304.38  4790.3  300.29
  4879.4  299.53  4943.4  298.94  4971.7  297.03  4976.8  296.29  4981.0  294.16
  4991.4  287.01  4994.2  286.51  4997.4  287.01  5004.6  287.29  5014.9  295.07
  5035.3  300.32  5147.5  303.56  5249.6  311.54  5286.0  316.27  5300.6  318.77
  5325.5  320.14  5341.4  322.55  5409.0  323.41  5573.1  326.38  5582.1  327.40
#Mann=10,-1,0
  4314.2    0.08       0  4472.7    0.16       0  4620.5    0.08       0
  4676.0    0.05       0  4879.4    0.08       0  4981.0    0.05       0
  4991.4    0.04       0  4997.4    0.05       0  5286.0     0.1       0
  5409.0    0.08       0
Bank Sta=4991.4,4997.4
Exp/Cntr=0.3,0.1

Type RM Length L Ch R = 1,914,549,549,549
BEGIN DESCRIPTION:
Mapping XS dec42a19
END DESCRIPTION:
XS GIS Cut Line= 4
      3814032.13     10478581.41      3814500.89     10478734.19
      3814917.56     10478630.03      3815122.00     10478494.89
#Sta/Elev= 30
  4332.3  309.29  4344.8  308.98  4419.4  304.58  4600.3  308.78  4703.5  305.83
  4916.2  295.68  4978.6  295.60  4985.0  291.55  4990.1  291.70  4996.2  285.12
  4999.0  284.62  5002.2  285.12  5026.2  295.95  5046.6  296.21  5108.7  295.98
  5133.2  301.98  5149.4  300.40  5205.4  299.78  5237.5  303.90  5246.6  303.23
  5252.3  299.98  5274.3  300.15  5329.2  304.68  5341.7  310.50  5371.8  314.48
  5413.9  312.76  5423.0  315.46  5429.0  313.74  5459.1  315.02  5499.9  322.16
#Mann=11,-1,0
  4332.3    0.08       0  4344.8    0.05       0  4419.4    0.16       0
  4703.5    0.05       0  4916.2    0.16       0  4996.2    0.07       0
  5002.2    0.16       0  5046.6    0.05       0  5149.4    0.08       0
  5252.3     0.1       0  5274.3    0.08       0
Bank Sta=4996.2,5002.2
Exp/Cntr=0.3,0.1

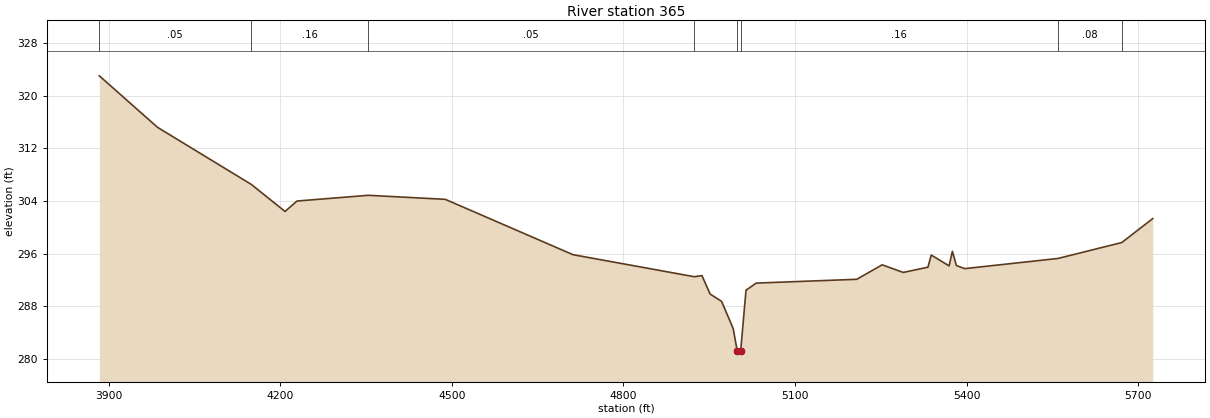
Type RM Length L Ch R = 1,365,0,0,0
BEGIN DESCRIPTION:
UNT163 IN BECR 1.0
END DESCRIPTION:
XS GIS Cut Line= 4
      3813716.18     10478650.87      3814507.83     10479202.94
      3814732.71     10479233.98      3815063.56     10478674.77
#Sta/Elev= 30
  3883.7  323.02  3985.4  315.19  4149.2  306.52  4208.4  302.40  4229.4  303.98
  4353.9  304.85  4488.5  304.24  4711.9  295.82  4924.1  292.47  4937.4  292.64
  4951.6  289.84  4971.8  288.72  4992.0  284.58  4999.1  281.20  5001.8  280.70
  5005.1  281.20  5014.4  290.42  5032.3  291.50  5208.1  292.08  5252.5  294.28
  5289.4  293.12  5332.5  293.92  5338.3  295.77  5369.5  294.12  5375.3  296.33
  5382.3  294.17  5396.8  293.70  5560.0  295.25  5671.5  297.67  5725.6  301.31
#Mann=8,-1,0
  3883.7    0.05       0  4149.2    0.16       0  4353.9    0.05       0
  4924.1    0.16       0  4999.1    0.07       0  5005.1    0.16       0
  5560.0    0.08       0  5671.5     0.1       0
Bank Sta=4999.1,5005.1
Exp/Cntr=0.3,0.1

Chan Stop Cuts=-1