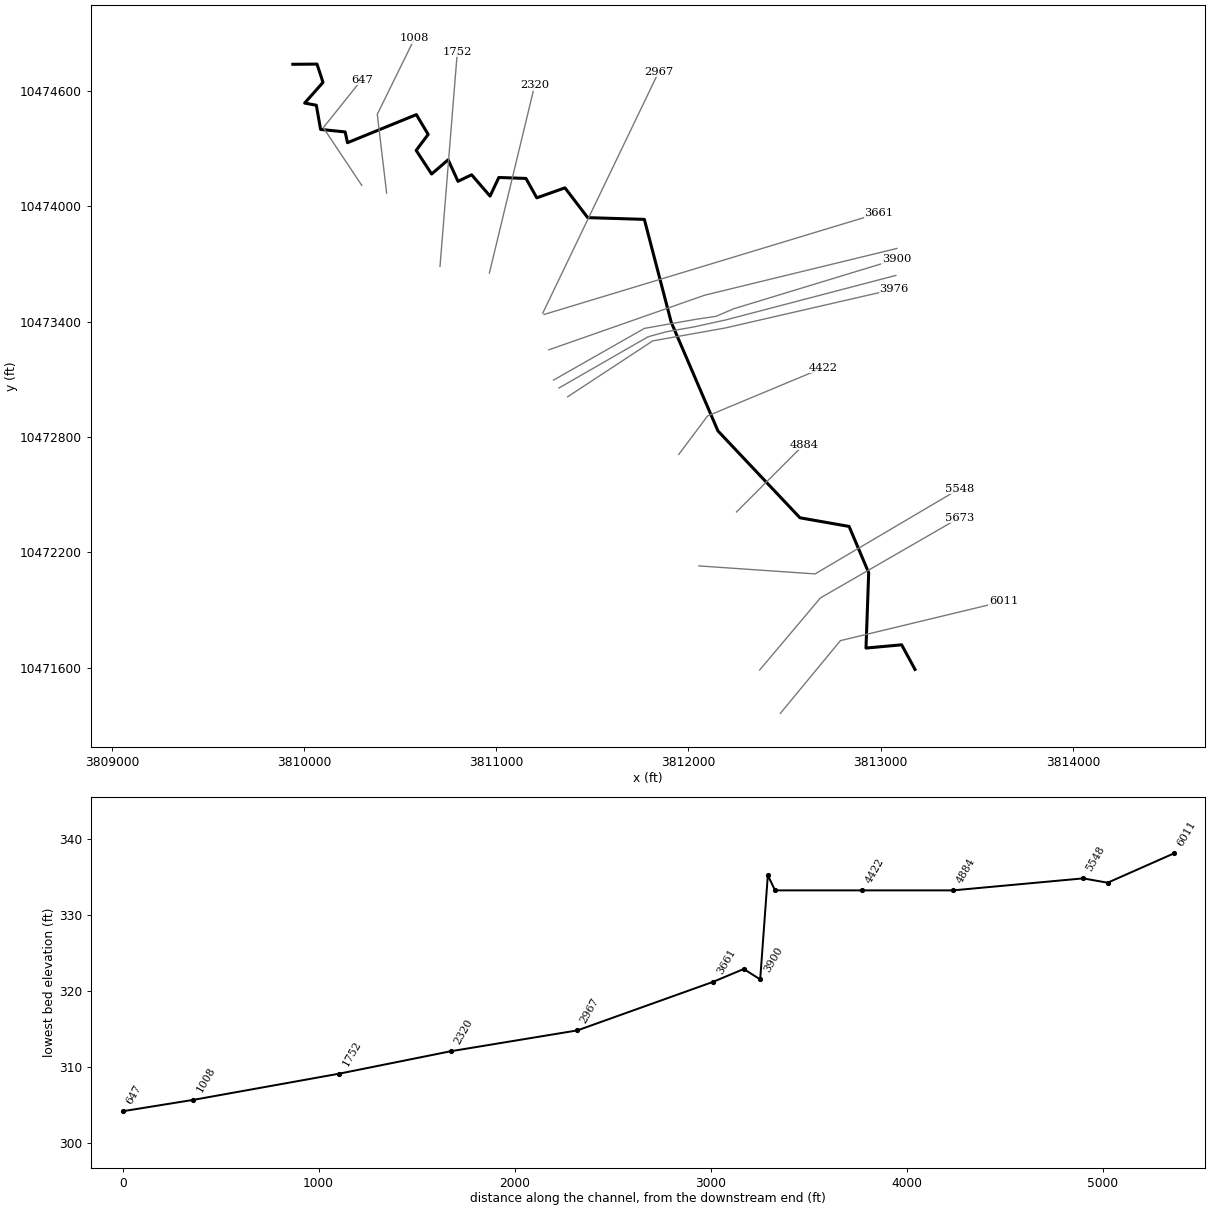
--- UNT164 IN BECR.prj (project) ---

Proj Title=UNT164 IN BECR Base Level Engineering
Current Plan=p01
Default Exp/Contr=0.3,0.1
English Units
Geom File=g01
Flow File=f01
Plan File=p01
Y Axis Title=Elevation
X Axis Title(PF)=Main Channel Distance
X Axis Title(XS)=Station
BEGIN DESCRIPTION:
UNT164 IN BECR
END DESCRIPTION:
DSS Export Rating Curves= 0
DSS Export Rating Curve Sorted= 0
DSS Export Volume Flow Curves= 0
DXF OffsetX= 0
DXF OffsetY= 0
DXF ScaleX= 1
DXF ScaleY= 10

--- UNT164 IN BECR.p01 (plan) ---

Plan Title=Multiple Run
Short Identifier=Multiple
Geom File=g01
Flow File=f01
Subcritical Flow
K Sum by GR= 0
Std Step Tol= 0.01
Critical Tol= 0.01
Num of Std Step Trials= 20
Max Error Tol= 0.3
Flow Tol Ratio= 0.001
Split Flow NTrial= 30
Split Flow Tol= 0.02
Split Flow Ratio= 0.02
Log Output Level= 0
Friction Slope Method= 1
Unsteady Friction Slope Method= 2
Unsteady Bridges Friction Slope Method= 1
Parabolic Critical Depth
Global Vel Dist=  1 , 1 , 1
Global Log Level= 0
CheckData=True
Encroach Param= -1, 0, 0, 0
BEGIN DESCRIPTION:
Multiple Run
END DESCRIPTION:

--- UNT164 IN BECR.f01 (steady flow) ---

Flow Title=Multiple
Program Version=4.10
Number of Profiles= 7
Profile Names=10-year,25-year,50-year,1pct_min,100-year,1pct_plu,500-year
River Rch & RM=UNT164 IN BECR,Reach-1         ,6011
     399     526     627     551     746    1008    1056
Boundary for River Rch & Prof#=UNT164 IN BECR,Reach-1         , 1
Up Type= 0
Dn Type= 3
Dn Slope=0.0046
Boundary for River Rch & Prof#=UNT164 IN BECR,Reach-1         , 2
Up Type= 0
Dn Type= 3
Dn Slope=0.0046
Boundary for River Rch & Prof#=UNT164 IN BECR,Reach-1         , 3
Up Type= 0
Dn Type= 3
Dn Slope=0.0046
Boundary for River Rch & Prof#=UNT164 IN BECR,Reach-1         , 4
Up Type= 0
Dn Type= 3
Dn Slope=0.0046
Boundary for River Rch & Prof#=UNT164 IN BECR,Reach-1         , 5
Up Type= 0
Dn Type= 3
Dn Slope=0.0046
Boundary for River Rch & Prof#=UNT164 IN BECR,Reach-1         , 6
Up Type= 0
Dn Type= 3
Dn Slope=0.0046
Boundary for River Rch & Prof#=UNT164 IN BECR,Reach-1         , 7
Up Type= 0
Dn Type= 3
Dn Slope=0.0046
DSS Import GetInterval= 0
DSS Import GetPeak= 0
DSS Import FillOption= 0

--- UNT164 IN BECR.g01 (geometry) ---

Geom Title=Existing Conditions
Program Version=4.10

River Reach=UNT164 IN BECR  ,Reach-1
Reach XY= 30
      3813178.75       10471591.      3813109.25       10471719.
      3812923.75       10471702.      3812937.75       10472094.
      3812835.75       10472335.        3812580.       10472380.
      3812153.25       10472832.        3811910.       10473398.
      3811770.25       10473933.       3811475.5       10473942.
      3811357.25       10474097.       3811210.5       10474045.
      3811154.25       10474146.        3811013.       10474151.
      3810967.25       10474054.       3810871.5       10474165.
       3810800.5       10474131.      3810749.25       10474243.
      3810663.25       10474169.      3810582.75       10474292.
      3810645.25       10474375.      3810583.75       10474478.
       3810225.5       10474332.      3810213.25       10474388.
       3810085.5       10474401.      3810063.25       10474527.
       3810002.5       10474538.        3810098.       10474646.
      3810066.75       10474741.        3809941.       10474740.

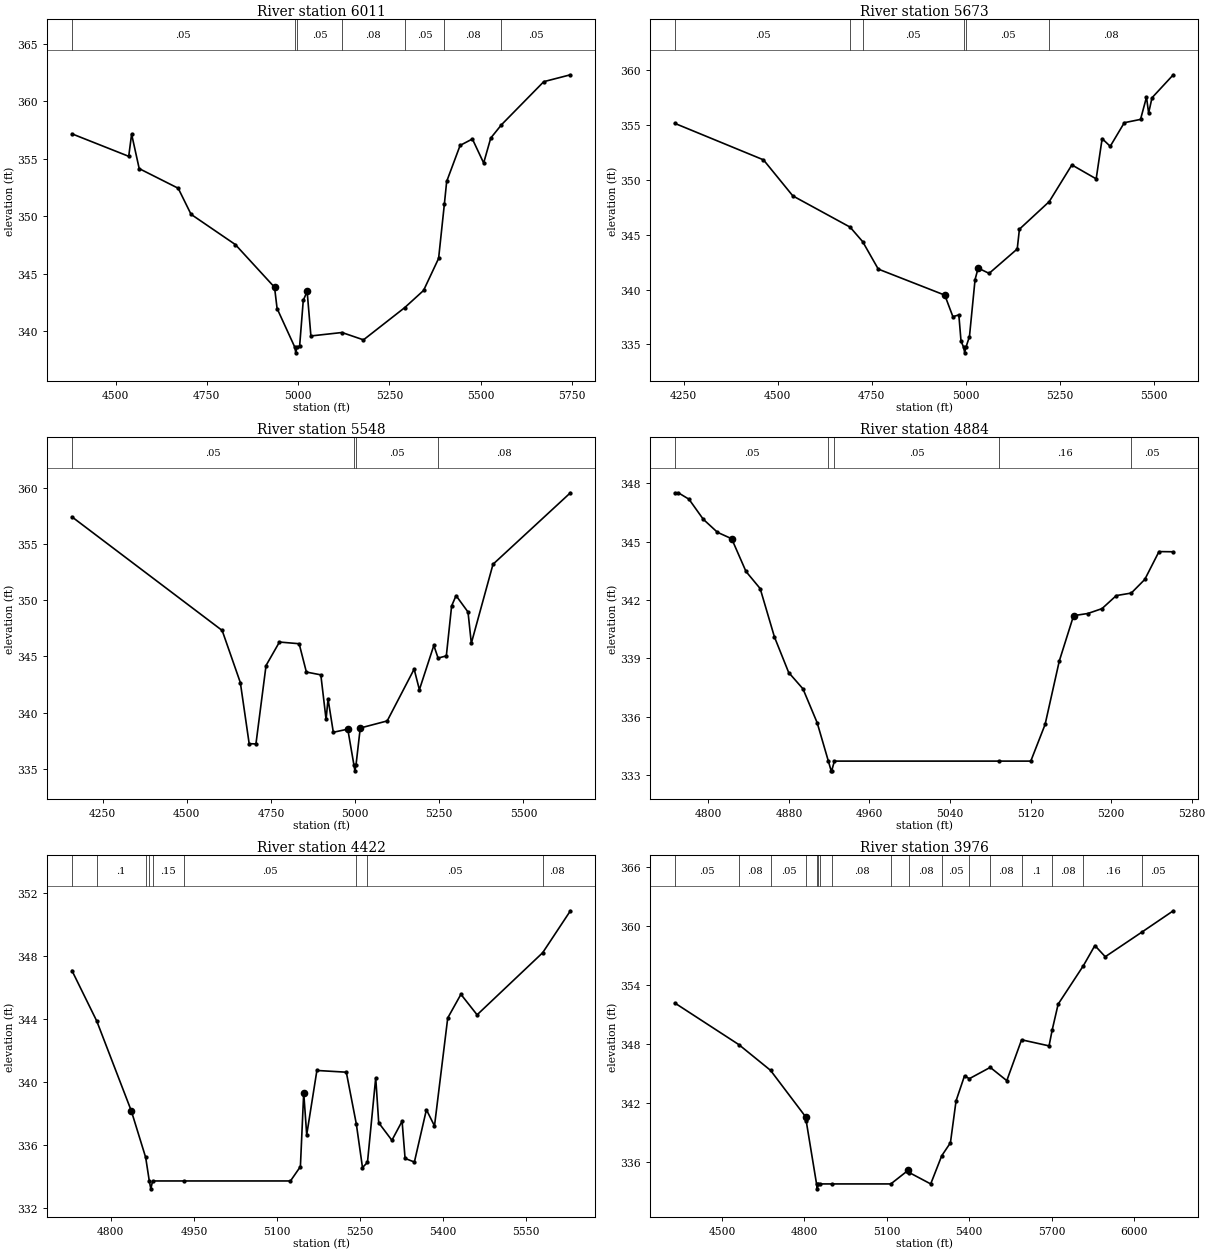
Type RM Length L Ch R = 1 ,6011    ,338,338,338
BEGIN DESCRIPTION:
UNT164 IN BECR 12.0
END DESCRIPTION:
XS GIS Cut Line= 3
      3812478.02     10471362.16      3812790.53     10471740.64
       3813640.6     10471945.35
#Sta/Elev= 30
  4380.4  357.17    4536  355.21  4543.9  357.14  4564.7  354.14  4671.5  352.43
  4706.7  350.16  4827.9  347.53  4935.3  343.81  4942.3  341.96  4990.7   338.6
  4993.5   338.1  4996.7   338.6    5004  338.68    5014  342.67  5024.6  343.45
  5034.9  339.57    5120  339.87  5178.9  339.23  5291.9  342.04  5343.4  343.53
  5384.6  346.32  5400.4  351.05  5406.7  353.02  5443.5  356.16  5477.1  356.72
    5508  354.63  5527.4   356.8  5556.8  357.96  5672.6  361.71  5745.6  362.31
#Mann= 7 ,-1 , 0
  4380.4     .05       0  4990.7     .04       0  4996.7     .05       0
    5120     .08       0  5291.9     .05       0  5400.4     .08       0
  5556.8     .05       0
Bank Sta=4935.3,5024.6
XS Rating Curve= 0 ,0
Exp/Cntr=0.3,0.1

Type RM Length L Ch R = 1 ,5673    ,125,125,125
BEGIN DESCRIPTION:
UNT164 IN BECR 11.0
END DESCRIPTION:
XS GIS Cut Line= 3
      3812370.41     10471587.88      3812686.36     10471962.86
      3813408.55     10472379.51
#Sta/Elev= 30
  4226.5  355.12  4462.1   351.8  4540.1  348.52  4692.1  345.68  4725.5  344.36
    4767  341.86  4943.7  339.49  4965.2  337.53    4981  337.69  4986.8  335.31
  4993.8  334.74  4996.5  334.24  4999.8  334.74  5009.2  335.72  5024.1  340.91
  5032.3  341.95  5061.4  341.47  5136.1  343.69  5141.9  345.49  5221.1     348
  5281.2  351.34  5345.8  350.07  5361.6  353.73  5383.1  353.03  5420.5  355.18
  5463.6  355.48  5479.4   357.5  5485.1  356.06  5494.1  357.45  5550.6  359.54
#Mann= 6 ,-1 , 0
  4226.5     .05       0  4692.1     .08       0  4725.5     .05       0
  4993.8     .04       0  4999.8     .05       0  5221.1     .08       0
Bank Sta=4943.7,5032.3
XS Rating Curve= 0 ,0
Exp/Cntr=0.3,0.1

Type RM Length L Ch R = 1 ,5548    ,664,664,664
BEGIN DESCRIPTION:
UNT164 IN BECR 10.0
END DESCRIPTION:
XS GIS Cut Line= 3
      3812054.44     10472129.53      3812658.59     10472087.86
      3813412.09     10472532.32
#Sta/Elev= 30
    4159  357.41  4605.2   347.3  4659.2  342.66  4685.4  337.23  4705.5   337.2
  4735.5  344.18  4775.3  346.27  4833.8  346.12  4855.3   343.6  4898.2  343.35
  4913.8  339.38  4919.6  341.21  4935.3  338.24  4978.2  338.52  4996.6  335.31
  4999.4  334.81  5002.6  335.31  5015.3  338.62  5095.3  339.25  5175.3  343.86
  5190.9  342.03  5233.8  345.97  5246.4  344.84  5270.9  345.04  5286.6  349.48
  5299.8   350.4  5335.3  348.94  5345.1  346.16  5409.5  353.19  5639.4  359.55
#Mann= 4 ,-1 , 0
    4159     .05       0  4996.6     .04       0  5002.6     .05       0
  5246.4     .08       0
Bank Sta=4978.2,5015.3
XS Rating Curve= 0 ,0
Exp/Cntr=0.3,0.1

Type RM Length L Ch R = 1 ,4884    ,462,462,462
BEGIN DESCRIPTION:
UNT164 IN BECR 9.0
END DESCRIPTION:
XS GIS Cut Line= 3
      3812249.62      10472410.2      3812399.61     10472560.19
      3812599.64     10472760.22
#Sta/Elev= 28
  4766.7  347.51  4770.2  347.51  4780.8  347.18    4795  346.15  4809.1  345.48
  4823.2  345.15  4837.4  343.47  4851.5  342.59  4865.7   340.1  4879.8  338.28
    4894  337.44  4908.1   335.7  4919.2  333.73    4922  333.23  4922.5  333.23
  4925.2  333.73  5088.2  333.73  5120.2  333.73  5134.4  335.61  5148.5  338.87
  5162.7   341.2  5176.8  341.31  5190.9  341.56  5205.1  342.23    5220  342.36
  5233.4  343.06  5247.5  344.49  5261.7  344.48
#Mann= 5 ,-1 , 0
  4766.7     .05       0  4919.2    .033       0  4925.2     .05       0
  5088.2     .16       0    5220     .05       0
Bank Sta=4823.2,5162.7
XS Rating Curve= 0 ,0
Exp/Cntr=0.3,0.1

Type RM Length L Ch R = 1 ,4422    ,446,446,446
BEGIN DESCRIPTION:
UNT164 IN BECR 8.0
END DESCRIPTION:
XS GIS Cut Line= 3
      3811949.61     10472710.19      3812099.61     10472910.19
      3812699.61     10473160.19
#Sta/Elev= 30
  4729.7  347.08  4774.5  343.88    4837  338.17  4862.9  335.22  4869.4  333.73
  4872.2  333.23  4875.4  333.73  4931.3  333.73  5124.3  333.73  5142.2  334.64
  5148.2  339.33  5153.6  336.66    5172  340.74  5225.1  340.63  5243.2  337.34
  5254.3  334.58  5263.3  334.91  5278.2  340.28  5283.6  337.42  5307.4  336.31
  5325.8  337.52  5331.2  335.16    5348  334.93  5369.7  338.25  5384.3  337.22
  5408.2  344.07    5432  345.57  5461.2  344.27  5579.6  348.21  5629.7  350.87
#Mann= 9 ,-1 , 0
  4729.7     .05       0  4774.5      .1       0  4862.9     .15       0
  4869.4    .033       0  4875.4     .15       0  4931.3     .05       0
  5243.2     .16       0  5263.3     .05       0  5579.6     .08       0
Bank Sta=4837,5148.2
XS Rating Curve= 0 ,0
Exp/Cntr=0.3,0.1

Type RM Length L Ch R = 1 ,3976    ,37,37,37
BEGIN DESCRIPTION:
Mapping XS 18b1d7f0
END DESCRIPTION:
XS GIS Cut Line= 4
      3811371.23     10473009.72      3811813.97     10473300.54
      3812191.57     10473367.81      3813070.44     10473569.62
#Sta/Elev= 30
  4327.7  352.16  4560.9  347.92  4676.3   345.3  4804.3  340.56  4806.5   340.1
  4843.9  333.73  4846.7  333.23  4849.9  333.73  4854.7  333.73  4900.3  333.73
  5114.3  333.73    5178  335.13  5181.2  334.89  5259.5  333.73  5299.7   336.6
  5331.3  337.92  5351.8  342.19  5382.6  344.74  5400.2  344.45  5476.3   345.6
  5536.5  344.25  5590.4  348.41  5690.4  347.79  5701.8  349.41  5723.5  352.04
  5815.4  355.96  5857.2  358.01    5895  356.87  6027.4  359.36  6142.7  361.55
#Mann= 17 ,-1 , 0
  4327.7     .05       0  4560.9     .08       0  4676.3     .05       0
  4806.5     .08       0  4843.9     .07       0  4849.9     .08       0
  4854.7     .05       0  4900.3     .08       0  5114.3     .05       0
  5181.2     .08       0  5299.7     .05       0  5400.2     .16       0
  5476.3     .08       0  5590.4      .1       0  5701.8     .08       0
  5815.4     .16       0  6027.4     .05       0
Bank Sta=4804.3,5178
XS Rating Curve= 0 ,0
Exp/Cntr=0.3,0.1

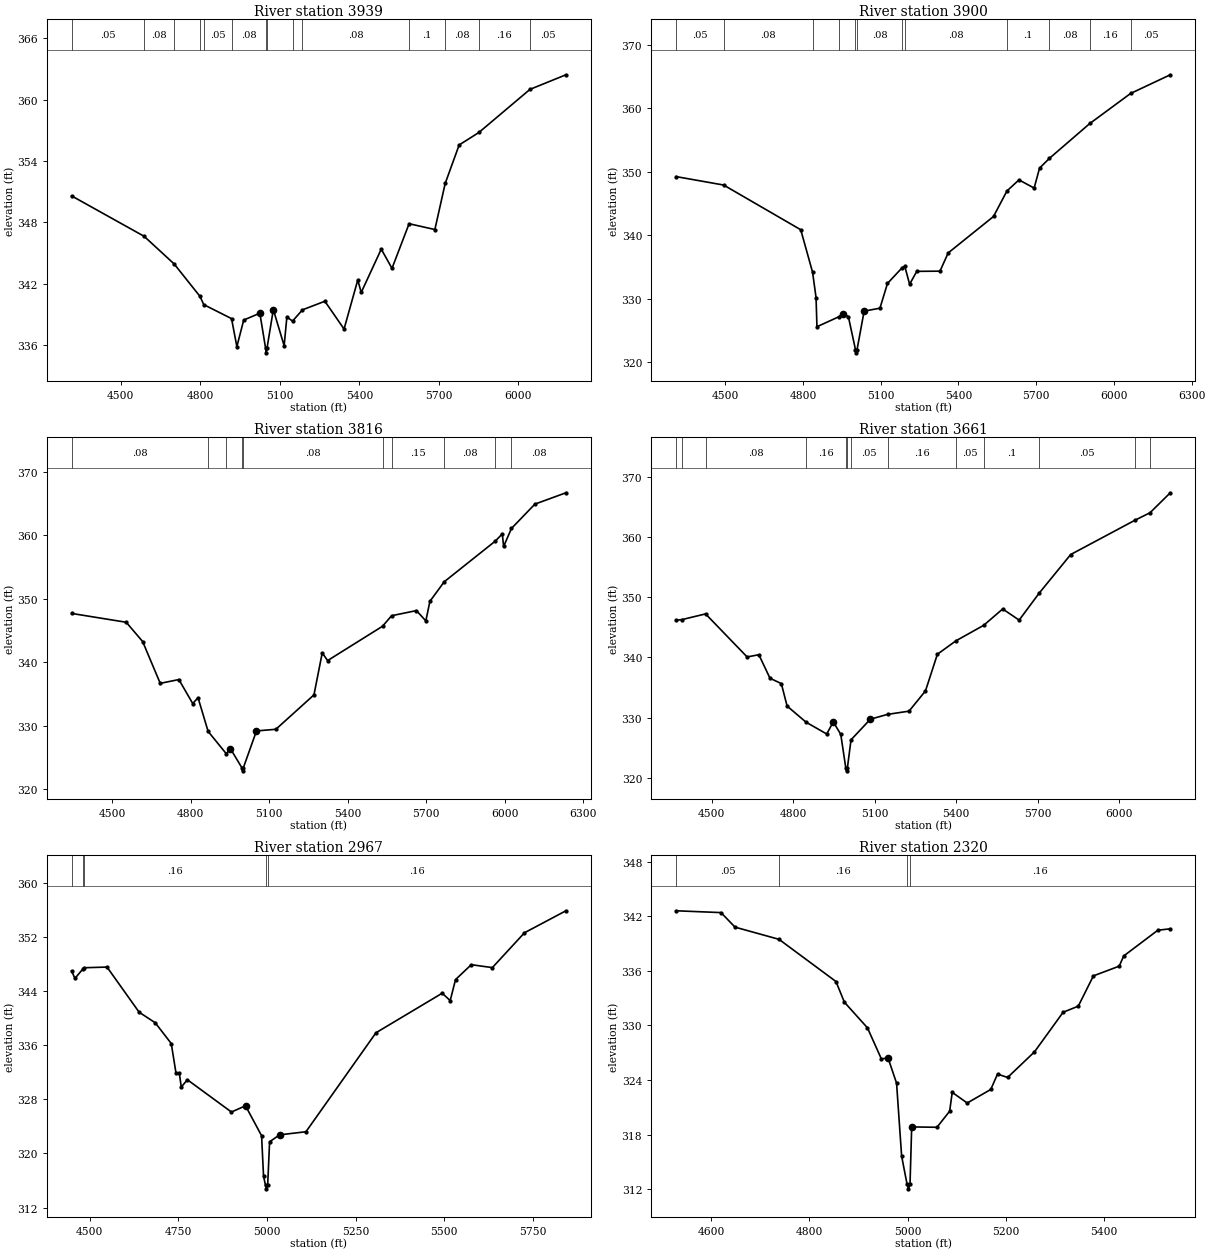
Type RM Length L Ch R = 1 ,3939    ,39,39,39
BEGIN DESCRIPTION:
Mapping XS 4bfb70ac
END DESCRIPTION:
XS GIS Cut Line= 6
      3811325.72     10473055.33       3811790.1     10473322.24
      3811885.58     10473348.28       3812022.3     10473372.15
      3812191.57     10473409.04      3813079.18     10473641.25
#Sta/Elev= 30
  4315.1  350.58  4588.2  346.63  4701.6  343.92  4799.2  340.74  4813.2  339.94
    4918  338.57  4938.1  335.83  4963.9  338.43  5024.8   339.1  5046.1  335.72
  5048.9  335.22  5052.1  335.72  5075.6  339.45  5116.4  335.92  5126.7  338.72
  5148.2  338.33  5185.6  339.43    5270  340.27  5342.4  337.55  5394.1  342.35
  5407.1  341.13  5482.7  345.37  5523.2  343.49  5587.7  347.86  5684.9  347.29
  5723.8   351.8  5776.5  355.57  5850.9  356.79  6043.5  361.01  6179.2  362.44
#Mann= 14 ,-1 , 0
  4315.1     .05       0  4588.2     .08       0  4701.6     .05       0
  4799.2     .08       0  4813.2     .05       0    4918     .08       0
  5046.1     .07       0  5052.1     .08       0  5148.2     .05       0
  5185.6     .08       0  5587.7      .1       0  5723.8     .08       0
  5850.9     .16       0  6043.5     .05       0
Bank Sta=5024.8,5075.6
XS Rating Curve= 0 ,0
Exp/Cntr=0.3,0.1

Type RM Length L Ch R = 1 ,3900    ,84,84,84
BEGIN DESCRIPTION:
Mapping XS 5eae1c99
END DESCRIPTION:
XS GIS Cut Line= 6
       3811297.5     10473096.56      3811770.57     10473365.64
      3812041.83     10473413.38      3812143.83     10473428.57
      3812234.98     10473467.64      3813082.34     10473725.53
#Sta/Elev= 30
  4309.8  349.25  4493.5  347.92  4791.1  340.88  4836.7   334.2  4850.2  330.21
  4853.6  325.61  4938.2  327.18  4954.6  327.68  4974.9   327.2  5002.4     322
  5005.1   321.5  5008.4     322  5035.8  328.07  5096.8  328.53  5125.8  332.42
  5181.5  334.86  5192.5  335.15  5211.4   332.3  5238.9  334.33  5328.5  334.36
  5360.2  337.23  5535.2  342.97    5587  346.99  5633.5  348.73    5692  347.44
  5712.9  350.59  5751.2  352.13    5907  357.61  6064.4  362.34  6217.5  365.28
#Mann= 12 ,-1 , 0
  4309.8     .05       0  4493.5     .08       0  4836.7     .05       0
  4938.2     .08       0  5002.4     .07       0  5008.4     .08       0
  5181.5     .05       0  5192.5     .08       0    5587      .1       0
  5751.2     .08       0    5907     .16       0  6064.4     .05       0
Bank Sta=4954.6,5035.8
XS Rating Curve= 0 ,0
Exp/Cntr=0.3,0.1

Type RM Length L Ch R = 1 ,3816    ,155,155,155
BEGIN DESCRIPTION:
UNT164 IN BECR 7.0
END DESCRIPTION:
XS GIS Cut Line= 3
      3811272.83       10473254.      3812085.35     10473538.73
      3813084.99      10473781.7
#Sta/Elev= 30
  4344.7  347.68  4553.2  346.29    4616  343.25  4683.3  336.66  4754.5  337.26
  4807.5  333.48  4827.8   334.4  4866.3  329.09  4935.7  325.57  4951.8  326.35
  4995.2  323.37    4998  322.87  5001.2  323.37  5051.2  329.16  5125.4  329.42
    5271  334.84  5302.7  341.47  5323.2  340.25  5533.2  345.66  5567.8  347.32
  5662.9  348.13  5698.8   346.5  5714.3  349.59  5769.3  352.68  5964.6  359.09
  5991.1  360.22  5996.2  358.24  6026.2  361.08  6115.7  364.91  6234.4   366.7
#Mann= 10 ,-1 , 0
  4344.7     .08       0  4866.3      .1       0  4935.7     .08       0
  4995.2     .07       0  5001.2     .08       0  5533.2      .1       0
  5567.8     .15       0  5769.3     .08       0  5964.6     .16       0
  6026.2     .08       0
Bank Sta=4951.8,5051.2
XS Rating Curve= 0 ,0
Exp/Cntr=0.3,0.1

Type RM Length L Ch R = 1 ,3661    ,694,694,694
BEGIN DESCRIPTION:
UNT164 IN BECR 6.0
END DESCRIPTION:
XS GIS Cut Line= 2
      3811248.54     10473438.03      3812990.54     10473965.49
#Sta/Elev= 30
  4368.9  346.15  4391.1  346.28  4477.6  347.22  4630.6  340.08  4673.9  340.45
  4714.8  336.55  4756.6  335.66  4777.9  331.93  4847.7  329.26  4923.8   327.3
  4947.8  329.31  4975.5  327.24  4993.9  321.69  4996.7  321.19  4999.9  321.69
  5013.3  326.34  5084.7  329.76  5148.3  330.56  5226.9  331.09  5287.5  334.45
  5331.3  340.53  5399.8  342.76  5501.9  345.33  5571.8  348.04  5632.4  346.19
  5706.1  350.66  5822.3  357.07  6060.3  362.79  6114.5     364    6189  367.31
#Mann= 13 ,-1 , 0
  4368.9     .08       0  4391.1     .05       0  4477.6     .08       0
  4847.7     .16       0  4993.9     .07       0  4999.9     .16       0
  5013.3     .05       0  5148.3     .16       0  5399.8     .05       0
  5501.9      .1       0  5706.1     .05       0  6060.3     .16       0
  6114.5     .08       0
Bank Sta=4947.8,5084.7
XS Rating Curve= 0 ,0
Exp/Cntr=0.3,0.1

Type RM Length L Ch R = 1 ,2967    ,647,647,647
BEGIN DESCRIPTION:
UNT164 IN BECR 5.0
END DESCRIPTION:
XS GIS Cut Line= 2
      3811241.62     10473445.02      3811845.18      10474700.7
#Sta/Elev= 30
  4449.7  346.94  4458.8  345.84  4481.9  347.28  4484.6  347.42  4549.3  347.52
  4639.9  340.85  4685.2   339.3  4730.4  336.23  4743.9  331.81  4753.1  331.85
  4758.6   329.8  4775.7  330.89    4900  326.12  4939.7  327.04    4985  322.62
  4990.5  316.65  4996.1  315.28  4998.8  314.78  5002.1  315.28  5007.6  321.73
  5035.8  322.75  5110.1  323.21  5307.4  337.82  5494.1  343.66  5516.7  342.57
  5531.7  345.67  5576.1  347.87  5635.5  347.44    5726  352.58  5842.9  355.83
#Mann= 5 ,-1 , 0
  4449.7     .08       0  4481.9     .05       0  4484.6     .16       0
  4996.1     .07       0  5002.1     .16       0
Bank Sta=4939.7,5035.8
XS Rating Curve= 0 ,0
Exp/Cntr=0.3,0.1

Type RM Length L Ch R = 1 ,2320    ,568,568,568
BEGIN DESCRIPTION:
UNT164 IN BECR 4.0
END DESCRIPTION:
XS GIS Cut Line= 2
      3810963.83     10473653.35      3811199.94     10474632.48
#Sta/Elev= 30
  4528.2  342.61  4619.8  342.41  4648.4  340.81    4738  339.47  4854.1  334.83
  4871.2  332.56  4918.2  329.74  4946.7  326.31  4960.1  326.44  4977.6  323.65
  4987.9  315.63    4999  312.53  5001.8  312.03    5005  312.53  5008.4  318.84
  5059.9   318.8  5085.8  320.57    5091  322.64  5121.6  321.47  5169.6  322.96
  5183.3  324.65  5203.9  324.28  5258.6  327.09    5317  331.45  5347.9  332.12
  5378.7  335.45  5431.3  336.52  5440.5  337.64    5510  340.47  5535.4  340.63
#Mann= 4 ,-1 , 0
  4528.2     .05       0    4738     .16       0    4999     .07       0
    5005     .16       0
Bank Sta=4960.1,5008.4
XS Rating Curve= 0 ,0
Exp/Cntr=0.3,0.1

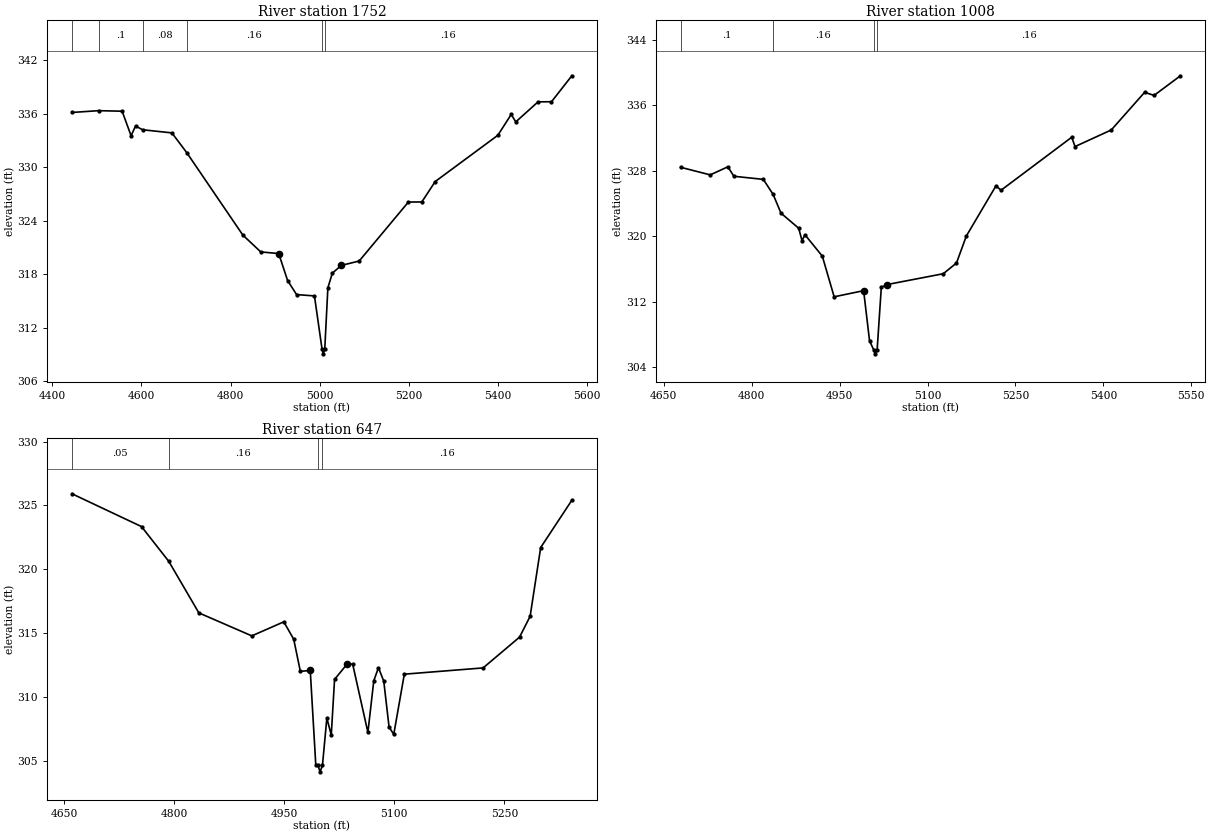
Type RM Length L Ch R = 1 ,1752    ,744,744,744
BEGIN DESCRIPTION:
UNT164 IN BECR 3.0
END DESCRIPTION:
XS GIS Cut Line= 2
      3810706.88     10473688.04      3810797.12      10474805.6
#Sta/Elev= 30
  4444.1  336.13  4503.9  336.33  4556.6  336.27  4576.7  333.52  4586.7  334.61
  4602.7  334.19  4668.2  333.84  4701.5  331.63  4827.5  322.38  4867.6   320.5
  4907.8  320.32  4927.8  317.29  4947.9  315.72    4988  315.57  5005.1  309.58
  5007.8  309.08  5011.1  309.58  5018.1  316.48  5028.1  318.12  5048.2  318.99
  5088.3  319.48  5198.7  326.09  5228.8   326.1  5258.9  328.39  5399.3  333.57
  5429.4  335.91  5439.5  335.07  5489.6  337.32  5519.7  337.33  5565.3  340.24
#Mann= 6 ,-1 , 0
  4444.1     .05       0  4503.9      .1       0  4602.7     .08       0
  4701.5     .16       0  5005.1     .07       0  5011.1     .16       0
Bank Sta=4907.8,5048.2
XS Rating Curve= 0 ,0
Exp/Cntr=0.3,0.1

Type RM Length L Ch R = 1 ,1008    ,361,361,361
BEGIN DESCRIPTION:
UNT164 IN BECR 2.0
END DESCRIPTION:
XS GIS Cut Line= 3
       3810429.1     10474069.96      3810380.49      10474479.7
       3810574.7     10474875.06
#Sta/Elev= 30
  4678.5  328.43  4729.1   327.5  4759.3  328.49  4769.4  327.33  4819.7  326.95
  4836.5  325.11  4849.9  322.82  4880.1  320.98  4885.8  319.46  4890.8  320.18
  4920.4  317.57  4940.6   312.6  4990.9  313.35    5001  307.24    5008  306.13
  5010.8  305.63    5014  306.13  5021.1  313.76  5031.2   314.1  5126.9  315.42
  5149.4  316.73  5166.3  320.04  5216.8  326.16  5225.4  325.62  5346.1   332.1
  5351.7  330.96  5413.6  332.99  5470.5  337.59  5486.6  337.21  5531.6  339.61
#Mann= 4 ,-1 , 0
  4678.5      .1       0  4836.5     .16       0    5008     .07       0
    5014     .16       0
Bank Sta=4990.9,5031.2
XS Rating Curve= 0 ,0
Exp/Cntr=0.3,0.1

Type RM Length L Ch R = 1 ,647     ,0,0,0
BEGIN DESCRIPTION:
UNT164 IN BECR 1.0
END DESCRIPTION:
XS GIS Cut Line= 3
      3810299.63     10474110.16      3810099.61     10474410.19
      3810299.58     10474660.15
#Sta/Elev= 30
    4661  325.91  4755.7  323.34  4792.8  320.62  4833.8  316.58  4905.9  314.78
  4949.5  315.88    4963  314.51    4972     312  4985.5  312.07    4993   304.7
  4996.1  304.63  4998.8  304.13  5002.1  304.63  5008.1  308.34  5014.1  307.01
  5018.6  311.37  5035.2  312.54  5043.2  312.58    5064  307.22    5072  311.26
  5078.4  312.29  5085.6  311.23  5092.8  307.65  5099.2  307.06  5113.6  311.78
  5220.9  312.27  5270.5  314.68  5284.9  316.31  5299.3   321.7  5341.7   325.4
#Mann= 4 ,-1 , 0
    4661     .05       0  4792.8     .16       0  4996.1     .07       0
  5002.1     .16       0
Bank Sta=4985.5,5035.2
XS Rating Curve= 0 ,0
Exp/Cntr=0.3,0.1

Chan Stop Cuts=-1
Use User Specified Reach Order=0
Composite Channel Slope=5