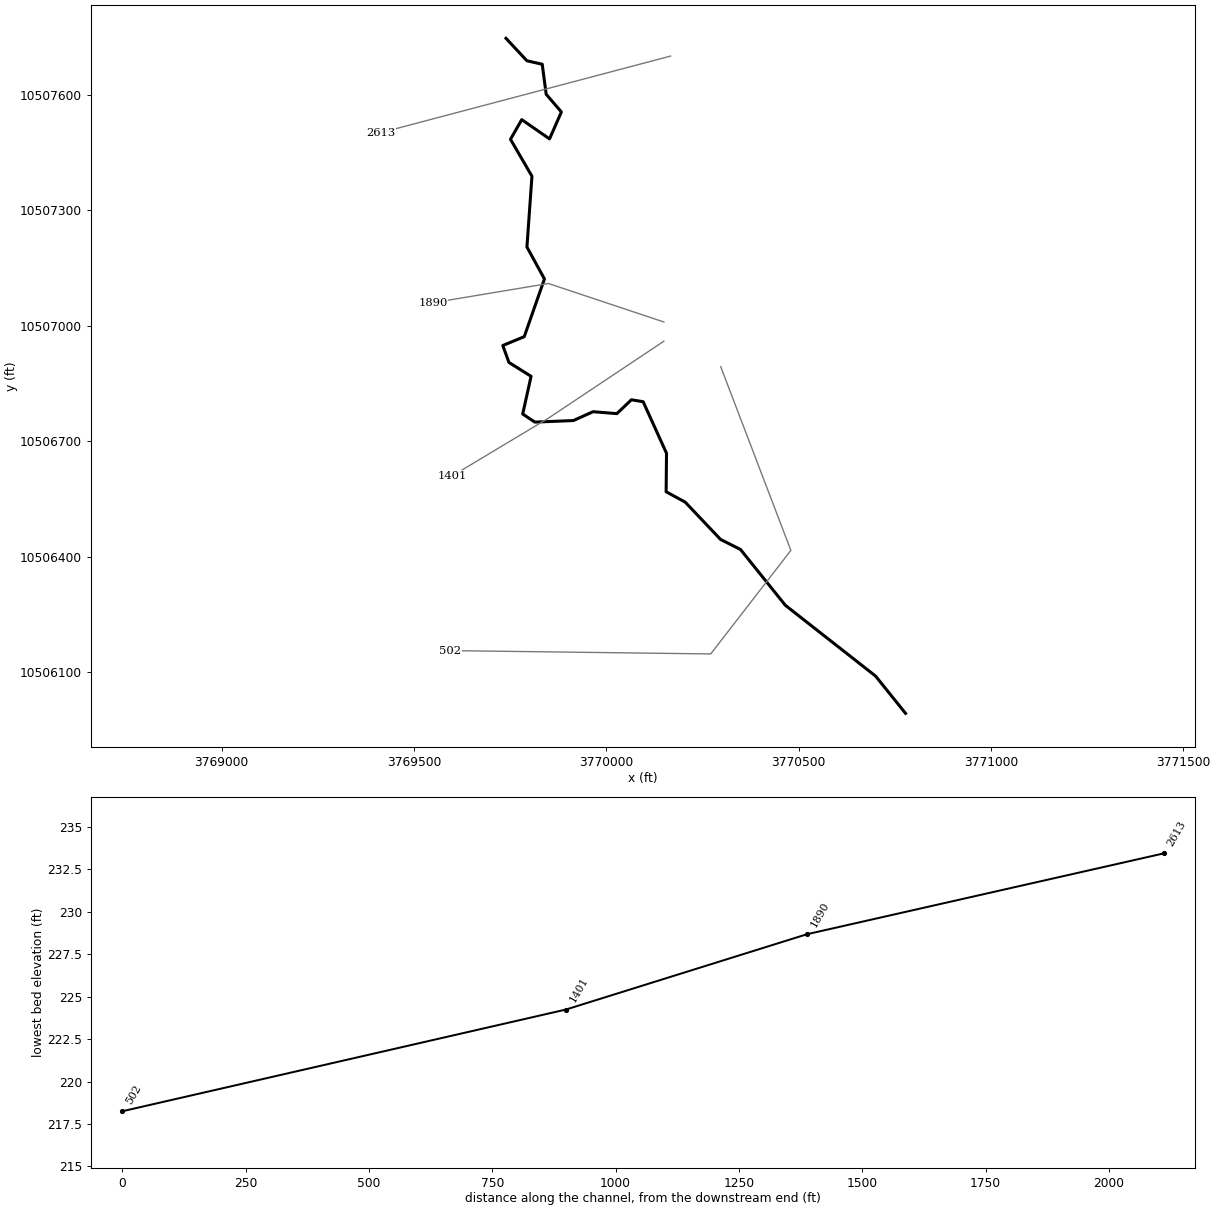
--- ZACH BRANCH.prj (project) ---

Proj Title=ZACH BRANCH Base Level Engineering
Current Plan=p01
Default Exp/Contr=0.3,0.1
English Units
Geom File=g01
Flow File=f01
Plan File=p01
BEGIN DESCRIPTION:
ZACH BRANCH
END DESCRIPTION:

--- ZACH BRANCH.p01 (plan) ---

Plan Title=Multiple Run
Short Identifier=Multiple
Geom File=g01
Flow File=f01
Subcritical Flow
K Sum by GR= 0
Std Step Tol= 0.01
Critical Tol= 0.01
Num of Std Step Trials= 20
Max Error Tol= 0.3
Flow Tol Ratio= 0.001
Split Flow NTrial= 30
Split Flow Tol= 0.02
Split Flow Ratio= 0.02
Log Output Level= 0
Friction Slope Method= 1
Unsteady Friction Slope Method= 2
Unsteady Bridges Friction Slope Method= 1
Parabolic Critical Depth
Global Vel Dist=  1 , 1 , 1
Global Log Level= 0
CheckData=True
Encroach Param= -1, 0, 0, 0
BEGIN DESCRIPTION:
Multiple Run
END DESCRIPTION:

--- ZACH BRANCH.f01 (steady flow) ---

Flow Title=Multiple
Number of Profiles=7
Profile Names=10-year,25-year,50-year,1pct_min,100-year,1pct_plu,500-year
River Rch & RM= ZACH BRANCH,Reach-1,2613
     618     845    1034     931    1259    1703    1874
Boundary for River Rch & Prof#=ZACH BRANCH,Reach-1,1
Up Type=0
Dn Type=3
Dn Slope=0.005
Boundary for River Rch & Prof#=ZACH BRANCH,Reach-1,2
Up Type=0
Dn Type=3
Dn Slope=0.005
Boundary for River Rch & Prof#=ZACH BRANCH,Reach-1,3
Up Type=0
Dn Type=3
Dn Slope=0.005
Boundary for River Rch & Prof#=ZACH BRANCH,Reach-1,4
Up Type=0
Dn Type=3
Dn Slope=0.005
Boundary for River Rch & Prof#=ZACH BRANCH,Reach-1,5
Up Type=0
Dn Type=3
Dn Slope=0.005
Boundary for River Rch & Prof#=ZACH BRANCH,Reach-1,6
Up Type=0
Dn Type=3
Dn Slope=0.005
Boundary for River Rch & Prof#=ZACH BRANCH,Reach-1,7
Up Type=0
Dn Type=3
Dn Slope=0.005

--- ZACH BRANCH.g01 (geometry) ---

Geom Title=Existing Conditions

River Reach=ZACH BRANCH,Reach-1
Reach XY= 30
      3769739.33     10507747.34      3769793.75     10507689.00
      3769833.50     10507680.00      3769843.75     10507602.00
      3769883.25     10507556.00      3769852.50     10507486.00
      3769780.25     10507536.00      3769751.00     10507485.00
      3769806.75     10507389.00      3769793.75     10507205.00
      3769839.25     10507122.00      3769786.75     10506972.00
      3769731.00     10506949.00      3769747.00     10506905.00
      3769804.50     10506869.00      3769782.75     10506771.00
      3769814.25     10506750.00      3769914.50     10506754.00
      3769965.50     10506777.00      3770027.50     10506772.00
      3770065.25     10506808.00      3770095.75     10506803.00
      3770156.50     10506669.00      3770155.50     10506569.00
      3770205.00     10506542.00      3770297.00     10506445.00
      3770348.75     10506419.00      3770465.25     10506274.00
      3770699.75     10506090.00      3770777.75     10505993.00

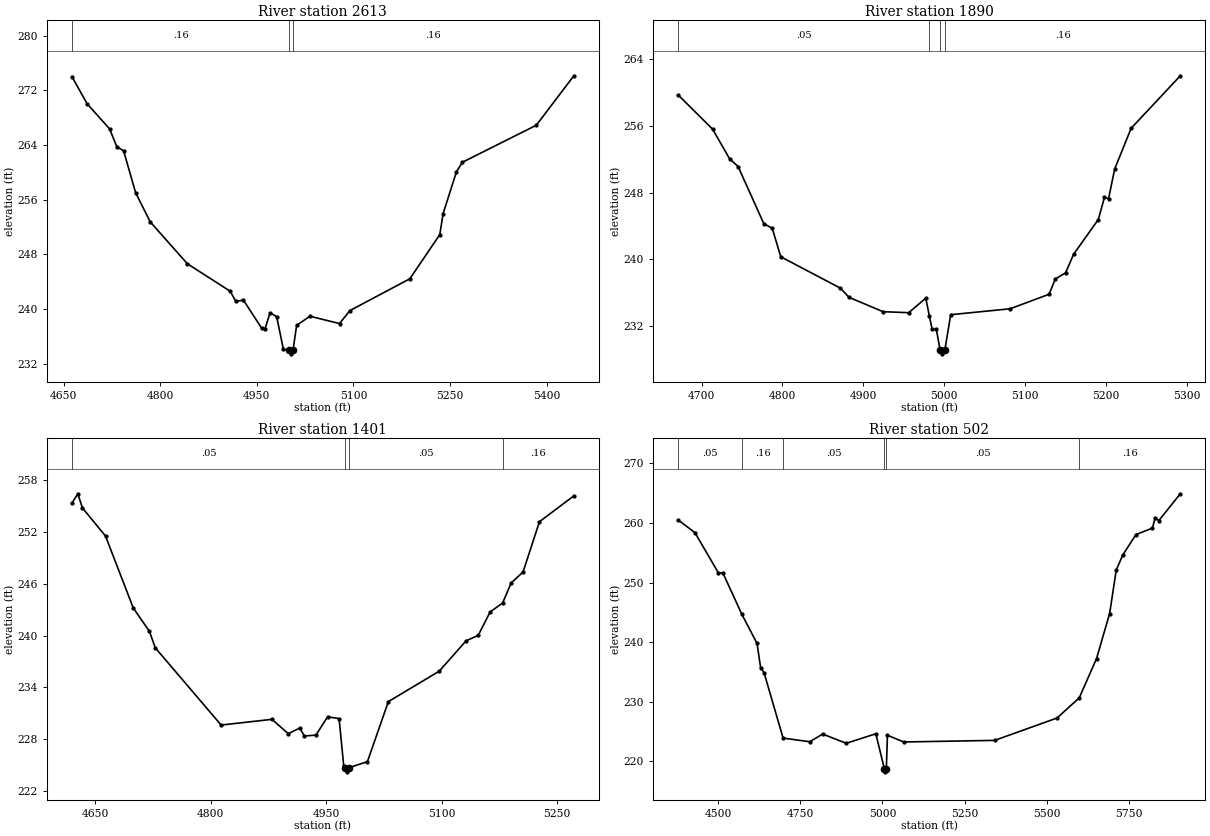
Type RM Length L Ch R = 1,2613,723,723,723
BEGIN DESCRIPTION:
ZACH BRANCH 4.0
END DESCRIPTION:
XS GIS Cut Line= 2
      3770167.16     10507701.26      3769413.26     10507501.96
#Sta/Elev= 30
  4662.7  273.99  4686.2  270.02  4721.3  266.33  4732.6  263.68  4742.9  263.16
  4761.6  257.01  4784.3  252.74  4842.1  246.61  4908.4  242.61  4917.4  241.10
  4929.1  241.30  4957.6  237.17  4962.8  237.12  4970.5  239.45  4980.8  238.87
  4991.2  234.10  5000.1  233.94  5002.8  233.44  5006.1  233.94  5011.8  237.61
  5032.5  238.94  5078.4  237.87  5094.6  239.77  5187.7  244.42  5234.2  250.88
  5239.4  253.96  5260.1  260.07  5269.3  261.46  5384.2  266.88  5442.5  274.11
#Mann=3,-1,0
  4662.7    0.16       0  5000.1    0.07       0  5006.1    0.16       0
Bank Sta=5000.1,5006.1
Exp/Cntr=0.3,0.1

Type RM Length L Ch R = 1,1890,489,489,489
BEGIN DESCRIPTION:
ZACH BRANCH 3.0
END DESCRIPTION:
XS GIS Cut Line= 3
      3770149.65     10507010.17      3769849.61     10507110.19
      3769549.62     10507060.19
#Sta/Elev= 30
  4671.4  259.67  4713.6  255.61  4734.7  252.05  4745.2  251.12  4776.9  244.29
  4787.4  243.72  4797.9  240.31  4871.7  236.55  4882.3  235.45  4924.4  233.73
  4956.1  233.61  4977.1  235.35  4981.6  233.23  4985.0  231.62  4990.2  231.62
  4994.8  229.18  4997.6  228.68  5000.8  229.18  5008.0  233.37  5081.4  234.08
  5129.6  235.82  5137.2  237.64  5149.9  238.38  5160.0  240.63  5190.4  244.77
  5198.0  247.42  5203.1  247.27  5210.7  250.84  5231.0  255.71  5291.8  262.00
#Mann=4,-1,0
  4671.4    0.05       0  4981.6    0.16       0  4994.8    0.07       0
  5000.8    0.16       0
Bank Sta=4994.8,5000.8
Exp/Cntr=0.3,0.1

Type RM Length L Ch R = 1,1401,899,899,899
BEGIN DESCRIPTION:
ZACH BRANCH 2.0
END DESCRIPTION:
XS GIS Cut Line= 3
      3770149.64     10506960.21      3769849.61     10506760.19
      3769599.65     10506610.21
#Sta/Elev= 30
  4619.6  255.31  4627.2  256.39  4633.2  254.76  4663.2  251.50  4699.3  243.18
  4720.3  240.48  4727.8  238.59  4813.4  229.65  4879.5  230.31  4900.6  228.65
  4915.6  229.30  4921.6  228.38  4936.6  228.49  4951.7  230.60  4966.7  230.40
  4972.7  224.93  4974.2  224.74  4976.9  224.24  4980.2  224.74  5003.5  225.42
  5030.7  232.36  5096.8  235.88  5131.8  239.40  5147.4  240.01  5162.9  242.73
  5179.1  243.75  5190.1  246.06  5205.7  247.35  5227.0  253.16  5271.7  256.15
#Mann=4,-1,0
  4619.6    0.05       0  4974.2    0.03       0  4980.2    0.05       0
  5179.1    0.16       0
Bank Sta=4974.2,4980.2
Exp/Cntr=0.3,0.1

Type RM Length L Ch R = 1,502,0,0,0
BEGIN DESCRIPTION:
ZACH BRANCH 1.0
END DESCRIPTION:
XS GIS Cut Line= 4
      3770297.37     10506894.00      3770479.67     10506416.54
      3770271.34     10506147.45      3769594.39     10506156.12
#Sta/Elev= 30
  4378.6  260.48  4428.9  258.39  4500.4  251.63  4513.8  251.65  4571.9  244.67
  4618.0  239.80  4628.9  235.75  4639.6  234.85  4697.4  223.91  4778.7  223.30
  4817.8  224.59  4889.7  223.04  4979.8  224.64  5005.8  218.75  5008.5  218.25
  5011.8  218.75  5015.1  224.39  5064.9  223.26  5341.7  223.53  5531.8  227.29
  5599.3  230.67  5651.8  237.25  5691.8  244.82  5711.8  252.10  5731.8  254.64
  5771.8  258.06  5821.8  259.15  5830.4  260.81  5841.8  260.42  5907.0  264.91
#Mann=6,-1,0
  4378.6    0.05       0  4571.9    0.16       0  4697.4    0.05       0
  5005.8    0.03       0  5011.8    0.05       0  5599.3    0.16       0
Bank Sta=5005.8,5011.8
Exp/Cntr=0.3,0.1

Chan Stop Cuts=-1