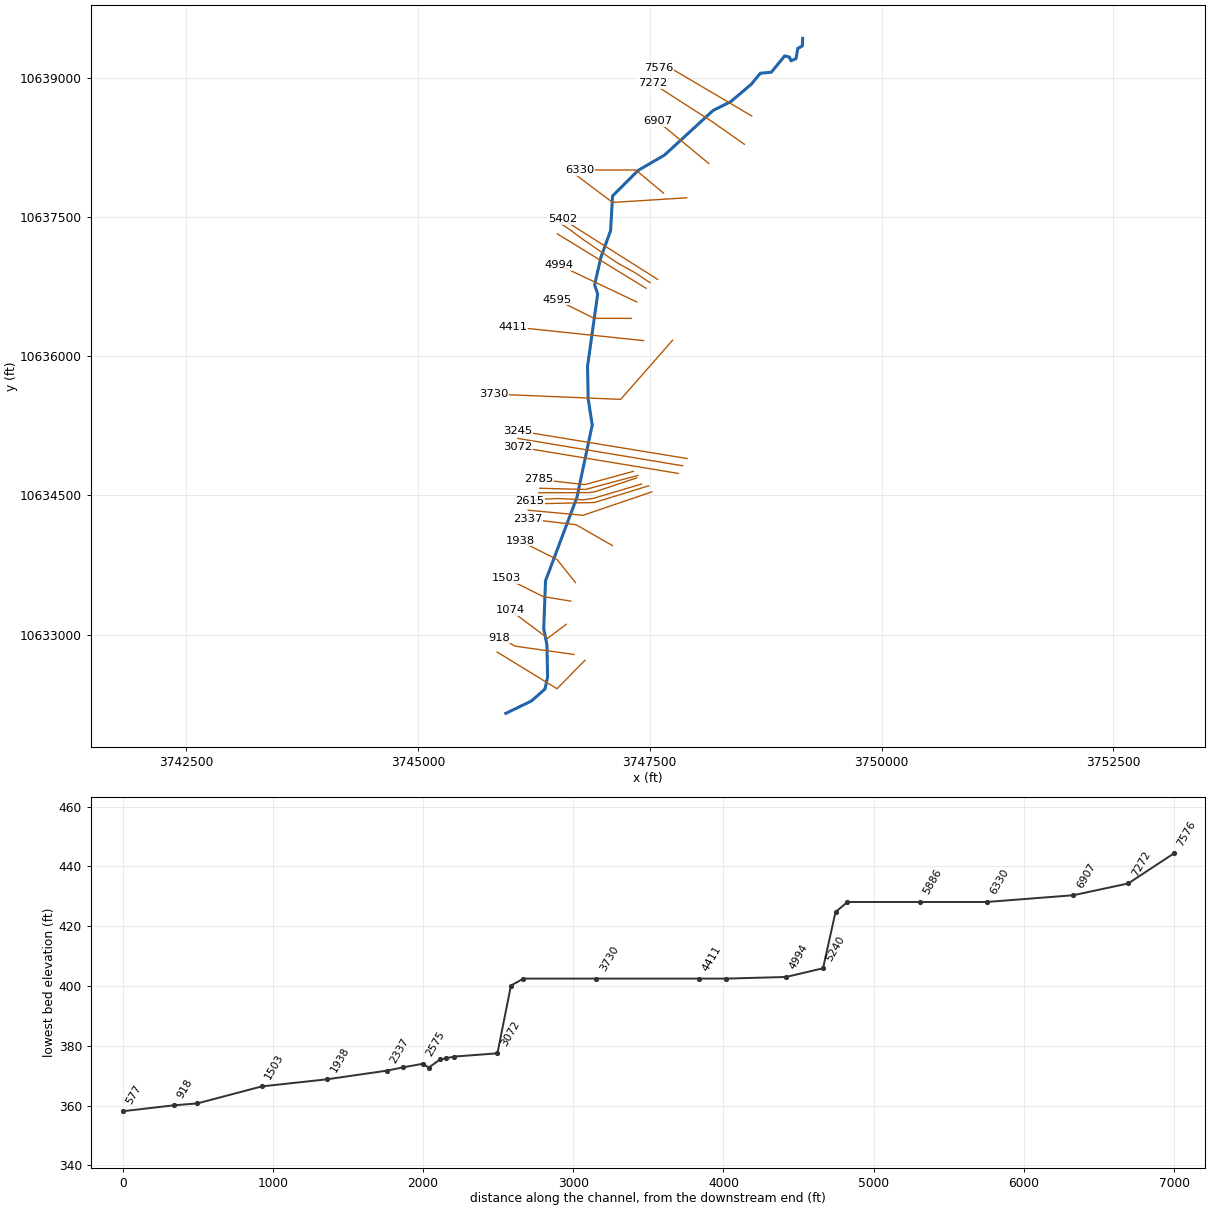
--- BASSET CREEK TRIBUTARY.prj (project) ---

Proj Title=BASSET CREEK TRIBUTARY Base Level Engineering
Current Plan=p01
Default Exp/Contr=0.3,0.1
English Units
Geom File=g01
Flow File=f01
Plan File=p01
Y Axis Title=Elevation
X Axis Title(PF)=Main Channel Distance
X Axis Title(XS)=Station
BEGIN DESCRIPTION:
BASSET CREEK TRIBUTARY
END DESCRIPTION:
DSS Export Rating Curves= 0
DSS Export Rating Curve Sorted= 0
DSS Export Volume Flow Curves= 0
DXF OffsetX= 0
DXF OffsetY= 0
DXF ScaleX= 1
DXF ScaleY= 10

--- BASSET CREEK TRIBUTARY.p01 (plan) ---

Plan Title=Multiple Run
Short Identifier=Multiple
Geom File=g01
Flow File=f01
Subcritical Flow
K Sum by GR= 0
Std Step Tol= 0.01
Critical Tol= 0.01
Num of Std Step Trials= 20
Max Error Tol= 0.3
Flow Tol Ratio= 0.001
Split Flow NTrial= 30
Split Flow Tol= 0.02
Split Flow Ratio= 0.02
Log Output Level= 0
Friction Slope Method= 1
Unsteady Friction Slope Method= 2
Unsteady Bridges Friction Slope Method= 1
Parabolic Critical Depth
Global Vel Dist=  1 , 1 , 1
Global Log Level= 0
CheckData=True
Encroach Param= -1, 0, 0, 0
BEGIN DESCRIPTION:
Multiple Run
END DESCRIPTION:

--- BASSET CREEK TRIBUTARY.f01 (steady flow) ---

Flow Title=Multiple
Program Version=4.10
Number of Profiles= 7
Profile Names=10-year,25-year,50-year,1pct_min,100-year,1pct_plu,500-year
River Rch & RM=BASSET CREEK TRI,Reach-1         ,7576
     461     619     750     670     906    1225    1324
River Rch & RM=BASSET CREEK TRI,Reach-1         ,6330
     973    1364    1700    1557    2105    2847    3240
River Rch & RM=BASSET CREEK TRI,Reach-1         ,5886
     973    1364    1700    1557    2105    2847    3240
Boundary for River Rch & Prof#=BASSET CREEK TRI,Reach-1         , 1
Up Type= 0
Dn Type= 3
Dn Slope=0.006
Boundary for River Rch & Prof#=BASSET CREEK TRI,Reach-1         , 2
Up Type= 0
Dn Type= 3
Dn Slope=0.006
Boundary for River Rch & Prof#=BASSET CREEK TRI,Reach-1         , 3
Up Type= 0
Dn Type= 3
Dn Slope=0.006
Boundary for River Rch & Prof#=BASSET CREEK TRI,Reach-1         , 4
Up Type= 0
Dn Type= 3
Dn Slope=0.006
Boundary for River Rch & Prof#=BASSET CREEK TRI,Reach-1         , 5
Up Type= 0
Dn Type= 3
Dn Slope=0.006
Boundary for River Rch & Prof#=BASSET CREEK TRI,Reach-1         , 6
Up Type= 0
Dn Type= 3
Dn Slope=0.006
Boundary for River Rch & Prof#=BASSET CREEK TRI,Reach-1         , 7
Up Type= 0
Dn Type= 3
Dn Slope=0.006
DSS Import GetInterval= 0
DSS Import GetPeak= 0
DSS Import FillOption= 0

--- BASSET CREEK TRIBUTARY.g01 (geometry) ---

Geom Title=Existing Conditions
Program Version=4.10

River Reach=BASSET CREEK TRI,Reach-1
Reach XY= 30
       3749149.5       10639430.      3749145.75       10639348.
        3749097.       10639321.      3749078.25       10639212.
      3749023.25       10639187.      3749006.75       10639228.
       3748955.5       10639241.       3748811.5       10639065.
        3748692.       10639053.      3748596.75       10638936.
       3748372.5       10638746.       3748184.5       10638653.
       3747659.5       10638171.       3747375.5       10638006.
       3747099.5       10637730.      3747077.75       10637355.
       3746973.5       10637068.      3746905.25       10636770.
        3746939.       10636675.      3746829.25       10635892.
      3746836.25       10635541.        3746880.       10635260.
      3746714.75       10634479.      3746376.25       10633580.
      3746356.75       10633065.       3746391.5       10632888.
       3746398.5       10632541.      3746370.75       10632413.
      3746224.75       10632284.        3745948.       10632150.

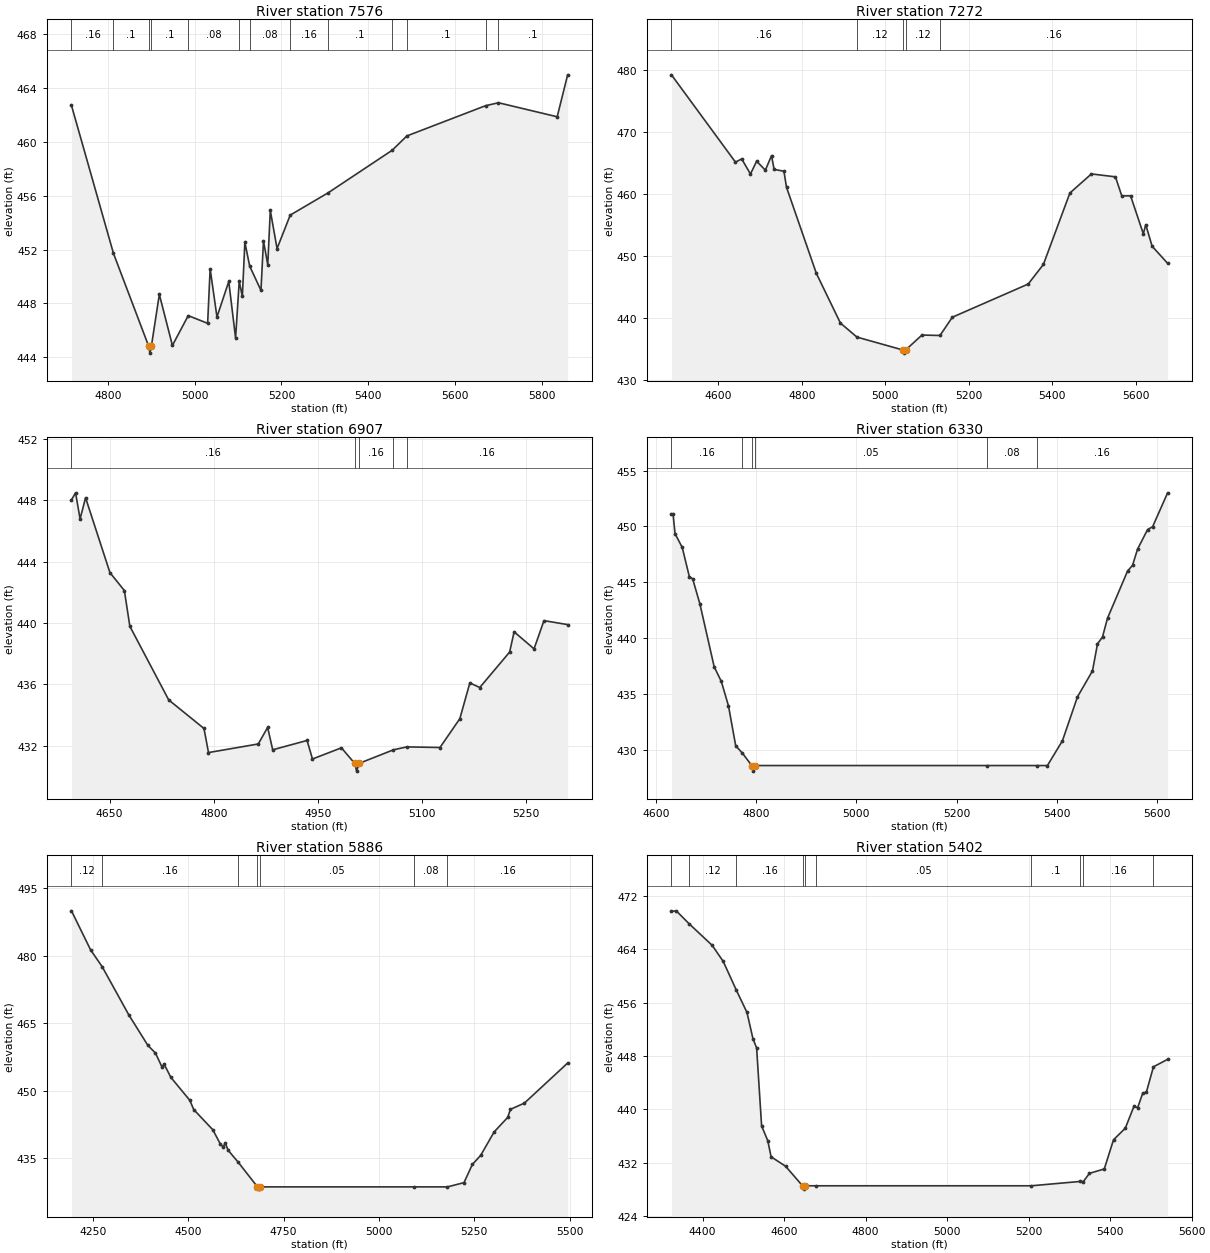
Type RM Length L Ch R = 1 ,7576    ,304,304,304
BEGIN DESCRIPTION:
Mapping XS 31de71d7
END DESCRIPTION:
XS GIS Cut Line= 3
      3748599.92     10638592.79       3747737.6     10639101.59
      3747595.49      10639108.2
#Sta/Elev= 30
  4716.1  462.68  4812.8  451.72  4894.2  444.82  4896.9  444.32  4900.2  444.82
  4918.6  448.67  4948.7  444.89  4985.2   447.1  5029.9  446.53  5035.7  450.57
  5051.4     447  5078.6  449.63  5094.3  445.44  5102.7  449.64  5109.9  448.52
  5115.7  452.54  5126.8  450.77  5152.8  448.97  5158.6  452.64  5168.5  450.87
  5174.3   454.9  5189.9  452.07  5220.2  454.55  5307.9  456.21  5455.3  459.36
  5489.1  460.42  5670.3  462.66  5700.2  462.88  5835.5  461.84  5859.6  464.95
#Mann= 13 ,-1 , 0
  4716.1     .16       0  4812.8      .1       0  4894.2     .07       0
  4900.2      .1       0  4985.2     .08       0  5102.7     .16       0
  5126.8     .08       0  5220.2     .16       0  5307.9      .1       0
  5455.3     .16       0  5489.1      .1       0  5670.3     .08       0
  5700.2      .1       0
Bank Sta=4894.2,4900.2
XS Rating Curve= 0 ,0
Exp/Cntr=0.3,0.1

Type RM Length L Ch R = 1 ,7272    ,365,365,365
BEGIN DESCRIPTION:
Mapping XS d3b1beea
END DESCRIPTION:
XS GIS Cut Line= 3
      3748520.74     10638287.56      3748171.78     10638532.35
      3747531.19     10638943.79
#Sta/Elev= 30
  4488.1  479.24  4641.4  465.13  4656.2  465.66  4677.2  463.22    4692  465.28
  4712.9  463.84  4727.7  466.19  4733.8  463.96  4757.3  463.67  4763.5  461.07
  4834.9  447.17  4892.6  439.13  4932.1  436.87  5042.4  434.78  5045.2  434.28
  5048.4  434.78  5087.7   437.2  5130.9  437.13  5160.4  440.08    5342  445.44
  5378.4  448.61  5441.8  460.15  5493.3  463.23  5550.8  462.76    5566  459.68
  5587.1  459.69  5617.5  453.56  5623.4  455.02  5638.6  451.55  5675.7  448.79
#Mann= 5 ,-1 , 0
  4488.1     .16       0  4932.1     .12       0  5042.4     .07       0
  5048.4     .12       0  5130.9     .16       0
Bank Sta=5042.4,5048.4
XS Rating Curve= 0 ,0
Exp/Cntr=0.3,0.1

Type RM Length L Ch R = 1 ,6907    ,577,577,577
BEGIN DESCRIPTION:
BASSET CREEK TRIBUTARY 19.0
END DESCRIPTION:
XS GIS Cut Line= 2
      3748137.37     10638079.92      3747586.47     10638535.39
#Sta/Elev= 30
  4595.1  448.02    4601  448.48  4607.5  446.78  4615.4  448.16  4650.5  443.28
  4671.3  442.11  4679.2  439.78  4735.2  434.98    4786  433.12  4792.5  431.55
  4864.2  432.11  4877.7  433.19    4885  431.73  4934.5  432.34  4942.3  431.13
    4984  431.86  5003.2  430.84  5005.9  430.34  5009.2  430.84    5059  431.73
  5078.3  431.92    5126  431.88  5154.6  433.76    5169  436.09  5183.3  435.79
  5226.3   438.1  5232.8  439.42  5261.5  438.31  5275.8  440.15  5309.9  439.89
#Mann= 5 ,-1 , 0
  4595.1     .16       0  5003.2     .07       0  5009.2     .16       0
    5059     .12       0  5078.3     .16       0
Bank Sta=5003.2,5009.2
XS Rating Curve= 0 ,0
Exp/Cntr=0.3,0.1

Type RM Length L Ch R = 1 ,6330    ,444,444,444
BEGIN DESCRIPTION:
BASSET CREEK TRIBUTARY 14.0
END DESCRIPTION:
XS GIS Cut Line= 3
      3747649.64     10637760.16      3747349.61     10638010.19
      3746749.57     10638010.19
#Sta/Elev= 30
  4630.8  451.08  4634.1  451.08    4638  449.35  4652.3  448.12  4666.6  445.49
  4673.1  445.31  4687.5  443.08  4716.1  437.43  4730.4  436.11  4744.7  433.92
  4759.1  430.35  4772.5  429.69  4791.2  428.58    4794  428.08  4797.2  428.58
  5261.2  428.58  5360.1  428.58  5381.4  428.58  5411.4   430.8  5441.4  434.73
  5471.4  437.06  5481.4  439.48  5491.4   440.1  5501.4  441.78  5541.4     446
  5551.4  446.52  5561.4  447.97  5581.4  449.72  5591.4  449.97  5621.4  453.01
#Mann= 6 ,-1 , 0
  4630.8     .16       0  4772.5     .05       0  4791.2    .033       0
  4797.2     .05       0  5261.2     .08       0  5360.1     .16       0
Bank Sta=4791.2,4797.2
XS Rating Curve= 0 ,0
Exp/Cntr=0.3,0.1

Type RM Length L Ch R = 1 ,5886    ,484,484,484
BEGIN DESCRIPTION:
BASSET CREEK TRIBUTARY 13.0
END DESCRIPTION:
XS GIS Cut Line= 3
      3747899.57     10637710.19      3747099.61     10637660.19
      3746699.62     10637960.18
#Sta/Elev= 30
  4193.5  489.95  4243.6  481.28  4274.3  477.49  4343.8  466.83  4393.8  460.05
  4413.9  458.31  4431.4  455.14  4436.4  455.89    4454  452.95  4504.1   447.8
  4514.1  445.78  4564.2  441.28  4584.2  438.09  4591.7  437.42  4596.7  438.39
  4604.3  436.73  4630.9  434.06  4681.4  428.58  4684.2  428.08  4687.4  428.58
    5092  428.58  5179.8  428.58  5223.1  429.52    5245  433.56  5266.9  435.59
  5302.3  440.81  5337.7  444.02    5345  445.82  5381.5   447.2    5495  456.11
#Mann= 7 ,-1 , 0
  4193.5     .12       0  4274.3     .16       0  4630.9     .05       0
  4681.4    .033       0  4687.4     .05       0    5092     .08       0
  5179.8     .16       0
Bank Sta=4681.4,4687.4
XS Rating Curve= 0 ,0
Exp/Cntr=0.3,0.1

Type RM Length L Ch R = 1 ,5402    ,79,79,79
BEGIN DESCRIPTION:
BASSET CREEK TRIBUTARY 12.0
END DESCRIPTION:
XS GIS Cut Line= 2
       3747586.2     10636829.89      3746557.52     10637480.96
#Sta/Elev= 30
  4323.6  469.65  4335.4  469.74  4366.5  467.83  4423.6  464.57  4450.7  462.16
    4483  457.84  4508.9  454.53  4523.6  450.59  4532.6  449.21  4544.8  437.55
    4560  435.32  4568.1  432.92  4603.6  431.51  4645.2  428.58  4647.9  428.08
  4651.2  428.58  4678.1  428.58  5206.5  428.58  5326.5  429.23  5334.2  429.21
  5349.2  430.44  5385.6   431.1  5408.3  435.47  5437.3  437.21  5458.5   440.5
  5467.5  440.27  5479.7   442.4    5489  442.62  5506.2  446.39    5541  447.51
#Mann= 10 ,-1 , 0
  4323.6     .16       0  4366.5     .12       0    4483     .16       0
  4645.2    .033       0  4651.2     .16       0  4678.1     .05       0
  5206.5      .1       0  5326.5     .08       0  5334.2     .16       0
  5506.2     .05       0
Bank Sta=4645.2,4651.2
XS Rating Curve= 0 ,0
Exp/Cntr=0.3,0.1

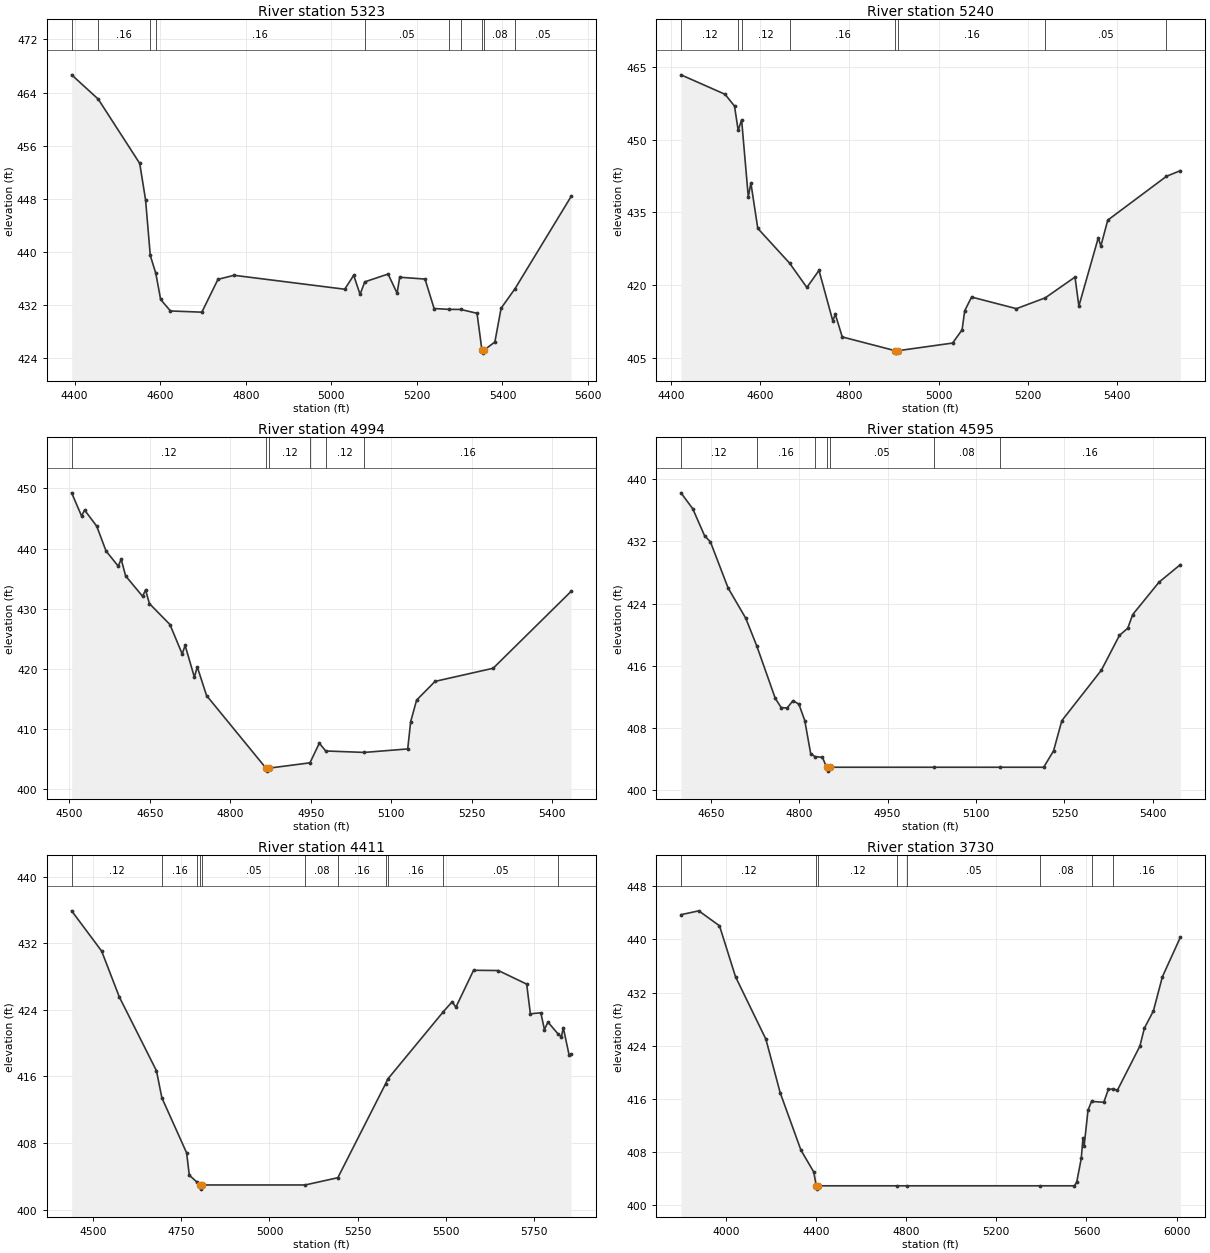
Type RM Length L Ch R = 1 ,5323    ,83,83,83
BEGIN DESCRIPTION:
Mapping XS 0d490f4d
END DESCRIPTION:
XS GIS Cut Line= 6
      3747503.75     10636795.16      3747342.14     10636901.93
      3747140.02     10637014.34      3746766.84     10637270.94
      3746640.24     10637365.67      3746530.67     10637438.06
#Sta/Elev= 30
  4393.1  466.67  4455.2  463.01  4552.2  453.31  4565.9   447.8  4576.9  439.42
  4589.8  436.73  4601.1  432.79    4624  431.05  4697.4  430.87  4735.1  435.82
  4772.8  436.43  5031.3  434.33  5052.3  436.43  5067.2  433.55  5078.1  435.44
  5132.7  436.62  5153.7  433.73  5159.8  436.14    5219  435.86  5240.2  431.42
  5275.2  431.29  5302.3  431.28  5340.5   430.7  5351.9  425.19  5354.7  424.69
  5357.9  425.19  5382.2  426.37  5396.8  431.46  5429.5  434.43  5560.4  448.32
#Mann= 10 ,-1 , 0
  4393.1     .12       0  4455.2     .16       0  4576.9     .12       0
  4589.8     .16       0  5078.1     .05       0  5275.2      .1       0
  5302.3     .08       0  5351.9     .07       0  5357.9     .08       0
  5429.5     .05       0
Bank Sta=5351.9,5357.9
XS Rating Curve= 0 ,0
Exp/Cntr=0.3,0.1

Type RM Length L Ch R = 1 ,5240    ,246,246,246
BEGIN DESCRIPTION:
Mapping XS 6145fcdb
END DESCRIPTION:
XS GIS Cut Line= 2
      3747460.33     10636734.41      3746505.47     10637320.34
#Sta/Elev= 30
  4422.2  463.44    4521  459.42  4542.3  456.98  4550.5  451.97  4558.2  454.14
  4573.2   438.2    4579   441.1  4594.5   431.7  4665.7  424.53  4704.6  419.49
  4731.8  423.02  4762.6  412.63  4768.5  413.92  4783.9  409.27  4902.8  406.42
  4905.6  405.92  4908.8  406.42  5031.4     408  5052.7  410.73  5058.6  414.68
    5074  417.51  5174.6  415.11  5239.2  417.34    5306  421.64  5314.7  415.65
  5358.2  429.75    5364  428.07  5379.5  433.41  5511.2  442.47  5542.5  443.64
#Mann= 8 ,-1 , 0
  4422.2     .12       0  4550.5     .16       0  4558.2     .12       0
  4665.7     .16       0  4902.8     .07       0  4908.8     .16       0
  5239.2     .05       0  5511.2     .16       0
Bank Sta=4902.8,4908.8
XS Rating Curve= 0 ,0
Exp/Cntr=0.3,0.1

Type RM Length L Ch R = 1 ,4994    ,399,399,399
BEGIN DESCRIPTION:
BASSET CREEK TRIBUTARY 11.0
END DESCRIPTION:
XS GIS Cut Line= 2
      3747360.51     10636586.84      3746519.49     10636985.67
#Sta/Elev= 30
  4504.3  449.27  4522.8  445.42  4528.4  446.41  4551.1  443.72  4568.3  439.62
  4591.1  437.08  4596.6  438.23  4604.9  435.46  4636.5  432.07  4642.1  433.13
  4649.2  430.86  4687.5  427.38  4710.3  422.49  4715.8  423.91    4733  418.64
  4738.5  420.32  4755.7  415.58  4866.4  403.51  4869.2  403.01  4872.4  403.51
  4948.4  404.39  4965.9  407.66  4977.7  406.36  5049.9  406.12  5130.6   406.7
  5136.1  411.23  5147.2  414.82  5181.6  417.93  5289.8  420.11  5435.1  432.89
#Mann= 6 ,-1 , 0
  4504.3     .12       0  4866.4     .07       0  4872.4     .12       0
  4948.4     .16       0  4977.7     .12       0  5049.9     .16       0
Bank Sta=4866.4,4872.4
XS Rating Curve= 0 ,0
Exp/Cntr=0.3,0.1

Type RM Length L Ch R = 1 ,4595    ,184,184,184
BEGIN DESCRIPTION:
BASSET CREEK TRIBUTARY 10.0
END DESCRIPTION:
XS GIS Cut Line= 3
      3747299.63     10636410.19      3746899.61     10636410.19
      3746499.64     10636610.17
#Sta/Elev= 30
  4599.5  438.26  4619.5  436.21  4639.5  432.75  4649.5  431.94  4679.5  426.01
  4709.5  422.11  4727.9   418.6  4759.5  411.81  4769.5  410.64  4779.5  410.58
  4789.5  411.52  4799.5  411.08  4809.5  408.96  4819.5  404.72  4826.8  404.33
  4839.5  404.23  4846.5  402.96  4849.3  402.46  4852.5  402.96  5028.2  402.96
    5141  402.96  5214.7  402.96  5231.5  405.07  5245.5  408.95  5312.6  415.45
  5343.3  419.93  5357.3  420.84  5365.7   422.6  5410.4  426.77  5446.7  429.03
#Mann= 7 ,-1 , 0
  4599.5     .12       0  4727.9     .16       0  4826.8     .05       0
  4846.5    .033       0  4852.5     .05       0  5028.2     .08       0
    5141     .16       0
Bank Sta=4846.5,4852.5
XS Rating Curve= 0 ,0
Exp/Cntr=0.3,0.1

Type RM Length L Ch R = 1 ,4411    ,681,681,681
BEGIN DESCRIPTION:
BASSET CREEK TRIBUTARY 9.0
END DESCRIPTION:
XS GIS Cut Line= 2
      3747434.28     10636170.18      3746024.17      10636317.7
#Sta/Elev= 30
  4438.4  435.88  4523.5  431.05  4573.8  425.53  4679.1  416.68  4694.6  413.42
  4764.8  406.81  4772.4  404.13  4794.5  403.29  4802.1  402.96  4804.8  402.46
  4808.1  402.96  5101.2  402.96    5194  403.83  5329.7  415.12  5335.4  415.66
    5493  423.74  5518.9  424.98    5529  424.29  5579.3  428.74  5649.6  428.71
  5730.1  427.08  5740.6  423.51  5770.3  423.64  5780.4  421.62  5790.4  422.52
  5818.7  421.12  5828.8  420.74  5833.9  421.86  5850.7  418.53  5856.2  418.68
#Mann= 11 ,-1 , 0
  4438.4     .12       0  4694.6     .16       0  4794.5     .05       0
  4802.1    .033       0  4808.1     .05       0  5101.2     .08       0
    5194     .16       0  5329.7     .12       0  5335.4     .16       0
    5493     .05       0  5818.7     .16       0
Bank Sta=4802.1,4808.1
XS Rating Curve= 0 ,0
Exp/Cntr=0.3,0.1

Type RM Length L Ch R = 1 ,3730    ,485,485,485
BEGIN DESCRIPTION:
BASSET CREEK TRIBUTARY 8.0
END DESCRIPTION:
XS GIS Cut Line= 3
      3747746.74     10636174.48      3747186.88      10635536.5
      3745819.65     10635592.92
#Sta/Elev= 30
  3799.9  443.71  3878.9  444.29  3970.9  442.04  4042.1  434.38  4176.8     425
  4240.4  416.94  4332.5  408.32  4389.4  405.03  4400.6  402.96  4403.4  402.46
  4406.6  402.96  4759.5  402.96  4803.7  402.96  5395.7  402.96  5546.7  402.96
  5556.7  403.52  5576.8  407.07  5584.4  410.17  5589.4  408.88  5606.8  414.33
  5622.4  415.64  5676.9  415.52  5696.9  417.44  5719.9  417.53  5736.9   417.3
    5837  423.95    5857  426.65    5897  429.24  5937.1  434.39  6017.1  440.34
#Mann= 8 ,-1 , 0
  3799.9     .12       0  4400.6    .033       0  4406.6     .12       0
  4759.5     .12       0  4803.7     .05       0  5395.7     .08       0
  5622.4     .05       0  5719.9     .16       0
Bank Sta=4400.6,4406.6
XS Rating Curve= 0 ,0
Exp/Cntr=0.3,0.1

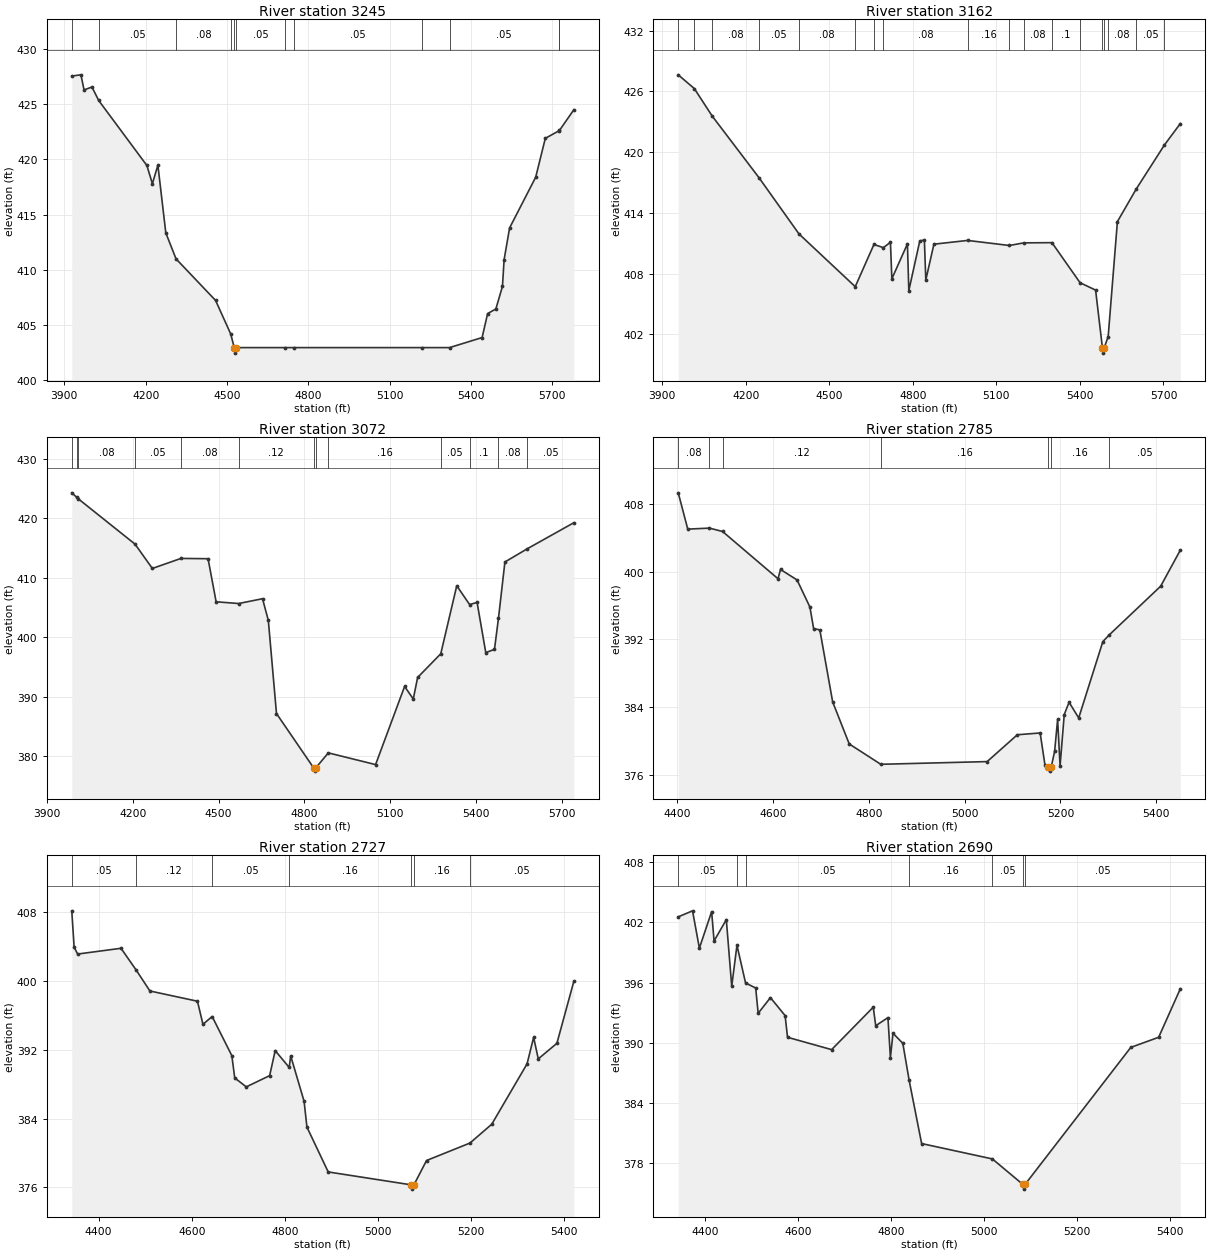
Type RM Length L Ch R = 1 ,3245    ,83,83,83
BEGIN DESCRIPTION:
BASSET CREEK TRIBUTARY 7.0
END DESCRIPTION:
XS GIS Cut Line= 2
      3747903.01     10634898.48      3746075.79     10635197.95
#Sta/Elev= 30
  3927.6  427.55  3961.4  427.66  3972.9  426.29    4002  426.56  4026.8  425.34
  4204.6  419.45  4224.9   417.8  4245.2  419.48  4274.4  413.35    4312     411
    4458  407.23  4513.7   404.2  4526.8  402.96  4529.5  402.46  4532.8  402.96
  4715.5  402.96  4745.9  402.96  5219.9  402.96  5320.8  402.96  5440.9  403.87
  5461.2  406.04  5491.6  406.46  5515.9   408.5    5522  410.92  5542.3   413.8
  5638.5  418.39    5674  421.91  5724.3  422.59    5726  422.62  5779.2   424.5
#Mann= 12 ,-1 , 0
  3927.6     .08       0  4026.8     .05       0    4312     .08       0
  4513.7     .05       0  4526.8    .033       0  4532.8     .05       0
  4715.5     .08       0  4745.9     .05       0  5219.9     .08       0
  5320.8     .05       0  5724.3     .16       0    5726     .05       0
Bank Sta=4526.8,4532.8
XS Rating Curve= 0 ,0
Exp/Cntr=0.3,0.1

Type RM Length L Ch R = 1 ,3162    ,90,90,90
BEGIN DESCRIPTION:
Mapping XS f8bf71c2
END DESCRIPTION:
XS GIS Cut Line= 2
      3747855.32     10634820.35      3746076.72     10635115.33
#Sta/Elev= 30
  3957.6  427.64  4015.4  426.28  4079.4  423.57  4247.9  417.46  4391.3  411.91
  4593.2   406.7  4660.3  410.87  4694.1  410.56  4719.6  411.08  4724.7  407.48
  4780.6  410.93  4785.6  406.31    4825  411.22  4841.5  411.31  4846.6  407.36
  4875.7   410.9  4996.8  411.27  5146.7  410.77  5198.7  411.03  5299.6  411.05
  5400.5  407.09  5456.3  406.36  5480.9  400.63  5483.6  400.13  5486.9  400.63
  5501.5  401.77  5534.6  413.13  5602.4  416.36  5703.3   420.7  5760.5  422.82
#Mann= 18 ,-1 , 0
  3957.6     .08       0  4015.4     .05       0  4079.4     .08       0
  4247.9     .05       0  4391.3     .08       0  4593.2     .12       0
  4660.3     .05       0  4694.1     .08       0  4996.8     .16       0
  5146.7     .05       0  5198.7     .08       0  5299.6      .1       0
  5400.5     .05       0  5480.9     .07       0  5486.9     .05       0
  5501.5     .08       0  5602.4     .05       0  5703.3     .16       0
Bank Sta=5480.9,5486.9
XS Rating Curve= 0 ,0
Exp/Cntr=0.3,0.1

Type RM Length L Ch R = 1 ,3072    ,287,287,287
BEGIN DESCRIPTION:
Mapping XS 659b3d53
END DESCRIPTION:
XS GIS Cut Line= 2
      3747807.57     10634737.88       3746075.8     10635024.34
#Sta/Elev= 30
  3986.6  424.32  4003.3  423.59  4008.1  423.36  4207.9  415.68  4268.3  411.59
  4368.3  413.28  4463.1  413.23  4491.3  405.98  4570.2  405.69  4653.5   406.5
  4673.8  402.84  4702.3  387.17  4832.9  377.98  4835.7  377.48  4838.9  377.98
  4883.5  380.55  5048.8  378.58  5150.2  391.73  5180.6  389.62  5195.7  393.24
  5276.6  397.23  5332.6  408.68  5377.5  405.51  5403.6  405.88    5434  397.43
  5464.4  397.97  5478.4  403.21  5500.9  412.68  5579.3  414.91  5741.9  419.29
#Mann= 13 ,-1 , 0
  3986.6     .08       0  4003.3     .05       0  4008.1     .08       0
  4207.9     .05       0  4368.3     .08       0  4570.2     .12       0
  4832.9     .07       0  4838.9     .12       0  4883.5     .16       0
  5276.6     .05       0  5377.5      .1       0  5478.4     .08       0
  5579.3     .05       0
Bank Sta=4832.9,4838.9
XS Rating Curve= 0 ,0
Exp/Cntr=0.3,0.1

Type RM Length L Ch R = 1 ,2785    ,58,58,58
BEGIN DESCRIPTION:
Mapping XS 957e7bf2
END DESCRIPTION:
XS GIS Cut Line= 3
      3747324.91     10634760.14      3746798.86     10634616.91
      3746298.83      10634674.2
#Sta/Elev= 30
  4401.9  409.37  4421.8  405.07    4467  405.19  4494.5  404.79  4610.3  399.19
  4615.5  400.29    4650  399.05  4676.9  395.84  4684.6  393.29  4697.6  393.13
  4724.4   384.6    4759  379.62  4824.9  377.21    5047  377.53  5110.1  380.71
  5157.7  380.92  5167.8  377.11  5174.8   376.9  5177.6   376.4  5180.8   376.9
  5187.9  378.73  5194.2  382.53  5199.3  377.01    5208   383.1  5218.1  384.56
  5238.2   382.7  5288.6  391.74  5301.6  392.52  5409.4  398.31  5450.4  402.58
#Mann= 7 ,-1 , 0
  4401.9     .08       0    4467     .05       0  4494.5     .12       0
  4824.9     .16       0  5174.8     .07       0  5180.8     .16       0
  5301.6     .05       0
Bank Sta=5174.8,5180.8
XS Rating Curve= 0 ,0
Exp/Cntr=0.3,0.1

Type RM Length L Ch R = 1 ,2727    ,37,37,37
BEGIN DESCRIPTION:
BASSET CREEK TRIBUTARY 6.0
END DESCRIPTION:
XS GIS Cut Line= 3
      3747371.82     10634715.88      3746806.67     10634564.82
      3746313.23     10634577.81
#Sta/Elev= 30
  4342.3  408.18  4347.4  403.94  4354.9  403.15  4448.1  403.82  4481.1  401.25
  4510.2  398.85  4612.3  397.66  4624.1  394.97  4643.9  395.88  4686.2  391.32
  4692.4  388.73  4717.2  387.69  4767.4     389  4779.3  391.91  4809.4  389.95
  4812.6   391.3  4841.4  386.01  4847.5  383.01  4893.2  377.79  5071.4  376.29
  5074.1  375.79  5077.4  376.29  5104.4  379.12  5197.6  381.15  5244.5  383.34
  5320.4  390.37  5334.5  393.45  5344.5  390.95  5384.5  392.76  5420.9  399.98
#Mann= 7 ,-1 , 0
  4342.3     .05       0  4481.1     .12       0  4643.9     .05       0
  4809.4     .16       0  5071.4     .07       0  5077.4     .16       0
  5197.6     .05       0
Bank Sta=5071.4,5077.4
XS Rating Curve= 0 ,0
Exp/Cntr=0.3,0.1

Type RM Length L Ch R = 1 ,2690    ,75,75,75
BEGIN DESCRIPTION:
Mapping XS d62d1a08
END DESCRIPTION:
XS GIS Cut Line= 5
      3747358.81     10634689.24      3746916.09     10634541.66
      3746844.91     10634531.25      3746596.64     10634529.51
      3746303.02     10634529.51
#Sta/Elev= 30
  4342.5  402.55  4373.3  403.15    4388  399.43  4414.4  403.07  4419.6  400.15
    4446  402.27  4457.6  395.63  4468.9  399.72  4487.4  395.96  4509.2  395.46
  4514.5  392.94  4540.9   394.5  4572.5  392.71  4577.7  390.55  4672.6  389.32
  4762.2  393.55  4767.5   391.7  4793.8  392.51  4799.1  388.53  4804.7  390.95
  4825.8  389.95  4839.4  386.27  4866.3  379.96  5018.5  378.43  5083.4  375.92
  5086.2  375.42  5089.4  375.92  5316.4  389.54  5376.4  390.55    5423  395.38
#Mann= 7 ,-1 , 0
  4342.5     .05       0  4468.9     .12       0  4487.4     .05       0
  4839.4     .16       0  5018.5     .05       0  5083.4     .07       0
  5089.4     .05       0
Bank Sta=5083.4,5089.4
XS Rating Curve= 0 ,0
Exp/Cntr=0.3,0.1

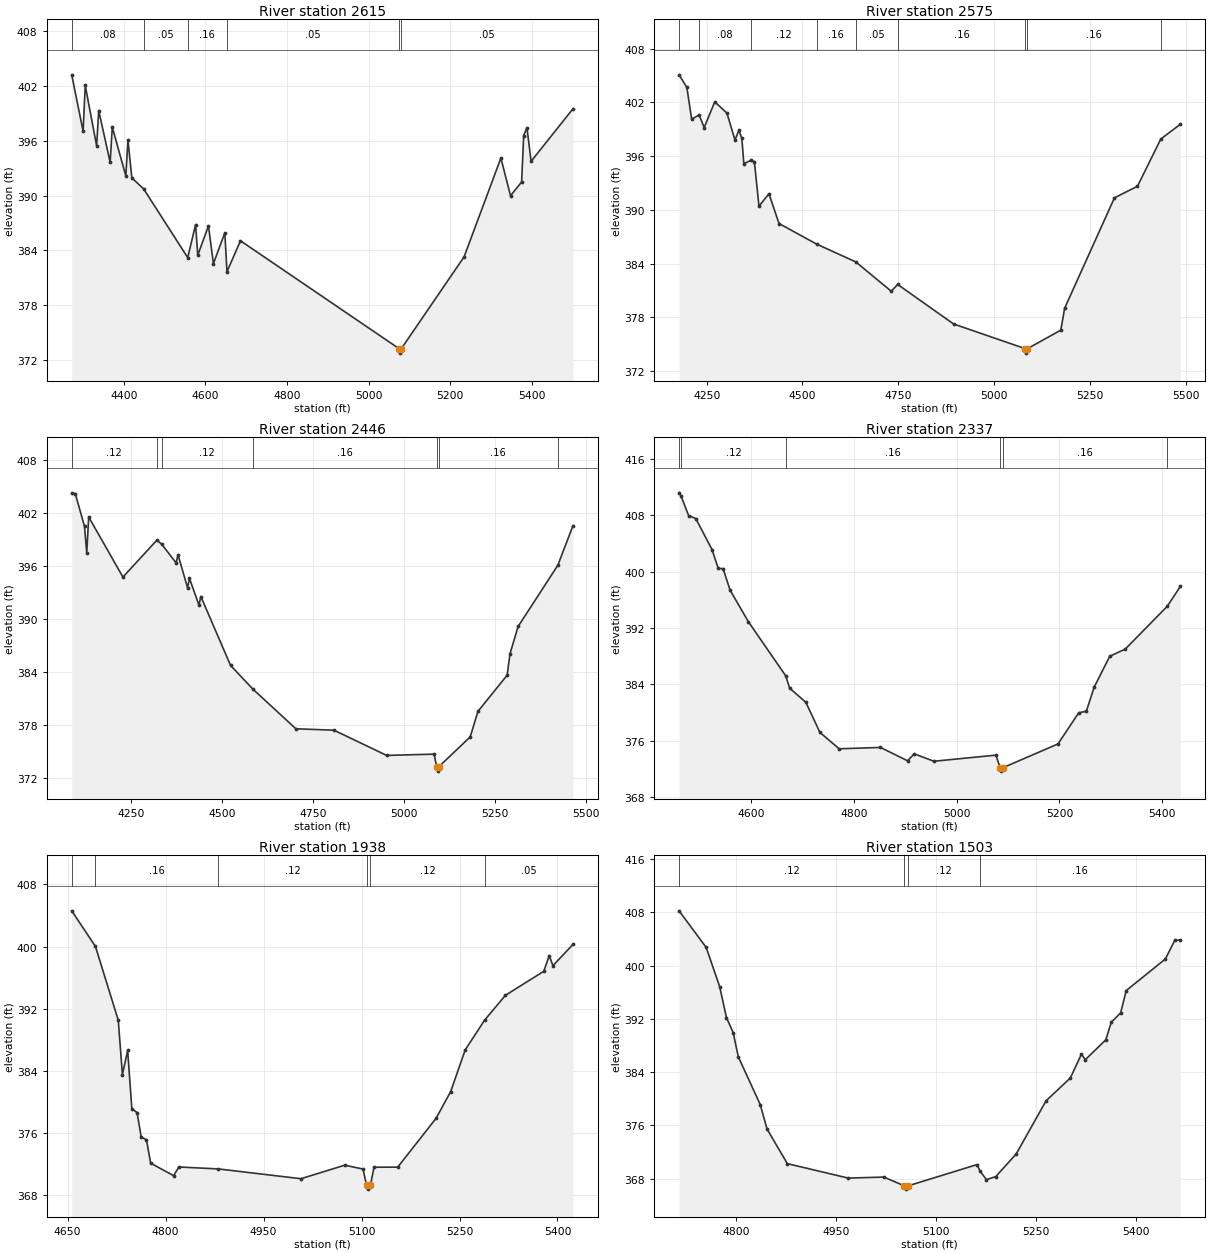
Type RM Length L Ch R = 1 ,2615    ,40,40,40
BEGIN DESCRIPTION:
Mapping XS 870994e5
END DESCRIPTION:
XS GIS Cut Line= 6
      3747410.88     10634623.26      3746891.78     10634468.75
      3746784.14     10634453.12      3746520.25     10634467.01
      3746381.37      10634461.8      3746207.74     10634439.23
#Sta/Elev= 30
  4272.5  403.24  4300.4  397.05  4305.6  402.07  4333.5  395.46  4338.7  399.32
  4366.7  393.64  4371.9  397.51  4405.1  392.15  4410.3  396.08  4419.9  391.94
  4448.9  390.72  4556.8   383.2  4576.2  386.82  4581.4  383.46  4607.7  386.67
  4619.8  382.54  4647.8  385.92    4653  381.65  4686.2  385.04  5074.6  373.22
  5077.4  372.72  5080.6  373.22  5234.3  383.28  5324.5  394.11  5348.1  389.98
  5375.3  391.49  5380.4  396.58  5388.4  397.44  5398.5  393.75  5501.2  399.52
#Mann= 6 ,-1 , 0
  4272.5     .08       0  4448.9     .05       0  4556.8     .16       0
    4653     .05       0  5074.6     .04       0  5080.6     .05       0
Bank Sta=5074.6,5080.6
XS Rating Curve= 0 ,0
Exp/Cntr=0.3,0.1

Type RM Length L Ch R = 1 ,2575    ,129,129,129
BEGIN DESCRIPTION:
Mapping XS e938b381
END DESCRIPTION:
XS GIS Cut Line= 3
      3747488.96     10634603.89      3746903.02      10634424.2
      3746207.67     10634408.57
#Sta/Elev= 30
    4178  405.08  4198.2  403.68  4210.8  400.12  4230.2   400.6  4243.5  399.19
  4271.1  402.06  4302.8  400.81  4323.8   397.8  4334.2  398.89  4341.8  397.98
    4347  395.16  4366.1  395.54  4374.5  395.38  4386.5   390.4  4412.5   391.8
  4438.8  388.47    4537  386.17  4639.2  384.18  4731.7  380.91  4748.6  381.66
  4894.3  377.25  5081.4  374.49  5084.1  373.99  5087.4  374.49  5174.4  376.56
  5184.4  379.01  5314.4  391.34  5374.4  392.63  5435.4  397.91  5486.4  399.56
#Mann= 9 ,-1 , 0
    4178     .12       0  4230.2     .08       0  4366.1     .12       0
    4537     .16       0  4639.2     .05       0  4748.6     .16       0
  5081.4     .07       0  5087.4     .16       0  5435.4     .05       0
Bank Sta=5081.4,5087.4
XS Rating Curve= 0 ,0
Exp/Cntr=0.3,0.1

Type RM Length L Ch R = 1 ,2446    ,109,109,109
BEGIN DESCRIPTION:
Mapping XS 8dd8ea67
END DESCRIPTION:
XS GIS Cut Line= 3
      3747522.85     10634538.79      3746780.63     10634286.18
      3746189.49     10634340.86
#Sta/Elev= 30
  4086.3  404.29  4096.2  404.19  4121.4  400.49  4127.6  397.47  4132.9  401.56
    4227  394.76  4320.4  398.94  4333.9  398.46  4373.2  396.37  4378.5  397.28
  4404.6  393.56  4409.9  394.61    4436  391.59  4441.2  392.56  4522.8  384.77
  4584.2  382.09  4702.4   377.6    4807  377.44  4951.7  374.59  5082.3  374.73
  5089.3  373.31    5092  372.81  5095.3  373.31  5181.5  376.68  5202.8  379.57
  5283.1  383.66    5291   386.1  5313.2  389.17  5422.3  396.09    5464  400.58
#Mann= 7 ,-1 , 0
  4086.3     .12       0  4320.4     .16       0  4333.9     .12       0
  4584.2     .16       0  5089.3     .07       0  5095.3     .16       0
  5422.3     .05       0
Bank Sta=5089.3,5095.3
XS Rating Curve= 0 ,0
Exp/Cntr=0.3,0.1

Type RM Length L Ch R = 1 ,2337    ,399,399,399
BEGIN DESCRIPTION:
BASSET CREEK TRIBUTARY 5.0
END DESCRIPTION:
XS GIS Cut Line= 3
      3747095.69     10633960.68      3746705.11     10634184.61
      3746183.14     10634246.94
#Sta/Elev= 30
  4459.6  411.19  4463.5  410.72  4478.1  407.96  4492.1  407.54  4523.7  403.13
  4535.8  400.47  4545.3  400.43  4558.8  397.39  4594.2  392.93  4667.1  385.23
  4674.8  383.48  4706.4  381.46  4733.8  377.19  4771.2  374.87  4851.7  375.06
  4904.3  373.17  4917.5  374.15  4955.6   373.1  5076.5  373.97  5084.5   372.2
  5087.2   371.7  5090.5   372.2  5197.3  375.56  5237.6  379.98  5252.4  380.19
  5267.8  383.63  5298.1     388  5328.3  389.02  5409.9  395.08  5435.5  397.91
#Mann= 6 ,-1 , 0
  4459.6     .16       0  4463.5     .12       0  4667.1     .16       0
  5084.5     .07       0  5090.5     .16       0  5409.9     .05       0
Bank Sta=5084.5,5090.5
XS Rating Curve= 0 ,0
Exp/Cntr=0.3,0.1

Type RM Length L Ch R = 1 ,1938    ,435,435,435
BEGIN DESCRIPTION:
BASSET CREEK TRIBUTARY 4.0
END DESCRIPTION:
XS GIS Cut Line= 3
      3746699.58     10633560.22      3746499.61     10633810.19
      3746099.63     10634010.18
#Sta/Elev= 30
  4656.4  404.61  4692.7  400.03  4727.6  390.55    4734  383.54    4742  386.64
  4748.4  379.15  4756.4  378.65  4762.8  375.48  4770.8  375.16  4777.2  372.14
  4812.4  370.53  4820.4  371.65  4880.7   371.4  5007.3  370.14  5074.3  371.88
  5102.3  371.38  5107.7   369.3  5110.4   368.8  5113.7   369.3  5119.1  371.62
  5155.4  371.63  5214.1  377.91  5236.5  381.36  5258.8  386.73  5288.5  390.55
  5320.3  393.74    5379  396.83  5387.4  398.85    5393  397.55  5423.7  400.29
#Mann= 6 ,-1 , 0
  4656.4     .12       0  4692.7     .16       0  4880.7     .12       0
  5107.7     .07       0  5113.7     .12       0  5288.5     .05       0
Bank Sta=5107.7,5113.7
XS Rating Curve= 0 ,0
Exp/Cntr=0.3,0.1

Type RM Length L Ch R = 1 ,1503    ,429,429,429
BEGIN DESCRIPTION:
BASSET CREEK TRIBUTARY 3.0
END DESCRIPTION:
XS GIS Cut Line= 3
      3746649.62     10633360.19      3746349.61     10633410.19
      3745949.57     10633610.21
#Sta/Elev= 30
  4714.8  408.24  4755.4  402.74  4775.6  396.85  4785.8   392.2  4795.9  389.94
  4803.5  386.31  4836.5  379.11  4846.6  375.46    4877  370.25  4968.3  368.08
  5021.7  368.23  5052.3  366.92    5055  366.42  5058.3  366.92  5161.5  370.11
  5165.7  369.17  5175.5  367.84  5189.4   368.3  5220.2  371.72  5264.9  379.69
  5301.3  383.12    5318  386.72  5323.6  385.86  5354.4  388.85  5362.7   391.5
  5376.7  392.91  5385.1  396.26  5443.8  401.01  5457.8  403.79  5466.2  403.87
#Mann= 4 ,-1 , 0
  4714.8     .12       0  5052.3     .07       0  5058.3     .12       0
  5165.7     .16       0
Bank Sta=5052.3,5058.3
XS Rating Curve= 0 ,0
Exp/Cntr=0.3,0.1

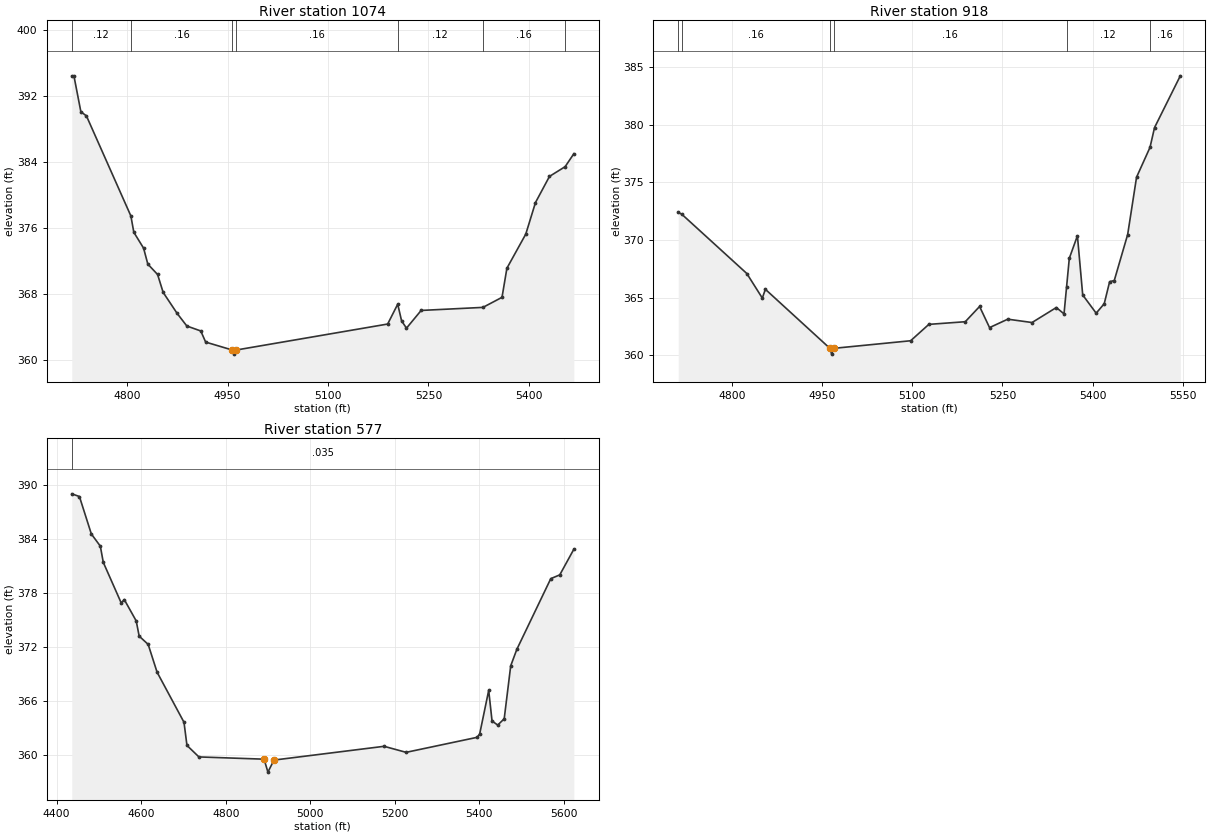
Type RM Length L Ch R = 1 ,1074    ,156,156,156
BEGIN DESCRIPTION:
BASSET CREEK TRIBUTARY 2.0
END DESCRIPTION:
XS GIS Cut Line= 3
      3746599.64     10633110.21      3746399.61     10632960.19
      3745999.64     10633260.17
#Sta/Elev= 30
  4717.3   394.5  4720.5   394.5  4730.9  390.14  4739.2  389.64  4805.6   377.5
    4810  375.52  4824.6  373.59  4830.9  371.66  4845.5   370.4  4853.8  368.23
  4874.6  365.69  4889.2  364.15    4910  363.55  4917.3   362.2    4957  361.24
  4959.8  360.74    4963  361.24  5189.2  364.39  5204.2   366.8    5210  364.77
  5217.3  363.89  5239.2  366.04  5331.5  366.41    5360  367.63  5367.3  371.16
  5395.5   375.3    5410  379.13  5430.9   382.3  5454.3  383.48  5467.3  385.05
#Mann= 7 ,-1 , 0
  4717.3     .12       0  4805.6     .16       0    4957     .07       0
    4963     .16       0  5204.2     .12       0  5331.5     .16       0
  5454.3     .12       0
Bank Sta=4957,4963
XS Rating Curve= 0 ,0
Exp/Cntr=0.3,0.1

Type RM Length L Ch R = 1 ,918     ,341,341,341
BEGIN DESCRIPTION:
Mapping XS 43f6e45d
END DESCRIPTION:
XS GIS Cut Line= 3
      3746682.55     10632785.63      3746052.33     10632874.17
      3745874.59     10632963.63
#Sta/Elev= 30
  4710.6  372.38  4716.3  372.24  4824.7  367.09  4850.5  364.96  4855.6  365.72
    4963   360.6  4965.8   360.1    4969   360.6  5097.3  361.26  5127.6  362.68
  5188.2  362.91    5212  364.23  5228.6   362.4  5258.9  363.13  5299.3  362.84
  5339.7  364.14  5352.5  363.59  5356.7  365.89  5361.3  368.41  5374.8  370.36
  5383.6  365.23    5406  363.65  5419.4  364.47  5428.4  366.38  5436.1  366.48
  5458.4  370.47  5473.2  375.44  5495.6  378.03  5503.1  379.74    5546  384.23
#Mann= 6 ,-1 , 0
  4710.6     .12       0  4716.3     .16       0    4963     .07       0
    4969     .16       0  5356.7     .12       0  5495.6     .16       0
Bank Sta=4963,4969
XS Rating Curve= 0 ,0
Exp/Cntr=0.3,0.1

Type RM Length L Ch R = 1 ,577     ,0,0,0
BEGIN DESCRIPTION:
BASSET CREEK TRIBUTARY 1.0
END DESCRIPTION:
XS GIS Cut Line= 3
       3746802.3      10632723.1      3746500.25     10632415.84
      3745854.54     10632811.59
#Sta/Elev= 30
  4435.7  389.06  4453.8  388.76    4482   384.6  4503.3  383.24  4510.3  381.44
  4552.8  376.92  4559.9  377.31  4588.2  374.93  4595.2  373.24  4616.5  372.32
  4637.6  369.23  4701.3  363.66  4708.3  361.09  4736.6  359.81  4890.8  359.56
  4899.9  358.12  4914.2  359.46  5174.8  360.99    5227  360.32  5395.1  361.99
  5401.1  362.37  5422.4  367.21  5430.3  363.81  5443.7  363.35  5459.1  364.05
  5474.5  369.94  5488.9  371.76  5569.3  379.63  5590.6  380.05  5623.9   382.9
#Mann= 1 ,-1 , 0
  4435.7    .035       0
Bank Sta=4890.8,4914.2
XS Rating Curve= 0 ,0
Exp/Cntr=0.3,0.1

Chan Stop Cuts=-1
Use User Specified Reach Order=0
Composite Channel Slope=5