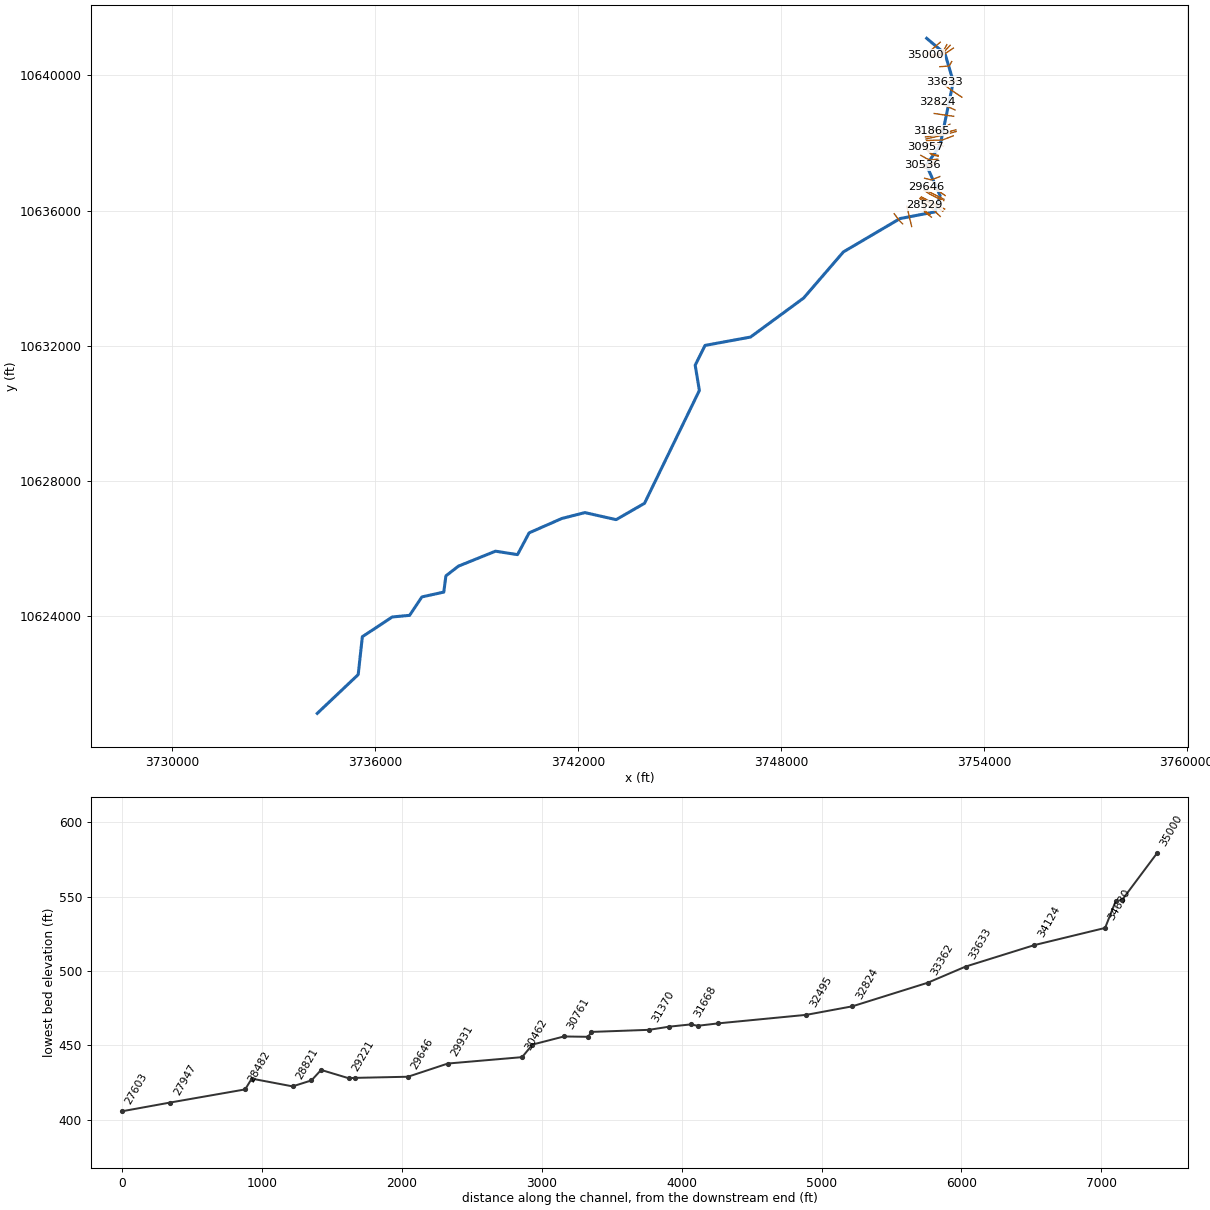
--- BASSET CREEK.prj (project) ---

Proj Title=BASSET CREEK Base Level Engineering
Current Plan=p01
Default Exp/Contr=0.3,0.1
English Units
Geom File=g01
Flow File=f01
Plan File=p01
Y Axis Title=Elevation
X Axis Title(PF)=Main Channel Distance
X Axis Title(XS)=Station
BEGIN DESCRIPTION:
BASSET CREEK
END DESCRIPTION:
DSS Export Rating Curves= 0
DSS Export Rating Curve Sorted= 0
DSS Export Volume Flow Curves= 0
DXF OffsetX= 0
DXF OffsetY= 0
DXF ScaleX= 1
DXF ScaleY= 10

--- BASSET CREEK.p01 (plan) ---

Plan Title=Multiple Run
Program Version=4.10
Short Identifier=Multiple
Geom File=g01
Flow File=f01
Subcritical Flow
K Sum by GR= 0
Std Step Tol= 0.01
Critical Tol= 0.01
Num of Std Step Trials= 20
Max Error Tol= 0.3
Flow Tol Ratio= 0.001
Split Flow NTrial= 30
Split Flow Tol= 0.02
Split Flow Ratio= 0.02
Log Output Level= 0
Friction Slope Method= 1
Unsteady Friction Slope Method= 2
Unsteady Bridges Friction Slope Method= 1
Parabolic Critical Depth
Global Vel Dist= 1 , 1 , 1
Global Log Level= 0
CheckData=True
Encroach Param=-1 ,0,0, 0
BEGIN DESCRIPTION:
Multiple Run
END DESCRIPTION:
Computation Interval=1HOUR
Output Interval=1HOUR
Run HTab= 0
Run UNet= 0
Run PostProcess= 0
Run WQNet= 0
UNET Theta= 1
UNET Theta Warmup= 1
UNET ZTol= 0.02
UNET ZSATol= 0.05
UNET MxIter= 20
UNET MaxInSteps= 0
UNET DtIC= 0
UNET DtMin= 0
UNET MaxCRTS= 20
UNET WFStab= 2
UNET SFStab= 1
UNET WFX= 1
UNET SFX= 1
UNET DSS MLevel= 4
UNET DZMax Abort= 100
UNET Convert EG Bridges= 0
UNET Use Existing IB Tables=-1
UNET Froude Reduction=False
UNET Froude Limit= 1
UNET Froude Power= 10
UNET Time Slicing=0,0, 5
UNET Junction Losses=0
Instantaneous Interval=1HOUR
Write IC File= 0
Write IC File at Sim End=0
Echo Input=False
Echo Parameters=False
Echo Output=False
Write Detailed= 0
WQ AD Non Conservative
WQ ULTIMATE=-1
WQ Max Comp Step=1HOUR
WQ Output Interval=15MIN
WQ Output Selected Increments= 0
WQ Output face flow=0
WQ Output face velocity=0
WQ Output face area=0
WQ Output face dispersion=0
WQ Output cell volume=0
WQ Output cell surface area=0
WQ Output cell continuity=0
WQ Output cumulative cell continuity=0
WQ Output face conc=0
WQ Output face dconc_dx=0
WQ Output face courant=0
WQ Output face peclet=0
WQ Output face adv mass=0
WQ Output face disp mass=0
WQ Output cell mass=0
WQ Output cell source sink temp=0
WQ Output cell source sink nsm=0
WQ Output MaxMinRange=-1
WQ Daily Max Min Mean=-1
WQ Daily Range=0
WQ Daily Time=0
WQ Create Restart=0
WQ Fixed Restart=0
WQ System Summary=0
WQ Use Fixed Temperature=0
Sorting and Armoring Iterations= 10
XS Update Threshold= 0.02
Hydraulics Update Threshold= 0.02
Energy Slope Method= 1
Volume Change Method= 0
XS Weighting Method= 0
Number of US Weighted Cross Sections= 1
Number of DS Weighted Cross Sections= 1
Upstream XS Weight=0.25
Main XS Weight=0.5
Downstream XS Weight=0.25
Number of DS XS's Weighted with US Boundary= 1
Upstream Boundary Weight= 1
Weight of XSs Associated with US Boundary= 0
Number of US XS's Weighted with DS Boundary= 1
Downstream Boundary Weight= 0.5
Weight of XSs Associated with DS Boundary= 0.5
Sediment Output Level= 4
Mass or Volume Output= 0
Output Increment Type= 1
Profile and TS Output Increment= 10
XS Output Flag= 0
XS Output Increment= 10
Disregard all LS=0
Disregard all Conn=0
Disregard all Breaches=0
Disregard all Pumps=0

--- BASSET CREEK.f01 (steady flow) ---

Flow Title=Multiple
Program Version=4.10
Number of Profiles= 7
Profile Names=10-year,25-year,50-year,1pct_min,100-year,1pct_plu,500-year
River Rch & RM=BASSET CREEK,Reach-1         ,35000
     284     370     438     384     519     702     729
River Rch & RM=BASSET CREEK,Reach-1         ,29931
     542     735     895     803    1086    1468    1602
River Rch & RM=BASSET CREEK,Reach-1         ,29270
     542     735     895     803    1086    1468    1602
River Rch & RM=BASSET CREEK,Reach-1         ,25852
     940    1312    1630    1488    2013    2722    3079
River Rch & RM=BASSET CREEK,Reach-1         ,25393
     940    1312    1630    1488    2013    2722    3079
River Rch & RM=BASSET CREEK,Reach-1         ,20657
    1574    2257    2854    2647    3580    4842    5658
River Rch & RM=BASSET CREEK,Reach-1         ,20143
    1574    2257    2854    2647    3580    4842    5658
River Rch & RM=BASSET CREEK,Reach-1         ,19775
    1812    2609    3307    3073    4156    5620    6591
River Rch & RM=BASSET CREEK,Reach-1         ,19287
    1812    2609    3307    3073    4156    5620    6591
River Rch & RM=BASSET CREEK,Reach-1         ,15149
    2017    2909    3692    3433    4642    6278    7372
River Rch & RM=BASSET CREEK,Reach-1         ,8832
    2137    3073    3892    3609    4881    6600    7708
Boundary for River Rch & Prof#=BASSET CREEK,Reach-1         , 1
Up Type= 0
Dn Type= 3
Dn Slope=0.004
Boundary for River Rch & Prof#=BASSET CREEK,Reach-1         , 2
Up Type= 0
Dn Type= 3
Dn Slope=0.004
Boundary for River Rch & Prof#=BASSET CREEK,Reach-1         , 3
Up Type= 0
Dn Type= 3
Dn Slope=0.004
Boundary for River Rch & Prof#=BASSET CREEK,Reach-1         , 4
Up Type= 0
Dn Type= 3
Dn Slope=0.004
Boundary for River Rch & Prof#=BASSET CREEK,Reach-1         , 5
Up Type= 0
Dn Type= 3
Dn Slope=0.004
Boundary for River Rch & Prof#=BASSET CREEK,Reach-1         , 6
Up Type= 0
Dn Type= 3
Dn Slope=0.004
Boundary for River Rch & Prof#=BASSET CREEK,Reach-1         , 7
Up Type= 0
Dn Type= 3
Dn Slope=0.004
DSS Import GetInterval= 0
DSS Import GetPeak= 0
DSS Import FillOption= 0

--- BASSET CREEK.g01 (geometry) ---

Geom Title=Existing Conditions
Program Version=4.10

River Reach=BASSET CREEK    ,Reach-1
Reach XY= 30
      3752310.67     10641098.96      3752851.98     10640643.16
      3753098.41     10639819.39      3752706.25       10637932.
        3752301.       10637350.       3752708.5       10636442.
      3752557.35      10635965.7        3751521.       10635767.
      3749846.75       10634781.      3748670.75       10633417.
      3747098.75       10632262.        3745754.       10632015.
        3745462.       10631430.      3745585.75       10630682.
      3743962.75       10627344.      3743124.25       10626861.
        3742199.       10627069.       3741516.5       10626895.
      3740549.75       10626470.       3740206.5       10625826.
        3739555.       10625928.        3738458.       10625485.
      3738087.25       10625197.      3738025.75       10624718.
        3737377.       10624575.      3737014.25       10624030.
        3736502.       10623982.      3735616.25       10623398.
       3735493.5       10622277.        3734282.       10621130.

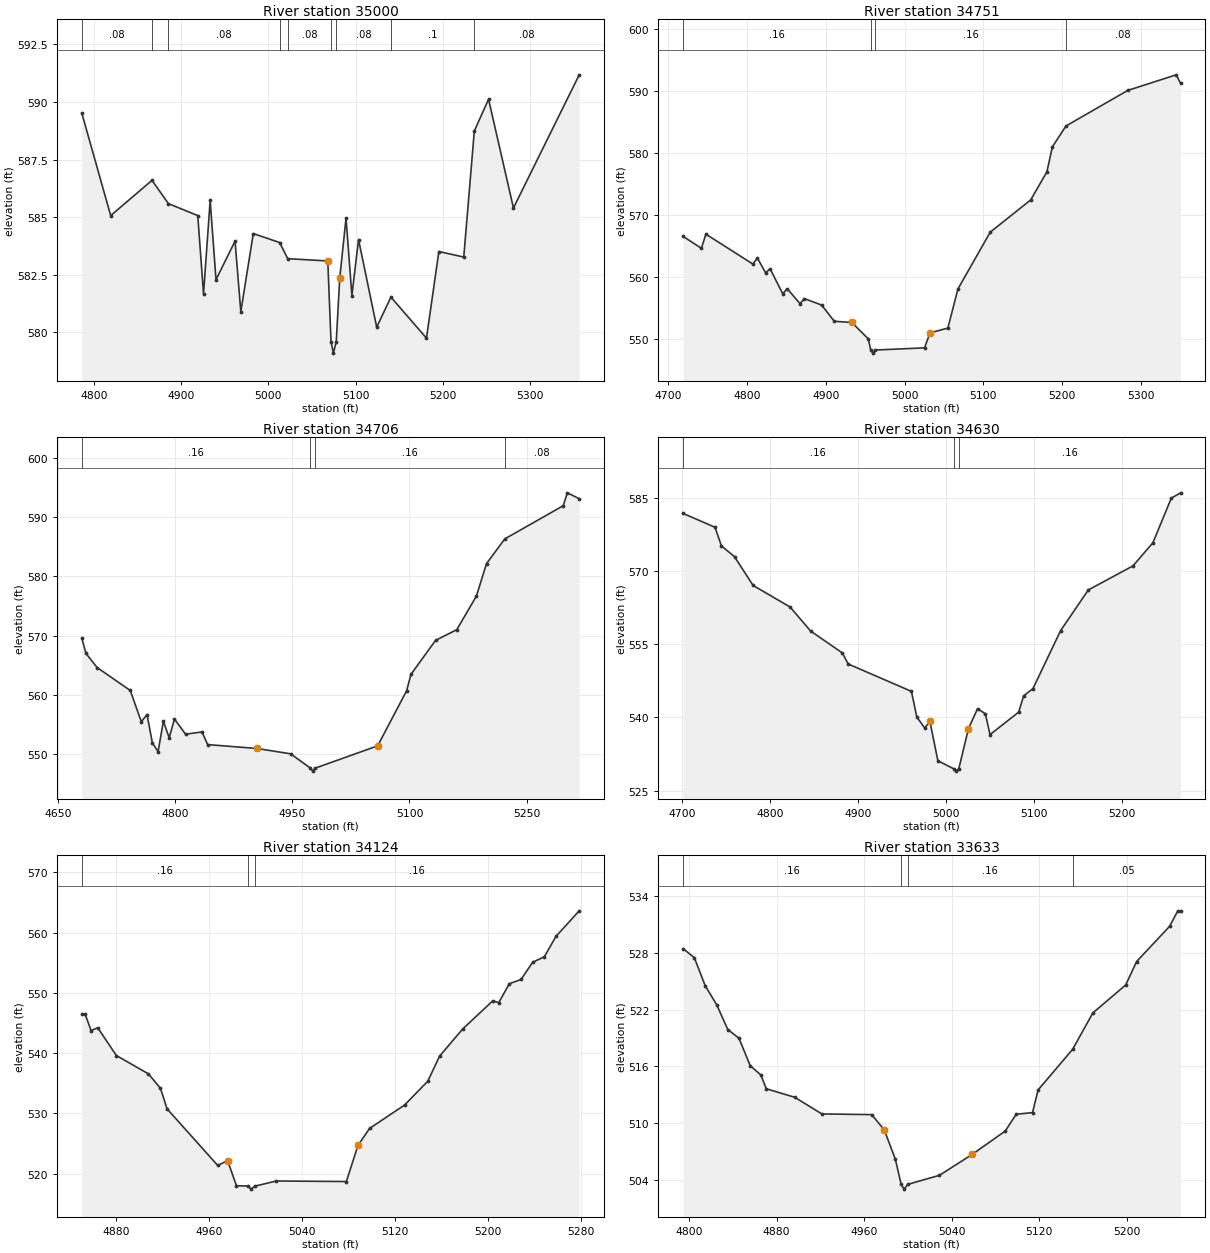
Type RM Length L Ch R = 1 ,35000   ,249,249,249
BEGIN DESCRIPTION:
BASSET CREEK 76.0
END DESCRIPTION:
XS GIS Cut Line= 2
      3752711.56     10640985.27      3752283.59     10640609.39
#Sta/Elev= 30
  4786.3  589.52  4819.4  585.07  4866.7   586.6  4885.5  585.59  4919.1  585.07
  4925.7  581.67  4933.3  585.73    4940  582.29  4961.8  583.96  4968.4   580.9
  4982.7  584.29  5012.9   583.9  5022.1   583.2    5068   583.1  5071.7   579.6
  5074.4   579.1  5077.7   579.6  5081.7  582.36  5088.9  584.96  5095.6   581.6
  5103.2  584.03    5124  580.23  5140.3  581.53    5181  579.75  5195.2  583.51
  5223.7  583.27  5235.8  588.74  5252.1  590.12  5280.6   585.4  5355.9  591.18
#Mann= 9 ,-1 , 0
  4786.3     .08       0  4866.7     .16       0  4885.5     .08       0
  5012.9      .1       0  5022.1     .08       0  5071.7     .07       0
  5077.7     .08       0  5140.3      .1       0  5235.8     .08       0
Bank Sta=5068,5081.7
XS Rating Curve= 0 ,0
Exp/Cntr=0.3,0.1

Type RM Length L Ch R = 1 ,34751   ,45,45,45
BEGIN DESCRIPTION:
Mapping XS a74bd3a2
END DESCRIPTION:
XS GIS Cut Line= 4
      3752907.55      10640912.3       3752809.9     10640734.35
      3752695.96     10640654.05      3752414.24     10640589.04
#Sta/Elev= 30
  4718.9  566.58  4742.1  564.67  4747.8  566.95  4807.5  562.12  4813.2   563.1
  4823.6  560.71  4829.3  561.36  4845.4  557.33  4851.1  558.15  4867.2  555.74
  4872.9  556.54  4894.7  555.51  4910.8  552.89  4933.1   552.7    4954  550.04
  4957.1  548.25  4959.9  547.75  4963.1  548.25  5025.4   548.6  5032.3  551.02
    5055  551.79  5067.8  558.11  5108.8  567.27  5160.2  572.48  5180.7     577
  5187.7  581.04    5205  584.41  5283.5  590.15  5344.9  592.66  5350.4  591.29
#Mann= 4 ,-1 , 0
  4718.9     .16       0  4957.1     .07       0  4963.1     .16       0
    5205     .08       0
Bank Sta=4933.1,5032.3
XS Rating Curve= 0 ,0
Exp/Cntr=0.3,0.1

Type RM Length L Ch R = 1 ,34706   ,76,76,76
BEGIN DESCRIPTION:
Mapping XS 6feae438
END DESCRIPTION:
XS GIS Cut Line= 5
      3753005.06     10640892.65      3752845.34     10640719.91
      3752770.69     10640653.07      3752681.28     10640620.09
      3752483.57     10640559.65
#Sta/Elev= 30
    4680  569.55  4685.4  566.98  4699.6   564.6  4742.1  560.73  4756.3  555.45
  4763.6  556.66  4770.5  551.86  4777.8   550.4  4784.6  555.54    4792  552.74
  4798.8   555.9    4813  553.34    4834  553.73  4841.3  551.59  4904.8  550.93
  4947.7  550.03  4973.1  547.61  4975.9  547.11  4979.1  547.61  5059.2  551.38
  5096.3  560.67  5101.9  563.45  5133.4  569.18  5160.6  570.99  5185.7  576.64
  5198.7  582.14  5222.1  586.31    5297  591.91  5302.3  594.09  5317.5   593.1
#Mann= 4 ,-1 , 0
    4680     .16       0  4973.1     .07       0  4979.1     .16       0
  5222.1     .08       0
Bank Sta=4904.8,5059.2
XS Rating Curve= 0 ,0
Exp/Cntr=0.3,0.1

Type RM Length L Ch R = 1 ,34630   ,506,506,506
BEGIN DESCRIPTION:
BASSET CREEK 75.0
END DESCRIPTION:
XS GIS Cut Line= 3
      3753099.61     10640810.19      3752840.49     10640635.41
      3752599.62     10640560.19
#Sta/Elev= 30
  4701.3  581.87  4737.5  579.03  4744.8  575.21  4759.7  572.99  4780.7   567.1
  4822.8  562.66  4846.1  557.73  4882.2  553.23  4888.7  550.97  4960.6  545.35
  4966.7  540.08  4975.6  537.85  4981.6  539.17  4990.6  531.11  5008.4  529.48
  5011.1  528.98  5014.4  529.48  5025.3  537.68  5035.7  541.81  5044.6  540.73
  5049.8  536.47  5082.3  541.08  5088.1  544.45  5098.6  545.92    5130  557.82
  5161.5  566.17  5212.2  571.11  5234.8  575.85  5255.7     585  5266.2   586.1
#Mann= 3 ,-1 , 0
  4701.3     .16       0  5008.4     .07       0  5014.4     .16       0
Bank Sta=4981.6,5025.3
XS Rating Curve= 0 ,0
Exp/Cntr=0.3,0.1

Type RM Length L Ch R = 1 ,34124   ,491,491,491
BEGIN DESCRIPTION:
BASSET CREEK 74.0
END DESCRIPTION:
XS GIS Cut Line= 3
       3753049.6     10640410.18      3752977.61     10640279.15
      3752699.65     10640260.19
#Sta/Elev= 30
  4850.5  546.52  4853.3  546.52  4858.5  543.75  4864.2  544.22  4880.3  539.61
  4907.8  536.57  4918.2  534.17  4923.9  530.76  4967.5  521.36    4976  522.16
  4983.6     518  4993.6  517.93  4996.3  517.43  4999.6  517.93    5018  518.78
  5078.2  518.69  5088.2  524.68  5098.2  527.51  5128.3  531.39  5148.3  535.35
  5158.4   539.5  5178.4  544.03  5204.3   548.7  5209.3  548.38  5218.5  551.53
  5228.5  552.23  5238.6   555.1  5248.6     556  5258.6  559.39  5278.6  563.63
#Mann= 3 ,-1 , 0
  4850.5     .16       0  4993.6     .07       0  4999.6     .16       0
Bank Sta=4976,5088.2
XS Rating Curve= 0 ,0
Exp/Cntr=0.3,0.1

Type RM Length L Ch R = 1 ,33633   ,271,271,271
BEGIN DESCRIPTION:
BASSET CREEK 73.0
END DESCRIPTION:
XS GIS Cut Line= 3
      3753299.61     10639860.19      3753098.41     10639819.39
      3752849.58     10639810.19
#Sta/Elev= 30
  4794.7  528.44  4804.9  527.49  4814.9  524.51  4825.3  522.52  4835.5  519.89
  4845.7  518.97  4855.9  516.08  4865.6  515.09  4870.7  513.62  4896.7  512.72
  4921.4  510.96  4966.9  510.89  4978.4  509.28  4988.6  506.15  4993.8  503.51
  4996.6  503.01  4999.8  503.51  5028.8  504.47  5058.8  506.69  5088.9  509.15
  5098.9  510.93  5113.8   511.1  5118.9   513.5  5150.4  517.79  5168.9  521.64
  5198.9   524.6  5208.9  527.08    5239   530.8  5246.5  532.44    5249  532.44
#Mann= 4 ,-1 , 0
  4794.7     .16       0  4993.8     .07       0  4999.8     .16       0
  5150.4     .05       0
Bank Sta=4978.4,5058.8
XS Rating Curve= 0 ,0
Exp/Cntr=0.3,0.1

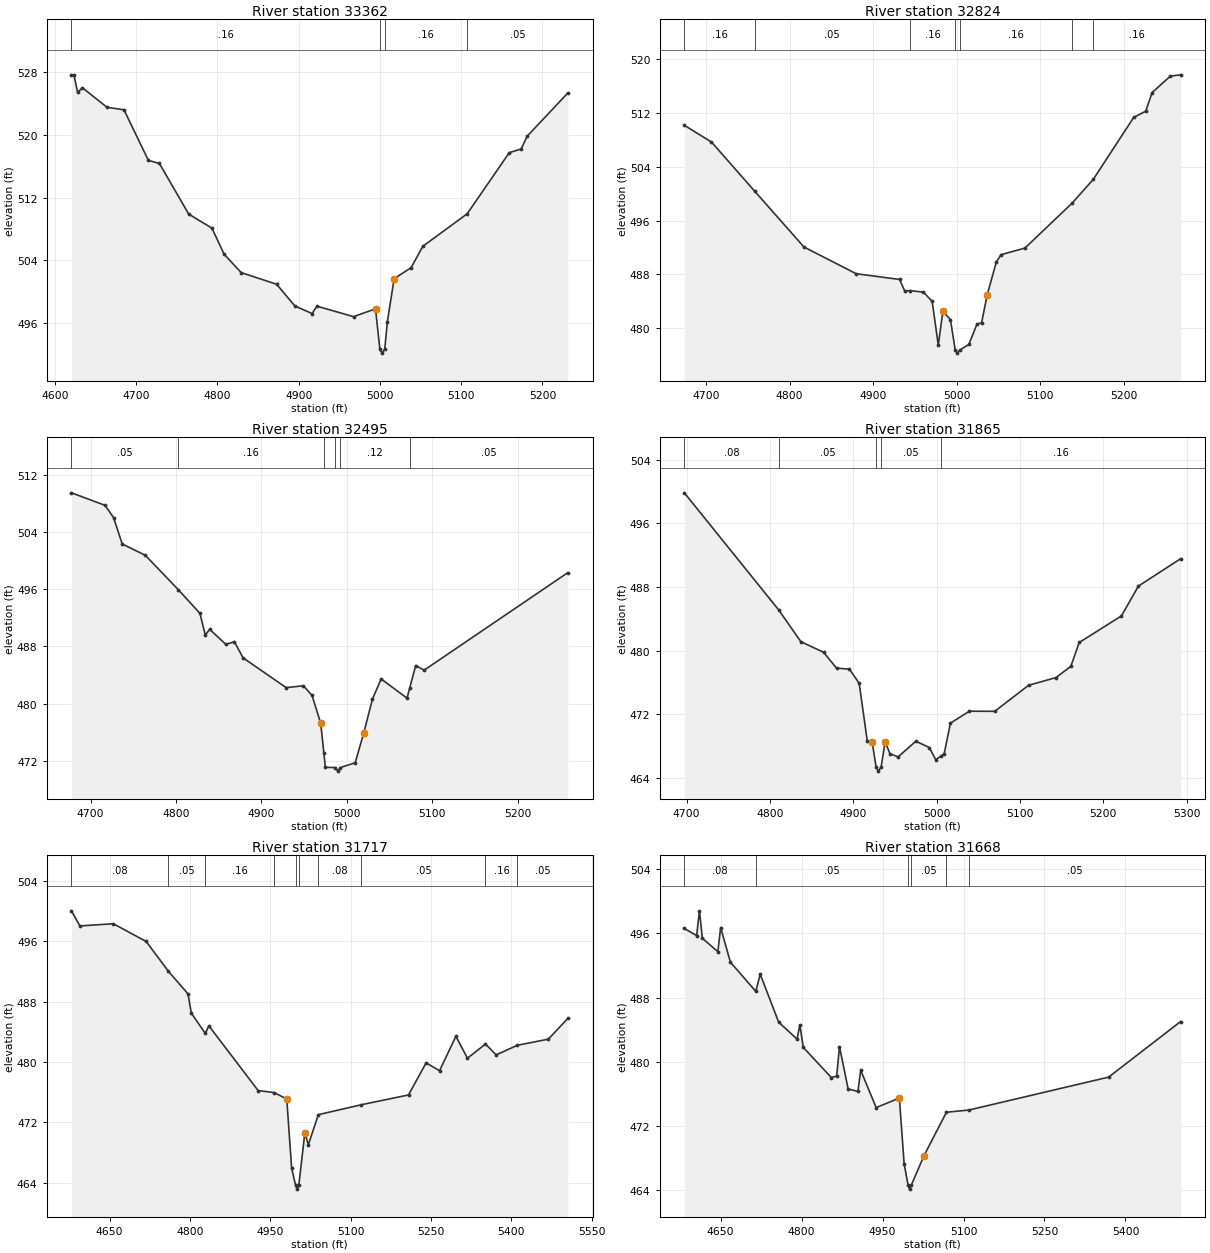
Type RM Length L Ch R = 1 ,33362   ,538,538,538
BEGIN DESCRIPTION:
BASSET CREEK 72.0
END DESCRIPTION:
XS GIS Cut Line= 3
      3753349.61     10639360.19      3753049.61     10639560.19
      3752849.57     10639710.22
#Sta/Elev= 30
  4620.5  527.69  4623.5  527.69    4628  525.45    4634  526.03  4664.1  523.55
  4685.1  523.22  4715.1  516.76  4728.7  516.36  4764.7   509.9  4793.3   508.1
  4808.3  504.77  4829.3  502.42  4872.9  500.93  4895.4  498.15  4916.5  497.19
  4922.5  498.13  4967.5  496.79  4994.6  497.79  4999.9  492.63  5002.7  492.13
  5005.9  492.63  5009.2  496.17  5017.5  501.65  5038.3  503.04  5052.9  505.79
  5107.4  509.94  5159.2  517.75  5173.8  518.21  5181.1  519.84  5231.1  525.36
#Mann= 4 ,-1 , 0
  4620.5     .16       0  4999.9     .07       0  5005.9     .16       0
  5107.4     .05       0
Bank Sta=4994.6,5017.5
XS Rating Curve= 0 ,0
Exp/Cntr=0.3,0.1

Type RM Length L Ch R = 1 ,32824   ,329,329,329
BEGIN DESCRIPTION:
Mapping XS 9d76ba24
END DESCRIPTION:
XS GIS Cut Line= 2
      3753150.14     10638980.07      3752608.47     10639223.13
#Sta/Elev= 30
  4674.1  510.18  4706.6  507.69  4758.2  500.39  4817.2  492.08  4879.7   488.1
  4931.6  487.25  4937.7  485.55    4944  485.59  4960.2  485.36  4970.6  483.99
  4977.9  477.49  4983.4  482.53  4992.5  481.26  4998.1  476.79  5000.8  476.29
  5004.1  476.79  5014.5  477.58  5024.3  480.64  5029.7  480.79  5036.4  484.96
  5047.3  489.82  5052.9  490.93  5081.6  491.92    5138   498.6  5163.3  502.13
  5211.7  511.36  5226.1  512.28  5233.7  515.05  5255.6   517.5  5267.8  517.69
#Mann= 7 ,-1 , 0
  4674.1     .16       0  4758.2     .05       0    4944     .16       0
  4998.1     .07       0  5004.1     .16       0    5138     .05       0
  5163.3     .16       0
Bank Sta=4983.4,5036.4
XS Rating Curve= 0 ,0
Exp/Cntr=0.3,0.1

Type RM Length L Ch R = 1 ,32495   ,630,630,630
BEGIN DESCRIPTION:
Mapping XS df19375d
END DESCRIPTION:
XS GIS Cut Line= 2
      3753108.43     10638792.58      3752533.31     10638875.73
#Sta/Elev= 30
  4677.7  509.44  4716.9   507.7    4727  505.98  4737.1  502.29  4764.1  500.72
  4802.6  495.93  4828.1   492.6  4834.4  489.56  4839.5  490.37  4858.4  488.27
  4868.5  488.62  4878.6  486.38  4929.1  482.22  4949.3  482.48  4959.4  481.13
  4969.5  477.24  4973.2   473.1    4975  471.08  4986.7  471.05  4989.5  470.55
  4992.7  471.05  5009.9  471.72    5020  475.91  5030.1  480.61  5040.3  483.43
  5070.6  480.75  5073.7  482.14  5080.7  485.29  5090.8  484.67  5258.8  498.28
#Mann= 6 ,-1 , 0
  4677.7     .05       0  4802.6     .16       0  4973.2     .12       0
  4986.7     .07       0  4992.7     .12       0  5073.7     .05       0
Bank Sta=4969.5,5020
XS Rating Curve= 0 ,0
Exp/Cntr=0.3,0.1

Type RM Length L Ch R = 1 ,31865   ,148,148,148
BEGIN DESCRIPTION:
BASSET CREEK 69.0
END DESCRIPTION:
XS GIS Cut Line= 3
       3752999.6     10638560.18      3752749.61     10638410.19
      3752449.58     10638360.18
#Sta/Elev= 30
  4697.2  499.86  4810.4  485.12  4837.1  481.11  4864.3  479.78  4879.9  477.78
  4895.4  477.65  4907.1  475.87  4916.8   468.6  4922.7  468.44  4927.4  465.31
  4930.2  464.81  4933.4  465.31  4938.2  468.53    4944  467.01  4953.8   466.6
  4975.1  468.58  4991.3  467.78  4998.9  466.26  5005.1  466.68    5009  466.95
  5016.6  470.85  5039.4  472.36  5069.8  472.34  5110.4  475.62  5143.3  476.59
  5161.1     478  5171.2  481.01  5221.9  484.36  5242.2  488.11  5292.9  491.56
#Mann= 5 ,-1 , 0
  4697.2     .08       0  4810.4     .05       0  4927.4     .04       0
  4933.4     .05       0  5005.1     .16       0
Bank Sta=4922.7,4938.2
XS Rating Curve= 0 ,0
Exp/Cntr=0.3,0.1

Type RM Length L Ch R = 1 ,31717   ,49,49,49
BEGIN DESCRIPTION:
Mapping XS d3cccafc
END DESCRIPTION:
XS GIS Cut Line= 4
      3753174.69     10638394.76      3752744.18     10638271.51
      3752534.11      10638228.1       3752274.1      10638181.3
#Sta/Elev= 30
    4579  500.02  4594.7  498.02  4657.1  498.31  4718.5  495.96  4760.1     492
  4796.5  489.03  4802.7  486.48  4828.9  483.78  4835.4   484.8  4927.5  476.22
  4957.1  475.96  4980.9  475.11    4990  465.95  4997.4  463.67  5000.1  463.17
  5003.4  463.67  5014.7  470.64  5021.2  469.05  5039.9  473.03  5119.9  474.34
  5208.2  475.64  5241.1  479.89  5266.2  478.85  5296.7  483.41  5318.2   480.5
  5351.9  482.38  5371.8  480.95  5411.6  482.22  5469.4  483.03  5505.5  485.77
#Mann= 10 ,-1 , 0
    4579     .08       0  4760.1     .05       0  4828.9     .16       0
  4957.1     .05       0  4997.4     .04       0  5003.4     .05       0
  5039.9     .08       0  5119.9     .05       0  5351.9     .16       0
  5411.6     .05       0
Bank Sta=4980.9,5014.7
XS Rating Curve= 0 ,0
Exp/Cntr=0.3,0.1

Type RM Length L Ch R = 1 ,31668   ,157,157,157
BEGIN DESCRIPTION:
Mapping XS f0a93f4b
END DESCRIPTION:
XS GIS Cut Line= 3
      3753181.72      10638342.7        3752798.     10638235.05
      3752289.33     10638123.94
#Sta/Elev= 30
  4582.9  496.61  4605.7  495.72  4610.9  498.81  4616.3  495.39    4645  493.72
  4650.2  496.72  4668.2  492.41  4715.2  488.77  4723.5   490.9  4757.6  484.93
  4791.7  482.81  4796.9   484.6  4803.2  481.78  4855.1  478.02  4865.1   478.2
  4870.3  481.87  4886.3  476.59  4904.4  476.29  4909.6  478.92  4938.2  474.27
  4981.2  475.46    4990  467.28  4997.3   464.6    5000   464.1  5003.3   464.6
  5026.7  468.26  5068.4  473.69  5109.6  473.96  5368.8  478.07  5502.1     485
#Mann= 6 ,-1 , 0
  4582.9     .08       0  4715.2     .05       0  4997.3     .04       0
  5003.3     .05       0  5068.4     .08       0  5109.6     .05       0
Bank Sta=4981.2,5026.7
XS Rating Curve= 0 ,0
Exp/Cntr=0.3,0.1

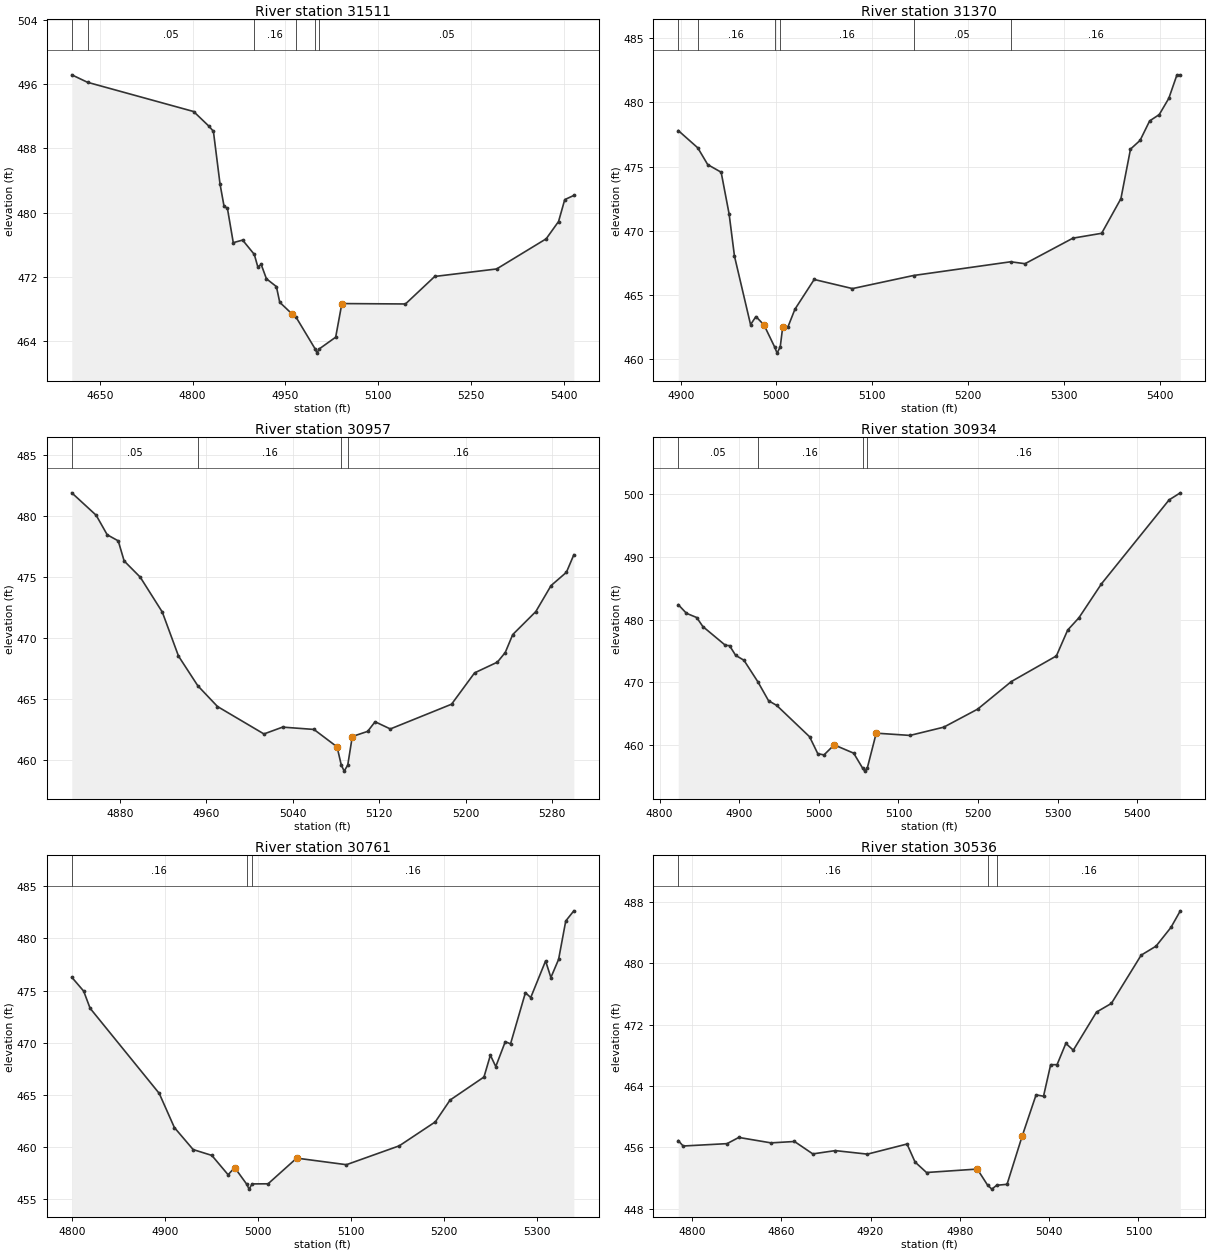
Type RM Length L Ch R = 1 ,31511   ,141,141,141
BEGIN DESCRIPTION:
Mapping XS 2fe7da54
END DESCRIPTION:
XS GIS Cut Line= 3
      3753093.15     10638214.22      3752773.69     10638090.95
      3752304.91     10638077.06
#Sta/Elev= 30
  4604.8  497.14  4630.3  496.21  4801.7  492.58  4826.3  490.77  4833.7  490.12
  4844.4  483.57  4850.9   480.8  4856.3  480.56  4865.8  476.28  4880.9   476.6
  4899.8  474.82  4905.5  473.26  4910.9  473.57  4919.4  471.79  4935.5  470.82
  4940.9  468.87  4961.3  467.38  4967.1  467.04  4998.3  463.05  5001.1  462.55
  5004.3  463.05  5031.3  464.53  5041.3  468.71  5144.1  468.66  5191.4  472.08
  5291.4  473.01  5371.5  476.76  5391.5  478.91  5401.5  481.63  5416.2  482.15
#Mann= 6 ,-1 , 0
  4604.8     .08       0  4630.3     .05       0  4899.8     .16       0
  4967.1     .05       0  4998.3     .04       0  5004.3     .05       0
Bank Sta=4961.3,5041.3
XS Rating Curve= 0 ,0
Exp/Cntr=0.3,0.1

Type RM Length L Ch R = 1 ,31370   ,413,413,413
BEGIN DESCRIPTION:
BASSET CREEK 68.0
END DESCRIPTION:
XS GIS Cut Line= 3
      3752799.64     10637910.17      3752699.61     10637960.19
       3752287.6     10637974.63
#Sta/Elev= 30
  4897.5  477.81  4917.9  476.46  4928.3  475.15  4942.3  474.56  4950.6  471.31
  4956.2  468.02    4973  462.68  4978.6  463.31    4987  462.66    4998  460.96
  5000.7  460.46    5004  460.96  5006.5  462.46  5011.8  462.46  5019.3  463.88
  5039.4   466.2  5079.4  465.49  5143.1  466.51  5244.5  467.58  5259.5  467.43
  5309.5  469.42  5339.5   469.8  5359.6   472.5  5369.6  476.36  5379.6  477.04
  5389.6  478.56  5399.6  479.05  5409.6  480.32  5418.1  482.15  5421.6  482.15
#Mann= 6 ,-1 , 0
  4897.5     .05       0  4917.9     .16       0    4998     .07       0
    5004     .16       0  5143.1     .05       0  5244.5     .16       0
Bank Sta=4987,5006.5
XS Rating Curve= 0 ,0
Exp/Cntr=0.3,0.1

Type RM Length L Ch R = 1 ,30957   ,23,23,23
BEGIN DESCRIPTION:
Mapping XS 41ec722e
END DESCRIPTION:
XS GIS Cut Line= 4
      3752651.71     10637635.28      3752507.22     10637665.15
       3752447.5     10637692.23      3752273.72     10637874.28
#Sta/Elev= 30
  4835.3  481.88  4857.9  480.04  4868.1  478.44  4878.3  477.94  4883.8  476.29
  4898.7  474.96  4919.1   472.1  4934.1  468.49    4952  466.05  4970.2  464.35
  5013.2   462.1  5030.5  462.66  5059.5  462.47  5080.9  461.04  5084.8  459.55
  5087.5  459.05  5090.8  459.55    5095  461.89  5109.2  462.31  5116.1   463.1
  5130.2  462.51  5186.9  464.54  5208.2  467.11  5229.3  467.99  5236.6  468.78
  5243.5  470.25  5264.9  472.14    5279  474.27  5293.2  475.36  5300.1   476.8
#Mann= 4 ,-1 , 0
  4835.3     .05       0    4952     .16       0  5084.8     .07       0
  5090.8     .16       0
Bank Sta=5080.9,5095
XS Rating Curve= 0 ,0
Exp/Cntr=0.3,0.1

Type RM Length L Ch R = 1 ,30934   ,173,173,173
BEGIN DESCRIPTION:
BASSET CREEK 67.0
END DESCRIPTION:
XS GIS Cut Line= 3
       3752649.6     10637610.19      3752449.61     10637660.19
      3752149.62     10637960.18
#Sta/Elev= 30
  4823.5  482.38  4833.8     481  4846.7  480.32  4854.4  478.88  4882.8  475.87
  4887.9  475.83  4895.6  474.27    4906  473.49  4923.4  470.06  4936.9  467.02
  4947.2  466.26  4988.4  461.26  4998.7  458.56  5006.5  458.35  5019.3  459.96
  5043.8  458.63  5054.9  456.26  5057.7  455.76  5060.9  456.26  5072.1  461.83
  5114.5  461.47  5156.9  462.79  5199.4  465.67  5241.8  470.09  5298.3  474.18
  5312.5  478.32  5326.6  480.28  5354.9  485.71  5439.8  499.13  5453.9  500.26
#Mann= 4 ,-1 , 0
  4823.5     .05       0  4923.4     .16       0  5054.9     .07       0
  5060.9     .16       0
Bank Sta=5019.3,5072.1
XS Rating Curve= 0 ,0
Exp/Cntr=0.3,0.1

Type RM Length L Ch R = 1 ,30761   ,225,225,225
BEGIN DESCRIPTION:
Mapping XS 9ac3dcea
END DESCRIPTION:
XS GIS Cut Line= 5
      3752639.18     10637526.53      3752469.88      10637505.7
      3752406.07     10637497.88      3752286.28     10637553.87
      3752135.27     10637638.49
#Sta/Elev= 30
  4799.3  476.29  4812.1  474.96    4819  473.32  4893.4  465.16  4909.7  461.89
  4929.9  459.78    4950  459.22  4967.5  457.37  4974.6  458.05  4987.3  456.49
  4990.1  455.99  4993.3  456.49  5010.5   456.5  5041.3  458.96  5094.8  458.33
  5151.7  460.14  5190.4  462.43  5206.3  464.52  5242.8  466.73  5249.7  468.82
  5255.5  467.73  5265.7  470.11  5271.4  469.91  5287.4  474.81  5293.1  474.34
  5309.1  477.85  5314.8  476.26  5323.1     478  5330.8  481.68  5339.5  482.65
#Mann= 3 ,-1 , 0
  4799.3     .16       0  4987.3     .07       0  4993.3     .16       0
Bank Sta=4974.6,5041.3
XS Rating Curve= 0 ,0
Exp/Cntr=0.3,0.1

Type RM Length L Ch R = 1 ,30536   ,74,74,74
BEGIN DESCRIPTION:
Mapping XS 921bf7e4
END DESCRIPTION:
XS GIS Cut Line= 5
      3752488.06     10637436.53      3752354.69     10637360.12
       3752315.1     10637346.93      3752256.07     10637344.84
      3752173.32     10637347.58
#Sta/Elev= 30
  4790.8  456.87  4794.1  456.16  4823.6  456.47  4831.5  457.28  4853.1  456.57
  4868.9  456.75  4881.2  455.13  4896.3  455.56  4917.9   455.1  4944.5  456.42
  4949.9  454.07  4957.6   452.7  4991.7  453.15  4998.7  451.03  5001.5  450.53
  5004.7  451.03  5011.7  451.16  5021.8  457.42  5031.2  462.84  5036.2  462.66
    5041  466.78  5045.3  466.78  5051.2  469.56  5056.2  468.67  5071.8  473.65
  5081.8  474.78  5101.8  481.08  5111.8  482.26  5121.8   484.7  5128.1  486.87
#Mann= 3 ,-1 , 0
  4790.8     .16       0  4998.7     .07       0  5004.7     .16       0
Bank Sta=4991.7,5021.8
XS Rating Curve= 0 ,0
Exp/Cntr=0.3,0.1

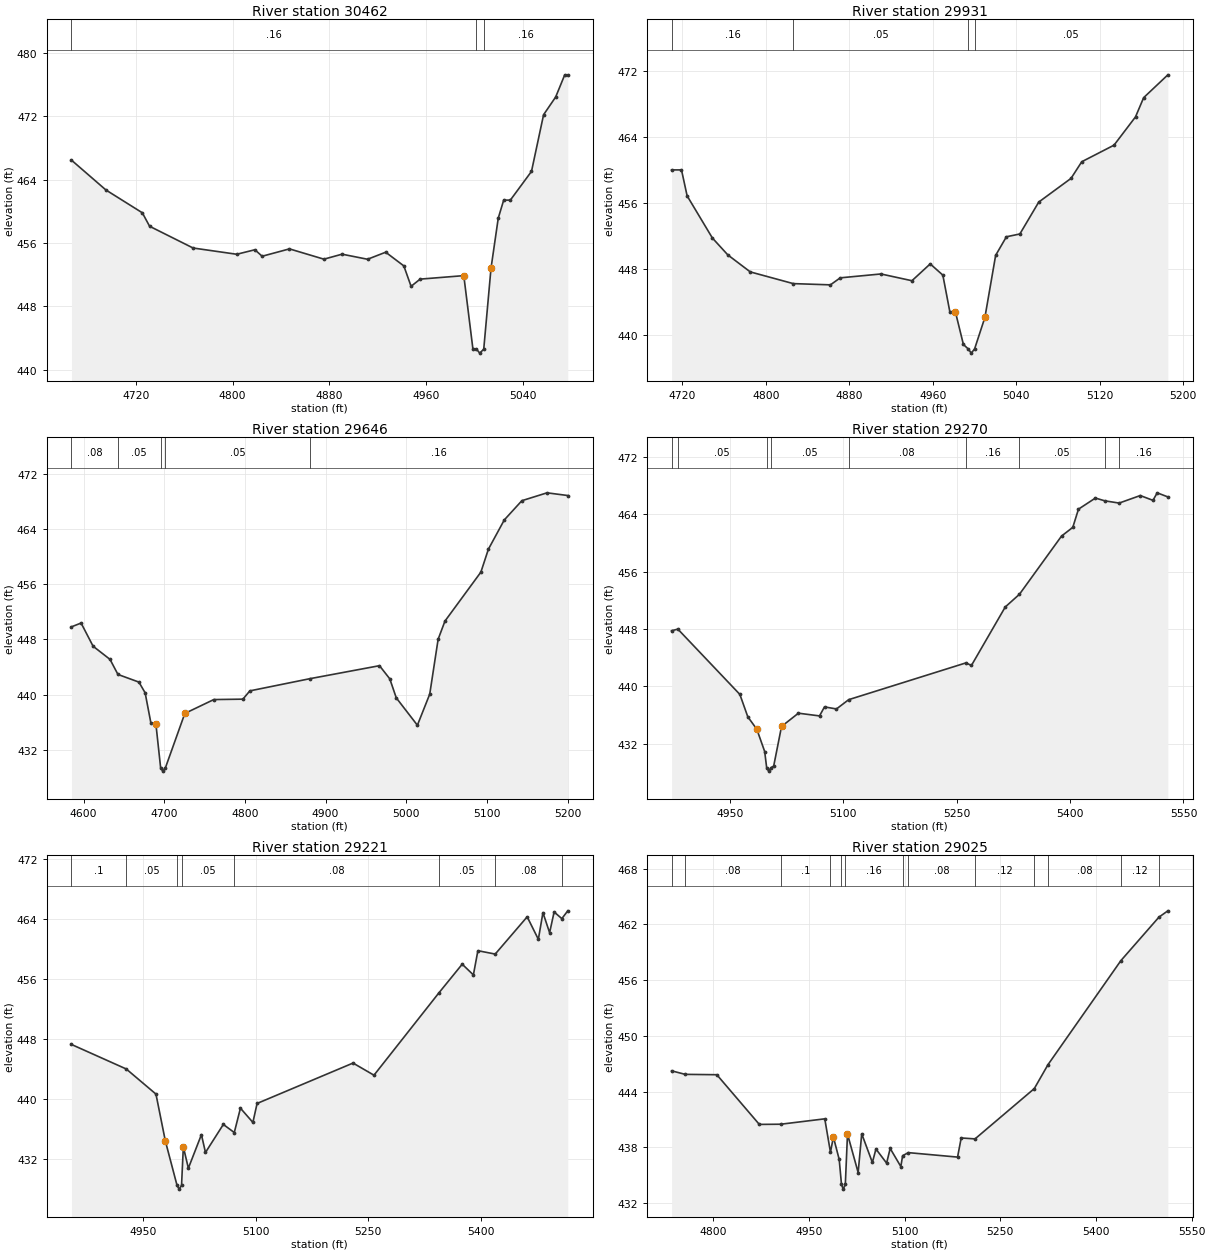
Type RM Length L Ch R = 1 ,30462   ,531,531,531
BEGIN DESCRIPTION:
BASSET CREEK 66.0
END DESCRIPTION:
XS GIS Cut Line= 3
      3752599.59     10637460.17      3752299.61     10637260.19
      3752249.64     10637260.19
#Sta/Elev= 30
  4666.7  466.47  4695.2   462.7  4725.3  459.82  4731.3  458.12  4767.3  455.37
  4803.4  454.58  4818.4  455.15  4824.4  454.33    4847  455.26  4875.5  453.96
  4890.5  454.59  4911.6  453.95  4926.6  454.84  4941.6  453.11  4947.6  450.53
  4955.1  451.44  4991.2  451.88  4998.7  442.67  5001.7  442.59  5004.4  442.09
  5007.7  442.59  5013.7   452.8  5019.7  459.14  5024.2  461.42  5029.7  461.42
  5047.2  465.05  5057.2  472.21  5067.2  474.45  5074.7  477.25  5077.2  477.25
#Mann= 3 ,-1 , 0
  4666.7     .16       0  5001.7     .07       0  5007.7     .16       0
Bank Sta=4991.2,5013.7
XS Rating Curve= 0 ,0
Exp/Cntr=0.3,0.1

Type RM Length L Ch R = 1 ,29931   ,285,285,285
BEGIN DESCRIPTION:
BASSET CREEK 65.0
END DESCRIPTION:
XS GIS Cut Line= 3
      3752699.65     10637010.21      3752449.61     10636910.19
      3752249.57      10636960.2
#Sta/Elev= 30
  4709.8  460.01  4719.3  460.01  4724.7  456.86  4748.9  451.75  4763.7   449.7
  4785.2  447.64  4826.4  446.22    4862  446.07  4871.4  446.92  4910.4  447.39
  4940.1  446.57  4957.6  448.61  4969.7  447.25  4976.4  442.81  4981.7  442.81
  4989.4  438.84  4994.1  438.29  4996.9  437.79  5000.1  438.29    5010  442.12
  5020.3  449.65  5030.6   451.9  5043.5  452.24  5061.6  456.11  5092.5  458.98
  5102.8     461  5133.7  463.01  5154.3  466.44  5162.1  468.77  5185.3  471.54
#Mann= 4 ,-1 , 0
  4709.8     .16       0  4826.4     .05       0  4994.1     .04       0
  5000.1     .05       0
Bank Sta=4981.7,5010
XS Rating Curve= 0 ,0
Exp/Cntr=0.3,0.1

Type RM Length L Ch R = 1 ,29646   ,376,376,376
BEGIN DESCRIPTION:
Mapping XS 1b27df99
END DESCRIPTION:
XS GIS Cut Line= 3
      3752854.96     10636448.85      3752601.52     10636622.44
      3752304.84     10636705.23
#Sta/Elev= 30
  4585.1  449.82    4597  450.37  4611.9  447.01  4632.9   445.1  4642.7  442.92
  4668.7  441.81  4676.4  440.26  4683.6  435.85  4689.7  435.79  4695.6  429.41
  4698.3  428.91  4701.6  429.41  4725.6  437.27  4761.5  439.28  4797.6  439.34
  4806.2  440.54  4880.8  442.31  4966.9  444.19  4979.7  442.28  4987.7  439.53
  5013.9  435.56  5029.2  440.07  5039.6  448.02  5048.1  450.66  5092.6  457.75
  5101.9  461.07  5121.6  465.31  5143.4   468.1  5174.6  469.24  5200.3  468.85
#Mann= 5 ,-1 , 0
  4585.1     .08       0  4642.7     .05       0  4695.6     .07       0
  4701.6     .05       0  4880.8     .16       0
Bank Sta=4689.7,4725.6
XS Rating Curve= 0 ,0
Exp/Cntr=0.3,0.1

Type RM Length L Ch R = 1 ,29270   ,49,49,49
BEGIN DESCRIPTION:
BASSET CREEK 64.0
END DESCRIPTION:
XS GIS Cut Line= 2
      3752820.26     10636337.72      3752234.03     10636632.57
#Sta/Elev= 30
  4873.2  447.75  4881.5  447.98  4963.5  438.86    4974  435.73  4985.9     434
  4996.3  430.89  4998.9  428.65  5001.6  428.15  5004.9  428.65  5008.2  428.85
  5018.6  434.39  5040.9  436.24  5068.8  435.86  5075.4  437.12  5091.2  436.83
  5107.4  438.13  5262.3  443.26  5269.7  442.91  5314.4  451.07  5333.2  452.85
  5388.8  460.97  5403.7  462.19  5411.2  464.73  5433.6  466.28  5446.1  465.89
    5465  465.58  5492.9  466.63  5509.7  465.96  5515.3  467.01  5529.4  466.44
#Mann= 9 ,-1 , 0
  4873.2     .08       0  4881.5     .05       0  4998.9     .04       0
  5004.9     .05       0  5107.4     .08       0  5262.3     .16       0
  5333.2     .05       0  5446.1     .08       0    5465     .16       0
Bank Sta=4985.9,5018.6
XS Rating Curve= 0 ,0
Exp/Cntr=0.3,0.1

Type RM Length L Ch R = 1 ,29221   ,196,196,196
BEGIN DESCRIPTION:
Mapping XS 531cd9e1
END DESCRIPTION:
XS GIS Cut Line= 4
       3752813.9     10636299.45      3752625.06     10636376.29
      3752394.59     10636493.47      3752230.36     10636605.98
#Sta/Elev= 30
  4854.3  447.24  4927.3  443.97  4966.9  440.62  4979.4  434.37    4995  428.44
  4997.8  427.94    5001  428.44  5003.4  433.58  5010.1  430.73  5027.5  435.21
  5032.9  432.83  5056.7  436.57  5071.3  435.49  5079.5  438.74  5096.1  436.84
  5101.7  439.37  5229.6  444.76  5257.5  443.14  5343.6  454.07  5375.1  457.95
    5390  456.52    5396  459.75  5419.1   459.3  5461.7  464.27  5476.6  461.27
  5482.7  464.83  5491.6  462.15  5497.6  464.92  5507.9  464.03  5515.8  465.07
#Mann= 8 ,-1 , 0
  4854.3      .1       0  4927.3     .05       0    4995     .04       0
    5001     .05       0  5071.3     .08       0  5343.6     .05       0
  5419.1     .08       0  5507.9     .16       0
Bank Sta=4979.4,5003.4
XS Rating Curve= 0 ,0
Exp/Cntr=0.3,0.1

Type RM Length L Ch R = 1 ,29025   ,69,69,69
BEGIN DESCRIPTION:
Mapping XS 13cab80e
END DESCRIPTION:
XS GIS Cut Line= 4
      3752842.48     10636049.47      3752602.92     10636174.46
      3752458.39     10636247.38      3752152.89     10636409.19
#Sta/Elev= 30
  4734.9  446.23  4756.2  445.85  4805.8  445.81  4872.4  440.46  4906.1  440.48
    4975  441.06  4983.9  437.46  4988.5   439.1  4997.6  436.69  5001.2  433.99
  5003.9  433.49  5007.2  433.99  5010.6  439.42  5027.3  435.28  5032.9  439.45
  5049.6  436.36  5055.2  437.81  5071.9  436.29  5077.5  437.87  5094.2  435.92
    5097  437.09    5106  437.42  5183.1  436.94  5188.8     439  5210.5   438.9
  5303.4  444.32  5324.8  446.89  5439.1   458.1  5498.7  462.78  5512.7  463.46
#Mann= 13 ,-1 , 0
  4734.9     .15       0  4756.2     .08       0  4906.1      .1       0
  4983.9     .16       0  5001.2     .07       0  5007.2     .16       0
    5097     .12       0    5106     .08       0  5210.5     .12       0
  5303.4      .1       0  5324.8     .08       0  5439.1     .12       0
  5498.7     .08       0
Bank Sta=4988.5,5010.6
XS Rating Curve= 0 ,0
Exp/Cntr=0.3,0.1

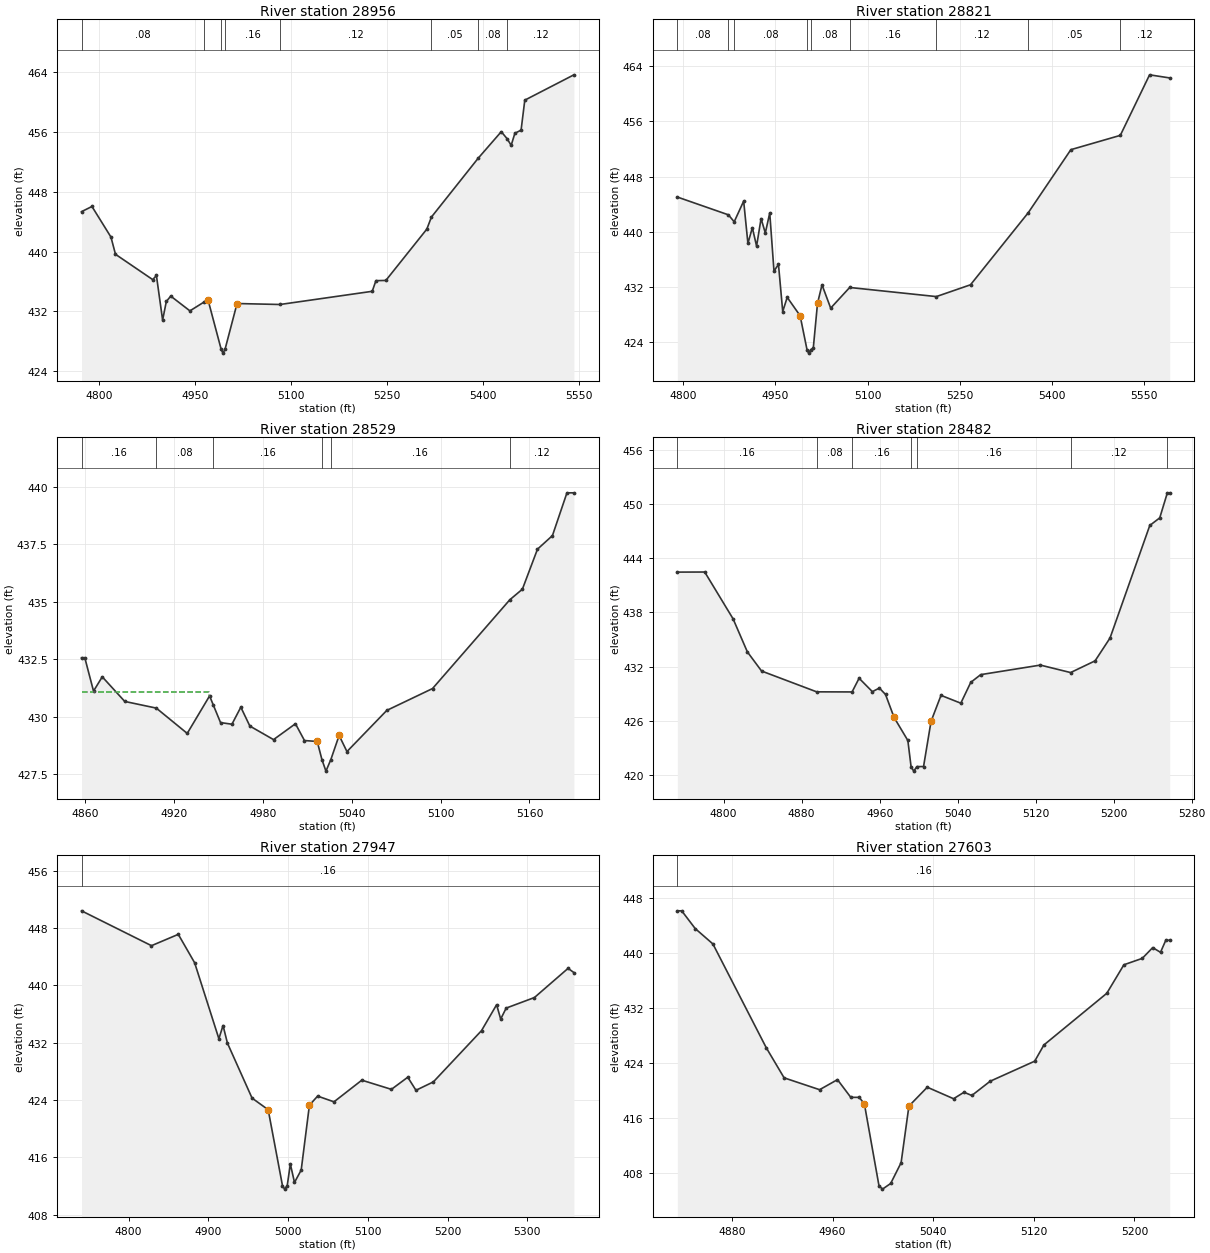
Type RM Length L Ch R = 1 ,28956   ,135,135,135
BEGIN DESCRIPTION:
BASSET CREEK 63.0
END DESCRIPTION:
XS GIS Cut Line= 2
      3752788.98     10635987.04      3752130.25     10636385.75
#Sta/Elev= 30
    4772  445.32  4788.3  446.01    4818  441.93  4825.1  439.63  4883.3  436.25
  4889.1   436.8  4898.8  430.85  4904.6  433.33  4911.5  434.05  4941.5  432.08
    4964  433.28    4970  433.49  4990.4  426.94  4993.1  426.44  4996.4  426.94
  5015.2  433.06  5082.4  432.93  5226.6  434.69  5232.4  436.11  5247.9  436.14
    5312  442.99  5319.2   444.6  5392.2  452.44  5428.4  455.99  5437.5  455.06
  5443.9  454.17  5449.7  455.78  5459.4   456.2  5465.2   460.2    5542  463.58
#Mann= 8 ,-1 , 0
    4772     .08       0    4964     .16       0  4990.4     .07       0
  4996.4     .16       0  5082.4     .12       0  5319.2     .05       0
  5392.2     .08       0  5437.5     .12       0
Bank Sta=4970,5015.2
XS Rating Curve= 0 ,0
Exp/Cntr=0.3,0.1

Type RM Length L Ch R = 1 ,28821   ,292,292,292
BEGIN DESCRIPTION:
Mapping XS 36d13d8b
END DESCRIPTION:
XS GIS Cut Line= 3
      3752712.66     10635830.74       3752441.8     10636087.71
      3752108.44     10636355.09
#Sta/Elev= 30
  4790.4  445.04  4873.5  442.46  4882.9  441.45  4898.3  444.45  4905.2  438.32
  4912.4   440.6  4919.3  437.93  4926.6  441.92  4933.5  439.83  4940.7  442.73
  4947.6  434.31  4954.9  435.29  4961.8  428.45  4969.1  430.51  4990.1  427.85
  5001.3  422.93    5004  422.43  5007.3  422.93  5011.5  423.14  5018.4  429.65
  5025.7  432.32  5039.8  428.95  5070.7  431.94  5211.6  430.62  5267.2  432.33
  5361.2  442.78  5430.4   451.9  5510.8  453.97  5558.4  462.74  5591.1  462.29
#Mann= 9 ,-1 , 0
  4790.4     .08       0  4873.5     .16       0  4882.9     .08       0
  5001.3     .07       0  5007.3     .08       0  5070.7     .16       0
  5211.6     .12       0  5361.2     .05       0  5510.8     .12       0
Bank Sta=4990.1,5018.4
XS Rating Curve= 0 ,0
Exp/Cntr=0.3,0.1

Type RM Length L Ch R = 1 ,28529   ,47,47,47
BEGIN DESCRIPTION:
Mapping XS 00d54335
END DESCRIPTION:
XS GIS Cut Line= 4
      3752408.35     10635888.83       3752311.5     10635951.84
      3752274.52     10636003.92      3752245.88      10636154.4
#Sta/Elev= 30
  4857.4  432.56  4859.6  432.56  4865.5  431.11  4871.4  431.73  4886.6  430.66
  4907.9  430.37  4928.8  429.27  4943.9   430.9  4946.5  430.49  4951.3  429.74
    4959  429.67    4965  430.41  4971.1  429.59  4987.1     429  5001.9  429.69
    5008  428.96  5016.6  428.92  5019.8  428.13  5022.5  427.63  5025.8  428.13
  5031.4  429.18  5036.7  428.48  5063.6  430.27  5094.5  431.22  5146.7  435.08
  5155.2  435.54  5165.4  437.28  5175.5  437.87  5185.3  439.73    5190  439.73
#Mann= 6 ,-1 , 0
  4857.4     .16       0  4907.9     .08       0  4946.5     .16       0
  5019.8     .07       0  5025.8     .16       0  5146.7     .12       0
#XS Ineff= 2 , 0
         4943.47  431.06
Permanent Ineff=
       F       F
Bank Sta=5016.6,5031.4
XS Rating Curve= 0 ,0
Exp/Cntr=0.3,0.1

Type RM Length L Ch R = 1 ,28482   ,535,535,535
BEGIN DESCRIPTION:
BASSET CREEK 62.0
END DESCRIPTION:
XS GIS Cut Line= 3
      3752449.58     10635810.21      3752249.61     10635960.19
      3752199.61     10636210.18
#Sta/Elev= 30
  4752.5  442.48  4780.6  442.49  4809.7  437.29  4824.3  433.63  4838.9   431.5
  4895.4  429.19  4931.7  429.18  4938.9   430.7  4952.5  429.21  4959.7  429.61
    4966   428.9 4974.77  426.35  4988.9  423.79  4992.2  420.89  4994.9  420.39
  4998.2  420.89    5005   420.9  5012.7  425.92  5022.9   428.8  5043.2  427.93
  5053.4  430.24  5063.6   431.1  5124.8  432.16  5155.8  431.33  5180.9  432.63
  5196.2  435.16    5237  447.66  5247.2   448.5    5255  451.28  5257.4  451.28
#Mann= 7 ,-1 , 0
  4752.5     .16       0  4895.4     .08       0  4931.7     .16       0
  4992.2     .07       0  4998.2     .16       0  5155.8     .12       0
    5255     .05       0
Bank Sta=4974.77,5012.7
XS Rating Curve= 0 ,0
Exp/Cntr=0.3,0.1

Type RM Length L Ch R = 1 ,27947   ,344,344,344
BEGIN DESCRIPTION:
Mapping XS 9e181501
END DESCRIPTION:
XS GIS Cut Line= 2
      3751865.41     10635532.17      3751723.05     10636132.84
#Sta/Elev= 30
  4741.1  450.38  4828.8  445.52  4862.4   447.1  4882.9  443.14  4913.3  432.55
  4918.5  434.39    4924  431.94  4954.9  424.27  4975.1  422.65    4993  412.08
  4995.7  411.58    4999  412.08  5002.9  415.08  5008.1  412.51  5016.5  414.24
  5026.8  423.28  5037.1  424.55  5057.6  423.75  5092.5  426.77  5129.6  425.49
  5150.1  427.18  5160.4  425.36  5182.2  426.53  5242.6  433.68  5261.5  437.29
  5266.6  435.29  5273.5  436.82  5308.9  438.29  5351.1  442.36  5358.4  441.77
#Mann= 1 ,-1 , 0
  4741.1     .16       0
Bank Sta=4975.1,5026.8
XS Rating Curve= 0 ,0
Exp/Cntr=0.3,0.1

Type RM Length L Ch R = 1 ,27603   ,418,418,418
BEGIN DESCRIPTION:
BASSET CREEK 60.0
END DESCRIPTION:
XS GIS Cut Line= 3
      3751599.62     10635610.18      3751499.61     10635710.19
      3751349.63     10635910.16
#Sta/Elev= 30
  4836.6   446.1  4840.1   446.1  4850.8  443.53  4864.9  441.29  4907.3  426.23
  4921.5  421.86  4949.7  420.14  4963.9   421.6  4974.5  419.03  4981.2  419.03
  4985.3  418.08  4996.9  406.21  4999.7  405.71  5006.2  406.53  5014.5  409.55
  5020.7  417.76  5035.3   420.5  5056.2  418.83  5064.5  419.77  5070.7   419.3
  5085.3  421.37  5120.7  424.28    5128  426.63    5178  434.13  5191.6  438.27
  5206.2   439.2  5214.5  440.76  5220.7  440.08  5224.9  441.83    5228  441.83
#Mann= 1 ,-1 , 0
  4836.6     .16       0
Bank Sta=4985.3,5020.7
XS Rating Curve= 0 ,0
Exp/Cntr=0.3,0.1