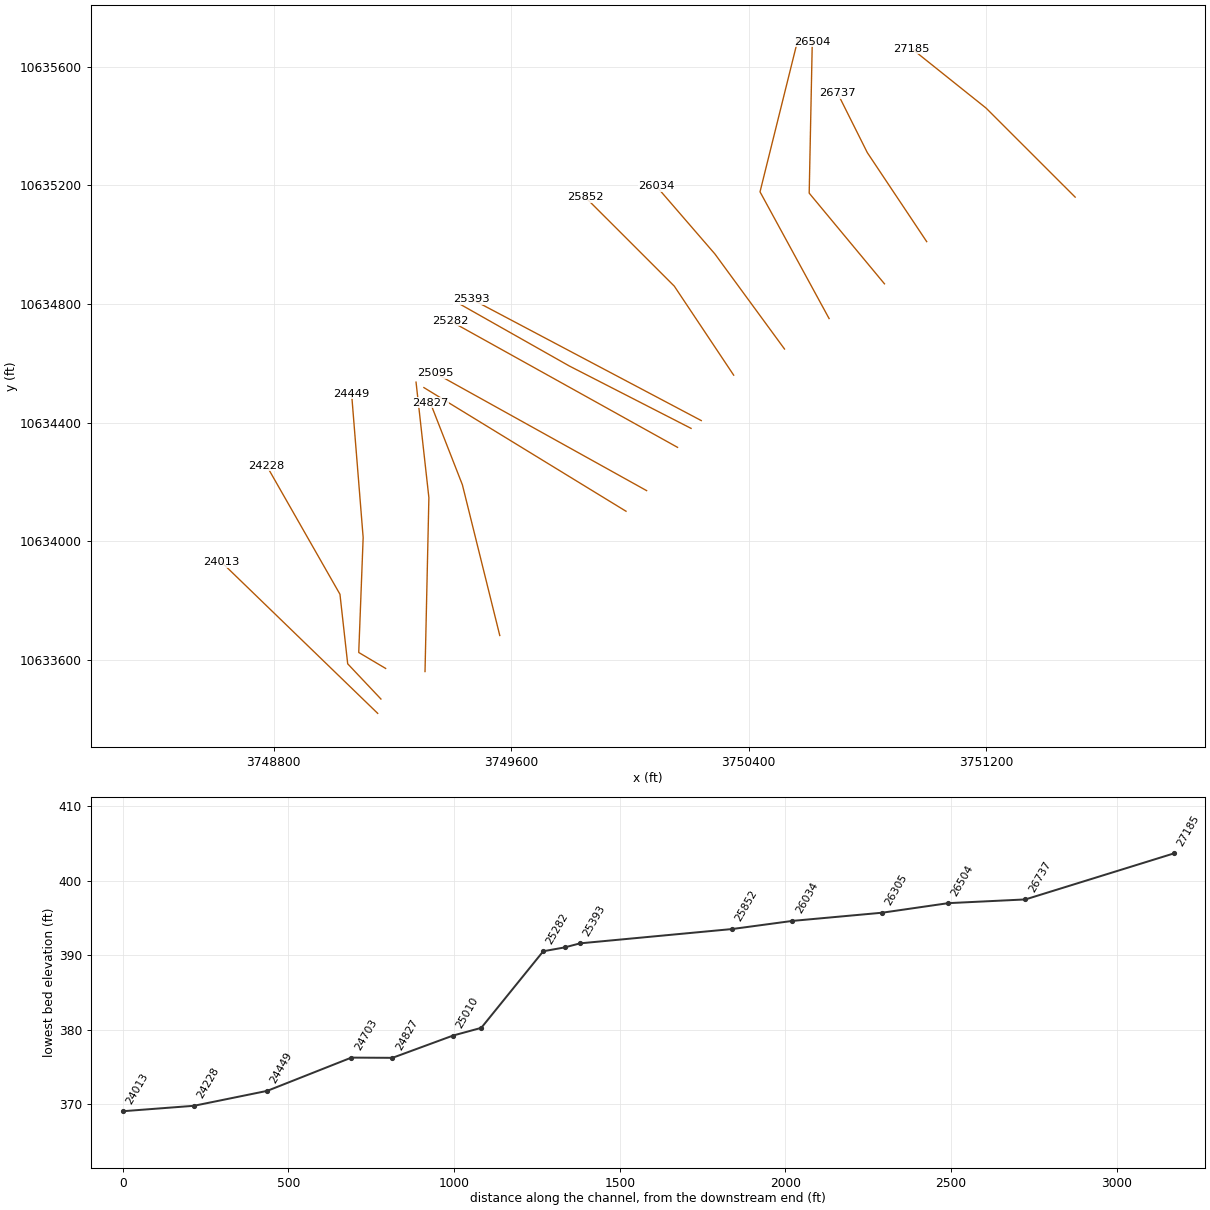
HEC-RAS study BASSET CREEK.prj: BASSET CREEK Base Level Engineering

--- BASSET CREEK.g01 (geometry) --- (continued)

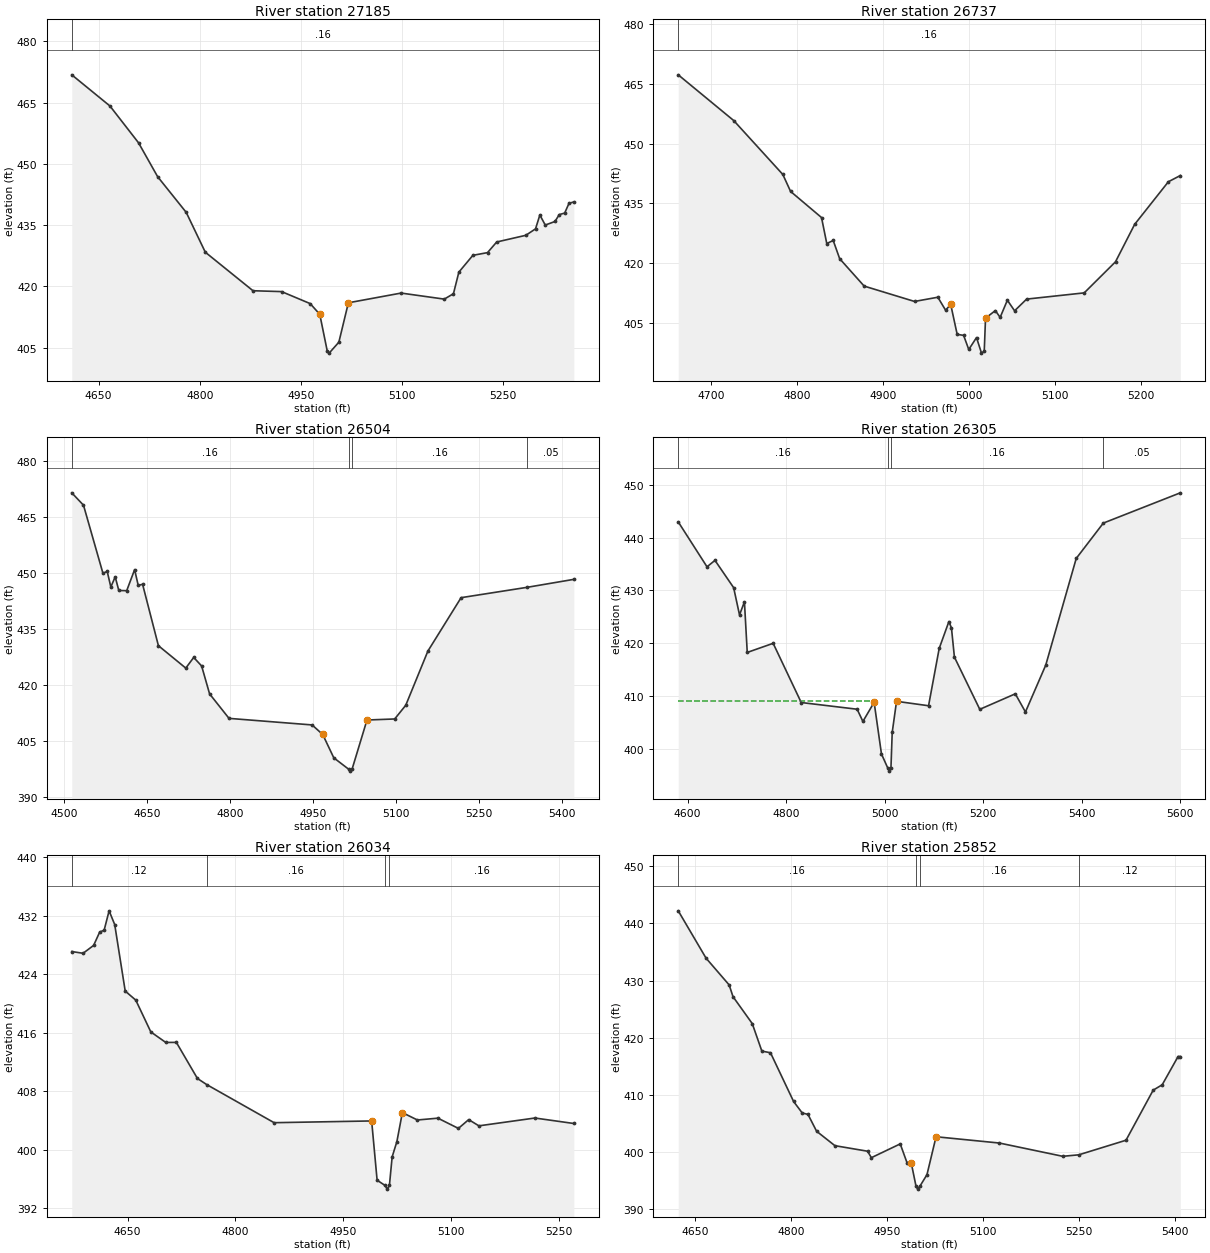
Type RM Length L Ch R = 1 ,27185   ,448,448,448
BEGIN DESCRIPTION:
BASSET CREEK 59.0
END DESCRIPTION:
XS GIS Cut Line= 3
      3751499.61     10635160.19      3751199.61     10635460.19
      3750949.62     10635660.18
#Sta/Elev= 30
  4610.3  471.78  4666.9  464.15  4709.3  455.14  4737.6  446.85    4780  438.11
  4808.3  428.36    4879  418.93  4921.4  418.72  4963.8  415.78    4978  413.16
  4989.1  404.16  4991.9  403.66  5006.3  406.34  5020.4  415.98  5098.6  418.36
  5162.6  416.88  5176.2   418.2  5184.2  423.48    5205   427.6  5226.7  428.26
  5240.3  430.86  5283.5   432.5  5297.9  434.08  5304.3  437.47  5312.3  435.01
  5326.7  435.88  5333.1  437.57  5341.1  437.94  5347.5  440.32  5354.7  440.67
#Mann= 1 ,-1 , 0
  4610.3     .16       0
Bank Sta=4978,5020.4
XS Rating Curve= 0 ,0
Exp/Cntr=0.3,0.1

Type RM Length L Ch R = 1 ,26737   ,233,233,233
BEGIN DESCRIPTION:
BASSET CREEK 58.0
END DESCRIPTION:
XS GIS Cut Line= 3
       3750999.6      10635010.2      3750799.61     10635310.19
      3750699.63     10635510.15
#Sta/Elev= 30
  4661.8  467.24  4726.4  455.77  4783.5  442.26  4792.5  438.02  4828.5  431.47
  4834.6  424.96  4842.1  425.72  4849.6  421.16  4878.1  414.29  4936.7  410.44
  4963.8   411.5  4972.8  408.26  4978.8  409.68  4986.3   402.2  4993.8  401.94
  4999.8   398.4  5008.8  401.39  5014.6  397.49  5017.8  397.99  5019.3  406.25
  5030.7  408.15  5036.3  406.45  5044.7  410.75  5053.1   408.1  5067.1  411.03
  5134.1  412.59  5170.5  420.38  5192.8  429.77    5232  440.44  5245.9     442
#Mann= 1 ,-1 , 0
  4661.8     .16       0
Bank Sta=4978.8,5019.3
XS Rating Curve= 0 ,0
Exp/Cntr=0.3,0.1

Type RM Length L Ch R = 1 ,26504   ,199,199,199
BEGIN DESCRIPTION:
Mapping XS 7dd30b75
END DESCRIPTION:
XS GIS Cut Line= 3
      3750857.39     10634868.02      3750603.93     10635173.55
      3750614.35     10635683.97
#Sta/Elev= 30
  4514.5  471.58  4535.7  468.26  4570.8  450.04  4578.6   450.5  4585.1  446.34
    4593  449.06  4599.5  445.41  4613.8  445.35  4628.1     451  4634.6  446.77
  4642.5  447.06  4671.1  430.61  4720.6   424.6  4734.9  427.46  4749.2  425.18
  4763.6   417.7  4798.7  411.13  4948.9  409.37  4968.1  406.81  4988.1  400.56
  5015.1  397.49  5017.9  396.99  5021.1  397.49  5048.1  410.69  5098.2  410.97
  5118.2  414.65  5158.2  429.17  5218.2  443.48  5337.8  446.26    5422  448.39
#Mann= 4 ,-1 , 0
  4514.5     .16       0  5015.1     .07       0  5021.1     .16       0
  5337.8     .05       0
Bank Sta=4968.1,5048.1
XS Rating Curve= 0 ,0
Exp/Cntr=0.3,0.1

Type RM Length L Ch R = 1 ,26305   ,271,271,271
BEGIN DESCRIPTION:
BASSET CREEK 57.0
END DESCRIPTION:
XS GIS Cut Line= 3
      3750670.94     10634750.95      3750438.33     10635177.99
      3750566.78     10635695.29
#Sta/Elev= 30
  4580.9  442.98  4639.3  434.46  4655.5  435.68  4693.4   430.5  4705.3  425.34
  4715.3  427.82    4721  418.22  4773.6  419.95  4830.6  408.72  4944.1  407.45
  4955.8  405.13  4978.6  408.76  4993.5  398.96  5006.7  396.21  5009.4  395.71
  5012.7  396.21  5015.3  403.04  5024.1  408.95  5089.1  408.11  5110.7  418.98
  5130.4  424.08  5135.6  422.86  5141.6  417.33  5193.1  407.43  5265.2  410.37
  5285.8  406.93    5327  415.81  5388.9  436.05  5443.9  442.75  5600.2  448.49
#Mann= 4 ,-1 , 0
  4580.9     .16       0  5006.7     .07       0  5012.7     .16       0
  5443.9     .05       0
#XS Ineff= 2 , 0
          4977.5  409.07 5185.91          408.77
Permanent Ineff=
       F       F
Bank Sta=4978.6,5024.1
XS Rating Curve= 0 ,0
Exp/Cntr=0.3,0.1

Type RM Length L Ch R = 1 ,26034   ,182,182,182
BEGIN DESCRIPTION:
Mapping XS ebf0fc95
END DESCRIPTION:
XS GIS Cut Line= 3
      3750520.77     10634648.29      3750286.42     10634968.56
      3750089.59     10635196.47
#Sta/Elev= 30
  4572.4  427.12  4588.1  426.88  4602.8  427.96  4611.2  429.78  4617.4  430.04
  4624.3  432.69  4632.1  430.81  4646.7  421.71  4661.4  420.47  4682.3  416.12
  4703.1  414.68  4717.8  414.69  4747.1  409.75  4759.9  408.92  4853.7   403.7
  4989.3  403.94  4996.9  395.83    5008  395.11  5010.8  394.61    5014  395.11
  5017.8  399.02  5024.4  401.12    5032  405.08  5052.9  404.07  5081.4  404.32
  5109.9  402.92  5124.2  404.12  5138.4  403.27  5216.3  404.34  5270.4  403.59
#Mann= 4 ,-1 , 0
  4572.4     .12       0  4759.9     .16       0    5008     .07       0
    5014     .16       0
Bank Sta=4989.3,5032
XS Rating Curve= 0 ,0
Exp/Cntr=0.3,0.1

Type RM Length L Ch R = 1 ,25852   ,459,459,459
BEGIN DESCRIPTION:
BASSET CREEK 56.0
END DESCRIPTION:
XS GIS Cut Line= 3
       3750349.6      10634560.2      3750149.61     10634860.19
      3749849.61     10635160.19
#Sta/Elev= 30
    4624  442.19  4667.5  433.91  4703.6  429.23  4709.6  427.18  4739.7  422.47
  4754.7  417.66  4768.2  417.37  4804.3  408.85  4817.8  406.84  4826.8  406.59
  4840.3  403.64  4868.9  401.12  4919.9  400.15  4925.9  399.02    4971  401.43
  4981.5  398.17  4988.1  398.17  4995.7  394.02  4998.4  393.52  5001.7  394.02
  5012.8  396.05    5027  402.68    5126  401.58    5225  399.26  5250.1  399.52
  5323.9  402.07  5366.4  410.83  5380.5  411.77  5405.3  416.71  5408.8  416.71
#Mann= 4 ,-1 , 0
    4624     .16       0  4995.7     .07       0  5001.7     .16       0
  5250.1     .12       0
Bank Sta=4988.1,5027
XS Rating Curve= 0 ,0
Exp/Cntr=0.3,0.1

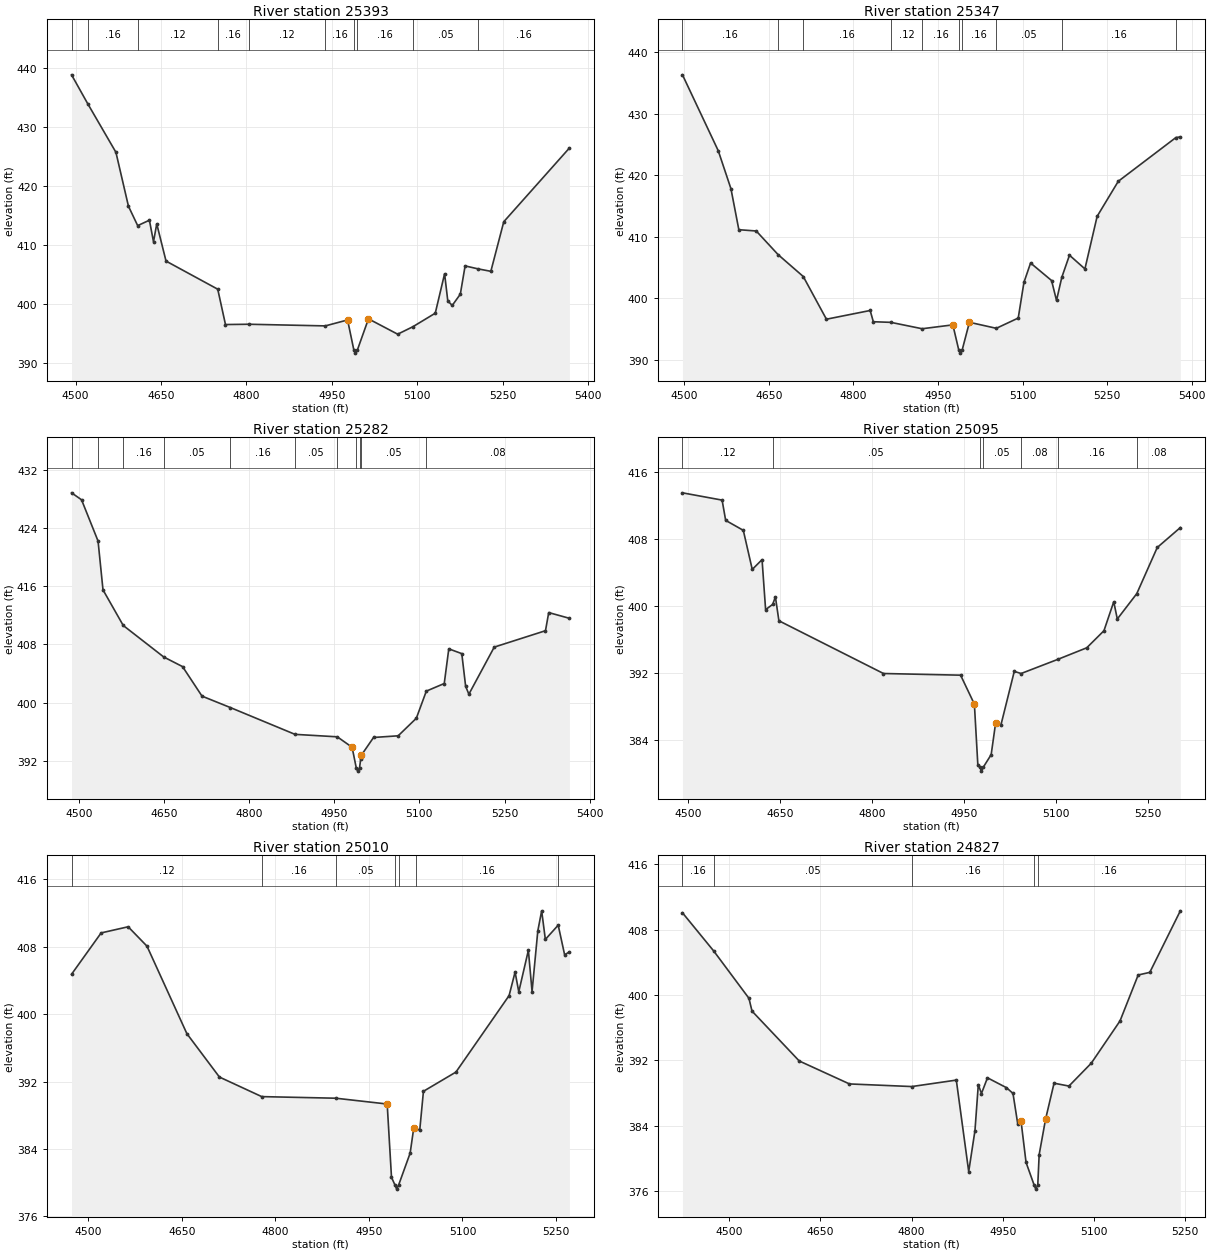
Type RM Length L Ch R = 1 ,25393   ,46,46,46
BEGIN DESCRIPTION:
Mapping XS ae8b26a6
END DESCRIPTION:
XS GIS Cut Line= 2
      3750240.45     10634407.14      3749467.67     10634816.05
#Sta/Elev= 30
  4492.9  438.92  4521.1  434.04  4570.8  425.75  4592.8  416.58    4609  413.28
  4629.6   414.2  4636.8  410.54  4642.5  413.58  4658.8  407.25  4749.6  402.47
  4763.2  396.46  4804.5  396.51  4938.5  396.23  4977.6  397.24  4988.7   392.1
  4991.4   391.6  4994.7   392.1  5014.3  397.43  5065.6  394.82  5092.3  396.09
  5131.6  398.39    5148   405.1  5153.6  400.47  5161.4  399.71  5175.6  401.62
    5184  406.43  5206.6  405.93  5229.2  405.51  5251.9  413.94  5367.2  426.48
#Mann= 10 ,-1 , 0
  4492.9     .12       0  4521.1     .16       0    4609     .12       0
  4749.6     .16       0  4804.5     .12       0  4938.5     .16       0
  4988.7     .07       0  4994.7     .16       0  5092.3     .05       0
  5206.6     .16       0
Bank Sta=4977.6,5014.3
XS Rating Curve= 0 ,0
Exp/Cntr=0.3,0.1

Type RM Length L Ch R = 1 ,25347   ,65,65,65
BEGIN DESCRIPTION:
Mapping XS 0dd84584
END DESCRIPTION:
XS GIS Cut Line= 3
      3750206.12     10634380.84      3749796.43     10634590.89
       3749428.4     10634799.21
#Sta/Elev= 30
  4496.7  436.36  4560.2     424  4582.7  417.82  4596.7  411.15  4627.6  410.94
  4666.4  407.09    4711  403.53  4752.1  396.58  4829.7     398  4835.3  396.17
  4866.4  396.07  4921.9  395.03  4976.4  395.66  4986.9  391.56  4989.6  391.06
  4992.9  391.56  5005.8  396.08  5053.5   395.1  5092.4  396.77  5102.5  402.57
  5114.3  405.73  5151.5  402.88  5160.3  399.64  5169.7   403.4  5183.3     407
  5210.7  404.77  5232.4  413.33  5269.9  419.03  5372.1  426.15    5380  426.25
#Mann= 10 ,-1 , 0
  4496.7     .16       0  4666.4     .12       0    4711     .16       0
  4866.4     .12       0  4921.9     .16       0  4986.9     .07       0
  4992.9     .16       0  5053.5     .05       0  5169.7     .16       0
  5372.1     .08       0
Bank Sta=4976.4,5005.8
XS Rating Curve= 0 ,0
Exp/Cntr=0.3,0.1

Type RM Length L Ch R = 1 ,25282   ,187,187,187
BEGIN DESCRIPTION:
BASSET CREEK 55.0
END DESCRIPTION:
XS GIS Cut Line= 2
      3750160.51      10634316.9      3749393.86     10634743.59
#Sta/Elev= 30
    4487  428.91  4504.6  427.95  4533.7  422.26  4542.4  415.53  4578.1  410.62
  4649.4  406.28  4682.6  404.95  4716.9  400.88  4766.7  399.31  4880.8  395.61
  4955.3  395.27  4981.4  393.83  4988.6  391.04  4991.3  390.54  4994.6  391.04
  4996.5  392.17  4997.4   392.7  5019.2  395.18  5062.6  395.41  5094.6  397.83
  5112.2  401.57  5143.8  402.62  5151.8   407.4  5174.7  406.74  5181.5  402.23
  5187.2  401.15  5231.9  407.64  5322.2   409.9  5327.9   412.4  5364.4  411.61
#Mann= 11 ,-1 , 0
    4487     .12       0  4533.7     .05       0  4578.1     .16       0
  4649.4     .05       0  4766.7     .16       0  4880.8     .05       0
  4955.3     .16       0  4988.6     .04       0  4994.6     .16       0
  4996.5     .05       0  5112.2     .08       0
Bank Sta=4981.4,4997.4
XS Rating Curve= 0 ,0
Exp/Cntr=0.3,0.1

Type RM Length L Ch R = 1 ,25095   ,85,85,85
BEGIN DESCRIPTION:
BASSET CREEK 54.0
END DESCRIPTION:
XS GIS Cut Line= 2
      3750056.38     10634171.05      3749346.11     10634566.03
#Sta/Elev= 30
  4490.5  413.51  4555.2  412.64    4561  410.22  4589.8  409.03  4604.4  404.36
  4620.4  405.53  4626.2  399.56  4637.7  400.18  4642.2  401.08  4647.9  398.23
  4818.6  391.93  4944.5  391.73    4967  388.27  4972.7  380.95  4975.8  380.77
  4978.6  380.27  4981.8  380.77  4994.4  382.24  5001.7  386.03  5010.4   385.8
  5032.1  392.18  5043.3  391.93  5102.9  393.61  5150.4     395  5178.5  397.04
  5194.5   400.5  5200.3  398.44  5232.1  401.47  5265.5  406.98  5303.2  409.36
#Mann= 7 ,-1 , 0
  4490.5     .12       0  4637.7     .05       0  4975.8     .04       0
  4981.8     .05       0  5043.3     .08       0  5102.9     .16       0
  5232.1     .08       0
Bank Sta=4967,5001.7
XS Rating Curve= 0 ,0
Exp/Cntr=0.3,0.1

Type RM Length L Ch R = 1 ,25010   ,183,183,183
BEGIN DESCRIPTION:
Mapping XS daae4473
END DESCRIPTION:
XS GIS Cut Line= 2
      3749986.98     10634101.58       3749306.4     10634518.26
#Sta/Elev= 30
  4473.4  404.72  4520.8  409.62  4564.1  410.35  4594.3  408.05  4658.2  397.68
  4710.4  392.53  4778.2  390.21    4897  390.02  4979.3  389.33  4986.2  380.64
  4991.7  379.74  4994.5  379.24  4997.7  379.74  5016.1  383.51  5021.9  386.51
  5025.6  386.41  5031.5  386.25  5037.4  390.84  5089.5  393.12  5174.7  402.19
  5184.3  404.98  5190.2  402.64  5205.6  407.56  5211.5  402.67  5220.7  409.85
  5226.9  412.24  5232.8  408.85  5253.4  410.54  5263.7  407.03  5271.4  407.37
#Mann= 7 ,-1 , 0
  4473.4     .12       0  4778.2     .16       0    4897     .05       0
  4991.7     .04       0  4997.7     .05       0  5025.6     .16       0
  5253.4     .15       0
Bank Sta=4979.3,5021.9
XS Rating Curve= 0 ,0
Exp/Cntr=0.3,0.1

Type RM Length L Ch R = 1 ,24827   ,124,124,124
BEGIN DESCRIPTION:
Mapping XS c0c0197e
END DESCRIPTION:
XS GIS Cut Line= 3
      3749561.88     10633682.87      3749436.01     10634190.69
      3749328.16     10634466.78
#Sta/Elev= 30
  4422.8  410.06  4474.5  405.36  4532.2   399.6  4537.3  398.03    4615  391.93
  4697.7  389.12  4800.3   388.8  4873.6  389.59    4894   378.4  4904.3  383.41
  4909.8  389.03    4915  387.95  4924.9  389.87  4956.2  388.66  4966.9  387.96
  4974.8  384.19  4980.2  384.54  4988.4  379.52  5001.7  376.75  5004.4  376.25
  5007.7  376.75    5010  380.48  5020.6  384.83  5034.5  389.21    5059  388.86
  5095.8  391.66  5143.1  396.83    5173  402.45  5192.1  402.77  5242.4   410.3
#Mann= 5 ,-1 , 0
  4422.8     .16       0  4474.5     .05       0  4800.3     .16       0
  5001.7     .07       0  5007.7     .16       0
Bank Sta=4980.2,5020.6
XS Rating Curve= 0 ,0
Exp/Cntr=0.3,0.1

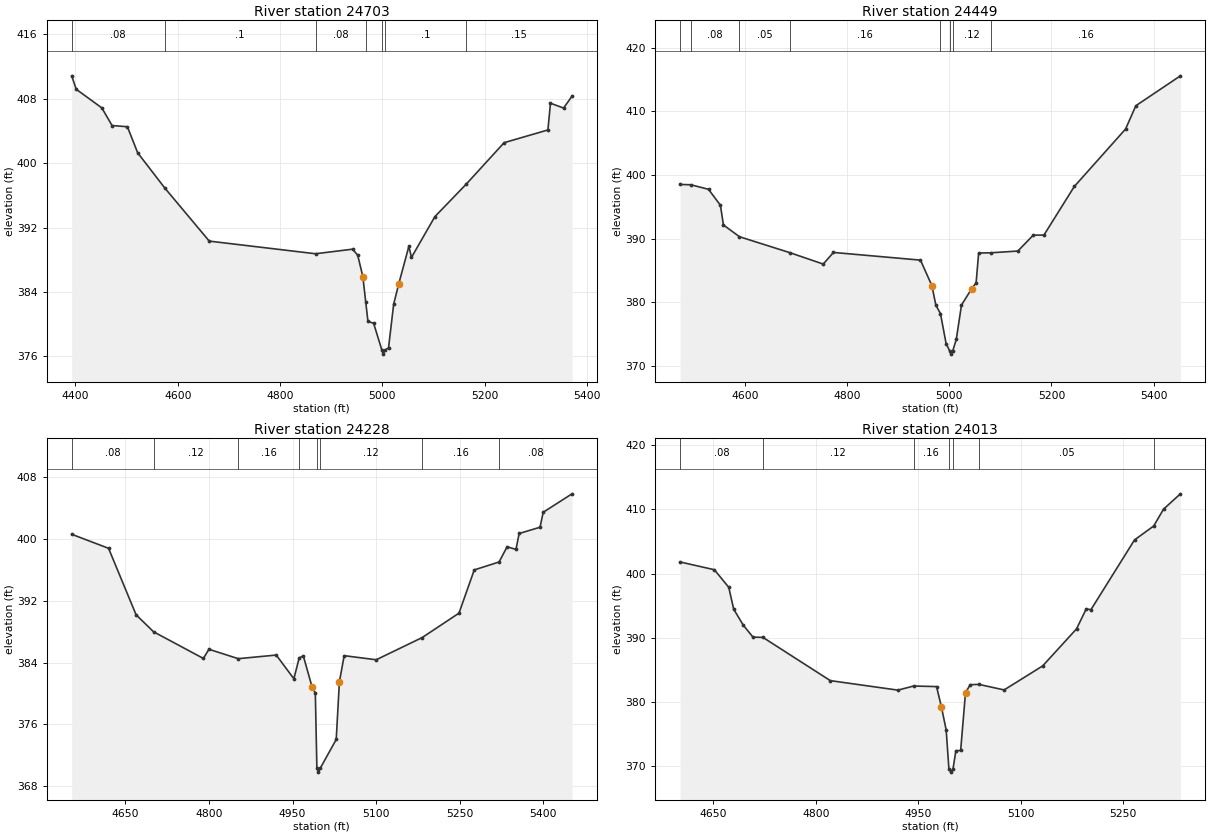
Type RM Length L Ch R = 1 ,24703   ,254,254,254
BEGIN DESCRIPTION:
Mapping XS 41f55771
END DESCRIPTION:
XS GIS Cut Line= 3
      3749310.14     10633561.31      3749323.16     10634147.29
      3749279.91     10634536.57
#Sta/Elev= 30
  4392.7  410.83  4401.6  409.16  4451.6  406.85  4471.6  404.66  4501.6  404.51
  4521.6  401.28  4574.7   396.9  4661.6  390.31  4869.3  388.74  4941.7  389.31
  4951.7  388.56  4961.7  385.91  4967.4  382.74  4971.7  380.35  4982.8  380.11
  4998.9  376.78  5001.6  376.28  5004.9  376.78  5011.9  377.05    5022  382.49
    5032  385.03  5051.7  389.67  5056.7  388.28  5102.5  393.35  5163.9  397.39
  5237.8  402.53  5323.4  404.11  5328.4  407.43    5354  406.83  5370.5   408.3
#Mann= 7 ,-1 , 0
  4392.7     .08       0  4574.7      .1       0  4869.3     .08       0
  4967.4      .1       0  4998.9     .07       0  5004.9      .1       0
  5163.9     .15       0
Bank Sta=4961.7,5032
XS Rating Curve= 0 ,0
Exp/Cntr=0.3,0.1

Type RM Length L Ch R = 1 ,24449   ,221,221,221
BEGIN DESCRIPTION:
BASSET CREEK 53.0
END DESCRIPTION:
XS GIS Cut Line= 4
      3749177.46     10633571.86      3749086.92     10633625.59
      3749101.81     10634012.74      3749062.89     10634497.05
#Sta/Elev= 30
  4473.6   398.5  4494.5  398.45  4529.2  397.74  4552.5  395.23  4558.4  392.13
  4589.8  390.28  4688.1  387.78  4753.6  385.98  4773.6  387.81  4943.8   386.6
  4966.3  382.56  4973.8  379.53  4982.9   378.2  4993.9  373.49  5000.9  372.32
  5003.6  371.82  5006.9  372.32  5013.9  374.16    5024  379.53    5044  382.12
  5052.6  383.01  5057.6  387.72    5081  387.75  5134.3  388.03  5164.4  390.53
  5185.3  390.54  5244.7  398.18    5345  407.22  5365.1  410.88  5452.2  415.58
#Mann= 8 ,-1 , 0
  4473.6      .1       0  4494.5     .08       0  4589.8     .05       0
  4688.1     .16       0  4982.9     .12       0  5000.9     .07       0
  5006.9     .12       0    5081     .16       0
Bank Sta=4966.3,5044
XS Rating Curve= 0 ,0
Exp/Cntr=0.3,0.1

Type RM Length L Ch R = 1 ,24228   ,215,215,215
BEGIN DESCRIPTION:
Mapping XS b8e6a895
END DESCRIPTION:
XS GIS Cut Line= 5
      3749161.65     10633468.75      3749049.73     10633587.39
      3749043.39     10633644.44      3749023.68     10633821.77
      3748776.44     10634255.52
#Sta/Elev= 30
  4553.4  400.64  4619.6  398.82    4669  390.21  4700.3  388.01  4789.8  384.55
  4799.8  385.74  4852.4  384.52  4920.6  384.99  4952.3  381.92  4961.8  384.61
  4969.2  384.89    4985  380.84  4990.8  380.08  4993.6  370.32  4996.3  369.82
  4999.6  370.32  5028.3  374.05    5034  381.51  5042.6  384.91  5100.1  384.38
  5182.7  387.26  5248.7  390.42  5276.1  396.02  5320.7  397.05  5335.1  399.02
    5351  398.68  5356.7  400.74  5394.2  401.55  5399.9  403.49  5451.6  405.88
#Mann= 8 ,-1 , 0
  4553.4     .08       0  4700.3     .12       0  4852.4     .16       0
  4961.8     .12       0  4993.6     .07       0  4999.6     .12       0
  5182.7     .16       0  5320.7     .08       0
Bank Sta=4985,5034
XS Rating Curve= 0 ,0
Exp/Cntr=0.3,0.1

Type RM Length L Ch R = 1 ,24013   ,349,349,349
BEGIN DESCRIPTION:
BASSET CREEK 52.0
END DESCRIPTION:
XS GIS Cut Line= 2
      3749150.79     10633420.37       3748624.5     10633930.15
#Sta/Elev= 30
  4601.2  401.82  4651.4  400.61  4672.5  397.87  4679.7  394.47  4693.8  391.97
    4708  390.11  4722.6  390.07  4821.2  383.34  4920.2  381.86  4943.3   382.5
  4976.8  382.41  4983.8  379.31  4990.9  375.66  4994.9  369.59  4997.7  369.09
  5000.9  369.59  5005.1  372.42  5012.1  372.46  5019.2  381.48  5026.2  382.71
  5038.9  382.75  5075.8  381.89  5132.2  385.63  5181.8   391.4    5196  394.51
  5202.9  394.39  5266.7  405.25  5294.8  407.42  5309.2  410.04  5333.9  412.43
#Mann= 7 ,-1 , 0
  4601.2     .08       0  4722.6     .12       0  4943.3     .16       0
  4994.9     .07       0  5000.9     .16       0  5038.9     .05       0
  5294.8     .08       0
Bank Sta=4983.8,5019.2
XS Rating Curve= 0 ,0
Exp/Cntr=0.3,0.1