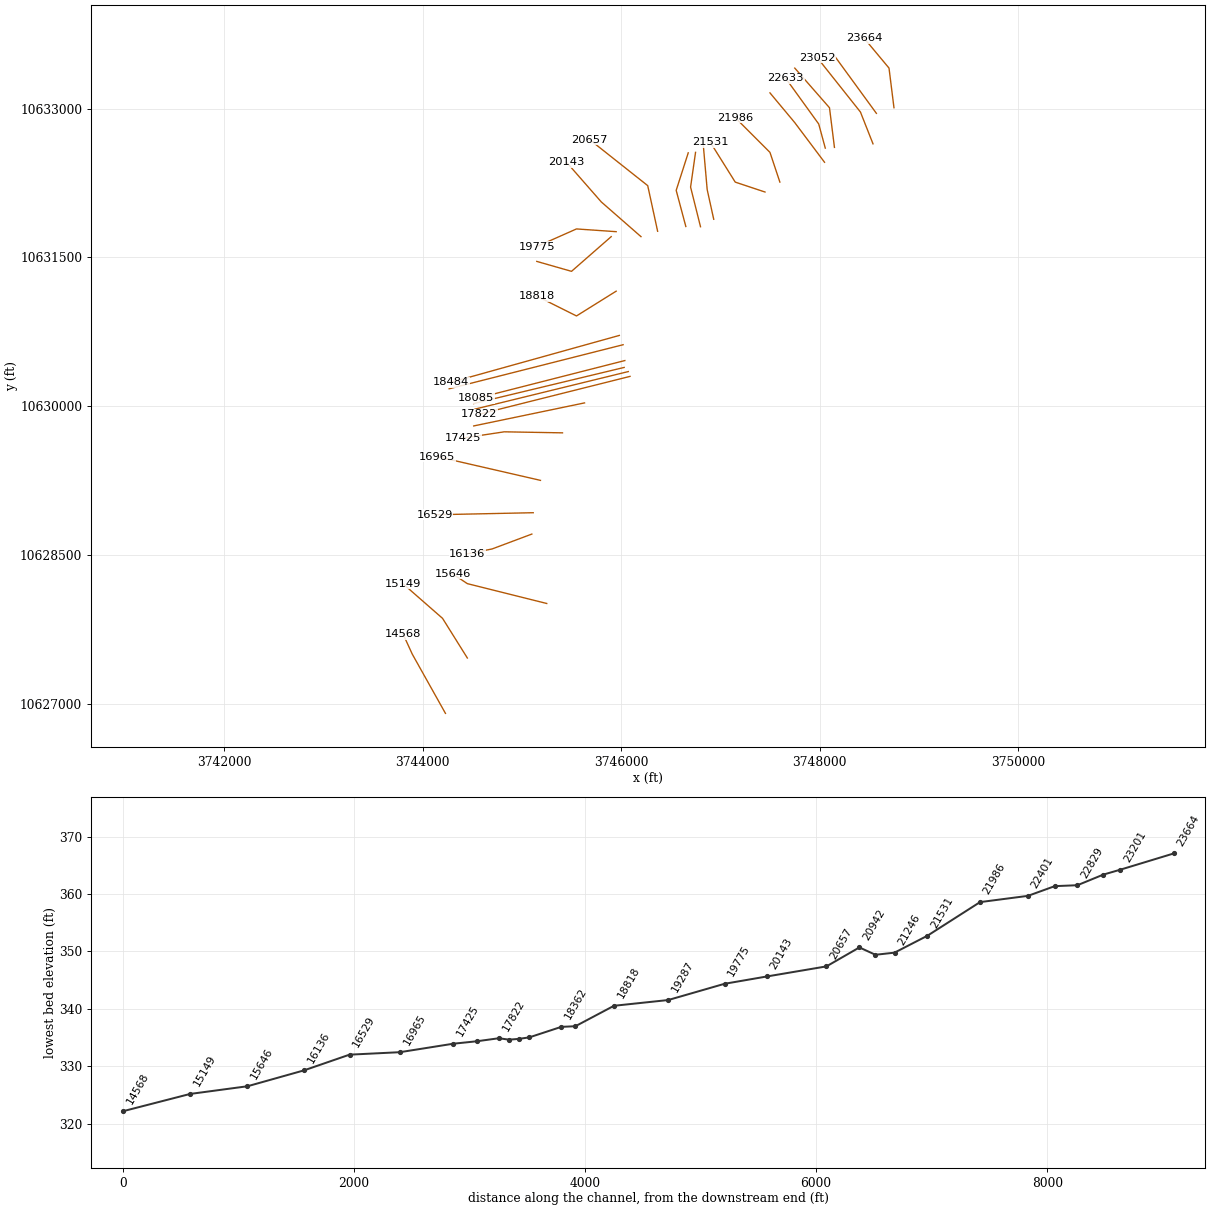
HEC-RAS study BASSET CREEK.prj: BASSET CREEK Base Level Engineering

--- BASSET CREEK.g01 (geometry) --- (continued)

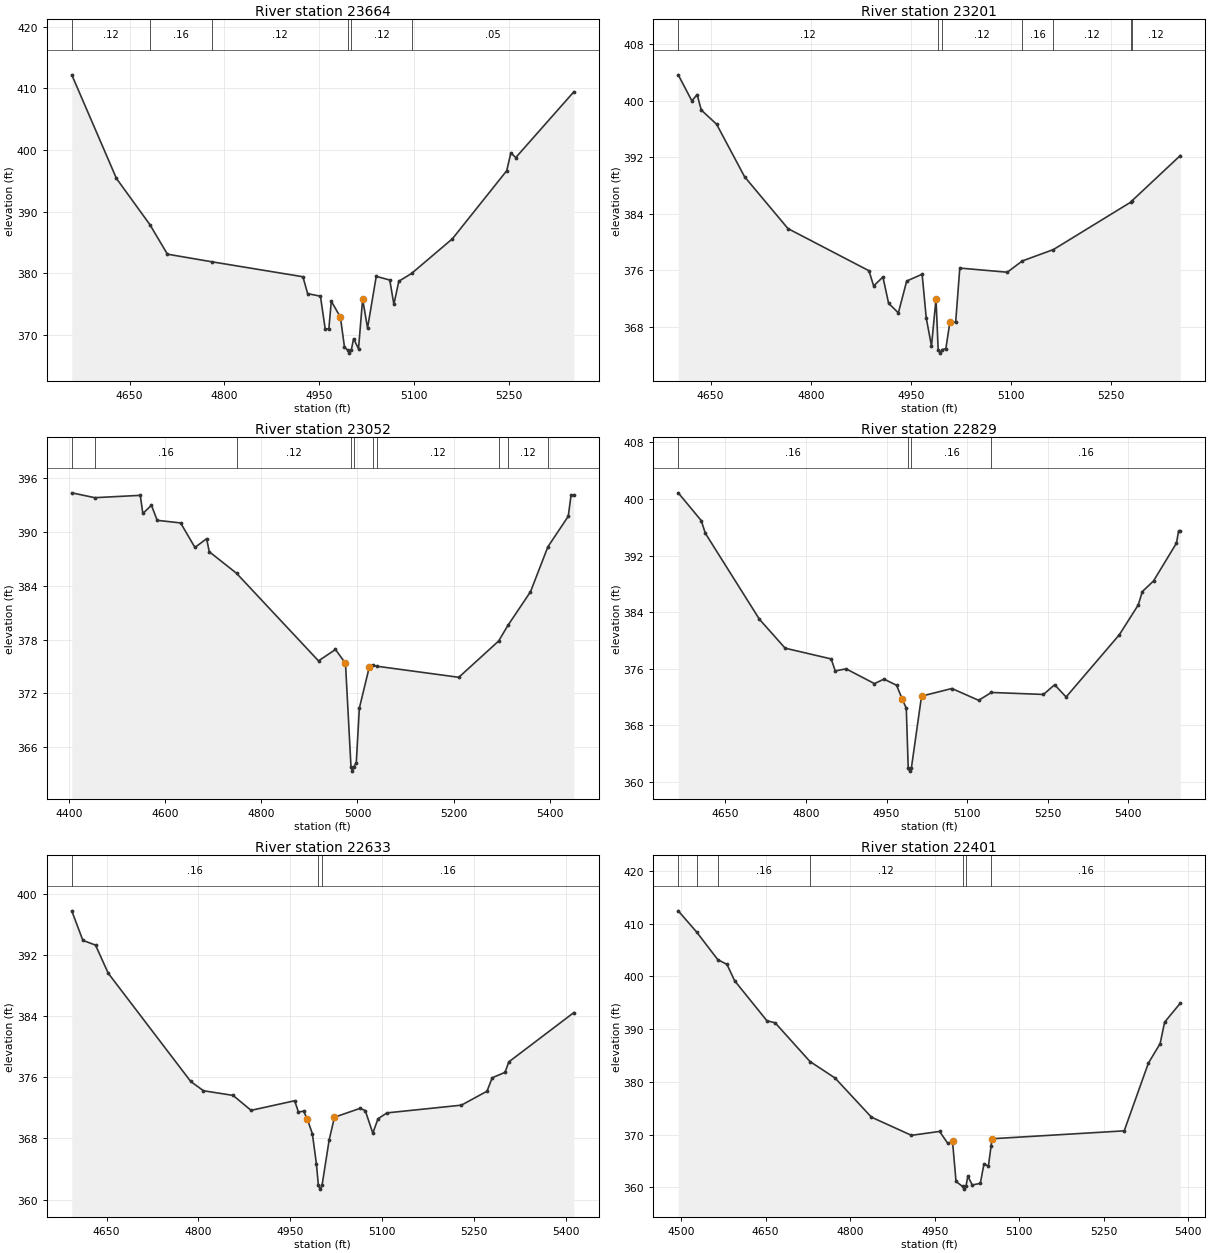
Type RM Length L Ch R = 1 ,23664   ,463,463,463
BEGIN DESCRIPTION:
BASSET CREEK 51.0
END DESCRIPTION:
XS GIS Cut Line= 3
      3748749.61     10633010.15      3748699.61     10633410.19
      3748449.58     10633710.22
#Sta/Elev= 30
  4558.6  412.17  4629.2  395.38    4682   387.9  4709.8   383.1  4780.4  381.86
    4924  379.44  4931.5   376.7  4951.7  376.29  4959.2     371    4965     371
  4968.9  375.47  4983.2  372.91  4989.7  368.05  4994.5  367.56  4997.3  367.06
  5000.5  367.56  5004.1   369.4  5011.9  367.77  5018.4  375.81  5026.2  371.13
  5039.9   379.5  5061.3  378.91  5067.8  374.97  5075.6  378.71  5095.7  379.97
  5160.3  385.59  5246.2  396.63  5252.7  399.51  5260.5  398.76  5352.3  409.42
#Mann= 6 ,-1 , 0
  4558.6     .12       0    4682     .16       0  4780.4     .12       0
  4994.5     .07       0  5000.5     .12       0  5095.7     .05       0
Bank Sta=4983.2,5018.4
XS Rating Curve= 0 ,0
Exp/Cntr=0.3,0.1

Type RM Length L Ch R = 1 ,23201   ,149,149,149
BEGIN DESCRIPTION:
BASSET CREEK 50.0
END DESCRIPTION:
XS GIS Cut Line= 2
      3748572.31     10632953.69      3748129.61     10633561.32
#Sta/Elev= 30
  4601.5  403.69  4621.9     400  4629.8  400.89    4636   398.7    4659  396.68
  4700.9  389.23  4765.8  381.89  4887.1  375.91  4894.1  373.76    4908  375.02
  4916.5   371.3  4931.1  369.94  4943.6  374.45  4966.7  375.42  4972.9  369.19
  4980.7  365.26  4987.5  371.93  4990.7  364.73  4993.5  364.23  4996.7  364.73
  5002.2  364.86  5008.4  368.69  5016.9  368.59  5023.1  376.29  5094.2   375.7
  5116.7   377.3  5163.4  378.92    5279  385.63  5281.4  385.87  5353.3  392.25
#Mann= 7 ,-1 , 0
  4601.5     .12       0  4990.7     .07       0  4996.7     .12       0
  5116.7     .16       0  5163.4     .12       0    5279     .16       0
  5281.4     .12       0
Bank Sta=4987.5,5008.4
XS Rating Curve= 0 ,0
Exp/Cntr=0.3,0.1

Type RM Length L Ch R = 1 ,23052   ,223,223,223
BEGIN DESCRIPTION:
Mapping XS 39861204
END DESCRIPTION:
XS GIS Cut Line= 3
      3748538.19     10632646.15      3748411.45     10632967.34
       3747977.4     10633514.24
#Sta/Elev= 30
  4406.2  394.33  4453.9  393.79  4548.6  394.05  4553.9  392.03  4571.8  392.95
  4583.7  391.27  4632.4  390.98  4662.2  388.25  4686.5  389.23  4691.9  387.78
  4748.6  385.38    4919  375.63  4954.3   376.9  4975.1  375.35  4986.5  363.86
  4989.3  363.36  4992.5  363.86  4997.5  364.28  5003.9  370.37  5024.7  374.97
  5032.8  375.13    5041  375.03  5210.6   373.8  5293.4  377.84  5312.7  379.58
  5359.6  383.32  5395.8  388.33  5438.1  391.72  5443.9  394.08  5449.7  394.08
#Mann= 10 ,-1 , 0
  4406.2     .12       0  4453.9     .16       0  4748.6     .12       0
  4986.5     .07       0  4992.5     .12       0  5032.8     .16       0
    5041     .12       0  5293.4     .16       0  5312.7     .12       0
  5395.8     .16       0
Bank Sta=4975.1,5024.7
XS Rating Curve= 0 ,0
Exp/Cntr=0.3,0.1

Type RM Length L Ch R = 1 ,22829   ,196,196,196
BEGIN DESCRIPTION:
BASSET CREEK 49.0
END DESCRIPTION:
XS GIS Cut Line= 3
      3748149.61     10632610.19      3748099.61     10633010.19
      3747749.62     10633410.18
#Sta/Elev= 30
  4562.3  400.86  4605.1  396.94  4612.7  395.15  4713.5  382.98  4761.3   378.9
    4847  377.38  4854.6  375.68  4874.7  375.98  4927.6  373.89  4945.3  374.53
  4968.7  373.66  4979.2  371.72  4986.8   370.4  4990.4  362.02  4993.2  361.52
  4996.4  362.02  5015.2  372.12  5071.7   373.2  5121.5  371.53  5145.2  372.64
  5242.1  372.36    5263  373.73  5284.3     372  5383.5  380.81  5418.6  385.01
  5426.2   386.9  5447.1  388.41  5489.8  393.76  5493.6  395.44  5496.9  395.44
#Mann= 4 ,-1 , 0
  4562.3     .16       0  4990.4     .07       0  4996.4     .16       0
  5145.2     .16       0
Bank Sta=4979.2,5015.2
XS Rating Curve= 0 ,0
Exp/Cntr=0.3,0.1

Type RM Length L Ch R = 1 ,22633   ,232,232,232
BEGIN DESCRIPTION:
Mapping XS 7ab7f2c3
END DESCRIPTION:
XS GIS Cut Line= 3
      3748057.29     10632602.74      3747991.31     10632845.81
      3747658.86      10633306.4
#Sta/Elev= 30
  4593.2  397.82  4611.3  393.95    4632  393.33  4652.7  389.65  4787.4  375.47
  4808.2  374.25  4856.6  373.64    4886  371.68  4957.2  372.94  4963.3  371.47
  4971.9  371.57    4978  370.49  4986.1  368.62  4992.7  364.68  4995.9  361.86
  4998.7  361.36  5001.9  361.86  5013.6  367.84  5022.2  370.78  5063.9  371.94
  5072.5  371.65  5084.8  368.69  5093.3  370.58    5108  371.35  5229.5  372.36
  5271.3  374.19  5279.8  375.95  5300.7  376.66  5306.9  378.03  5413.1  384.49
#Mann= 3 ,-1 , 0
  4593.2     .16       0  4995.9     .07       0  5001.9     .16       0
Bank Sta=4978,5022.2
XS Rating Curve= 0 ,0
Exp/Cntr=0.3,0.1

Type RM Length L Ch R = 1 ,22401   ,415,415,415
BEGIN DESCRIPTION:
BASSET CREEK 48.0
END DESCRIPTION:
XS GIS Cut Line= 3
      3748049.62     10632460.17      3747749.61     10632860.19
      3747499.63     10633160.16
#Sta/Elev= 30
  4495.1  412.43  4527.6  408.43  4565.2  403.18  4581.6  402.27  4595.1  399.18
  4652.4  391.59    4667   391.2  4728.8  383.86  4773.2  380.74  4837.8  373.31
  4908.7  369.87  4958.7  370.61  4973.2  368.34  4981.6  368.71  4987.8  361.14
  4999.3  360.17    5002  359.67  5005.3  360.17  5008.8  362.12  5016.6  360.46
  5030.9  360.76  5037.4  364.48  5045.2  364.02  5049.9  367.78  5051.7  369.22
  5286.1  370.72    5329  383.57  5349.8  387.25  5357.7  391.31  5385.6  394.93
#Mann= 7 ,-1 , 0
  4495.1     .16       0  4527.6     .12       0  4565.2     .16       0
  4728.8     .12       0  4999.3     .07       0  5005.3     .12       0
  5049.9     .16       0
Bank Sta=4981.6,5051.7
XS Rating Curve= 0 ,0
Exp/Cntr=0.3,0.1

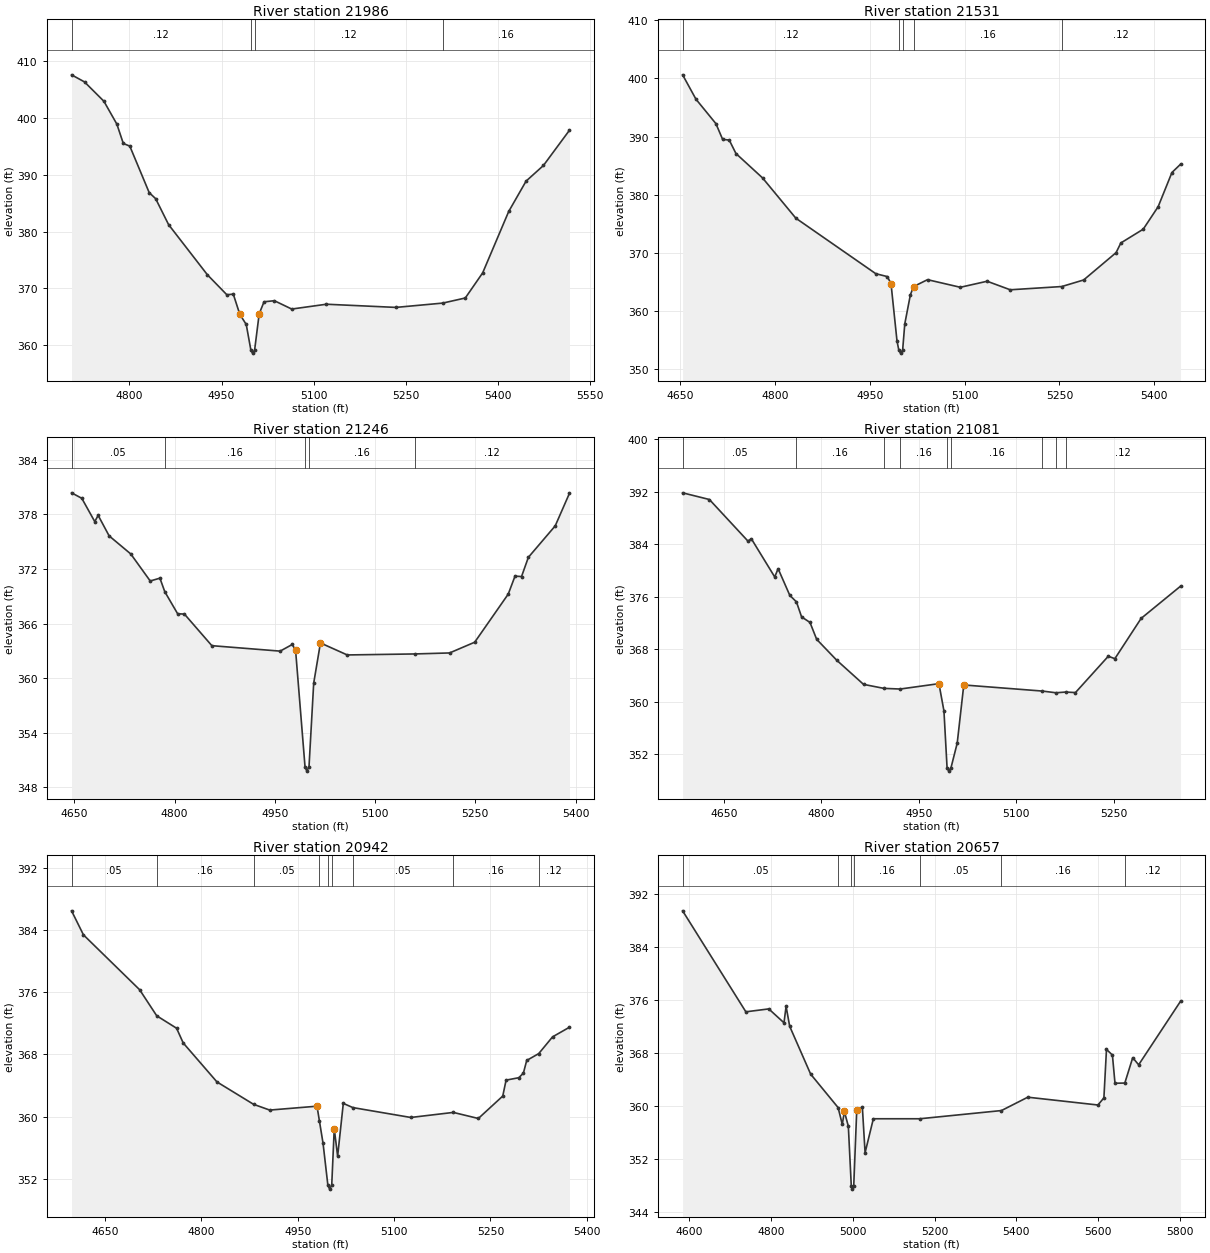
Type RM Length L Ch R = 1 ,21986   ,455,455,455
BEGIN DESCRIPTION:
BASSET CREEK 47.0
END DESCRIPTION:
XS GIS Cut Line= 3
      3747599.61     10632260.17      3747499.61     10632560.19
      3747149.62     10632910.17
#Sta/Elev= 30
  4705.7  407.64  4726.8  406.39  4758.4  402.98  4779.5  398.95    4790  395.54
  4800.6  395.07  4832.2  386.87  4842.7  385.81  4863.8  381.23  4927.1  372.38
  4958.7  368.87  4969.2  368.98  4979.8  365.42  4990.3  363.63  4997.9  359.08
  5000.6  358.58  5003.9  359.08  5011.4  365.52  5019.3  367.63  5036.1  367.82
  5064.4  366.35  5120.9   367.2  5234.1  366.64  5310.4   367.4  5347.2   368.3
  5375.5  372.73  5417.9  383.55  5446.2   388.9  5474.5  391.66  5516.9  397.87
#Mann= 4 ,-1 , 0
  4705.7     .12       0  4997.9     .07       0  5003.9     .12       0
  5310.4     .16       0
Bank Sta=4979.8,5011.4
XS Rating Curve= 0 ,0
Exp/Cntr=0.3,0.1

Type RM Length L Ch R = 1 ,21531   ,285,285,285
BEGIN DESCRIPTION:
BASSET CREEK 46.0
END DESCRIPTION:
XS GIS Cut Line= 3
      3747449.64     10632160.18      3747149.61     10632260.19
      3746899.59     10632660.22
#Sta/Elev= 30
  4653.7  400.62  4674.8  396.43  4706.4  392.22    4717  389.52  4727.5  389.39
  4738.1  387.08  4780.2  382.88  4832.9  375.95  4959.4   366.4  4977.6   365.9
  4983.5  364.71    4993  354.82  4995.9  353.23  4998.6  352.73  5001.9  353.23
  5005.3  357.76  5014.2  362.78  5019.3  364.19  5041.3  365.37  5093.2  364.06
  5135.6   365.1  5172.2  363.63  5253.8  364.19  5288.4  365.32  5339.7  370.02
  5347.3  371.69  5382.7  374.06  5406.3  377.93  5428.1  383.81  5441.7  385.23
#Mann= 5 ,-1 , 0
  4653.7     .12       0  4995.9     .07       0  5001.9     .12       0
  5019.3     .16       0  5253.8     .12       0
Bank Sta=4983.5,5019.3
XS Rating Curve= 0 ,0
Exp/Cntr=0.3,0.1

Type RM Length L Ch R = 1 ,21246   ,165,165,165
BEGIN DESCRIPTION:
Mapping XS 1f3d6573
END DESCRIPTION:
XS GIS Cut Line= 3
      3746932.96     10631885.27      3746866.99     10632183.86
       3746828.8     10632621.41
#Sta/Elev= 30
  4645.8  380.37  4661.1  379.77  4680.5  377.21  4685.6  377.89    4702  375.64
  4734.4  373.65  4763.5  370.68    4778  370.99  4785.3   369.5  4804.5  367.08
  4814.7  367.04  4855.7  363.57  4957.9  362.97    4976   363.7    4981  363.07
  4995.1  350.28  4997.8  349.78  5001.1  350.28  5008.1  359.45  5018.2  363.87
  5058.3  362.55    5159  362.66  5211.4  362.77    5249  363.95  5299.2  369.24
  5309.3  371.21  5319.1  371.17  5329.3  373.28  5369.5  376.74  5390.8  380.32
#Mann= 5 ,-1 , 0
  4645.8     .05       0  4785.3     .16       0  4995.1     .07       0
  5001.1     .16       0    5159     .12       0
Bank Sta=4981,5018.2
XS Rating Curve= 0 ,0
Exp/Cntr=0.3,0.1

Type RM Length L Ch R = 1 ,21081   ,139,139,139
BEGIN DESCRIPTION:
BASSET CREEK 45.0
END DESCRIPTION:
XS GIS Cut Line= 3
      3746799.61     10631810.17      3746699.61     10632210.19
      3746749.61     10632560.21
#Sta/Elev= 30
  4586.6  391.85  4627.8  390.83  4687.1  384.49  4692.3  384.85  4728.3  379.02
  4733.5  380.28  4751.5  376.21  4761.7  375.22  4769.6  372.93  4782.5  372.09
  4792.8  369.51  4823.7  366.32  4864.9  362.64  4896.2  362.03  4921.3  361.93
  4980.9  362.75  4988.6  358.58  4993.4  349.91  4996.1  349.41  4999.4  349.91
    5009  353.68  5019.1  362.55  5139.9  361.62  5160.8  361.36    5176  361.47
  5190.9  361.39  5241.4  366.93  5251.5  366.56  5291.9   372.7  5352.5  377.61
#Mann= 9 ,-1 , 0
  4586.6     .05       0  4761.7     .16       0  4896.2     .05       0
  4921.3     .16       0  4993.4     .07       0  4999.4     .16       0
  5139.9     .05       0  5160.8     .16       0    5176     .12       0
Bank Sta=4980.9,5019.1
XS Rating Curve= 0 ,0
Exp/Cntr=0.3,0.1

Type RM Length L Ch R = 1 ,20942   ,285,285,285
BEGIN DESCRIPTION:
Mapping XS 12cbe93d
END DESCRIPTION:
XS GIS Cut Line= 3
      3746651.72     10631812.31      3746554.49     10632176.92
      3746675.98     10632555.24
#Sta/Elev= 30
  4598.2  386.46  4616.7  383.37  4704.1  376.32  4730.7  372.97  4761.6  371.37
  4771.9  369.48  4824.4  364.47  4881.4  361.59  4906.5  360.85  4980.1  361.35
  4983.8  359.47  4989.5  356.58    4997  351.19  4999.7  350.69    5003  351.19
  5006.9  358.45  5012.2  354.93    5021  361.71  5035.9  361.17    5126   359.9
  5192.2  360.55  5231.1  359.77  5269.1  362.65  5274.3   364.7  5294.1  365.01
  5301.2   365.6  5306.4  367.23  5325.1  368.11  5346.6  370.26  5372.9   371.5
#Mann= 9 ,-1 , 0
  4598.2     .05       0  4730.7     .16       0  4881.4     .05       0
  4983.8     .16       0    4997     .07       0    5003     .16       0
  5035.9     .05       0  5192.2     .16       0  5325.1     .12       0
Bank Sta=4980.1,5006.9
XS Rating Curve= 0 ,0
Exp/Cntr=0.3,0.1

Type RM Length L Ch R = 1 ,20657   ,514,514,514
BEGIN DESCRIPTION:
BASSET CREEK 44.0
END DESCRIPTION:
XS GIS Cut Line= 3
      3746367.43     10631764.51      3746267.61     10632224.54
      3745683.16     10632687.77
#Sta/Elev= 30
  4584.4  389.47  4738.9   374.2  4794.9  374.64  4832.1  372.54  4837.2  375.03
    4846  372.01  4897.2  364.78  4964.3  359.72  4974.5  357.18  4979.6  359.13
  4989.3   356.9  4996.5  347.89  4999.3  347.39  5002.5  347.89  5009.8  359.29
  5023.6  359.75  5030.2  352.89  5050.4  358.03  5163.9  358.03  5363.4  359.27
  5427.7  361.29  5599.2  360.11  5613.7  361.19    5620  368.52  5634.5  367.66
  5640.8   363.4  5664.8  363.43  5684.1  367.26  5698.6  366.19  5800.9  375.79
#Mann= 7 ,-1 , 0
  4584.4     .05       0  4964.3     .16       0  4996.5     .07       0
  5002.5     .16       0  5163.9     .05       0  5363.4     .16       0
  5664.8     .12       0
Bank Sta=4979.6,5009.8
XS Rating Curve= 0 ,0
Exp/Cntr=0.3,0.1

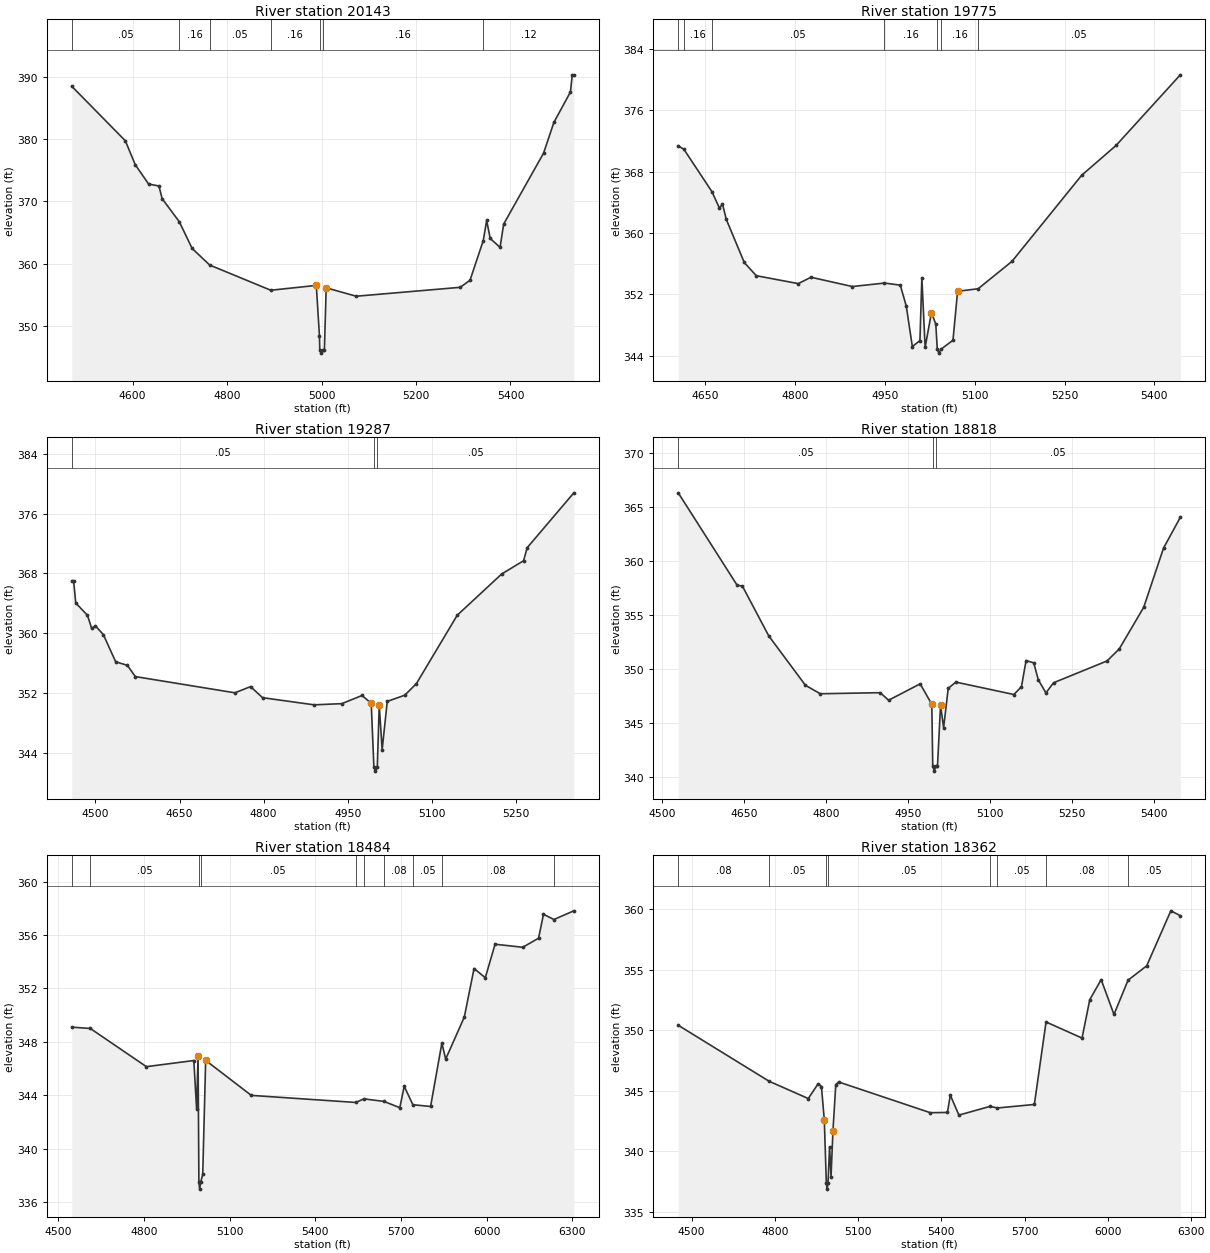
Type RM Length L Ch R = 1 ,20143   ,368,368,368
BEGIN DESCRIPTION:
BASSET CREEK 43.0
END DESCRIPTION:
XS GIS Cut Line= 3
      3746199.64     10631710.16      3745799.61     10632060.19
      3745449.58     10632460.22
#Sta/Elev= 30
  4471.1   388.5  4584.6  379.74  4605.4  375.92  4633.9  372.79  4655.7  372.49
  4662.4  370.46  4698.8  366.74    4726  362.45  4763.1  359.79  4892.5  355.74
  4988.9  356.52  4995.5  348.43  4996.3  346.14  4999.1  345.64  5002.3  346.14
    5006  346.14  5009.8  356.13  5073.4  354.78  5293.6  356.21  5314.4  357.35
  5342.4  363.72  5349.6  366.95  5357.1  364.06    5378  362.62  5385.6  366.37
  5470.1  377.76  5491.9  382.69    5527  387.59  5530.8  390.34  5534.2  390.34
#Mann= 7 ,-1 , 0
  4471.1     .05       0  4698.8     .16       0  4763.1     .05       0
  4892.5     .16       0  4996.3     .07       0  5002.3     .16       0
  5342.4     .12       0
Bank Sta=4988.9,5009.8
XS Rating Curve= 0 ,0
Exp/Cntr=0.3,0.1

Type RM Length L Ch R = 1 ,19775   ,488,488,488
BEGIN DESCRIPTION:
BASSET CREEK 42.0
END DESCRIPTION:
XS GIS Cut Line= 3
      3745949.64     10631760.19      3745549.61     10631787.81
      3745149.65     10631610.21
#Sta/Elev= 30
  4604.7  371.35  4614.2  370.89    4661  365.38  4673.6  363.22  4678.6  363.79
  4684.9  361.78    4715  356.16    4735  354.44  4805.2  353.41  4826.4  354.24
  4895.4  353.03  4949.2  353.48  4975.6  353.21  4985.6  350.48  4995.7  345.22
  5008.4  345.99  5011.6  354.17  5017.1   345.1  5027.6  349.64  5034.9  348.13
  5037.4  344.86  5040.1  344.36  5043.4  344.86  5063.6  346.04  5071.3  352.41
  5105.6  352.74  5162.2  356.31  5278.5  367.51  5335.9  371.39  5443.3  380.59
#Mann= 7 ,-1 , 0
  4604.7     .05       0  4614.2     .16       0    4661     .05       0
  4949.2     .16       0  5037.4     .07       0  5043.4     .16       0
  5105.6     .05       0
Bank Sta=5027.6,5071.3
XS Rating Curve= 0 ,0
Exp/Cntr=0.3,0.1

Type RM Length L Ch R = 1 ,19287   ,469,469,469
BEGIN DESCRIPTION:
BASSET CREEK 41.0
END DESCRIPTION:
XS GIS Cut Line= 3
      3745899.57     10631710.16      3745499.61     10631360.19
      3745149.58      10631460.2
#Sta/Elev= 30
  4457.8  367.01  4461.1  367.01  4464.9  364.03  4485.8  362.38  4493.3  360.62
    4500  360.97  4514.2  359.79  4536.1  356.16  4556.9  355.69  4571.2  354.18
  4748.7  352.01  4776.7  352.84    4798  351.36  4890.1   350.4  4939.4  350.56
  4975.5  351.65  4991.9  350.62  4996.7  342.03  4999.4  341.53  5002.7  342.03
  5006.2  350.35  5011.4  344.41  5020.5  350.86  5051.7  351.69  5072.5  353.24
  5145.3  362.39  5224.6  367.91  5263.6  369.68  5270.1  371.43  5353.3  378.77
#Mann= 3 ,-1 , 0
  4457.8     .05       0  4996.7     .03       0  5002.7     .05       0
Bank Sta=4991.9,5006.2
XS Rating Curve= 0 ,0
Exp/Cntr=0.3,0.1

Type RM Length L Ch R = 1 ,18818   ,334,334,334
BEGIN DESCRIPTION:
BASSET CREEK 40.0
END DESCRIPTION:
XS GIS Cut Line= 3
      3745949.63      10631160.2      3745549.61     10630910.19
      3745149.64     10631110.17
#Sta/Elev= 30
  4529.6  366.32  4637.5  357.75    4647  357.68  4695.3  353.06  4762.5  348.48
  4789.6   347.7  4899.3   347.8  4914.6   347.1  4972.4  348.62  4993.7  346.72
  4995.4  341.03  4998.1  340.53  5001.4  341.03  5004.1  341.03  5009.7  346.63
  5015.3  344.56  5023.7   348.2  5037.7  348.78  5143.9  347.63  5157.8  348.36
  5166.2  350.77  5180.2  350.57  5188.6  348.99  5202.6  347.78  5216.5  348.72
  5314.4  350.74  5336.7  351.85  5381.5  355.71  5417.8   361.2  5448.5  364.05
#Mann= 3 ,-1 , 0
  4529.6     .05       0  4995.4     .03       0  5001.4     .05       0
Bank Sta=4993.7,5009.7
XS Rating Curve= 0 ,0
Exp/Cntr=0.3,0.1

Type RM Length L Ch R = 1 ,18484   ,122,122,122
BEGIN DESCRIPTION:
Mapping XS 72c2ebeb
END DESCRIPTION:
XS GIS Cut Line= 2
      3745981.54     10630713.77      3744287.11     10630241.55
#Sta/Elev= 30
  4546.7   349.1  4611.7     349  4808.2  346.14  4974.3   346.6    4984  342.99
  4989.2  346.93  4992.1  337.47  4994.8  336.97  4998.1  337.47  5005.5  338.07
  5015.8  346.61  5175.7  343.99  5541.9  343.46  5570.1  343.73  5640.1  343.54
    5696  343.07  5711.4  344.67  5741.7  343.29  5803.8  343.16  5843.3   347.9
  5856.7  346.71  5921.9  349.85  5956.1  353.49  5995.5   352.8  6029.7  355.31
  6126.6  355.08  6182.1  355.76  6199.3  357.55  6235.9  357.16  6305.7  357.81
#Mann= 10 ,-1 , 0
  4546.7     .08       0  4611.7     .05       0  4992.1     .03       0
  4998.1     .05       0  5541.9     .16       0  5570.1     .05       0
  5640.1     .08       0  5741.7     .05       0  5843.3     .08       0
  6235.9     .05       0
Bank Sta=4989.2,5015.8
XS Rating Curve= 0 ,0
Exp/Cntr=0.3,0.1

Type RM Length L Ch R = 1 ,18362   ,277,277,277
BEGIN DESCRIPTION:
BASSET CREEK 39.0
END DESCRIPTION:
XS GIS Cut Line= 2
      3746019.81     10630620.04      3744266.35      10630175.6
#Sta/Elev= 30
  4451.8  350.41  4779.1  345.78  4920.3  344.35  4956.1  345.58  4967.8  345.34
  4978.1  342.56  4985.4  337.36  4988.2  336.86  4991.4  337.36  4997.1  340.36
  5002.3  337.89  5009.1  341.66  5019.4   345.5  5029.7  345.72  5359.8  343.18
  5421.7   343.2    5432  344.63    5463  342.98  5574.8   343.7  5601.9  343.57
  5734.8  343.86    5777  350.68  5906.6  349.35  5934.6  352.53  5975.6  354.18
  6021.7   351.3  6072.5  354.14  6139.5  355.32  6226.6  359.87  6260.7  359.47
#Mann= 8 ,-1 , 0
  4451.8     .08       0  4779.1     .05       0  4985.4     .04       0
  4991.4     .05       0  5574.8     .08       0  5601.9     .05       0
    5777     .08       0  6072.5     .05       0
Bank Sta=4978.1,5009.1
XS Rating Curve= 0 ,0
Exp/Cntr=0.3,0.1

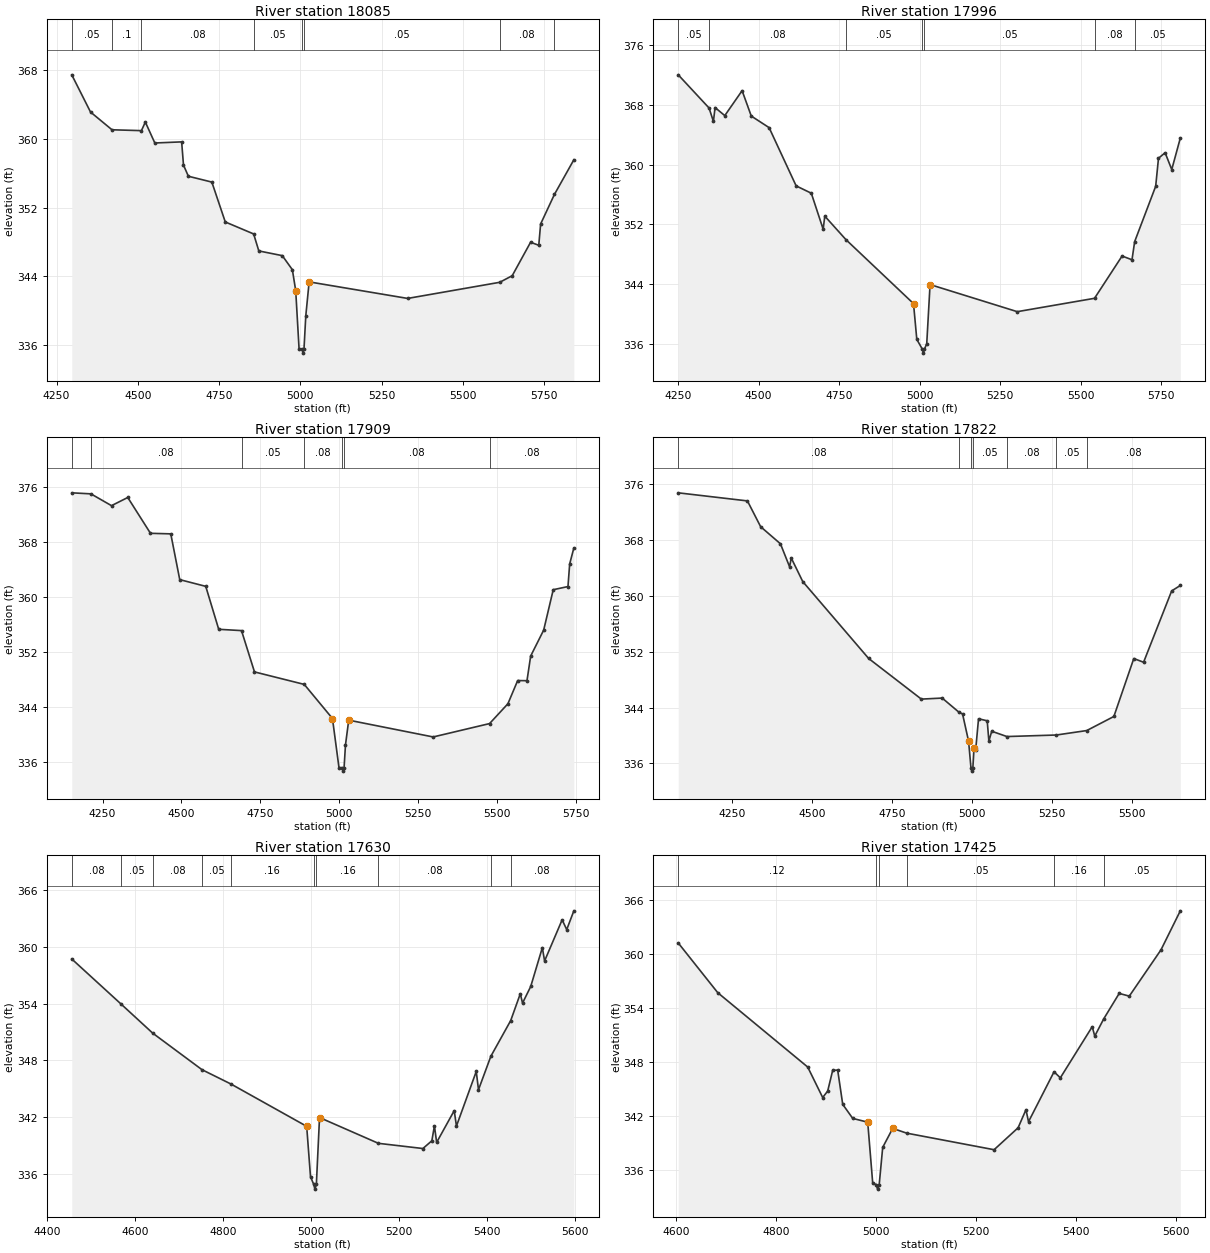
Type RM Length L Ch R = 1 ,18085   ,89,89,89
BEGIN DESCRIPTION:
Mapping XS 44f0a559
END DESCRIPTION:
XS GIS Cut Line= 2
      3746037.14     10630460.31      3744540.61     10630078.36
#Sta/Elev= 30
  4296.6  367.49  4354.3  363.15  4420.4  361.08  4510.9  360.98  4522.9  361.98
  4552.1  359.54  4634.6  359.67  4640.3  356.96  4655.3  355.66  4727.5  354.98
  4768.8  350.33  4856.1  348.93    4872  346.95  4944.2   346.4  4975.2  344.76
  4985.5  342.32  4995.8  335.55    5005  335.53  5007.8  335.03    5011  335.53
  5016.5  339.38  5026.8  343.34  5329.8  341.41    5613  343.29  5651.5  344.06
    5708  347.96  5733.2  347.61  5738.9  350.09  5781.5  353.55  5841.1  357.58
#Mann= 8 ,-1 , 0
  4296.6     .05       0  4420.4      .1       0  4510.9     .08       0
  4856.1     .05       0    5005     .04       0    5011     .05       0
    5613     .08       0  5781.5     .05       0
Bank Sta=4985.5,5026.8
XS Rating Curve= 0 ,0
Exp/Cntr=0.3,0.1

Type RM Length L Ch R = 1 ,17996   ,87,87,87
BEGIN DESCRIPTION:
Mapping XS 0d1a81bd
END DESCRIPTION:
XS GIS Cut Line= 2
      3746030.24     10630390.87       3744513.7     10630026.49
#Sta/Elev= 30
  4250.3  372.03    4346  367.59  4359.6  365.79  4364.7  367.65  4394.9  366.57
  4448.7  369.91  4477.2  366.51  4532.6  364.96  4616.6  357.16  4663.7  356.18
  4700.5  351.36  4705.6  353.11  4771.4  349.96  4981.2   341.4  4991.4  336.61
    5009  335.27  5011.8  334.77    5015  335.27  5022.3  336.05  5032.6  343.95
  5303.5  340.32  5543.5  342.11  5629.1  347.77  5659.9  347.27  5668.2   349.7
  5733.5  357.11  5742.2  360.86  5762.8   361.6  5783.4  359.35    5810  363.56
#Mann= 7 ,-1 , 0
  4250.3     .05       0    4346     .08       0  4771.4     .05       0
    5009     .04       0    5015     .05       0  5543.5     .08       0
  5668.2     .05       0
Bank Sta=4981.2,5032.6
XS Rating Curve= 0 ,0
Exp/Cntr=0.3,0.1

Type RM Length L Ch R = 1 ,17909   ,87,87,87
BEGIN DESCRIPTION:
Mapping XS 48bbfe77
END DESCRIPTION:
XS GIS Cut Line= 2
      3746071.87      10630349.2      3744526.75     10629970.73
#Sta/Elev= 30
  4152.5  375.19  4213.2  375.04  4278.4  373.32  4329.9  374.51  4401.9  369.29
  4466.2  369.21  4494.6  362.54    4577  361.56  4618.1   355.3  4690.3  355.11
  4731.4  349.09  4889.1  347.27  4978.5   342.3  4999.1  335.15  5009.3  335.13
    5012  334.63  5015.3  335.13  5019.7  338.43    5030  342.06  5297.6  339.61
  5476.3  341.56  5534.4  344.45  5565.3  347.83  5594.8  347.81  5606.5   351.4
  5647.7  355.18    5678  361.07  5724.7  361.53  5730.1  364.83  5743.3  367.15
#Mann= 7 ,-1 , 0
  4152.5     .05       0  4213.2     .08       0  4690.3     .05       0
  4889.1     .08       0  5009.3     .07       0  5015.3     .08       0
  5476.3     .08       0
Bank Sta=4978.5,5030
XS Rating Curve= 0 ,0
Exp/Cntr=0.3,0.1

Type RM Length L Ch R = 1 ,17822   ,192,192,192
BEGIN DESCRIPTION:
Mapping XS 0cae0608
END DESCRIPTION:
XS GIS Cut Line= 2
      3746089.22     10630300.59      3744568.35     10629918.63
#Sta/Elev= 30
  4081.8   374.8  4297.9  373.64  4339.2  369.94    4401  367.49  4429.6  364.19
  4434.8  365.45  4470.7  362.07  4676.5  351.04  4841.1  345.21  4906.2  345.36
  4959.6  343.29  4969.7   343.1  4988.7  339.15    4996  335.38  4998.8  334.88
    5002  335.38  5005.7  338.18  5010.8  337.96  5019.7  342.39  5046.8   342.1
    5052  339.19  5060.9   340.6  5108.4  339.84  5262.7  340.06  5357.7   340.7
  5442.4  342.72  5504.6  351.03  5535.2   350.5  5622.9  360.73  5649.9  361.51
#Mann= 7 ,-1 , 0
  4081.8     .08       0  4959.6     .05       0    4996     .03       0
    5002     .05       0  5108.4     .08       0  5262.7     .05       0
  5357.7     .08       0
Bank Sta=4988.7,5005.7
XS Rating Curve= 0 ,0
Exp/Cntr=0.3,0.1

Type RM Length L Ch R = 1 ,17630   ,205,205,205
BEGIN DESCRIPTION:
BASSET CREEK 38.0
END DESCRIPTION:
XS GIS Cut Line= 2
      3745630.88     10630033.22      3744513.71     10629800.77
#Sta/Elev= 30
  4456.7  358.72  4568.7  353.95  4640.6  350.87  4752.6     347  4818.5  345.48
  4990.6     341  4999.3  335.67  5006.6  334.85  5009.3  334.35  5012.6  334.85
  5019.8  341.93  5153.6   339.2  5254.7  338.65  5275.1  339.47  5280.9  341.05
    5286   339.3  5325.9  342.66    5331  341.03    5376  346.81  5381.1  344.88
  5409.2  348.42  5454.3   352.2  5476.1  355.04  5481.2  354.05  5499.8  355.81
  5526.2  359.92  5531.3  358.51  5571.2  362.87  5581.6  361.83  5597.8  363.82
#Mann= 10 ,-1 , 0
  4456.7     .08       0  4568.7     .05       0  4640.6     .08       0
  4752.6     .05       0  4818.5     .16       0  5006.6     .07       0
  5012.6     .16       0  5153.6     .08       0  5409.2     .05       0
  5454.3     .08       0
Bank Sta=4990.6,5019.8
XS Rating Curve= 0 ,0
Exp/Cntr=0.3,0.1

Type RM Length L Ch R = 1 ,17425   ,460,460,460
BEGIN DESCRIPTION:
BASSET CREEK 37.0
END DESCRIPTION:
XS GIS Cut Line= 3
      3745408.71     10629731.14      3744821.86     10629741.56
       3744408.7     10629679.06
#Sta/Elev= 30
  4604.6  361.28  4683.7  355.75  4863.7  347.49  4893.7   344.1  4903.7  344.82
  4913.7  347.12  4923.7  347.15  4933.8  343.34  4953.8  341.78  4983.8  341.36
  4993.8  334.59  5000.8  334.42  5003.5  333.92  5006.8  334.42  5013.8  338.56
  5033.8  340.67  5061.9  340.14  5236.7   338.3  5284.8  340.74  5300.5  342.75
  5305.6  341.41  5356.7  346.96  5369.3  346.29  5433.1  351.97  5438.2  350.93
  5456.2  352.85  5487.1  355.67  5507.3  355.37  5570.8  360.52  5609.4  364.85
#Mann= 6 ,-1 , 0
  4604.6     .12       0  5000.8     .07       0  5006.8     .12       0
  5061.9     .05       0  5356.7     .16       0  5456.2     .05       0
Bank Sta=4983.8,5033.8
XS Rating Curve= 0 ,0
Exp/Cntr=0.3,0.1

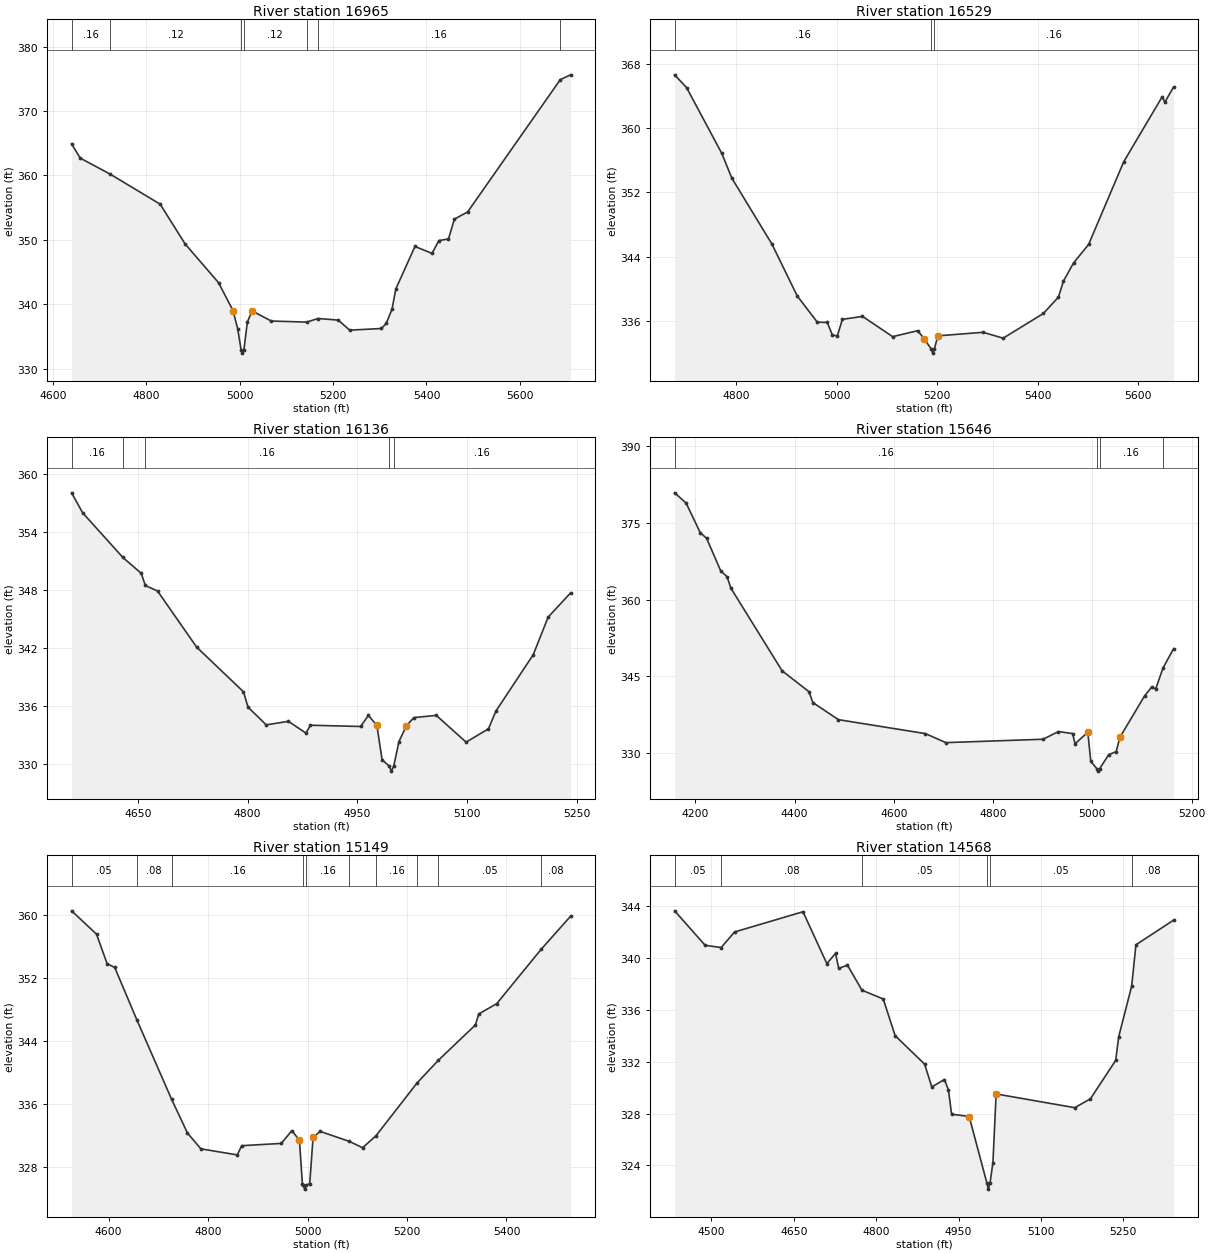
Type RM Length L Ch R = 1 ,16965   ,436,436,436
BEGIN DESCRIPTION:
BASSET CREEK 36.0
END DESCRIPTION:
XS GIS Cut Line= 2
      3745186.41     10629251.98      3744144.81     10629491.55
#Sta/Elev= 30
  4639.9  364.91  4658.2   362.7  4722.2  360.22  4829.6  355.55  4882.9   349.4
  4954.7  343.37  4985.5  339.06  4995.8   336.2    5003  332.95  5005.8  332.45
    5009  332.95  5016.3  337.26  5026.5  338.99  5067.6  337.43  5143.5  337.26
  5167.9  337.82  5211.2  337.57  5235.5  336.01  5303.6  336.27  5313.9  337.05
  5326.3  339.28  5334.4   342.4  5375.4  348.99    5412  347.92  5426.7  349.91
  5447.2  350.15  5459.9  353.23  5488.3  354.35  5686.7  374.86  5708.7  375.61
#Mann= 7 ,-1 , 0
  4639.9     .16       0  4722.2     .12       0    5003     .07       0
    5009     .12       0  5143.5     .05       0  5167.9     .16       0
  5686.7     .05       0
Bank Sta=4985.5,5026.5
XS Rating Curve= 0 ,0
Exp/Cntr=0.3,0.1

Type RM Length L Ch R = 1 ,16529   ,393,393,393
BEGIN DESCRIPTION:
BASSET CREEK 35.0
END DESCRIPTION:
XS GIS Cut Line= 2
       3745113.5     10628925.59      3744120.52     10628904.75
#Sta/Elev= 30
  4677.3  366.63  4701.2  365.03  4771.2  356.86  4791.2  353.78  4871.2  345.56
  4921.2  339.15  4961.3  335.87  4981.3  335.83  4991.3  334.27  5001.3  334.17
  5011.3  336.22  5051.3  336.59  5111.3  334.07  5161.3  334.81  5174.7  333.75
  5188.3  332.52  5191.1  332.02  5194.3  332.52  5201.3  334.17  5291.3  334.61
  5331.3  333.88  5411.4  336.95  5441.4  338.99  5451.4  340.99  5471.4  343.23
  5501.4  345.53  5571.4  355.83  5648.1  363.92  5653.1  363.22  5670.5  365.11
#Mann= 3 ,-1 , 0
  4677.3     .16       0  5188.3     .07       0  5194.3     .16       0
Bank Sta=5174.7,5201.3
XS Rating Curve= 0 ,0
Exp/Cntr=0.3,0.1

Type RM Length L Ch R = 1 ,16136   ,490,490,490
BEGIN DESCRIPTION:
BASSET CREEK 34.0
END DESCRIPTION:
XS GIS Cut Line= 3
      3745099.62     10628710.19      3744699.61     10628560.19
      3744449.57     10628510.18
#Sta/Elev= 30
  4559.5  358.09  4574.6  356.02  4629.6   351.4  4654.7  349.76  4660.3   348.5
    4677  347.93  4730.4  342.13  4794.5   337.5  4800.7  335.91  4825.6  334.08
  4855.9  334.44  4879.9  333.23  4886.1  334.04  4954.7  333.91  4965.3  335.05
  4976.9  334.02    4984  330.48  4993.9  329.79  4996.7  329.29  4999.9  329.79
  5007.1  332.35  5017.3  333.99  5027.5  334.83  5058.1  335.06  5098.9  332.29
  5129.5  333.67  5139.7  335.51  5190.7  341.34  5211.1  345.23  5241.7  347.73
#Mann= 5 ,-1 , 0
  4559.5     .16       0  4629.6     .12       0  4660.3     .16       0
  4993.9     .07       0  4999.9     .16       0
Bank Sta=4976.9,5017.3
XS Rating Curve= 0 ,0
Exp/Cntr=0.3,0.1

Type RM Length L Ch R = 1 ,15646   ,497,497,497
BEGIN DESCRIPTION:
BASSET CREEK 33.0
END DESCRIPTION:
XS GIS Cut Line= 3
      3745249.65     10628010.18      3744449.61     10628210.19
      3744299.65     10628310.16
#Sta/Elev= 30
  4158.5  380.81  4181.7  378.81  4210.1  373.04    4223  371.93  4251.3  365.59
  4264.2  364.44  4271.9   362.2    4375  346.09  4429.1  342.02  4436.9   339.9
  4488.4  336.56  4663.6  333.84  4704.9  332.08  4900.7  332.74  4931.6  334.24
    4960  333.85  4965.1  331.86  4990.7  334.12  4996.7  328.42  5008.7  327.02
  5011.5  326.52  5014.7  327.02  5032.7  329.72  5047.8  330.32  5055.3  333.11
  5104.9  341.17  5119.9  342.99  5127.4  342.53  5142.1  346.62  5163.4   350.4
#Mann= 4 ,-1 , 0
  4158.5     .16       0  5008.7     .07       0  5014.7     .16       0
  5142.1     .05       0
Bank Sta=4990.7,5055.3
XS Rating Curve= 0 ,0
Exp/Cntr=0.3,0.1

Type RM Length L Ch R = 1 ,15149   ,581,581,581
BEGIN DESCRIPTION:
BASSET CREEK 32.0
END DESCRIPTION:
XS GIS Cut Line= 3
      3744449.61     10627460.18      3744199.61     10627860.19
      3743799.62     10628210.18
#Sta/Elev= 30
  4525.6  360.55  4575.7  357.58    4597  353.83  4612.3  353.35  4656.8  346.69
  4726.7  336.59  4758.5  332.31  4785.6   330.3  4858.7  329.53  4867.6   330.7
  4947.2  330.99  4968.4  332.61  4983.7   331.4  4989.6  325.86  4991.4  325.68
  4994.1  325.18  4997.4  325.68  5004.4  325.88  5011.1  331.75  5025.3  332.52
  5084.3  331.24  5110.7  330.44  5137.7  331.97  5220.3  338.68  5262.9  341.55
  5337.6  346.05  5344.2  347.44  5380.3  348.75  5469.7  355.66  5528.8  359.86
#Mann= 10 ,-1 , 0
  4525.6     .05       0  4656.8     .08       0  4726.7     .16       0
  4991.4     .07       0  4997.4     .16       0  5084.3     .05       0
  5137.7     .16       0  5220.3     .08       0  5262.9     .05       0
  5469.7     .08       0
Bank Sta=4983.7,5011.1
XS Rating Curve= 0 ,0
Exp/Cntr=0.3,0.1

Type RM Length L Ch R = 1 ,14568   ,134,134,134
BEGIN DESCRIPTION:
Mapping XS 0bc2b8b7
END DESCRIPTION:
XS GIS Cut Line= 3
      3744228.99      10626901.7      3743894.78      10627498.5
      3743801.48     10627702.46
#Sta/Elev= 30
  4433.1  343.63  4488.7  340.97  4517.8   340.8  4542.3     342  4666.8  343.56
  4710.2  339.56  4726.1  340.35  4731.8  339.19  4747.8  339.44  4774.1  337.51
  4812.9  336.83  4834.6     334  4888.2  331.81  4901.3  330.05  4924.2  330.62
  4931.6  329.82  4937.3  327.95  4969.3  327.77  5001.4  322.67  5004.2  322.17
  5007.4  322.67  5012.6  324.22  5018.4  329.51  5161.5  328.45    5190  329.13
  5236.1   332.1  5241.6  333.93  5265.2  337.83  5272.9  341.01  5341.4  342.91
#Mann= 6 ,-1 , 0
  4433.1     .05       0  4517.8     .08       0  4774.1     .05       0
  5001.4     .04       0  5007.4     .05       0  5265.2     .08       0
Bank Sta=4969.3,5018.4
XS Rating Curve= 0 ,0
Exp/Cntr=0.3,0.1