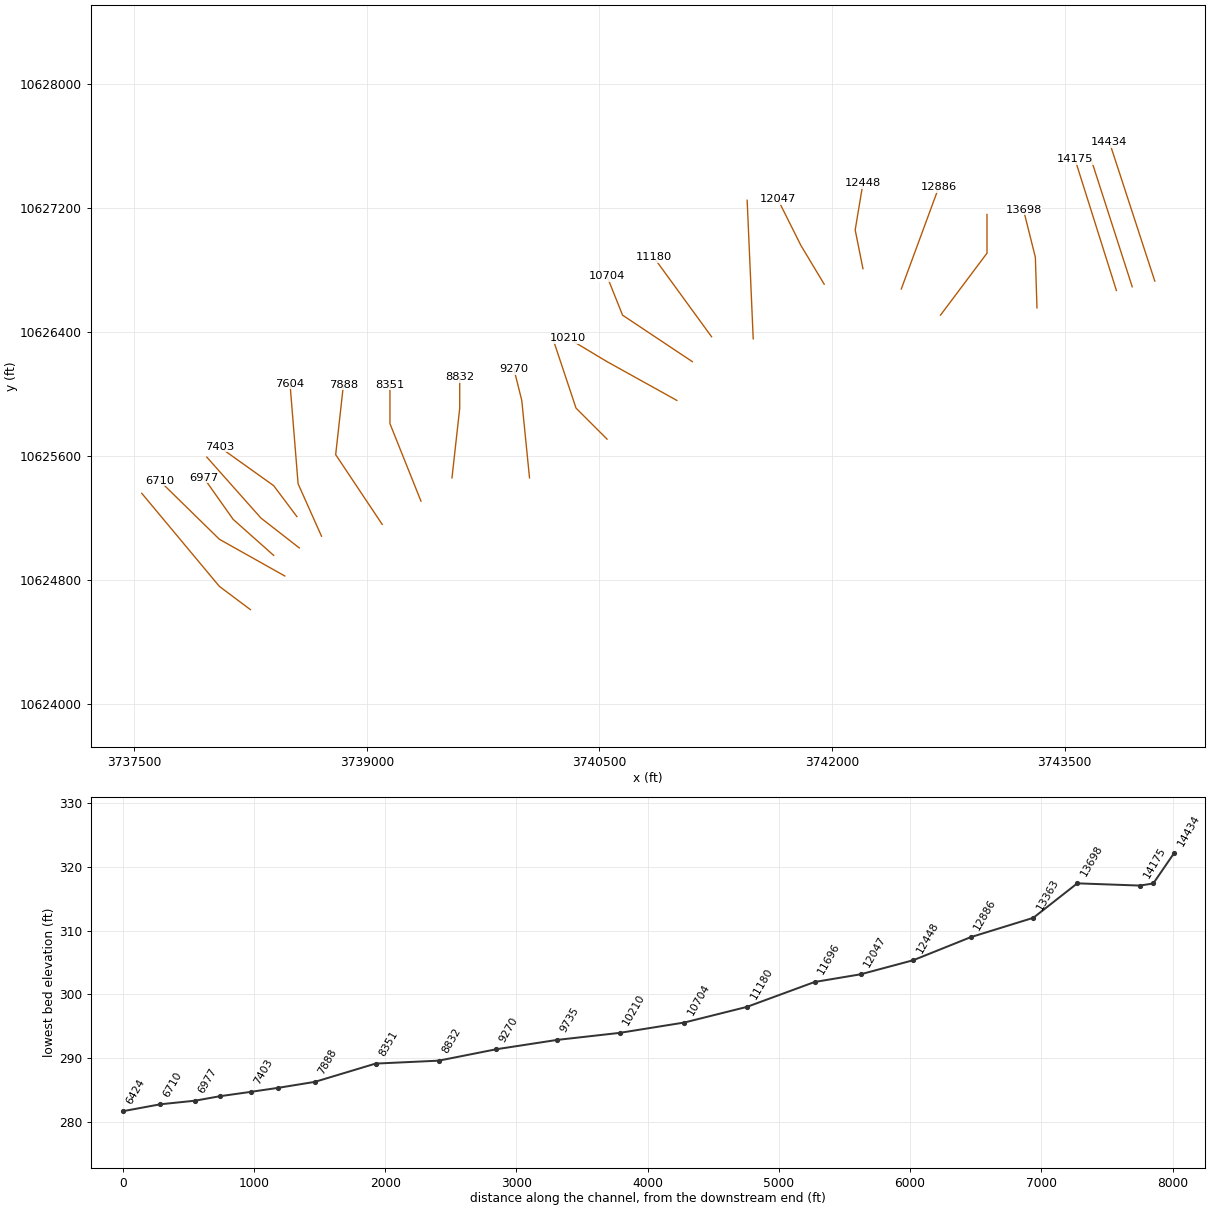
HEC-RAS study BASSET CREEK.prj: BASSET CREEK Base Level Engineering

--- BASSET CREEK.g01 (geometry) --- (continued)

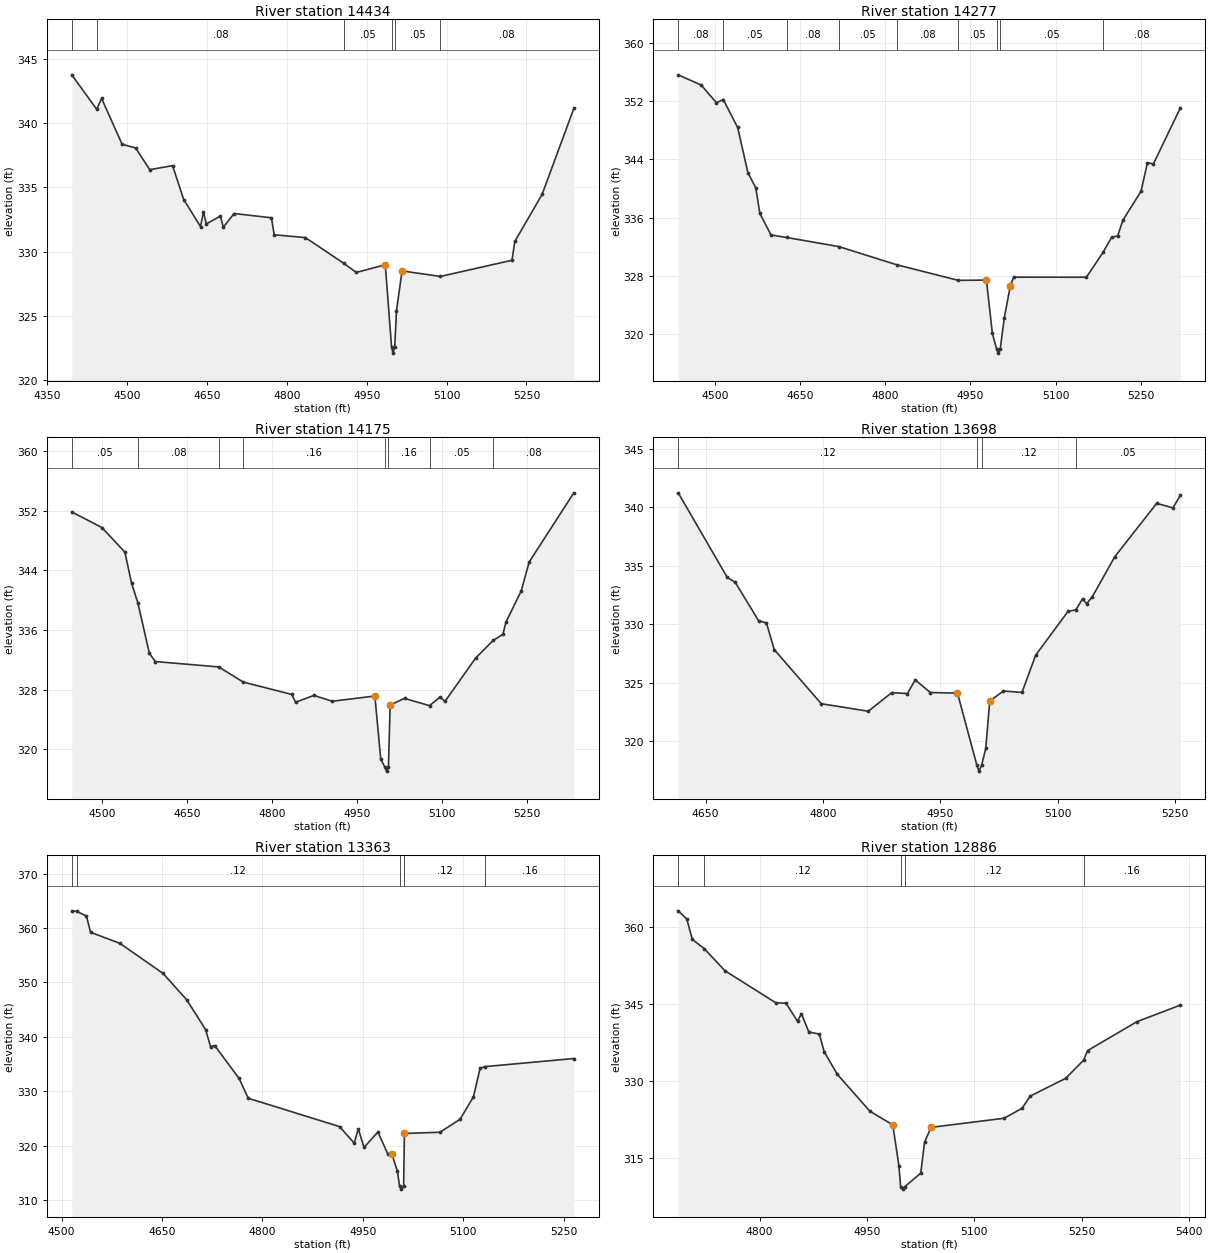
Type RM Length L Ch R = 1 ,14434   ,157,157,157
BEGIN DESCRIPTION:
BASSET CREEK 31.0
END DESCRIPTION:
XS GIS Cut Line= 2
      3744081.42     10626730.24      3743789.01     10627626.97
#Sta/Elev= 30
  4395.9  343.75  4442.8  341.07  4451.9  341.92  4490.5  338.35  4515.7  338.07
  4542.4  336.38  4585.2  336.69  4606.2  334.06  4637.8  331.95  4643.3  333.11
  4648.6  332.16  4675.2  332.77  4680.5   331.9  4700.9  332.97    4771  332.64
  4776.2  331.32  4834.8   331.1  4907.3  329.09  4930.5  328.39  4984.9  328.99
  4996.6  322.62  4999.3  322.12  5002.6  322.62  5005.9  325.42  5016.4  328.51
  5088.5  328.08  5222.9  329.34  5228.2   330.8  5279.4  334.45  5339.1  341.14
#Mann= 6 ,-1 , 0
  4395.9     .05       0  4442.8     .08       0  4907.3     .05       0
  4996.6     .04       0  5002.6     .05       0  5088.5     .08       0
Bank Sta=4984.9,5016.4
XS Rating Curve= 0 ,0
Exp/Cntr=0.3,0.1

Type RM Length L Ch R = 1 ,14277   ,102,102,102
BEGIN DESCRIPTION:
BASSET CREEK 30.0
END DESCRIPTION:
XS GIS Cut Line= 2
        3743936.     10626693.41      3743664.77      10627535.3
#Sta/Elev= 30
  4435.2  355.61  4475.7   354.2  4502.5  351.78  4514.5  352.22  4539.9  348.38
  4557.9  342.18  4571.9  340.08  4578.9  336.59  4598.7  333.62  4626.1  333.28
    4718  332.03  4819.8  329.54  4928.5  327.39  4978.1  327.43  4988.6  320.11
  4996.3   317.9    4999   317.4  5002.3   317.9  5009.7  322.29  5020.2  326.61
  5026.1  327.83  5154.3  327.82  5183.5  331.23  5198.8  333.31  5209.3  333.48
  5218.5  335.65  5250.5  339.62  5261.8  343.53  5272.3  343.38  5319.7  351.06
#Mann= 9 ,-1 , 0
  4435.2     .08       0  4514.5     .05       0  4626.1     .08       0
    4718     .05       0  4819.8     .08       0  4928.5     .05       0
  4996.3     .04       0  5002.3     .05       0  5183.5     .08       0
Bank Sta=4978.1,5020.2
XS Rating Curve= 0 ,0
Exp/Cntr=0.3,0.1

Type RM Length L Ch R = 1 ,14175   ,477,477,477
BEGIN DESCRIPTION:
Mapping XS ef3b9758
END DESCRIPTION:
XS GIS Cut Line= 2
      3743834.02      10626669.5       3743567.2     10627515.52
#Sta/Elev= 30
  4445.9  351.82    4499  349.73  4539.7  346.44  4551.5  342.29  4562.8  339.59
  4582.9   332.9  4593.4  331.76  4705.5  331.04  4748.9  329.01  4834.6  327.35
  4841.4  326.31  4873.7  327.22  4906.1  326.44  4981.4  327.14  4991.9  318.64
  4999.4  317.57  5002.1  317.07  5005.4  317.57  5008.4  325.93  5033.8  326.82
    5078  325.85  5096.7     327  5105.4  326.43  5159.6  332.24  5190.4  334.59
  5207.7  335.41    5213  337.04  5240.1  341.24    5254   345.1    5333  354.38
#Mann= 8 ,-1 , 0
  4445.9     .05       0  4562.8     .08       0  4705.5     .05       0
  4748.9     .16       0  4999.4     .07       0  5005.4     .16       0
    5078     .05       0  5190.4     .08       0
Bank Sta=4981.4,5008.4
XS Rating Curve= 0 ,0
Exp/Cntr=0.3,0.1

Type RM Length L Ch R = 1 ,13698   ,335,335,335
BEGIN DESCRIPTION:
BASSET CREEK 29.0
END DESCRIPTION:
XS GIS Cut Line= 3
      3743321.86     10626557.51      3743311.44     10626883.92
      3743235.06     10627189.44
#Sta/Elev= 30
    4615  341.25  4677.7     334  4687.7   333.6  4717.7   330.3  4727.7  330.11
  4737.7  327.82  4797.8  323.19  4857.8  322.55  4887.8  324.14  4907.8  324.06
  4917.8  325.23  4937.2  324.15  4971.8   324.1  4996.6  317.92  4999.3  317.42
  5002.6  317.92  5007.9  319.36    5013  323.42  5030.5  324.28  5054.2  324.16
  5071.7  327.35    5113   331.1    5123  331.23  5131.6  332.18  5136.7  331.75
  5143.9  332.33  5172.8  335.78  5226.3  340.35    5247  339.96  5256.5  341.03
#Mann= 4 ,-1 , 0
    4615     .12       0  4996.6     .07       0  5002.6     .12       0
    5123     .05       0
Bank Sta=4971.8,5013
XS Rating Curve= 0 ,0
Exp/Cntr=0.3,0.1

Type RM Length L Ch R = 1 ,13363   ,477,477,477
BEGIN DESCRIPTION:
BASSET CREEK 28.0
END DESCRIPTION:
XS GIS Cut Line= 3
      3742699.59     10626510.17      3742999.61     10626910.19
      3742999.61     10627160.16
#Sta/Elev= 30
  4515.1  363.15  4522.7  363.04    4537  362.19  4543.2  359.21    4587  357.17
  4651.6  351.64    4687  346.77  4715.1   341.3  4722.4  338.21  4728.7  338.38
  4765.1  332.34  4778.7  328.71  4915.1   323.5    4937  320.46  4943.2  323.09
  4951.6  319.67  4972.4  322.51    4987  318.52  4993.2  318.47  5001.6  315.29
  5004.8  312.51  5007.6  312.01  5010.8  312.51    5012  322.24  5065.1  322.46
  5095.1  324.84  5115.1  328.96  5125.1  334.23  5132.9  334.53  5265.1  336.01
#Mann= 5 ,-1 , 0
  4515.1     .08       0  4522.7     .12       0  5004.8     .07       0
  5010.8     .12       0  5132.9     .16       0
Bank Sta=4993.2,5012
XS Rating Curve= 0 ,0
Exp/Cntr=0.3,0.1

Type RM Length L Ch R = 1 ,12886   ,438,438,438
BEGIN DESCRIPTION:
Mapping XS 647055c8
END DESCRIPTION:
XS GIS Cut Line= 2
      3742446.94       10626679.      3742689.35     10627336.96
#Sta/Elev= 30
  4686.4  363.09  4698.3   361.5  4706.1  357.53  4722.6  355.76  4751.6  351.44
  4822.6  345.21  4836.9  345.12    4853  341.61  4858.4  343.09  4868.8  339.53
  4883.5  339.12  4890.2  335.69  4908.6  331.29  4954.1  324.12  4986.1  321.46
  4994.6  313.48    4997  309.47  4999.7  308.97    5003  309.47  5025.1  312.08
  5030.4  318.08  5039.4  320.98  5141.5  322.75  5166.7   324.7  5177.9  327.06
  5227.6  330.52  5252.6  334.06    5258   335.9  5327.1  341.54  5387.6  344.75
#Mann= 5 ,-1 , 0
  4686.4     .05       0  4722.6     .12       0    4997     .07       0
    5003     .12       0  5252.6     .16       0
Bank Sta=4986.1,5039.4
XS Rating Curve= 0 ,0
Exp/Cntr=0.3,0.1

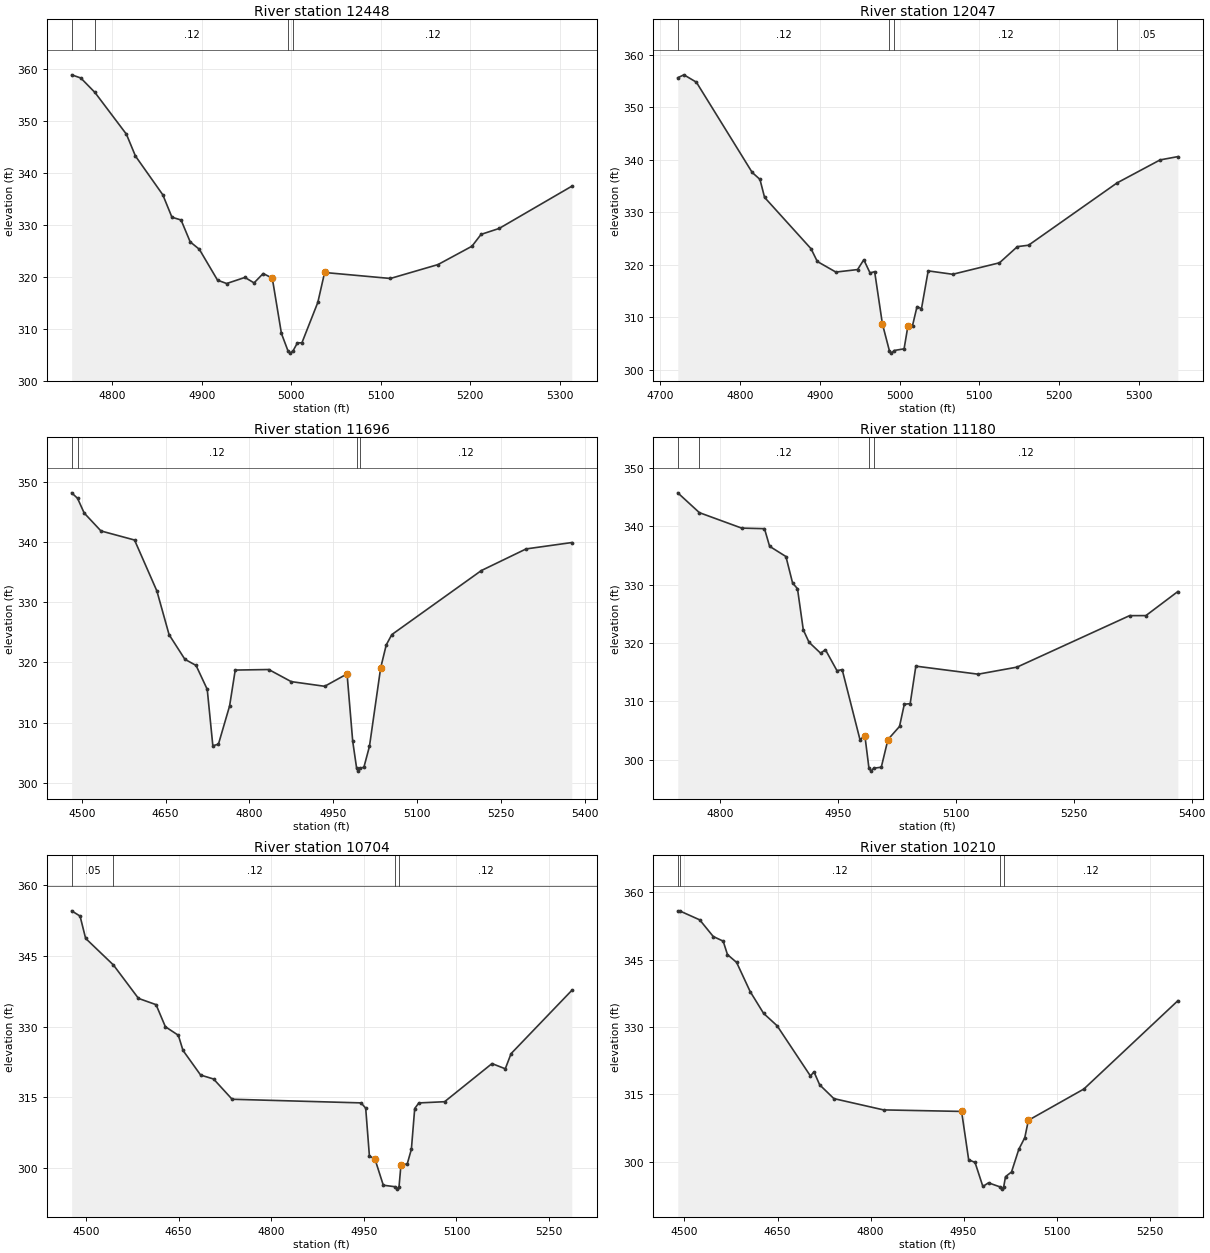
Type RM Length L Ch R = 1 ,12448   ,401,401,401
BEGIN DESCRIPTION:
BASSET CREEK 26.0
END DESCRIPTION:
XS GIS Cut Line= 3
       3742199.6     10626810.23      3742149.61     10627060.19
      3742199.62     10627360.24
#Sta/Elev= 30
  4754.6  358.88  4764.8  358.27  4780.6  355.49  4815.8  347.46  4825.9  343.26
  4856.5   335.8  4866.7  331.49  4876.9  330.96  4887.1  326.75  4897.3  325.33
  4917.7  319.38  4927.9  318.74  4948.3  319.91  4958.5  318.86  4968.7  320.66
  4978.9  319.77  4989.1  309.14  4996.3  305.85  4999.1  305.35  5002.3  305.85
    5007  307.33    5012  307.33  5029.8  315.11  5037.4  320.86  5110.9  319.71
  5164.1  322.38  5202.1  325.91  5212.3  328.19  5232.5  329.33  5313.7  337.45
#Mann= 4 ,-1 , 0
  4754.6     .05       0  4780.6     .12       0  4996.3     .07       0
  5002.3     .12       0
Bank Sta=4978.9,5037.4
XS Rating Curve= 0 ,0
Exp/Cntr=0.3,0.1

Type RM Length L Ch R = 1 ,12047   ,351,351,351
BEGIN DESCRIPTION:
BASSET CREEK 25.0
END DESCRIPTION:
XS GIS Cut Line= 3
      3741949.59     10626710.22      3741799.61     10626960.19
      3741649.62     10627260.17
#Sta/Elev= 30
  4721.9  355.64  4729.6  356.19  4745.2  354.79  4815.2  337.58  4824.9  336.26
  4830.7  332.83    4889  323.03  4896.8  320.61  4920.1  318.59  4947.3  319.07
  4955.1  320.94  4962.9  318.42  4968.7  318.67  4978.4  308.72  4987.1  303.64
  4989.8  303.14  4993.1  303.64  5005.6  303.96  5010.5   308.4  5016.2   308.4
  5021.8  312.01  5027.4  311.61  5035.8  318.82  5066.5  318.17  5125.2  320.36
  5147.6  323.44  5161.6  323.71  5272.6  335.59  5326.5  339.97  5348.8   340.6
#Mann= 4 ,-1 , 0
  4721.9     .12       0  4987.1     .07       0  4993.1     .12       0
  5272.6     .05       0
Bank Sta=4978.4,5010.5
XS Rating Curve= 0 ,0
Exp/Cntr=0.3,0.1

Type RM Length L Ch R = 1 ,11696   ,516,516,516
BEGIN DESCRIPTION:
Mapping XS 14306612
END DESCRIPTION:
XS GIS Cut Line= 2
      3741492.07     10626357.81      3741453.01     10627251.86
#Sta/Elev= 30
  4481.8  348.22  4492.3  347.31  4504.2  344.86  4534.2  341.88  4594.3  340.37
  4634.3  331.89  4656.1  324.63  4684.4  320.53  4704.4  319.51  4724.4  315.53
  4734.4  306.16  4744.4   306.4  4764.4  312.77  4774.5  318.74  4834.5  318.83
  4874.6  316.82  4934.6  316.04  4974.6   318.1  4984.7  306.91  4991.7  302.43
  4994.4  301.93  4997.7  302.43  5004.7  302.56  5014.7  306.06  5034.7  319.08
  5044.7  322.92  5054.7  324.64  5214.9  335.29    5295  338.89  5376.7  339.95
#Mann= 4 ,-1 , 0
  4481.8     .05       0  4492.3     .12       0  4991.7     .07       0
  4997.7     .12       0
Bank Sta=4974.6,5034.7
XS Rating Curve= 0 ,0
Exp/Cntr=0.3,0.1

Type RM Length L Ch R = 1 ,11180   ,476,476,476
BEGIN DESCRIPTION:
BASSET CREEK 23.0
END DESCRIPTION:
XS GIS Cut Line= 2
      3741223.54     10626370.92      3740849.05     10626885.84
#Sta/Elev= 30
  4745.8  345.76  4773.3  342.36  4827.1  339.71  4856.2  339.61  4862.7  336.59
  4883.5  334.83    4892  330.28  4898.2  329.32  4905.6  322.26  4912.9  320.13
  4927.6  318.26  4933.8  318.84  4948.5  315.25  4955.1  315.44  4977.8  303.41
    4984  304.12  4989.2  298.52  4991.9  298.02  4995.2  298.52  5004.9  298.69
  5013.4  303.44  5028.1  305.68  5034.2  309.49  5041.7   309.6  5048.9  316.03
  5128.2  314.65  5177.7  315.86    5321  324.69  5341.8   324.7  5382.5  328.83
#Mann= 4 ,-1 , 0
  4745.8     .05       0  4773.3     .12       0  4989.2     .07       0
  4995.2     .12       0
Bank Sta=4984,5013.4
XS Rating Curve= 0 ,0
Exp/Cntr=0.3,0.1

Type RM Length L Ch R = 1 ,10704   ,494,494,494
BEGIN DESCRIPTION:
BASSET CREEK 22.0
END DESCRIPTION:
XS GIS Cut Line= 3
      3741099.64     10626210.17      3740649.61     10626510.19
      3740549.62     10626760.17
#Sta/Elev= 30
  4476.7  354.56  4490.3  353.44  4499.3  348.72  4544.4  343.07  4584.9     336
  4613.4  334.67  4628.5  329.99  4649.5  328.18    4657  324.98  4685.6  319.75
  4706.6  318.91  4736.6  314.62  4945.5  313.85    4953  312.73    4959   302.6
    4968  301.94  4981.5   296.4    5001  296.07  5003.8  295.57    5007  296.07
  5010.1  300.66  5020.3  300.92    5027  304.02  5032.4  312.66  5039.1  313.84
  5080.8   314.1  5157.6  322.18  5179.1  321.08  5188.5  324.29  5286.8  337.69
#Mann= 4 ,-1 , 0
  4476.7     .05       0  4544.4     .12       0    5001     .07       0
    5007     .12       0
Bank Sta=4968,5010.1
XS Rating Curve= 0 ,0
Exp/Cntr=0.3,0.1

Type RM Length L Ch R = 1 ,10210   ,475,475,475
BEGIN DESCRIPTION:
BASSET CREEK 21.0
END DESCRIPTION:
XS GIS Cut Line= 3
       3740999.6      10625960.2      3740549.61     10626210.19
      3740299.62     10626360.18
#Sta/Elev= 30
  4489.2  355.83  4492.2  355.82  4524.6  353.82  4546.4  350.12  4562.4  349.09
  4569.3   346.1  4584.1  344.35  4605.9  337.88  4627.6  333.02  4649.3  330.28
  4703.1   319.1  4708.8  320.02    4718  317.13  4740.9  314.07  4820.9  311.56
  4946.8  311.22  4958.2  300.48  4968.5  299.87  4981.1  294.53  4990.2  295.34
  5008.7  294.44  5011.5  293.94  5014.7  294.44  5017.6  296.71  5027.3  297.76
    5039  302.78  5048.7  305.39  5054.5  309.25  5143.9   316.2  5295.5  335.84
#Mann= 4 ,-1 , 0
  4489.2     .05       0  4492.2     .12       0  5008.7     .07       0
  5014.7     .12       0
Bank Sta=4946.8,5054.5
XS Rating Curve= 0 ,0
Exp/Cntr=0.3,0.1

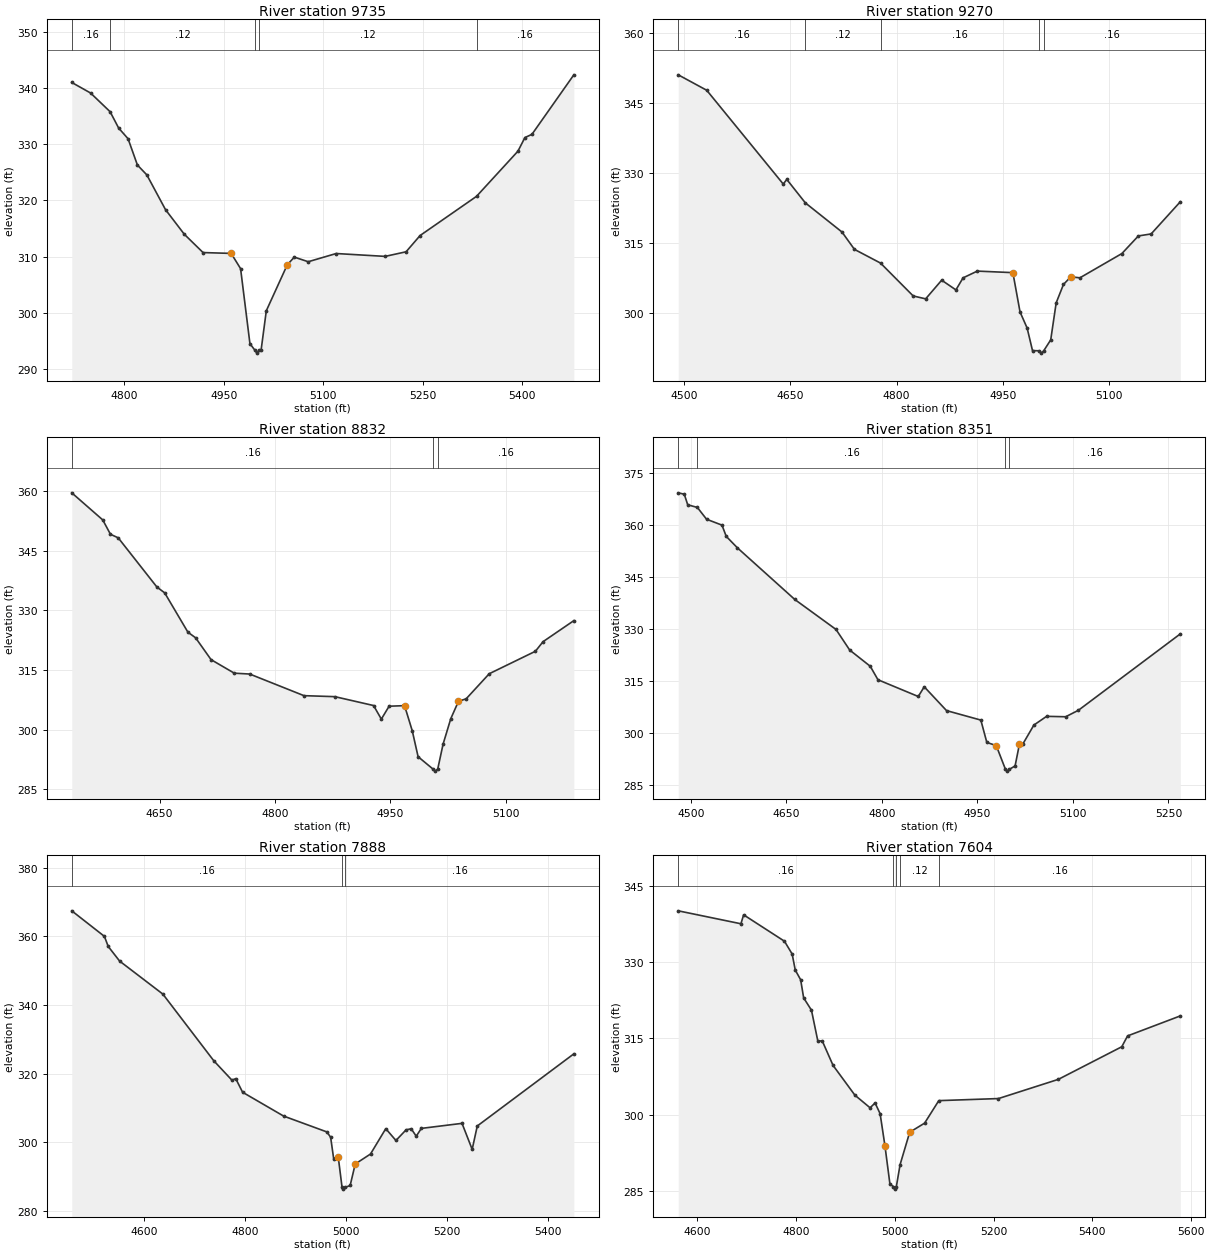
Type RM Length L Ch R = 1 ,9735    ,465,465,465
BEGIN DESCRIPTION:
BASSET CREEK 20.0
END DESCRIPTION:
XS GIS Cut Line= 3
      3740549.62     10625710.17      3740349.61     10625910.19
      3740199.61     10626360.18
#Sta/Elev= 30
  4720.6  340.99  4748.9  339.12  4778.4  335.79  4791.3  332.88  4805.5  330.98
  4819.6   326.3  4833.8  324.55    4862  318.36  4890.3  313.99  4918.6  310.73
    4961  310.58  4975.2  307.87  4989.3  294.52  4996.9  293.34  4999.7  292.84
  5002.9  293.34  5006.1  293.34    5014  300.38  5045.6  308.55  5056.2  309.92
  5077.2   309.1  5119.4  310.56  5193.2  310.05  5224.8  310.87  5245.9  313.76
    5331  320.73  5393.5  328.77    5404  331.19  5414.6  331.76  5477.8  342.35
#Mann= 5 ,-1 , 0
  4720.6     .16       0  4778.4     .12       0  4996.9     .07       0
  5002.9     .12       0    5331     .16       0
Bank Sta=4961,5045.6
XS Rating Curve= 0 ,0
Exp/Cntr=0.3,0.1

Type RM Length L Ch R = 1 ,9270    ,438,438,438
BEGIN DESCRIPTION:
BASSET CREEK 19.0
END DESCRIPTION:
XS GIS Cut Line= 3
      3740049.61     10625460.22      3739999.61     10625960.19
      3739949.61     10626160.17
#Sta/Elev= 30
  4491.7  351.05  4531.9  347.74  4639.9  327.63  4644.9  328.62  4671.1  323.59
  4722.8  317.34  4740.4  313.62  4777.2  310.68  4823.3  303.63  4840.9  303.01
  4863.5  307.01  4883.6  304.93  4893.7  307.51  4913.8  308.96    4964  308.63
  4974.1   300.2  4984.1  296.75  4991.7  291.91  5001.5  291.87  5004.2  291.37
  5007.5  291.87  5017.4  294.21  5025.1  302.15  5035.4   306.1  5045.7  307.73
  5058.6  307.52  5117.9  312.73  5141.1   316.5  5159.1  316.93  5200.3  323.83
#Mann= 5 ,-1 , 0
  4491.7     .16       0  4671.1     .12       0  4777.2     .16       0
  5001.5     .07       0  5007.5     .16       0
Bank Sta=4964,5045.7
XS Rating Curve= 0 ,0
Exp/Cntr=0.3,0.1

Type RM Length L Ch R = 1 ,8832    ,481,481,481
BEGIN DESCRIPTION:
BASSET CREEK 18.0
END DESCRIPTION:
XS GIS Cut Line= 3
      3739549.61     10625460.16      3739599.61     10625910.19
      3739599.61     10626110.19
#Sta/Elev= 30
  4535.9   359.5  4576.2  352.69  4586.2  349.09  4596.3  348.19  4646.6  335.83
  4656.7  334.37  4686.9  324.49  4696.9  323.08    4717  317.59  4747.2  314.19
  4767.3  313.97  4837.8  308.54    4878  308.29  4928.3  306.06  4938.4  302.65
  4948.5  305.89  4968.6  306.03  4978.6  299.72  4986.2   293.2  5005.7  290.08
  5008.5  289.58  5011.7  290.08  5018.7  296.37  5028.7  302.76  5038.7  307.12
  5048.7  307.75  5078.7  314.05  5138.7  319.69  5148.7  322.11  5188.7  327.39
#Mann= 3 ,-1 , 0
  4535.9     .16       0  5005.7     .07       0  5011.7     .16       0
Bank Sta=4968.6,5038.7
XS Rating Curve= 0 ,0
Exp/Cntr=0.3,0.1

Type RM Length L Ch R = 1 ,8351    ,463,463,463
BEGIN DESCRIPTION:
BASSET CREEK 17.0
END DESCRIPTION:
XS GIS Cut Line= 3
      3739349.62     10625310.15      3739149.61     10625810.19
      3739149.61     10626060.23
#Sta/Elev= 30
    4480  369.22  4489.5  368.82  4494.9  365.77    4510  365.02  4524.5  361.62
  4548.7  359.92  4555.4  356.69  4572.9  353.39  4663.1  338.52  4727.8   329.9
  4749.3  323.97  4781.6   319.3  4793.7  315.42    4857   310.6  4866.4  313.39
  4901.4  306.54  4955.3  303.81  4964.7  297.38  4979.5  296.47    4994  289.62
  4996.8  289.12    5000  289.62  5009.1  290.62  5015.9  296.87  5021.1  296.87
  5038.6  302.38  5058.6  304.89  5088.6  304.77  5108.6  306.64  5268.6  328.62
#Mann= 4 ,-1 , 0
    4480     .05       0    4510     .16       0    4994     .07       0
    5000     .16       0
Bank Sta=4979.5,5015.9
XS Rating Curve= 0 ,0
Exp/Cntr=0.3,0.1

Type RM Length L Ch R = 1 ,7888    ,284,284,284
BEGIN DESCRIPTION:
BASSET CREEK 16.0
END DESCRIPTION:
XS GIS Cut Line= 3
      3739099.63     10625160.16      3738799.61     10625610.19
      3738849.61     10626060.15
#Sta/Elev= 30
  4457.4  367.49    4522  360.03  4529.5   357.1  4552.1  352.82  4637.7  343.18
  4738.4  323.73  4774.4  318.05  4781.9   318.5  4795.5  314.53  4876.6  307.58
  4962.2  302.95  4969.7  301.39  4975.7  295.13  4984.7  295.69  4992.3  286.75
    4995  286.25  4998.3  286.75  5008.3  287.31  5018.4  293.59  5048.6   296.5
  5078.8   303.9  5098.9  300.45    5119  303.56  5129.1  303.87  5139.1   301.7
  5149.2  303.98  5229.7  305.45  5249.8  297.86  5259.9  304.68    5451  325.74
#Mann= 3 ,-1 , 0
  4457.4     .16       0  4992.3     .07       0  4998.3     .16       0
Bank Sta=4984.7,5018.4
XS Rating Curve= 0 ,0
Exp/Cntr=0.3,0.1

Type RM Length L Ch R = 1 ,7604    ,201,201,201
BEGIN DESCRIPTION:
Mapping XS 0a4f5edf
END DESCRIPTION:
XS GIS Cut Line= 3
      3738708.36     10625083.68       3738557.3     10625422.25
      3738505.33     10626066.62
#Sta/Elev= 30
  4561.1  340.15  4688.1   337.6  4693.6  339.36  4776.3  334.16  4791.9  331.64
  4798.2  328.47  4809.1  326.57  4815.2  322.99    4831  320.57  4843.9   314.5
  4852.9  314.51  4874.8  309.68    4919  303.82  4949.8  301.33  4959.9  302.28
  4970.1  300.17  4979.9  293.84    4990  286.29    4997   285.8  4999.8   285.3
    5003   285.8  5010.6  290.14  5030.1  296.52  5060.2   298.3    5089  302.74
  5209.9  303.15  5331.1  306.93  5459.7  313.36  5471.5   315.5  5578.3  319.44
#Mann= 5 ,-1 , 0
  4561.1     .16       0    4997     .07       0    5003     .16       0
  5010.6     .12       0    5089     .16       0
Bank Sta=4979.9,5030.1
XS Rating Curve= 0 ,0
Exp/Cntr=0.3,0.1

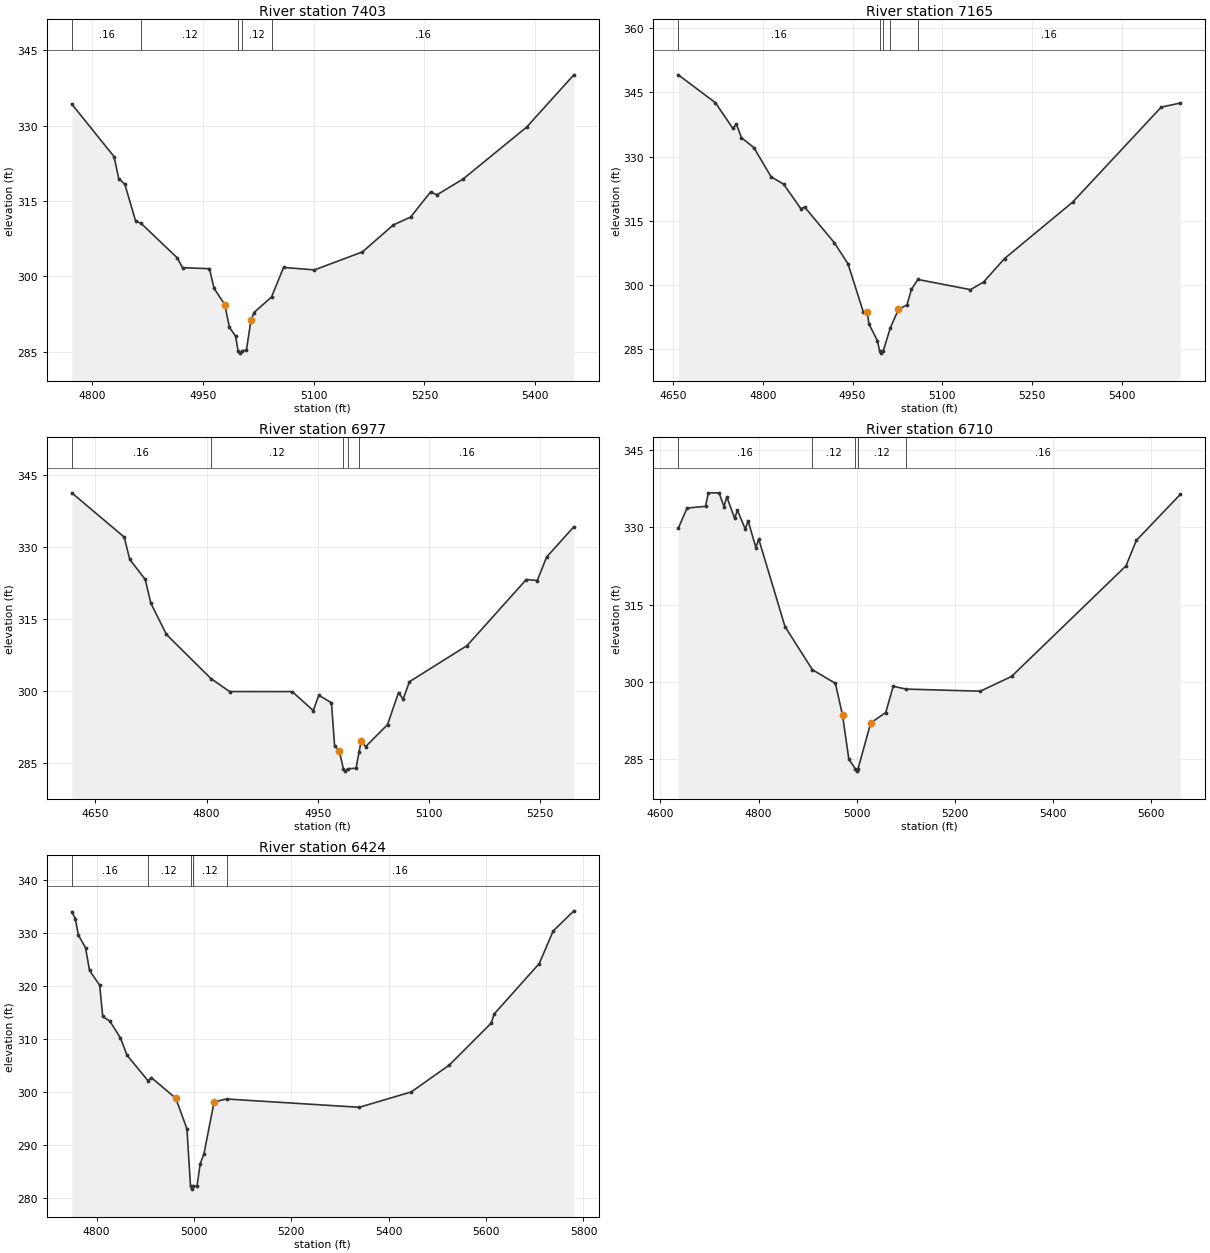
Type RM Length L Ch R = 1 ,7403    ,238,238,238
BEGIN DESCRIPTION:
BASSET CREEK 15.0
END DESCRIPTION:
XS GIS Cut Line= 3
      3738549.63     10625210.17      3738399.61     10625410.19
      3738049.64     10625660.16
#Sta/Elev= 30
  4772.3  334.31  4829.6  323.83  4835.9  319.46  4844.2  318.33  4858.8     311
  4866.2  310.54    4915   303.7  4922.3  301.71  4958.8  301.51    4965  297.61
  4979.6  294.35  4985.9  289.81  4994.2  288.07  4997.5  285.19  5000.2  284.69
  5003.5  285.19  5008.8  285.25    5015   291.2  5019.2  292.78  5042.9  295.88
  5059.2  301.76    5101  301.27  5166.1  304.86  5207.9  310.23  5231.2  311.78
  5258.3   316.8  5266.9  316.22  5302.5  319.39  5388.5  329.72  5452.4  340.13
#Mann= 5 ,-1 , 0
  4772.3     .16       0  4866.2     .12       0  4997.5     .07       0
  5003.5     .12       0  5042.9     .16       0
Bank Sta=4979.6,5015
XS Rating Curve= 0 ,0
Exp/Cntr=0.3,0.1

Type RM Length L Ch R = 1 ,7165    ,188,188,188
BEGIN DESCRIPTION:
Mapping XS 1f53a5fd
END DESCRIPTION:
XS GIS Cut Line= 3
      3738565.14     10625008.17      3738317.72      10625200.9
      3737968.74     10625594.15
#Sta/Elev= 30
  4658.6  349.13  4720.8   342.6  4749.7  336.63    4756  337.54  4764.2  334.43
    4785   332.1  4813.9  325.26  4834.7  323.56  4863.7  317.78    4870  318.18
  4919.8   309.8  4942.4  304.91  4967.9  293.69  4974.6  293.69  4977.4  290.84
  4991.7  286.88  4995.3   284.5  4998.1     284  5001.3   284.5  5013.3  289.95
  5026.8  294.25    5041  295.28  5048.5  298.93  5059.2  301.24  5147.2  298.86
    5169  300.63  5204.1  306.13  5317.8  319.31    5466  341.56    5498  342.53
#Mann= 5 ,-1 , 0
  4658.6     .16       0  4995.3     .07       0  5001.3     .16       0
  5013.3     .12       0  5059.2     .16       0
Bank Sta=4974.6,5026.8
XS Rating Curve= 0 ,0
Exp/Cntr=0.3,0.1

Type RM Length L Ch R = 1 ,6977    ,267,267,267
BEGIN DESCRIPTION:
BASSET CREEK 14.0
END DESCRIPTION:
XS GIS Cut Line= 3
      3738399.64     10624960.16      3738138.03     10625193.09
      3737949.58     10625460.23
#Sta/Elev= 30
  4618.1  341.35  4688.8  332.12  4696.3  327.46  4717.2  323.28  4724.7  318.35
  4745.7  311.82  4805.8  302.61  4830.9   299.9  4915.4  299.89  4943.8  295.93
  4951.3  299.13  4968.4  297.55  4972.6  288.57  4978.8  287.59  4984.4   283.8
  4987.2   283.3  4990.4   283.8  5001.5   283.9  5005.6  287.27  5008.3  289.49
  5014.5  288.43    5044     293  5058.8  299.69    5065  298.31  5073.6  301.96
  5151.2  309.48  5231.2  323.27    5246  323.06  5258.5  327.94  5295.3  334.27
#Mann= 5 ,-1 , 0
  4618.1     .16       0  4805.8     .12       0  4984.4     .07       0
  4990.4     .12       0  5005.6     .16       0
Bank Sta=4978.8,5008.3
XS Rating Curve= 0 ,0
Exp/Cntr=0.3,0.1

Type RM Length L Ch R = 1 ,6710    ,286,286,286
BEGIN DESCRIPTION:
Mapping XS cc5cb7da
END DESCRIPTION:
XS GIS Cut Line= 3
      3738471.62     10624827.09      3738049.72     10625064.08
      3737664.43     10625441.57
#Sta/Elev= 30
  4636.4   329.8  4654.4  333.75    4692  334.08  4697.8  336.68  4719.5   336.7
  4729.7  334.04  4735.4  335.92  4751.3  331.76  4757.1   333.3    4773  329.67
  4778.8  331.28  4794.7  326.07  4800.4  327.75    4854  310.76  4909.9  302.39
  4956.7  299.75  4971.3  293.56  4984.1  285.06    4997  283.23  4999.8  282.73
    5003  283.23  5028.7  292.08  5059.3  294.09  5074.6  299.19  5100.6  298.64
    5252  298.23  5315.7  301.09    5549  322.54  5570.1  327.48  5659.7   336.4
#Mann= 5 ,-1 , 0
  4636.4     .16       0  4909.9     .12       0    4997     .07       0
    5003     .12       0  5100.6     .16       0
Bank Sta=4971.3,5028.7
XS Rating Curve= 0 ,0
Exp/Cntr=0.3,0.1

Type RM Length L Ch R = 1 ,6424    ,293,293,293
BEGIN DESCRIPTION:
BASSET CREEK 13.0
END DESCRIPTION:
XS GIS Cut Line= 3
      3738249.63     10624610.17      3738049.61     10624760.19
      3737549.58     10625360.23
#Sta/Elev= 30
  4749.1  333.95  4756.4  332.62  4762.7  329.52  4777.3  327.15  4785.6  322.86
  4806.4  320.08  4812.7  314.21  4827.3  313.31  4849.1  310.14  4862.7  306.87
  4905.5  302.09  4912.7  302.65  4962.7  298.77  4985.6  293.01    4993  282.14
  4995.8  281.64    4999  282.14  5006.3   282.2  5012.8  286.41  5020.6   288.3
  5041.4   298.1  5066.9  298.63  5339.5  297.07  5446.3  299.96  5524.4  305.03
  5610.3  312.92  5616.8  314.68  5709.2  324.17  5737.8  330.31  5780.2   334.1
#Mann= 5 ,-1 , 0
  4749.1     .16       0  4905.5     .12       0    4993     .07       0
    4999     .12       0  5066.9     .16       0
Bank Sta=4962.7,5041.4
XS Rating Curve= 0 ,0
Exp/Cntr=0.3,0.1