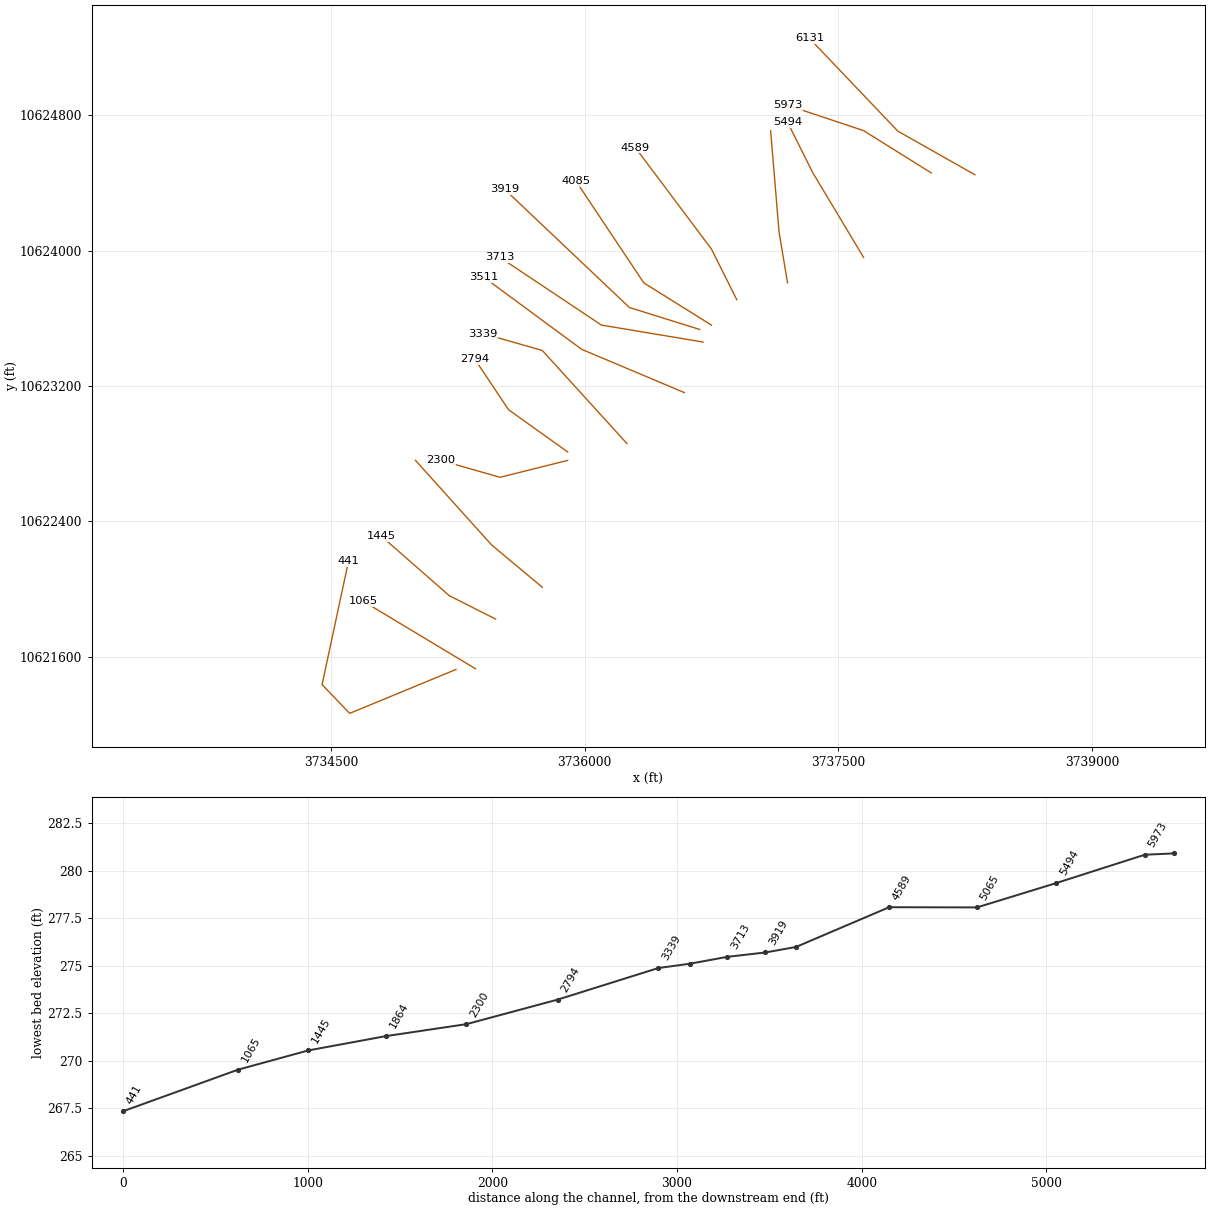
HEC-RAS study BASSET CREEK.prj: BASSET CREEK Base Level Engineering

--- BASSET CREEK.g01 (geometry) --- (continued)

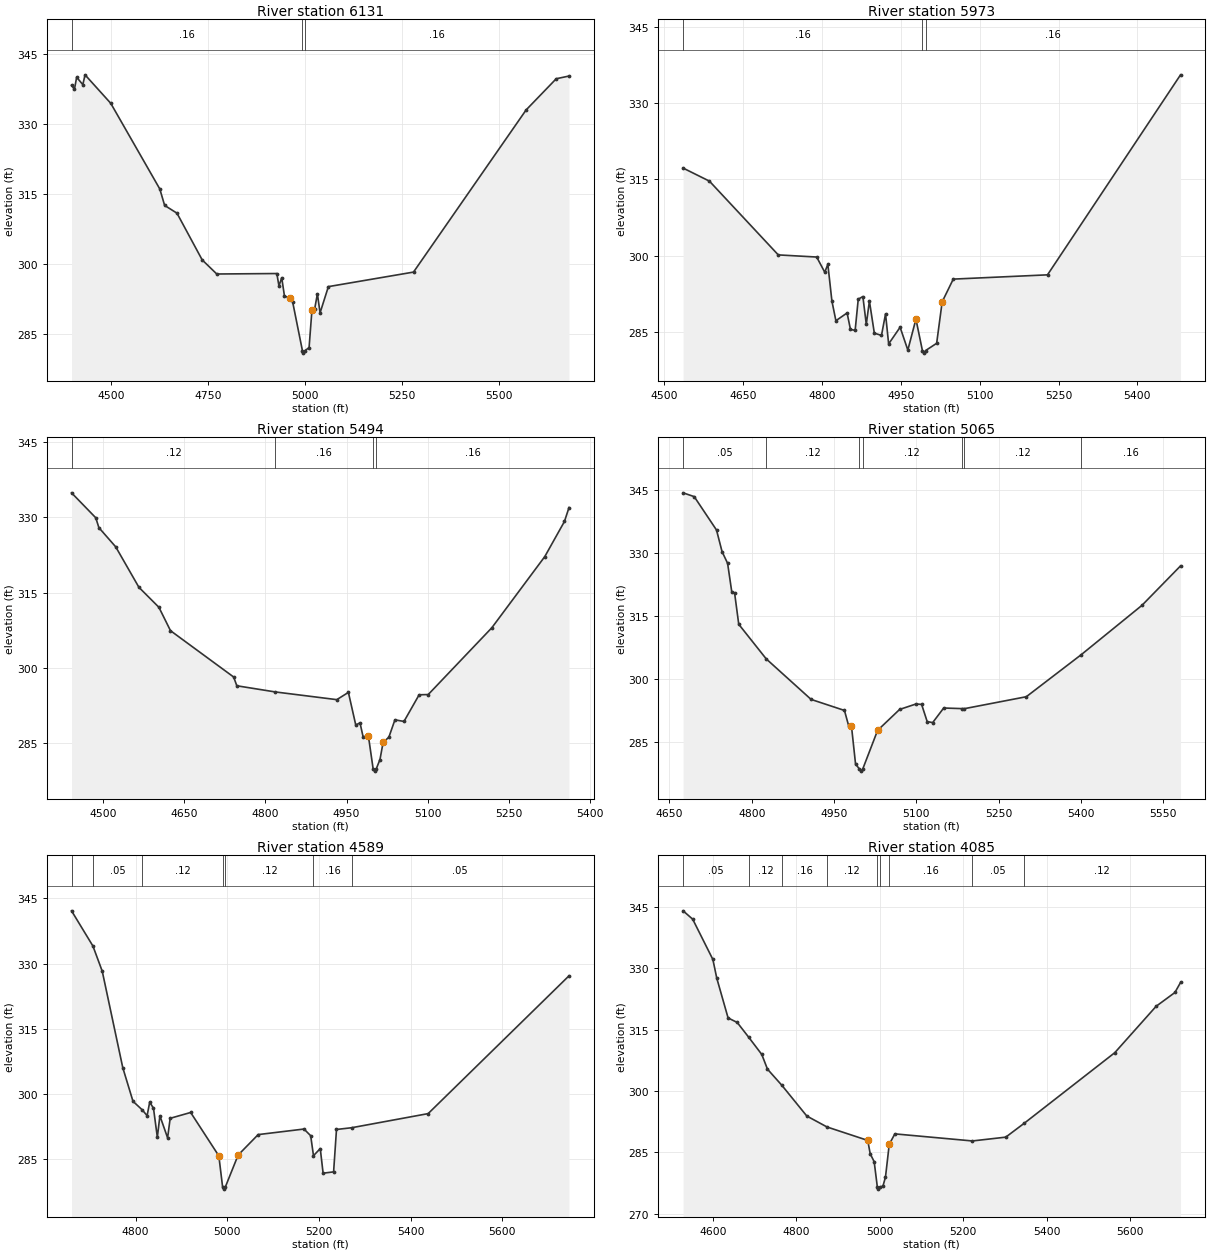
Type RM Length L Ch R = 1 ,6131    ,158,158,158
BEGIN DESCRIPTION:
Mapping XS efe21ad9
END DESCRIPTION:
XS GIS Cut Line= 3
      3738307.53      10624449.5      3737851.81     10624707.31
      3737329.12       10625256.
#Sta/Elev= 30
  4397.8   338.4  4405.3  337.52    4411  340.11  4426.9  338.52  4432.6  340.63
  4498.8  334.52  4625.2  316.13  4637.6  312.61  4669.4  310.94  4734.3  300.92
  4771.9  297.89  4926.6  297.99  4932.1  295.32  4939.2   297.1  4946.2  293.19
  4960.4  292.69  4967.3  291.92  4992.6  281.41  4995.3  280.91  4998.6  281.41
  5009.7   282.1    5017  290.09  5023.9  290.31  5031.1  293.63    5038  289.55
  5059.4  295.18  5278.7   298.3  5568.7  333.09  5646.3  339.79  5679.2  340.37
#Mann= 3 ,-1 , 0
  4397.8     .16       0  4992.6     .07       0  4998.6     .16       0
Bank Sta=4960.4,5017
XS Rating Curve= 0 ,0
Exp/Cntr=0.3,0.1

Type RM Length L Ch R = 1 ,5973    ,479,479,479
BEGIN DESCRIPTION:
BASSET CREEK 12.0
END DESCRIPTION:
XS GIS Cut Line= 3
      3738049.57     10624460.21      3737649.61     10624710.19
       3737199.6     10624860.19
#Sta/Elev= 30
    4536  317.22  4586.1  314.65    4717  300.15  4790.1  299.73  4805.4  296.74
  4811.3   298.3    4819  291.08  4826.6  287.21  4847.9  288.74  4854.3  285.49
  4863.2  285.32  4869.1  291.45  4877.9  291.96  4884.4  286.49  4890.3  291.09
  4899.7  284.76  4913.3  284.33    4921  288.56  4926.9  282.65  4948.7  285.93
  4963.4  281.44  4978.8  287.52  4991.1  281.34  4993.8  280.84  4997.1  281.34
  5018.2  282.77  5028.7  290.93  5049.8  295.39    5229  296.23    5482  335.55
#Mann= 3 ,-1 , 0
    4536     .16       0  4991.1     .07       0  4997.1     .16       0
Bank Sta=4978.8,5028.7
XS Rating Curve= 0 ,0
Exp/Cntr=0.3,0.1

Type RM Length L Ch R = 1 ,5494    ,429,429,429
BEGIN DESCRIPTION:
BASSET CREEK 11.0
END DESCRIPTION:
XS GIS Cut Line= 3
      3737649.61     10623960.18      3737349.61     10624460.19
      3737199.61     10624760.18
#Sta/Elev= 30
  4442.2  334.91  4486.9  329.93  4492.7  327.96  4523.8  324.12  4566.6  316.05
  4603.5  312.06  4624.9  307.39  4741.5  298.14  4747.4  296.39  4818.3  295.16
    4932  293.62  4953.4  295.07    4967  288.55  4974.8  288.99  4980.6  286.18
  4990.3   286.4    4999  279.85  5001.7  279.35    5005  279.85  5011.7  281.67
  5017.5  285.09  5028.1  286.12  5039.3  289.59    5056  289.27    5084  294.59
  5100.8  294.64  5218.2  307.97    5316  322.18  5352.3  329.19  5360.7  331.97
#Mann= 4 ,-1 , 0
  4442.2     .12       0  4818.3     .16       0    4999     .07       0
    5005     .16       0
Bank Sta=4990.3,5017.5
XS Rating Curve= 0 ,0
Exp/Cntr=0.3,0.1

Type RM Length L Ch R = 1 ,5065    ,476,476,476
BEGIN DESCRIPTION:
BASSET CREEK 10.0
END DESCRIPTION:
XS GIS Cut Line= 3
      3737199.62     10623810.14      3737149.61     10624110.19
      3737099.61     10624710.23
#Sta/Elev= 30
    4675  344.43  4695.3  343.52  4735.9  335.56    4746  330.41  4756.1  327.62
  4763.8  320.72  4768.8   320.6  4776.4  313.09  4826.5  304.83  4908.2  295.17
    4969  292.54  4976.6   288.9  4981.7   288.9  4989.2  279.77  4996.3  278.57
    4999  278.07  5002.3  278.57  5029.4  287.79  5069.5  292.78  5099.6  294.09
  5109.6  293.97  5119.7  289.89  5129.7  289.64  5149.8  293.12  5182.3  292.98
  5187.4  292.96  5300.3  295.81  5400.4  305.84    5511   317.6  5581.3  327.01
#Mann= 7 ,-1 , 0
    4675     .05       0  4826.5     .12       0  4996.3     .07       0
  5002.3     .12       0  5182.3     .16       0  5187.4     .12       0
  5400.4     .16       0
Bank Sta=4981.7,5029.4
XS Rating Curve= 0 ,0
Exp/Cntr=0.3,0.1

Type RM Length L Ch R = 1 ,4589    ,504,504,504
BEGIN DESCRIPTION:
BASSET CREEK 9.0
END DESCRIPTION:
XS GIS Cut Line= 3
      3736899.59     10623710.22      3736749.61     10624010.19
      3736299.59     10624610.21
#Sta/Elev= 30
  4660.1  342.13  4706.8  334.02  4727.1  328.23  4771.9  306.03  4794.2  298.29
  4814.4  296.32    4825  294.98  4830.6  298.08  4838.9  296.71  4847.3  290.02
  4852.9  294.95  4869.7  289.88  4875.3  294.38    4920  295.72  4981.5  285.73
  4989.7  278.58  4992.4  278.08  4995.7  278.58  5023.6  285.92  5067.3  290.63
  5167.3  291.91  5181.9  290.37    5188  285.78  5202.8  287.41    5209  281.75
  5231.9  282.05  5238.2  291.81  5271.2  292.21  5438.2  295.46  5745.5  327.17
#Mann= 7 ,-1 , 0
  4660.1     .08       0  4706.8     .05       0  4814.4     .12       0
  4989.7     .07       0  4995.7     .12       0    5188     .16       0
  5271.2     .05       0
Bank Sta=4981.5,5023.6
XS Rating Curve= 0 ,0
Exp/Cntr=0.3,0.1

Type RM Length L Ch R = 1 ,4085    ,166,166,166
BEGIN DESCRIPTION:
BASSET CREEK 8.0
END DESCRIPTION:
XS GIS Cut Line= 3
      3736749.64     10623560.17      3736349.61     10623810.19
      3735949.63     10624410.15
#Sta/Elev= 30
  4528.6  344.04  4551.6     342    4600  332.15  4609.4  327.56  4636.5  317.85
  4658.4  316.74  4686.4  313.07  4717.3  308.92  4730.9  305.33  4765.5  301.37
  4825.2  293.87  4873.7  291.19  4971.4   287.9  4977.3  284.62  4986.8   282.7
  4994.4  276.49  4997.1  275.99  5000.4  276.49  5007.8  276.72  5013.9  278.94
  5022.9  286.91  5023.2  287.01  5036.4   289.5  5222.3  287.77  5302.3   288.7
  5346.4  292.08  5563.7  309.35  5662.9   320.7  5707.9  324.07  5721.4  326.52
#Mann= 9 ,-1 , 0
  4528.6     .05       0  4686.4     .12       0  4765.5     .16       0
  4873.7     .12       0  4994.4     .07       0  5000.4     .12       0
  5023.2     .16       0  5222.3     .05       0  5346.4     .12       0
Bank Sta=4971.4,5022.9
XS Rating Curve= 0 ,0
Exp/Cntr=0.3,0.1

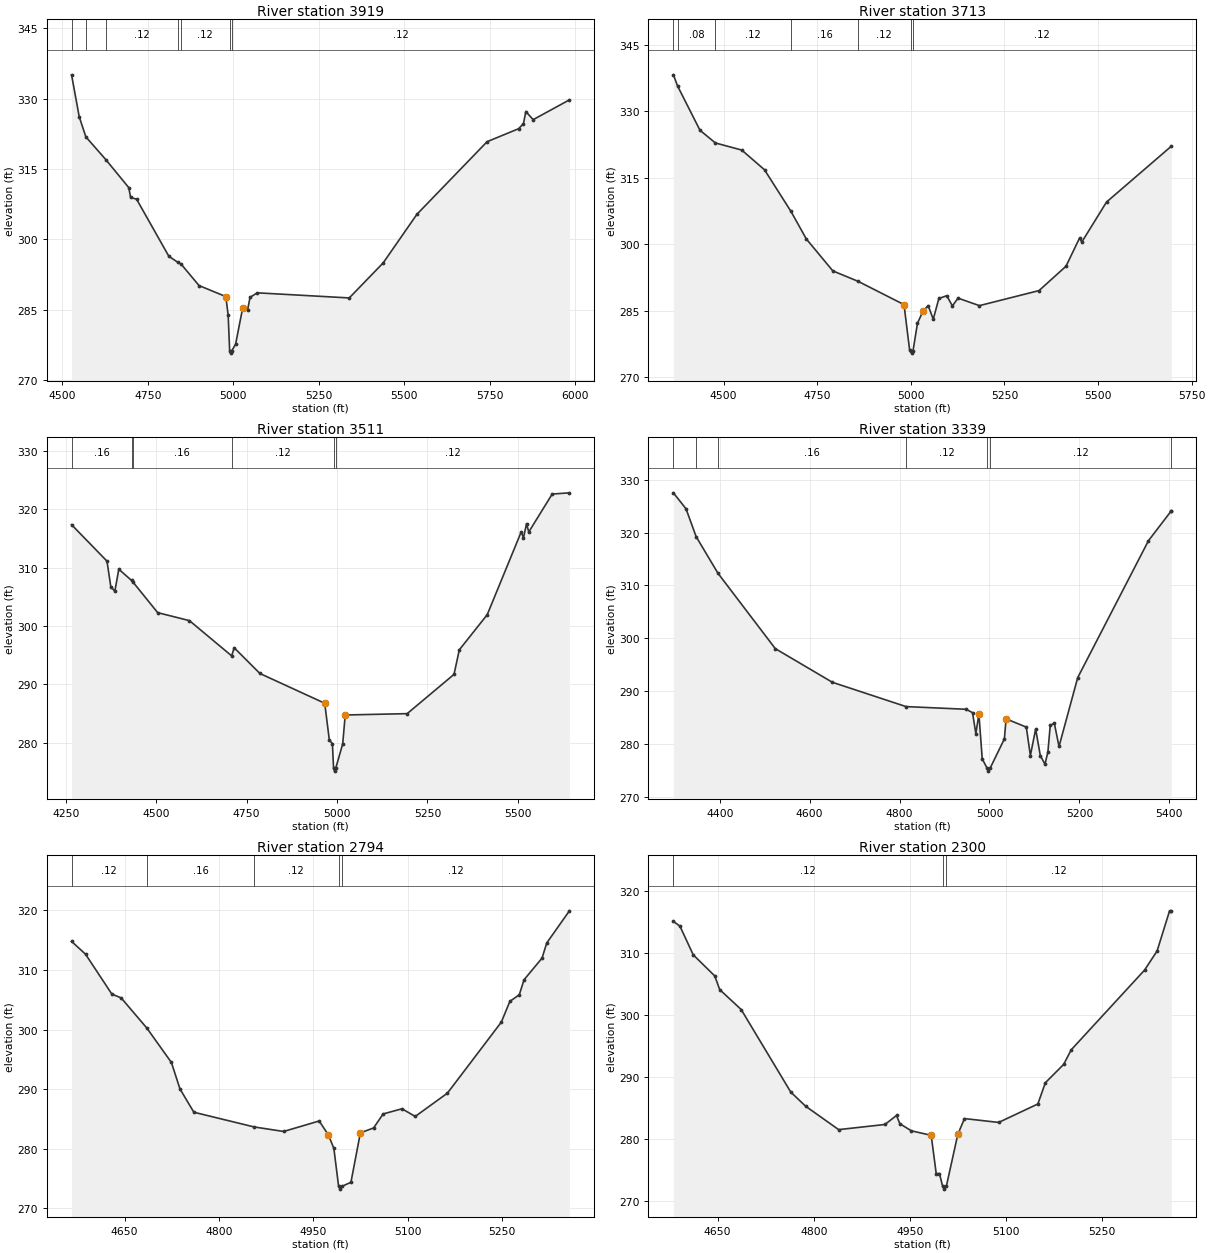
Type RM Length L Ch R = 1 ,3919    ,206,206,206
BEGIN DESCRIPTION:
Mapping XS dcf13ca4
END DESCRIPTION:
XS GIS Cut Line= 3
      3736681.03     10623534.26      3736264.39     10623664.46
      3735524.65     10624365.26
#Sta/Elev= 30
  4526.9  335.05  4549.3  326.11  4568.7  321.82  4626.9  316.98  4694.2  310.99
  4699.5   308.9    4717  308.53  4811.3  296.36  4836.7  295.11    4847   294.7
  4899.6  290.11  4977.9  287.76  4984.8  283.75  4989.1   276.2  4991.9   275.7
  4995.1   276.2  5006.3  277.55  5027.3  285.37  5041.5  284.89  5048.7  287.59
  5069.8  288.56  5338.8  287.47  5437.9  294.94  5536.6  305.31  5741.7  320.79
  5833.9  323.56  5848.1  324.66    5855  327.22  5876.4  325.49  5982.4  329.71
#Mann= 7 ,-1 , 0
  4526.9     .08       0  4568.7     .05       0  4626.9     .12       0
  4836.7     .16       0    4847     .12       0  4989.1     .07       0
  4995.1     .12       0
Bank Sta=4977.9,5027.3
XS Rating Curve= 0 ,0
Exp/Cntr=0.3,0.1

Type RM Length L Ch R = 1 ,3713    ,202,202,202
BEGIN DESCRIPTION:
BASSET CREEK 7.0
END DESCRIPTION:
XS GIS Cut Line= 3
       3736699.6     10623460.19      3736099.61     10623560.19
      3735499.59      10623960.2
#Sta/Elev= 30
  4366.1  338.17  4377.4  335.63  4437.1  325.68  4478.3  322.82  4548.6  321.22
  4609.4  316.78  4680.2  307.38  4720.9  301.21  4791.9  293.99    4859  291.66
  4981.9   286.4  4996.9  276.17  4999.9  275.97  5002.7  275.47  5005.9  275.97
  5017.9  282.22    5033  284.99  5046.5  286.17    5060  283.11    5075  287.78
  5096.1  288.41  5111.1  286.09  5126.1  287.86  5183.2  286.17  5342.4  289.56
  5414.5  295.05  5450.6  301.39  5456.6  300.49  5522.7  309.51  5695.5  322.07
#Mann= 7 ,-1 , 0
  4366.1      .1       0  4377.4     .08       0  4478.3     .12       0
  4680.2     .16       0    4859     .12       0  4999.9     .07       0
  5005.9     .12       0
Bank Sta=4981.9,5033
XS Rating Curve= 0 ,0
Exp/Cntr=0.3,0.1

Type RM Length L Ch R = 1 ,3511    ,172,172,172
BEGIN DESCRIPTION:
Mapping XS 71cf2e93
END DESCRIPTION:
XS GIS Cut Line= 3
      3736589.93     10623160.98      3735982.27     10623417.07
      3735404.98     10623842.44
#Sta/Elev= 30
    4266  317.34    4364  311.09  4374.6  306.68  4385.7  305.95  4396.6  309.71
    4432  307.78  4435.8  307.51  4504.1  302.27  4591.9   300.9  4708.7  294.86
  4715.6  296.25  4786.8  291.84    4966  286.74  4978.7  280.43  4987.2  279.83
  4990.4  275.61  4993.1  275.11  4996.4  275.61  5015.7  279.79  5022.6  284.73
  5193.9  284.96  5323.4  291.69  5338.1   295.9  5415.2  301.91  5509.3  316.12
  5515.5  315.08  5523.9  317.51  5530.1  316.09  5594.9  322.59  5642.5   322.8
#Mann= 6 ,-1 , 0
    4266     .16       0    4432     .05       0  4435.8     .16       0
  4708.7     .12       0  4990.4     .07       0  4996.4     .12       0
Bank Sta=4966,5022.6
XS Rating Curve= 0 ,0
Exp/Cntr=0.3,0.1

Type RM Length L Ch R = 1 ,3339    ,545,545,545
BEGIN DESCRIPTION:
BASSET CREEK 6.0
END DESCRIPTION:
XS GIS Cut Line= 3
      3736249.62     10622860.18      3735749.61     10623410.19
      3735399.63     10623510.18
#Sta/Elev= 30
    4297  327.53  4325.1  324.51  4347.6  319.24  4396.1  312.32  4523.7  298.05
  4650.8  291.68  4814.4  287.09  4948.1  286.58  4962.3  285.94  4969.7  281.96
  4976.5  285.69  4983.9   277.2  4995.1  275.38  4997.8  274.88  5001.1  275.38
  5033.2  280.98  5036.9  284.77  5081.9  283.21    5091  277.83  5102.7  282.84
  5113.1  277.81  5123.5  276.19    5130  278.53  5135.2  283.57  5144.3  283.91
  5154.7  279.55  5196.3  292.58  5353.6  318.47  5403.3     324  5404.3     324
#Mann= 7 ,-1 , 0
    4297     .08       0  4347.6     .12       0  4396.1     .16       0
  4814.4     .12       0  4995.1     .07       0  5001.1     .12       0
  5403.3     .16       0
Bank Sta=4976.5,5036.9
XS Rating Curve= 0 ,0
Exp/Cntr=0.3,0.1

Type RM Length L Ch R = 1 ,2794    ,494,494,494
BEGIN DESCRIPTION:
BASSET CREEK 5.0
END DESCRIPTION:
XS GIS Cut Line= 3
      3735899.65     10622810.16      3735549.61     10623060.19
      3735349.62     10623360.17
#Sta/Elev= 30
  4565.9  314.81  4588.1  312.66  4629.9  305.96  4644.6  305.33  4685.4  300.27
  4724.5  294.48    4738  290.06  4760.1  286.13  4855.8  283.66  4902.7   282.9
  4959.2  284.66  4973.9   282.3  4982.5  280.05    4990  273.72  4992.7  273.22
    4996  273.72  5009.6  274.37  5024.6  282.67  5045.6  283.49  5060.7  285.84
  5090.7  286.71  5111.7  285.42  5162.8  289.33  5248.5  301.26    5262  304.74
    5277  305.85  5284.5  308.36  5313.1     312  5320.6  314.55  5356.6  319.94
#Mann= 5 ,-1 , 0
  4565.9     .12       0  4685.4     .16       0  4855.8     .12       0
    4990     .07       0    4996     .12       0
Bank Sta=4973.9,5024.6
XS Rating Curve= 0 ,0
Exp/Cntr=0.3,0.1

Type RM Length L Ch R = 1 ,2300    ,436,436,436
BEGIN DESCRIPTION:
BASSET CREEK 4.0
END DESCRIPTION:
XS GIS Cut Line= 3
      3735899.63     10622760.19      3735499.61     10622660.19
      3735149.65     10622760.18
#Sta/Elev= 30
  4581.1  315.05  4591.4  314.26    4612  309.66  4645.6  306.26  4653.3  304.06
  4686.8  300.85  4764.1  287.56  4787.3  285.28  4838.8  281.51    4911  282.34
    4929  283.79  4934.2  282.46  4952.2  281.32  4983.1  280.59  4990.9  274.44
    4996  274.44  5000.8  272.43  5003.6  271.93  5006.8  272.43  5024.6  280.75
    5035  283.29  5088.3  282.67  5149.4  285.64  5161.1  289.06  5189.7  292.02
  5201.4  294.36  5315.8   307.2  5335.3  310.27  5354.8  316.74  5357.4  316.74
#Mann= 3 ,-1 , 0
  4581.1     .12       0  5000.8     .07       0  5006.8     .12       0
Bank Sta=4983.1,5024.6
XS Rating Curve= 0 ,0
Exp/Cntr=0.3,0.1

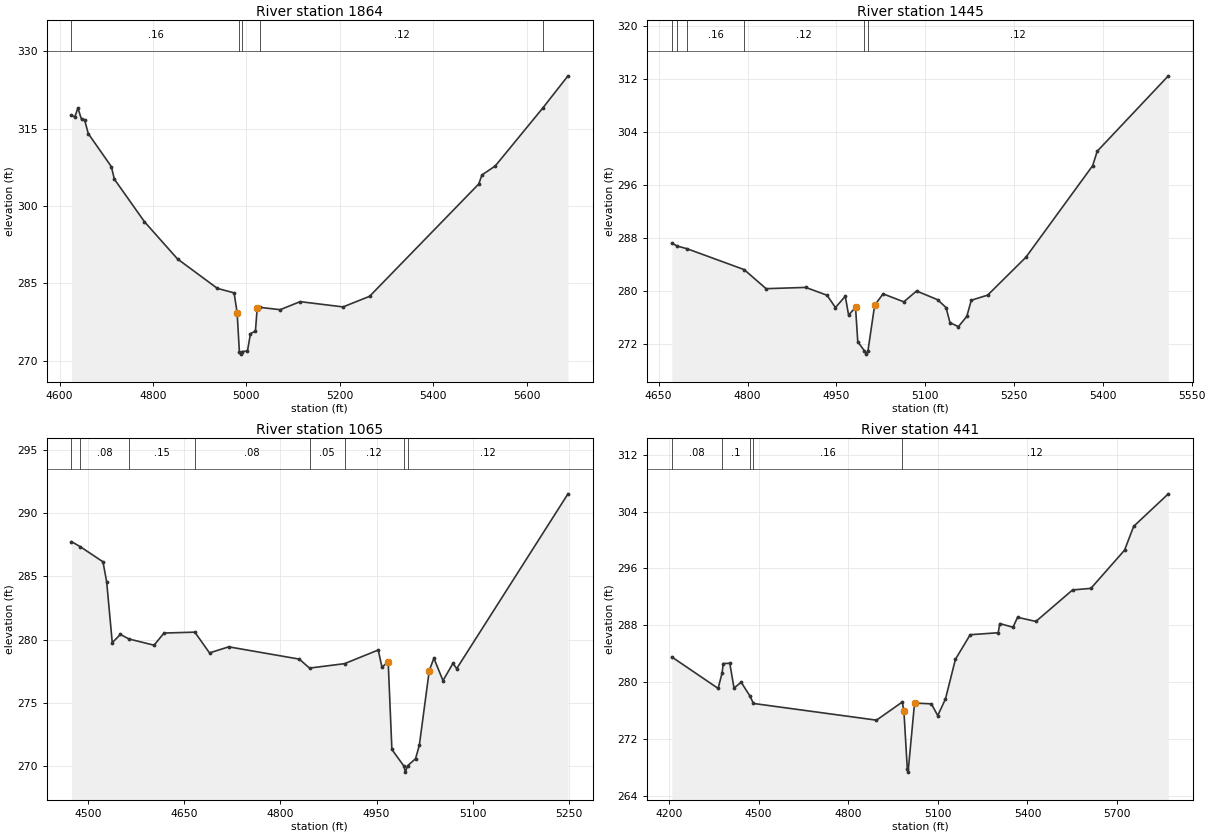
Type RM Length L Ch R = 1 ,1864    ,419,419,419
BEGIN DESCRIPTION:
BASSET CREEK 3.0
END DESCRIPTION:
XS GIS Cut Line= 3
       3735749.6     10622010.19      3735449.61     10622260.19
       3734999.6      10622760.2
#Sta/Elev= 30
  4625.6  317.57  4632.7  317.27  4639.3  318.98  4647.1  316.79  4653.6  316.73
  4661.4  314.05  4710.9  307.64  4717.4  305.21  4781.8  296.96  4852.7  289.74
    4938  284.04  4973.8  283.17  4980.3  279.34  4985.1   271.8  4987.9   271.3
  4991.1   271.8  5002.4   271.9  5008.9  275.28  5019.5  275.75  5023.2  280.18
  5029.4  280.36  5072.5  279.91  5115.1  281.47  5207.1  280.45  5263.9   282.5
  5497.8  304.28  5504.5  306.02  5532.9  307.75  5635.4  319.06  5688.8  325.23
#Mann= 5 ,-1 , 0
  4625.6     .16       0  4985.1     .07       0  4991.1     .16       0
  5029.4     .12       0  5635.4     .16       0
Bank Sta=4980.3,5023.2
XS Rating Curve= 0 ,0
Exp/Cntr=0.3,0.1

Type RM Length L Ch R = 1 ,1445    ,380,380,380
BEGIN DESCRIPTION:
BASSET CREEK 2.0
END DESCRIPTION:
XS GIS Cut Line= 3
       3735473.5     10621821.76      3735199.61     10621960.19
       3734799.6     10622310.19
#Sta/Elev= 30
  4672.2  287.25  4681.2  286.82  4698.6  286.39  4794.3  283.27  4831.4   280.4
  4898.3  280.59  4934.3  279.41  4948.5  277.56  4965.1  279.26  4970.7  276.42
  4982.4   277.6  4986.2  272.41  4997.4  271.05  5000.2  270.55  5003.4  271.05
  5014.7  277.91  5028.9  279.62    5064  278.42  5085.4  280.05    5121  278.74
  5135.2  277.56  5141.9  275.29  5156.1  274.68  5170.3  276.23  5177.9  278.66
  5205.5  279.43    5270  285.12  5382.9  298.92  5390.5  301.08  5510.6  312.43
#Mann= 6 ,-1 , 0
  4672.2     .16       0  4681.2     .12       0  4698.6     .16       0
  4794.3     .12       0  4997.4     .07       0  5003.4     .12       0
Bank Sta=4982.4,5014.7
XS Rating Curve= 0 ,0
Exp/Cntr=0.3,0.1

Type RM Length L Ch R = 1 ,1065    ,624,624,624
BEGIN DESCRIPTION:
Mapping XS 0f68d174
END DESCRIPTION:
XS GIS Cut Line= 2
      3735354.14     10621528.36      3734690.34     10621927.39
#Sta/Elev= 30
  4474.1  287.75  4487.6  287.36  4523.2  286.16    4529  284.57  4537.7  279.77
  4550.4  280.42  4563.8  280.06  4602.9  279.57  4618.4  280.53  4666.5   280.6
  4689.4  278.96  4719.4  279.44  4829.4  278.47  4845.4  277.76    4900  278.11
  4952.6  279.19  4958.4  277.83  4968.1  278.26  4973.9  271.33  4992.3  270.04
    4995  269.54  4998.3  270.04  5010.8   270.6  5016.7  271.66  5032.2  277.57
  5039.4  278.54  5053.6  276.77  5069.1  278.13    5075  277.72  5248.6  291.53
#Mann= 8 ,-1 , 0
  4474.1      .1       0  4487.6     .08       0  4563.8     .15       0
  4666.5     .08       0  4845.4     .05       0    4900     .12       0
  4992.3     .07       0  4998.3     .12       0
Bank Sta=4968.1,5032.2
XS Rating Curve= 0 ,0
Exp/Cntr=0.3,0.1

Type RM Length L Ch R = 1 ,441     ,0,0,0
BEGIN DESCRIPTION:
BASSET CREEK 1.0
END DESCRIPTION:
XS GIS Cut Line= 4
      3735238.92     10621523.81      3734610.43     10621264.22
      3734447.24     10621434.36       3734603.5     10622163.56
#Sta/Elev= 30
  4209.8  283.55  4364.7  279.13  4377.6  281.24  4382.2  282.63  4403.8  282.66
  4417.9  279.17  4441.8     280  4471.4  278.04  4482.9  277.01  4894.7  274.66
  4981.2  277.22  4986.5  275.89  4997.7  267.85  5000.4  267.35    5022  277.06
  5078.3  276.96  5099.7   275.3  5125.5  277.65  5158.9  283.23  5208.3  286.68
  5302.1  286.96  5307.2  288.25  5351.5  287.73  5366.7  289.13  5428.1  288.55
  5550.8  292.98  5612.2   293.2  5724.7  298.57  5755.4  301.93  5871.3   306.5
#Mann= 5 ,-1 , 0
  4209.8     .08       0  4377.6      .1       0  4471.4     .05       0
  4482.9     .16       0  4981.2     .12       0
Bank Sta=4986.5,5022
XS Rating Curve= 0 ,0
Exp/Cntr=0.3,0.1

Chan Stop Cuts=-1
Use User Specified Reach Order=0
Composite Channel Slope=5