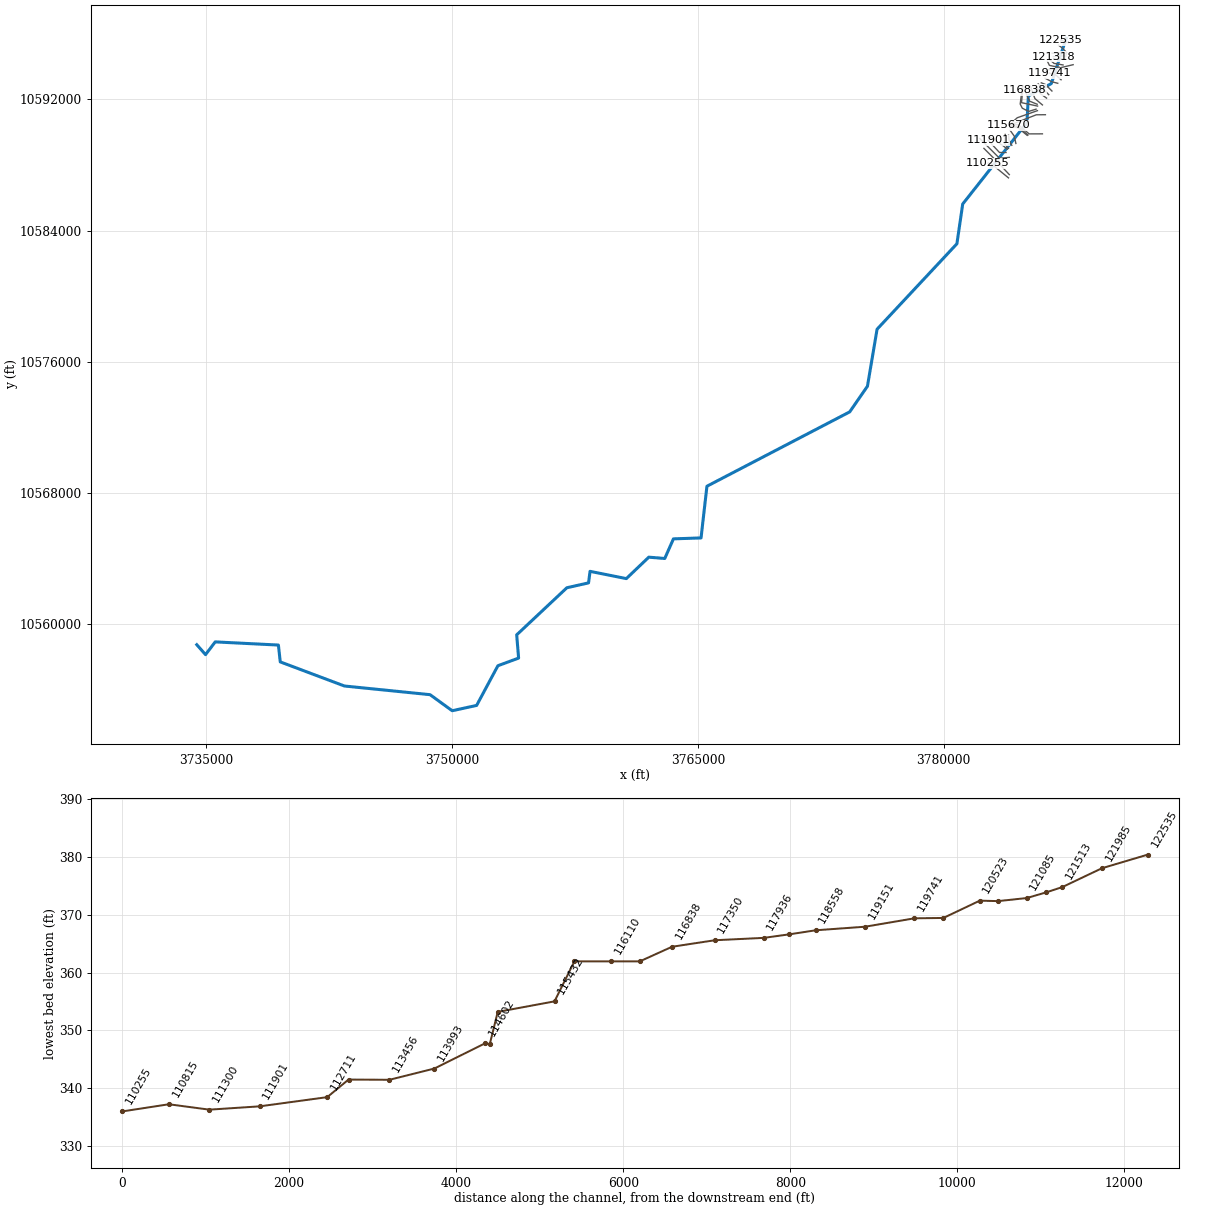
--- BOX CREEK.prj (project) ---

Proj Title=BOX CREEK Base Level Engineering
Current Plan=p01
Default Exp/Contr=0.3,0.1
English Units
Geom File=g01
Flow File=f01
Plan File=p01
Y Axis Title=Elevation
X Axis Title(PF)=Main Channel Distance
X Axis Title(XS)=Station
BEGIN DESCRIPTION:
BOX CREEK
END DESCRIPTION:
DSS Export Rating Curves= 0
DSS Export Rating Curve Sorted= 0
DSS Export Volume Flow Curves= 0
DXF OffsetX= 0
DXF OffsetY= 0
DXF ScaleX= 1
DXF ScaleY= 10

--- BOX CREEK.p01 (plan) ---

Plan Title=Multiple Run
Short Identifier=Multiple
Geom File=g01
Flow File=f01
Subcritical Flow
K Sum by GR= 0
Std Step Tol= 0.01
Critical Tol= 0.01
Num of Std Step Trials= 20
Max Error Tol= 0.3
Flow Tol Ratio= 0.001
Split Flow NTrial= 30
Split Flow Tol= 0.02
Split Flow Ratio= 0.02
Log Output Level= 0
Friction Slope Method= 1
Unsteady Friction Slope Method= 2
Unsteady Bridges Friction Slope Method= 1
Parabolic Critical Depth
Global Vel Dist=  1 , 1 , 1
Global Log Level= 0
CheckData=True
Encroach Param= -1, 0, 0, 0
BEGIN DESCRIPTION:
Multiple Run
END DESCRIPTION:

--- BOX CREEK.f01 (steady flow) ---

Flow Title=Multiple
Program Version=4.10
Number of Profiles= 7
Profile Names=10-year,25-year,50-year,1pct_min,100-year,1pct_plu,500-year
River Rch & RM=BOX CREEK,Reach-1         ,122535
     775    1069    1318    1194    1615    2184    2434
River Rch & RM=BOX CREEK,Reach-1         ,121085
    1038    1449    1799    1640    2218    2999    3384
River Rch & RM=BOX CREEK,Reach-1         ,116110
    1632    2320    2916    2686    3632    4913    5660
River Rch & RM=BOX CREEK,Reach-1         ,110815
    1939    2779    3511    3250    4395    5944    6916
River Rch & RM=BOX CREEK,Reach-1         ,108766
    1939    2779    3511    3250    4395    5944    6916
River Rch & RM=BOX CREEK,Reach-1         ,107316
    2394    3453    4380    4066    5499    7436    8706
River Rch & RM=BOX CREEK,Reach-1         ,106768
    2394    3453    4380    4066    5499    7436    8706
River Rch & RM=BOX CREEK,Reach-1         ,101965
    2906    4205    5347    4972    6724    9094   10679
River Rch & RM=BOX CREEK,Reach-1         ,94582
    3031    4391    5587    5198    7030    9507   11177
River Rch & RM=BOX CREEK,Reach-1         ,93501
    3031    4391    5587    5198    7030    9507   11177
River Rch & RM=BOX CREEK,Reach-1         ,90420
    3012    4352    5528    5132    6941    9387   10991
River Rch & RM=BOX CREEK,Reach-1         ,85815
    3093    4470    5678    5271    7129    9641   11286
River Rch & RM=BOX CREEK,Reach-1         ,84639
    3093    4470    5678    5271    7129    9641   11286
River Rch & RM=BOX CREEK,Reach-1         ,81699
    4081    5952    7606    7101    9604   12988   15373
River Rch & RM=BOX CREEK,Reach-1         ,80358
    4081    5952    7606    7101    9604   12988   15373
River Rch & RM=BOX CREEK,Reach-1         ,79883
    4201    6123    7822    7298    9869   13347   15779
River Rch & RM=BOX CREEK,Reach-1         ,77876
    4201    6123    7822    7298    9869   13347   15779
River Rch & RM=BOX CREEK,Reach-1         ,73243
    4384    6385    8153    7601   10280   13902   16410
River Rch & RM=BOX CREEK,Reach-1         ,66340
    4572    6659    8502    7926   10718   14495   17103
River Rch & RM=BOX CREEK,Reach-1         ,62917
    4611    6709    8560    7973   10783   14582   17179
River Rch & RM=BOX CREEK,Reach-1         ,58831
    4789    6977    8909    8305   11232   15190   17923
River Rch & RM=BOX CREEK,Reach-1         ,56091
    4895    7133    9110    8493   11486   15533   18331
River Rch & RM=BOX CREEK,Reach-1         ,53372
    4953    7204    9191    8558   11574   15652   18423
River Rch & RM=BOX CREEK,Reach-1         ,52762
    4953    7204    9191    8558   11574   15652   18423
River Rch & RM=BOX CREEK,Reach-1         ,44738
    5129    7464    9525    8871   11997   16224   19104
River Rch & RM=BOX CREEK,Reach-1         ,40464
    5253    7647    9760    9090   12293   16625   19580
River Rch & RM=BOX CREEK,Reach-1         ,39240
    5413    7877   10052    9359   12657   17116   20143
River Rch & RM=BOX CREEK,Reach-1         ,37724
    5413    7877   10052    9359   12657   17116   20143
River Rch & RM=BOX CREEK,Reach-1         ,35111
    5440    7907   10082    9378   12683   17152   20149
River Rch & RM=BOX CREEK,Reach-1         ,34578
    5440    7907   10082    9378   12683   17152   20149
River Rch & RM=BOX CREEK,Reach-1         ,30369
    5592    8138   10386    9670   13078   17687   20815
River Rch & RM=BOX CREEK,Reach-1         ,29571
    5592    8138   10386    9670   13078   17687   20815
River Rch & RM=BOX CREEK,Reach-1         ,27873
    5666    8244   10520    9793   13244   17911   21069
River Rch & RM=BOX CREEK,Reach-1         ,24890
    5808    8453   10789   10044   13583   18370   21612
River Rch & RM=BOX CREEK,Reach-1         ,19960
    5745    8347   10641    9893   13380   18094   21234
River Rch & RM=BOX CREEK,Reach-1         ,17202
    5860    8523   10874   10119   13684   18506   21753
River Rch & RM=BOX CREEK,Reach-1         ,14413
    5913    8595   10960   10193   13785   18643   21889
River Rch & RM=BOX CREEK,Reach-1         ,8357
    6016    8744   11149   10368   14021   18962   22258
Boundary for River Rch & Prof#=BOX CREEK,Reach-1         , 1
Up Type= 0
Dn Type= 3
Dn Slope=0.003
Boundary for River Rch & Prof#=BOX CREEK,Reach-1         , 2
Up Type= 0
Dn Type= 3
Dn Slope=0.003
Boundary for River Rch & Prof#=BOX CREEK,Reach-1         , 3
Up Type= 0
Dn Type= 3
Dn Slope=0.003
Boundary for River Rch & Prof#=BOX CREEK,Reach-1         , 4
Up Type= 0
Dn Type= 3
Dn Slope=0.003
Boundary for River Rch & Prof#=BOX CREEK,Reach-1         , 5
Up Type= 0
Dn Type= 3
Dn Slope=0.003
Boundary for River Rch & Prof#=BOX CREEK,Reach-1         , 6
Up Type= 0
Dn Type= 3
Dn Slope=0.003
Boundary for River Rch & Prof#=BOX CREEK,Reach-1         , 7
Up Type= 0
Dn Type= 3
Dn Slope=0.003
DSS Import GetInterval= 0
DSS Import GetPeak= 0
DSS Import FillOption= 0

--- BOX CREEK.g01 (geometry) ---

Geom Title=Existing Conditions
Program Version=4.10

River Reach=BOX CREEK       ,Reach-1
Reach XY= 30
        3787469.       10595732.       3786561.5       10592964.
        3785162.       10592212.       3785073.5       10590579.
       3781155.5       10585616.       3780801.5       10583191.
      3775931.25       10577978.      3775344.25       10574501.
      3774262.25       10572936.      3765551.25       10568399.
      3765192.25       10565246.      3763509.25       10565189.
        3762979.       10563992.      3762005.25       10564072.
      3760634.75       10562764.      3758421.25       10563207.
      3758328.75       10562503.      3757006.75       10562206.
       3753945.5       10559333.        3754062.       10557914.
        3752800.       10557450.        3751501.       10555027.
      3750010.25       10554704.      3748659.75       10555683.
      3743436.75       10556212.      3739520.75       10557683.
      3739408.75       10558710.      3735554.75       10558903.
        3734963.       10558126.      3734428.25       10558732.

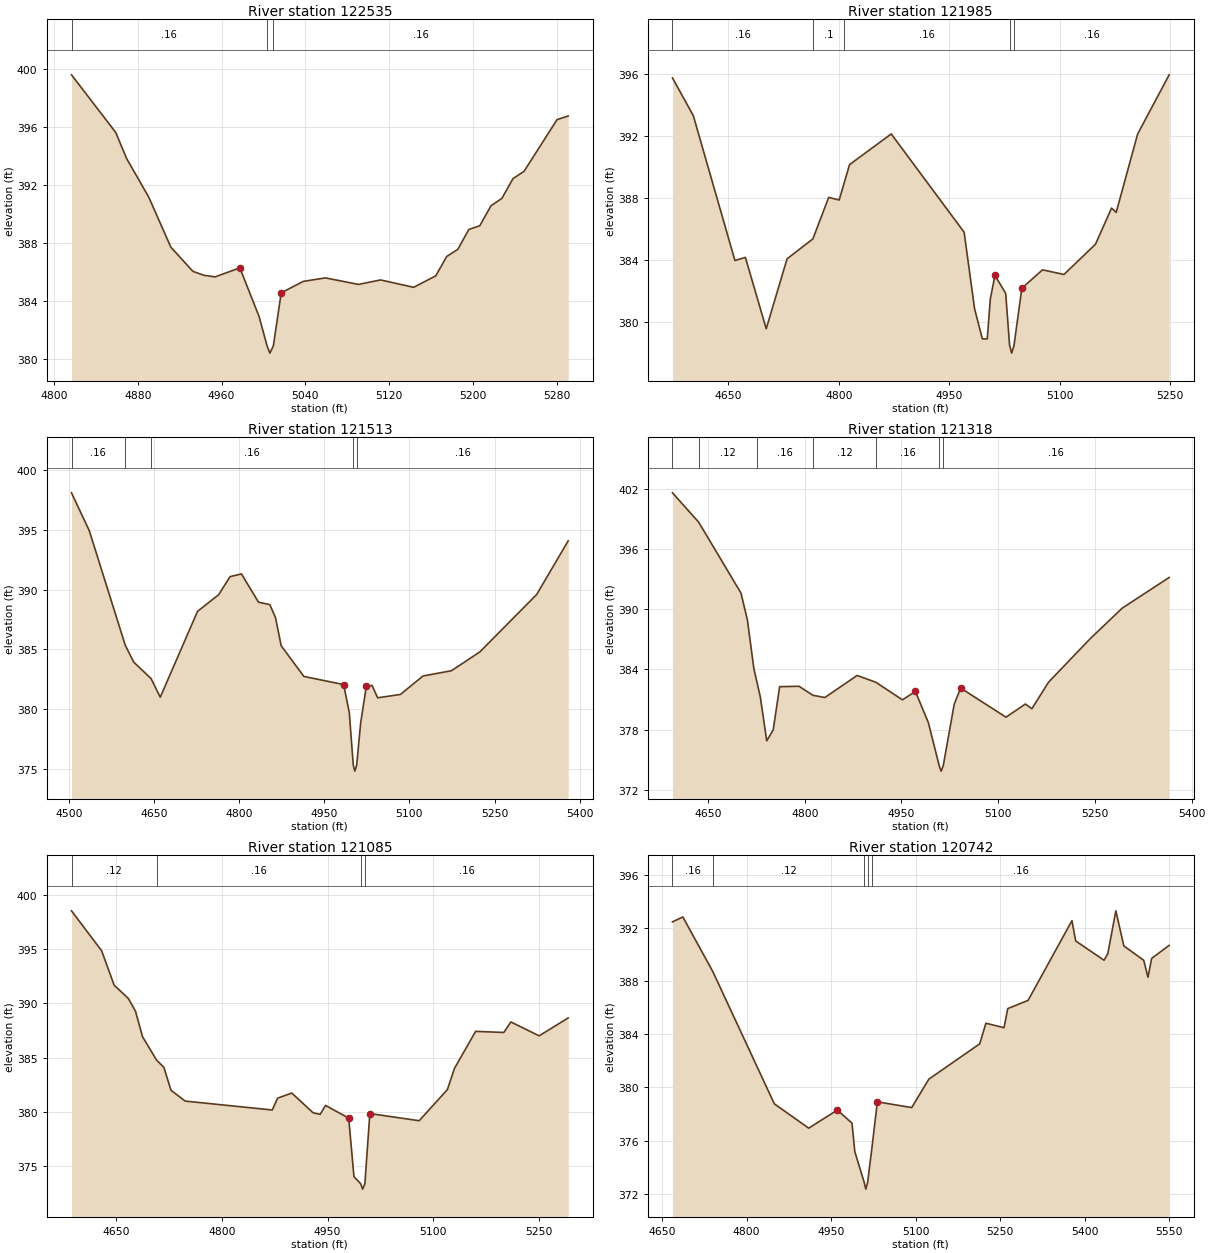
Type RM Length L Ch R = 1 ,122535  ,550,550,550
BEGIN DESCRIPTION:
BOX CREEK 178.0
END DESCRIPTION:
XS GIS Cut Line= 3
      3787599.63     10595460.18      3787449.61     10595510.19
      3787149.58      10595610.2
#Sta/Elev= 30
  4816.7  399.58  4858.9  395.61  4869.4   393.8  4890.5  391.14  4911.6  387.69
  4932.7  386.02  4943.2  385.75  4953.8  385.64  4977.5  386.26  4995.9   382.9
  5003.5  380.88  5006.2  380.38  5009.5  380.88    5017  384.54  5038.1  385.33
  5059.2  385.57  5090.8  385.12  5111.9  385.43  5143.5  384.92  5164.6  385.71
  5175.1  387.05  5185.7  387.54  5196.2  388.91  5206.7  389.17  5217.3  390.54
  5227.8  391.06  5238.4  392.42  5248.9  392.92  5280.5  396.49  5291.1  396.74
#Mann= 3 ,-1 , 0
  4816.7     .16       0  5003.5     .07       0  5009.5     .16       0
Bank Sta=4977.5,5017
XS Rating Curve= 0 ,0
Exp/Cntr=0.3,0.1

Type RM Length L Ch R = 1 ,121985  ,472,472,472
BEGIN DESCRIPTION:
BOX CREEK 177.0
END DESCRIPTION:
XS GIS Cut Line= 3
       3787499.6      10594860.2      3787199.61     10595160.19
      3786999.57     10595310.22
#Sta/Elev= 30
  4574.2  395.76  4602.5  393.33    4659  383.99  4673.2  384.19  4701.5  379.59
  4729.8   384.1  4764.8  385.38  4786.3  388.06  4800.5  387.89  4806.7  388.89
  4814.6  390.17  4871.2  392.15  4970.2  385.81  4984.3  380.89  4994.9  378.94
  5001.6  378.94  5005.7   381.5    5012  383.03  5026.6  381.87  5031.9  378.52
  5034.7  378.02  5037.9  378.52  5048.5   382.2  5076.6  383.39  5105.7  383.09
  5148.5  385.04  5170.3  387.37  5176.6  387.09  5205.7  392.14  5248.5  395.96
#Mann= 5 ,-1 , 0
  4574.2     .16       0  4764.8      .1       0  4806.7     .16       0
  5031.9     .07       0  5037.9     .16       0
Bank Sta=5012,5048.5
XS Rating Curve= 0 ,0
Exp/Cntr=0.3,0.1

Type RM Length L Ch R = 1 ,121513  ,195,195,195
BEGIN DESCRIPTION:
BOX CREEK 176.0
END DESCRIPTION:
XS GIS Cut Line= 3
      3787480.17     10594765.42      3787252.37     10594829.65
        3786614.     10594815.77
#Sta/Elev= 30
  4504.6  398.12  4535.9  394.95  4599.3  385.34  4614.3  383.92    4645  382.53
    4661  380.98  4726.7  388.18    4764  389.58    4784  391.09  4804.1  391.32
  4834.1  388.95  4854.1  388.74  4864.1  387.65  4874.1  385.29  4914.1  382.72
  4984.1  382.04  4994.1  379.69  5001.1  375.28  5003.8  374.78  5007.1  375.28
  5014.1  378.81  5024.1  381.88  5034.1  381.97  5044.1  380.93  5084.1  381.21
  5124.1  382.76  5174.1   383.2  5224.2  384.78  5324.2  389.59  5379.8  394.09
#Mann= 5 ,-1 , 0
  4504.6     .16       0  4599.3     .12       0    4645     .16       0
  5001.1     .07       0  5007.1     .16       0
Bank Sta=4984.1,5024.1
XS Rating Curve= 0 ,0
Exp/Cntr=0.3,0.1

Type RM Length L Ch R = 1 ,121318  ,233,233,233
BEGIN DESCRIPTION:
Mapping XS 06c6665b
END DESCRIPTION:
XS GIS Cut Line= 3
      3787455.73     10594644.12       3787197.5      10594652.8
      3786687.52      10594609.4
#Sta/Elev= 30
  4594.9   401.6  4635.5  398.68  4701.1  391.61  4711.1  388.93  4721.1  384.08
  4726.1  382.67  4731.1  381.26  4741.1  376.87  4751.1  377.96  4761.1  382.27
  4791.1  382.31  4812.8  381.41  4831.2  381.19  4881.3  383.39  4910.3  382.71
  4951.5  380.96  4971.6  381.79  4991.7  378.69  5008.7  374.35  5011.5  373.85
  5014.7  374.35  5031.8  380.52  5041.8  382.13  5112.1  379.23  5142.2  380.54
  5152.2  380.07  5178.1  382.72  5242.6  387.05  5292.3   390.1  5365.1  393.16
#Mann= 7 ,-1 , 0
  4594.9     .16       0  4635.5     .12       0  4726.1     .16       0
  4812.8     .12       0  4910.3     .16       0  5008.7     .07       0
  5014.7     .16       0
Bank Sta=4971.6,5041.8
XS Rating Curve= 0 ,0
Exp/Cntr=0.3,0.1

Type RM Length L Ch R = 1 ,121085  ,343,343,343
BEGIN DESCRIPTION:
BOX CREEK 175.0
END DESCRIPTION:
XS GIS Cut Line= 3
      3787399.63     10594510.19      3786999.61     10594460.19
      3786698.36       10594464.
#Sta/Elev= 30
  4586.9  398.54  4629.7  394.85  4647.4  391.68  4667.5  390.46  4677.6  389.29
  4687.7  386.92  4707.5  384.78  4717.9   384.1    4728  381.99  4748.2  380.99
  4871.6  380.17  4879.2  381.26  4899.3  381.73  4929.6  379.91  4939.6  379.77
  4947.2  380.59    4980  379.42  4987.5  374.02    4997  373.37  4999.8  372.87
    5003  373.37    5010  379.84    5080  379.18    5120  382.05    5130     384
    5160  387.42    5200  387.32    5210  388.29  5250.1  387.01  5291.3  388.66
#Mann= 4 ,-1 , 0
  4586.9     .12       0  4707.5     .16       0    4997     .07       0
    5003     .16       0
Bank Sta=4980,5010
XS Rating Curve= 0 ,0
Exp/Cntr=0.3,0.1

Type RM Length L Ch R = 1 ,120742  ,219,219,219
BEGIN DESCRIPTION:
BOX CREEK 174.0
END DESCRIPTION:
XS GIS Cut Line= 3
       3787277.7     10594099.72      3786725.27     10594197.21
      3786483.49      10594407.5
#Sta/Elev= 30
  4668.5  392.46  4686.9  392.83  4740.2  388.71  4849.3  378.76  4910.3  376.93
    4961  378.29  4987.1  377.31  4992.1  375.16  5008.8  372.84  5011.6  372.34
  5014.8  372.84  5022.3  375.39  5032.1  378.91  5093.1  378.48  5123.5  380.62
  5213.8  383.28  5224.7  384.83  5256.9  384.49  5263.5  385.93  5299.6  386.55
  5377.4  392.55  5384.1  391.02  5434.4  389.57  5441.1  390.07  5455.3  393.29
  5469.5  390.65  5504.7  389.57  5512.3  388.29  5518.9  389.71  5549.9  390.69
#Mann= 5 ,-1 , 0
  4668.5     .16       0  4740.2     .12       0  5008.8     .07       0
  5014.8     .12       0  5022.3     .16       0
Bank Sta=4961,5032.1
XS Rating Curve= 0 ,0
Exp/Cntr=0.3,0.1

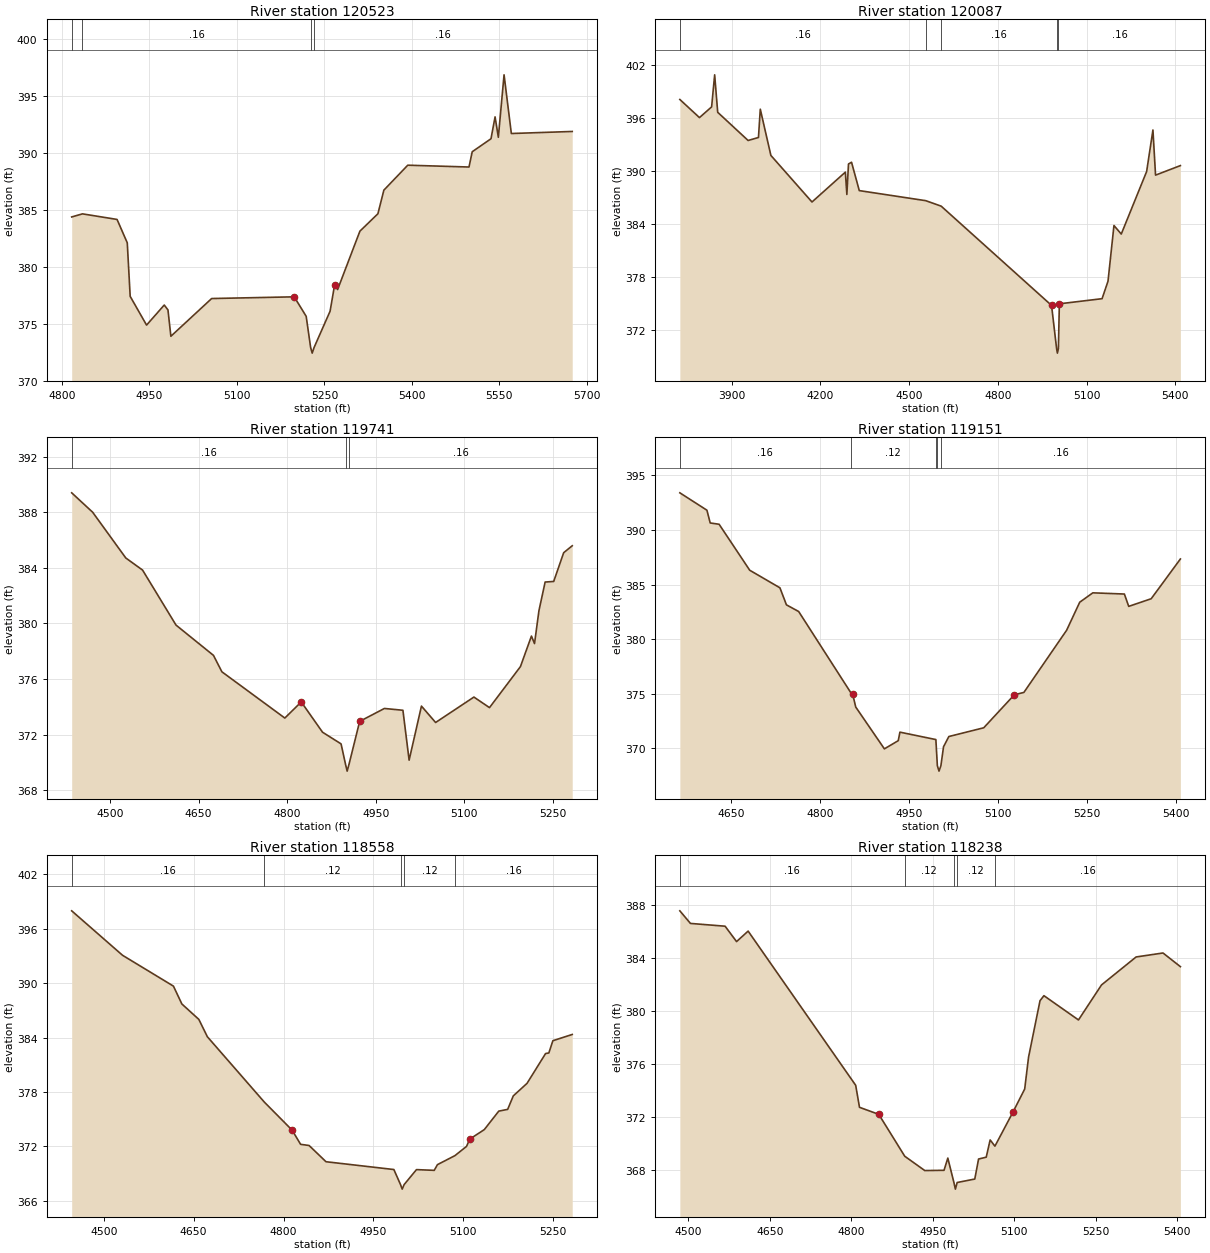
Type RM Length L Ch R = 1 ,120523  ,436,436,436
BEGIN DESCRIPTION:
Mapping XS ac85f886
END DESCRIPTION:
XS GIS Cut Line= 4
      3787026.61     10593971.03      3786689.34     10594020.51
      3786445.85      10594075.2      3786326.06     10594314.78
#Sta/Elev= 30
  4816.6  384.37  4835.1  384.64  4894.4  384.15  4911.9   382.1  4916.9   377.4
    4945  374.88  4975.3  376.64  4981.7  376.21  4986.7   373.9  5056.6  377.21
  5198.2  377.36  5218.7  375.65  5226.3  372.92    5229  372.42  5232.3  372.92
  5259.7   376.1  5267.5  378.42  5272.6     378  5310.8  383.12  5341.7  384.65
  5351.9  386.72  5392.9  388.91  5497.9  388.75  5503.4  390.09  5535.6  391.23
  5542.6  393.15  5548.2  391.36    5558  396.84  5570.5  391.69  5674.9  391.87
#Mann= 4 ,-1 , 0
  4816.6     .12       0  4835.1     .16       0  5226.3     .07       0
  5232.3     .16       0
Bank Sta=5198.2,5267.5
XS Rating Curve= 0 ,0
Exp/Cntr=0.3,0.1

Type RM Length L Ch R = 1 ,120087  ,346,346,346
BEGIN DESCRIPTION:
BOX CREEK 173.0
END DESCRIPTION:
XS GIS Cut Line= 3
      3787894.04     10594117.07      3786774.27     10593847.98
      3786236.03     10593795.89
#Sta/Elev= 30
  3724.6  398.13  3790.9  396.08    3832  397.29  3842.3  400.92  3852.6  396.68
  3955.4  393.49  3990.4  393.83  3996.6  397.03  4032.4   391.8  4171.4  386.53
  4284.2  389.91  4289.3  387.38  4294.8  390.83  4305.1  391.03  4331.3  387.82
    4556  386.68  4608.2  386.06  4981.4  374.83  4998.5  369.93  5001.2  369.43
  5004.5  369.93  5007.8  375.01  5152.2  375.59  5172.3  377.57  5192.4  383.87
  5217.1   382.9  5302.9  389.98  5324.2  394.68    5333  389.57    5417  390.65
#Mann= 5 ,-1 , 0
  3724.6     .16       0    4556     .12       0  4608.2     .16       0
  4998.5     .07       0  5004.5     .16       0
Bank Sta=4981.4,5007.8
XS Rating Curve= 0 ,0
Exp/Cntr=0.3,0.1

Type RM Length L Ch R = 1 ,119741  ,590,590,590
BEGIN DESCRIPTION:
BOX CREEK 172.0
END DESCRIPTION:
XS GIS Cut Line= 3
      3787156.24     10593196.91       3786852.4     10593474.71
      3786435.77     10593604.91
#Sta/Elev= 30
  4434.9   389.4  4470.5     388  4526.6  384.71    4555  383.84  4611.7  379.88
  4675.2   377.7  4689.4  376.52  4796.1  373.19  4823.9  374.35    4860  372.17
  4891.4  371.33  4898.9  369.87  4901.7  369.37  4904.9  369.87  4922.9  372.95
  4964.8  373.88  4996.2  373.75  5006.7  370.16  5027.6  374.05  5051.6  372.87
  5116.5   374.7  5142.9  373.94  5195.3  376.89    5214  379.09  5219.2  378.55
  5226.7  380.92  5237.2  382.98  5251.7  383.02  5268.6  385.09  5283.1  385.59
#Mann= 3 ,-1 , 0
  4434.9     .16       0  4898.9     .07       0  4904.9     .16       0
Bank Sta=4823.9,4922.9
XS Rating Curve= 0 ,0
Exp/Cntr=0.3,0.1

Type RM Length L Ch R = 1 ,119151  ,593,593,593
BEGIN DESCRIPTION:
BOX CREEK 171.0
END DESCRIPTION:
XS GIS Cut Line= 3
      3786953.75     10592982.43      3786599.59      10593072.7
      3786176.02     10593294.91
#Sta/Elev= 30
  4563.8  393.41  4609.4  391.82    4615  390.65    4630  390.53  4681.6  386.32
  4732.5  384.71  4743.5  383.15  4764.1  382.54  4851.7  375.13  4855.1  374.98
  4860.3  373.79  4908.6  369.96    4932  370.71  4934.8  371.49  4995.4  370.81
  4997.9  368.42  5000.7  367.92  5003.9  368.42  5008.3  370.15  5017.3  371.09
  5076.1  371.89  5127.6  374.91  5143.8  375.13  5215.8  380.82  5237.9  383.39
    5260  384.25  5313.2  384.14  5320.5  383.01  5358.4  383.71  5407.6  387.35
#Mann= 5 ,-1 , 0
  4563.8     .16       0  4851.7     .12       0  4995.4     .16       0
  4997.9     .07       0  5003.9     .16       0
Bank Sta=4855.1,5127.6
XS Rating Curve= 0 ,0
Exp/Cntr=0.3,0.1

Type RM Length L Ch R = 1 ,118558  ,320,320,320
BEGIN DESCRIPTION:
BOX CREEK 170.0
END DESCRIPTION:
XS GIS Cut Line= 3
      3786599.59      10592510.2      3786199.61     10592910.19
      3785949.63     10593010.18
#Sta/Elev= 30
  4446.6  397.98  4531.4  393.08  4616.3  389.68  4630.4  387.71  4658.7  386.01
  4672.9   384.1    4768  376.89  4814.3   373.8  4828.4  372.24  4842.6  372.11
  4870.8  370.32    4984  369.46  4995.1   367.8  4997.9   367.3  5001.1   367.8
  5021.7  369.45  5051.3  369.37  5056.7     370  5085.8  370.99  5105.2  372.01
  5110.5  372.81  5134.8  373.86    5159   375.9  5173.8  376.09  5183.2  377.58
  5206.1  378.96  5237.1  382.25  5242.5  382.31  5249.2  383.66  5281.5  384.35
#Mann= 5 ,-1 , 0
  4446.6     .16       0    4768     .12       0  4995.1     .07       0
  5001.1     .12       0  5085.8     .16       0
Bank Sta=4814.3,5110.5
XS Rating Curve= 0 ,0
Exp/Cntr=0.3,0.1

Type RM Length L Ch R = 1 ,118238  ,302,302,302
BEGIN DESCRIPTION:
BOX CREEK 169.0
END DESCRIPTION:
XS GIS Cut Line= 2
      3786405.13       10592288.      3785760.57     10592946.42
#Sta/Elev= 30
  4484.4  387.58  4503.9  386.63  4567.7  386.42  4588.8  385.26  4610.1  386.05
  4808.1  374.42  4815.1  372.76  4850.6  372.23  4898.4  369.07  4935.3  367.99
  4970.7  368.01  4977.7  368.93  4988.9  367.09  4991.6  366.59  4994.9  367.09
  5027.3  367.35  5034.3  368.86  5048.4     369  5055.6   370.3  5064.4  369.83
    5098  372.43  5119.2  374.14  5126.3  376.54  5147.4   380.8  5154.6  381.18
  5218.2  379.35  5260.6  381.99  5324.3   384.1  5373.8   384.4  5405.8  383.37
#Mann= 5 ,-1 , 0
  4484.4     .16       0  4898.4     .12       0  4988.9     .07       0
  4994.9     .12       0  5064.4     .16       0
Bank Sta=4850.6,5098
XS Rating Curve= 0 ,0
Exp/Cntr=0.3,0.1

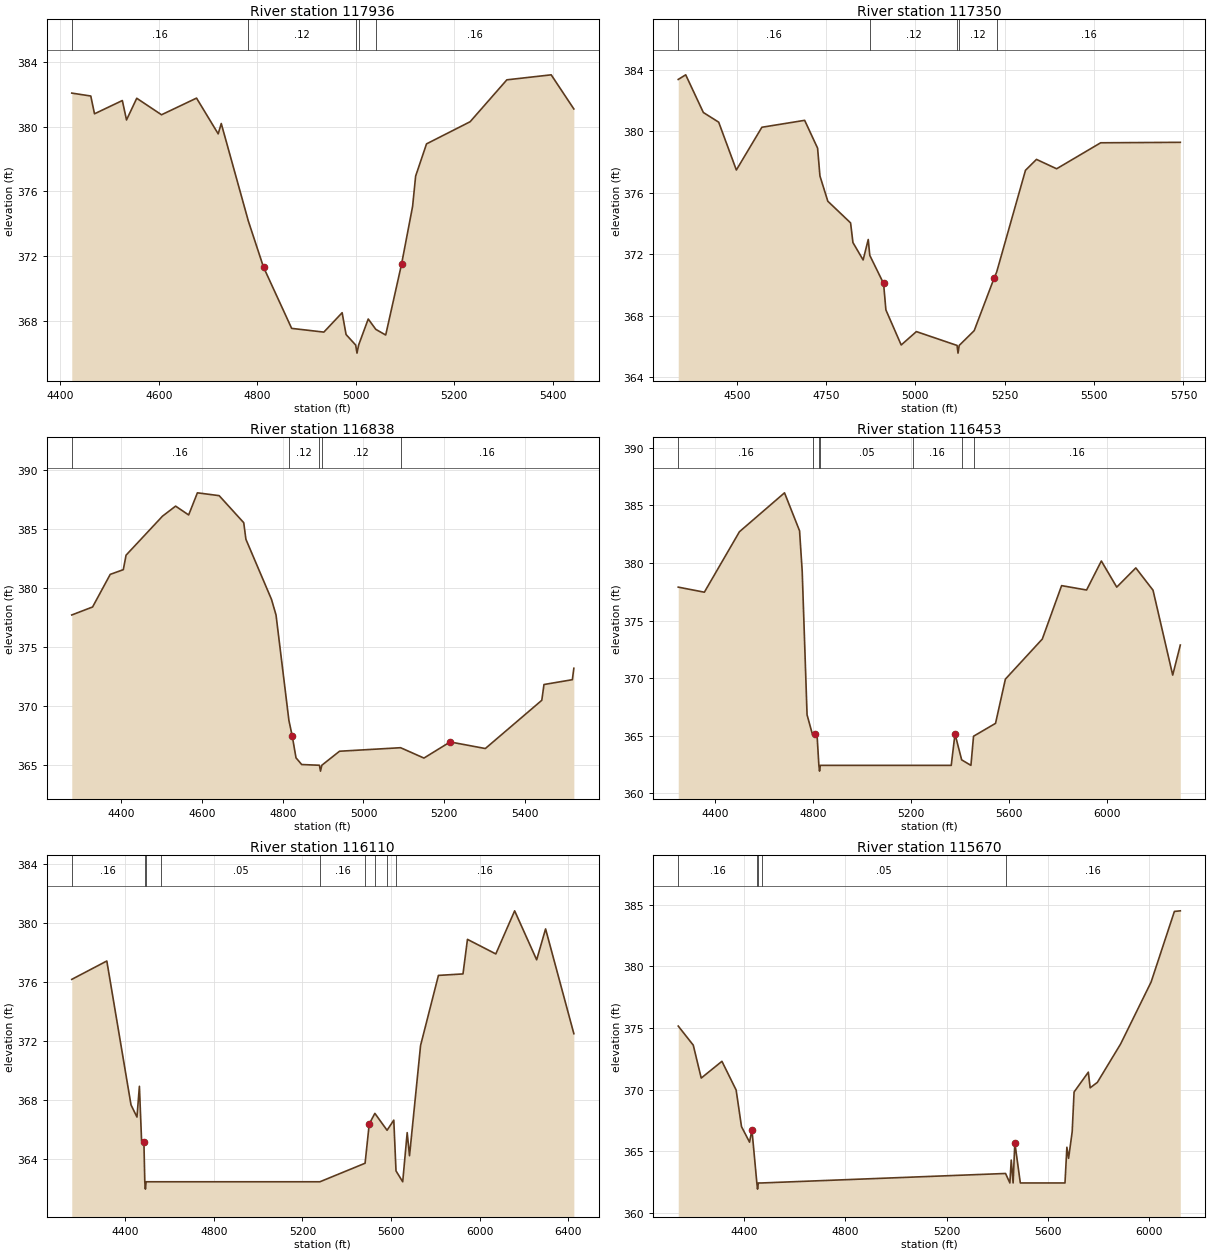
Type RM Length L Ch R = 1 ,117936  ,586,586,586
BEGIN DESCRIPTION:
BOX CREEK 168.0
END DESCRIPTION:
XS GIS Cut Line= 3
      3786270.82     10592077.13      3785888.85     10592354.92
      3785637.13     10592841.01
#Sta/Elev= 30
  4423.3  382.07  4461.9  381.89  4469.5  380.79    4526  381.61  4534.5  380.41
  4555.3  381.75  4605.6  380.73  4676.7  381.76  4720.7  379.55  4726.9  380.19
  4781.9  374.16  4812.7  371.31  4869.9  367.52  4935.3  367.29  4972.4  368.49
  4980.4  367.14  4999.9  366.49  5002.6  365.99  5005.9  366.49  5025.4   368.1
  5040.8  367.46  5060.9  367.11    5093  371.48  5115.5  375.06  5121.7  376.94
  5143.8  378.93  5232.4   380.3  5306.9  382.89    5397   383.2    5443  381.09
#Mann= 5 ,-1 , 0
  4423.3     .16       0  4781.9     .12       0  4999.9     .07       0
  5005.9     .12       0  5040.8     .16       0
Bank Sta=4812.7,5093
XS Rating Curve= 0 ,0
Exp/Cntr=0.3,0.1

Type RM Length L Ch R = 1 ,117350  ,512,512,512
BEGIN DESCRIPTION:
BOX CREEK 167.0
END DESCRIPTION:
XS GIS Cut Line= 3
      3786019.09     10591660.45      3785558.99      10592051.1
      3785290.09     10592805.75
#Sta/Elev= 30
  4336.4  383.38  4357.3  383.68  4406.7  381.23  4449.6   380.6    4499  377.49
  4570.4  380.27  4690.1  380.72  4726.3  378.91  4732.9   377.1  4754.9  375.46
  4818.6  374.05  4825.2  372.77  4853.7  371.64    4868  372.97  4872.3  371.94
  4910.9  370.11  4917.4  368.39  4960.2  366.11  5002.7  366.98  5116.5  366.08
  5119.2  365.58  5122.5  366.08  5164.4  367.04  5220.7  370.49  5227.4  370.86
  5307.9  377.47  5338.7  378.18  5395.1  377.57  5518.3  379.26  5741.1  379.29
#Mann= 5 ,-1 , 0
  4336.4     .16       0  4872.3     .12       0  5116.5     .07       0
  5122.5     .12       0  5227.4     .16       0
Bank Sta=4910.9,5220.7
XS Rating Curve= 0 ,0
Exp/Cntr=0.3,0.1

Type RM Length L Ch R = 1 ,116838  ,385,385,385
BEGIN DESCRIPTION:
BOX CREEK 166.0
END DESCRIPTION:
XS GIS Cut Line= 3
      3785697.86     10591703.89      3785229.13     10591894.85
      3784934.29     10592571.25
#Sta/Elev= 30
  4277.2  377.72  4328.8   378.4  4372.5  381.17  4404.9  381.57  4411.7   382.8
  4502.1  386.12  4534.5  386.97  4566.8  386.22  4588.5   388.1  4642.4  387.86
  4703.3  385.56  4708.7  384.15    4772  379.05  4783.3  377.72  4815.2  368.76
  4823.5  367.43  4832.8  365.58  4846.9  365.01  4890.8  364.95  4893.5  364.45
  4896.8  364.95  4940.6  366.14  5091.9  366.44  5149.8  365.56  5214.6  366.93
  5301.9  366.37  5441.8  370.47  5447.2  371.81  5517.5  372.22  5521.2  373.19
#Mann= 5 ,-1 , 0
  4277.2     .16       0  4815.2     .12       0  4890.8     .07       0
  4896.8     .12       0  5091.9     .16       0
Bank Sta=4823.5,5214.6
XS Rating Curve= 0 ,0
Exp/Cntr=0.3,0.1

Type RM Length L Ch R = 1 ,116453  ,343,343,343
BEGIN DESCRIPTION:
BOX CREEK 165.0
END DESCRIPTION:
XS GIS Cut Line= 3
      3785723.88     10591591.04      3784743.02     10591799.36
      3784838.51     10592841.06
#Sta/Elev= 30
  4248.7  377.91  4355.3  377.47  4498.4  382.72  4682.4   386.1  4743.8   382.8
  4754.6  379.28  4774.4  366.82  4797.3  365.05  4805.1  365.16  4815.3  365.03
  4822.6  362.43  4825.3  361.93  4828.6  362.43    5205  362.43  5362.7  362.43
  5378.1  365.16  5405.3  362.91  5443.1  362.43  5453.7  364.96  5543.5  366.08
  5583.7  369.92  5734.3   373.4  5813.1  378.04    5915  377.66  5975.3  380.18
  6038.1  377.91  6115.9  379.58  6186.2  377.64  6266.5  370.27  6297.5  372.88
#Mann= 7 ,-1 , 0
  4248.7     .16       0  4797.3     .05       0  4822.6    .035       0
  4828.6     .05       0    5205     .16       0  5405.3     .12       0
  5453.7     .16       0
Bank Sta=4805.1,5378.1
XS Rating Curve= 0 ,0
Exp/Cntr=0.3,0.1

Type RM Length L Ch R = 1 ,116110  ,440,440,440
BEGIN DESCRIPTION:
Mapping XS 88a77a86
END DESCRIPTION:
XS GIS Cut Line= 6
      3785630.83     10591404.05      3785208.83      10591273.5
      3785129.89     10591285.65      3784789.88     10591464.76
      3784662.37      10591713.7      3784798.78     10592786.77
#Sta/Elev= 30
  4158.2  376.19  4316.5  377.44  4425.7  367.66  4452.6  366.83  4463.6  368.92
  4473.5   365.2    4484  365.13    4488  362.43  4490.7  361.93    4494  362.43
  4561.8  362.43  5278.8  362.43  5482.8  363.69  5501.5  366.36    5527  367.08
  5582.1  365.93  5612.4  366.62  5622.4  363.17  5652.7  362.43  5672.9  365.77
  5683.4   364.2  5733.4   371.7    5814  376.46  5924.9  376.56  5945.1  378.91
  6073.1  377.92  6158.2  380.85  6257.6  377.52  6297.9  379.62  6425.5   372.5
#Mann= 9 ,-1 , 0
  4158.2     .16       0    4488    .033       0    4494     .16       0
  4561.8     .05       0  5278.8     .16       0  5482.8     .12       0
    5527     .16       0  5582.1     .12       0  5622.4     .16       0
Bank Sta=4484,5501.5
XS Rating Curve= 0 ,0
Exp/Cntr=0.3,0.1

Type RM Length L Ch R = 1 ,115670  ,238,238,238
BEGIN DESCRIPTION:
BOX CREEK 164.0
END DESCRIPTION:
XS GIS Cut Line= 3
      3785715.28     10591313.27       3784482.6     10590879.23
       3783979.1     10590427.81
#Sta/Elev= 30
  4139.6  375.16    4199  373.61  4230.4  370.94  4312.2   372.3  4368.3  369.97
  4389.5     367  4421.3  365.74  4430.7  366.74  4450.1  362.43  4452.8  361.93
  4456.1  362.43  4469.3  362.43  5432.4   363.2  5449.5  362.43  5454.9  364.29
  5462.3  362.43  5469.1  365.69  5490.8  362.43  5667.2  362.43  5674.7  365.33
  5681.4  364.43  5695.6  366.58  5703.1  369.81  5759.4  371.42  5766.6  370.15
    5795  370.59    5887  373.71  6007.3  378.73  6099.3  384.46  6122.7  384.51
#Mann= 5 ,-1 , 0
  4139.6     .16       0  4450.1    .033       0  4456.1     .16       0
  4469.3     .05       0  5432.4     .16       0
Bank Sta=4430.7,5469.1
XS Rating Curve= 0 ,0
Exp/Cntr=0.3,0.1

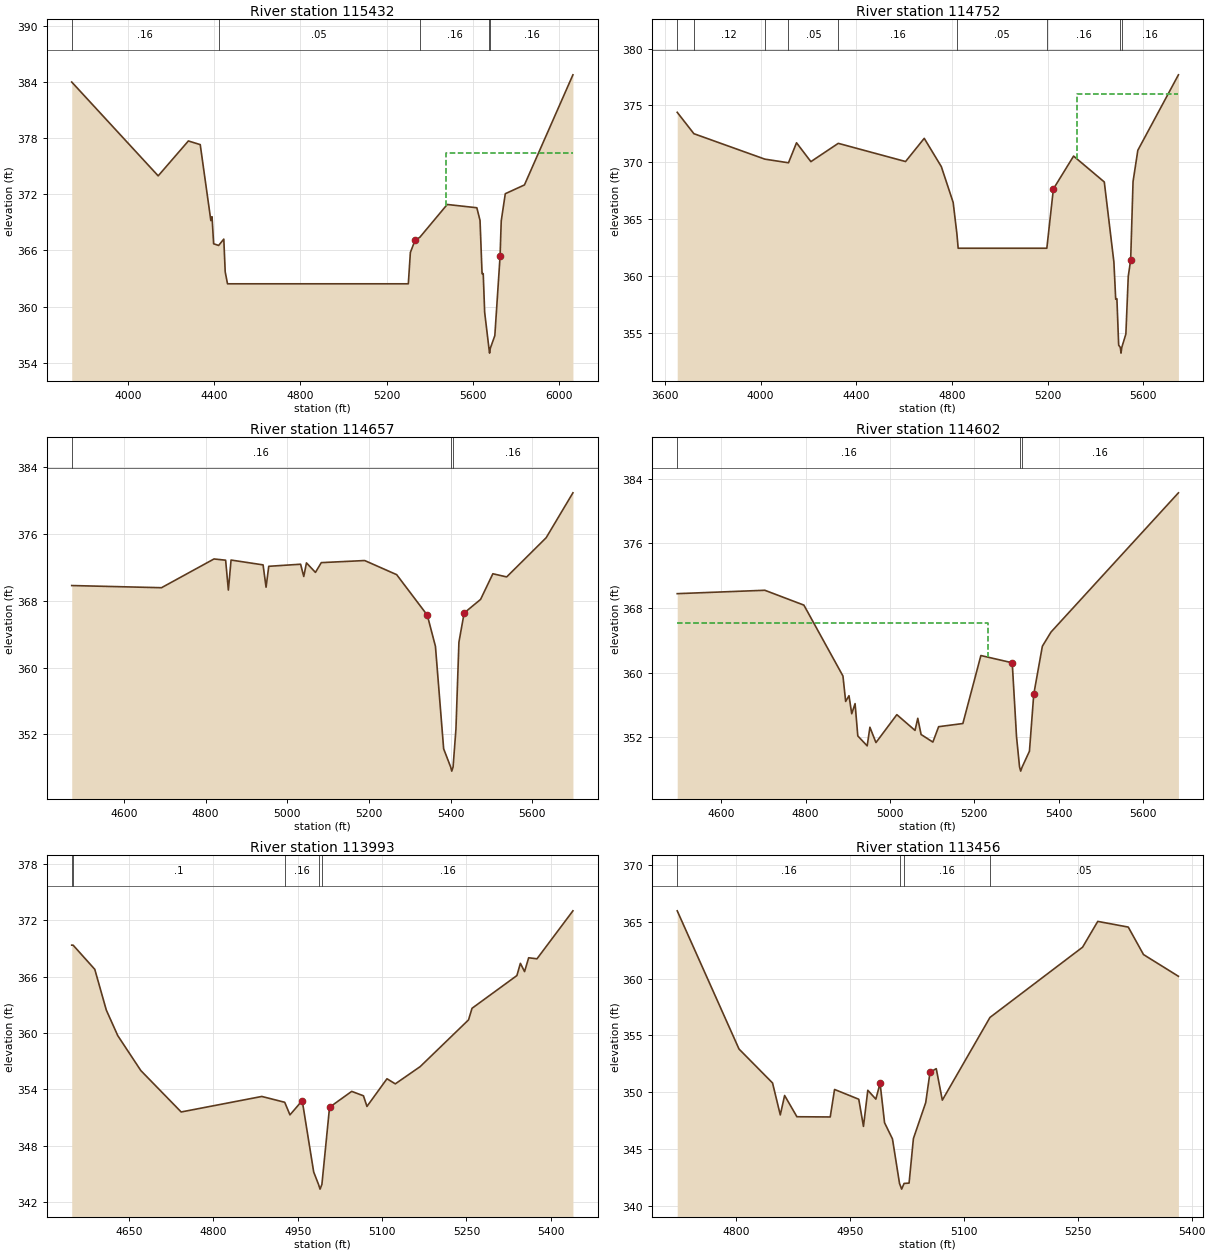
Type RM Length L Ch R = 1 ,115432  ,680,680,680
BEGIN DESCRIPTION:
BOX CREEK 163.0
END DESCRIPTION:
XS GIS Cut Line= 4
      3786200.63     10591065.01      3785649.61     10591060.19
      3784999.61     10590810.19       3783999.6     10590410.19
#Sta/Elev= 30
  3739.8     384  4140.8  373.97  4280.8   377.7  4335.8  377.31  4385.1  369.19
  4390.5   369.6    4398  366.71  4421.2  366.53  4445.1  367.21  4451.6  363.71
  4462.3  362.43  5300.9  362.43  5310.4  365.78  5331.9  367.07  5354.5  367.41
  5481.3  370.91  5618.7  370.56  5633.5   369.2  5642.9  363.51  5648.3  363.52
    5655  359.37  5674.9  355.52  5677.7  355.02  5680.9  355.52  5702.1  356.89
  5726.4  365.35  5731.8  369.15  5750.6  372.06  5839.5     373  6064.3  384.77
#Mann= 5 ,-1 , 0
  3739.8     .16       0  4421.2     .05       0  5354.5     .16       0
  5674.9    .033       0  5680.9     .16       0
#XS Ineff= 2 , 0
                         5477.27          376.36
Permanent Ineff=
       F       F
Bank Sta=5331.9,5726.4
XS Rating Curve= 0 ,0
Exp/Cntr=0.3,0.1

Type RM Length L Ch R = 1 ,114752  ,95,95,95
BEGIN DESCRIPTION:
BOX CREEK 162.0
END DESCRIPTION:
XS GIS Cut Line= 4
      3786018.31     10589897.47       3785208.3     10589894.85
      3784531.22     10590462.56      3784130.16     10590441.72
#Sta/Elev= 30
  3651.6  374.39  3721.2  372.51  4017.9  370.27  4116.7  369.95  4150.3  371.71
  4210.3  370.05  4324.8  371.66  4606.1  370.06  4684.2   372.1  4755.7  369.61
  4805.1  366.46  4820.7  363.71    4826  362.43  5196.7  362.43  5224.1  367.65
  5308.6  370.54  5436.9  368.26    5477  361.22  5484.6  357.94  5489.6  357.99
    5497   353.9    5504   353.7  5506.8   353.2    5510   353.7  5527.1  354.88
  5537.1  359.96  5547.1  361.39  5557.1   368.3  5577.1  371.05  5746.8  377.69
#Mann= 9 ,-1 , 0
  3651.6     .05       0  3721.2     .12       0  4017.9     .16       0
  4116.7     .05       0  4324.8     .16       0  4820.7     .05       0
  5196.7     .16       0    5504    .033       0    5510     .16       0
#XS Ineff= 2 , 0
                         5322.44          375.98
Permanent Ineff=
       F       F
Bank Sta=5224.1,5547.1
XS Rating Curve= 0 ,0
Exp/Cntr=0.3,0.1

Type RM Length L Ch R = 1 ,114657  ,55,55,55
BEGIN DESCRIPTION:
Mapping XS 7086f552
END DESCRIPTION:
XS GIS Cut Line= 3
      3785137.34     10589827.42      3784515.59     10590353.18
      3784104.35     10590389.62
#Sta/Elev= 30
  4472.2  369.81    4692  369.55  4820.6  372.99    4849  372.84  4855.7  369.27
  4862.3  372.86  4940.7  372.28    4948  369.61  4954.6  372.11  5032.6  372.36
  5040.3  370.89  5046.9  372.52  5068.9  371.38  5083.2  372.55  5189.5   372.8
  5267.8  371.11  5342.7  366.27  5362.7  362.54  5382.8  350.28  5399.9  348.11
  5402.6  347.61  5405.9  348.11  5412.9  352.65  5420.2  363.04    5433  366.53
  5473.2  368.15  5503.3  371.22  5537.1  370.84  5633.8  375.53  5699.3   380.9
#Mann= 3 ,-1 , 0
  4472.2     .16       0  5399.9     .07       0  5405.9     .16       0
Bank Sta=5342.7,5433
XS Rating Curve= 0 ,0
Exp/Cntr=0.3,0.1

Type RM Length L Ch R = 1 ,114602  ,609,609,609
BEGIN DESCRIPTION:
BOX CREEK 161.0
END DESCRIPTION:
XS GIS Cut Line= 3
      3785088.47     10589806.33      3784528.61     10590264.64
      3784073.76     10590358.21
#Sta/Elev= 30
  4495.8  369.78  4703.4   370.2    4796  368.36  4888.6  359.57    4895  356.42
  4902.9  357.13  4909.4  354.89  4917.3  356.15  4923.8  352.14    4946  350.91
  4952.5  353.22  4966.8  351.32  5016.3  354.78  5059.4  352.83  5065.9  354.33
  5073.8  352.32  5101.7  351.38  5115.4  353.29  5172.8  353.68  5215.5  362.11
  5289.8  361.21    5300  352.03  5307.2  348.28  5309.9  347.78  5313.2  348.28
  5330.6  350.25  5340.8   357.3  5361.2  363.26  5381.7  365.02  5683.7  382.28
#Mann= 3 ,-1 , 0
  4495.8     .16       0  5307.2     .07       0  5313.2     .16       0
#XS Ineff= 2 , 0
         5232.47  366.15
Permanent Ineff=
       F       F
Bank Sta=5289.8,5340.8
XS Rating Curve= 0 ,0
Exp/Cntr=0.3,0.1

Type RM Length L Ch R = 1 ,113993  ,537,537,537
BEGIN DESCRIPTION:
BOX CREEK 160.0
END DESCRIPTION:
XS GIS Cut Line= 3
      3784399.61     10589310.19      3784299.61     10589760.19
       3784049.6      10590110.2
#Sta/Elev= 30
  4548.2  369.34  4550.7  369.34  4589.2  366.77  4609.7  362.44  4630.1  359.72
  4671.1  356.01  4742.8  351.61  4886.2  353.26  4926.9  352.64  4936.2   351.3
    4958  352.82  4978.4  345.23    4987  343.91  4989.7  343.41    4993  343.91
  5006.6  352.11    5046   353.8  5066.9  353.33  5073.1   352.2  5108.7  355.14
  5123.5   354.6  5167.7  356.43  5253.7   361.4  5259.9  362.63  5339.7  366.11
  5345.9  367.41  5353.3  366.53  5360.6     368  5375.4  367.89  5439.3  372.99
#Mann= 5 ,-1 , 0
  4548.2     .05       0  4550.7      .1       0  4926.9     .16       0
    4987     .07       0    4993     .16       0
Bank Sta=4958,5006.6
XS Rating Curve= 0 ,0
Exp/Cntr=0.3,0.1

Type RM Length L Ch R = 1 ,113456  ,490,490,490
BEGIN DESCRIPTION:
BOX CREEK 159.0
END DESCRIPTION:
XS GIS Cut Line= 3
      3784151.02     10589199.51      3783981.74     10589514.64
      3783953.16     10589815.96
#Sta/Elev= 30
  4722.2  365.96  4803.6   353.8  4847.8  350.81    4858     348  4863.7  349.71
  4879.9  347.84  4923.8  347.82  4929.5  350.24  4961.4  349.38  4967.6  346.99
  4973.3  350.17  4983.9  349.39  4989.5  350.78  4995.4  347.31  5005.8  345.89
  5015.1  341.97  5017.9  341.47  5021.1  341.97  5027.7     342  5033.4  345.92
  5049.6  349.08  5055.3  351.76  5063.5  352.07  5071.5   349.3  5134.3  356.58
  5256.3  362.76  5276.3  365.03  5316.5  364.53  5336.6  362.11  5382.6   360.2
#Mann= 4 ,-1 , 0
  4722.2     .16       0  5015.1     .07       0  5021.1     .16       0
  5134.3     .05       0
Bank Sta=4989.5,5055.3
XS Rating Curve= 0 ,0
Exp/Cntr=0.3,0.1

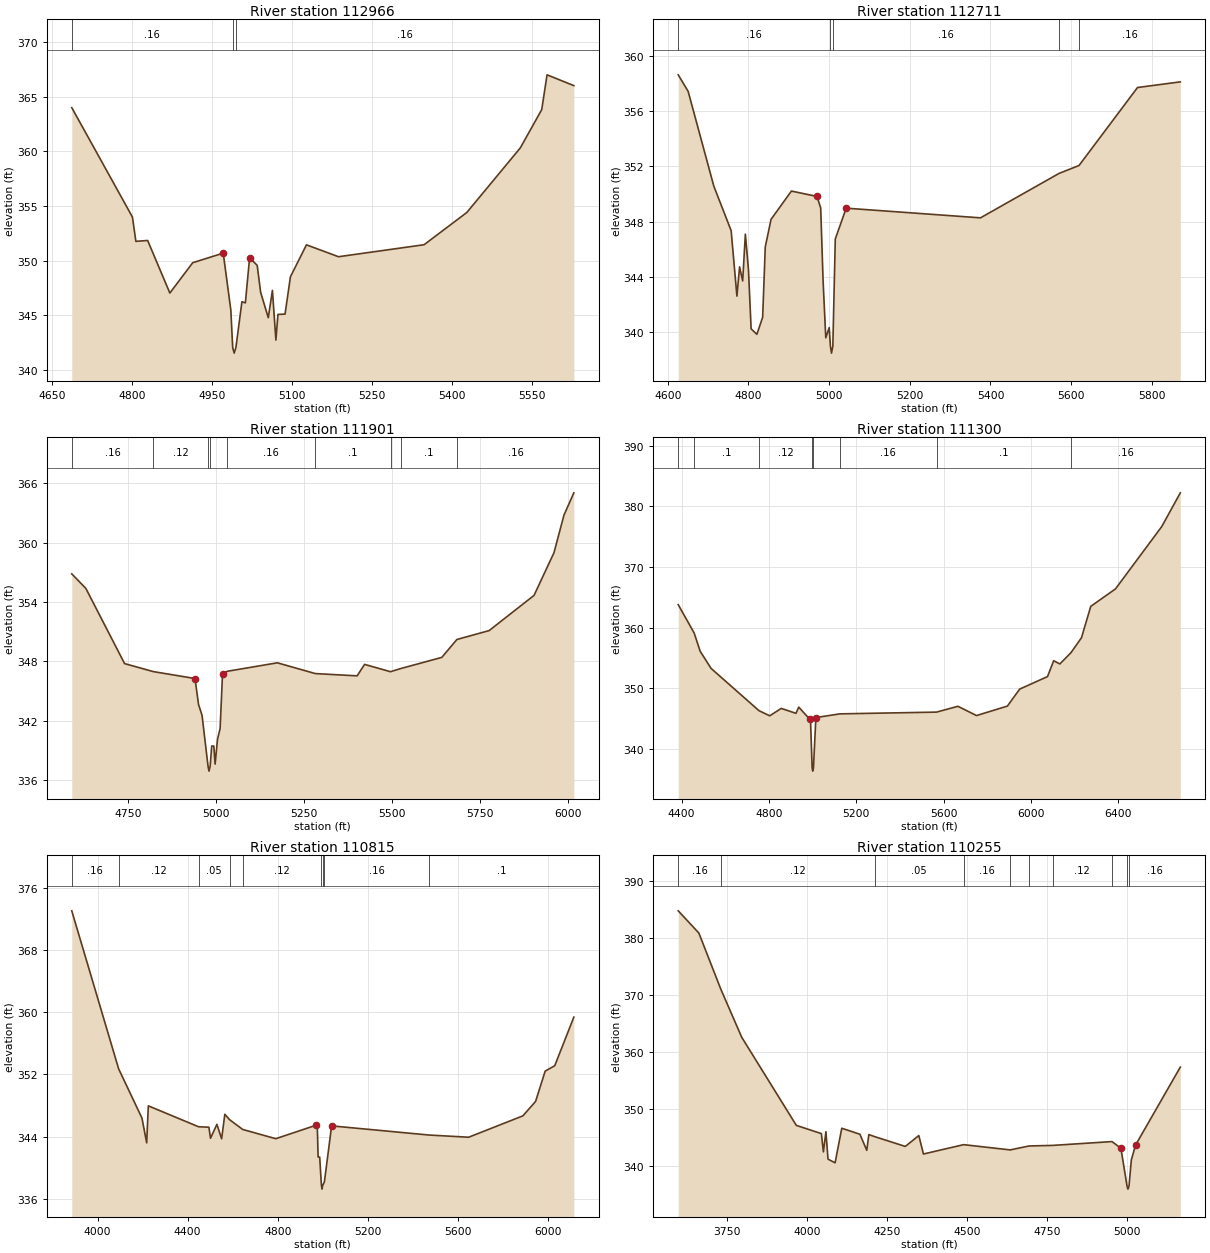
Type RM Length L Ch R = 1 ,112966  ,255,255,255
BEGIN DESCRIPTION:
BOX CREEK 158.0
END DESCRIPTION:
XS GIS Cut Line= 3
      3783949.59     10589010.21      3783699.61     10589310.19
      3783749.61     10589860.24
#Sta/Elev= 30
  4686.6  364.02  4800.5  353.99    4807  351.76  4829.1  351.84  4870.8  347.02
  4913.7   349.8    4971  350.68  4985.3  345.46  4988.8  342.01  4991.6  341.51
  4994.8  342.01  5006.1  346.22  5012.6  346.12  5020.5  350.25  5034.8  349.56
  5041.3  347.08  5055.6  344.76  5063.4  347.26  5069.9  342.71  5073.8  345.06
  5087.1  345.09  5097.2  348.51  5127.3  351.44  5187.5  350.35  5348.2  351.45
  5428.5  354.41  5528.9  360.33  5569.1  363.84  5579.1  367.03  5629.4  366.04
#Mann= 3 ,-1 , 0
  4686.6     .16       0  4988.8     .07       0  4994.8     .16       0
Bank Sta=4971,5020.5
XS Rating Curve= 0 ,0
Exp/Cntr=0.3,0.1

Type RM Length L Ch R = 1 ,112711  ,810,810,810
BEGIN DESCRIPTION:
BOX CREEK 157.0
END DESCRIPTION:
XS GIS Cut Line= 3
      3783864.56     10588970.36      3783637.99     10589160.48
      3782846.35     10589683.89
#Sta/Elev= 30
  4625.9  358.63  4650.5  357.43  4714.2  350.56  4757.1  347.34  4771.4   342.6
    4778  344.72  4785.7   343.7  4792.3  347.09    4800  344.52  4806.6  340.23
  4820.9  339.83  4835.2  341.07  4841.7  346.16    4856  348.16  4906.5  350.21
  4970.1  349.82  4979.1  348.98  4985.1  343.66  4991.7  339.58  5000.2  340.32
  5003.2  338.97  5005.9  338.47  5009.2  338.97  5015.3  346.74  5042.3  348.97
  5375.3  348.27  5570.1  351.49  5619.5  352.06  5764.6  357.71  5870.7  358.12
#Mann= 5 ,-1 , 0
  4625.9     .16       0  5003.2     .07       0  5009.2     .16       0
  5570.1      .1       0  5619.5     .16       0
Bank Sta=4970.1,5042.3
XS Rating Curve= 0 ,0
Exp/Cntr=0.3,0.1

Type RM Length L Ch R = 1 ,111901  ,601,601,601
BEGIN DESCRIPTION:
BOX CREEK 156.0
END DESCRIPTION:
XS GIS Cut Line= 3
      3783799.61     10588760.19      3783399.61     10588760.19
      3782699.62     10589510.17
#Sta/Elev= 30
  4589.8  356.84  4629.8  355.37  4739.8  347.76  4821.5  346.95  4939.8  346.25
  4949.8  343.63  4959.8  342.53  4976.8  337.38  4979.6  336.88  4982.8  337.38
  4987.3  339.42  4993.2  339.42  4996.9  337.59  5003.7   340.1  5011.1   341.2
  5017.9  346.67    5031  346.98  5173.7  347.84  5281.5  346.75  5400.2  346.52
  5421.4  347.68    5495  346.94  5524.2  347.26  5640.8  348.39  5683.6   350.2
  5775.1   351.1  5902.6  354.66  5959.3  358.98  5987.6  362.78  6015.7  365.04
#Mann= 9 ,-1 , 0
  4589.8     .16       0  4821.5     .12       0  4976.8     .07       0
  4982.8     .12       0    5031     .16       0  5281.5      .1       0
    5495     .16       0  5524.2      .1       0  5683.6     .16       0
Bank Sta=4939.8,5017.9
XS Rating Curve= 0 ,0
Exp/Cntr=0.3,0.1

Type RM Length L Ch R = 1 ,111300  ,485,485,485
BEGIN DESCRIPTION:
BOX CREEK 155.0
END DESCRIPTION:
XS GIS Cut Line= 3
      3783999.59     10588460.19      3783399.61     10588410.19
      3782199.62     10589610.18
#Sta/Elev= 30
  4384.3  363.78  4457.2  359.11  4484.6   356.1  4534.8  353.26    4754  346.29
  4803.2  345.44  4855.9  346.66  4923.6  345.85  4936.2  346.87  4986.4  344.88
  4989.9  344.88  4997.5  336.81  5000.2  336.31  5003.5  336.81  5014.6  345.15
  5124.8  345.76    5567  346.05  5665.2  347.01    5750  345.48  5891.5  347.04
    5948  349.85  6075.3  351.91  6103.6  354.53  6131.9     354    6183  355.87
  6230.9  358.33  6273.3   363.5  6386.4  366.38  6598.6  376.68  6683.4  382.24
#Mann= 8 ,-1 , 0
  4384.3     .05       0  4457.2      .1       0    4754     .12       0
  4997.5     .07       0  5003.5     .12       0  5124.8     .16       0
    5567      .1       0    6183     .16       0
Bank Sta=4986.4,5014.6
XS Rating Curve= 0 ,0
Exp/Cntr=0.3,0.1

Type RM Length L Ch R = 1 ,110815  ,560,560,560
BEGIN DESCRIPTION:
BOX CREEK 154.0
END DESCRIPTION:
XS GIS Cut Line= 3
      3783999.59     10587410.21      3783249.61     10588210.19
      3782449.63     10589010.17
#Sta/Elev= 30
  3885.8  373.06  4093.8  352.72  4197.2  346.39  4218.2   343.2  4225.5  347.96
  4448.2  345.27  4494.2  345.21  4501.5  343.79  4529.8  345.58  4550.8  343.72
    4565  346.88    4586  346.18  4644.3  344.92  4791.1  343.73  4968.4  345.45
  4975.3  345.36  4978.9  341.37  4985.9  341.37  4993.5  337.74  4996.3  337.24
  4999.5  337.74  5006.8  338.17  5038.9  345.38  5471.8   344.2    5647  343.92
  5887.5  346.67    5944  348.53  5986.5  352.43  6028.9  353.12  6113.7  359.38
#Mann= 9 ,-1 , 0
  3885.8     .16       0  4093.8     .12       0  4448.2     .05       0
    4586     .16       0  4644.3     .12       0  4993.5     .07       0
  4999.5     .12       0  5006.8     .16       0  5471.8      .1       0
Bank Sta=4968.4,5038.9
XS Rating Curve= 0 ,0
Exp/Cntr=0.3,0.1

Type RM Length L Ch R = 1 ,110255  ,498,498,498
BEGIN DESCRIPTION:
BOX CREEK 153.0
END DESCRIPTION:
XS GIS Cut Line= 3
      3783949.58     10587210.22      3782849.61     10588110.19
      3782699.63     10588110.19
#Sta/Elev= 30
  3596.4  384.82    3661  380.92  3729.9  371.04  3795.2  362.63    3966  347.18
  4044.3  345.74  4050.7  342.54  4058.6  346.08  4065.1  341.26  4087.3  340.62
  4108.2  346.68  4164.9  345.63  4186.4  342.81  4192.9  345.57  4211.6   345.2
    4307  343.49  4349.3   345.4  4363.7  342.16  4489.5   343.8  4635.4  342.88
  4694.2  343.57  4768.2  343.67  4953.9  344.34  4981.7  343.17    5001   336.5
  5003.7     336    5007   336.5  5014.4  341.15  5027.6  343.73  5167.6   357.4
#Mann= 10 ,-1 , 0
  3596.4     .16       0  3729.9     .12       0  4211.6     .05       0
  4489.5     .16       0  4635.4     .12       0  4694.2     .16       0
  4768.2     .12       0  4953.9     .16       0    5001     .07       0
    5007     .16       0
Bank Sta=4981.7,5027.6
XS Rating Curve= 0 ,0
Exp/Cntr=0.3,0.1