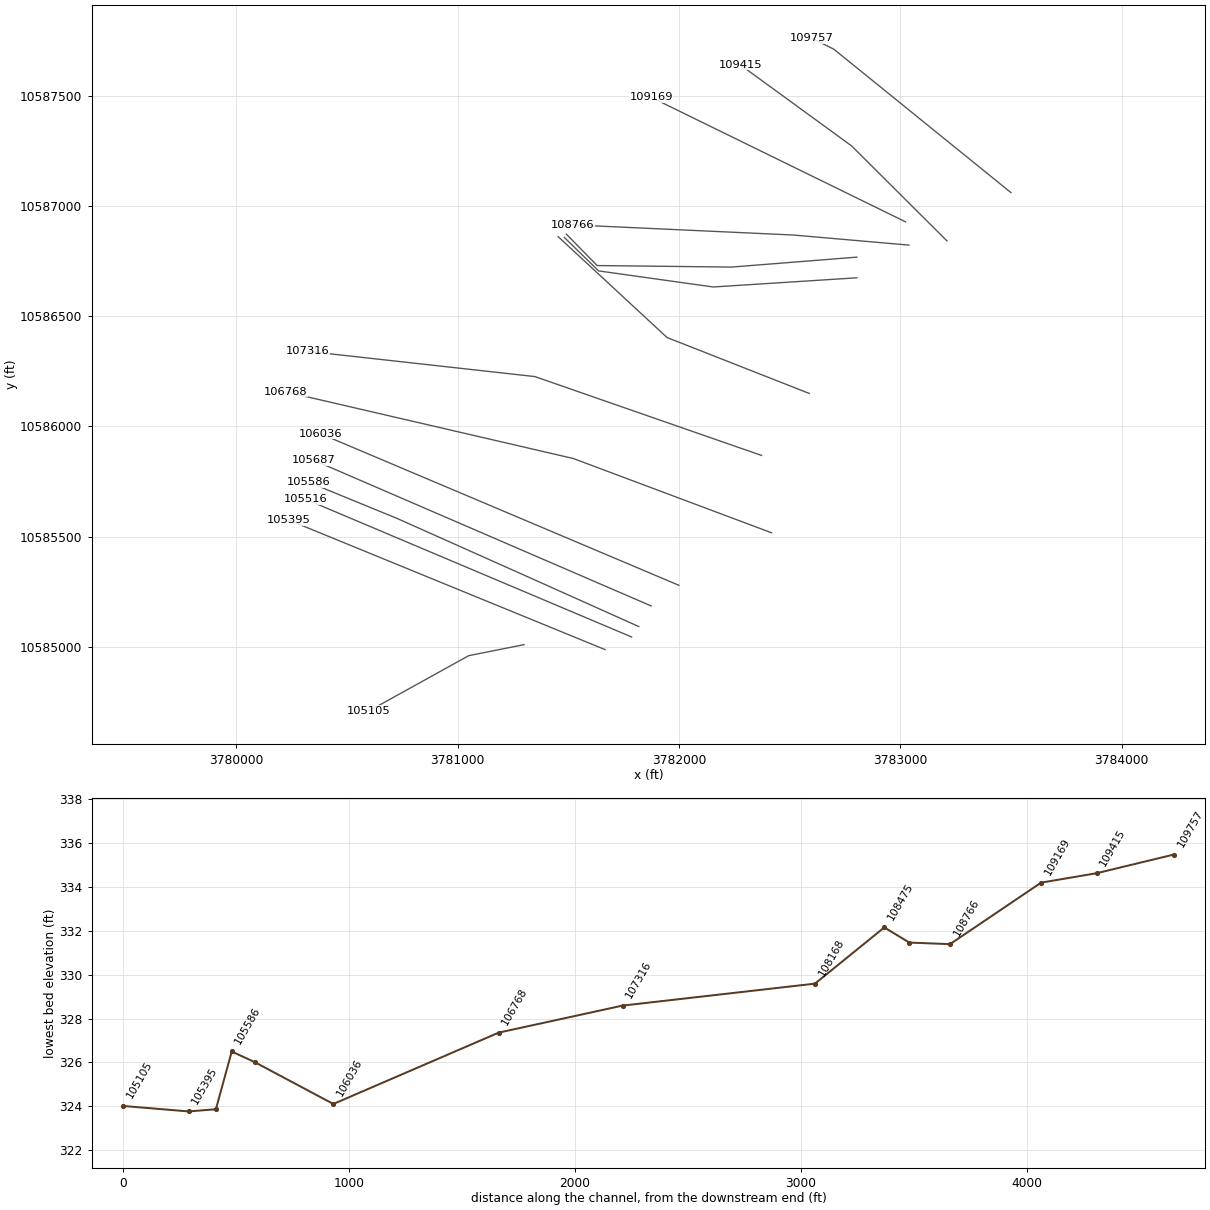
HEC-RAS study BOX CREEK.prj: BOX CREEK Base Level Engineering

--- BOX CREEK.g01 (geometry) --- (continued)

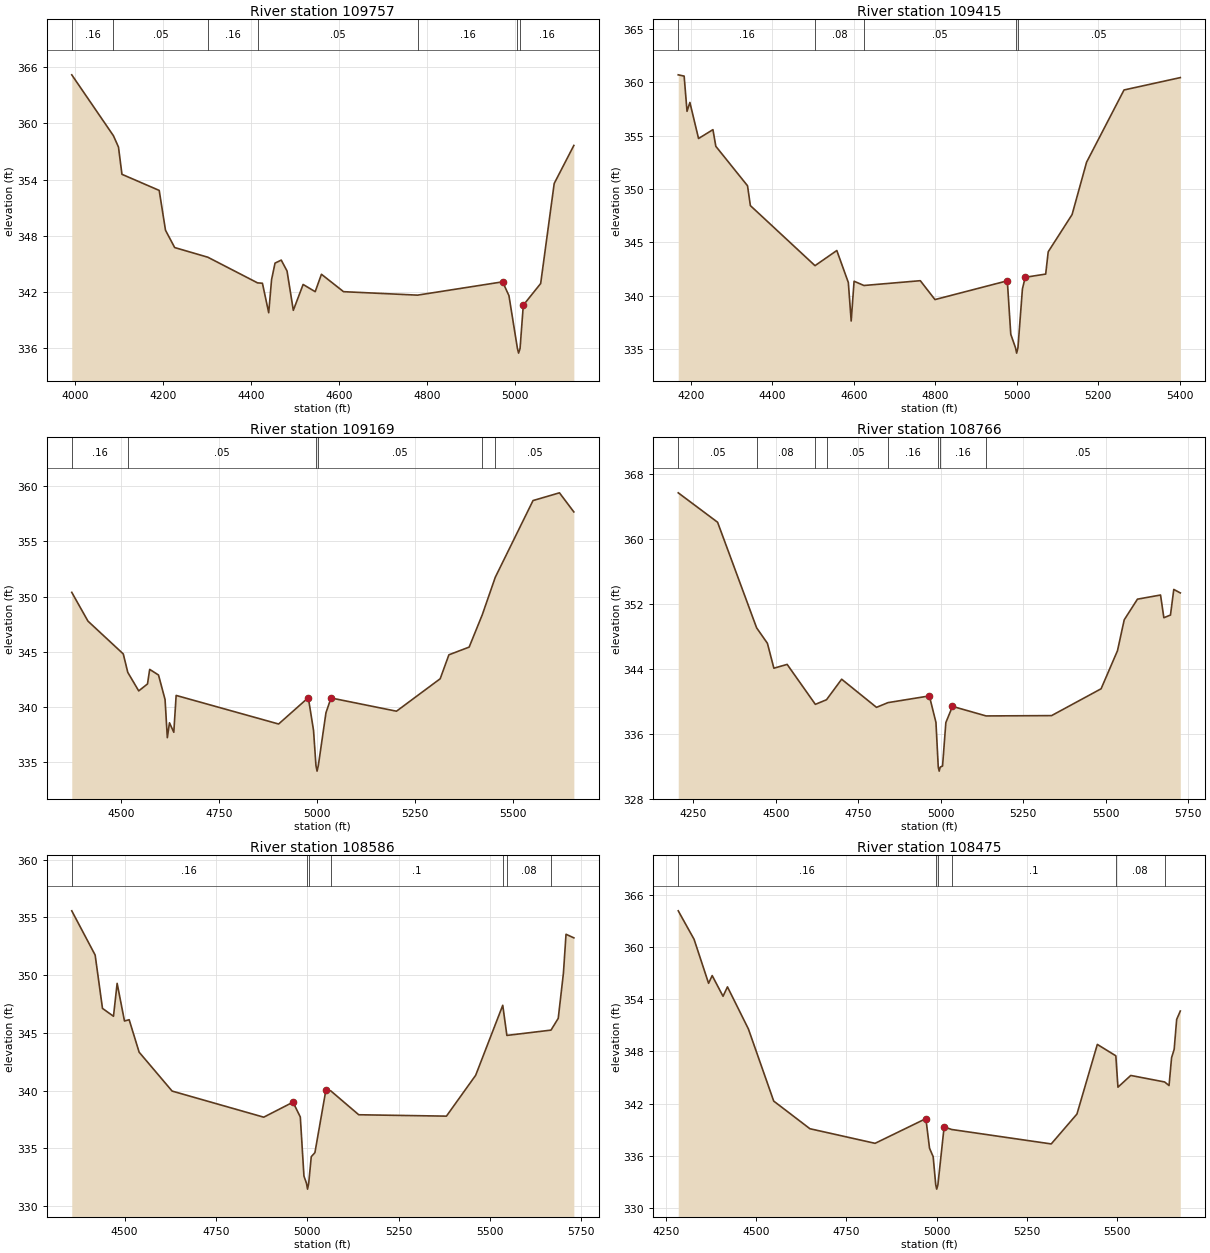
Type RM Length L Ch R = 1 ,109757  ,342,342,342
BEGIN DESCRIPTION:
BOX CREEK 152.0
END DESCRIPTION:
XS GIS Cut Line= 3
      3783499.61     10587060.19      3782699.61     10587710.19
       3782599.6      10587760.2
#Sta/Elev= 30
  3991.8  365.18  4086.6  358.68  4098.1  357.47    4106  354.56  4190.8  352.84
  4205.1  348.59    4226  346.74  4301.4  345.71  4414.6  342.97  4425.7  342.93
    4440  339.78  4446.5  343.32  4454.4  345.08  4468.5   345.4  4481.7  344.24
    4496  340.04  4518.3   342.8  4545.8  342.03    4560  343.89  4610.3  342.03
  4778.7  341.66  4972.3  343.08  4986.7  341.61    5006  335.97  5008.7  335.47
    5012  335.97  5019.4  340.59  5058.9   342.9  5089.7  353.58  5134.4  357.64
#Mann= 7 ,-1 , 0
  3991.8     .16       0  4086.6     .05       0  4301.4     .16       0
  4414.6     .05       0  4778.7     .16       0    5006     .07       0
    5012     .16       0
Bank Sta=4972.3,5019.4
XS Rating Curve= 0 ,0
Exp/Cntr=0.3,0.1

Type RM Length L Ch R = 1 ,109415  ,246,246,246
BEGIN DESCRIPTION:
BOX CREEK 151.0
END DESCRIPTION:
XS GIS Cut Line= 3
      3783210.76     10586840.83      3782780.19      10587271.4
       3782276.7     10587639.47
#Sta/Elev= 30
  4168.9  360.71  4183.4  360.59  4190.5  357.29  4197.5  358.12  4218.8  354.74
  4254.1  355.57  4261.2  354.01    4339  350.31    4346  348.45  4504.7  342.82
  4558.2  344.24  4586.5  341.24  4593.5  337.63  4600.6  341.36  4624.8  340.96
  4763.2  341.41  4799.2  339.64  4976.8   341.4  4985.3  336.39  4996.9  335.12
  4999.7  334.62  5002.9  335.12  5013.9  340.64  5020.8  341.73    5071  342.03
  5077.2  344.12  5135.8  347.61  5171.4  352.52  5263.3  359.29  5401.5  360.45
#Mann= 5 ,-1 , 0
  4168.9     .16       0  4504.7     .08       0  4624.8     .05       0
  4996.9     .03       0  5002.9     .05       0
Bank Sta=4976.8,5020.8
XS Rating Curve= 0 ,0
Exp/Cntr=0.3,0.1

Type RM Length L Ch R = 1 ,109169  ,403,403,403
BEGIN DESCRIPTION:
Mapping XS 341ec51c
END DESCRIPTION:
XS GIS Cut Line= 2
      3783023.25     10586927.65      3781873.49     10587492.25
#Sta/Elev= 30
  4373.9  350.39  4415.3  347.78  4505.3  344.81  4516.8  343.14  4544.7  341.46
  4567.1  342.09  4572.7  343.41  4595.2   342.9  4611.9  340.68  4617.7  337.22
  4623.2  338.57  4634.2  337.71  4640.2  341.05  4901.6  338.46  4977.4  340.85
  4990.7  337.88  4996.9  334.69  4999.7  334.19  5002.9  334.69  5022.4  339.48
  5035.3  340.82  5202.3  339.62  5313.8  342.56    5336  344.73  5387.7  345.43
  5421.2  348.36  5454.4  351.76  5550.7  358.71  5618.1  359.41  5654.8  357.68
#Mann= 6 ,-1 , 0
  4373.9     .16       0  4516.8     .05       0  4996.9     .03       0
  5002.9     .05       0  5421.2     .16       0  5454.4     .05       0
Bank Sta=4977.4,5035.3
XS Rating Curve= 0 ,0
Exp/Cntr=0.3,0.1

Type RM Length L Ch R = 1 ,108766  ,180,180,180
BEGIN DESCRIPTION:
BOX CREEK 150.0
END DESCRIPTION:
XS GIS Cut Line= 3
      3783038.44     10586822.01      3782516.09     10586867.75
       3781519.8     10586913.76
#Sta/Elev= 30
  4204.1  365.73  4323.4   362.1  4441.7  349.07  4474.4  347.16    4494  344.09
  4534.2  344.56  4619.7  339.63  4653.5   340.2  4699.4  342.73    4805  339.26
  4839.6  339.84  4965.2  340.67  4985.2   337.4  4992.2  331.89    4995  331.39
  4998.2  331.89  5005.2  332.02  5015.2  337.38  5035.3  339.38  5137.2   338.2
  5335.6  338.24  5485.7  341.55  5535.4  346.25  5555.8  350.06  5595.9  352.61
  5665.9  353.12  5675.9  350.32    5696  350.65    5706  353.81  5725.8  353.38
#Mann= 8 ,-1 , 0
  4204.1     .05       0  4441.7     .08       0  4619.7     .16       0
  4653.5     .05       0  4839.6     .16       0  4992.2     .07       0
  4998.2     .16       0  5137.2     .05       0
Bank Sta=4965.2,5035.3
XS Rating Curve= 0 ,0
Exp/Cntr=0.3,0.1

Type RM Length L Ch R = 1 ,108586  ,111,111,111
BEGIN DESCRIPTION:
BOX CREEK 149.0
END DESCRIPTION:
XS GIS Cut Line= 4
      3782803.43      10586767.5      3782237.44     10586722.36
       3781629.8      10586729.3      3781490.88      10586871.7
#Sta/Elev= 30
  4355.2  355.56  4419.2  351.73  4439.3  347.11  4469.4  346.43  4479.4  349.28
  4499.5  346.02  4512.3  346.13  4539.6  343.32  4629.9  339.95  4880.7  337.69
  4960.8  338.99  4980.8  337.71  4990.8  332.59  4997.8  331.96  5000.6  331.46
  5003.8  331.96  5010.8  334.27  5020.8  334.62  5050.8  340.03  5064.2  339.97
  5140.8   337.9  5380.8  337.78  5460.9  341.32    5535  347.38  5546.3  344.77
  5667.1  345.23  5686.9  346.25  5701.1  350.17  5708.2  353.53  5729.6  353.22
#Mann= 7 ,-1 , 0
  4355.2     .16       0  4997.8     .07       0  5003.8     .16       0
  5064.2      .1       0    5535     .05       0  5546.3     .08       0
  5667.1     .05       0
Bank Sta=4960.8,5050.8
XS Rating Curve= 0 ,0
Exp/Cntr=0.3,0.1

Type RM Length L Ch R = 1 ,108475  ,307,307,307
BEGIN DESCRIPTION:
Mapping XS 69ad9c6b
END DESCRIPTION:
XS GIS Cut Line= 4
      3782803.39     10586673.74      3782154.11     10586632.08
      3781636.75     10586704.99       3781481.8      10586856.5
#Sta/Elev= 30
  4284.4  364.17  4328.3  360.89  4368.4  355.83  4378.4  356.72  4408.4  354.34
  4420.7  355.42  4478.6  350.58  4548.7  342.28  4648.9   339.1  4829.3  337.42
  4969.9  340.26    4980  336.86  4990.1  335.88  4997.2  332.65  4999.9  332.15
  5003.2  332.65  5020.4  339.31  5041.5  339.01  5316.9  337.35  5388.1  340.79
  5444.5   348.8  5495.7  347.49  5501.6  343.88    5537  345.23  5630.7  344.48
    5643  344.07    5650  347.27  5657.2  348.23  5664.1  351.67  5674.2  352.64
#Mann= 6 ,-1 , 0
  4284.4     .16       0  4997.2     .07       0  5003.2     .16       0
  5041.5      .1       0  5495.7     .08       0  5630.7     .05       0
Bank Sta=4969.9,5020.4
XS Rating Curve= 0 ,0
Exp/Cntr=0.3,0.1

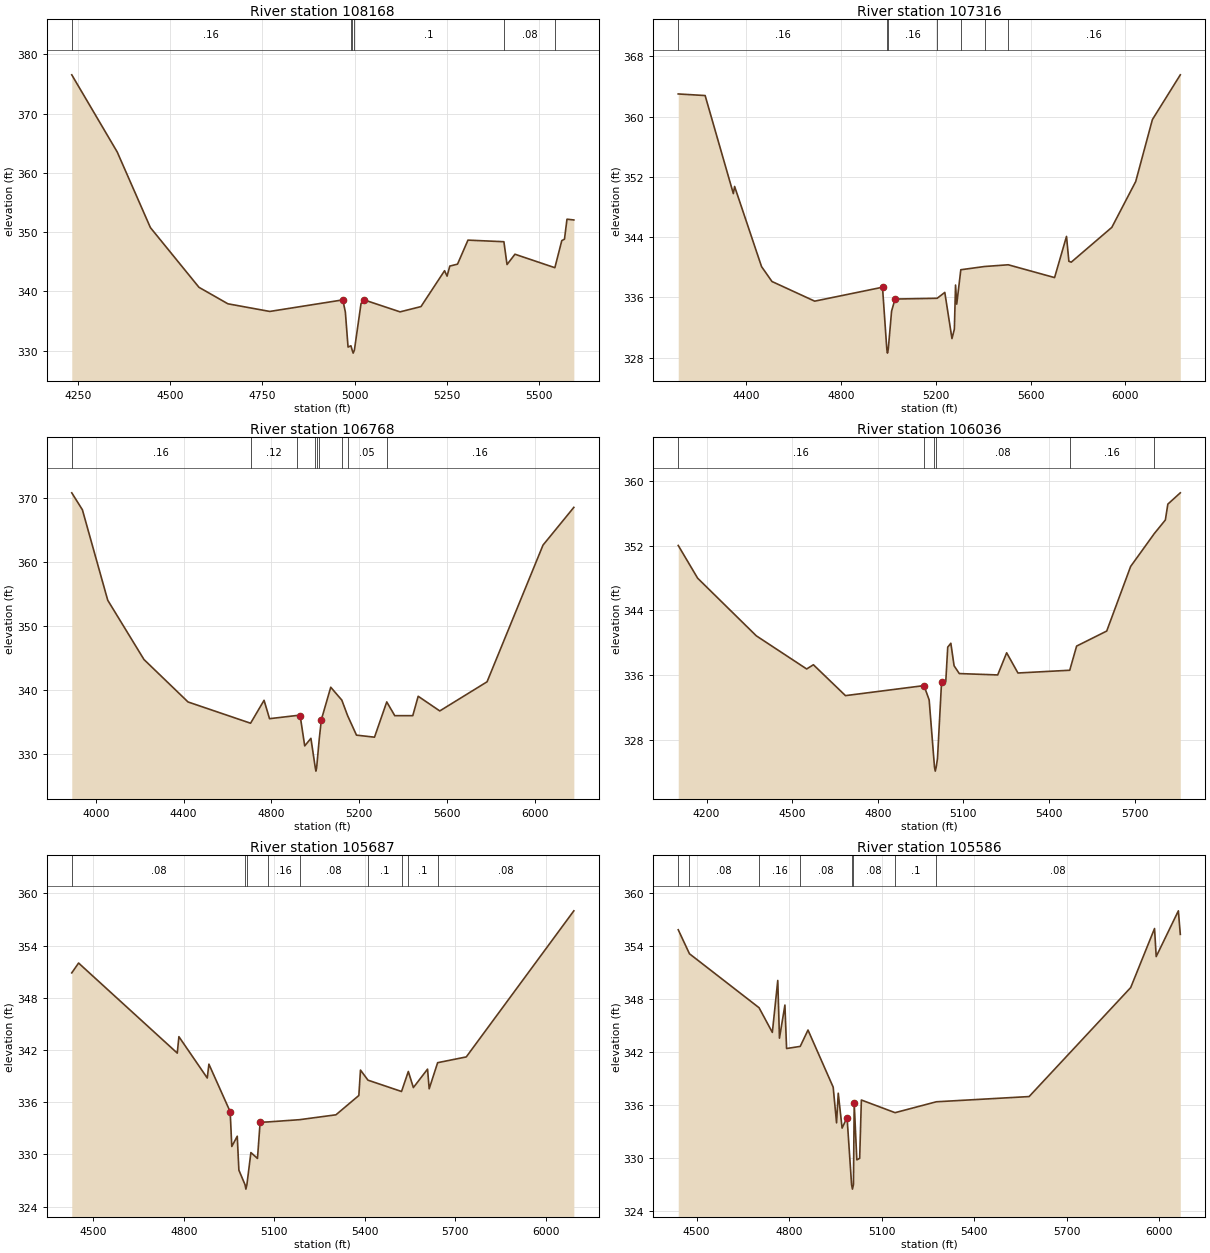
Type RM Length L Ch R = 1 ,108168  ,852,852,852
BEGIN DESCRIPTION:
BOX CREEK 148.0
END DESCRIPTION:
XS GIS Cut Line= 3
      3782588.12     10586149.44      3781945.77     10586402.91
      3781453.69     10586860.34
#Sta/Elev= 30
  4232.8  376.53  4356.1  363.52  4446.2  350.76    4578  340.69  4656.5  337.91
  4770.1  336.62  4968.3  338.57  4975.2  336.52  4982.5  330.61  4990.3  330.83
  4993.7  330.09  4996.4  329.59  4999.7  330.09  5017.7  337.94    5025  338.59
  5123.7  336.55  5180.4  337.44  5244.4  343.49  5251.2  342.58  5258.6  344.27
  5279.6   344.6  5307.9  348.65  5405.4  348.38  5413.9  344.53  5435.4  346.27
  5543.7     344  5562.5  348.57  5569.8  348.81  5576.6  352.18  5595.2  352.05
#Mann= 6 ,-1 , 0
  4232.8     .16       0  4990.3      .1       0  4993.7     .07       0
  4999.7      .1       0  5405.4     .08       0  5543.7     .05       0
Bank Sta=4968.3,5025
XS Rating Curve= 0 ,0
Exp/Cntr=0.3,0.1

Type RM Length L Ch R = 1 ,107316  ,548,548,548
BEGIN DESCRIPTION:
BOX CREEK 147.0
END DESCRIPTION:
XS GIS Cut Line= 3
      3782372.85     10585868.19      3781348.55     10586225.83
      3780322.64      10586340.2
#Sta/Elev= 30
  4114.2     363  4227.6  362.79  4346.6  349.77  4351.9  350.72  4465.5  340.08
  4509.5   338.1  4689.6  335.49  4975.6  337.34  4993.8  329.09  4996.5  328.59
  4999.8  329.09  5013.9  334.17  5028.5  335.77  5205.9  335.87  5238.3  336.65
  5268.5  330.52  5278.6  331.77  5283.6  337.63  5288.6  335.09  5305.8  339.66
  5405.8  340.09  5505.7  340.32  5701.2  338.62  5751.5  344.09  5761.5  340.78
  5771.6  340.67  5942.7  345.29  6043.3  351.37  6113.7   359.6  6231.4  365.54
#Mann= 7 ,-1 , 0
  4114.2     .16       0  4993.8     .07       0  4999.8     .16       0
  5205.9     .05       0  5305.8     .16       0  5405.8     .05       0
  5505.7     .16       0
Bank Sta=4975.6,5028.5
XS Rating Curve= 0 ,0
Exp/Cntr=0.3,0.1

Type RM Length L Ch R = 1 ,106768  ,732,732,732
BEGIN DESCRIPTION:
BOX CREEK 146.0
END DESCRIPTION:
XS GIS Cut Line= 3
      3782418.04     10585517.48      3781522.16      10585854.3
      3780224.12     10586156.25
#Sta/Elev= 30
  3889.6  370.82    3938  368.18  4053.6  354.05  4218.9  344.79  4419.9  338.16
  4705.1  334.84  4766.6  338.42  4791.5  335.55  4916.3  336.05  4931.5  335.95
    4952   331.3  4980.3  332.48  5000.3  327.86  5003.1  327.36  5006.3  327.86
  5018.8  332.57  5028.1  335.42  5070.7  340.46  5121.2  338.45  5147.8  336.01
  5188.1  332.98  5270.3  332.66  5326.1  338.17  5362.7  336.02  5444.8  336.02
  5469.5  339.05    5568  336.76  5783.6  341.31  6038.7  362.65  6179.4  368.55
#Mann= 9 ,-1 , 0
  3889.6     .16       0  4705.1     .12       0  4916.3     .16       0
  5000.3     .07       0  5006.3     .16       0  5018.8      .1       0
  5121.2     .08       0  5147.8     .05       0  5326.1     .16       0
Bank Sta=4931.5,5028.1
XS Rating Curve= 0 ,0
Exp/Cntr=0.3,0.1

Type RM Length L Ch R = 1 ,106036  ,349,349,349
BEGIN DESCRIPTION:
Mapping XS af56cd56
END DESCRIPTION:
XS GIS Cut Line= 2
      3781999.08     10585279.41      3780379.34     10585966.88
#Sta/Elev= 30
  4100.7  352.03  4168.7  347.98  4374.3  340.85  4550.8  336.75  4574.4  337.27
  4686.8  333.45  4961.9  334.69    4962  334.69  4980.1  332.92  4998.8  324.61
  5001.5  324.11  5004.8  324.61  5009.3  325.67  5023.5   335.1  5038.4  335.22
  5045.2  339.45  5056.1  339.93  5067.5  337.14  5085.7  336.18  5220.3  336.01
  5251.7  338.75  5291.3  336.25  5472.8  336.59  5496.9  339.58  5602.4  341.44
  5686.2  349.43  5769.4  353.51  5807.9  355.18  5816.6  357.14  5860.3  358.54
#Mann= 6 ,-1 , 0
  4100.7     .16       0  4961.9     .08       0  4998.8     .07       0
  5004.8     .08       0  5472.8     .16       0  5769.4     .08       0
Bank Sta=4962,5023.5
XS Rating Curve= 0 ,0
Exp/Cntr=0.3,0.1

Type RM Length L Ch R = 1 ,105687  ,101,101,101
BEGIN DESCRIPTION:
BOX CREEK 145.0
END DESCRIPTION:
XS GIS Cut Line= 2
      3781874.06     10585185.67      3780348.04     10585847.11
#Sta/Elev= 30
  4429.2  350.87  4451.8     352  4778.7  341.65  4784.1  343.54    4878  338.79
  4883.5  340.38  4953.9  334.92  4959.3  330.92  4977.4   332.1  4982.8   328.2
  5003.3  326.52    5006  326.02  5009.3  326.52  5022.6  330.22  5044.4  329.55
  5053.2  333.71  5078.7  333.74  5183.9     334  5304.3  334.56  5380.2  336.78
  5385.6   339.7  5410.5  338.54  5521.6  337.24  5544.1  339.54  5560.8  337.69
  5607.8  339.81  5613.2  337.55  5641.2  340.55    5736  341.21  6092.4     358
#Mann= 9 ,-1 , 0
  4429.2     .08       0  5003.3     .07       0  5009.3     .08       0
  5078.7     .16       0  5183.9     .08       0  5410.5      .1       0
  5521.6     .08       0  5544.1      .1       0  5641.2     .08       0
Bank Sta=4953.9,5053.2
XS Rating Curve= 0 ,0
Exp/Cntr=0.3,0.1

Type RM Length L Ch R = 1 ,105586  ,70,70,70
BEGIN DESCRIPTION:
Mapping XS 5ec84b32
END DESCRIPTION:
XS GIS Cut Line= 4
      3781818.03     10585092.21      3781331.91     10585310.96
      3780727.74     10585581.79       3780326.7     10585746.73
#Sta/Elev= 30
  4440.3  355.81  4476.7   353.1  4702.5     347  4745.6  344.21  4763.2  350.08
  4768.7  343.56  4786.4   347.3  4791.8  342.39  4836.1  342.63  4861.3  344.48
    4943  338.02  4953.9  333.99  4959.4  337.34  4971.9   333.4    4988  334.59
  5002.7     327  5005.5   326.5  5008.7     327  5011.2  336.18  5019.7  329.81
  5028.9  329.98  5034.4  336.57  5143.8  335.14  5277.5  336.37  5578.6  336.96
  5908.2  349.28  5985.5  355.95  5990.9  352.78  6062.8  357.95  6069.1  355.29
#Mann= 8 ,-1 , 0
  4440.3     .05       0  4476.7     .08       0  4702.5     .16       0
  4836.1     .08       0  5002.7     .07       0  5008.7     .08       0
  5143.8      .1       0  5277.5     .08       0
Bank Sta=4988,5011.2
XS Rating Curve= 0 ,0
Exp/Cntr=0.3,0.1

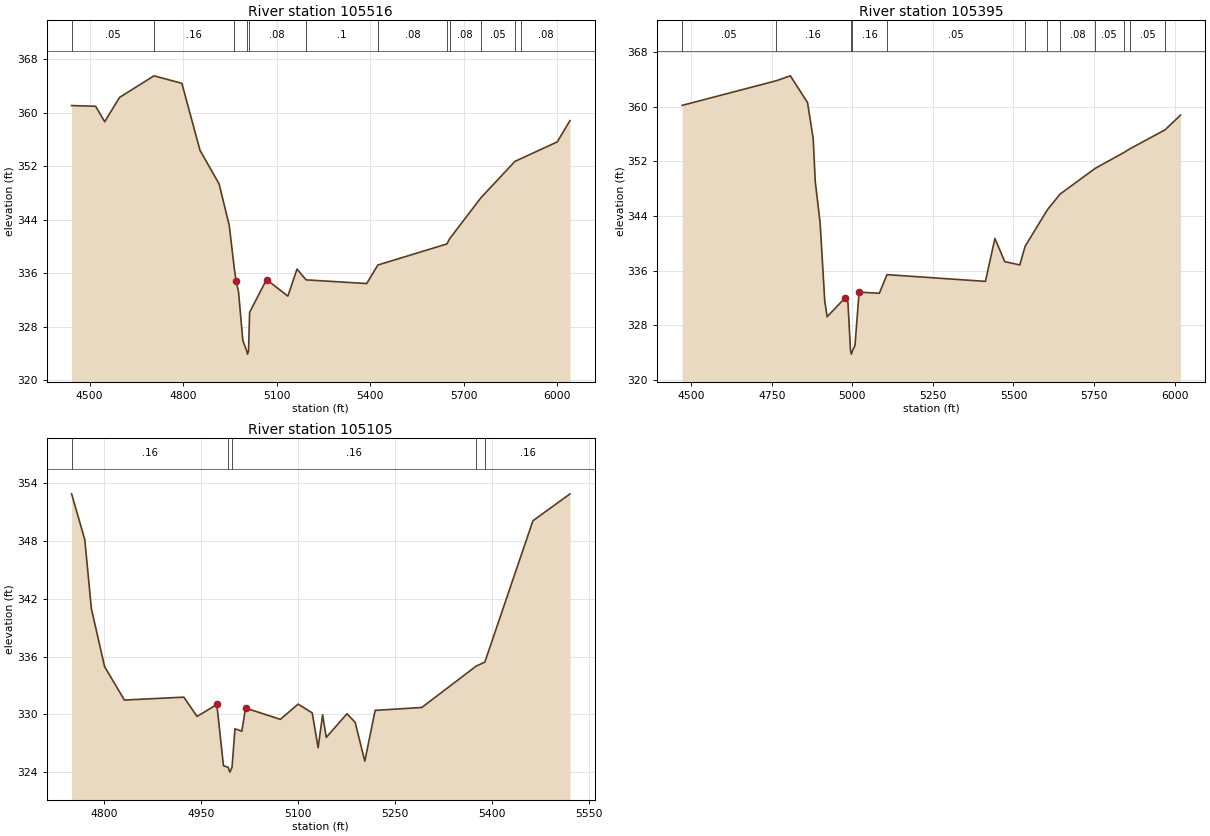
Type RM Length L Ch R = 1 ,105516  ,121,121,121
BEGIN DESCRIPTION:
BOX CREEK 144.0
END DESCRIPTION:
XS GIS Cut Line= 2
      3781785.58     10585045.01      3780313.09     10585669.39
#Sta/Elev= 30
    4442  361.05  4519.2  360.95  4548.3  358.63  4595.6  362.26  4706.4   365.5
  4795.9  364.38  4854.1  354.36  4915.5  349.32  4948.1  343.09    4964  336.75
  4969.9  334.84  4977.8  333.17  4991.6  325.89  5003.9  324.37  5006.7  323.87
  5009.9  324.37  5013.3  330.12  5067.6  335.02  5136.1  332.55  5165.4  336.59
  5194.5  334.98  5389.1  334.43  5424.9   337.2  5646.4  340.35  5655.3  341.13
  5755.6  347.26  5864.8   352.7  5885.7  353.15  6000.7  355.62  6041.4   358.8
#Mann= 12 ,-1 , 0
    4442     .05       0  4706.4     .16       0    4964     .08       0
  5003.9     .07       0  5009.9     .08       0  5194.5      .1       0
  5424.9     .08       0  5646.4     .05       0  5655.3     .08       0
  5755.6     .05       0  5864.8      .1       0  5885.7     .08       0
Bank Sta=4969.9,5067.6
XS Rating Curve= 0 ,0
Exp/Cntr=0.3,0.1

Type RM Length L Ch R = 1 ,105395  ,290,290,290
BEGIN DESCRIPTION:
Mapping XS 9904ab00
END DESCRIPTION:
XS GIS Cut Line= 2
      3781665.78     10584987.72      3780235.34     10585575.51
#Sta/Elev= 30
  4471.8  360.22  4763.3  363.82  4807.7  364.55    4861  360.63  4878.5  355.37
    4885  349.05  4900.1  342.98  4914.4  331.58  4921.7  329.24  4975.8  331.93
  4986.3  331.41  4994.4  324.27  4997.2  323.77  5000.4  324.27  5008.2  325.01
    5021  332.85  5083.9  332.69  5107.5  335.42    5413  334.43  5442.4  340.72
  5473.1  337.32  5519.7  336.84    5536  339.56  5605.5  344.94  5644.6  347.22
  5753.3  350.98  5841.5  353.28  5861.9  353.87  5970.5  356.64  6018.3  358.79
#Mann= 12 ,-1 , 0
  4471.8     .05       0  4763.3     .16       0  4994.4     .07       0
  5000.4     .16       0  5107.5     .05       0    5536     .08       0
  5605.5     .05       0  5644.6     .08       0  5753.3     .05       0
  5841.5      .1       0  5861.9     .05       0  5970.5      .1       0
Bank Sta=4975.8,5021
XS Rating Curve= 0 ,0
Exp/Cntr=0.3,0.1

Type RM Length L Ch R = 1 ,105105  ,524,524,524
BEGIN DESCRIPTION:
BOX CREEK 143.0
END DESCRIPTION:
XS GIS Cut Line= 3
      3781299.66      10585010.2      3781049.61     10584960.19
      3780599.59     10584710.18
#Sta/Elev= 30
  4750.4  352.86  4770.8  348.11    4781  340.95  4801.4  334.95    4832  331.49
  4923.8  331.79  4944.2  329.79  4974.8  331.03    4985  324.68  4992.2  324.52
  4994.9  324.02  4998.2  324.52  5002.8  328.51  5013.4  328.26  5019.1  330.66
  5072.9  329.49  5100.3  331.07  5122.1  330.16  5131.2  326.55  5138.1  329.96
  5143.8  327.62  5175.8  330.07  5188.4  329.18  5203.3  325.16  5219.3  330.42
  5291.4  330.72  5375.2     335  5388.7  335.42    5463  350.07  5520.2  352.85
#Mann= 5 ,-1 , 0
  4750.4     .16       0  4992.2     .07       0  4998.2     .16       0
  5375.2     .12       0  5388.7     .16       0
Bank Sta=4974.8,5019.1
XS Rating Curve= 0 ,0
Exp/Cntr=0.3,0.1