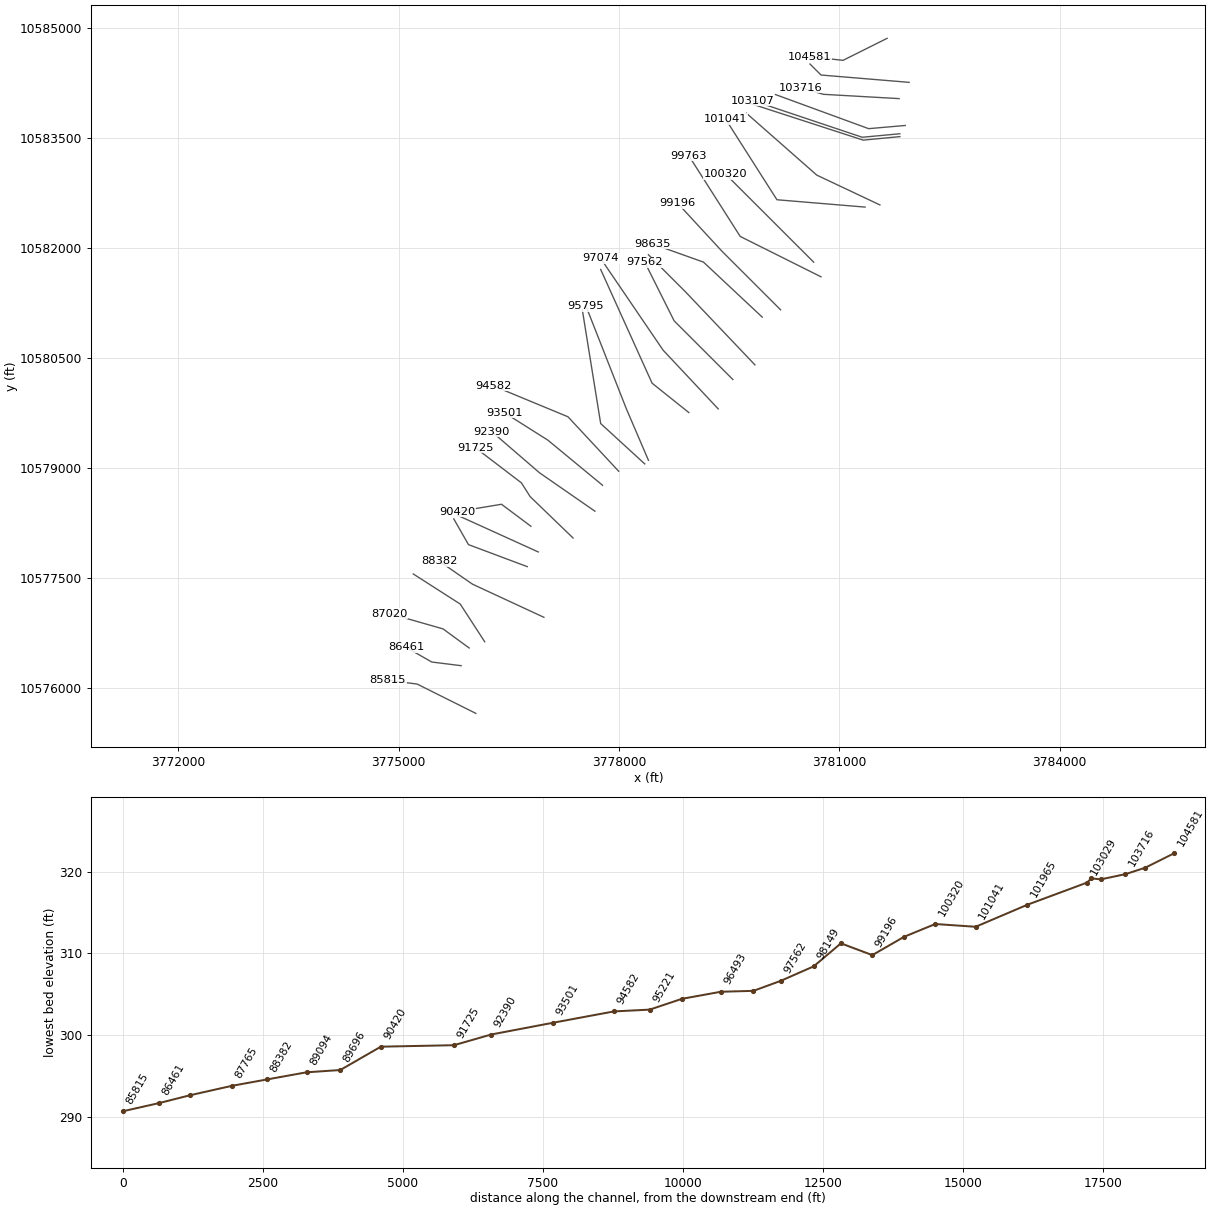
HEC-RAS study BOX CREEK.prj: BOX CREEK Base Level Engineering

--- BOX CREEK.g01 (geometry) --- (continued)

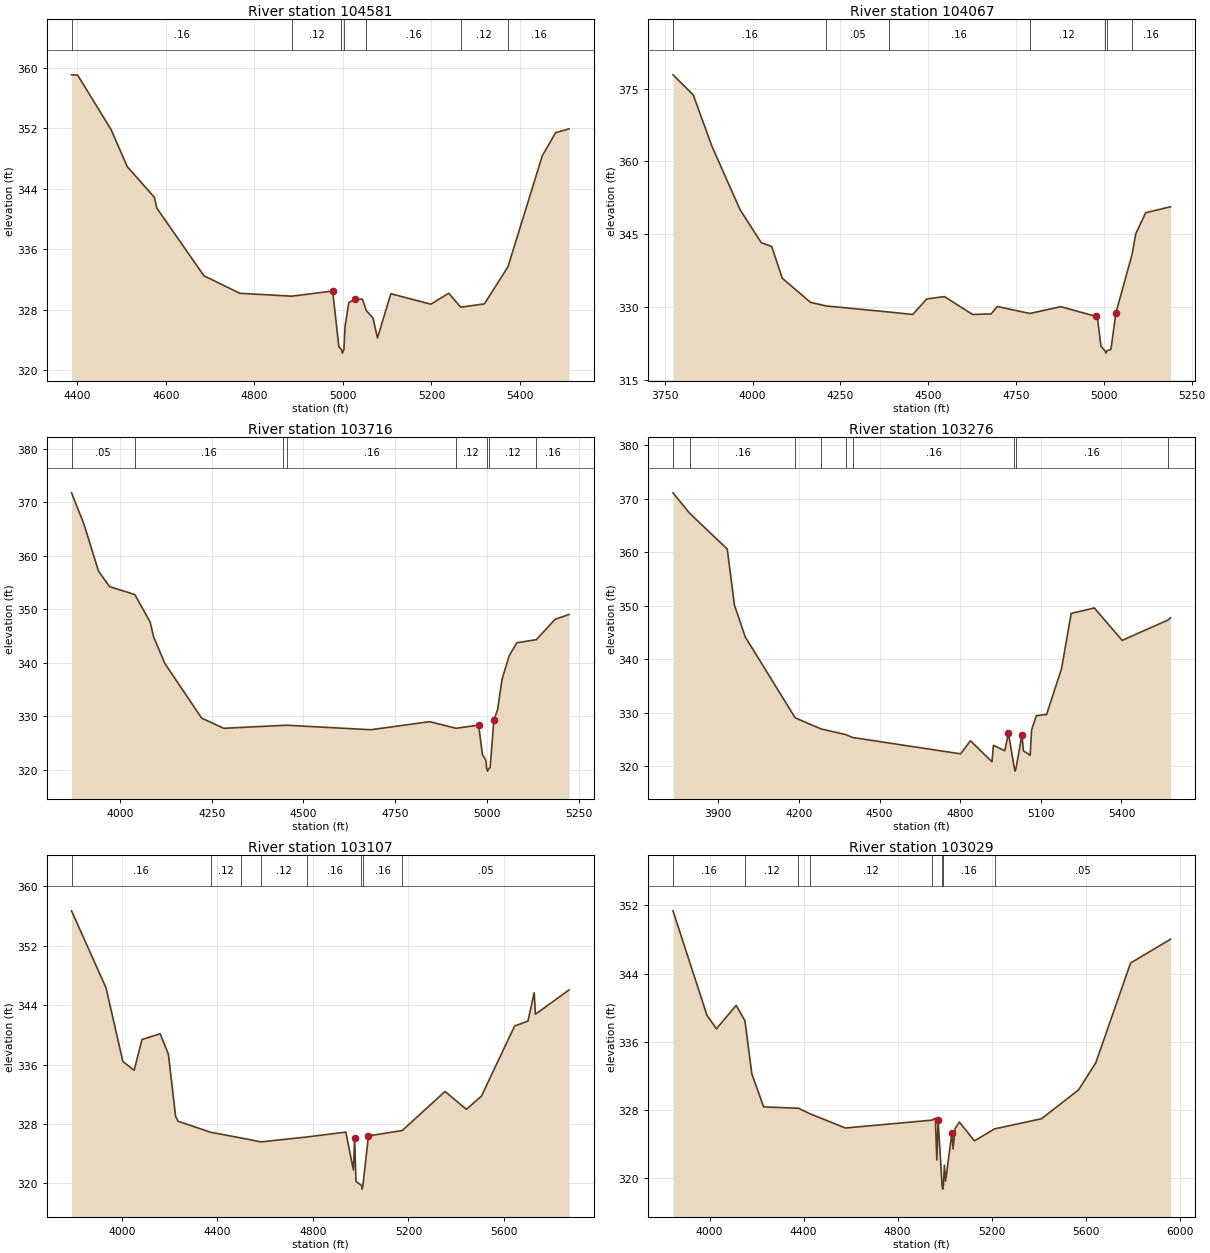
Type RM Length L Ch R = 1 ,104581  ,514,514,514
BEGIN DESCRIPTION:
BOX CREEK 142.0
END DESCRIPTION:
XS GIS Cut Line= 3
      3781649.58     10584860.17      3781049.61     10584560.19
      3780599.56     10584610.19
#Sta/Elev= 30
  4387.3   359.1  4401.2  359.06  4476.7  351.84    4513  346.96  4574.5  342.88
  4580.1  341.44  4686.3   332.5  4767.4  330.18  4884.6   329.8    4977  330.48
    4991  323.12  4996.4  322.76  4999.1  322.26  5002.4  322.76    5005  325.78
  5013.4  328.95  5027.3  329.38  5044.1  329.41    5053   327.9  5068.1   326.9
  5078.2  324.27  5108.4  330.12  5198.9  328.74  5239.2  330.19  5266.1  328.34
  5319.7  328.78  5372.9  333.69  5450.5   348.4  5480.7  351.45  5510.9  351.95
#Mann= 7 ,-1 , 0
  4387.3     .16       0  4884.6     .12       0  4996.4     .07       0
  5002.4     .12       0    5053     .16       0  5266.1     .12       0
  5372.9     .16       0
Bank Sta=4977,5027.3
XS Rating Curve= 0 ,0
Exp/Cntr=0.3,0.1

Type RM Length L Ch R = 1 ,104067  ,351,351,351
BEGIN DESCRIPTION:
BOX CREEK 141.0
END DESCRIPTION:
XS GIS Cut Line= 3
      3781949.63     10584260.19      3780749.61     10584360.19
      3780599.62     10584510.18
#Sta/Elev= 30
  3773.4  377.85  3831.1  373.71  3883.8   363.2  3964.1  350.09  4024.3  343.29
  4054.4  342.46  4084.5  335.94  4164.8  330.96    4210  330.22  4387.8  328.97
  4455.8  328.47  4495.9  331.67  4546.1  332.15  4626.4  328.46  4679.1  328.59
  4696.6  330.11  4789.1  328.67  4877.2  330.08  4977.6  328.07  4981.1  328.07
  4991.7  321.93  5002.9     321  5005.6   320.5  5008.9     321    5020  321.26
  5034.2  328.76  5080.3  340.87  5090.7  345.09    5119  349.44  5189.7  350.66
#Mann= 7 ,-1 , 0
  3773.4     .16       0    4210     .05       0  4387.8     .16       0
  4789.1     .12       0  5002.9     .07       0  5008.9     .12       0
  5080.3     .16       0
Bank Sta=4977.6,5034.2
XS Rating Curve= 0 ,0
Exp/Cntr=0.3,0.1

Type RM Length L Ch R = 1 ,103716  ,440,440,440
BEGIN DESCRIPTION:
BOX CREEK 140.0
END DESCRIPTION:
XS GIS Cut Line= 3
      3781813.13     10584038.59      3780782.27     10584097.19
      3780473.25     10584187.95
#Sta/Elev= 30
  3868.5  371.76  3902.1  365.95  3942.1  357.08  3972.2  354.22  4040.7  352.74
  4082.4  347.63  4092.4  344.76  4122.4  339.88  4222.6  329.64  4282.7  327.73
  4445.4  328.28  4454.6   328.3  4683.3  327.46  4843.6  328.97  4915.4  327.73
  4976.8  328.32  4987.2  322.85  4996.4  321.79  4998.6  320.22  5001.3  319.72
  5004.6  320.22    5008  320.33  5018.4  329.21  5028.9  331.35  5040.2  336.78
  5060.1   341.3    5081  343.73  5133.9   344.3  5185.2  348.12  5223.1  349.02
#Mann= 8 ,-1 , 0
  3868.5     .05       0  4040.7     .16       0  4445.4     .05       0
  4454.6     .16       0  4915.4     .12       0  4998.6     .07       0
  5004.6     .12       0  5133.9     .16       0
Bank Sta=4976.8,5018.4
XS Rating Curve= 0 ,0
Exp/Cntr=0.3,0.1

Type RM Length L Ch R = 1 ,103276  ,169,169,169
BEGIN DESCRIPTION:
BOX CREEK 139.0
END DESCRIPTION:
XS GIS Cut Line= 3
       3781897.2     10583672.56      3781398.07     10583629.15
       3780130.7     10584093.57
#Sta/Elev= 30
  3731.8   371.1  3793.9  367.27  3933.7  360.59  3960.3  350.13  4000.4  344.18
  4186.2  329.05  4282.3  326.97  4374.6  325.91  4399.9  325.37  4801.8  322.31
  4838.2  324.76  4918.5  320.82  4923.8  323.91    4966  322.89  4979.5   326.2
  5001.7  319.58  5004.4  319.08  5007.7  319.58  5029.9  325.88  5035.2  322.88
  5060.4  322.04  5065.7  326.76  5083.2  329.44  5121.4  329.67  5177.1  338.22
  5212.9  348.55  5299.1  349.58  5402.7  343.52    5575  347.37  5582.6  347.74
#Mann= 9 ,-1 , 0
  3731.8     .05       0  3793.9     .16       0  4186.2     .05       0
  4282.3     .16       0  4374.6     .05       0  4399.9     .16       0
  5001.7     .07       0  5007.7     .16       0    5575     .05       0
Bank Sta=4979.5,5029.9
XS Rating Curve= 0 ,0
Exp/Cntr=0.3,0.1

Type RM Length L Ch R = 1 ,103107  ,78,78,78
BEGIN DESCRIPTION:
Mapping XS bbb09f4d
END DESCRIPTION:
XS GIS Cut Line= 3
      3781823.45     10583559.71      3781311.27     10583511.97
      3779823.57     10584010.76
#Sta/Elev= 30
    3789  356.72  3933.5  346.34  4003.8  336.42  4051.1  335.22  4084.1  339.37
  4160.2  340.15  4194.6  337.39  4224.7  329.03  4234.8  328.36  4371.1  326.87
  4500.1  326.09  4582.4  325.57  4776.9  326.24  4937.7  326.89  4969.3  321.78
  4974.5  326.15  4980.2  320.23  5003.1   319.7  5005.8   319.2  5009.1   319.7
  5032.4  326.38  5173.9   327.1  5353.1  332.37  5442.5  329.96  5505.6  331.74
  5644.6   341.2  5700.2  341.85  5726.4  345.67  5731.7  342.78  5872.5  346.06
#Mann= 8 ,-1 , 0
    3789     .16       0  4371.1     .12       0  4500.1     .16       0
  4582.4     .12       0  4776.9     .16       0  5003.1     .07       0
  5009.1     .16       0  5173.9     .05       0
Bank Sta=4974.5,5032.4
XS Rating Curve= 0 ,0
Exp/Cntr=0.3,0.1

Type RM Length L Ch R = 1 ,103029  ,1064,1064,1064
BEGIN DESCRIPTION:
BOX CREEK 138.0
END DESCRIPTION:
XS GIS Cut Line= 3
      3781823.43     10583520.65      3781324.29      10583472.9
      3779787.84     10583972.03
#Sta/Elev= 30
  3844.4  351.37  3988.9   339.1  4029.1  337.52  4113.1  340.26  4150.6  338.45
  4179.7  332.23    4230  328.34  4378.1  328.18  4425.6  327.55  4578.3  325.86
    4946  326.78  4960.6     327    4967   322.1  4972.3  326.79  4989.1  319.18
  4991.9  318.68  4995.1  319.18    4999   321.5  5004.2  319.62  5030.9  325.23
  5036.2  323.41  5044.7   325.8  5062.9  326.56  5126.8  324.35  5212.8  325.76
  5412.7  326.95  5570.4  330.35  5643.3  333.52  5791.2  345.24  5961.3  348.03
#Mann= 8 ,-1 , 0
  3844.4     .16       0  4150.6     .12       0  4378.1     .16       0
  4425.6     .12       0    4946     .16       0  4989.1     .07       0
  4995.1     .16       0  5212.8     .05       0
Bank Sta=4972.3,5030.9
XS Rating Curve= 0 ,0
Exp/Cntr=0.3,0.1

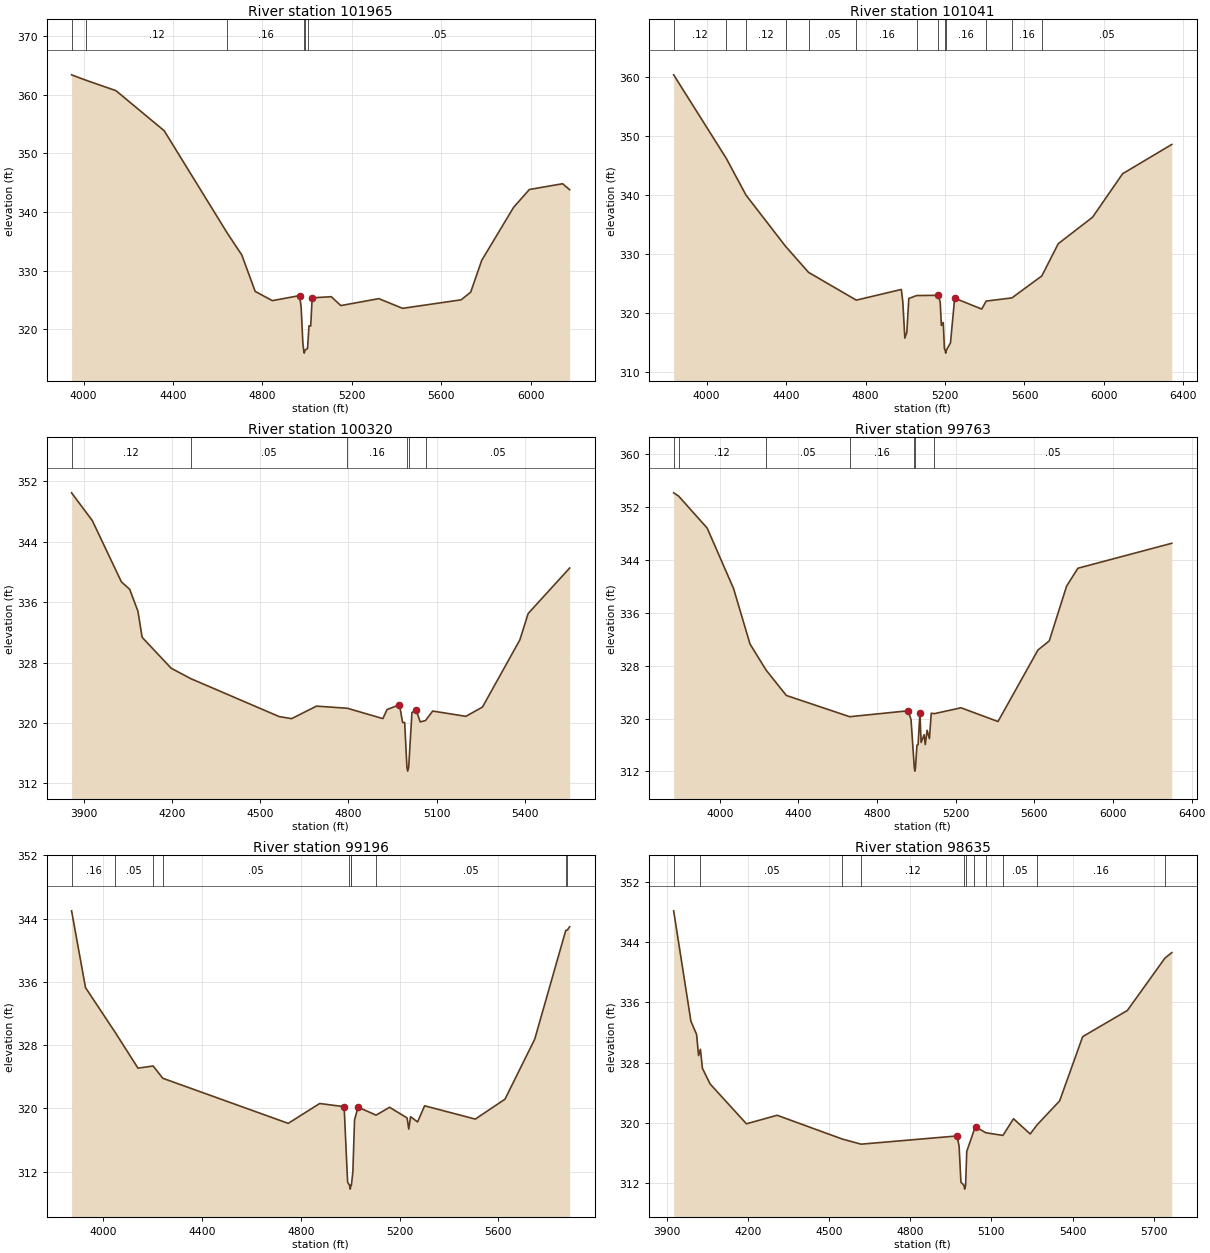
Type RM Length L Ch R = 1 ,101965  ,924,924,924
BEGIN DESCRIPTION:
BOX CREEK 137.0
END DESCRIPTION:
XS GIS Cut Line= 3
      3781551.87     10582589.54      3780692.46     10582995.81
      3779734.38     10583839.33
#Sta/Elev= 30
  3946.6  363.37  4009.4  362.47  4144.8  360.68  4360.7  353.85  4643.4  336.38
  4707.7  332.69  4767.6  326.48  4844.2  324.91  4966.4  325.77  4973.1  323.78
  4980.7  317.71  4984.3  316.47  4987.1  315.97  4990.3  316.47  5001.6  316.75
  5003.7  317.98  5008.2  320.63  5015.8  320.58  5022.4  325.39  5107.8  325.58
  5150.5  324.07  5320.3  325.25  5426.6   323.6  5688.5  325.05  5731.1  326.35
  5780.5  331.77  5922.8  340.79  5993.5  343.84    6142  344.82  6173.7   343.8
#Mann= 6 ,-1 , 0
  3946.6     .16       0  4009.4     .12       0  4643.4     .16       0
  4984.3     .07       0  4990.3     .16       0  5003.7     .05       0
Bank Sta=4966.4,5022.4
XS Rating Curve= 0 ,0
Exp/Cntr=0.3,0.1

Type RM Length L Ch R = 1 ,101041  ,721,721,721
BEGIN DESCRIPTION:
BOX CREEK 136.0
END DESCRIPTION:
XS GIS Cut Line= 3
      3781349.56     10582560.19      3780149.61     10582660.19
      3779449.58     10583760.23
#Sta/Elev= 30
  3833.8  360.39  4098.6  346.25  4198.2  340.02  4397.3  331.35  4512.8  326.95
  4753.4  322.24  4980.2  324.05  4987.7  321.92  4997.8  315.82  5007.8  316.78
  5017.8  322.52  5057.4  323.02  5166.1  323.06  5175.9  321.93  5181.8  317.96
  5191.2  318.45  5197.1  314.01  5200.9  313.77  5203.6  313.27  5206.9  313.77
  5227.6     315  5248.7  322.57    5385  320.73  5407.2  322.08  5536.9  322.62
  5687.5  326.34  5770.3   331.8    5943  336.28  6094.5  343.65  6341.8   348.6
#Mann= 13 ,-1 , 0
  3833.8     .12       0  4098.6     .16       0  4198.2     .12       0
  4397.3     .16       0  4512.8     .05       0  4753.4     .16       0
  5057.4     .12       0  5166.1     .16       0  5200.9     .07       0
  5206.9     .16       0  5407.2     .05       0  5536.9     .16       0
  5687.5     .05       0
Bank Sta=5166.1,5248.7
XS Rating Curve= 0 ,0
Exp/Cntr=0.3,0.1

Type RM Length L Ch R = 1 ,100320  ,557,557,557
BEGIN DESCRIPTION:
BOX CREEK 135.0
END DESCRIPTION:
XS GIS Cut Line= 3
      3780649.58     10581810.21      3779849.61     10582610.19
      3779449.62     10583010.17
#Sta/Elev= 30
  3856.6  350.48  3927.3   346.8  4026.3  338.69  4054.6   337.7  4082.8  334.78
    4097  331.34    4196  327.24  4262.9  325.86  4563.7  320.84  4606.1  320.56
    4691  322.22    4796  321.94  4917.2  320.57  4931.4  321.77  4973.8   322.4
  4984.4  320.05  4991.5  320.05  4999.1  314.11  5001.8  313.61  5005.1  314.11
  5016.2  321.37  5030.4  321.71  5044.5  320.13  5062.5  320.31  5086.9  321.57
  5200.1  320.87  5256.6   322.1  5383.9     331  5412.2  334.49  5553.6  340.52
#Mann= 6 ,-1 , 0
  3856.6     .12       0  4262.9     .05       0    4796     .16       0
  4999.1     .07       0  5005.1     .16       0  5062.5     .05       0
Bank Sta=4973.8,5030.4
XS Rating Curve= 0 ,0
Exp/Cntr=0.3,0.1

Type RM Length L Ch R = 1 ,99763   ,567,567,567
BEGIN DESCRIPTION:
BOX CREEK 134.0
END DESCRIPTION:
XS GIS Cut Line= 3
      3780749.63     10581610.18      3779649.61     10582160.19
      3778949.61     10583260.19
#Sta/Elev= 30
  3765.1  354.18  3790.6  353.68  3935.6  348.84  4069.8  339.69  4153.6  331.28
  4235.1  327.35  4338.1   323.5  4660.5  320.28  4958.6  321.18  4972.6  319.83
  4989.2  312.54  4991.9  312.04  4995.2  312.54  5002.6  315.97  5008.5  316.05
  5017.8  320.91  5023.7  316.38    5039  317.55  5044.9  316.06  5054.2  318.23
  5066.1  316.96  5075.4  320.81  5090.6  320.74  5226.9  321.63  5414.9  319.55
  5618.1  330.38  5675.7  331.76  5763.7  340.04  5821.3  342.76  6298.8  346.54
#Mann= 7 ,-1 , 0
  3765.1     .16       0  3790.6     .12       0  4235.1     .05       0
  4660.5     .16       0  4989.2     .07       0  4995.2     .16       0
  5090.6     .05       0
Bank Sta=4958.6,5017.8
XS Rating Curve= 0 ,0
Exp/Cntr=0.3,0.1

Type RM Length L Ch R = 1 ,99196   ,561,561,561
BEGIN DESCRIPTION:
BOX CREEK 133.0
END DESCRIPTION:
XS GIS Cut Line= 3
      3780199.59     10581160.21      3779399.61     10581960.19
      3778799.63     10582610.17
#Sta/Elev= 30
  3872.7  344.97  3929.2  335.26  4050.1  329.57  4141.4  325.09  4202.9  325.36
    4242  323.81  4749.5  318.11  4876.8  320.62  4975.8  320.22  4989.9  310.67
  4997.5   310.3  5000.3   309.8  5003.5   310.3  5005.1   310.3  5011.1  311.96
  5017.9  318.53  5032.1  320.16  5105.1  319.15  5159.7  320.14  5230.6   318.8
  5237.4  317.39  5244.7  318.95  5273.1  318.29  5301.5  320.33  5506.7  318.65
  5626.9  321.17  5747.2  328.75  5872.8   342.5  5878.6  342.52  5888.6  342.96
#Mann= 10 ,-1 , 0
  3872.7     .16       0  4050.1     .05       0  4202.9     .16       0
    4242     .05       0  4997.5     .03       0  5003.5     .05       0
  5005.1     .16       0  5105.1     .05       0  5872.8     .08       0
  5878.6     .05       0
Bank Sta=4975.8,5032.1
XS Rating Curve= 0 ,0
Exp/Cntr=0.3,0.1

Type RM Length L Ch R = 1 ,98635   ,486,486,486
BEGIN DESCRIPTION:
BOX CREEK 132.0
END DESCRIPTION:
XS GIS Cut Line= 3
      3779949.58     10581060.22      3779149.61     10581810.19
      3778449.65     10582060.17
#Sta/Elev= 30
  3926.4  348.13  3990.1   333.5  4011.1  331.74  4018.4  328.94  4025.3  329.77
  4032.6  327.26  4060.9  325.19  4195.2   319.9  4308.6  321.03  4549.9  317.87
  4618.7   317.2  4973.4  318.29  4980.7  316.93  4987.5  312.16  4998.7  311.74
  5001.4  311.24  5004.7  311.74    5009  316.25  5036.3  319.07  5044.2  319.43
  5079.6  318.71  5142.7  318.36  5181.7  320.57  5243.3  318.55  5268.3  319.74
  5352.1  322.94  5437.1  331.45  5602.2  334.92  5741.2  341.87  5766.2  342.59
#Mann= 11 ,-1 , 0
  3926.4     .16       0  4025.3     .05       0  4549.9     .16       0
  4618.7     .12       0  4998.7     .07       0  5004.7     .12       0
  5036.3     .05       0  5079.6     .12       0  5142.7     .05       0
  5268.3     .16       0  5741.2     .05       0
Bank Sta=4973.4,5044.2
XS Rating Curve= 0 ,0
Exp/Cntr=0.3,0.1

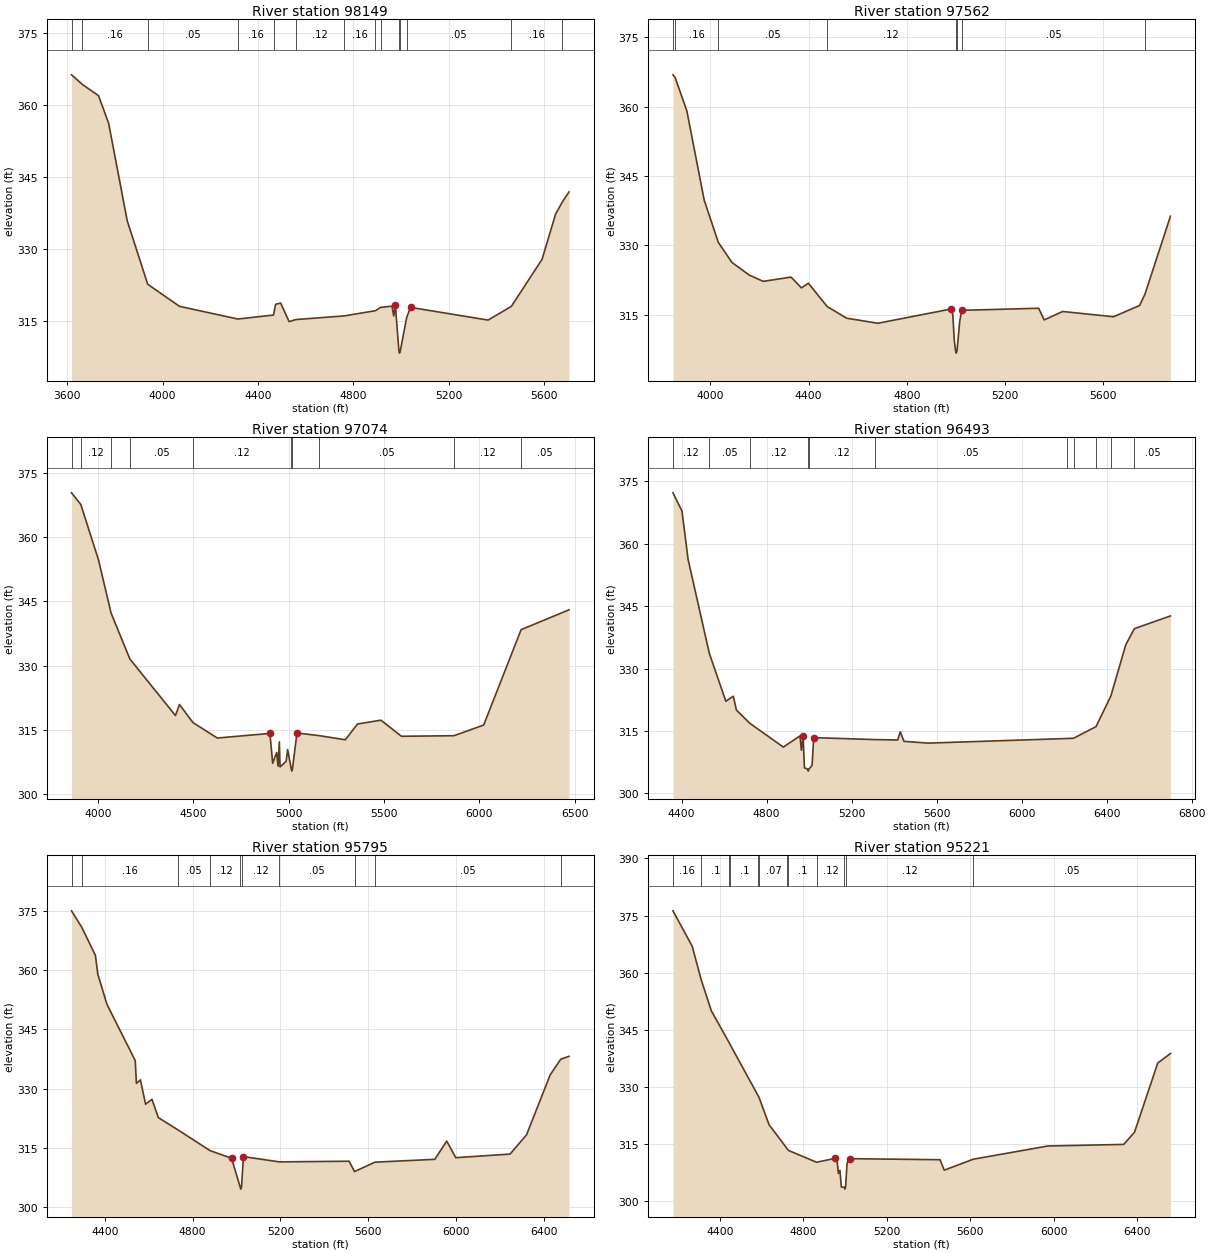
Type RM Length L Ch R = 1 ,98149   ,587,587,587
BEGIN DESCRIPTION:
BOX CREEK 131.0
END DESCRIPTION:
XS GIS Cut Line= 3
      3779849.62     10580410.18      3778899.61     10581410.19
      3778399.63     10581910.17
#Sta/Elev= 30
  3617.8  366.28  3663.7  364.26  3730.9  361.96  3773.3  356.23  3851.4  335.93
  3937.2  322.74  4070.6  318.15  4315.2  315.51  4464.9  316.34  4473.5  318.57
  4494.9  318.83  4530.2  314.97  4558.9   315.4  4761.6  316.16  4892.1  317.24
  4913.7  317.92  4961.7  318.19    4969  316.14  4975.9  318.35  4990.7  308.92
  4993.4  308.42  4996.7  308.92  5023.3  315.85  5039.5  317.93  5364.8  315.29
  5462.6  318.15  5591.1  327.93  5647.7   337.3  5676.4  339.88  5704.2  341.94
#Mann= 14 ,-1 , 0
  3617.8     .05       0  3663.7     .16       0  3937.2     .05       0
  4315.2     .16       0  4464.9     .05       0  4558.9     .12       0
  4761.6     .16       0  4892.1     .12       0  4913.7     .16       0
  4990.7     .07       0  4996.7     .16       0  5023.3     .05       0
  5462.6     .16       0  5676.4     .05       0
Bank Sta=4975.9,5039.5
XS Rating Curve= 0 ,0
Exp/Cntr=0.3,0.1

Type RM Length L Ch R = 1 ,97562   ,488,488,488
BEGIN DESCRIPTION:
BOX CREEK 130.0
END DESCRIPTION:
XS GIS Cut Line= 3
       3779549.6      10580210.2      3778749.61     10581010.19
       3778349.6     10581810.21
#Sta/Elev= 30
  3847.9  366.86  3856.4  366.33  3904.5  359.06  3975.2  339.72  4032.7   330.6
  4088.3  326.26    4159  323.52  4215.6  322.18  4328.7   323.1  4371.1  320.76
  4399.4  321.77  4475.6  316.74    4555  314.21  4682.3  313.11    4982  316.21
  4987.6  314.85  4993.2  309.57  4998.6  307.15  5001.4  306.65  5004.6  307.15
  5015.6  313.53    5024  315.95  5026.5  315.91    5337  316.36  5359.4  313.84
  5434.9  315.66  5641.7  314.52  5747.9  316.95  5769.7  319.38  5873.7  336.27
#Mann= 8 ,-1 , 0
  3847.9     .05       0  3856.4     .16       0  4032.7     .05       0
  4475.6     .12       0  4998.6     .07       0  5004.6     .12       0
  5026.5     .05       0  5769.7     .16       0
Bank Sta=4982,5024
XS Rating Curve= 0 ,0
Exp/Cntr=0.3,0.1

Type RM Length L Ch R = 1 ,97074   ,581,581,581
BEGIN DESCRIPTION:
BOX CREEK 129.0
END DESCRIPTION:
XS GIS Cut Line= 3
      3779349.64     10579810.16      3778599.61     10580610.19
      3777749.64     10581860.15
#Sta/Elev= 30
  3862.3  370.35  3910.8  367.64  4003.8  354.69  4069.4  342.32  4168.3  331.57
  4407.2  318.39  4428.2  320.97  4498.8  316.75  4626.5  313.14  4902.5  314.22
  4916.7  307.24  4937.7  309.78    4945  306.57  4951.8  312.25  4955.5  306.39
  4987.4  307.71  4995.2  310.44  5014.3  305.92    5017  305.42  5020.3  305.92
  5044.3  314.33  5162.2  313.69  5297.5  312.73  5361.5  316.41  5484.3  317.31
    5592  313.55    5867  313.68  6023.1  316.17  6219.2  338.42  6470.5  343.06
#Mann= 10 ,-1 , 0
  3862.3     .05       0  3910.8     .12       0  4069.4     .16       0
  4168.3     .05       0  4498.8     .12       0  5014.3     .07       0
  5020.3     .12       0  5162.2     .05       0    5867     .12       0
  6219.2     .05       0
Bank Sta=4902.5,5044.3
XS Rating Curve= 0 ,0
Exp/Cntr=0.3,0.1

Type RM Length L Ch R = 1 ,96493   ,698,698,698
BEGIN DESCRIPTION:
BOX CREEK 128.0
END DESCRIPTION:
XS GIS Cut Line= 3
       3778949.6      10579760.2      3778449.61     10580160.19
      3777749.62     10581710.16
#Sta/Elev= 30
  4359.2  372.27  4401.6   367.9  4430.4  356.25  4530.3  333.65  4608.1  322.12
  4643.3  323.34  4657.7  320.01  4720.6  316.83  4878.6  311.09  4957.1  313.79
  4963.5  310.35  4971.5  313.67  4977.9  306.09  4993.3  305.81    4996  305.31
  4999.3  305.81  5013.8  306.72  5021.4  313.37  5307.6   312.9  5416.5   312.8
  5428.8  314.76  5446.4  312.48  5559.1  312.05  6211.3  313.15    6244  313.22
  6349.8     316  6419.5  323.34    6490  335.72  6530.6  339.59  6700.2  342.65
#Mann= 11 ,-1 , 0
  4359.2     .12       0  4530.3     .05       0  4720.6     .12       0
  4993.3     .07       0  4999.3     .12       0  5307.6     .05       0
  6211.3     .12       0    6244     .16       0  6349.8     .12       0
  6419.5     .16       0  6530.6     .05       0
Bank Sta=4971.5,5021.4
XS Rating Curve= 0 ,0
Exp/Cntr=0.3,0.1

Type RM Length L Ch R = 1 ,95795   ,574,574,574
BEGIN DESCRIPTION:
BOX CREEK 127.0
END DESCRIPTION:
XS GIS Cut Line= 3
       3778399.6     10579110.22      3778099.61     10579810.19
      3777549.61     10581210.19
#Sta/Elev= 30
  4248.6  375.14  4295.7  370.91  4357.4  363.81  4368.2  359.07  4409.9  351.37
  4538.7   337.1  4544.1   331.3  4562.3   332.2  4585.8  326.01  4614.8  327.26
  4643.9  322.61  4731.5  319.56  4879.8  314.21  4977.5  312.28  5016.7  304.94
  5019.4  304.44  5022.7  304.94  5031.6   312.7  5195.6  311.36  5512.9  311.53
  5537.4   308.9  5630.3  311.29  5903.1  312.01  5957.3  316.64  5998.6  312.43
  6245.7  313.34  6320.9  318.25  6428.4  333.46  6476.4  337.44  6514.3  338.19
#Mann= 10 ,-1 , 0
  4248.6     .12       0  4295.7     .16       0  4731.5     .05       0
  4879.8     .12       0  5016.7     .07       0  5022.7     .12       0
  5195.6     .05       0  5537.4     .12       0  5630.3     .05       0
  6476.4     .16       0
Bank Sta=4977.5,5031.6
XS Rating Curve= 0 ,0
Exp/Cntr=0.3,0.1

Type RM Length L Ch R = 1 ,95221   ,639,639,639
BEGIN DESCRIPTION:
BOX CREEK 126.0
END DESCRIPTION:
XS GIS Cut Line= 3
       3778349.6      10579060.2      3777749.61     10579610.19
       3777499.6     10581160.23
#Sta/Elev= 30
  4175.3  376.24  4267.5  366.94  4310.4  358.16  4359.4  349.95  4445.5  341.51
  4449.4  341.09  4584.8  327.53  4588.5  327.11  4635.6  320.07  4724.1  313.62
  4727.5  313.32  4863.5  310.18  4953.8  311.23  4961.2  311.03    4968  307.23
  4975.4  308.08  4982.1  303.67  4996.4  303.62  4999.1  303.12  5002.4  303.62
  5009.5  309.94  5022.7  311.12  5455.2  310.85  5475.4   308.1  5614.2  310.98
  5971.8  314.45  6335.4  314.87  6387.1  318.08  6498.5  336.26  6559.3  338.75
#Mann= 12 ,-1 , 0
  4175.3     .16       0  4310.4      .1       0  4445.5     .16       0
  4449.4      .1       0  4584.8     .12       0  4588.5     .07       0
  4724.1     .05       0  4727.5      .1       0  4863.5     .12       0
  4996.4     .07       0  5002.4     .12       0  5614.2     .05       0
Bank Sta=4953.8,5022.7
XS Rating Curve= 0 ,0
Exp/Cntr=0.3,0.1

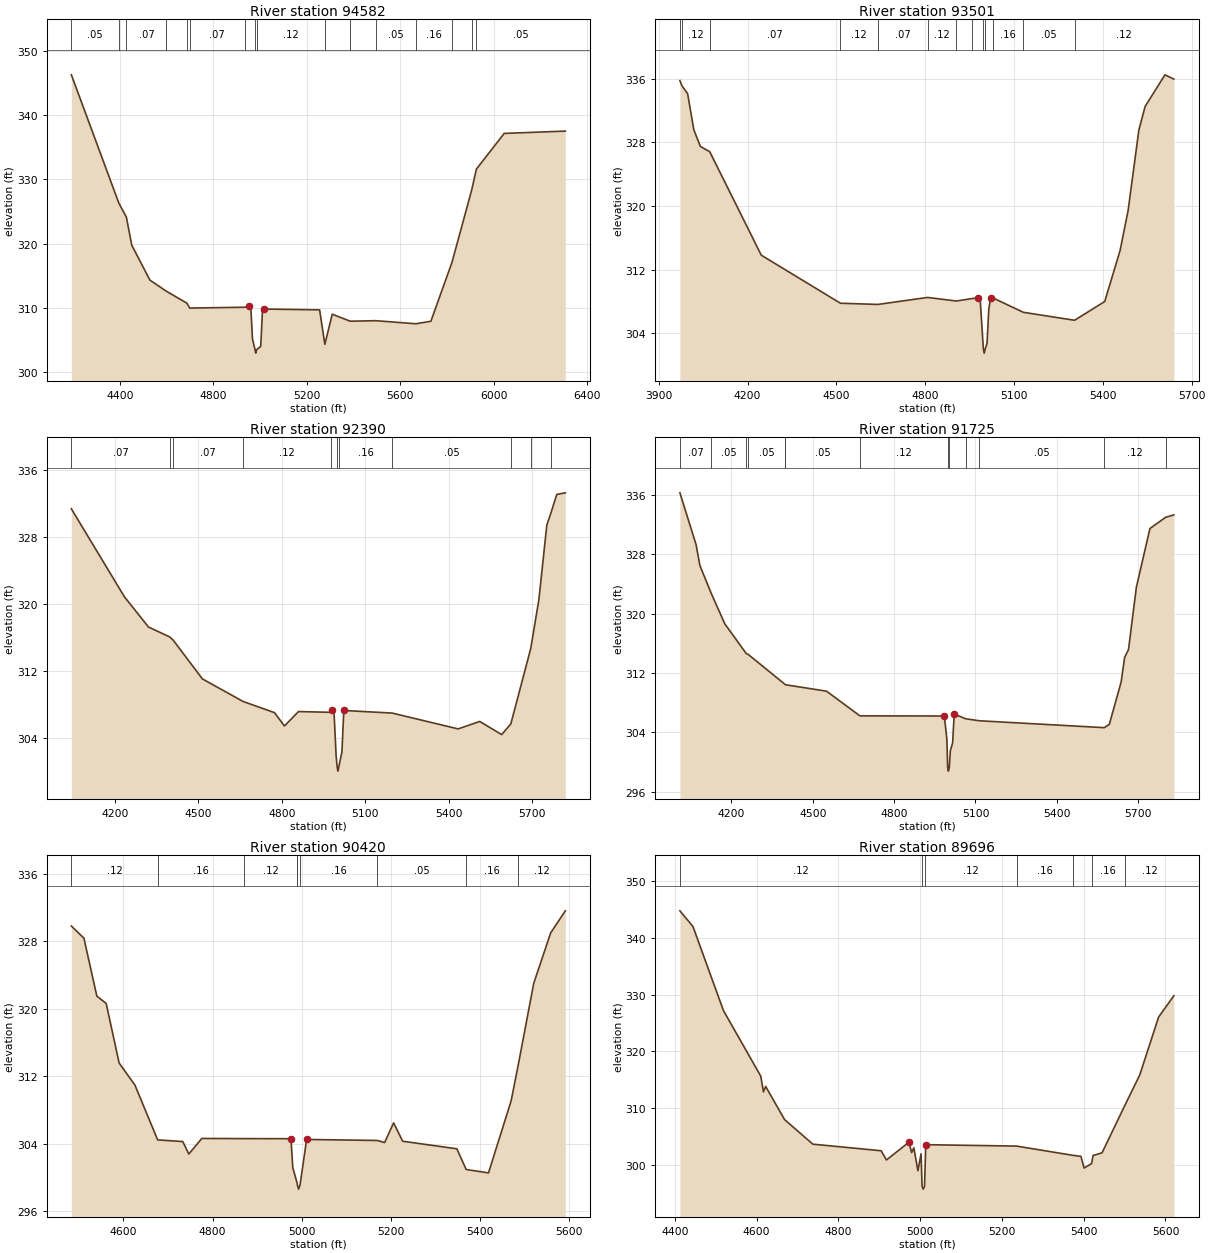
Type RM Length L Ch R = 1 ,94582   ,1081,1081,1081
BEGIN DESCRIPTION:
BOX CREEK 125.0
END DESCRIPTION:
XS GIS Cut Line= 3
      3777994.45     10578960.16      3777304.32     10579702.38
      3776288.71     10580123.38
#Sta/Elev= 30
  4193.2  346.32  4396.4   326.3  4428.6  324.12  4451.6  319.74  4529.3  314.29
  4599.4  312.56  4687.2   310.7  4699.4  309.93  4934.3  310.06  4953.8  310.21
  4960.7  310.09    4968   305.1  4979.2   303.4  4981.9   302.9  4985.2   303.4
  5003.2  303.95  5010.5  309.41  5017.4  309.78  5255.1  309.65  5277.5  304.28
  5309.2  308.97  5386.3  307.88  5495.1  307.96    5667  307.48  5731.1  307.87
  5821.4  317.07  5906.1  328.42  5925.7  331.61  6044.8  337.18  6306.1  337.54
#Mann= 16 ,-1 , 0
  4193.2     .05       0  4396.4     .12       0  4428.6     .07       0
  4599.4     .12       0  4687.2     .05       0  4699.4     .07       0
  4934.3     .12       0  4979.2     .07       0  4985.2     .12       0
  5277.5     .16       0  5386.3     .12       0  5495.1     .05       0
    5667     .16       0  5821.4     .12       0  5906.1     .16       0
  5925.7     .05       0
Bank Sta=4953.8,5017.4
XS Rating Curve= 0 ,0
Exp/Cntr=0.3,0.1

Type RM Length L Ch R = 1 ,93501   ,1111,1111,1111
BEGIN DESCRIPTION:
BOX CREEK 124.0
END DESCRIPTION:
XS GIS Cut Line= 3
      3777775.17     10578768.92      3777030.93     10579383.61
      3776436.59     10579759.51
#Sta/Elev= 30
  3971.4  335.77  3978.1  335.14  3997.5  334.13  4018.3  329.61  4040.5   327.5
  4072.1  326.84  4246.3  313.83  4513.7  307.79  4640.4  307.64  4808.1  308.52
  4905.3  308.07  4958.5  308.38  4978.3  308.44  4985.6  308.32  4996.5  302.02
  4999.3  301.52  5002.5  302.02  5008.9  302.77  5014.8  307.05  5021.1  308.51
  5028.2  308.47  5131.5  306.65  5304.5  305.65  5406.5  308.01  5458.2  314.41
  5485.3  319.43  5521.7  329.56  5542.9  332.53  5609.9   336.5  5639.9  335.96
#Mann= 13 ,-1 , 0
  3971.4     .05       0  3978.1     .12       0  4072.1     .07       0
  4513.7     .12       0  4640.4     .07       0  4808.1     .12       0
  4905.3     .16       0  4958.5     .12       0  4996.5     .07       0
  5002.5     .12       0  5028.2     .16       0  5131.5     .05       0
  5304.5     .12       0
Bank Sta=4978.3,5021.1
XS Rating Curve= 0 ,0
Exp/Cntr=0.3,0.1

Type RM Length L Ch R = 1 ,92390   ,665,665,665
BEGIN DESCRIPTION:
BOX CREEK 123.0
END DESCRIPTION:
XS GIS Cut Line= 3
        3777671.     10578415.88      3776916.63     10578939.11
      3776266.38     10579500.46
#Sta/Elev= 30
  4042.7  331.38  4233.8  320.87  4320.2  317.27  4396.4  316.09  4408.5  315.73
  4514.1  311.08  4660.2  308.39  4773.5  307.05  4809.3  305.46  4859.8  307.18
  4976.3  307.09    4981  307.34  4987.6  307.16  4995.3  301.86  4998.9  300.57
  5001.6  300.07  5004.9  300.57  5016.1  302.34  5022.9  307.31  5196.7     307
  5434.1  305.11    5512     306  5590.9  304.43  5623.8  305.71  5695.2  314.68
  5724.8  320.56  5753.3  329.45  5767.5  330.83  5789.1   333.1  5819.8  333.29
#Mann= 11 ,-1 , 0
  4042.7     .07       0  4396.4     .05       0  4408.5     .07       0
  4660.2     .12       0  4976.3     .16       0  4998.9     .07       0
  5004.9     .16       0  5196.7     .05       0  5623.8     .12       0
  5695.2     .16       0  5767.5     .12       0
Bank Sta=4981,5022.9
XS Rating Curve= 0 ,0
Exp/Cntr=0.3,0.1

Type RM Length L Ch R = 1 ,91725   ,1305,1305,1305
BEGIN DESCRIPTION:
BOX CREEK 122.0
END DESCRIPTION:
XS GIS Cut Line= 4
      3777373.82     10578050.14      3776789.64       10578614.
      3776670.26     10578801.96      3776045.42     10579279.48
#Sta/Elev= 30
  4010.3  336.28    4070  329.29  4084.1  326.47  4126.5  322.67    4176  318.61
  4254.9  314.61  4262.3  314.49  4397.7  310.46  4398.6  310.41  4550.8  309.54
  4673.9  306.21  4985.1  306.19  4994.5  303.09  4997.4  299.26  5000.1  298.76
  5003.4  299.26  5007.2  301.52  5015.6  302.54  5021.6  306.46  5063.7  305.82
  5113.9  305.55  5574.5  304.62  5593.4  305.06    5637  310.78  5649.8   314.1
  5664.1  315.15  5693.2  323.57  5743.1  331.47  5800.6  332.97  5831.3  333.31
#Mann= 13 ,-1 , 0
  4010.3     .07       0  4126.5     .05       0  4254.9     .12       0
  4262.3     .05       0  4397.7     .12       0  4398.6     .05       0
  4673.9     .12       0  4997.4     .07       0  5003.4     .12       0
  5063.7     .16       0  5113.9     .05       0  5574.5     .12       0
  5800.6     .16       0
Bank Sta=4985.1,5021.6
XS Rating Curve= 0 ,0
Exp/Cntr=0.3,0.1

Type RM Length L Ch R = 1 ,90420   ,724,724,724
BEGIN DESCRIPTION:
BOX CREEK 121.0
END DESCRIPTION:
XS GIS Cut Line= 3
      3776799.57     10578210.22      3776399.61     10578510.19
      3775799.64     10578410.19
#Sta/Elev= 30
  4483.2  329.83  4511.3   328.4  4540.4  321.51  4561.3  320.64  4590.4  313.56
  4625.9  310.93  4676.8  304.43  4733.2  304.23  4746.7  302.75  4775.9   304.6
  4870.2  304.58  4975.9  304.57    4980  301.13  4989.9  299.26  4990.3  299.08
    4993  298.58  4996.3  299.08    5011  304.48    5170  304.36  5185.9  304.11
  5206.2  306.45  5226.5  304.27  5348.1  303.37    5369  300.91  5419.1  300.51
  5469.8  309.06  5485.4  313.22  5520.5  323.02  5558.5  329.01  5591.4  331.64
#Mann= 9 ,-1 , 0
  4483.2     .12       0  4676.8     .16       0  4870.2     .12       0
  4989.9     .16       0  4990.3     .07       0  4996.3     .16       0
    5170     .05       0    5369     .16       0  5485.4     .12       0
Bank Sta=4975.9,5011
XS Rating Curve= 0 ,0
Exp/Cntr=0.3,0.1

Type RM Length L Ch R = 1 ,89696   ,602,602,602
BEGIN DESCRIPTION:
BOX CREEK 120.0
END DESCRIPTION:
XS GIS Cut Line= 3
      3776899.65     10577860.17      3776349.61     10578110.19
      3775799.65     10578360.17
#Sta/Elev= 30
  4412.2  344.81  4444.1  342.05  4518.8   327.2    4610  315.65  4616.6  312.87
    4622  313.84  4668.2  307.99  4737.4  303.65  4904.4  302.49  4917.5  300.86
  4972.5     304    4979  302.16  4984.5  303.01  4994.4  298.96  5002.1  301.94
  5004.6  296.22  5007.4  295.72  5010.6  296.22  5013.6  303.56  5235.6  303.31
  5373.7  301.68  5393.2   301.5  5400.9  299.44  5419.2  300.22  5422.8  301.65
  5444.8  302.12  5500.8  310.51  5537.1  315.86  5583.2  326.07  5620.5  329.83
#Mann= 7 ,-1 , 0
  4412.2     .12       0  5004.6     .07       0  5010.6     .12       0
  5235.6     .16       0  5373.7     .12       0  5419.2     .16       0
  5500.8     .12       0
Bank Sta=4972.5,5013.6
XS Rating Curve= 0 ,0
Exp/Cntr=0.3,0.1

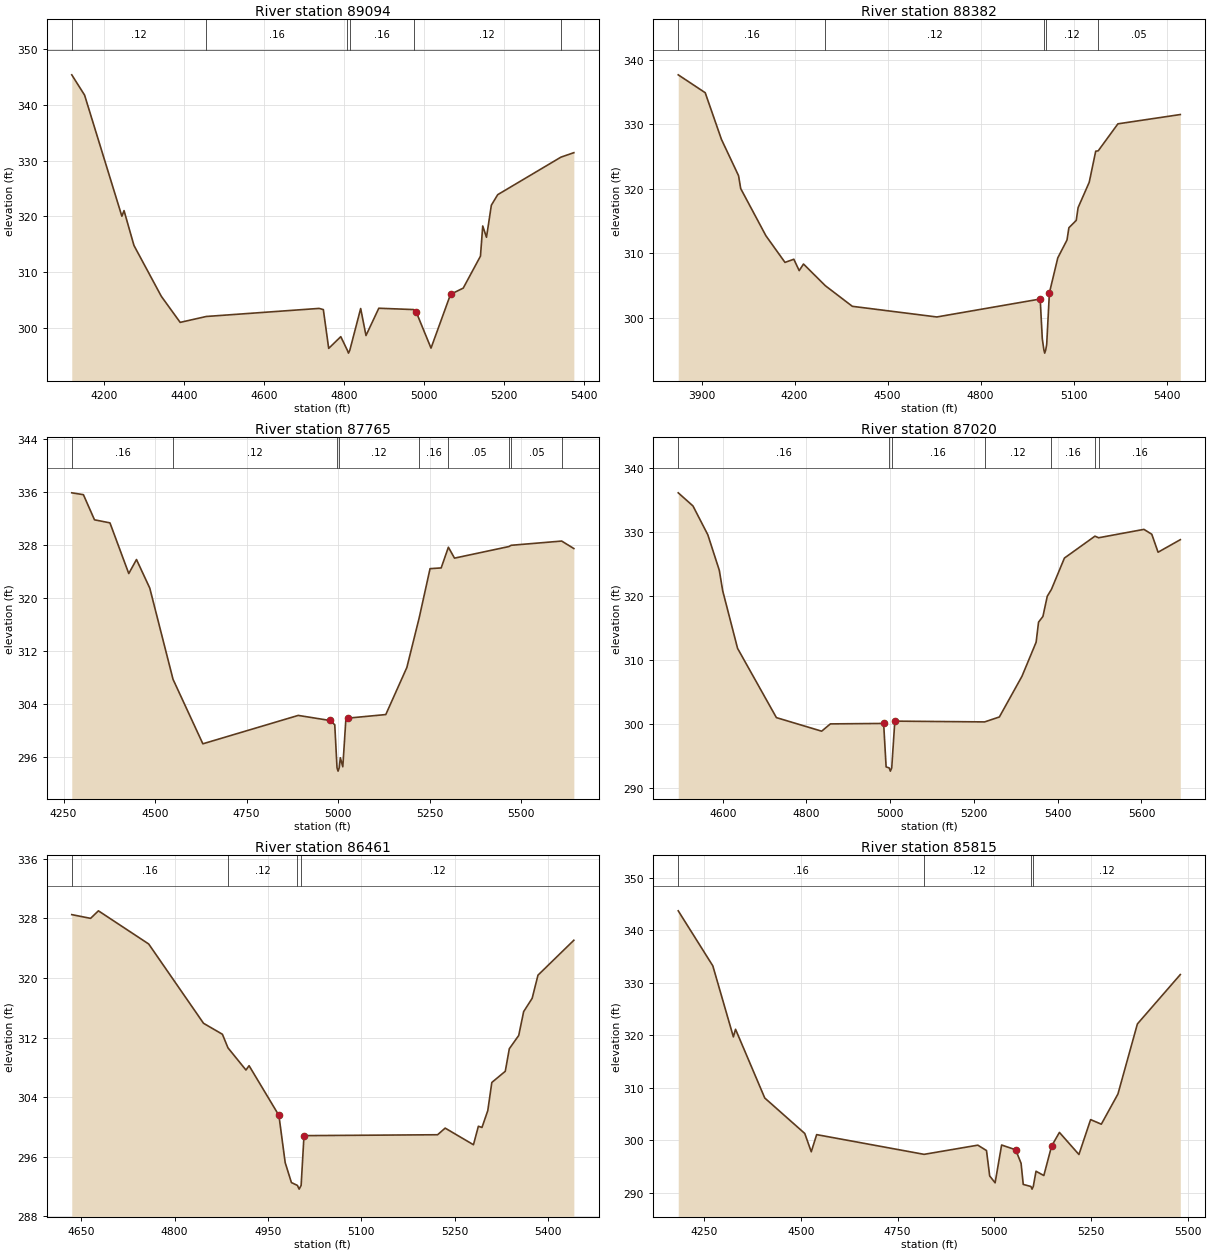
Type RM Length L Ch R = 1 ,89094   ,712,712,712
BEGIN DESCRIPTION:
BOX CREEK 119.0
END DESCRIPTION:
XS GIS Cut Line= 3
      3776749.63     10577660.18      3775949.61     10577960.19
      3775749.63     10578310.15
#Sta/Elev= 30
  4118.1  345.41  4150.2  341.77  4243.6  320.02    4249  321.03  4273.9  314.77
  4342.4  305.64  4389.6  300.96    4455  302.02  4737.6  303.47  4748.2  303.26
  4761.6  296.29  4791.9   298.4  4808.4  295.94  4811.2  295.44  4814.4  295.94
  4841.7  303.45    4855   298.6  4887.1   303.5  4974.6  303.26  4980.4  302.89
  5017.9  296.34  5066.8     306  5098.5  307.11  5141.7  312.85  5147.4  318.27
  5156.8  316.24    5169     322  5184.9  323.89  5343.3  330.63  5375.6  331.43
#Mann= 6 ,-1 , 0
  4118.1     .12       0    4455     .16       0  4808.4     .07       0
  4814.4     .16       0  4974.6     .12       0  5343.3     .05       0
Bank Sta=4980.4,5066.8
XS Rating Curve= 0 ,0
Exp/Cntr=0.3,0.1

Type RM Length L Ch R = 1 ,88382   ,617,617,617
BEGIN DESCRIPTION:
BOX CREEK 118.0
END DESCRIPTION:
XS GIS Cut Line= 3
      3776976.12     10576969.73      3776003.91     10577421.11
      3775553.59     10577732.87
#Sta/Elev= 30
  3824.7  337.66  3911.7  334.89  3964.2  327.65  4019.3  322.04  4026.2  320.05
  4107.5  312.74  4169.1  308.61  4197.6   309.1  4214.9  307.34  4228.8  308.36
  4299.2     305  4386.3  301.81  4658.8  300.16  4992.3  302.94  4999.1   296.8
  5004.2  295.06  5006.9  294.56  5010.2  295.06  5013.3  295.93    5022   303.9
  5049.1  309.32  5078.8  312.08  5084.9  313.98  5108.5  315.11  5114.6   317.1
  5150.4  321.01  5171.4  325.83  5179.5  325.89    5243  330.07  5444.3  331.51
#Mann= 5 ,-1 , 0
  3824.7     .16       0  4299.2     .12       0  5004.2     .07       0
  5010.2     .12       0  5179.5     .05       0
Bank Sta=4992.3,5022
XS Rating Curve= 0 ,0
Exp/Cntr=0.3,0.1

Type RM Length L Ch R = 1 ,87765   ,745,745,745
BEGIN DESCRIPTION:
BOX CREEK 117.0
END DESCRIPTION:
XS GIS Cut Line= 3
      3776170.56     10576636.42      3775837.25     10577150.28
      3775198.33     10577560.01
#Sta/Elev= 30
  4272.3  335.85  4304.1  335.57  4334.4  331.77  4376.6  331.31    4428  323.65
  4449.1  325.77  4485.4  321.45  4548.9  307.67  4630.4  297.92  4890.9  302.21
    4977  301.45  4990.7   300.8  4996.9  294.29  4999.7  293.79  5002.9  294.29
  5005.9  295.81  5012.7  294.45  5021.1  301.67    5027   301.8  5130.1  302.34
  5187.6  309.45  5221.4  316.97    5251  324.39  5281.4   324.5  5301.1  327.63
  5317.8  325.98  5466.4  327.73  5472.6  327.92  5610.6  328.56  5643.8  327.43
#Mann= 9 ,-1 , 0
  4272.3     .16       0  4548.9     .12       0  4996.9     .07       0
  5002.9     .12       0  5221.4     .16       0  5301.1     .05       0
  5466.4     .16       0  5472.6     .05       0  5610.6     .16       0
Bank Sta=4977,5027
XS Rating Curve= 0 ,0
Exp/Cntr=0.3,0.1

Type RM Length L Ch R = 1 ,87020   ,559,559,559
BEGIN DESCRIPTION:
BOX CREEK 116.0
END DESCRIPTION:
XS GIS Cut Line= 3
       3775958.8     10576551.36      3775602.94     10576811.75
      3774874.16     10577019.97
#Sta/Elev= 30
  4493.8  336.12    4529  334.07  4564.5  329.56  4591.9  324.01    4600  320.81
  4635.5  311.82  4728.2     301  4836.3  298.88  4857.1  300.02  4984.3  300.09
  4990.2   293.3  4997.6  293.14  5000.4  292.64  5003.6  293.14    5011  300.45
  5225.5  300.33  5260.6   301.1  5314.6  307.46  5348.4  312.78  5354.2  315.92
  5364.6   316.8    5375  319.96  5384.9  321.03    5416  325.93  5488.9  329.35
  5497.6   329.1  5605.8  330.41  5624.6  329.65  5639.6  326.84  5692.7   328.8
#Mann= 7 ,-1 , 0
  4493.8     .16       0  4997.6     .07       0  5003.6     .16       0
  5225.5     .12       0  5384.9     .16       0  5488.9     .05       0
  5497.6     .16       0
Bank Sta=4984.3,5011
XS Rating Curve= 0 ,0
Exp/Cntr=0.3,0.1

Type RM Length L Ch R = 1 ,86461   ,646,646,646
BEGIN DESCRIPTION:
BOX CREEK 115.0
END DESCRIPTION:
XS GIS Cut Line= 3
      3775849.61     10576310.19      3775449.61     10576360.19
      3775099.64     10576560.17
#Sta/Elev= 30
    4635  328.52  4665.2  328.02  4677.8  329.03  4758.5  324.58  4846.6  313.93
  4876.9  312.46  4885.8  310.64  4914.7  307.66  4919.7  308.24  4967.6  301.57
  4977.7  295.23  4987.7  292.55  4997.3  292.17  5000.1  291.67  5003.3  292.17
  5007.9  298.85  5222.4  298.97  5234.6  299.86    5280  297.63  5287.9  300.11
  5293.7  299.95    5303  302.21  5309.5  305.99  5331.1  307.49  5337.6  310.52
  5352.7   312.3  5360.6   315.5  5374.3  317.29  5383.6  320.39  5441.2  325.08
#Mann= 4 ,-1 , 0
    4635     .16       0  4885.8     .12       0  4997.3     .07       0
  5003.3     .12       0
Bank Sta=4967.6,5007.9
XS Rating Curve= 0 ,0
Exp/Cntr=0.3,0.1

Type RM Length L Ch R = 1 ,85815   ,619,619,619
BEGIN DESCRIPTION:
BOX CREEK 114.0
END DESCRIPTION:
XS GIS Cut Line= 3
      3776049.57     10575660.21      3775249.61     10576060.19
      3774849.61     10576110.19
#Sta/Elev= 30
  4183.2  343.72  4272.6  333.23  4325.7  319.69  4331.3  321.14  4406.8  308.04
  4510.2  301.28    4527  297.79  4540.9  301.06  4818.5   297.3  4957.4  299.05
  4979.8  298.03  4988.1  293.18  5002.1  291.87  5018.9  299.08  5055.2  298.17
  5069.2  295.59  5074.8  291.57  5094.7  291.17  5097.5  290.67  5100.7  291.17
  5107.8  294.08    5128  293.26  5148.1  298.88  5168.3  301.48  5218.7  297.27
  5248.9  303.92  5276.6  303.05  5319.5   308.8  5369.8  322.16  5480.7  331.57
#Mann= 4 ,-1 , 0
  4183.2     .16       0  4818.5     .12       0  5094.7     .07       0
  5100.7     .12       0
Bank Sta=5055.2,5148.1
XS Rating Curve= 0 ,0
Exp/Cntr=0.3,0.1