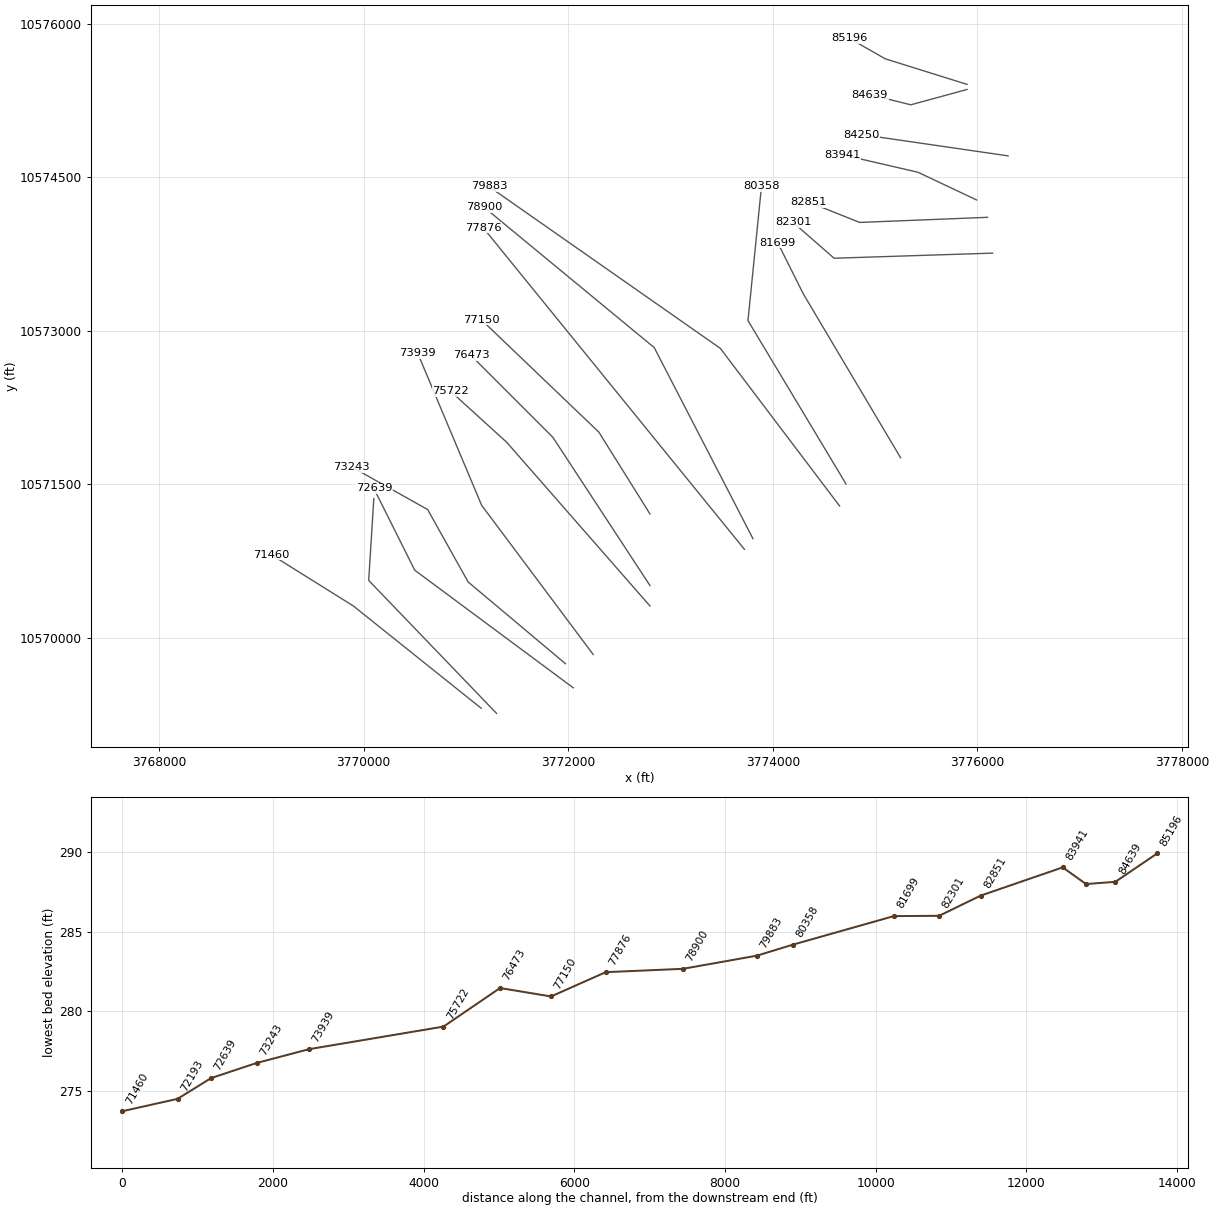
HEC-RAS study BOX CREEK.prj: BOX CREEK Base Level Engineering

--- BOX CREEK.g01 (geometry) --- (continued)

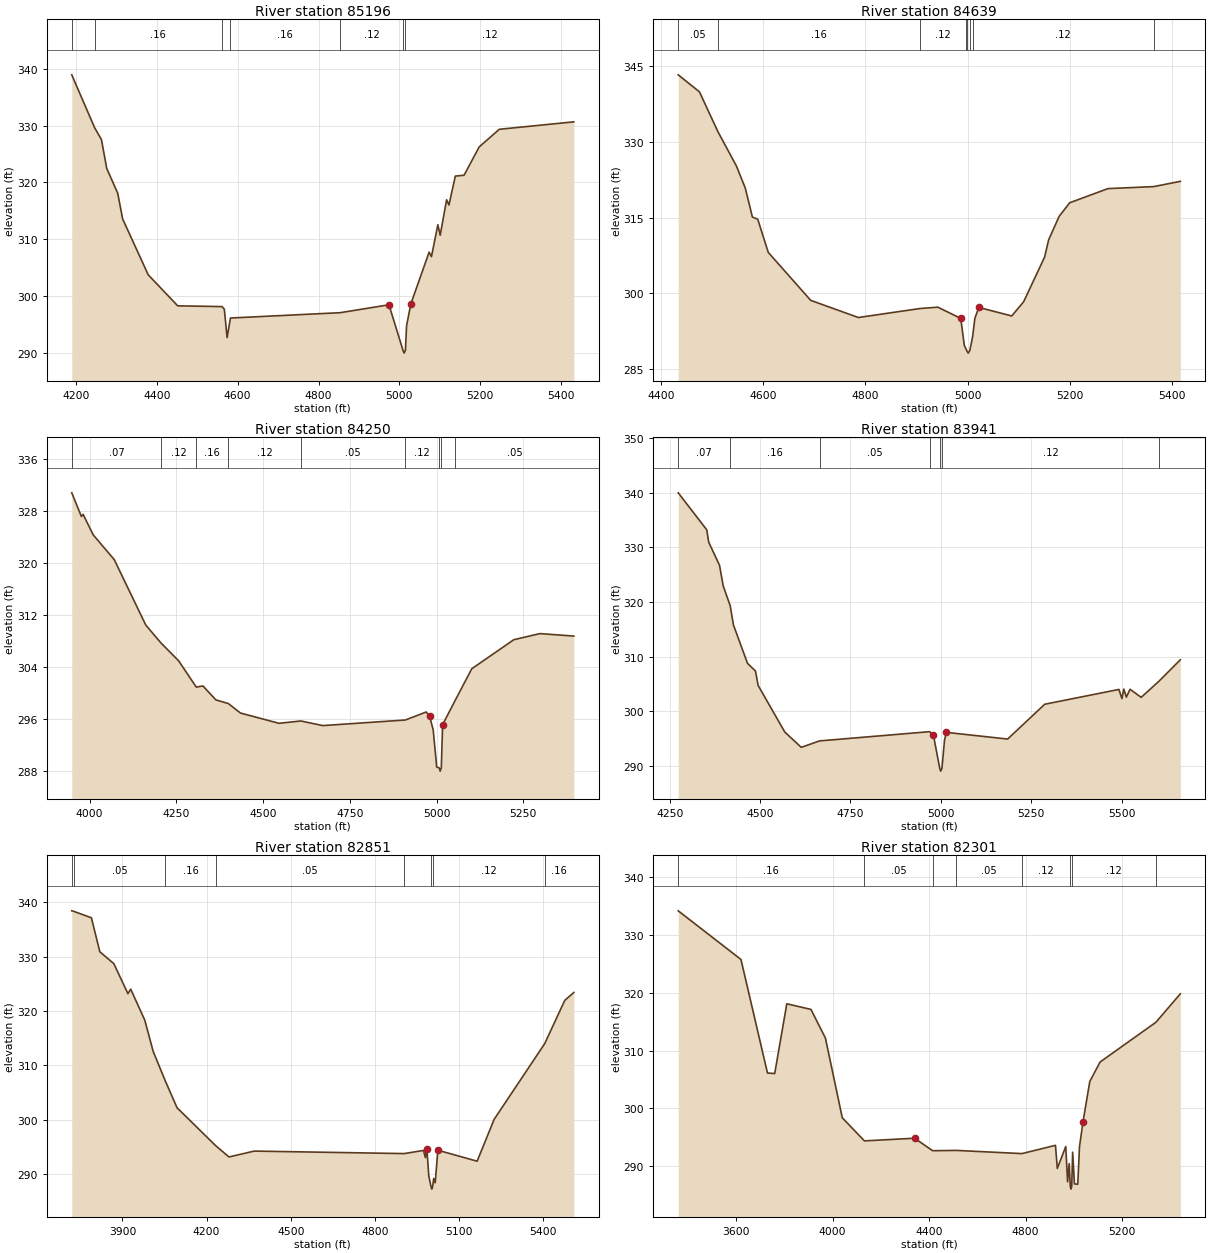
Type RM Length L Ch R = 1 ,85196   ,557,557,557
BEGIN DESCRIPTION:
BOX CREEK 113.0
END DESCRIPTION:
XS GIS Cut Line= 3
      3775899.63     10575410.18      3775099.61     10575660.19
       3774749.6      10575860.2
#Sta/Elev= 30
  4189.9  338.94  4246.5  329.62  4263.3  327.53  4276.4  322.45  4303.6  318.08
  4315.6  313.58    4379  303.72  4451.8  298.27  4561.4  298.13  4567.1  297.67
  4573.9  292.67  4582.2  296.12  4853.5  297.06  4974.1  298.45  5008.8  290.44
  5011.6  289.94  5014.8  290.44  5017.6  294.73  5028.1  298.58  5073.4  307.72
  5079.2  306.93    5095  312.54  5100.8   310.7  5116.6  316.94  5122.4  316.02
  5138.2  321.11  5159.8  321.26  5197.2  326.25  5246.9  329.35  5431.2  330.66
#Mann= 7 ,-1 , 0
  4189.9     .05       0  4246.5     .16       0  4561.4     .12       0
  4582.2     .16       0  4853.5     .12       0  5008.8     .07       0
  5014.8     .12       0
Bank Sta=4974.1,5028.1
XS Rating Curve= 0 ,0
Exp/Cntr=0.3,0.1

Type RM Length L Ch R = 1 ,84639   ,389,389,389
BEGIN DESCRIPTION:
BOX CREEK 112.0
END DESCRIPTION:
XS GIS Cut Line= 3
      3775899.63     10575360.19      3775349.61     10575210.19
      3774949.63     10575310.18
#Sta/Elev= 30
  4433.6  343.25  4475.1  339.88  4511.3  331.99  4547.6  325.17  4564.9   320.8
  4578.7  315.09  4589.1  314.67  4609.8  308.09  4692.8   298.6    4786   295.2
  4906.7  296.98  4941.5  297.25  4986.4  295.03  4993.3  289.73  4996.3  289.06
  4998.1  288.65  5000.9  288.15  5004.1  288.65  5009.7  291.47    5014  295.04
  5021.7   297.2  5086.2  295.51  5109.4  298.31  5150.6  307.19  5158.3  310.56
  5178.9  315.23  5199.6  317.92  5274.3  320.72    5364  321.12    5416  322.16
#Mann= 8 ,-1 , 0
  4433.6     .05       0  4511.3     .16       0  4906.7     .12       0
  4996.3     .16       0  4998.1     .07       0  5004.1     .16       0
  5009.7     .12       0    5364     .05       0
Bank Sta=4986.4,5021.7
XS Rating Curve= 0 ,0
Exp/Cntr=0.3,0.1

Type RM Length L Ch R = 1 ,84250   ,309,309,309
BEGIN DESCRIPTION:
BOX CREEK 111.0
END DESCRIPTION:
XS GIS Cut Line= 2
       3776300.8     10574711.04      3774868.47     10574919.38
#Sta/Elev= 30
  3948.5  330.79  3976.2  327.16  3981.2  327.48  4010.3  324.33    4071  320.52
  4161.9  310.46  4206.2  307.68  4256.6  304.97  4307.4  300.93  4326.7   301.1
    4364  298.96  4399.8   298.4  4434.8  296.94  4545.9  295.36  4608.9  295.72
  4672.1  295.01  4910.4  295.87  4970.3   297.1  4980.4  296.41  4990.5  294.32
  5000.6  288.63  5007.8  288.51  5010.5  288.01  5013.8  288.51  5017.6  295.15
    5054   298.9  5101.7  303.75  5222.9  308.21    5298  309.15  5395.9  308.77
#Mann= 9 ,-1 , 0
  3948.5     .07       0  4206.2     .12       0  4307.4     .16       0
  4399.8     .12       0  4608.9     .05       0  4910.4     .12       0
  5007.8     .07       0  5013.8     .12       0    5054     .05       0
Bank Sta=4980.4,5017.6
XS Rating Curve= 0 ,0
Exp/Cntr=0.3,0.1

Type RM Length L Ch R = 1 ,83941   ,1090,1090,1090
BEGIN DESCRIPTION:
BOX CREEK 110.0
END DESCRIPTION:
XS GIS Cut Line= 3
      3775992.81       10574280.      3775419.91     10574550.83
       3774684.2     10574720.87
#Sta/Elev= 30
  4273.7  339.99  4352.6  333.22  4358.1  330.94  4387.9  326.73  4398.1  322.96
  4417.4  319.34  4426.4  315.81  4465.3  308.79  4487.4  307.37  4494.7  304.74
  4568.5  296.21    4614  293.41  4664.5  294.59  4969.1  296.28  4979.5  295.67
  4997.1  289.56  4999.8  289.06  5003.1  289.56  5010.3  294.76  5015.5  296.15
  5184.8  294.93  5287.5   301.3  5492.7  304.01    5501  302.34  5506.1  304.08
  5513.3   302.6  5523.5  304.04  5554.3  302.56  5603.4  305.51  5662.5  309.44
#Mann= 7 ,-1 , 0
  4273.7     .07       0  4417.4     .16       0  4664.5     .05       0
  4969.1     .12       0  4997.1     .07       0  5003.1     .12       0
  5603.4     .16       0
Bank Sta=4979.5,5015.5
XS Rating Curve= 0 ,0
Exp/Cntr=0.3,0.1

Type RM Length L Ch R = 1 ,82851   ,550,550,550
BEGIN DESCRIPTION:
BOX CREEK 109.0
END DESCRIPTION:
XS GIS Cut Line= 3
      3776099.56     10574110.19      3774849.61     10574060.19
      3774349.58      10574260.2
#Sta/Elev= 30
  3719.6  338.42  3725.9  338.34  3789.6  337.14  3819.6   330.9  3869.7   328.7
  3919.7   323.2  3929.7  324.03  3979.8  318.34  4009.8  312.58  4052.7   307.2
  4094.9  302.23  4232.4  295.27    4280  293.19  4370.1  294.27  4904.4  293.81
  4973.2  294.39    4980  293.08  4985.4  294.65  4992.1   289.7  4999.9  287.78
  5002.6  287.28  5005.9  287.78  5009.6  289.25    5015  288.45  5024.4  294.43
  5164.4  292.41    5225   300.1  5405.4  314.03  5476.8  321.97  5509.1  323.42
#Mann= 8 ,-1 , 0
  3719.6     .16       0  3725.9     .05       0  4052.7     .16       0
  4232.4     .05       0  4904.4     .12       0  4999.9     .07       0
  5005.9     .12       0  5405.4     .16       0
Bank Sta=4985.4,5024.4
XS Rating Curve= 0 ,0
Exp/Cntr=0.3,0.1

Type RM Length L Ch R = 1 ,82301   ,602,602,602
BEGIN DESCRIPTION:
BOX CREEK 108.0
END DESCRIPTION:
XS GIS Cut Line= 3
      3776149.65     10573760.19      3774599.61     10573710.19
      3774199.57     10574060.22
#Sta/Elev= 30
  3359.6  334.18  3619.8  325.76  3729.8   306.1  3759.8  306.02  3809.9  318.09
  3909.9  317.12    3970  312.17    4040  298.36  4131.9  294.36  4340.1  294.82
  4414.5  292.66  4513.4  292.71  4785.1  292.16  4924.2  293.59  4931.8   289.6
  4966.9  293.39  4974.5  287.27  4981.2  290.43  4985.7  286.51  4988.5  286.01
  4991.7  286.51  4995.4   292.4    5003  286.91  5016.7  286.86  5023.9  293.36
  5038.1  297.57  5066.6  304.65  5109.3  308.01  5340.8  314.89    5442  319.81
#Mann= 8 ,-1 , 0
  3359.6     .16       0  4131.9     .05       0  4414.5     .08       0
  4513.4     .05       0  4785.1     .12       0  4985.7     .07       0
  4991.7     .12       0  5340.8     .16       0
Bank Sta=4340.1,5038.1
XS Rating Curve= 0 ,0
Exp/Cntr=0.3,0.1

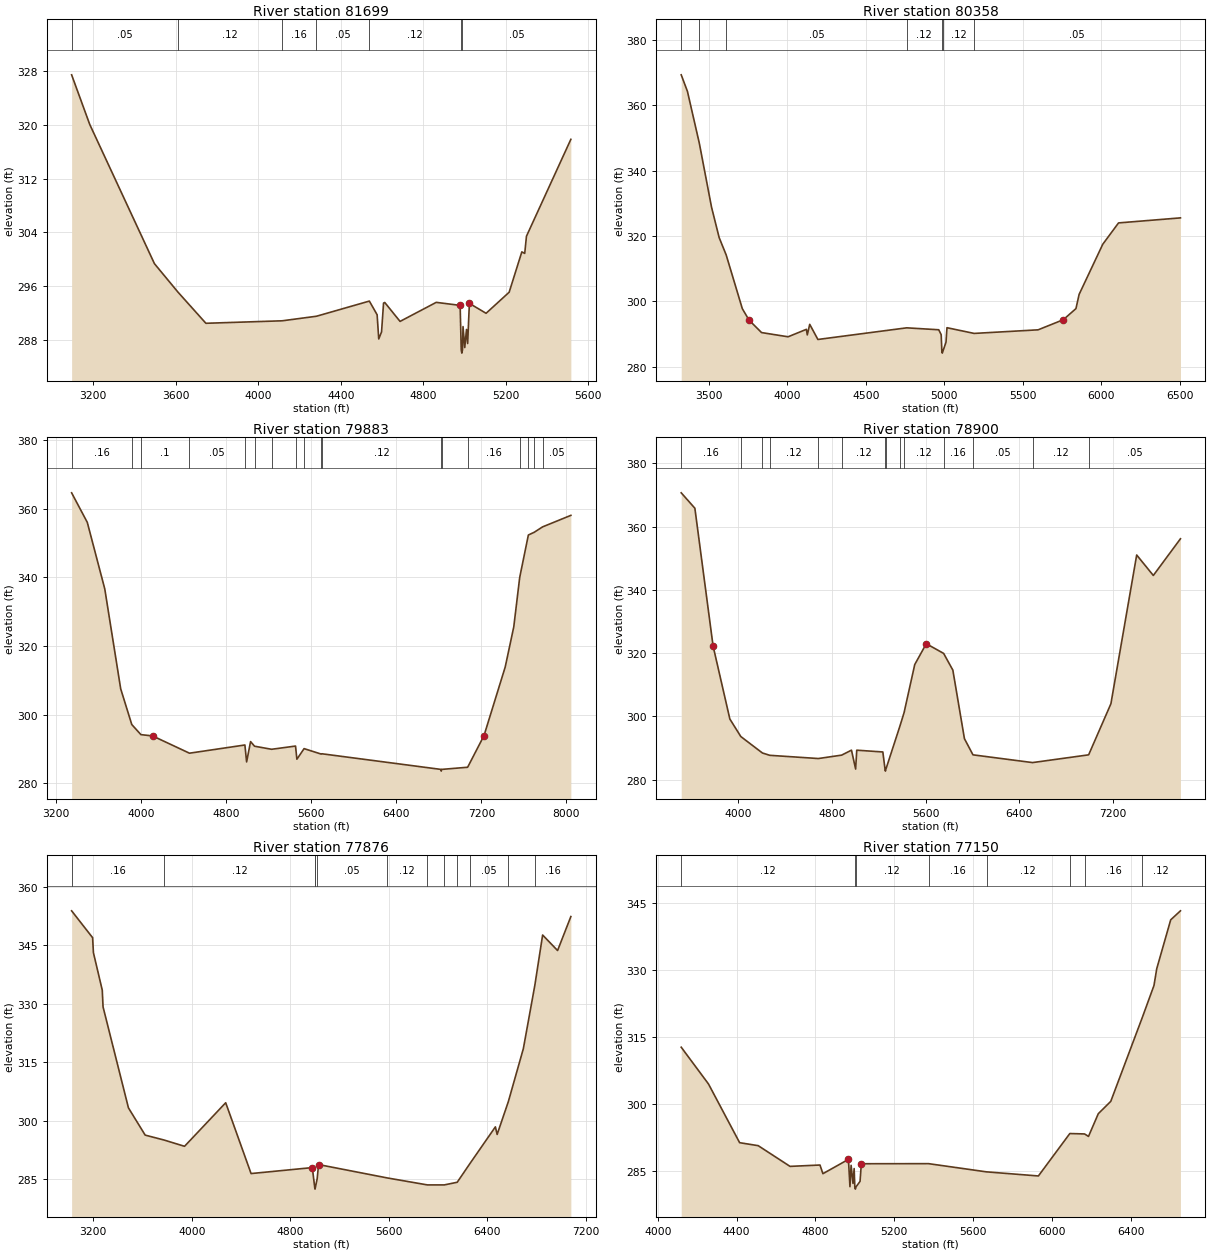
Type RM Length L Ch R = 1 ,81699   ,1341,1341,1341
BEGIN DESCRIPTION:
BOX CREEK 107.0
END DESCRIPTION:
XS GIS Cut Line= 3
      3775249.61     10571760.19      3774299.61     10573360.19
      3774049.61     10573860.19
#Sta/Elev= 30
  3095.6  327.49  3183.3   320.1    3497  299.33  3610.7   295.1  3746.4  290.44
  4116.2  290.81  4282.3  291.49  4538.7  293.75  4576.4  291.71  4584.2   288.1
  4597.8  289.16  4607.5  293.45  4613.4  293.54  4687.5  290.72  4862.9  293.56
  4978.7  293.11  4984.1  286.49  4986.9  285.99  4990.1  286.49  4992.7  289.95
  5001.1  286.82  5009.5  289.52  5015.1  287.42  5023.5  293.41  5104.5  291.93
  5216.3  295.07  5277.8  301.09  5291.8  300.86  5300.2  303.42  5515.4  317.87
#Mann= 7 ,-1 , 0
  3095.6     .05       0  3610.7     .12       0  4116.2     .16       0
  4282.3     .05       0  4538.7     .12       0  4984.1     .03       0
  4990.1     .05       0
Bank Sta=4978.7,5023.5
XS Rating Curve= 0 ,0
Exp/Cntr=0.3,0.1

Type RM Length L Ch R = 1 ,80358   ,475,475,475
BEGIN DESCRIPTION:
BOX CREEK 106.0
END DESCRIPTION:
XS GIS Cut Line= 3
       3774716.2     10571503.19      3773757.89     10573100.38
      3773889.83     10574412.84
#Sta/Elev= 30
  3323.2  369.36  3362.8   364.3  3438.6  348.42  3516.4  328.86    3565  319.54
  3609.6  314.26  3712.7  297.79  3755.5  294.29  3835.2  290.48  4004.2  289.19
  4120.9  291.47  4126.7  289.77  4142.2     293  4194.3  288.37  4760.1  291.93
  4964.4  291.34    4980  289.83  4984.4  284.69  4987.1  284.19  4990.4  284.69
  5010.7  287.53  5016.9  291.97  5190.2  290.22  5597.7  291.32  5758.5  294.42
  5838.9  297.82    5859  302.15  6009.8  317.51  6110.3  324.04  6504.9  325.58
#Mann= 7 ,-1 , 0
  3323.2     .12       0  3438.6     .16       0  3609.6     .05       0
  4760.1     .12       0  4984.4     .07       0  4990.4     .12       0
  5190.2     .05       0
Bank Sta=3755.5,5758.5
XS Rating Curve= 0 ,0
Exp/Cntr=0.3,0.1

Type RM Length L Ch R = 1 ,79883   ,983,983,983
BEGIN DESCRIPTION:
BOX CREEK 105.0
END DESCRIPTION:
XS GIS Cut Line= 3
       3774653.7     10571287.91      3773487.05     10572829.55
      3771223.86     10574412.39
#Sta/Elev= 30
  3346.2  364.65  3493.6  356.03  3657.9  336.64  3807.7   307.5  3911.9  297.09
  3997.9  294.14  4107.4  293.77  4454.4  288.73  4975.7  291.12  4991.9  286.18
  5029.1  292.11  5066.8  290.76  5226.8  289.87    5452  290.81  5464.7  286.97
  5532.4  290.06  5694.7  288.46    5700  288.56  6819.4     284  6822.2   283.5
  6825.4     284  7070.5  284.63  7224.4  293.85  7424.1  313.88  7504.4  325.56
  7560.1  339.96  7641.6  352.35  7695.7  353.13  7775.4  354.72  8041.3  358.08
#Mann= 18 ,-1 , 0
  3346.2     .16       0  3911.9     .05       0  3997.9      .1       0
  4454.4     .05       0  4975.7     .12       0  5066.8     .16       0
  5226.8     .05       0    5452     .16       0  5532.4     .05       0
  5694.7     .16       0    5700     .12       0  6819.4     .07       0
  6825.4     .12       0  7070.5     .16       0  7560.1      .1       0
  7641.6     .05       0  7695.7      .1       0  7775.4     .05       0
Bank Sta=4107.4,7224.4
XS Rating Curve= 0 ,0
Exp/Cntr=0.3,0.1

Type RM Length L Ch R = 1 ,78900   ,1024,1024,1024
BEGIN DESCRIPTION:
BOX CREEK 104.0
END DESCRIPTION:
XS GIS Cut Line= 3
      3773806.51     10570968.41      3772841.22     10572836.49
      3771174.54      10574211.5
#Sta/Elev= 30
  3512.4  370.67    3629   365.8  3784.5  322.24  3927.8  299.14  4021.5   293.6
  4205.6  288.41  4268.4  287.67  4683.7  286.65  4882.7  287.73  4966.4   289.3
  5001.8  283.32  5011.5  289.29  5234.2  288.73  5253.3  283.17  5256.1  282.67
  5259.3  283.17  5378.3   296.7  5415.6  301.17  5506.7  316.37  5605.1  322.96
  5753.5  319.89  5832.1  314.61  5931.1  292.93    6004  287.82  6512.7  285.37
  6991.8  287.82  7181.9  303.97  7402.1  351.01  7544.1  344.54  7775.8  356.14
#Mann= 14 ,-1 , 0
  3512.4     .16       0  4021.5     .12       0  4205.6     .05       0
  4268.4     .12       0  4683.7     .05       0  4882.7     .12       0
  5253.3     .07       0  5259.3     .12       0  5378.3     .16       0
  5415.6     .12       0  5753.5     .16       0    6004     .05       0
  6512.7     .12       0  6991.8     .05       0
Bank Sta=3784.5,5605.1
XS Rating Curve= 0 ,0
Exp/Cntr=0.3,0.1

Type RM Length L Ch R = 1 ,77876   ,726,726,726
BEGIN DESCRIPTION:
BOX CREEK 103.0
END DESCRIPTION:
XS GIS Cut Line= 2
      3773723.16     10570864.28      3771167.63     10574010.08
#Sta/Elev= 30
  3023.9  353.81  3194.3  346.92  3200.8  343.08  3272.6  333.47  3279.1  329.17
  3485.2  303.29    3621  296.31  3777.3  295.02  3940.6  293.44  4274.7  304.61
  4480.8  286.45  4977.9  287.98  4997.2  282.96  4999.9  282.46  5003.2  282.96
  5017.6  285.16  5028.5  288.76  5586.3  285.33  5912.2  283.54  6049.4  283.54
  6154.3  284.22  6257.2     289  6464.1  298.42  6478.5  296.48  6569.3  304.89
  6691.1  318.46  6784.7  334.76  6847.7  347.61  6969.1  343.63  7076.9  352.34
#Mann= 12 ,-1 , 0
  3023.9     .16       0  3777.3     .12       0  4997.2     .07       0
  5003.2     .12       0  5017.6     .05       0  5586.3     .12       0
  5912.2     .05       0  6049.4     .07       0  6154.3     .12       0
  6257.2     .05       0  6569.3     .12       0  6784.7     .16       0
Bank Sta=4977.9,5028.5
XS Rating Curve= 0 ,0
Exp/Cntr=0.3,0.1

Type RM Length L Ch R = 1 ,77150   ,677,677,677
BEGIN DESCRIPTION:
BOX CREEK 102.0
END DESCRIPTION:
XS GIS Cut Line= 3
      3772799.61     10571210.18      3772299.61     10572010.19
       3771149.6     10573110.19
#Sta/Elev= 30
  4118.4  312.74    4257  304.49    4415  291.34  4509.3  290.67  4670.9  286.03
    4823  286.33  4837.8  284.39  4967.5   287.6  4975.1  281.48    4981  286.26
  4990.5  282.22  4996.4  285.54  4999.8  281.43  5002.6  280.93  5005.8  281.43
  5026.4  282.67  5032.9  286.62  5374.1  286.64  5668.5   284.8  5931.9  283.88
  6091.5  293.39  6166.3   293.3  6186.3  292.74    6236  297.83  6299.5  300.61
  6459.3  319.38  6518.7  326.56  6532.9  330.36  6603.7  341.29  6653.2  343.31
#Mann= 8 ,-1 , 0
  4118.4     .12       0  4999.8     .07       0  5005.8     .12       0
  5374.1     .16       0  5668.5     .12       0  6091.5     .05       0
  6166.3     .16       0  6459.3     .12       0
Bank Sta=4967.5,5032.9
XS Rating Curve= 0 ,0
Exp/Cntr=0.3,0.1

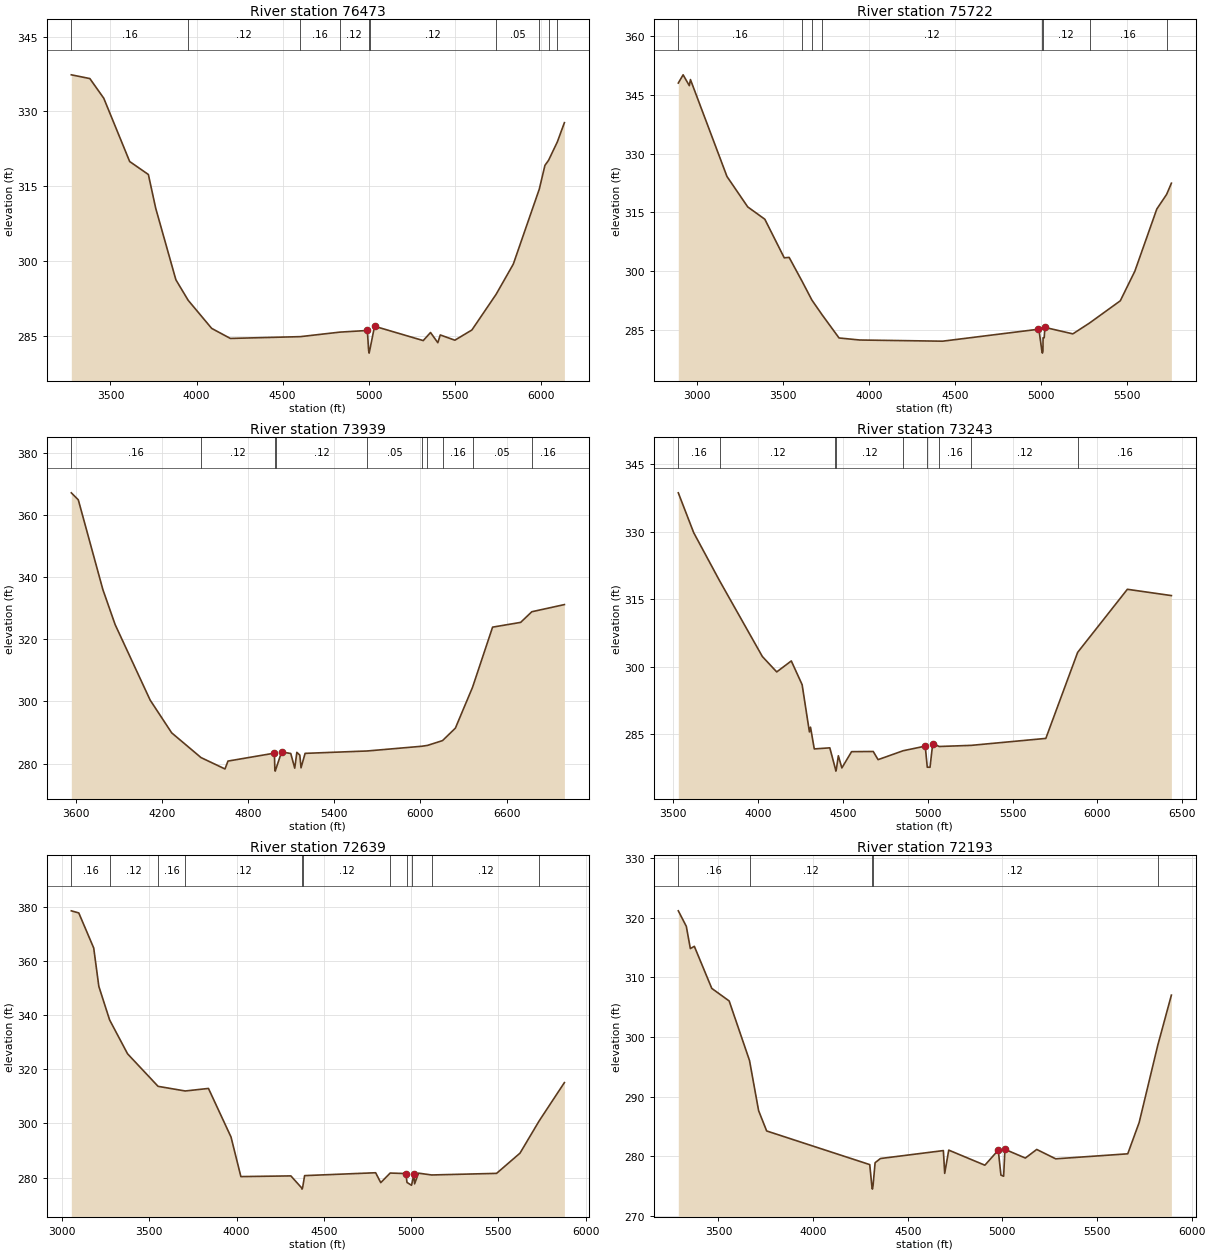
Type RM Length L Ch R = 1 ,76473   ,751,751,751
BEGIN DESCRIPTION:
BOX CREEK 101.0
END DESCRIPTION:
XS GIS Cut Line= 3
      3772799.63     10570510.16      3771849.61     10571960.19
      3771049.61     10572760.19
#Sta/Elev= 30
  3272.6  337.36  3380.2  336.61  3461.1  332.66  3611.8  319.94  3720.3  317.34
  3762.8  310.58  3880.1   296.2  3951.6  292.07  4088.1  286.43  4196.6  284.41
  4603.2  284.77  4833.3  285.68  4992.6  286.01  5000.1  281.96  5002.9  281.46
  5006.1  281.96  5034.4  286.86  5317.3  283.98  5359.7   285.6  5402.1  283.55
  5416.2  285.11  5501.1  284.06  5600.1  286.11  5740.9  293.28  5840.5  299.33
  5991.6   314.4  6024.4  319.17  6045.6   320.2  6096.4  323.88  6137.5  327.75
#Mann= 10 ,-1 , 0
  3272.6     .16       0  3951.6     .12       0  4603.2     .16       0
  4833.3     .12       0  5000.1     .07       0  5006.1     .12       0
  5740.9     .05       0  5991.6     .16       0  6045.6     .05       0
  6096.4     .16       0
Bank Sta=4992.6,5034.4
XS Rating Curve= 0 ,0
Exp/Cntr=0.3,0.1

Type RM Length L Ch R = 1 ,75722   ,1783,1783,1783
BEGIN DESCRIPTION:
BOX CREEK 100.0
END DESCRIPTION:
XS GIS Cut Line= 3
      3772799.63     10570310.17      3771399.61     10571910.19
      3770849.58     10572410.22
#Sta/Elev= 30
  2890.3  348.01  2918.3  350.11  2954.4  347.35    2961   348.9  3173.6  324.14
  3294.2  316.38  3393.8  313.23  3506.8  303.37  3535.3  303.48  3611.5  297.31
  3667.6  292.59  3727.2  288.82  3825.7   282.9  3946.2  282.38  4428.4  282.08
  4980.8   285.1  4988.4  285.23  5006.2  279.53    5009  279.03  5012.2  279.53
    5013  282.95  5019.7  282.95  5023.5   285.6  5186.3  283.95  5283.2  286.71
  5462.3  292.39  5547.1  299.96  5674.9  315.84    5732  319.57  5759.7  322.43
#Mann= 8 ,-1 , 0
  2890.3     .16       0  3611.5     .12       0  3667.6     .16       0
  3727.2     .12       0  5006.2     .07       0  5012.2     .12       0
  5283.2     .16       0    5732      .1       0
Bank Sta=4980.8,5023.5
XS Rating Curve= 0 ,0
Exp/Cntr=0.3,0.1

Type RM Length L Ch R = 1 ,73939   ,696,696,696
BEGIN DESCRIPTION:
BOX CREEK 99.0
END DESCRIPTION:
XS GIS Cut Line= 3
      3772243.97     10569836.53      3771153.72     10571294.82
      3770528.71     10572780.96
#Sta/Elev= 30
    3569  367.08  3617.7  364.82  3788.6  335.99    3874  324.73  4117.9  300.45
  4267.9  289.91  4472.1  281.96  4638.9  278.31  4659.8  280.84  4982.9  283.39
  4986.1  278.11  4988.8  277.61  4992.1  278.11  5032.9  283.77  5096.8  283.28
  5124.6  278.56  5139.2  283.64    5160  282.76  5168.3  278.68  5196.7  283.32
  5629.8  284.09  6007.9   285.6  6048.7  285.88  6153.4  287.42    6243  291.43
  6362.9  304.62  6502.1   323.9  6697.4  325.43  6775.1  328.85    7002  331.15
#Mann= 10 ,-1 , 0
    3569     .16       0  4472.1     .12       0  4986.1     .07       0
  4992.1     .12       0  5629.8     .05       0  6007.9     .16       0
  6048.7     .12       0  6153.4     .16       0  6362.9     .05       0
  6775.1     .16       0
Bank Sta=4982.9,5032.9
XS Rating Curve= 0 ,0
Exp/Cntr=0.3,0.1

Type RM Length L Ch R = 1 ,73243   ,604,604,604
BEGIN DESCRIPTION:
BOX CREEK 98.0
END DESCRIPTION:
XS GIS Cut Line= 4
      3771973.18      10569746.2      3771021.78     10570544.82
      3770625.94     10571253.16      3769883.76     10571669.34
#Sta/Elev= 30
  3531.3  338.65  3621.9  329.79  3774.3   319.1  4026.5  302.23  4111.1  298.81
  4196.9  301.25  4260.7  295.97  4303.6  285.46  4310.1  286.52  4332.2  281.68
  4423.8  281.92  4456.7  277.24  4459.4  276.74  4462.7  277.24    4474  280.16
  4494.8  277.45    4552  281.07  4679.5  281.11  4708.1  279.29  4855.2  281.27
  4985.8   282.3  4997.9  277.61    5014   277.6    5030  282.88  5068.3  282.22
  5256.2  282.47  5696.2  284.02  5883.7  303.16  6176.5  317.19  6435.8  315.79
#Mann= 9 ,-1 , 0
  3531.3     .16       0  3774.3     .12       0  4456.7     .07       0
  4462.7     .12       0  4855.2     .16       0  4997.9     .12       0
  5068.3     .16       0  5256.2     .12       0  5883.7     .16       0
Bank Sta=4985.8,5030
XS Rating Curve= 0 ,0
Exp/Cntr=0.3,0.1

Type RM Length L Ch R = 1 ,72639   ,446,446,446
BEGIN DESCRIPTION:
BOX CREEK 97.0
END DESCRIPTION:
XS GIS Cut Line= 3
      3772049.62     10569510.18      3770499.61     10570660.19
      3770099.59     10571460.22
#Sta/Elev= 30
  3053.4  378.41  3096.2  377.63  3181.7   364.7    3211  350.56  3272.9  338.16
  3375.8  325.67  3550.4  313.69    3706  311.98    3839  312.92  3968.3  294.99
  4024.7  280.41    4311  280.67  4372.2  276.29  4374.9  275.79  4378.2  276.29
  4389.8  280.77  4796.7  281.83  4825.9  278.18  4879.9  281.72  4969.9  281.53
  4976.2  278.26  5002.3   277.2 5016.48  281.48  5019.8  277.73  5042.1  281.68
  5117.6  281.01  5489.4   281.6  5623.5  289.05  5733.2  300.93  5877.9  315.07
#Mann= 11 ,-1 , 0
  3053.4     .16       0  3272.9     .12       0  3550.4     .16       0
    3706     .12       0  4372.2     .07       0  4378.2     .12       0
  4879.9     .16       0  4976.2     .12       0  5002.3     .16       0
  5117.6     .12       0  5733.2     .16       0
Bank Sta=4969.9,5016.48
XS Rating Curve= 0 ,0
Exp/Cntr=0.3,0.1

Type RM Length L Ch R = 1 ,72193   ,733,733,733
BEGIN DESCRIPTION:
BOX CREEK 96.0
END DESCRIPTION:
XS GIS Cut Line= 3
      3771299.58     10569260.22      3770049.61     10570560.19
      3770099.61      10571360.2
#Sta/Elev= 30
  3287.9  321.13  3330.2  318.53  3351.5   314.8  3372.6  315.18  3464.7  308.13
  3556.6  306.02  3664.1  296.04  3712.2  287.63  3754.7  284.23  4299.3  278.59
  4310.5  274.98  4313.2  274.48  4316.5  274.98  4327.6  278.91  4355.9  279.61
  4688.3  280.94  4695.3  277.12  4716.6  281.02  4907.5  278.49  4978.3  281.01
  4992.4  276.83  5006.6  276.64  5013.5  281.15  5121.4  279.69  5181.5  281.13
  5281.7  279.56  5662.4   280.4  5722.6  285.64  5820.7  298.56  5892.9     307
#Mann= 5 ,-1 , 0
  3287.9     .16       0  3664.1     .12       0  4310.5     .07       0
  4316.5     .12       0  5820.7     .16       0
Bank Sta=4978.3,5013.5
XS Rating Curve= 0 ,0
Exp/Cntr=0.3,0.1

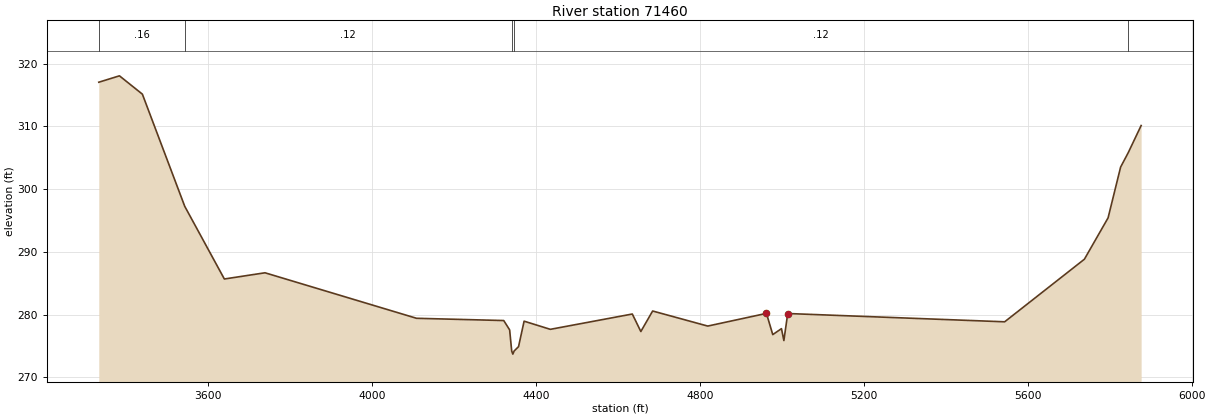
Type RM Length L Ch R = 1 ,71460   ,895,895,895
BEGIN DESCRIPTION:
BOX CREEK 95.0
END DESCRIPTION:
XS GIS Cut Line= 3
      3771149.57     10569310.22      3769899.61     10570310.19
      3769099.64     10570810.17
#Sta/Elev= 30
  3332.6  317.02    3383  318.04    3439  315.12  3542.4  297.25  3639.1  285.67
  3738.3  286.66  4108.1  279.41    4321  279.05  4335.4  277.56  4340.4   274.2
  4343.2   273.7  4346.4   274.2  4357.1  274.89  4370.7  278.95  4434.7  277.65
  4634.8  280.09  4655.6   277.3  4684.4  280.57  4818.9  278.17  4962.2  280.19
  4977.6  276.81  4998.8  277.76  5004.7  275.86  5014.1  280.17  5543.6  278.85
  5738.2  288.82    5796  295.41  5826.6   303.5  5845.3  305.81  5876.7  310.12
#Mann= 5 ,-1 , 0
  3332.6     .16       0  3542.4     .12       0  4340.4     .07       0
  4346.4     .12       0  5845.3     .16       0
Bank Sta=4962.2,5014.1
XS Rating Curve= 0 ,0
Exp/Cntr=0.3,0.1