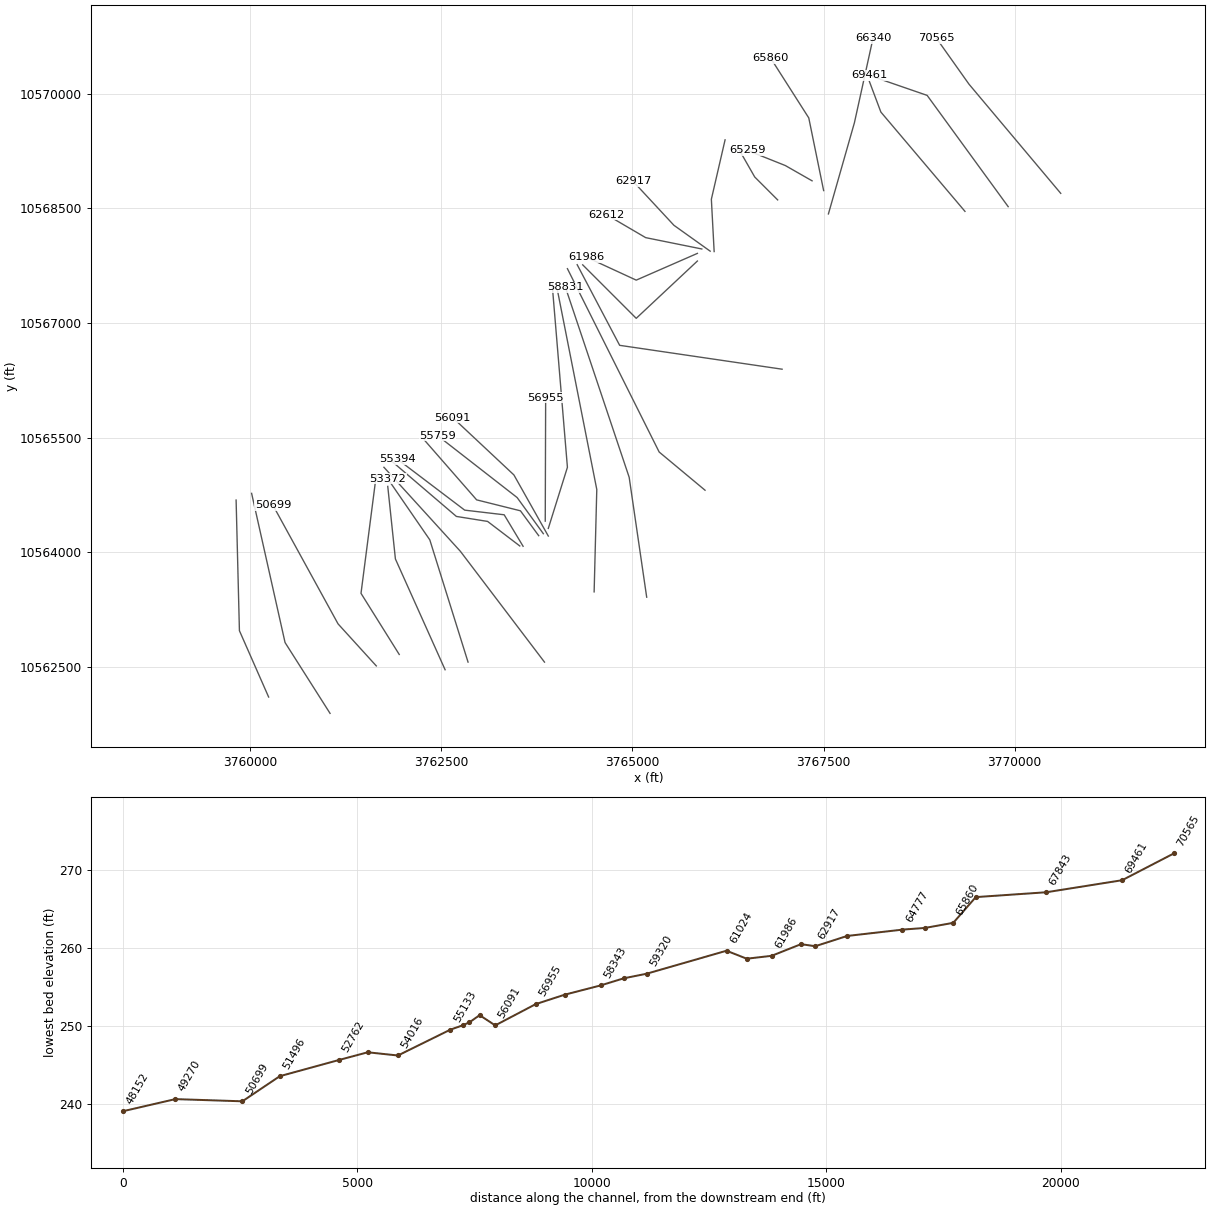
HEC-RAS study BOX CREEK.prj: BOX CREEK Base Level Engineering

--- BOX CREEK.g01 (geometry) --- (continued)

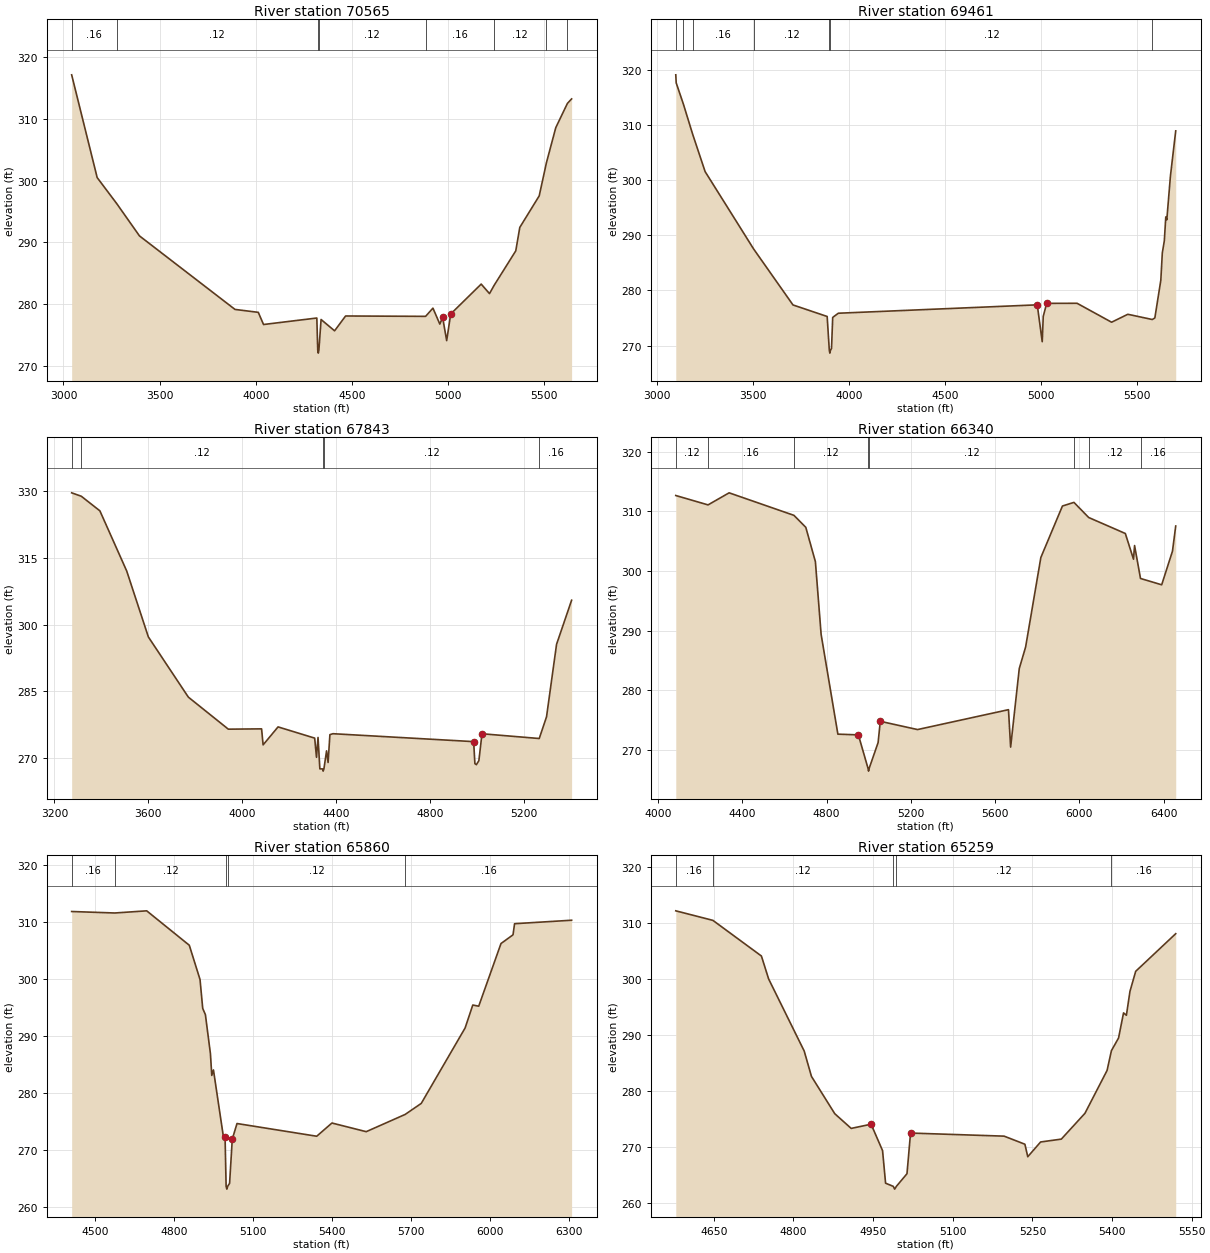
Type RM Length L Ch R = 1 ,70565   ,1104,1104,1104
BEGIN DESCRIPTION:
BOX CREEK 94.0
END DESCRIPTION:
XS GIS Cut Line= 3
      3770602.12     10568696.22      3769401.98     10570125.44
      3768978.02     10570723.78
#Sta/Elev= 30
  3042.7   317.1  3175.4  300.47  3276.2   296.3  3395.2  291.04  3892.1  279.14
  4013.1  278.67  4040.4   276.7  4317.5  277.75  4322.3  272.57    4325  272.07
  4328.3  272.57  4339.6  277.51  4409.9  275.68  4467.1  278.08  4883.1  278.02
  4921.3  279.35    4957  276.77  4971.8  277.84  4992.7  274.09  5013.6   278.4
  5172.2  283.24  5215.4   281.7  5239.5  283.04    5352  288.62  5372.9  292.41
  5473.8  297.51  5511.6   302.9    5560  308.55  5620.4  312.47  5642.3   313.2
#Mann= 8 ,-1 , 0
  3042.7     .16       0  3276.2     .12       0  4322.3     .07       0
  4328.3     .12       0  4883.1     .16       0  5239.5     .12       0
  5511.6     .16       0  5620.4     .05       0
Bank Sta=4971.8,5013.6
XS Rating Curve= 0 ,0
Exp/Cntr=0.3,0.1

Type RM Length L Ch R = 1 ,69461   ,1618,1618,1618
BEGIN DESCRIPTION:
BOX CREEK 93.0
END DESCRIPTION:
XS GIS Cut Line= 3
      3769914.84     10568521.88      3768854.92     10569978.42
       3768093.5     10570241.33
#Sta/Elev= 30
  3096.4  319.07  3098.6  317.61  3136.1  313.76  3184.1  308.34  3249.3  301.54
  3502.6   287.5  3707.6  277.37  3885.8  275.28    3897  269.14  3899.7  268.64
    3903  269.14  3908.5   269.5  3914.7  275.11    3944  275.87  4981.3  277.39
  5007.2  270.71  5012.5  275.29  5030.3  277.66    5189  277.67  5368.9  274.24
  5453.5  275.68  5581.3  274.73  5594.5  275.02  5625.6  281.85  5633.4  286.79
  5643.9     289  5651.5  293.32  5656.8   292.8  5675.7  300.72  5703.3  308.91
#Mann= 7 ,-1 , 0
  3096.4     .16       0  3136.1     .12       0  3184.1     .16       0
  3502.6     .12       0    3897     .07       0    3903     .12       0
  5581.3     .16       0
Bank Sta=4981.3,5030.3
XS Rating Curve= 0 ,0
Exp/Cntr=0.3,0.1

Type RM Length L Ch R = 1 ,67843   ,1503,1503,1503
BEGIN DESCRIPTION:
BOX CREEK 92.0
END DESCRIPTION:
XS GIS Cut Line= 3
       3769349.6      10568460.2      3768249.61     10569760.19
      3768099.62     10570160.16
#Sta/Elev= 30
  3273.3  329.65  3314.4  328.88  3393.6   325.6  3507.9  312.07  3600.2  297.25
  3770.5  283.73  3940.8  276.53  4082.5   276.6    4089     273  4152.7  277.04
  4308.7  274.52  4316.5   270.2    4323  274.67  4330.8  267.61  4342.1   267.6
  4344.8   267.1  4348.1   267.6  4359.4  271.66  4365.9  269.04  4373.6   275.3
  4386.7  275.51    4986  273.73  4991.4  268.78  4997.6  268.55  5008.3  269.45
  5021.6   275.5  5265.5  274.43  5296.6  279.31  5339.3   295.6  5403.4  305.51
#Mann= 5 ,-1 , 0
  3273.3     .16       0  3314.4     .12       0  4342.1     .07       0
  4348.1     .12       0  5265.5     .16       0
Bank Sta=4986,5021.6
XS Rating Curve= 0 ,0
Exp/Cntr=0.3,0.1

Type RM Length L Ch R = 1 ,66340   ,480,480,480
BEGIN DESCRIPTION:
BOX CREEK 91.0
END DESCRIPTION:
XS GIS Cut Line= 3
      3767563.46     10568426.81      3767903.72     10569621.21
      3768146.75     10570725.26
#Sta/Elev= 30
  4084.3  312.63  4237.4  311.06  4337.4  313.08    4645  309.31  4701.3   307.3
  4746.8  301.56  4774.1  289.35  4853.5  272.67  4950.8  272.55  4996.3  266.98
  4999.1  266.48  5002.3  266.98  5044.4  271.26  5054.8  274.82  5231.6  273.44
  5663.1  276.77  5673.3   270.5  5714.3  283.66  5744.4  287.26  5816.7  302.25
  5919.1  310.87  5973.7  311.48  6043.6  308.95  6217.6  306.27  6256.3  301.97
  6261.4  304.25  6289.6  298.74  6390.1  297.68  6441.3  303.31  6456.7  307.52
#Mann= 8 ,-1 , 0
  4084.3     .12       0  4237.4     .16       0    4645     .12       0
  4996.3     .07       0  5002.3     .12       0  5973.7     .16       0
  6043.6     .12       0  6289.6     .16       0
Bank Sta=4950.8,5054.8
XS Rating Curve= 0 ,0
Exp/Cntr=0.3,0.1

Type RM Length L Ch R = 1 ,65860   ,601,601,601
BEGIN DESCRIPTION:
BOX CREEK 90.0
END DESCRIPTION:
XS GIS Cut Line= 3
      3767500.95     10568732.28       3767306.5     10569683.71
      3766807.51     10570466.85
#Sta/Elev= 30
  4411.3   311.9  4575.2  311.64  4696.4  312.02  4858.3  305.98  4899.1  299.96
  4909.3   294.9  4919.5   293.8  4938.6  286.95  4943.7  283.14  4950.1   284.1
  4989.1  272.01  4994.2  272.38  4998.2  263.69  5000.9  263.19  5004.2  263.69
  5011.4  264.21  5021.6  271.95  5039.6   274.7  5342.5  272.47  5400.3  274.79
  5530.6  273.27  5678.7   276.3  5739.7  278.23  5906.4  291.47  5935.5  295.49
  5958.1  295.29  6042.7  306.28  6088.4  307.81  6094.3  309.76    6311  310.37
#Mann= 5 ,-1 , 0
  4411.3     .16       0  4575.2     .12       0  4998.2     .07       0
  5004.2     .12       0  5678.7     .16       0
Bank Sta=4994.2,5021.6
XS Rating Curve= 0 ,0
Exp/Cntr=0.3,0.1

Type RM Length L Ch R = 1 ,65259   ,482,482,482
BEGIN DESCRIPTION:
BOX CREEK 89.0
END DESCRIPTION:
XS GIS Cut Line= 3
      3767349.63     10568860.18      3766999.61     10569060.19
      3766499.57      10569260.2
#Sta/Elev= 30
  4578.3  312.18  4648.2  310.48  4739.6  304.12  4753.2  300.03  4820.2  287.17
  4833.9  282.64  4877.8  275.99  4908.7  273.37  4946.2  274.12  4967.8  269.41
  4973.5   263.6  4987.9  263.04  4990.6  262.54  4993.9  263.04  5013.8  265.29
  5020.5  272.54  5196.8  271.99  5235.9  270.55  5241.3  268.32  5265.5  270.95
  5304.5  271.46    5349  276.06  5390.7  283.71  5398.9  287.24  5412.3  289.49
  5421.7  293.97  5427.1  293.55  5433.8  297.81  5444.6  301.39    5520   308.1
#Mann= 5 ,-1 , 0
  4578.3     .16       0  4648.2     .12       0  4987.9     .07       0
  4993.9     .12       0  5398.9     .16       0
Bank Sta=4946.2,5020.5
XS Rating Curve= 0 ,0
Exp/Cntr=0.3,0.1

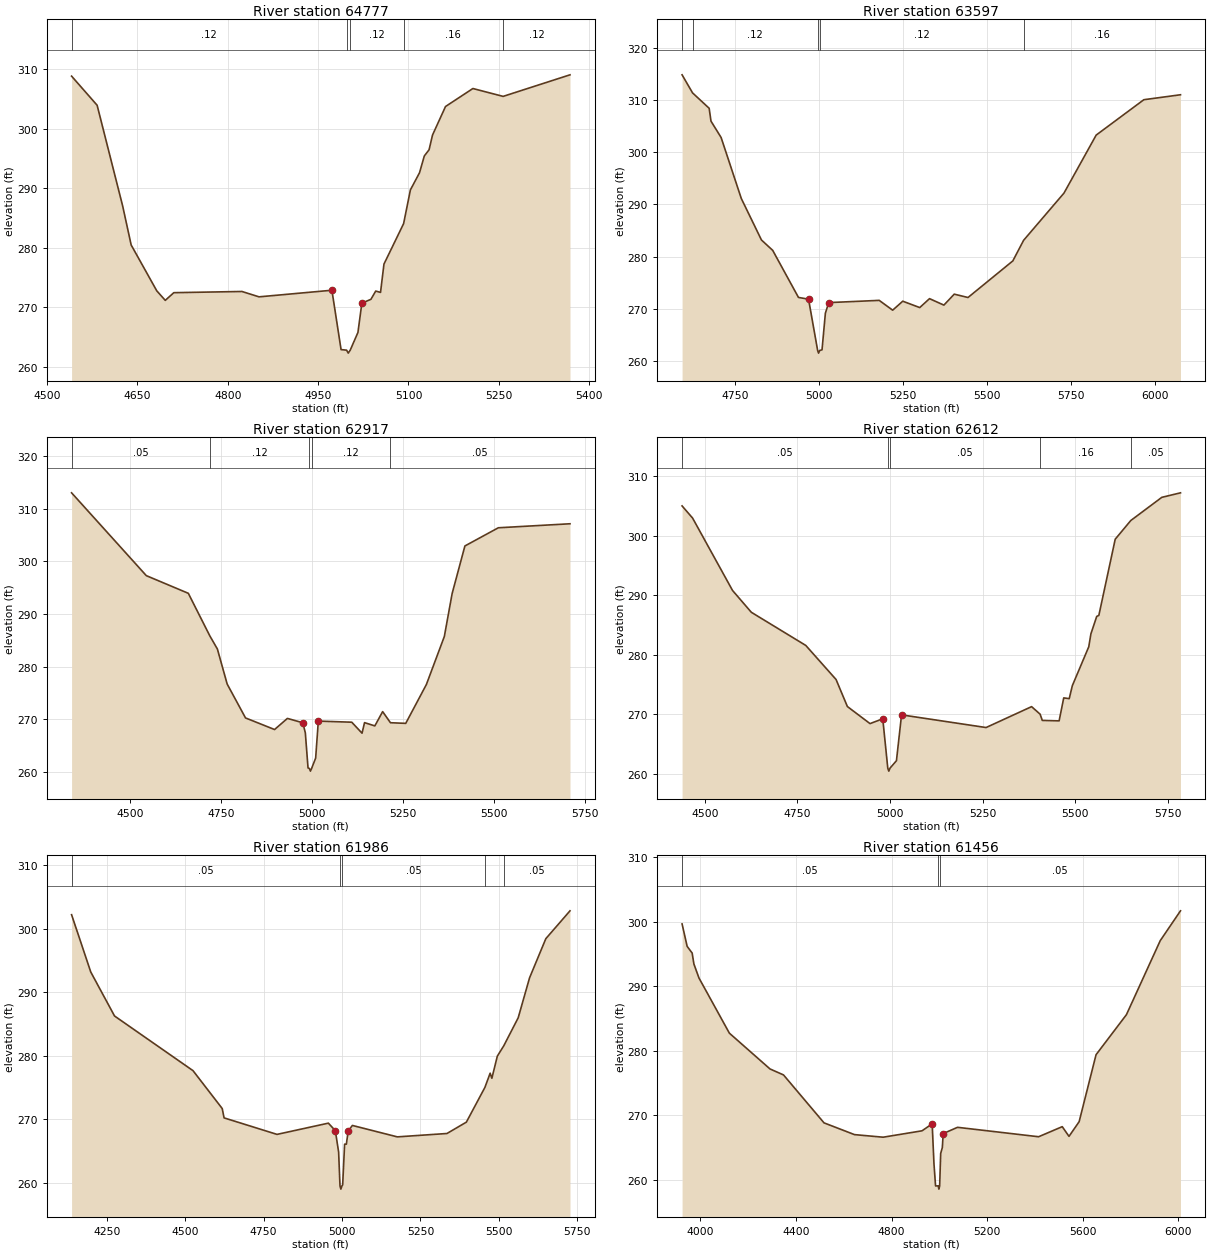
Type RM Length L Ch R = 1 ,64777   ,1180,1180,1180
BEGIN DESCRIPTION:
BOX CREEK 88.0
END DESCRIPTION:
XS GIS Cut Line= 3
      3766899.58     10568610.22      3766599.61     10568910.19
      3766399.63     10569260.16
#Sta/Elev= 30
  4540.8  308.83  4583.2  303.94  4625.6  287.02  4639.7  280.48  4682.2  272.78
  4696.3  271.18  4710.5  272.47  4823.6  272.67  4851.9  271.77  4972.9  272.88
  4988.1  262.91  4997.3  262.82    5000  262.32  5003.3  262.82  5016.1  265.79
  5022.6   270.7  5037.7  271.36  5045.6  272.74  5053.6  272.52  5059.3  277.27
  5091.9  284.06  5103.2  289.73  5118.3   292.6  5126.3  295.43  5134.2  296.47
  5139.9  298.94  5161.5  303.73  5206.9  306.75  5257.1  305.43  5368.1  309.05
#Mann= 5 ,-1 , 0
  4540.8     .12       0  4997.3     .07       0  5003.3     .12       0
  5091.9     .16       0  5257.1     .12       0
Bank Sta=4972.9,5022.6
XS Rating Curve= 0 ,0
Exp/Cntr=0.3,0.1

Type RM Length L Ch R = 1 ,63597   ,680,680,680
BEGIN DESCRIPTION:
BOX CREEK 87.0
END DESCRIPTION:
XS GIS Cut Line= 3
      3766068.87     10567934.18      3766032.41     10568619.04
      3766211.82     10569396.47
#Sta/Elev= 30
  4592.6  314.84  4623.9  311.37  4673.2  308.43  4678.7  305.96  4708.8  302.83
  4768.9  291.14  4828.9  283.19  4862.4   281.2  4939.1  272.18  4969.1  271.85
  4996.2  262.01  4998.9  261.51  5002.2  262.01  5009.2  262.15  5019.2  269.17
  5029.2  271.19  5179.4  271.62  5219.5  269.74  5249.5  271.46  5300.1  270.24
  5329.2  271.95    5372  270.71  5402.8  272.81  5443.8  272.17  5577.2  279.18
  5609.3  283.13  5729.5  292.18  5825.3  303.29  5967.2  310.07  6076.3  311.02
#Mann= 5 ,-1 , 0
  4592.6     .05       0  4623.9     .12       0  4996.2     .07       0
  5002.2     .12       0  5609.3     .16       0
Bank Sta=4969.1,5029.2
XS Rating Curve= 0 ,0
Exp/Cntr=0.3,0.1

Type RM Length L Ch R = 1 ,62917   ,305,305,305
BEGIN DESCRIPTION:
BOX CREEK 86.0
END DESCRIPTION:
XS GIS Cut Line= 3
      3766016.83     10567939.33      3765542.83      10568277.9
      3765006.76      10568855.6
#Sta/Elev= 30
  4338.2  312.99  4543.7  297.28  4659.2  293.93  4718.4  285.85  4739.1  283.37
  4766.1  276.71  4816.5  270.29  4896.4  268.09  4931.7   270.2  4974.2  269.37
    4981  267.45  4988.4  260.81  4992.2   260.7    4995   260.2  4998.2   260.7
  5009.4  262.68  5016.7  269.69  5108.6  269.48  5136.9   267.4  5143.8   269.4
  5172.1  268.78  5193.6  271.49  5215.1  269.38  5257.1  269.26  5313.8  276.62
  5363.2  285.73  5384.7  293.89  5419.8  302.91  5511.7  306.36  5708.8  307.12
#Mann= 5 ,-1 , 0
  4338.2     .05       0  4718.4     .12       0  4992.2     .07       0
  4998.2     .12       0  5215.1     .05       0
Bank Sta=4974.2,5016.7
XS Rating Curve= 0 ,0
Exp/Cntr=0.3,0.1

Type RM Length L Ch R = 1 ,62612   ,626,626,626
BEGIN DESCRIPTION:
BOX CREEK 85.0
END DESCRIPTION:
XS GIS Cut Line= 3
      3765907.45     10567967.99      3765173.04     10568116.44
      3764657.38     10568418.54
#Sta/Elev= 30
  4438.1     305  4466.5  302.96  4574.5   290.8  4625.2  287.14  4772.4  281.57
  4854.2  275.85  4884.8  271.31    4946  268.44  4980.4  269.25    4994  260.96
  4996.8  260.46    5000  260.96  5017.4  262.21  5031.2  269.91  5259.6  267.78
  5382.6  271.29  5405.7  270.02  5411.5  268.98    5457   268.9  5469.5  272.76
  5484.3  272.63  5492.7  274.81  5537.1  281.34  5542.9  283.51  5558.6  286.44
  5564.4  286.62  5608.6  299.41  5650.7  302.55  5734.5  306.44    5785   307.2
#Mann= 5 ,-1 , 0
  4438.1     .05       0    4994     .03       0    5000     .05       0
  5405.7     .16       0  5650.7     .05       0
Bank Sta=4980.4,5031.2
XS Rating Curve= 0 ,0
Exp/Cntr=0.3,0.1

Type RM Length L Ch R = 1 ,61986   ,530,530,530
BEGIN DESCRIPTION:
BOX CREEK 84.0
END DESCRIPTION:
XS GIS Cut Line= 3
      3765849.65     10567910.21      3765049.61     10567560.19
      3764399.65     10567860.17
#Sta/Elev= 30
  4137.7  302.19  4198.9  293.16  4274.6  286.24  4524.8  277.63    4618  271.66
  4623.9  270.19  4792.7  267.59  4956.4  269.36  4978.6  268.18  4989.1  264.81
  4993.5  259.47  4996.3  258.97  4999.5  259.47    5002  259.63  5008.2  266.05
  5013.7  266.05  5019.7  268.13    5033     269  5176.2   267.2  5334.5  267.73
  5396.4  269.52  5455.6     275  5472.2  277.23  5477.7  276.43  5495.1  279.91
  5515.5  281.53  5561.6  285.95  5597.9  292.25  5649.7  298.41  5726.8   302.8
#Mann= 5 ,-1 , 0
  4137.7     .05       0  4993.5     .03       0  4999.5     .05       0
  5455.6     .16       0  5515.5     .05       0
Bank Sta=4978.6,5019.7
XS Rating Curve= 0 ,0
Exp/Cntr=0.3,0.1

Type RM Length L Ch R = 1 ,61456   ,432,432,432
BEGIN DESCRIPTION:
BOX CREEK 83.0
END DESCRIPTION:
XS GIS Cut Line= 3
      3765849.59     10567810.17      3765049.61     10567060.19
      3764349.61     10567760.19
#Sta/Elev= 30
    3923  299.66  3944.2  296.19  3965.2  295.15  3972.5  293.46  3993.6   291.3
    4121  282.75    4291  277.21  4347.7  276.28  4517.2  268.86  4644.7  267.04
  4764.8  266.64  4927.5  267.63    4970  268.71  4977.3  262.65  4984.1   259.1
  4995.3   259.1  4998.1   258.6  5001.3   259.1  5005.6  264.12  5012.5  265.04
  5016.1   267.2  5076.1  268.17  5415.5  266.71  5514.5  268.27  5542.8  266.77
  5585.2  269.04    5656  279.41  5783.2  285.61  5924.7  297.07  6009.5  301.69
#Mann= 3 ,-1 , 0
    3923     .05       0  4995.3     .03       0  5001.3     .05       0
Bank Sta=4970,5016.1
XS Rating Curve= 0 ,0
Exp/Cntr=0.3,0.1

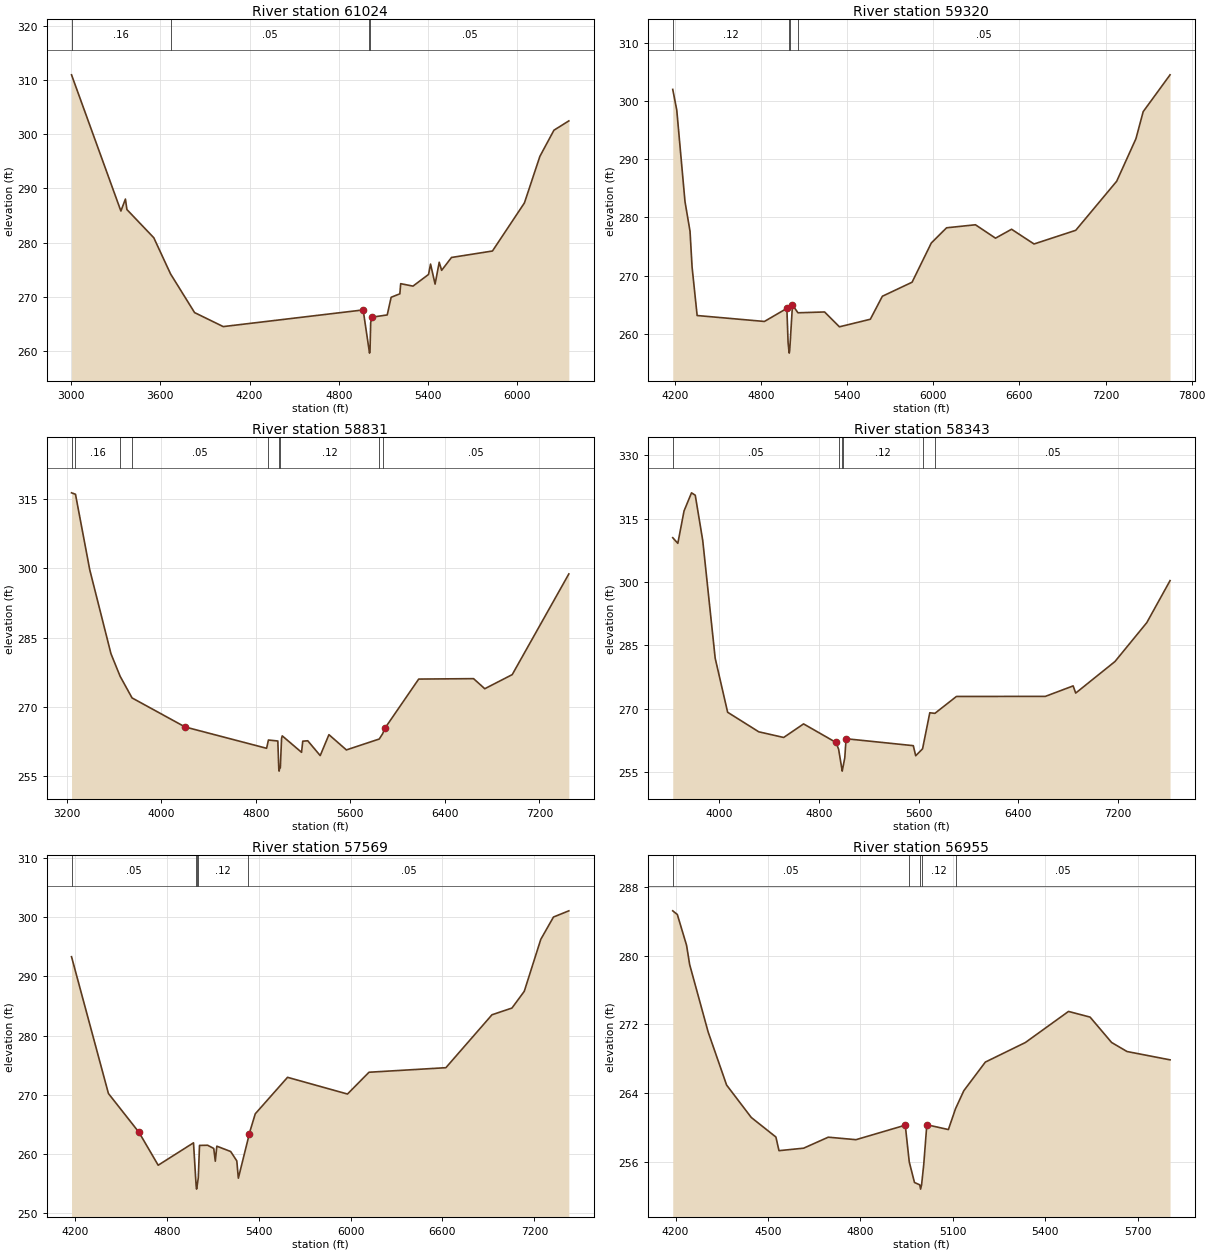
Type RM Length L Ch R = 1 ,61024   ,1704,1704,1704
BEGIN DESCRIPTION:
Mapping XS db0fdc5d
END DESCRIPTION:
XS GIS Cut Line= 3
      3766957.72     10566394.22      3764832.76     10566706.72
      3764277.22     10567762.23
#Sta/Elev= 30
  3004.3  310.91  3335.9  285.81  3366.3  288.01  3376.4  286.08    3557  280.88
  3669.3  274.23  3830.9  267.09  4023.3  264.51  4963.3  267.58  5003.4  260.12
  5006.2  259.62  5009.4  260.12  5013.8  265.25  5023.9  266.25    5125  266.66
  5151.2  269.91  5209.7  270.55  5215.4  272.42  5297.9  271.97  5402.4  274.12
    5416  276.03  5446.5  272.34  5474.2  276.37  5490.5  274.88  5556.7  277.25
  5831.8  278.44  6046.5   287.3  6150.5  295.89  6244.8   300.7  6344.9  302.42
#Mann= 4 ,-1 , 0
  3004.3     .16       0  3669.3     .05       0  5003.4     .03       0
  5009.4     .05       0
Bank Sta=4963.3,5023.9
XS Rating Curve= 0 ,0
Exp/Cntr=0.3,0.1

Type RM Length L Ch R = 1 ,59320   ,489,489,489
BEGIN DESCRIPTION:
BOX CREEK 82.0
END DESCRIPTION:
XS GIS Cut Line= 3
       3765949.6      10564810.2      3765349.61     10565310.19
       3764149.6      10567710.2
#Sta/Elev= 30
  4185.2  301.98  4213.2  298.43  4270.4  282.73  4305.6   277.6  4319.9  271.46
  4355.1  263.14  4823.7  262.12  4980.2  264.37  4988.6  258.51    4994  257.18
  4996.7  256.68    5000  257.18  5019.3  264.97  5057.1  263.61  5242.9  263.75
  5346.3   261.2  5561.6   262.5  5645.4  266.45  5852.3  268.86  5986.4   275.6
  6092.6  278.21  6293.9  278.73  6433.6  276.43  6545.4  277.96    6702  275.43
  6992.6  277.78  7277.7  286.21  7411.9  293.52  7462.2  298.16  7649.5  304.49
#Mann= 4 ,-1 , 0
  4185.2     .12       0    4994     .07       0    5000     .12       0
  5057.1     .05       0
Bank Sta=4980.2,5019.3
XS Rating Curve= 0 ,0
Exp/Cntr=0.3,0.1

Type RM Length L Ch R = 1 ,58831   ,488,488,488
BEGIN DESCRIPTION:
BOX CREEK 81.0
END DESCRIPTION:
XS GIS Cut Line= 3
      3765186.47     10563409.92      3764957.29      10564979.4
      3764124.34     10567464.39
#Sta/Elev= 30
  3241.3  316.31  3274.8     316  3395.4  299.66  3575.1  281.48  3652.3  276.62
  3753.3  271.93  4201.6  265.65  4891.5  261.03    4907  262.82  4986.5  262.61
  4994.7  256.59  4997.5  256.09  5000.7  256.59  5007.6  256.79  5018.1  263.18
    5024  263.72  5187.1  260.16  5197.4  262.57  5239.6  262.66  5345.1  259.45
  5418.9  263.98  5566.5  260.68  5844.6  263.04  5872.8  264.17  5893.5  265.41
  6178.3  276.01  6642.3   276.1  6737.2  273.92  6969.3  276.97  7448.3  298.76
#Mann= 9 ,-1 , 0
  3241.3     .05       0  3274.8     .16       0  3652.3     .12       0
  3753.3     .05       0    4907     .12       0  4994.7     .07       0
  5000.7     .12       0  5844.6     .16       0  5872.8     .05       0
Bank Sta=4201.6,5893.5
XS Rating Curve= 0 ,0
Exp/Cntr=0.3,0.1

Type RM Length L Ch R = 1 ,58343   ,774,774,774
BEGIN DESCRIPTION:
BOX CREEK 80.0
END DESCRIPTION:
XS GIS Cut Line= 3
      3764498.96      10563479.4      3764533.68     10564819.68
       3764019.8     10567423.83
#Sta/Elev= 30
  3625.1  310.46  3665.9  309.13  3715.9  316.81  3775.9  321.09  3805.9  320.52
    3866  309.81    3966  281.93    4066  269.13  4316.1   264.5  4516.2  263.16
  4676.2  266.37  4936.3  261.98  4957.8  260.36  4983.7  255.69  4986.5  255.19
  4989.7  255.69  5007.1  258.34  5017.6  262.86  5557.5  261.22  5576.8  258.83
  5631.9  260.47    5690  269.01  5731.1  268.87  5904.1  272.87  6618.3  272.89
  6841.8  275.37  6862.2  273.67  7177.6  281.14    7433  290.34  7620.2   300.3
#Mann= 6 ,-1 , 0
  3625.1     .05       0  4957.8     .12       0  4983.7     .07       0
  4989.7     .12       0  5631.9     .16       0  5731.1     .05       0
Bank Sta=4936.3,5017.6
XS Rating Curve= 0 ,0
Exp/Cntr=0.3,0.1

Type RM Length L Ch R = 1 ,57569   ,614,614,614
BEGIN DESCRIPTION:
BOX CREEK 79.0
END DESCRIPTION:
XS GIS Cut Line= 3
      3763899.62     10564310.23      3764149.61     10565110.19
      3763949.61     10567510.16
#Sta/Elev= 30
  4178.4  293.34  4419.3  270.18  4618.4  263.62  4744.1  258.04  4974.6  261.83
    4992  254.49  4994.8  253.99    4998  254.49  5005.9  255.92  5013.9  261.39
  5066.7  261.42  5106.8  260.88  5116.9  258.72  5126.9  261.26  5217.2  260.36
  5257.3  258.77  5267.4  255.84  5331.9  262.59  5337.6   263.3  5377.8  266.74
  5588.5  272.92  5979.8  270.09  6120.3  273.78  6622.1  274.55  6923.1  283.51
  7053.5  284.65  7133.8  287.48  7241.7  296.28  7324.5  300.06  7424.8  301.11
#Mann= 5 ,-1 , 0
  4178.4     .05       0    4992     .03       0    4998     .05       0
  5005.9     .12       0  5331.9     .05       0
Bank Sta=4618.4,5337.6
XS Rating Curve= 0 ,0
Exp/Cntr=0.3,0.1

Type RM Length L Ch R = 1 ,56955   ,864,864,864
BEGIN DESCRIPTION:
BOX CREEK 78.0
END DESCRIPTION:
XS GIS Cut Line= 2
      3763859.64     10564405.26      3763864.85     10566019.85
#Sta/Elev= 30
  4190.9  285.21  4205.8  284.78  4235.8  281.19  4245.8  278.95  4305.8   271.1
  4365.8  264.91  4445.8  261.14  4525.8  258.86  4535.8  257.27  4615.8  257.56
  4695.8  258.84  4785.8  258.55  4945.8  260.24  4958.8  255.95  4975.8  253.56
  4992.8  253.29  4995.6  252.79  4998.8  253.29  5005.8  255.66  5015.8  260.29
  5085.8  259.73  5108.9  262.15  5135.8  264.25  5205.8  267.59  5335.8  269.87
  5475.8  273.49  5545.8  272.83  5615.8  269.87  5665.8  268.82  5805.5  267.85
#Mann= 5 ,-1 , 0
  4190.9     .05       0  4958.8     .12       0  4992.8     .07       0
  4998.8     .12       0  5108.9     .05       0
Bank Sta=4945.8,5015.8
XS Rating Curve= 0 ,0
Exp/Cntr=0.3,0.1

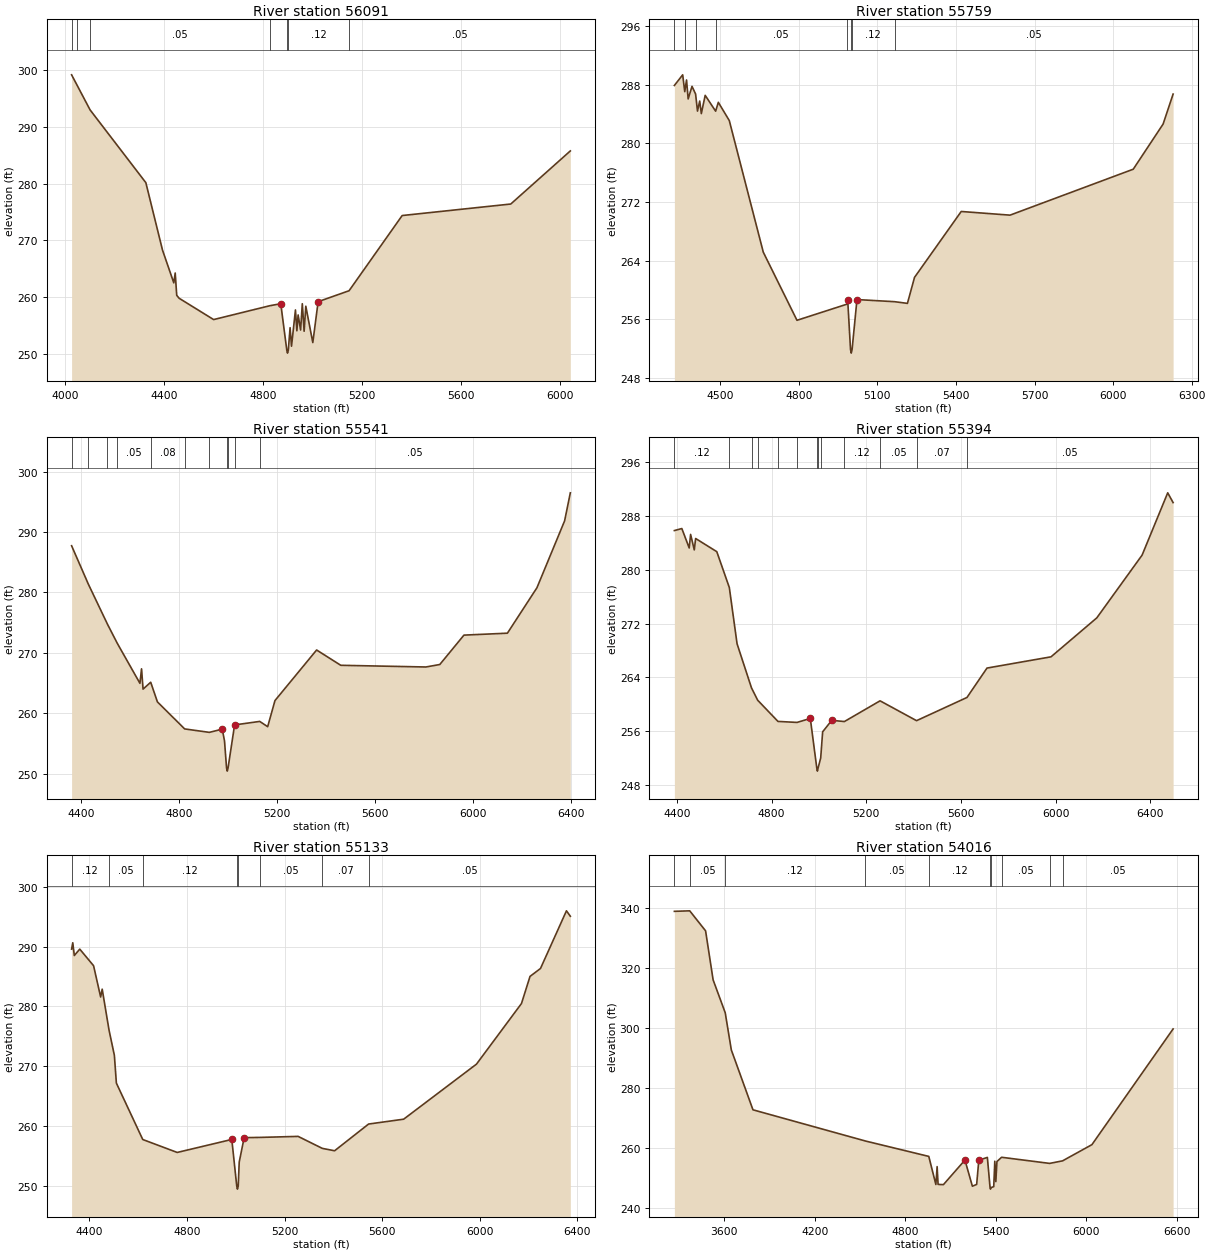
Type RM Length L Ch R = 1 ,56091   ,332,332,332
BEGIN DESCRIPTION:
BOX CREEK 77.0
END DESCRIPTION:
XS GIS Cut Line= 3
      3763899.63     10564210.16      3763449.61     10565010.19
      3762649.61     10565760.19
#Sta/Elev= 30
  4027.4  299.18  4049.5  297.35  4102.1  292.99  4327.3  280.15  4394.6  268.25
  4440.2  262.47  4445.9  264.21    4452  260.27  4461.8  259.75  4601.1  255.99
  4827.6  258.43  4872.3  258.79  4896.7  250.57  4899.5  250.07  4902.7  250.57
  4909.9  254.56  4915.7  251.29  4931.6  257.69  4937.3  254.01  4942.4  256.81
  4952.4  254.15  4959.3  258.79  4966.6  253.93  4973.4  258.35  5001.7  251.93
  5023.2  259.15  5148.2  261.08  5362.7  274.35  5801.3  276.38  6041.9  285.75
#Mann= 7 ,-1 , 0
  4027.4     .05       0  4049.5     .08       0  4102.1     .05       0
  4827.6     .12       0  4896.7     .07       0  4902.7     .12       0
  5148.2     .05       0
Bank Sta=4872.3,5023.2
XS Rating Curve= 0 ,0
Exp/Cntr=0.3,0.1

Type RM Length L Ch R = 1 ,55759   ,218,218,218
BEGIN DESCRIPTION:
Mapping XS 47b50dca
END DESCRIPTION:
XS GIS Cut Line= 3
      3763834.46     10564241.18      3763491.58     10564714.25
      3762450.39     10565525.52
#Sta/Elev= 30
    4325  287.91  4356.7  289.36  4364.6  287.06  4371.4  288.66  4377.6  286.07
  4392.3  287.79    4406  286.74  4413.2  284.41  4421.7  285.78  4427.9  284.07
  4442.6  286.56  4482.5   284.4  4492.8  285.61  4534.6  283.12  4664.5  265.15
  4793.1  255.86    4983  258.05  4986.8   258.6  4997.5  251.88  5000.3  251.38
  5003.5  251.88  5022.1  258.69  5165.5   258.4  5214.8  258.17  5241.9  261.72
  5420.2  270.71  5606.5  270.21    6077  276.48    6191  282.64  6229.2  286.73
#Mann= 8 ,-1 , 0
    4325     .08       0  4364.6     .05       0    4406     .08       0
  4482.5     .05       0    4983     .12       0  4997.5     .07       0
  5003.5     .12       0  5165.5     .05       0
Bank Sta=4986.8,5022.1
XS Rating Curve= 0 ,0
Exp/Cntr=0.3,0.1

Type RM Length L Ch R = 1 ,55541   ,147,147,147
BEGIN DESCRIPTION:
BOX CREEK 76.0
END DESCRIPTION:
XS GIS Cut Line= 4
      3763773.72     10564215.09      3763534.99     10564540.64
      3762962.07     10564683.87      3762276.27      10565469.5
#Sta/Elev= 30
  4359.6  287.73    4428  281.38  4506.2  274.75  4546.3  271.59  4638.7  264.98
  4645.3  267.38  4651.5  264.02  4682.7  265.16  4710.1  261.91  4821.4  257.44
  4922.1  256.87    4975   257.4  4984.2  255.45  4992.6  250.96  4995.4  250.46
  4998.6  250.96  5025.1  258.03  5025.4   258.1    5128  258.68  5160.5  257.81
  5190.3  262.13  5360.4  270.49  5459.1  267.96  5806.6  267.68  5863.5  268.09
  5962.2  272.95  6139.7  273.27  6260.3  280.78  6373.3  291.84  6396.7  296.48
#Mann= 11 ,-1 , 0
  4359.6     .16       0    4428     .08       0  4506.2     .16       0
  4546.3     .05       0  4682.7     .08       0  4821.4     .05       0
  4922.1     .07       0  4992.6     .07       0  4998.6     .07       0
  5025.1      .1       0    5128     .05       0
Bank Sta=4975,5025.4
XS Rating Curve= 0 ,0
Exp/Cntr=0.3,0.1

Type RM Length L Ch R = 1 ,55394   ,261,261,261
BEGIN DESCRIPTION:
BOX CREEK 75.0
END DESCRIPTION:
XS GIS Cut Line= 4
      3763569.69     10564076.26      3763322.31     10564488.56
      3762805.82     10564549.32      3761924.74     10565217.73
#Sta/Elev= 30
  4389.1  285.83  4420.6  286.13  4451.7  283.24  4457.6  285.26  4473.1  282.96
  4478.9  284.65  4568.3  282.69  4621.2  277.36  4653.9     269  4714.9  262.44
    4741  260.61  4826.7  257.46  4907.2  257.31  4963.3   257.9  4990.5  250.57
  4993.2  250.07  4996.5  250.57  5007.2  252.03  5015.4  255.91  5053.9  257.62
  5107.2  257.44    5258  260.52  5412.1  257.57  5625.1  261.02  5709.7  265.39
  5980.1  267.06  6173.5  272.85  6364.9  282.18  6473.1  291.44  6495.9  289.99
#Mann= 13 ,-1 , 0
  4389.1     .12       0  4621.2     .05       0  4714.9     .08       0
    4741     .12       0  4826.7     .08       0  4907.2      .1       0
  4990.5     .07       0  4996.5      .1       0  5007.2     .07       0
  5107.2     .12       0    5258     .05       0  5412.1     .07       0
  5625.1     .05       0
Bank Sta=4963.3,5053.9
XS Rating Curve= 0 ,0
Exp/Cntr=0.3,0.1

Type RM Length L Ch R = 1 ,55133   ,1117,1117,1117
BEGIN DESCRIPTION:
Mapping XS 7d28217d
END DESCRIPTION:
XS GIS Cut Line= 4
      3763526.27      10564080.6       3763105.3     10564401.75
      3762697.31     10564466.86      3761859.65       10565183.
#Sta/Elev= 30
    4327  289.57  4331.8  290.63  4338.1   288.5  4360.5  289.57  4417.1   286.8
  4446.1  281.58  4452.4  282.89  4480.6  276.03  4502.3  271.86  4510.6  267.21
  4618.7   257.8    4760  255.64  4983.8  257.81  5004.1  250.02  5006.9  249.52
  5010.1  250.02  5014.2  254.03  5034.4  258.11  5099.3  258.15  5255.6  258.32
  5354.8  256.32  5405.2  255.92  5544.6  260.38  5688.4  261.19    5987  270.38
  6171.4  280.49  6206.5  285.02  6249.4  286.34  6355.8  295.96  6371.7  295.06
#Mann= 8 ,-1 , 0
    4327     .12       0  4480.6     .05       0  4618.7     .12       0
  5004.1     .07       0  5010.1     .12       0  5099.3     .05       0
  5354.8     .07       0  5544.6     .05       0
Bank Sta=4983.8,5034.4
XS Rating Curve= 0 ,0
Exp/Cntr=0.3,0.1

Type RM Length L Ch R = 1 ,54016   ,644,644,644
BEGIN DESCRIPTION:
BOX CREEK 74.0
END DESCRIPTION:
XS GIS Cut Line= 3
      3763849.58     10562560.22      3762749.61     10564010.19
       3761749.6     10565110.19
#Sta/Elev= 30
  3269.2  338.75  3370.9  338.92  3476.1  332.25    3526  315.92  3606.3  304.97
  3646.7  292.59  3790.2  272.64  4535.8  262.25  4955.9  257.12  5002.9  247.75
  5011.2  253.72  5017.4   247.8  5052.8  247.71  5195.6   255.9  5244.9  247.19
  5273.3  247.79  5287.5  255.84  5344.3  256.79  5362.2  246.72    5365  246.22
  5368.2  246.72  5386.5  247.04  5393.6  255.51  5400.4  248.71  5407.8   255.4
  5438.6  256.83    5757  254.79    5843  255.64  6037.6  261.04  6575.8  299.58
#Mann= 10 ,-1 , 0
  3269.2     .12       0  3370.9     .05       0  3606.3     .12       0
  4535.8     .05       0  4955.9     .12       0  5362.2     .07       0
  5368.2     .12       0  5438.6     .05       0    5757     .12       0
    5843     .05       0
Bank Sta=5195.6,5287.5
XS Rating Curve= 0 ,0
Exp/Cntr=0.3,0.1

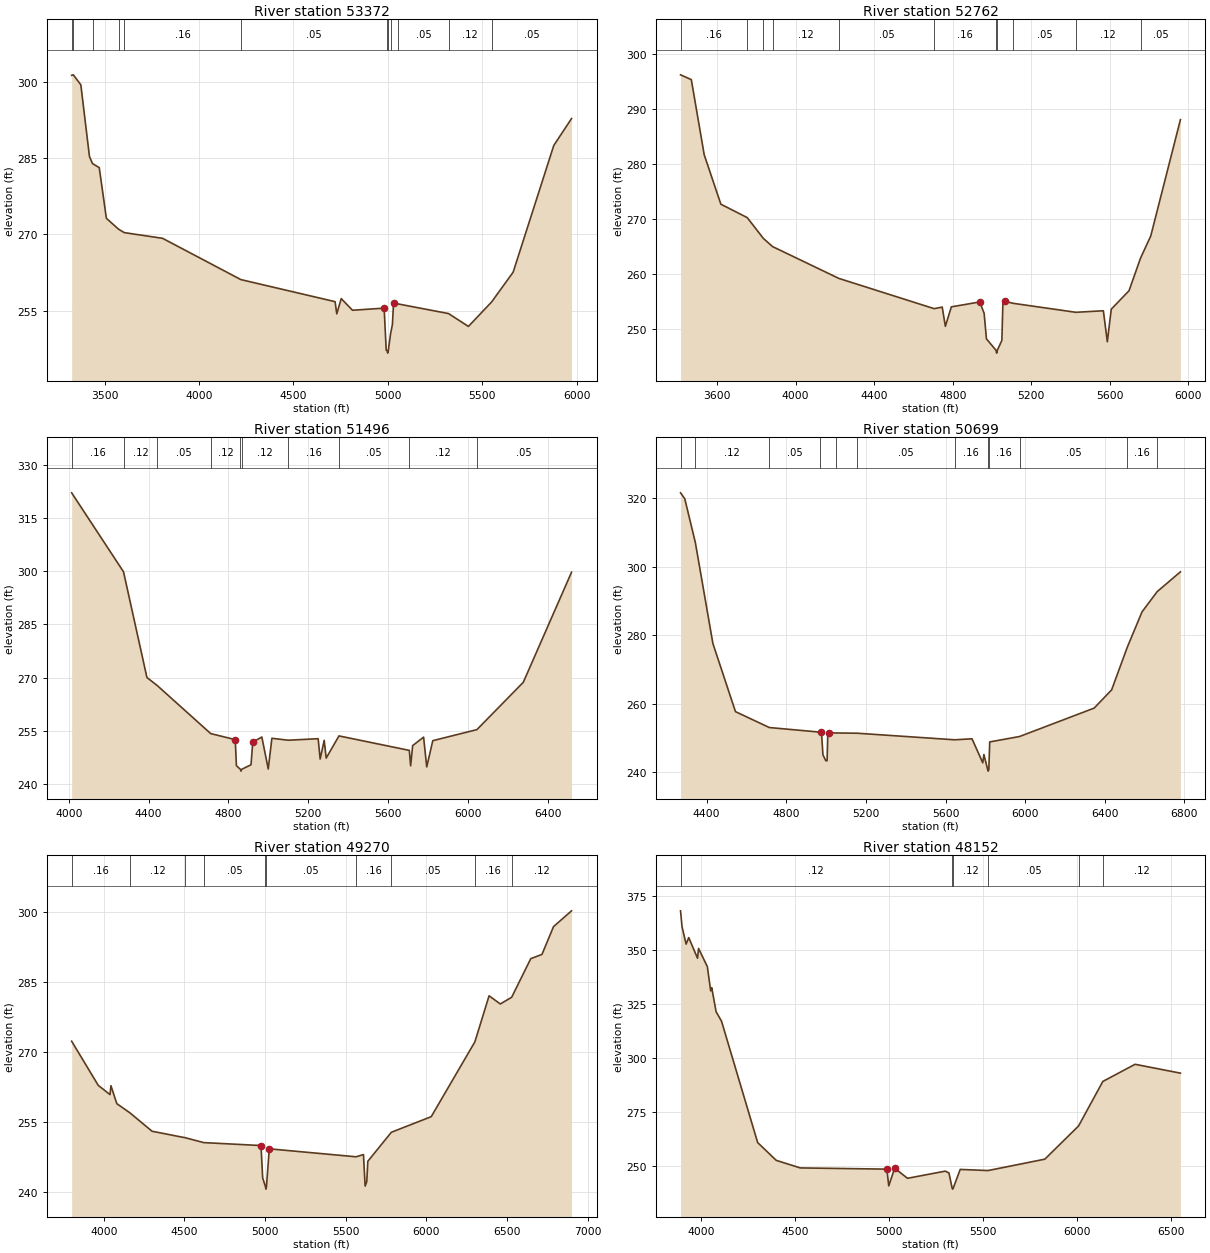
Type RM Length L Ch R = 1 ,53372   ,610,610,610
BEGIN DESCRIPTION:
BOX CREEK 73.0
END DESCRIPTION:
XS GIS Cut Line= 3
      3762849.61      10562560.2      3762349.61     10564160.19
      3761799.62     10564960.17
#Sta/Elev= 30
  3325.8  301.26  3334.6  301.36  3374.5  299.39  3420.1  285.29  3436.2  283.91
  3471.9  283.11  3509.7  273.14  3574.6  270.99  3604.2  270.33  3807.2  269.21
  4221.8  261.09  4720.8  256.75  4729.7  254.35  4753.3  257.35    4813  255.06
  4980.6  255.48  4991.6  247.19  4996.5  247.13  4999.2  246.63  5002.5  247.13
  5014.5   250.4  5024.4  252.27  5030.5  256.55  5056.5  256.29  5321.6  254.41
  5426.8  251.88  5549.7  256.69  5663.7  262.55  5878.9  287.47  5972.9  292.76
#Mann= 12 ,-1 , 0
  3325.8     .12       0  3334.6     .07       0  3436.2     .16       0
  3574.6     .07       0  3604.2     .16       0  4221.8     .05       0
  4996.5     .03       0  5002.5     .05       0  5014.5     .12       0
  5056.5     .05       0  5321.6     .12       0  5549.7     .05       0
Bank Sta=4980.6,5030.5
XS Rating Curve= 0 ,0
Exp/Cntr=0.3,0.1

Type RM Length L Ch R = 1 ,52762   ,1266,1266,1266
BEGIN DESCRIPTION:
BOX CREEK 72.0
END DESCRIPTION:
XS GIS Cut Line= 3
       3762549.6      10562460.2      3761899.61     10563910.19
       3761799.6     10564860.23
#Sta/Elev= 30
  3414.7   296.3  3469.5  295.43  3535.2  281.75  3619.9  272.76  3754.2  270.31
  3836.2  266.53  3883.1  265.04  4220.4  259.25  4705.7  253.74  4746.6  254.03
  4762.6  250.53    4793  254.07  4937.5  254.96  4959.9  252.91  4971.7  248.25
  5020.8  246.15  5023.6  245.65  5026.8  246.15  5050.2  247.97  5055.2  254.46
    5064  255.09  5108.6  254.71  5426.6  253.08  5566.8  253.36  5586.9  247.72
    5607  253.65  5697.5  257.01  5755.9  262.93  5808.1  266.98    5959  288.14
#Mann= 11 ,-1 , 0
  3414.7     .16       0  3754.2     .12       0  3836.2     .16       0
  3883.1     .12       0  4220.4     .05       0  4705.7     .16       0
  5020.8     .07       0  5026.8     .16       0  5108.6     .05       0
  5426.6     .12       0  5755.9     .05       0
Bank Sta=4937.5,5064
XS Rating Curve= 0 ,0
Exp/Cntr=0.3,0.1

Type RM Length L Ch R = 1 ,51496   ,797,797,797
BEGIN DESCRIPTION:
BOX CREEK 71.0
END DESCRIPTION:
XS GIS Cut Line= 3
      3761949.61     10562660.19      3761449.61     10563460.19
       3761649.6     10565010.14
#Sta/Elev= 30
  4013.9  322.19  4273.9  299.88  4391.3  270.02  4443.3  267.73    4711  254.18
  4834.1  252.46    4840   245.1    4860  244.07  4862.7  243.57    4866  244.07
  4913.1  245.37  4921.9  251.77  4967.4  253.21  4999.5  244.18  5017.8  252.85
  5099.5   252.3  5249.7  252.73  5259.8  246.98    5280  252.27    5290  247.25
  5354.1  253.52  5706.8  249.43  5713.5  245.07  5723.6  250.78  5778.4  253.17
  5794.2  244.76  5824.4  252.17  6045.6  255.29  6278.2  268.66  6520.1  299.76
#Mann= 10 ,-1 , 0
  4013.9     .16       0  4273.9     .12       0  4443.3     .05       0
    4711     .12       0    4860     .07       0    4866     .12       0
  5099.5     .16       0  5354.1     .05       0  5706.8     .12       0
  6045.6     .05       0
Bank Sta=4834.1,4921.9
XS Rating Curve= 0 ,0
Exp/Cntr=0.3,0.1

Type RM Length L Ch R = 1 ,50699   ,1429,1429,1429
BEGIN DESCRIPTION:
BOX CREEK 70.0
END DESCRIPTION:
XS GIS Cut Line= 3
      3761649.61     10562510.19      3761149.61     10563060.19
       3760299.6     10564610.21
#Sta/Elev= 30
    4269  321.62  4290.3  319.88  4343.4   307.1  4431.5  277.63    4545  257.73
  4714.9  253.09  4968.7  251.75  4976.8   251.9  4984.3  245.14  4998.5  243.41
  5005.2   243.4  5008.9  251.58  5012.3  251.58  5047.8   251.5  5155.7  251.43
  5646.1  249.51  5733.2   249.8  5787.2  242.78  5792.9  245.21  5811.7  240.86
  5814.4  240.36  5817.7  240.86  5822.1  248.89  5972.3  250.47  6346.7  258.76
  6434.6  264.09  6512.9  276.49  6587.2  286.86  6663.3  292.77  6780.1  298.55
#Mann= 12 ,-1 , 0
    4269     .16       0  4343.4     .12       0  4714.9     .05       0
  4968.7     .16       0  5047.8     .12       0  5155.7     .05       0
  5646.1     .16       0  5811.7     .07       0  5817.7     .16       0
  5972.3     .05       0  6512.9     .16       0  6663.3     .12       0
Bank Sta=4976.8,5012.3
XS Rating Curve= 0 ,0
Exp/Cntr=0.3,0.1

Type RM Length L Ch R = 1 ,49270   ,1118,1118,1118
BEGIN DESCRIPTION:
Mapping XS af3814f1
END DESCRIPTION:
XS GIS Cut Line= 3
      3761044.78     10561888.95      3760456.24     10562816.03
      3760018.75     10564769.11
#Sta/Elev= 30
  3800.8  272.31  3965.6  262.86  4038.5  260.88  4044.4  262.78  4080.8  258.94
  4162.2  256.97  4299.4  253.03  4506.6  251.63    4620   250.6  4974.9  249.97
  4985.2  243.05  5002.7  241.14  5005.4  240.64  5008.7  241.14  5026.2  249.27
  5564.5  247.56  5610.3  248.04  5620.5  241.29  5630.8  242.24  5637.1  246.59
    5783  252.81  6030.4  256.15  6301.1  272.17  6389.1  282.03  6458.8  280.28
  6529.3  281.72  6647.6  289.98    6717  290.89  6788.8  296.84  6900.4  300.22
#Mann= 10 ,-1 , 0
  3800.8     .16       0  4162.2     .12       0  4506.6     .16       0
    4620     .05       0  5002.7     .03       0  5008.7     .05       0
  5564.5     .16       0    5783     .05       0  6301.1     .16       0
  6529.3     .12       0
Bank Sta=4974.9,5026.2
XS Rating Curve= 0 ,0
Exp/Cntr=0.3,0.1

Type RM Length L Ch R = 1 ,48152   ,1075,1075,1075
BEGIN DESCRIPTION:
BOX CREEK 69.0
END DESCRIPTION:
XS GIS Cut Line= 3
       3760241.3     10562103.07      3759859.35     10562971.14
      3759815.95      10564681.2
#Sta/Elev= 30
  3890.7  368.06  3898.5  360.75  3920.3  352.64  3934.4  355.64  3981.1  346.09
  3986.6  350.63  4033.3  342.19  4051.1  330.96  4056.6  332.43  4079.9  321.29
  4108.7  316.92  4300.9  260.67  4399.7  252.42  4527.4  248.92  4988.2  248.35
  4998.2   240.6  5029.6  248.78  5098.2  244.11  5298.3  247.42  5318.3  246.63
  5335.3  239.59    5338  239.09  5341.3  239.59  5378.3  248.22  5526.7   247.7
  5828.5  252.98  6007.7  268.34    6137  288.99  6308.6  296.94  6549.7  292.84
#Mann= 6 ,-1 , 0
  3890.7     .12       0  5335.3     .07       0  5341.3     .12       0
  5526.7     .05       0  6007.7     .16       0    6137     .12       0
Bank Sta=4988.2,5029.6
XS Rating Curve= 0 ,0
Exp/Cntr=0.3,0.1