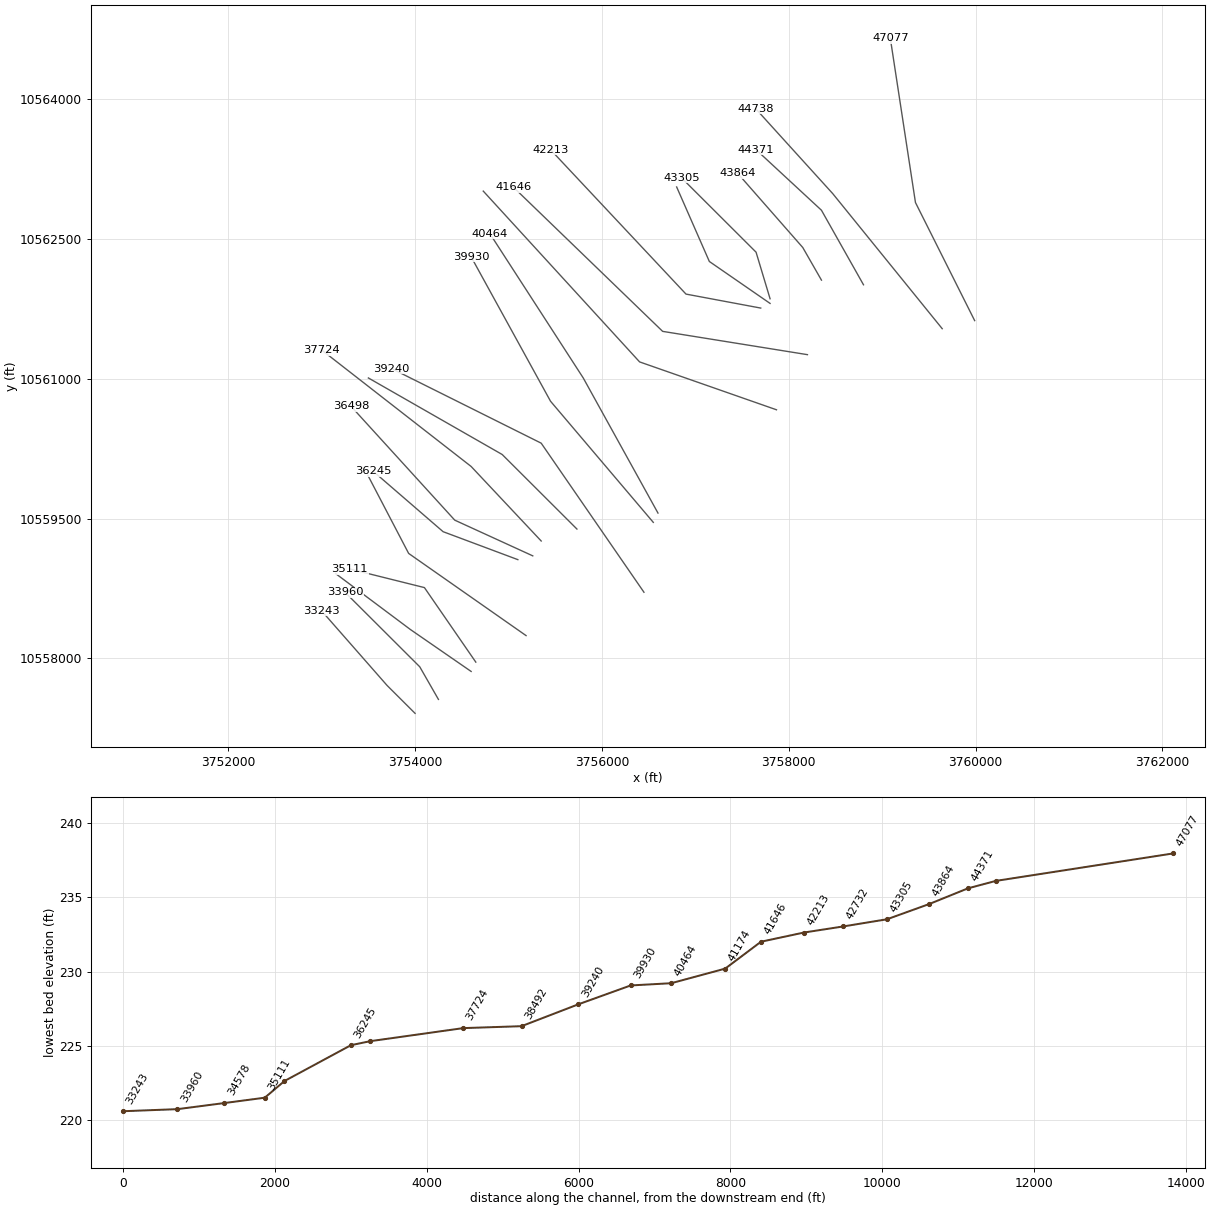
HEC-RAS study BOX CREEK.prj: BOX CREEK Base Level Engineering

--- BOX CREEK.g01 (geometry) --- (continued)

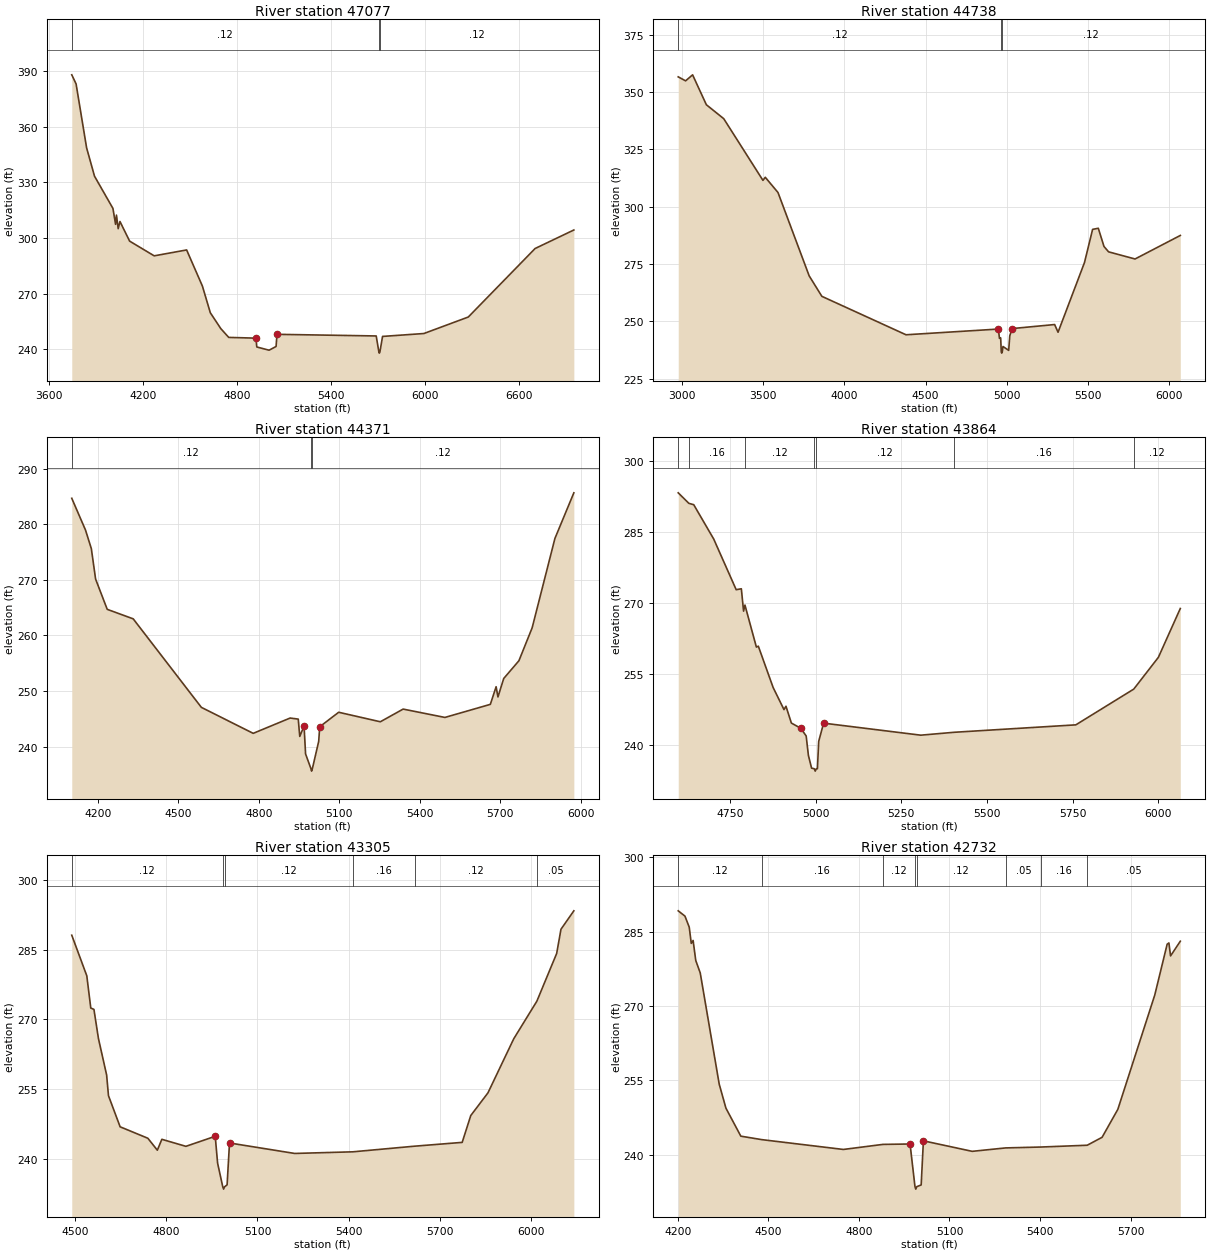
Type RM Length L Ch R = 1 ,47077   ,2339,2339,2339
BEGIN DESCRIPTION:
BOX CREEK 68.0
END DESCRIPTION:
XS GIS Cut Line= 3
      3759989.57     10561625.63      3759355.88     10562893.02
      3759086.77     10564655.21
#Sta/Elev= 30
    3748  388.08  3775.5  383.19  3842.5  348.72    3893  333.39  4010.4  316.01
  4027.2  307.43  4032.8  312.41  4043.8  305.11  4055.2  308.95  4116.7  298.38
  4273.2  290.44    4480  293.62  4580.4  274.15    4631  259.73    4698  251.16
  4748.3  246.44  4921.6  246.04  4927.2  241.28  5005.3  239.54    5050  241.54
  5055.8   248.1  5688.1  247.22  5705.4  238.46  5708.1  237.96  5711.4  238.46
  5728.6  246.97  5991.6  248.53  6274.9  257.43  6700.9   294.4  6947.6  304.38
#Mann= 3 ,-1 , 0
    3748     .12       0  5705.4     .07       0  5711.4     .12       0
Bank Sta=4921.6,5055.8
XS Rating Curve= 0 ,0
Exp/Cntr=0.3,0.1

Type RM Length L Ch R = 1 ,44738   ,367,367,367
BEGIN DESCRIPTION:
BOX CREEK 67.0
END DESCRIPTION:
XS GIS Cut Line= 3
      3759642.32     10561538.86      3758470.46      10562988.5
      3757645.81     10563899.95
#Sta/Elev= 30
  2976.5  356.55  3021.9   354.8    3065  357.43  3149.8  344.39  3256.9   338.3
  3498.4  311.42  3512.8  312.76  3591.1  306.13    3783  269.82  3861.3  260.87
  4379.8  244.11  4948.8   246.6  4955.5  242.56    4963  242.75  4966.7  236.61
  4969.5  236.11  4972.7  236.61  4977.2  239.01  5012.3  237.31  5019.1  243.66
  5033.3  246.81  5295.5  248.57  5316.5  245.22  5479.3  275.59  5529.4  290.06
  5564.5  290.54  5599.6  282.59    5628  280.26  5790.9  277.15  6069.7  287.41
#Mann= 3 ,-1 , 0
  2976.5     .12       0  4966.7     .07       0  4972.7     .12       0
Bank Sta=4948.8,5033.3
XS Rating Curve= 0 ,0
Exp/Cntr=0.3,0.1

Type RM Length L Ch R = 1 ,44371   ,507,507,507
BEGIN DESCRIPTION:
BOX CREEK 66.0
END DESCRIPTION:
XS GIS Cut Line= 3
      3758799.61     10562010.19      3758349.61     10562810.19
      3757649.63     10563460.17
#Sta/Elev= 30
  4101.9  284.65  4153.2  278.93  4174.9   275.6  4190.8  270.13  4234.2  264.69
  4331.1  262.98  4585.4  247.07  4778.8   242.4  4916.5  245.15  4946.8  244.96
  4952.5  241.85  4968.5  243.72  4974.2  238.69  4993.8  236.11  4996.6  235.61
  4999.8  236.11  5023.2  240.98  5026.9  243.58  5097.7  246.19  5253.1  244.48
  5338.1  246.76    5494  245.26  5663.5  247.61    5685  250.78  5691.9  248.94
  5713.4  252.26  5770.1  255.45  5819.4  261.36  5904.4  277.43    5975  285.63
#Mann= 3 ,-1 , 0
  4101.9     .12       0  4993.8     .07       0  4999.8     .12       0
Bank Sta=4968.5,5026.9
XS Rating Curve= 0 ,0
Exp/Cntr=0.3,0.1

Type RM Length L Ch R = 1 ,43864   ,559,559,559
BEGIN DESCRIPTION:
BOX CREEK 65.0
END DESCRIPTION:
XS GIS Cut Line= 3
      3758349.61     10562060.19      3758149.61     10562410.19
      3757449.62     10563210.17
#Sta/Elev= 30
  4598.5  293.32  4629.5   291.1  4643.8  290.81  4702.2  283.55  4767.7  272.87
  4782.8  273.06  4789.3  268.34  4793.3  269.62  4826.7  260.75  4832.4  260.94
  4875.6  252.22  4907.3  247.55  4913.1  248.26  4928.9  244.71  4956.3  243.61
  4972.1  241.98  4978.6  237.89  4987.9  235.19  4995.7  235.06  4998.5  234.56
  5001.7  235.06  5004.9  235.06  5008.7  240.85    5023  244.69  5306.7  242.15
    5404  242.76  5759.5  244.33  5928.7  251.88  6000.6  258.59  6064.6   268.9
#Mann= 7 ,-1 , 0
  4598.5     .12       0  4629.5     .16       0  4793.3     .12       0
  4995.7     .07       0  5001.7     .12       0    5404     .16       0
  5928.7     .12       0
Bank Sta=4956.3,5023
XS Rating Curve= 0 ,0
Exp/Cntr=0.3,0.1

Type RM Length L Ch R = 1 ,43305   ,573,573,573
BEGIN DESCRIPTION:
BOX CREEK 64.0
END DESCRIPTION:
XS GIS Cut Line= 3
       3757799.6     10561860.23      3757649.61     10562360.19
      3756849.64     10563160.16
#Sta/Elev= 30
  4488.5  288.12    4538  279.39  4551.1  272.46  4561.5  272.17  4576.3  265.92
  4603.3  258.06  4609.4  253.62  4647.7  246.93    4739  244.47  4770.3   241.9
  4785.1  244.24  4864.3  242.73  4960.9  244.89  4968.7  239.13  4985.7  234.03
  4988.5  233.53  4991.7  234.03    5000  234.45  5007.9  243.45  5222.6   241.2
    5414  241.55  5618.8  242.77  5774.1  243.58  5802.4  249.35    5859  254.23
  5943.9  265.85    6020  273.93  6085.3   284.2  6099.4   289.4  6141.8  293.36
#Mann= 6 ,-1 , 0
  4488.5     .12       0  4985.7     .07       0  4991.7     .12       0
    5414     .16       0  5618.8     .12       0    6020     .05       0
Bank Sta=4960.9,5007.9
XS Rating Curve= 0 ,0
Exp/Cntr=0.3,0.1

Type RM Length L Ch R = 1 ,42732   ,519,519,519
BEGIN DESCRIPTION:
BOX CREEK 63.0
END DESCRIPTION:
XS GIS Cut Line= 3
      3757799.57     10561810.21      3757149.61     10562260.19
      3756799.63     10563060.15
#Sta/Elev= 30
  4201.2  289.17  4223.5   288.1  4237.6  285.88  4244.4  282.61  4250.5  283.19
  4259.3  279.15  4274.1  276.65    4337  254.22  4359.3  249.37  4408.6  243.73
  4478.1  243.03  4748.5  241.05  4879.4  242.07  4969.4  242.15  4985.7  233.55
  4988.4  233.05  4991.7  233.55  5006.2  233.89  5013.6  242.79  5175.3  240.67
    5286  241.36  5403.6  241.54  5556.4   241.9  5605.7   243.5  5657.9  249.14
  5780.3   272.2  5821.3  282.44  5827.1  282.69  5832.6  280.08  5864.9  283.04
#Mann= 8 ,-1 , 0
  4201.2     .12       0  4478.1     .16       0  4879.4     .12       0
  4985.7     .07       0  4991.7     .12       0    5286     .05       0
  5403.6     .16       0  5556.4     .05       0
Bank Sta=4969.4,5013.6
XS Rating Curve= 0 ,0
Exp/Cntr=0.3,0.1

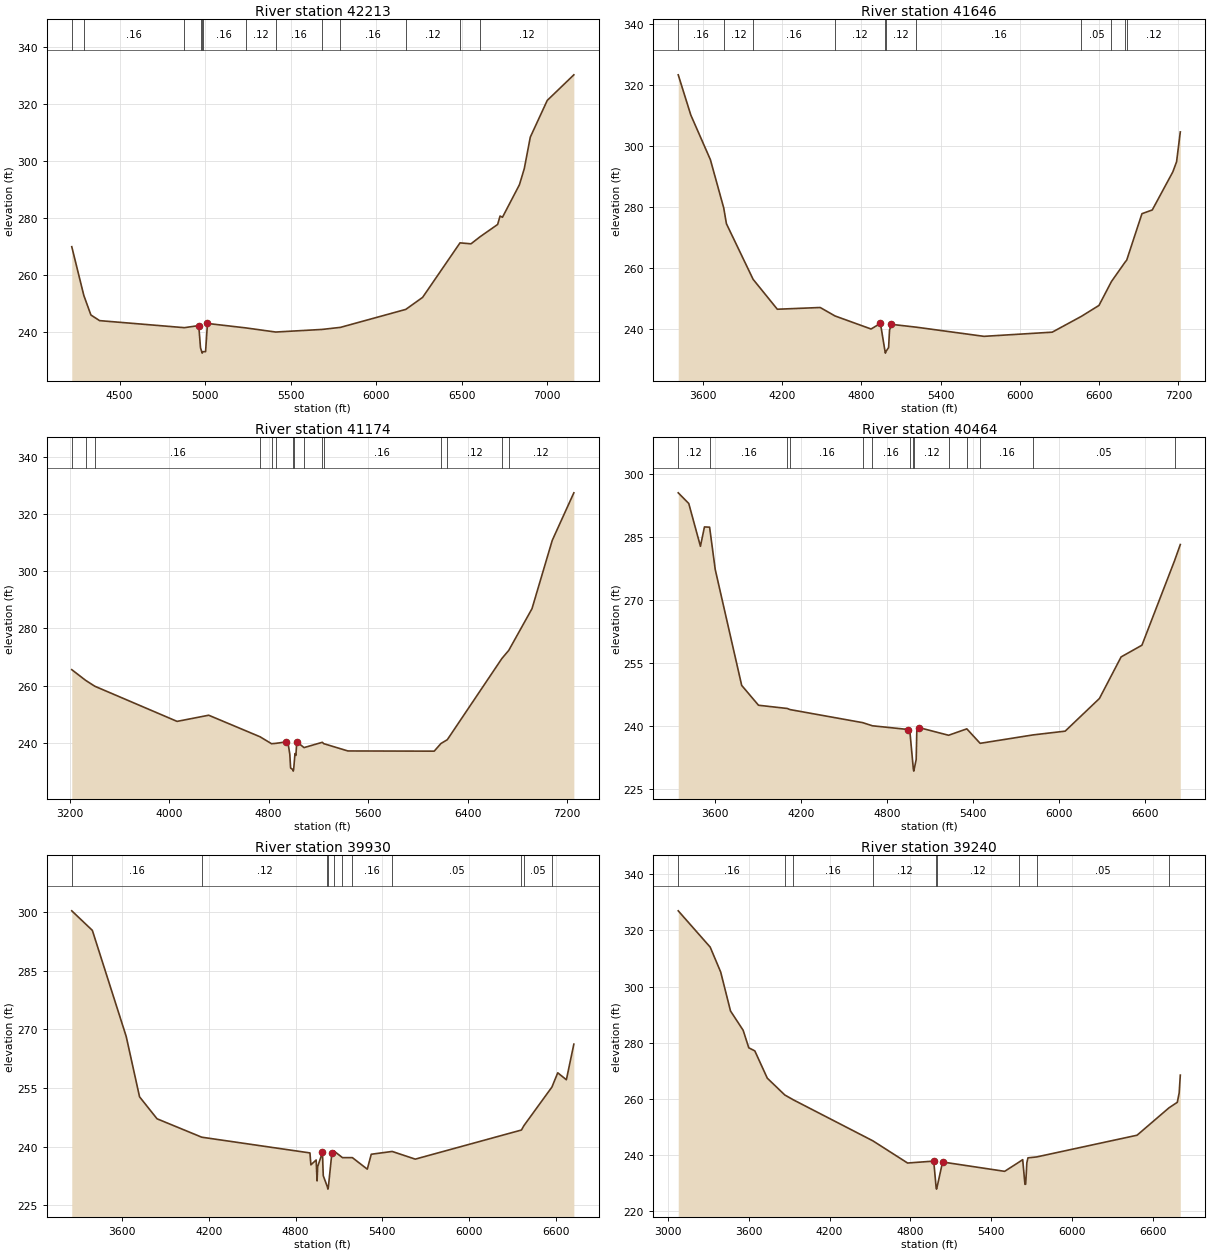
Type RM Length L Ch R = 1 ,42213   ,567,567,567
BEGIN DESCRIPTION:
BOX CREEK 62.0
END DESCRIPTION:
XS GIS Cut Line= 3
       3757699.6     10561760.19      3756899.61     10561910.19
      3755449.63     10563460.17
#Sta/Elev= 30
  4220.6  269.97  4291.1  252.88  4332.5  246.02  4383.4  244.04  4879.1  241.57
  4963.3   242.3  4973.5   234.5  4978.5  233.56  4980.7  233.14  4983.4  232.64
  4986.7  233.14  5003.2  233.17  5014.2  243.05  5238.3  241.49  5413.2  240.04
  5684.3  240.95  5792.2  241.68  6174.1  247.98  6272.6   252.2  6491.3  271.32
  6555.5  270.98  6608.1  273.44  6711.3  277.77  6725.4  280.72  6739.6   280.3
  6838.8  291.71  6867.1  297.35  6902.3   308.4  7001.4  321.28    7157  330.26
#Mann= 13 ,-1 , 0
  4220.6     .12       0  4291.1     .16       0  4879.1     .12       0
  4978.5     .16       0  4980.7     .07       0  4986.7     .16       0
  5238.3     .12       0  5413.2     .16       0  5684.3     .12       0
  5792.2     .16       0  6174.1     .12       0  6491.3     .16       0
  6608.1     .12       0
Bank Sta=4963.3,5014.2
XS Rating Curve= 0 ,0
Exp/Cntr=0.3,0.1

Type RM Length L Ch R = 1 ,41646   ,472,472,472
BEGIN DESCRIPTION:
BOX CREEK 61.0
END DESCRIPTION:
XS GIS Cut Line= 3
      3758199.58     10561260.19      3756649.61     10561510.19
      3755049.58     10563060.21
#Sta/Elev= 30
  3416.2  323.39  3511.4  310.18  3659.3  295.55  3760.3  279.69  3780.8   274.5
  3982.6  256.25  4165.7  246.43  4489.9     247  4602.3  244.22  4874.8  239.94
  4945.7  241.79  4980.7  232.52  4983.4  232.02  4986.7  232.52  5007.4  233.84
  5014.4  239.51  5028.5  241.47  5217.1  240.54  5728.7  237.53    6245   238.9
  6465.4  244.09  6598.7  247.68  6692.5  255.49  6797.9     262  6808.2  262.52
  6923.8   277.8  7001.8  279.02  7157.4  291.53  7185.7  294.86  7213.9  304.65
#Mann= 11 ,-1 , 0
  3416.2     .16       0  3760.3     .12       0  3982.6     .16       0
  4602.3     .12       0  4980.7     .07       0  4986.7     .12       0
  5217.1     .16       0  6465.4     .05       0  6692.5     .12       0
  6797.9     .07       0  6808.2     .12       0
Bank Sta=4945.7,5028.5
XS Rating Curve= 0 ,0
Exp/Cntr=0.3,0.1

Type RM Length L Ch R = 1 ,41174   ,710,710,710
BEGIN DESCRIPTION:
BOX CREEK 60.0
END DESCRIPTION:
XS GIS Cut Line= 3
      3757868.22     10560668.56      3756402.93     10561182.45
      3754729.55     10563015.52
#Sta/Elev= 30
    3218  265.62  3329.9  261.88  3402.5  259.85  4064.3  247.57  4318.6  249.72
    4731   242.2  4823.7  239.77  4860.6  239.92  4941.6  240.42  4955.8  240.04
    4970  236.19  4976.8   231.3  4994.9  230.71  4997.7  230.21  5000.9  230.71
  5011.9  236.34  5019.3   235.7  5026.1  240.46  5084.5  238.42  5231.6  240.27
  5242.6   239.8  5436.9  237.25  6130.7  237.18  6185.1  239.86  6235.8  241.17
  6674.9  269.54  6729.5  272.34  6916.4   286.9  7079.2  310.74  7252.8  327.34
#Mann= 15 ,-1 , 0
    3218     .16       0  3329.9     .12       0  3402.5     .16       0
    4731     .12       0  4823.7     .16       0  4860.6     .12       0
  4994.9     .07       0  5000.9     .12       0  5084.5     .16       0
  5231.6     .12       0  5242.6     .16       0  6185.1     .05       0
  6235.8     .12       0  6674.9     .05       0  6729.5     .12       0
Bank Sta=4941.6,5026.1
XS Rating Curve= 0 ,0
Exp/Cntr=0.3,0.1

Type RM Length L Ch R = 1 ,40464   ,534,534,534
BEGIN DESCRIPTION:
BOX CREEK 59.0
END DESCRIPTION:
XS GIS Cut Line= 3
      3756599.63     10559560.16      3755799.61     10561010.19
      3754799.59     10562560.21
#Sta/Elev= 30
  3342.7  295.51  3416.1  292.97  3497.5  282.78  3525.5  287.39  3561.4  287.33
  3600.6  277.26  3785.1  249.65  3902.4  244.92  4103.3  244.15  4121.6  243.89
  4629.7  240.77  4696.4  240.03  4947.2  239.14    4958  238.63    4982  229.73
  4984.8  229.23    4988  229.73  5001.8  231.99  5006.4  239.21  5021.5   239.6
  5227.8  237.77  5354.8   239.3  5447.7  235.85  5817.9  237.86  6040.5  238.75
  6279.4  246.53  6430.6  256.43  6575.8  259.22  6803.4  279.36  6843.4   283.2
#Mann= 14 ,-1 , 0
  3342.7     .12       0  3561.4     .16       0  4103.3     .12       0
  4121.6     .16       0  4629.7     .12       0  4696.4     .16       0
    4958     .12       0    4982     .07       0    4988     .12       0
  5227.8     .16       0  5354.8     .12       0  5447.7     .16       0
  5817.9     .05       0  6803.4     .16       0
Bank Sta=4947.2,5021.5
XS Rating Curve= 0 ,0
Exp/Cntr=0.3,0.1

Type RM Length L Ch R = 1 ,39930   ,690,690,690
BEGIN DESCRIPTION:
BOX CREEK 58.0
END DESCRIPTION:
XS GIS Cut Line= 3
      3756549.63     10559460.16      3755449.61     10560760.19
      3754599.63     10562310.15
#Sta/Elev= 30
  3252.9  300.42  3395.2  295.41  3629.2  268.22  3721.5  252.74  3842.4  247.11
  4151.5  242.39  4899.3  238.36  4905.9   235.3  4942.2  236.55  4948.7  231.19
  4952.6  234.82  4985.7   238.5  4991.4  232.52  5020.6  229.58  5023.4  229.08
  5026.6  229.58  5051.1  238.39    5069  238.75  5124.2  237.15  5192.7  237.15
  5295.7   234.2  5323.2  238.02  5467.8  238.74  5627.4  236.77  6361.4  244.23
  6378.2  245.34    6572  255.24  6612.3   258.9    6672  257.12  6723.6  266.24
#Mann= 11 ,-1 , 0
  3252.9     .16       0  4151.5     .12       0  5020.6     .07       0
  5026.6     .12       0    5069     .16       0  5124.2     .12       0
  5192.7     .16       0  5467.8     .05       0  6361.4     .16       0
  6378.2     .05       0    6572     .16       0
Bank Sta=4985.7,5051.1
XS Rating Curve= 0 ,0
Exp/Cntr=0.3,0.1

Type RM Length L Ch R = 1 ,39240   ,748,748,748
BEGIN DESCRIPTION:
BOX CREEK 57.0
END DESCRIPTION:
XS GIS Cut Line= 3
      3756449.62     10558710.17      3755349.61     10560310.19
      3753749.64     10561110.18
#Sta/Elev= 30
  3075.7  326.99  3313.2  314.06  3391.2  305.17  3464.1   291.3  3558.1  284.42
    3600  278.17  3644.7  277.08  3737.4  267.35  3867.5  261.36  3931.9  259.61
  4522.3  245.01  4779.9  237.11  4974.1   237.8    4992  228.31  4994.8  227.81
    4998  228.31  5039.7  237.48  5500.9  234.15  5606.5   237.4  5635.1  238.31
  5651.9   229.5  5657.4  229.58  5665.8  237.18  5674.2  238.96  5738.7  239.28
  6484.8  247.02  6722.8  256.81  6783.9  258.75  6797.8  262.11  6806.2  268.44
#Mann= 9 ,-1 , 0
  3075.7     .16       0  3867.5     .05       0  3931.9     .16       0
  4522.3     .12       0    4992     .07       0    4998     .12       0
  5606.5     .16       0  5738.7     .05       0  6722.8     .08       0
Bank Sta=4974.1,5039.7
XS Rating Curve= 0 ,0
Exp/Cntr=0.3,0.1

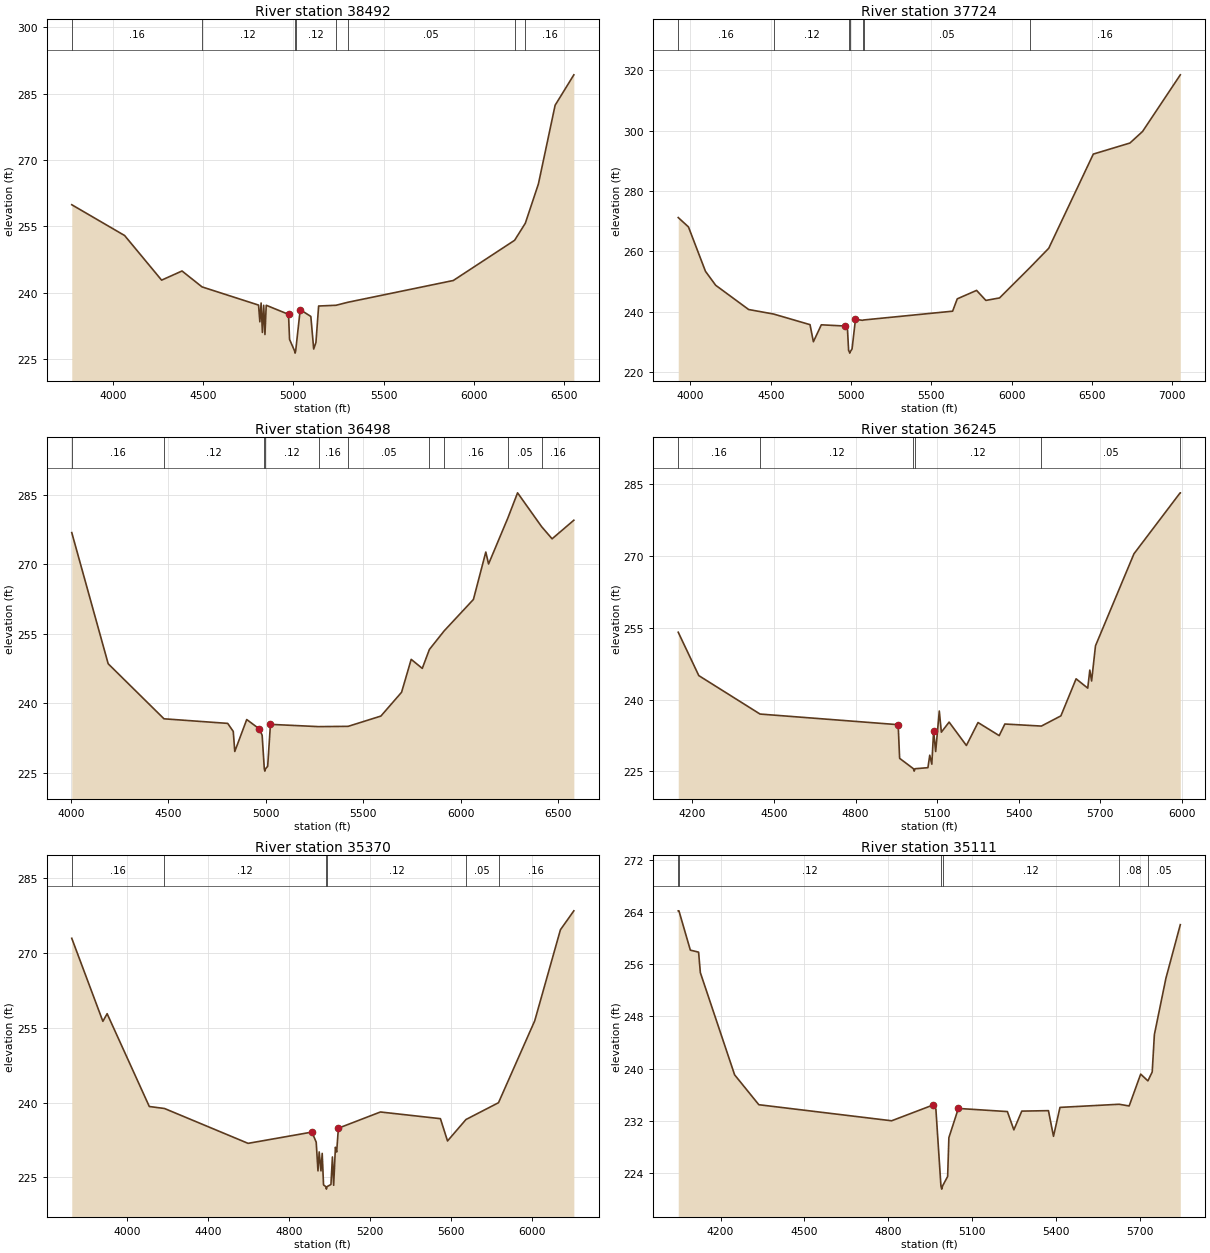
Type RM Length L Ch R = 1 ,38492   ,768,768,768
BEGIN DESCRIPTION:
BOX CREEK 56.0
END DESCRIPTION:
XS GIS Cut Line= 3
      3755732.22     10559388.52      3754932.25     10560188.49
       3753499.6      10561010.2
#Sta/Elev= 30
  3771.4  259.89  4064.3  252.93  4269.4  242.84  4382.5  244.91  4493.6  241.31
  4806.8   237.2  4813.9  233.41  4820.9  237.67    4828  231.02  4835.1  237.16
  4842.2  230.55  4849.2  237.16  4972.8  235.11  4978.6  229.44  5006.5  226.84
  5009.3  226.34  5012.5  226.84  5037.6  236.17  5096.5  234.63  5112.4  227.27
  5124.8  228.75  5139.7  236.99  5236.2  237.16  5302.1  237.84  5886.2  242.76
    6226  251.85  6285.3   255.7  6357.9  264.59  6450.5  282.38  6554.3  289.26
#Mann= 8 ,-1 , 0
  3771.4     .16       0  4493.6     .12       0  5006.5     .07       0
  5012.5     .12       0  5236.2     .16       0  5302.1     .05       0
    6226     .08       0  6285.3     .16       0
Bank Sta=4972.8,5037.6
XS Rating Curve= 0 ,0
Exp/Cntr=0.3,0.1

Type RM Length L Ch R = 1 ,37724   ,1226,1226,1226
BEGIN DESCRIPTION:
BOX CREEK 55.0
END DESCRIPTION:
XS GIS Cut Line= 3
       3755349.6     10559260.19      3754599.61     10560060.19
      3752999.59     10561310.21
#Sta/Elev= 30
    3924  271.16  3987.7  268.06  4093.7  253.33  4157.2  248.71  4362.6  240.67
  4517.9  239.17  4744.8  235.65  4765.8  229.99  4815.2   235.6  4964.1  235.19
  4978.3  233.93  4985.2  227.06  4989.5  226.71  4992.2  226.21  4995.5  226.71
  5006.6   227.6  5027.8  237.39  5072.1  237.09  5078.5   237.2  5632.9  240.12
  5661.8  244.21  5782.1  247.01    5840  243.69    5925  244.51  6113.4  254.51
  6231.6  260.98  6509.2  292.21  6737.1  295.87  6815.8   299.7    7051  318.49
#Mann= 7 ,-1 , 0
    3924     .16       0  4517.9     .12       0  4989.5     .07       0
  4995.5     .12       0  5072.1     .16       0  5078.5     .05       0
  6113.4     .16       0
Bank Sta=4964.1,5027.8
XS Rating Curve= 0 ,0
Exp/Cntr=0.3,0.1

Type RM Length L Ch R = 1 ,36498   ,253,253,253
BEGIN DESCRIPTION:
BOX CREEK 54.0
END DESCRIPTION:
XS GIS Cut Line= 3
      3755259.29     10559100.82      3754424.31     10559483.97
      3753311.05     10560709.28
#Sta/Elev= 30
  4005.5  276.89  4192.2  248.54  4478.4  236.64    4805  235.65  4833.5  233.91
  4841.3  229.58  4902.5  236.48  4967.4  234.45  4981.6  233.08  4992.7  225.83
  4995.5  225.33  4998.7  225.83  5009.9  226.36  5024.1  235.44  5270.9  234.95
  5422.5  235.01  5590.4  237.23  5696.5  242.38  5745.8  249.49  5802.6  247.54
  5839.1  251.63  5914.7  255.64  6064.8  262.44  6128.3  272.69  6142.5  270.11
  6241.5  280.06  6291.2  285.49  6414.6  278.17  6468.2  275.55  6579.7  279.57
#Mann= 10 ,-1 , 0
  4005.5     .16       0  4478.4     .12       0  4992.7     .07       0
  4998.7     .12       0  5270.9     .16       0  5422.5     .05       0
  5839.1     .08       0  5914.7     .16       0  6241.5     .05       0
  6414.6     .16       0
Bank Sta=4967.4,5024.1
XS Rating Curve= 0 ,0
Exp/Cntr=0.3,0.1

Type RM Length L Ch R = 1 ,36245   ,875,875,875
BEGIN DESCRIPTION:
BOX CREEK 53.0
END DESCRIPTION:
XS GIS Cut Line= 3
      3755099.62     10559060.19      3754299.61     10559360.19
      3753549.59      10560010.2
#Sta/Elev= 30
  4147.6  254.04  4223.3  244.99  4448.5  236.97  4956.6  234.75    4962  227.73
  5012.8  225.56  5015.5  225.06  5018.8  225.56  5066.1  225.78  5072.8  228.38
  5080.4  226.51    5087  233.39  5094.6  229.15  5107.9   237.6  5115.5  233.19
    5144  235.29  5207.6  230.41  5250.4   235.2  5328.3  232.47  5349.1  234.89
  5483.5  234.46  5555.2  236.59  5611.2  244.32    5654  242.38  5661.6  246.14
  5668.2  243.87  5682.5  251.21    5824  270.41  5993.9  283.13  5994.5  283.13
#Mann= 6 ,-1 , 0
  4147.6     .16       0  4448.5     .12       0  5012.8     .07       0
  5018.8     .12       0  5483.5     .05       0  5993.9     .16       0
Bank Sta=4956.6,5087
XS Rating Curve= 0 ,0
Exp/Cntr=0.3,0.1

Type RM Length L Ch R = 1 ,35370   ,259,259,259
BEGIN DESCRIPTION:
BOX CREEK 52.0
END DESCRIPTION:
XS GIS Cut Line= 3
      3755187.68     10558244.93       3753930.7      10559126.9
      3753494.44     10559964.79
#Sta/Elev= 30
  3725.2  272.95  3878.9   256.3  3899.9  257.83  4108.2  239.22  4183.2  238.82
  4596.2  231.83  4911.7  234.09  4932.7  232.06  4941.4  226.31  4947.5  230.11
  4956.2  226.31  4962.3  229.82  4968.9   223.5  4980.2  223.15    4983  222.65
  4986.2  223.15  5005.5  223.58  5012.8   229.1  5018.9  223.42  5027.6  231.05
  5033.7  230.09  5042.2  234.87  5249.9  238.12  5546.3  236.78  5581.4  232.31
  5672.5  236.61  5833.2  239.98  6012.2  256.41  6139.1  274.66  6205.4  278.46
#Mann= 6 ,-1 , 0
  3725.2     .16       0  4183.2     .12       0  4980.2     .07       0
  4986.2     .12       0  5672.5     .05       0  5833.2     .16       0
Bank Sta=4911.7,5042.2
XS Rating Curve= 0 ,0
Exp/Cntr=0.3,0.1

Type RM Length L Ch R = 1 ,35111   ,533,533,533
BEGIN DESCRIPTION:
BOX CREEK 51.0
END DESCRIPTION:
XS GIS Cut Line= 3
       3754649.6      10557960.2      3754099.61     10558760.19
      3753299.64     10558960.18
#Sta/Elev= 30
  4048.8  264.16  4051.3  264.16  4092.1  258.14  4121.6  257.83  4127.9  254.69
  4250.4  239.04    4337  234.46  4811.9     232  4961.4  234.44  4970.2  233.77
  4988.2  222.03    4991  221.53  4994.2  222.03  5012.2  223.47  5016.6  229.41
  5050.5  233.89  5225.8  233.41    5249  230.61  5277.3  233.48  5372.7  233.55
  5390.7  229.62  5413.9  234.05  5625.4  234.53  5661.3  234.27  5702.5  239.15
  5728.3  238.11  5743.7  239.48  5751.5  245.21  5792.7  253.83  5844.2  262.04
#Mann= 6 ,-1 , 0
  4048.8     .16       0  4051.3     .12       0  4988.2     .07       0
  4994.2     .12       0  5625.4     .08       0  5728.3     .05       0
Bank Sta=4961.4,5050.5
XS Rating Curve= 0 ,0
Exp/Cntr=0.3,0.1

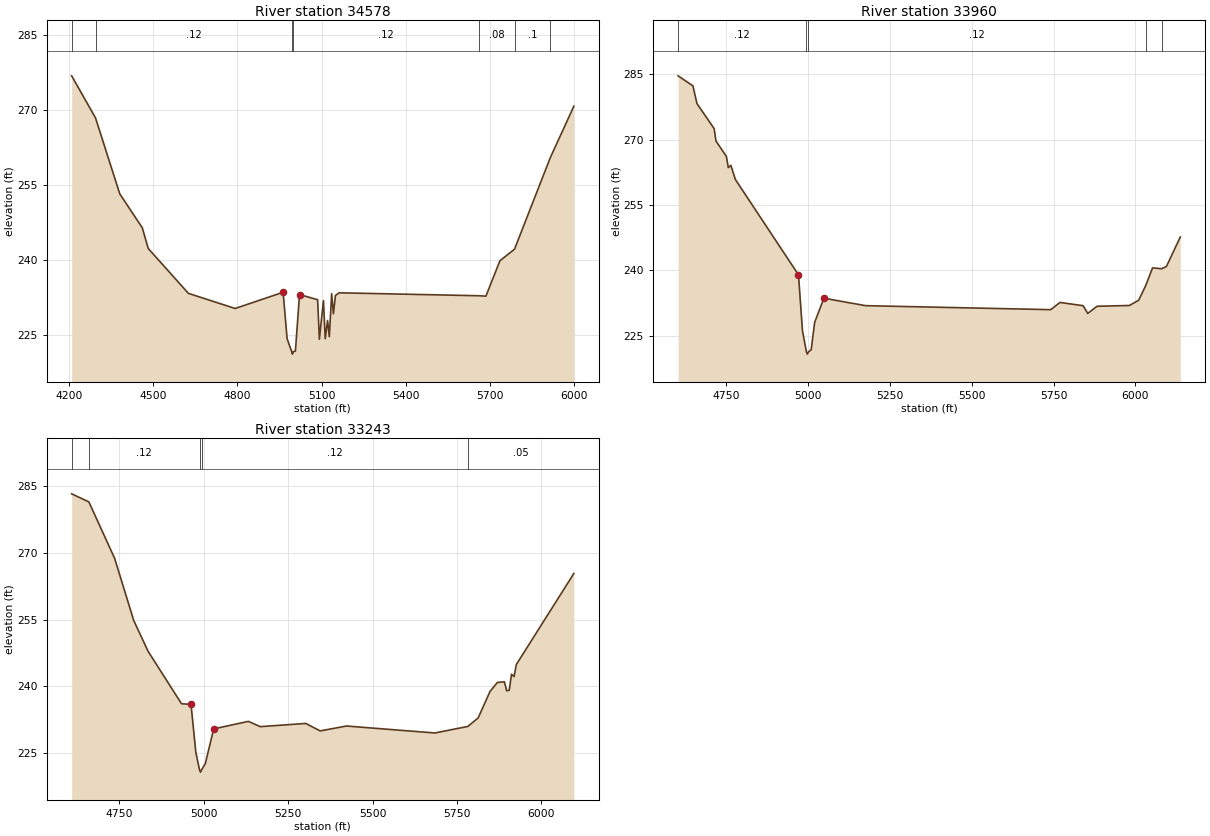
Type RM Length L Ch R = 1 ,34578   ,618,618,618
BEGIN DESCRIPTION:
BOX CREEK 50.0
END DESCRIPTION:
XS GIS Cut Line= 3
      3754599.57     10557860.21      3753949.61     10558310.19
      3753149.63     10558910.17
#Sta/Elev= 30
    4209   276.9  4294.2  268.46  4380.6  253.26    4461  246.46  4481.9  242.34
  4625.2  233.34  4792.1  230.31    4963  233.56  4977.2  224.26  4993.5  221.67
  4996.2  221.17  4999.5  221.67  5006.8  221.78  5021.4  233.09    5086  232.07
  5092.2  224.15  5106.8  231.91  5113.1  224.26  5121.4   227.9  5127.7  224.66
    5136  233.27  5142.2  229.25  5149.5  232.91  5163.1  233.45  5660.7  232.86
    5686  232.78    5736  239.87    5788  242.18  5915.2  260.46  5999.5  270.81
#Mann= 7 ,-1 , 0
    4209     .16       0  4294.2     .12       0  4993.5     .07       0
  4999.5     .12       0  5660.7     .08       0    5788      .1       0
  5915.2     .05       0
Bank Sta=4963,5021.4
XS Rating Curve= 0 ,0
Exp/Cntr=0.3,0.1

Type RM Length L Ch R = 1 ,33960   ,717,717,717
BEGIN DESCRIPTION:
BOX CREEK 49.0
END DESCRIPTION:
XS GIS Cut Line= 3
      3754249.59     10557560.23      3754049.61     10557910.19
      3753249.63     10558710.16
#Sta/Elev= 30
    4603  284.67  4648.3  282.36  4660.5  278.31  4713.1  272.55  4718.8  269.67
  4750.5  266.18  4756.3  263.59  4764.2  264.12  4777.9  260.87  4970.8  238.97
    4983  226.09  4995.1  221.26  4997.9  220.76  5001.1  221.26  5009.6  221.77
  5020.2  228.06  5048.5   233.6  5175.8  231.89  5741.5  230.97  5769.7  232.63
  5840.5  231.88  5854.6   230.1  5882.9  231.75  5981.9  231.93  6010.2  233.13
  6031.5  236.47  6052.6  240.56  6080.3  240.37    6095  240.89  6137.4  247.66
#Mann= 5 ,-1 , 0
    4603     .12       0  4995.1     .07       0  5001.1     .12       0
  6031.5     .05       0  6080.3     .08       0
Bank Sta=4970.8,5048.5
XS Rating Curve= 0 ,0
Exp/Cntr=0.3,0.1

Type RM Length L Ch R = 1 ,33243   ,533,533,533
BEGIN DESCRIPTION:
BOX CREEK 48.0
END DESCRIPTION:
XS GIS Cut Line= 3
      3753999.61     10557410.19      3753699.61     10557710.19
      3752999.59     10558510.21
#Sta/Elev= 30
  4608.9  283.33  4659.9  281.51  4736.2  268.79  4792.7  254.81  4835.2  247.86
  4934.2  236.04  4962.5  235.87  4976.6  225.11  4987.7  221.12  4990.5  220.62
  4993.7  221.12  5004.9  222.57  5029.6  230.36  5132.3  232.06  5167.5  230.87
  5302.2  231.59  5344.9  229.91  5422.8  231.01  5684.7  229.44  5782.5  230.92
  5812.9  232.84    5848  238.81  5869.8  240.83  5890.7  240.96  5897.3  238.94
  5904.9  239.08  5911.6  242.67  5919.2  242.15  5925.8  244.85  6096.2  265.38
#Mann= 5 ,-1 , 0
  4608.9     .16       0  4659.9     .12       0  4987.7     .07       0
  4993.7     .12       0  5782.5     .05       0
Bank Sta=4962.5,5029.6
XS Rating Curve= 0 ,0
Exp/Cntr=0.3,0.1