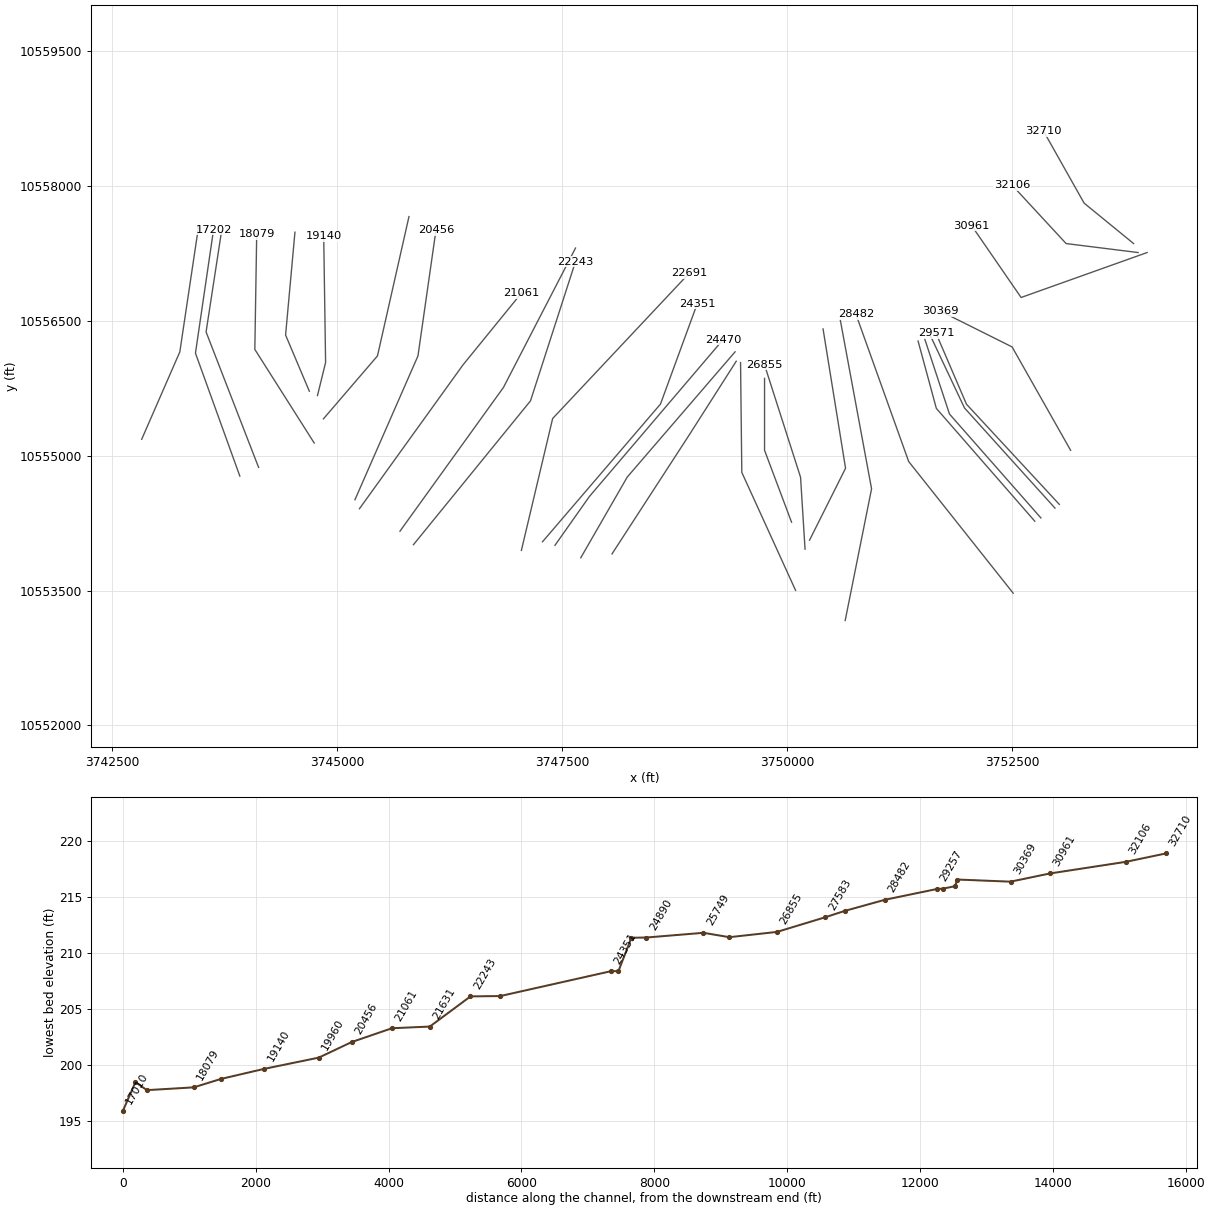
HEC-RAS study BOX CREEK.prj: BOX CREEK Base Level Engineering

--- BOX CREEK.g01 (geometry) --- (continued)

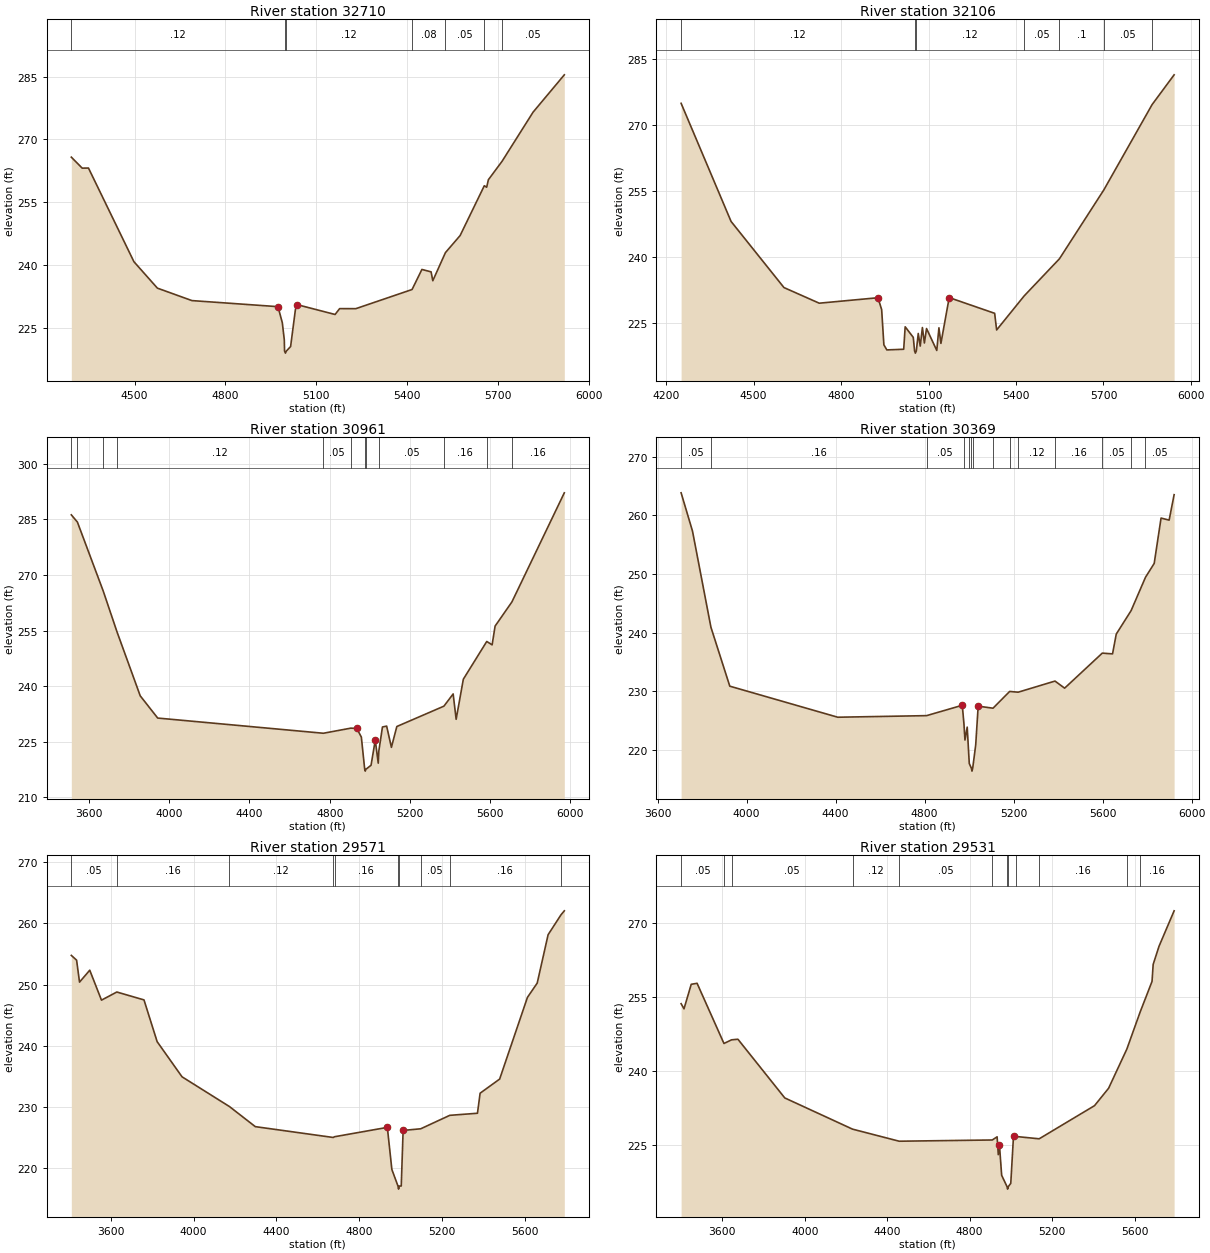
Type RM Length L Ch R = 1 ,32710   ,604,604,604
BEGIN DESCRIPTION:
BOX CREEK 47.0
END DESCRIPTION:
XS GIS Cut Line= 3
      3753849.64     10557360.17      3753299.61     10557810.19
      3752849.63     10558610.15
#Sta/Elev= 30
  4291.1  265.74    4327  263.11  4347.8  263.13  4497.9  240.74  4575.4  234.42
  4689.5  231.44  4973.8  229.99  4988.1  226.14  4994.6  222.08  4995.5  219.38
  4998.3  218.88  5001.5  219.38  5015.5  220.46  5031.4  229.33  5037.1  230.47
  5162.4  228.12  5177.4  229.52  5230.9  229.51  5416.7  234.09  5449.2  238.89
  5479.5  238.31  5485.2  236.19  5526.9  242.91  5575.4  246.99  5655.3   258.9
  5663.1  258.54  5668.8  260.34    5714  264.75  5816.4  276.49  5919.6  285.42
#Mann= 7 ,-1 , 0
  4291.1     .12       0  4995.5     .07       0  5001.5     .12       0
  5416.7     .08       0  5526.9     .05       0  5655.3      .1       0
    5714     .05       0
Bank Sta=4973.8,5037.1
XS Rating Curve= 0 ,0
Exp/Cntr=0.3,0.1

Type RM Length L Ch R = 1 ,32106   ,1145,1145,1145
BEGIN DESCRIPTION:
BOX CREEK 46.0
END DESCRIPTION:
XS GIS Cut Line= 3
      3753899.61     10557260.19      3753099.61     10557360.19
      3752499.62     10558010.17
#Sta/Elev= 30
  4251.4  274.86  4422.7  248.04  4604.1  233.02  4725.1  229.47  4926.6  230.71
  4939.2     228  4946.8  220.02  4956.9  218.86  5014.8  219.01  5019.8  224.11
  5047.6  221.71  5052.1  218.63  5054.9  218.13  5058.1  218.63  5064.7   222.6
  5071.5  219.73  5078.9  223.94  5085.7  220.44  5093.1  223.71  5128.2  218.74
  5135.6  223.88  5142.4  220.34  5170.8  230.74  5326.7  227.17  5333.5  223.39
  5427.9  231.12    5549  239.56  5701.1  255.19  5866.7  274.57  5942.2  281.33
#Mann= 7 ,-1 , 0
  4251.4     .12       0  5052.1     .07       0  5058.1     .12       0
  5427.9     .05       0    5549      .1       0  5701.1     .05       0
  5866.7      .1       0
Bank Sta=4926.6,5170.8
XS Rating Curve= 0 ,0
Exp/Cntr=0.3,0.1

Type RM Length L Ch R = 1 ,30961   ,592,592,592
BEGIN DESCRIPTION:
BOX CREEK 45.0
END DESCRIPTION:
XS GIS Cut Line= 3
       3753999.6     10557260.19      3752599.61     10556760.19
      3752049.62     10557560.17
#Sta/Elev= 30
    3512  286.25  3542.3   284.3    3671   265.7  3739.7  254.68  3855.5  237.41
  3942.6  231.41  4768.5  227.31  4905.3  228.69  4934.9   228.6  4957.7  226.28
  4974.4  217.59  4977.1  217.09  4980.4  217.59    5006  218.67    5027  225.45
  5041.9  219.24  5044.7  222.45  5062.9     229  5083.8  229.24  5107.5  223.51
  5134.6  229.13  5369.2  234.62  5415.3  237.92  5430.2  231.08  5466.1   241.9
  5582.8  252.08  5609.5  251.16  5624.4  256.23  5708.3  262.76  5969.4  292.19
#Mann= 12 ,-1 , 0
    3512     .16       0  3542.3     .12       0    3671     .16       0
  3739.7     .12       0  4768.5     .05       0  4905.3     .12       0
  4974.4     .07       0  4980.4     .12       0  5044.7     .05       0
  5369.2     .16       0  5582.8     .12       0  5708.3     .16       0
Bank Sta=4934.9,5027
XS Rating Curve= 0 ,0
Exp/Cntr=0.3,0.1

Type RM Length L Ch R = 1 ,30369   ,798,798,798
BEGIN DESCRIPTION:
BOX CREEK 44.0
END DESCRIPTION:
XS GIS Cut Line= 3
       3753149.6     10555060.21      3752499.61     10556210.19
      3751699.59      10556610.2
#Sta/Elev= 30
  3705.8  263.86    3757  257.32  3839.7  240.93  3924.5  230.86  4409.6  225.56
  4808.9  225.83  4969.3   227.6  4976.9  224.36  4981.3  221.67  4991.4  223.87
  5000.7  217.66  5010.1  216.86  5012.8  216.36  5016.1  216.86  5029.6  220.83
  5040.7  227.45  5107.4   227.1  5182.2  229.96  5220.2  229.83  5385.9  231.73
  5429.2  230.52  5598.4   236.5  5644.5  236.37  5661.2  239.75    5728  243.76
  5792.5  249.44  5831.7  251.81  5862.5  259.55  5898.8   259.2  5921.2  263.54
#Mann= 14 ,-1 , 0
  3705.8     .05       0  3839.7     .16       0  4808.9     .05       0
  4976.9     .16       0  5000.7     .05       0  5010.1     .07       0
  5016.1     .05       0  5107.4     .16       0  5182.2     .05       0
  5220.2     .12       0  5385.9     .16       0  5598.4     .05       0
    5728     .16       0  5792.5     .05       0
Bank Sta=4969.3,5040.7
XS Rating Curve= 0 ,0
Exp/Cntr=0.3,0.1

Type RM Length L Ch R = 1 ,29571   ,40,40,40
BEGIN DESCRIPTION:
Mapping XS 4dd33932
END DESCRIPTION:
XS GIS Cut Line= 3
      3753023.88     10554458.59      3751992.63     10555573.17
      3751653.18     10556365.77
#Sta/Elev= 30
  3409.2  254.78  3434.7     254  3448.9  250.41  3498.2  252.36  3554.9  247.46
  3628.9  248.79  3760.1   247.5  3823.7  240.67  3943.9  234.92  4172.7  230.06
  4297.7  226.77  4673.6     225  4680.5  225.12  4935.3  226.65  4957.1  219.77
  4986.7  217.05  4989.5  216.55  4992.7  217.05  5002.4  217.06  5011.5  226.15
  5096.6  226.42  5236.8  228.62  5370.5  228.96  5383.3  232.24  5477.6  234.55
  5611.8  247.91    5659  250.25  5711.6  258.16  5773.7  261.41  5789.9  262.07
#Mann= 10 ,-1 , 0
  3409.2     .05       0  3628.9     .16       0  4172.7     .12       0
  4673.6     .05       0  4680.5     .16       0  4986.7     .07       0
  4992.7     .16       0  5096.6     .05       0  5236.8     .16       0
  5773.7     .05       0
Bank Sta=4935.3,5011.5
XS Rating Curve= 0 ,0
Exp/Cntr=0.3,0.1

Type RM Length L Ch R = 1 ,29531   ,178,178,178
BEGIN DESCRIPTION:
BOX CREEK 43.0
END DESCRIPTION:
XS GIS Cut Line= 3
      3752975.83     10554416.84      3751970.63     10555531.41
      3751591.25     10556336.95
#Sta/Elev= 30
  3400.5  253.61  3414.5  252.57  3449.6  257.55    3478  257.75  3608.3  245.53
  3645.3  246.27  3676.1  246.39  3903.3  234.47  4232.1  228.13  4458.2  225.68
  4909.8  225.93  4933.2  226.57  4938.9  222.95  4944.4     225  4955.3  218.76
  4981.4  216.45  4984.2  215.95  4987.4  216.45  4999.5  217.12  5012.8  226.78
  5022.9  226.65  5137.3  226.17  5405.7   232.9  5474.1  236.44  5562.5  244.39
  5626.4  251.85  5684.7  258.14  5690.2  261.59  5718.5  265.26  5791.8  272.47
#Mann= 12 ,-1 , 0
  3400.5     .05       0  3608.3     .16       0  3645.3     .05       0
  4232.1     .12       0  4458.2     .05       0  4909.8     .16       0
  4981.4     .07       0  4987.4     .16       0  5022.9     .05       0
  5137.3     .16       0  5562.5     .05       0  5626.4     .16       0
Bank Sta=4944.4,5012.8
XS Rating Curve= 0 ,0
Exp/Cntr=0.3,0.1

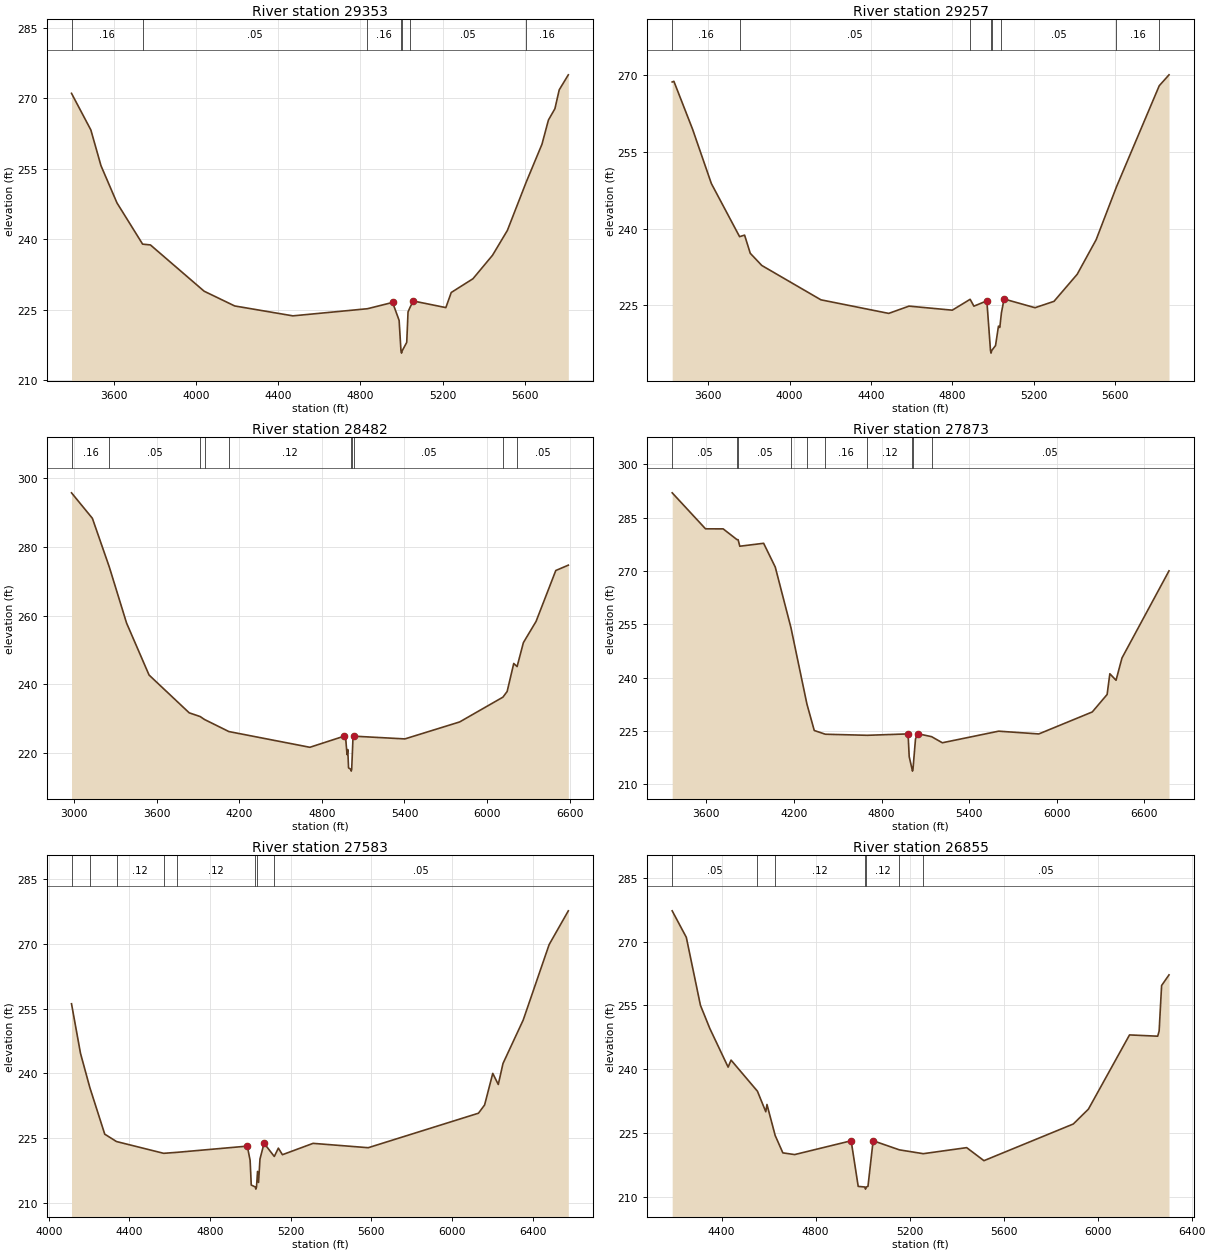
Type RM Length L Ch R = 1 ,29353   ,96,96,96
BEGIN DESCRIPTION:
BOX CREEK 42.0
END DESCRIPTION:
XS GIS Cut Line= 3
      3752819.59     10554307.46      3751803.97      10555463.7
      3751527.91     10556302.28
#Sta/Elev= 30
  3391.3  271.09  3485.6  263.29    3535  255.67  3612.8  247.76  3737.9  238.96
    3776  238.79  4037.9  228.93  4186.8  225.79  4470.5  223.68  4833.9   225.2
  4956.5  226.54  4988.3  222.71  4997.3  216.24    5000  215.74  5003.3  216.24
  5025.4  218.03  5031.8  224.53  5042.3  225.55  5057.1  226.85  5216.1  225.44
  5242.4  228.66  5348.4  231.59  5443.8   236.6  5516.1  241.89  5607.4  252.13
  5684.6  260.24  5716.1   265.4  5747.7  267.81  5768.8  271.84  5813.1  275.03
#Mann= 7 ,-1 , 0
  3391.3     .16       0  3737.9     .05       0  4833.9     .16       0
  4997.3     .07       0  5003.3     .16       0  5042.3     .05       0
  5607.4     .16       0
Bank Sta=4956.5,5057.1
XS Rating Curve= 0 ,0
Exp/Cntr=0.3,0.1

Type RM Length L Ch R = 1 ,29257   ,775,775,775
BEGIN DESCRIPTION:
Mapping XS 2fa8f825
END DESCRIPTION:
XS GIS Cut Line= 3
      3752751.88       10554271.      3751658.13      10555526.2
      3751455.14     10556275.72
#Sta/Elev= 30
  3423.3  268.59  3431.6  268.73  3523.7  259.36  3615.8  248.78  3754.5  238.42
  3779.1  238.72  3806.9  235.18  3863.6   232.8  4154.1   226.1  4487.3  223.45
    4587  224.87  4799.7  224.08  4887.5   226.2    4906  224.86  4969.6   225.9
  4987.5   216.2  4990.2   215.7  4993.5   216.2  5012.3  217.18  5026.6  220.96
  5033.2   220.7  5041.2  223.56  5054.1  226.26  5206.3  224.56  5299.5   225.8
  5413.5  231.08  5506.7  237.83  5606.4  248.13  5816.7  267.86  5864.7  269.99
#Mann= 8 ,-1 , 0
  3423.3     .16       0  3754.5     .05       0  4887.5     .16       0
  4987.5     .07       0  4993.5     .16       0  5041.2     .05       0
  5606.4     .16       0  5816.7     .05       0
Bank Sta=4969.6,5054.1
XS Rating Curve= 0 ,0
Exp/Cntr=0.3,0.1

Type RM Length L Ch R = 1 ,28482   ,609,609,609
BEGIN DESCRIPTION:
BOX CREEK 41.0
END DESCRIPTION:
XS GIS Cut Line= 3
       3752511.9     10553470.18      3751350.84     10554935.06
       3750764.9     10556573.53
#Sta/Elev= 30
    2981  295.77  3132.7  288.35  3255.4   274.2    3381  257.86  3544.5  242.72
  3836.1  231.72  3916.3  230.63  3947.3  229.78  4124.3  226.27  4712.7  221.69
  4962.5  224.94  4972.5  224.49  4982.6  219.57    4988  221.03  4993.7  215.69
  5010.4  215.25  5013.2  214.75  5016.4  215.25  5025.6  224.08  5035.6  224.92
  5402.9  224.13  5800.9  229.07  6115.4  236.29  6145.9  237.94  6193.8  246.09
  6218.2  245.19  6263.7  252.15    6356  258.34  6499.3  273.16  6590.3  274.71
#Mann= 10 ,-1 , 0
    2981     .16       0  3255.4     .05       0  3916.3     .07       0
  3947.3     .05       0  4124.3     .12       0  5010.4     .07       0
  5016.4     .12       0  5035.6     .05       0  6115.4     .08       0
  6218.2     .05       0
Bank Sta=4962.5,5035.6
XS Rating Curve= 0 ,0
Exp/Cntr=0.3,0.1

Type RM Length L Ch R = 1 ,27873   ,290,290,290
BEGIN DESCRIPTION:
BOX CREEK 40.0
END DESCRIPTION:
XS GIS Cut Line= 3
      3750645.54     10553166.37      3750938.52     10554631.24
      3750591.58     10556506.84
#Sta/Elev= 30
  3366.7  291.97    3595  281.85  3715.6  281.84  3809.6  278.84  3818.1  278.79
  3829.5  276.96  3992.7  277.79  4072.5  271.09  4179.8  254.06  4289.2  232.59
  4339.4  225.17  4415.1  224.12  4702.4  223.82  4981.6  224.21  4989.3  217.83
  5009.1  214.25  5011.8  213.75  5015.1  214.25  5032.4  222.77  5047.3  224.27
  5142.5  223.44  5216.2  221.72  5601.9  224.98  5876.6   224.2  6242.6  230.38
  6344.3  235.29    6363  241.12  6405.3  239.29    6446  245.55    6768  270.04
#Mann= 10 ,-1 , 0
  3366.7     .05       0  3809.6     .16       0  3818.1     .05       0
  4179.8     .16       0  4289.2     .12       0  4415.1     .16       0
  4702.4     .12       0  5009.1     .07       0  5015.1     .12       0
  5142.5     .05       0
Bank Sta=4981.6,5047.3
XS Rating Curve= 0 ,0
Exp/Cntr=0.3,0.1

Type RM Length L Ch R = 1 ,27583   ,728,728,728
BEGIN DESCRIPTION:
BOX CREEK 39.0
END DESCRIPTION:
XS GIS Cut Line= 3
      3750249.62     10554060.22      3750649.61     10554860.19
      3750399.61     10556410.16
#Sta/Elev= 30
  4112.8  256.16  4157.5  244.65  4203.8  236.73  4277.7  225.93    4336  224.22
  4569.9  221.49  4636.6  221.72  4984.8  223.16  4998.8  219.84  5004.4  214.14
  5024.5  213.69  5027.2  213.19  5030.5  213.69  5035.6  217.29  5040.6  214.74
  5047.7  220.17    5068  223.82  5118.7  220.76  5138.9  222.69  5159.1  221.17
  5311.1   223.8  5584.6  222.79  6131.5  230.79  6161.9   232.7  6202.4  240.02
  6229.8  237.45  6253.1  242.31  6353.4  252.39    6482  269.87  6577.2   277.7
#Mann= 8 ,-1 , 0
  4112.8     .05       0  4203.8     .16       0    4336     .12       0
  4569.9     .16       0  4636.6     .12       0  5024.5     .07       0
  5030.5     .12       0  5118.7     .05       0
Bank Sta=4984.8,5068
XS Rating Curve= 0 ,0
Exp/Cntr=0.3,0.1

Type RM Length L Ch R = 1 ,26855   ,717,717,717
BEGIN DESCRIPTION:
BOX CREEK 38.0
END DESCRIPTION:
XS GIS Cut Line= 3
      3750199.61     10553960.18      3750149.61     10554760.19
      3749749.61     10556010.18
#Sta/Elev= 30
  4189.6  277.21  4249.7  270.99  4309.8  255.04  4349.9  249.57  4427.6  240.52
  4440.1  242.17  4552.3  234.87  4587.9  230.04  4592.9  231.75  4627.8  224.48
  4660.5  220.39  4710.6  219.99  4951.1  223.23  4981.1  212.52  5009.5  212.38
  5012.2  211.88  5015.5  212.38  5022.7  212.53  5044.6  223.24  5156.3   221.1
    5258   220.2  5442.6  221.62  5516.1  218.56  5896.4  227.17  5960.7  230.66
  6135.6  248.08  6255.4  247.78  6261.6     249  6272.1  259.68  6303.6  262.17
#Mann= 7 ,-1 , 0
  4189.6     .05       0  4552.3     .16       0  4627.8     .12       0
  5009.5     .07       0  5015.5     .12       0  5156.3     .16       0
    5258     .05       0
Bank Sta=4951.1,5044.6
XS Rating Curve= 0 ,0
Exp/Cntr=0.3,0.1

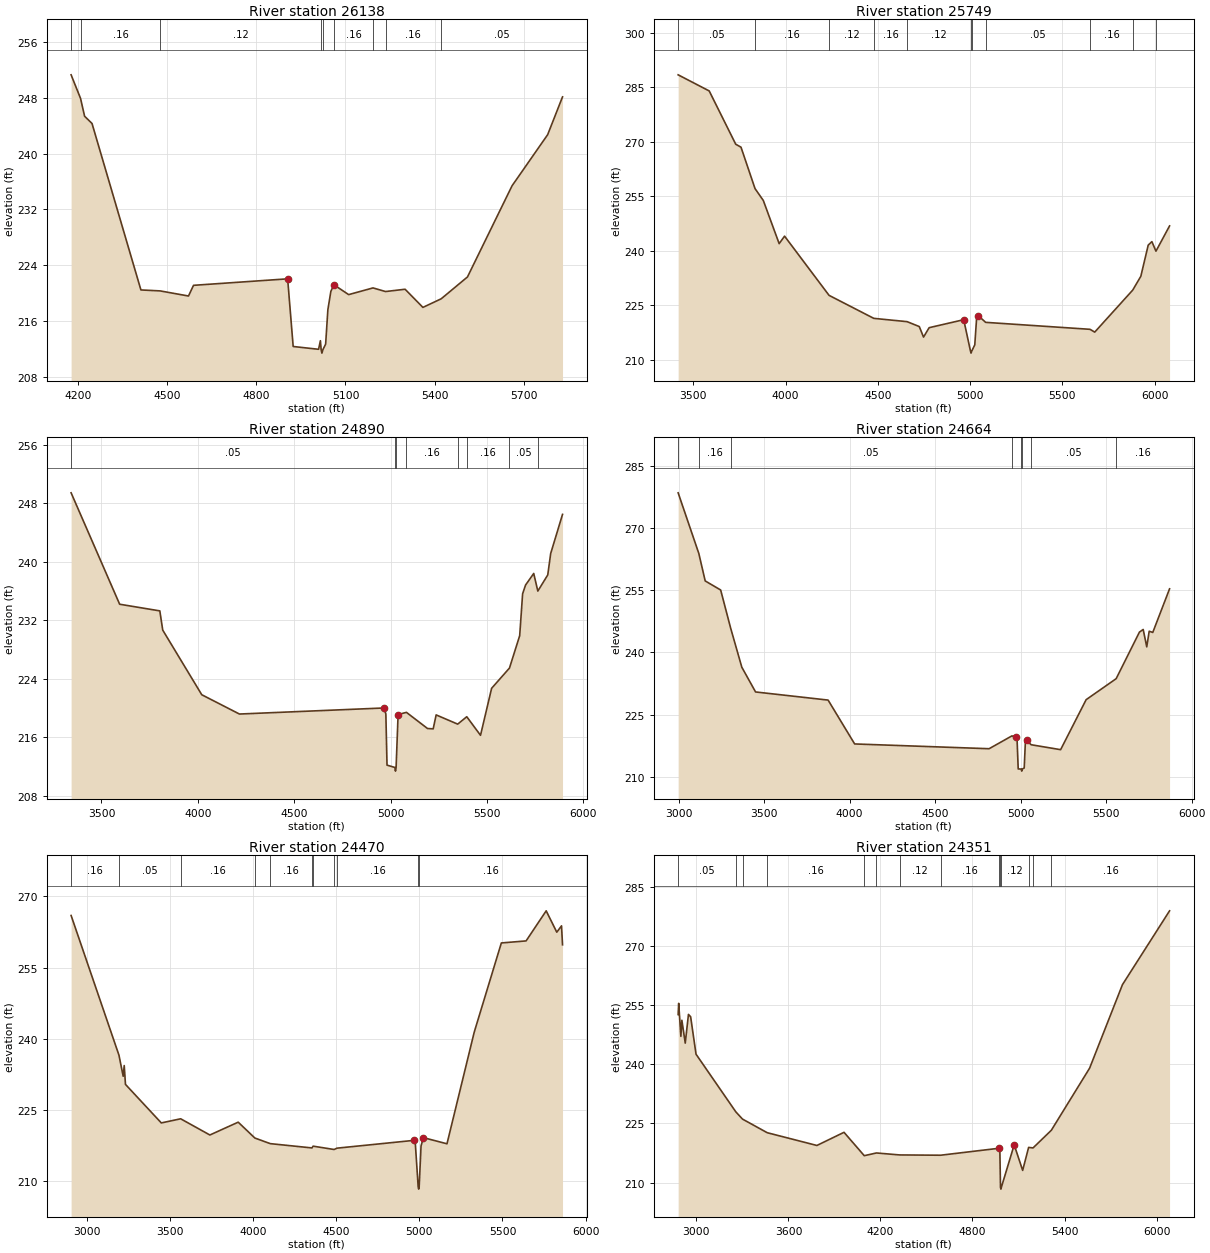
Type RM Length L Ch R = 1 ,26138   ,389,389,389
BEGIN DESCRIPTION:
BOX CREEK 37.0
END DESCRIPTION:
XS GIS Cut Line= 3
      3750049.62     10554260.15      3749749.61     10555060.19
      3749749.61     10555860.14
#Sta/Elev= 30
  4176.3  251.27    4208   247.9  4221.7  245.34  4246.7   244.3  4411.3  220.46
  4476.3  220.32  4571.5  219.59  4588.4  221.12  4905.3  222.05  4923.9  212.36
  5009.4  211.96  5015.6  213.19    5018  211.91  5020.7  211.41    5024  211.91
  5033.2   212.7  5040.7  217.62  5050.7  220.24  5060.7  221.19  5061.4  221.19
  5110.7  219.79  5192.7  220.75  5234.8  220.23  5300.7  220.56  5360.7  217.96
  5422.2  219.19  5510.7  222.32  5660.7  235.37  5780.7   242.7  5830.7  248.11
#Mann= 9 ,-1 , 0
  4176.3     .05       0    4208     .16       0  4476.3     .12       0
    5018     .07       0    5024     .12       0  5061.4     .16       0
  5192.7     .05       0  5234.8     .16       0  5422.2     .05       0
Bank Sta=4905.3,5060.7
XS Rating Curve= 0 ,0
Exp/Cntr=0.3,0.1

Type RM Length L Ch R = 1 ,25749   ,859,859,859
BEGIN DESCRIPTION:
BOX CREEK 36.0
END DESCRIPTION:
XS GIS Cut Line= 3
      3750094.24     10553501.87        3749497.      10554814.4
      3749483.12      10556035.9
#Sta/Elev= 30
  3417.3  288.48  3585.6  284.04  3729.4  269.36    3758  268.54    3834  257.13
  3878.8  253.87  3964.8  241.97  3994.1  244.03  4235.2  227.72  4477.7  221.38
  4658.3  220.47  4724.3  219.12  4747.3  216.22  4777.8  218.81  4965.1  221.01
  5002.1   212.3  5004.9   211.8  5008.1   212.3  5025.1  214.07  5035.1   221.5
  5045.1  222.07    5084  220.28  5649.9  218.36  5675.2  217.59  5881.3  229.17
  5925.2  232.98  5965.2  241.56  5985.2  242.52  6007.1  239.89  6080.9  246.85
#Mann= 11 ,-1 , 0
  3417.3     .05       0    3834     .16       0  4235.2     .12       0
  4477.7     .16       0  4658.3     .12       0  5002.1     .07       0
  5008.1     .12       0    5084     .05       0  5649.9     .16       0
  5881.3     .05       0  6007.1     .16       0
Bank Sta=4965.1,5045.1
XS Rating Curve= 0 ,0
Exp/Cntr=0.3,0.1

Type RM Length L Ch R = 1 ,24890   ,226,226,226
BEGIN DESCRIPTION:
Mapping XS 3a455345
END DESCRIPTION:
XS GIS Cut Line= 3
      3748055.33     10553907.52      3748910.37     10555226.97
      3749435.09      10556050.9
#Sta/Elev= 30
  3342.4  249.45  3594.2  234.21  3802.6   233.3  3817.7  230.67  4020.1  221.83
  4215.5  219.19  4965.9  220.02  4975.1  219.19  4981.1   212.2  5022.2  211.88
  5024.9  211.38  5028.2  211.88  5038.6  219.12  5081.8  219.42  5191.2  217.21
  5220.6  217.16  5235.9  219.07  5347.7  217.81  5394.8  218.82  5466.1  216.28
  5523.7  222.71  5616.3  225.48  5669.3  229.91  5684.5  235.64  5699.7  236.83
  5742.1  238.42  5763.4  236.01  5814.9  238.22  5830.1  241.15  5891.5   246.5
#Mann= 8 ,-1 , 0
  3342.4     .05       0  5022.2     .03       0  5028.2     .05       0
  5081.8     .16       0  5347.7     .05       0  5394.8     .16       0
  5616.3     .05       0  5763.4     .16       0
Bank Sta=4965.9,5038.6
XS Rating Curve= 0 ,0
Exp/Cntr=0.3,0.1

Type RM Length L Ch R = 1 ,24664   ,194,194,194
BEGIN DESCRIPTION:
BOX CREEK 35.0
END DESCRIPTION:
XS GIS Cut Line= 3
      3747708.13     10553864.15      3748224.61     10554762.56
      3749422.26     10556155.49
#Sta/Elev= 30
  2997.5  278.43  3118.4  263.81  3155.6   257.2  3246.1  255.01  3304.4  245.83
  3369.7  236.41  3450.2  230.44  3874.3  228.48  4029.5  217.91  4815.7  216.76
  4949.4  219.86  4971.5  219.48  4979.2  218.96  4985.8  211.89  5003.6  211.86
  5006.4  211.36  5009.6  211.86  5020.9  212.11  5028.6   219.2  5035.2  218.82
  5061.4  217.72  5233.8  216.53    5383  228.58  5558.6  233.64  5694.6  244.86
  5716.6   245.5  5737.4  241.31  5751.7  245.08  5772.6  244.78  5870.8  255.29
#Mann= 8 ,-1 , 0
  2997.5     .12       0  3118.4     .16       0  3304.4     .05       0
  4949.4     .08       0  5003.6     .07       0  5009.6     .08       0
  5061.4     .05       0  5558.6     .16       0
Bank Sta=4971.5,5035.2
XS Rating Curve= 0 ,0
Exp/Cntr=0.3,0.1

Type RM Length L Ch R = 1 ,24470   ,119,119,119
BEGIN DESCRIPTION:
BOX CREEK 34.0
END DESCRIPTION:
XS GIS Cut Line= 3
      3747421.64     10554002.98       3747803.6     10554545.54
      3749287.97     10556290.33
#Sta/Elev= 30
  2906.7  265.97  3194.3  236.58  3219.8  232.14    3226  234.39  3233.5  230.43
  3448.9  222.32  3565.4  223.19    3741  219.78  3911.2  222.48  4011.4  219.14
  4104.3  217.96  4354.6  217.06  4361.6  217.43  4487.7  216.73  4505.2  217.01
    4968  218.65  4975.4  218.34  4993.2  208.89    4996  208.39  4999.2  208.89
  5010.5  217.49  5024.8  219.22  5166.4  217.93  5330.1  241.41  5493.2  260.19
    5642  260.62  5762.8  266.95  5826.5  262.45    5855  263.79    5861  259.81
#Mann= 11 ,-1 , 0
  2906.7     .16       0  3194.3     .05       0  3565.4     .16       0
  4011.4     .05       0  4104.3     .16       0  4354.6     .12       0
  4361.6     .16       0  4487.7     .12       0  4505.2     .16       0
  4993.2     .07       0  4999.2     .16       0
Bank Sta=4968,5024.8
XS Rating Curve= 0 ,0
Exp/Cntr=0.3,0.1

Type RM Length L Ch R = 1 ,24351   ,1660,1660,1660
BEGIN DESCRIPTION:
Mapping XS b6551eb3
END DESCRIPTION:
XS GIS Cut Line= 3
      3747282.75     10554042.05      3748593.53     10555574.19
      3749001.53     10556689.69
#Sta/Elev= 30
  2880.9   252.6  2884.4  255.44  2898.7  247.07  2905.2  251.15  2927.2  245.36
  2948.1  252.63  2962.3  252.04  2997.5  242.55  3257.2  227.93  3300.6  226.11
  3461.8  222.66  3785.6  219.43  3962.4  222.76  4094.4  216.84    4174  217.53
  4325.1  217.03  4592.3  216.96  4972.9  218.72  4978.2  218.78  4982.6  208.87
  4985.3  208.37  4988.6  208.87  5071.9  219.59  5127.2  213.12    5166  218.94
  5194.9  218.81  5314.1  223.28  5563.8  239.02  5777.9  260.17    6085  278.87
#Mann= 14 ,-1 , 0
  2880.9     .05       0  3257.2     .12       0  3300.6     .05       0
  3461.8     .16       0  4094.4     .12       0    4174     .16       0
  4325.1     .12       0  4592.3     .16       0  4972.9     .12       0
  4982.6     .07       0  4988.6     .12       0    5166     .16       0
  5194.9     .12       0  5314.1     .16       0
Bank Sta=4972.9,5071.9
XS Rating Curve= 0 ,0
Exp/Cntr=0.3,0.1

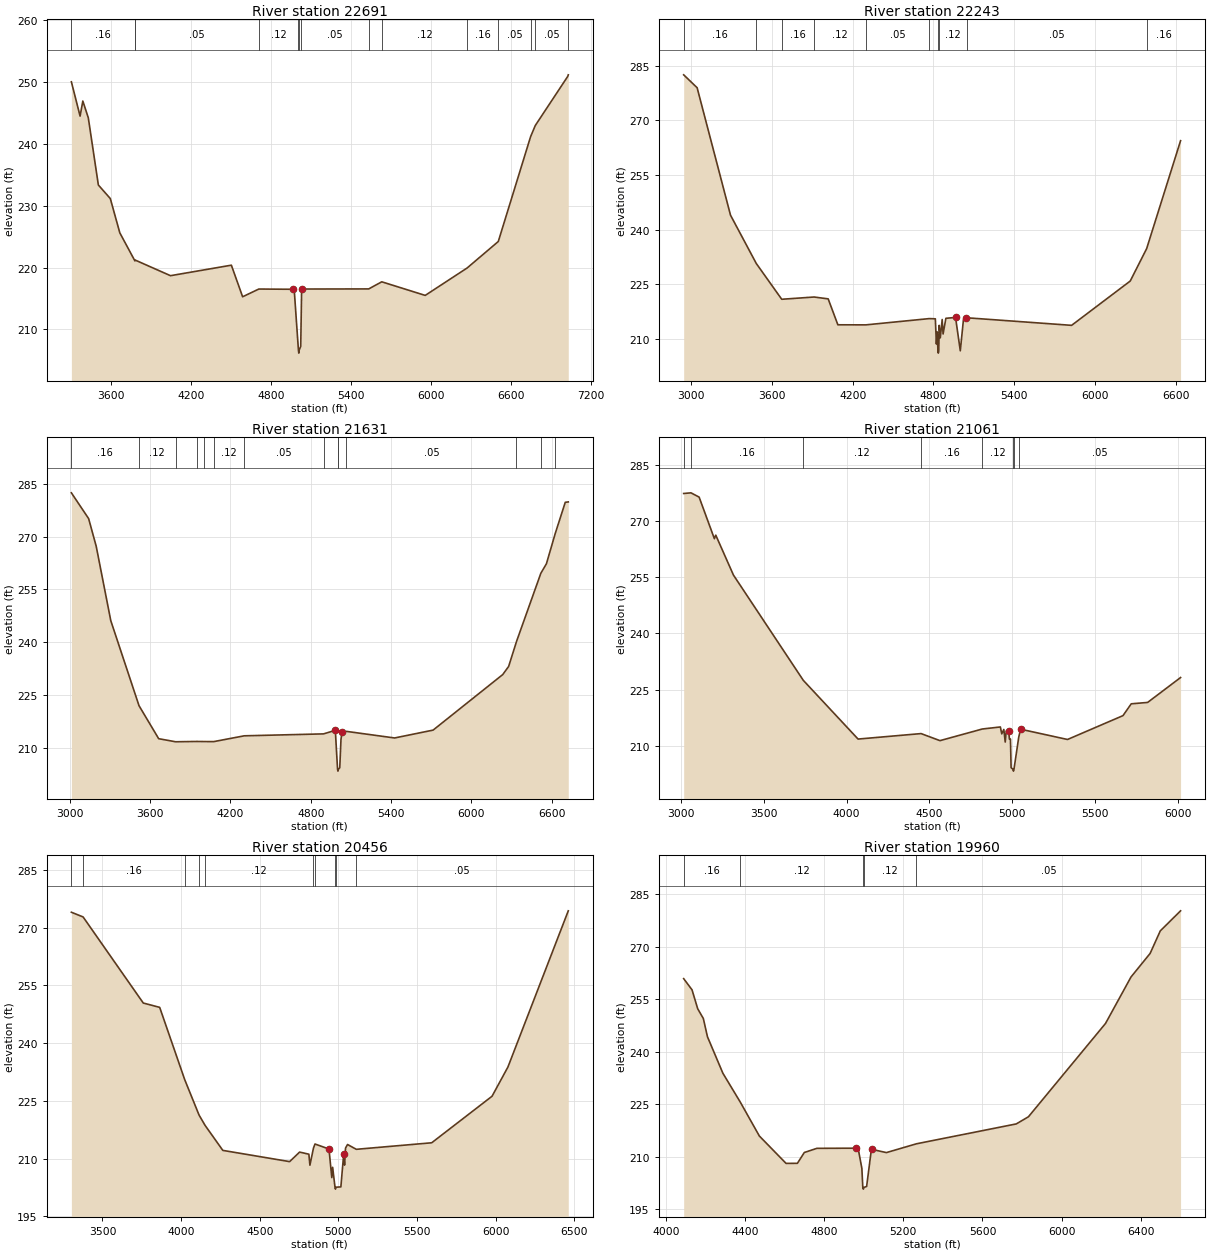
Type RM Length L Ch R = 1 ,22691   ,448,448,448
BEGIN DESCRIPTION:
BOX CREEK 33.0
END DESCRIPTION:
XS GIS Cut Line= 3
      3747048.39     10553946.58      3747395.61      10555413.6
      3748914.65     10557032.46
#Sta/Elev= 30
  3301.4  250.06  3366.7  244.51  3387.3  246.95  3428.4  244.23  3503.8  233.36
  3593.4  231.17  3664.8  225.62  3777.8  221.09  3779.5  221.22    4045  218.69
  4501.5  220.39    4586  215.28  4707.7  216.53  4965.1  216.49    4972  216.74
  5004.6  206.66  5007.4  206.16  5010.6  206.66  5021.8  207.25  5023.6  209.71
  5028.6  216.53    5532  216.55  5629.8   217.7  5955.7   215.5  6269.8  219.93
  6503.8  224.22  6746.2  241.18  6781.5  242.99  7025.3  250.95  7028.9  251.19
#Mann= 14 ,-1 , 0
  3301.4     .16       0  3777.8     .12       0  3779.5     .05       0
  4707.7     .12       0  5004.6     .07       0  5010.6     .12       0
  5023.6     .05       0    5532     .16       0  5629.8     .12       0
  6269.8     .16       0  6503.8     .05       0  6746.2     .16       0
  6781.5     .05       0  7025.3     .16       0
Bank Sta=4965.1,5028.6
XS Rating Curve= 0 ,0
Exp/Cntr=0.3,0.1

Type RM Length L Ch R = 1 ,22243   ,612,612,612
BEGIN DESCRIPTION:
BOX CREEK 32.0
END DESCRIPTION:
XS GIS Cut Line= 3
      3745849.58     10554010.15      3747149.61     10555610.19
      3747649.62     10557160.23
#Sta/Elev= 30
  2944.9  282.46  3044.8  278.92  3292.8  243.96  3483.9  230.73  3673.1   220.9
  3913.4  221.52  4018.1  221.01    4090   213.9    4298  213.88  4769.1   215.6
    4814  215.54  4821.9  208.62  4828.3  211.95  4833.3  206.63    4836  206.13
  4839.3  206.63  4842.7  213.75  4850.6  210.32  4864.8  215.35  4871.5  211.38
  4892.3  215.68  4964.1  215.92  4999.3  206.77  5022.5  215.25    5038  215.78
  5049.8  215.82  5826.1  213.75  6261.3   225.9  6383.3  234.79  6635.2  264.39
#Mann= 10 ,-1 , 0
  2944.9     .16       0  3483.9     .12       0  3673.1     .16       0
  3913.4     .12       0    4298     .05       0  4769.1     .12       0
  4833.3     .07       0  4839.3     .12       0  5049.8     .05       0
  6383.3     .16       0
Bank Sta=4964.1,5038
XS Rating Curve= 0 ,0
Exp/Cntr=0.3,0.1

Type RM Length L Ch R = 1 ,21631   ,570,570,570
BEGIN DESCRIPTION:
BOX CREEK 31.0
END DESCRIPTION:
XS GIS Cut Line= 3
      3745699.61     10554160.19      3746849.61     10555760.19
      3747649.62     10557310.21
#Sta/Elev= 30
  3010.7  282.42  3139.6  275.11  3196.1  267.29  3305.3  246.13  3516.2  222.02
  3663.4  212.64  3790.2  211.77    3951  211.86  4003.8  211.83  4075.5  211.82
  4303.2  213.46  4895.9  214.01  4983.9  215.02  5000.6  203.94  5003.4  203.44
  5006.6  203.94  5017.1  204.42  5026.1   212.4  5033.7  214.54    5067  214.72
  5426.8  212.85  5714.9  215.08  6235.3  230.84  6279.6  233.15  6338.1  240.19
  6520.3  259.59    6562  262.29  6628.3  270.93  6702.9  279.73  6725.4  279.84
#Mann= 14 ,-1 , 0
  3010.7     .16       0  3516.2     .12       0  3790.2     .05       0
    3951     .16       0  4003.8     .05       0  4075.5     .12       0
  4303.2     .05       0  4895.9     .12       0  5000.6     .07       0
  5006.6     .12       0    5067     .05       0  6338.1     .16       0
  6520.3     .12       0  6628.3     .16       0
Bank Sta=4983.9,5033.7
XS Rating Curve= 0 ,0
Exp/Cntr=0.3,0.1

Type RM Length L Ch R = 1 ,21061   ,605,605,605
BEGIN DESCRIPTION:
BOX CREEK 30.0
END DESCRIPTION:
XS GIS Cut Line= 3
      3745249.63     10554410.22      3746399.61     10556010.19
      3747049.58     10556810.15
#Sta/Elev= 30
  3015.7  277.33  3059.7  277.51    3109  276.37  3201.1  265.28  3209.6  266.22
  3316.4  255.57  3738.2   227.5    4069  211.84  4449.3   213.3  4563.7  211.42
  4819.1  214.52  4928.4  215.07  4936.8  213.23  4949.3   214.4  4957.8  211.05
    4964     214  4978.7  214.06    4983  211.84  4989.3  211.84  4993.3   204.2
  5004.6  203.79  5007.4  203.29  5010.6  203.79  5039.4  212.34  5050.5  214.47
    5334  211.73    5669  218.09  5718.8  221.24  5817.9  221.61  6016.8  228.25
#Mann= 8 ,-1 , 0
  3015.7     .05       0  3059.7     .16       0  3738.2     .12       0
  4449.3     .16       0  4819.1     .12       0  5004.6     .07       0
  5010.6     .12       0  5039.4     .05       0
Bank Sta=4978.7,5050.5
XS Rating Curve= 0 ,0
Exp/Cntr=0.3,0.1

Type RM Length L Ch R = 1 ,20456   ,496,496,496
BEGIN DESCRIPTION:
BOX CREEK 29.0
END DESCRIPTION:
XS GIS Cut Line= 3
      3745199.61     10554510.18      3745899.61     10556110.19
       3746099.6     10557510.14
#Sta/Elev= 30
  3302.1  274.04  3376.6  272.82  3759.4  250.44  3863.8  249.31    4023  230.52
  4114.3  221.31  4152.4  218.64  4265.4  212.13  4690.3  209.21  4753.8  211.69
  4812.7  211.14  4819.3  208.28  4841.9  212.73  4851.7  213.79  4940.6  212.49
  4958.5  205.06  4963.9  207.73  4978.9  202.56  4981.6  202.06  4984.9  202.56
  5016.2  202.64  5034.1  211.15  5039.6   208.3  5045.8  212.72  5058.6  213.66
  5114.4  212.41    5594  214.11  5977.9  226.21  6078.9  233.81  6462.7  274.41
#Mann= 10 ,-1 , 0
  3302.1     .05       0  3376.6     .16       0    4023     .12       0
  4114.3     .16       0  4152.4     .12       0  4841.9     .16       0
  4851.7     .12       0  4978.9     .07       0  4984.9     .12       0
  5114.4     .05       0
Bank Sta=4940.6,5034.1
XS Rating Curve= 0 ,0
Exp/Cntr=0.3,0.1

Type RM Length L Ch R = 1 ,19960   ,820,820,820
BEGIN DESCRIPTION:
BOX CREEK 28.0
END DESCRIPTION:
XS GIS Cut Line= 3
      3744849.61     10555410.19      3745449.61     10556110.19
      3745799.62     10557660.22
#Sta/Elev= 30
  4090.1  260.88  4132.3  257.68  4160.9  252.28  4189.4  249.48  4210.3  244.26
  4288.2  233.83  4376.3  225.55  4472.6  215.86  4607.6  208.03  4664.7  208.05
  4699.8  211.15  4763.4  212.34  4962.1  212.38  4969.8   212.9  4990.6   206.6
  4995.3  201.17  4998.1  200.67  5001.3  201.17  5014.6  201.43  5036.2  210.94
  5042.8  212.02  5114.6  211.12  5266.6  213.64  5770.7  219.32  5832.2  221.36
  6221.8  248.06  6350.6  261.35  6447.3   268.1  6498.6  274.54  6601.1  280.28
#Mann= 5 ,-1 , 0
  4090.1     .16       0  4376.3     .12       0  4995.3     .07       0
  5001.3     .12       0  5266.6     .05       0
Bank Sta=4962.1,5042.8
XS Rating Curve= 0 ,0
Exp/Cntr=0.3,0.1

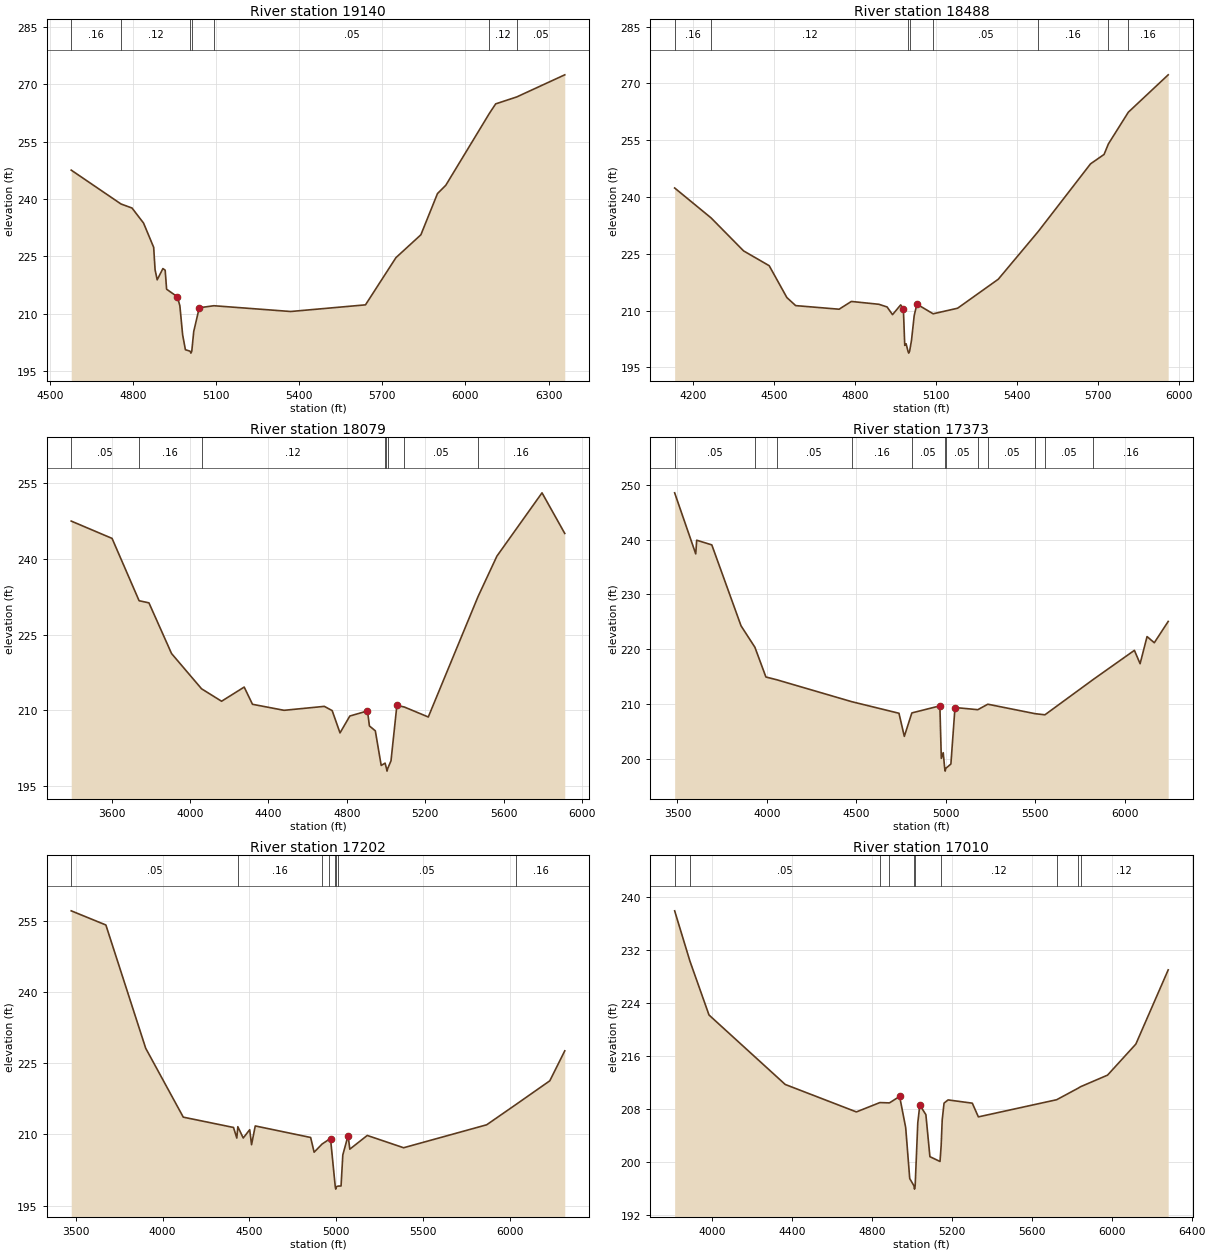
Type RM Length L Ch R = 1 ,19140   ,652,652,652
BEGIN DESCRIPTION:
BOX CREEK 27.0
END DESCRIPTION:
XS GIS Cut Line= 3
      3744783.05     10555668.76      3744873.33     10556036.86
       3744852.5      10557439.6
#Sta/Elev= 30
  4576.8  247.55  4756.5  238.69  4796.4  237.63    4838  233.69  4874.5  227.35
  4879.6  221.48  4887.2  218.85  4907.8  221.79    4916  221.37  4921.2  216.39
    4960  214.41  4969.1  212.05  4979.1  204.44  4989.1  200.56  5006.1  200.17
  5008.9  199.67  5012.1  200.17  5019.1  205.32  5039.1  211.54    5092  212.07
  5369.2  210.56  5639.2   212.3  5749.2  224.65  5839.2  230.63  5899.2  241.42
  5929.2  243.59  6086.7  262.41  6109.3  264.88  6185.1  266.69  6358.7  272.48
#Mann= 7 ,-1 , 0
  4576.8     .16       0  4756.5     .12       0  5006.1     .07       0
  5012.1     .12       0    5092     .05       0  6086.7     .12       0
  6185.1     .05       0
Bank Sta=4960,5039.1
XS Rating Curve= 0 ,0
Exp/Cntr=0.3,0.1

Type RM Length L Ch R = 1 ,18488   ,409,409,409
BEGIN DESCRIPTION:
BOX CREEK 26.0
END DESCRIPTION:
XS GIS Cut Line= 3
      3744692.79      10555717.4      3744428.89     10556342.42
      3744532.92     10557486.75
#Sta/Elev= 30
  4133.2  242.39  4268.2  234.48  4388.5  225.77  4483.3  221.86  4548.7  213.45
  4581.3  211.32  4742.1  210.37  4787.5  212.42  4889.7  211.67  4919.9  210.96
  4939.9  208.93  4970.1  211.51  4980.1  210.43  4985.2  200.81  4990.2  201.24
  4997.2  199.27  4999.9  198.77  5003.2  199.27  5010.2  202.15  5020.3  208.75
  5030.3  211.71  5090.2  209.16  5180.9  210.63  5331.5  218.29  5479.5   230.9
    5673  248.76  5723.2  251.25  5739.4  254.05  5813.1  262.41  5960.7  272.28
#Mann= 8 ,-1 , 0
  4133.2     .16       0  4268.2     .12       0  4997.2     .07       0
  5003.2     .12       0  5090.2     .05       0  5479.5     .16       0
  5739.4     .12       0  5813.1     .16       0
Bank Sta=4980.1,5030.3
XS Rating Curve= 0 ,0
Exp/Cntr=0.3,0.1

Type RM Length L Ch R = 1 ,18079   ,706,706,706
BEGIN DESCRIPTION:
Mapping XS 278735a5
END DESCRIPTION:
XS GIS Cut Line= 3
      3744747.02     10555140.75      3744087.28     10556182.45
      3744108.09     10557466.14
#Sta/Elev= 30
  3394.4   247.4  3602.7  243.98  3740.6  231.67  3790.8  231.25  3906.1  221.24
  4059.1  214.28  4161.2  211.82  4276.5  214.62  4318.8  211.22  4479.9  210.03
  4685.2  210.81  4725.2  209.97  4765.2  205.57  4815.2   208.9  4905.2  209.91
  4915.2  206.94  4945.2  205.98  4975.2  199.14  4995.1   199.6  5002.2  198.52
    5005  198.02  5008.2  198.52  5025.2  200.06  5055.2  211.01  5093.2  210.68
  5215.3  208.71  5468.7  232.46  5565.3  240.48  5795.3  252.98  5911.3  244.96
#Mann= 8 ,-1 , 0
  3394.4     .05       0  3740.6     .16       0  4059.1     .12       0
  4995.1     .16       0  5002.2     .07       0  5008.2     .16       0
  5093.2     .05       0  5468.7     .16       0
Bank Sta=4905.2,5055.2
XS Rating Curve= 0 ,0
Exp/Cntr=0.3,0.1

Type RM Length L Ch R = 1 ,17373   ,171,171,171
BEGIN DESCRIPTION:
Mapping XS 61e769b1
END DESCRIPTION:
XS GIS Cut Line= 3
      3744128.96     10554869.91      3743545.61      10556376.9
      3743718.94     10557507.03
#Sta/Elev= 30
  3484.3  248.51  3602.2  237.38  3607.5  239.87    3692  239.02  3855.5  224.26
    3933  220.35  3994.5  214.93  4053.9  214.44  4474.4  210.43  4738.4  208.32
  4768.3  204.11  4810.3  208.38  4967.1  209.67  4975.1  200.09  4985.8  201.13
  4994.1  198.27  4996.8  197.77  5000.1  198.27  5028.7  199.07  5051.6  209.37
  5179.1  208.97  5235.2  209.97  5500.2  208.24  5554.5  208.04  5824.9  214.49
  6054.6  219.79  6086.5  217.36  6125.4   222.3  6165.9  221.18  6243.6  225.06
#Mann= 12 ,-1 , 0
  3484.3     .05       0    3933     .16       0  4053.9     .05       0
  4474.4     .16       0  4810.3     .05       0  4994.1     .03       0
  5000.1     .05       0  5179.1     .07       0  5235.2     .05       0
  5500.2     .16       0  5554.5     .05       0  5824.9     .16       0
Bank Sta=4967.1,5051.6
XS Rating Curve= 0 ,0
Exp/Cntr=0.3,0.1

Type RM Length L Ch R = 1 ,17202   ,192,192,192
BEGIN DESCRIPTION:
BOX CREEK 25.0
END DESCRIPTION:
XS GIS Cut Line= 3
      3743920.63     10554772.69      3743427.56     10556140.79
       3743628.9     10557515.49
#Sta/Elev= 30
  3473.9  257.07  3673.6  254.09  3903.1  228.14  4119.6  213.64    4409  211.47
  4427.9  209.24  4433.9  211.63    4465  209.25  4502.3     211  4512.9  207.84
  4534.2  211.79  4853.4  209.36  4873.4  206.26  4918.9  207.97  4956.5  208.89
    4968  209.07  4995.3  198.99    4998  198.49  5001.3  198.99  5012.5  199.13
  5028.6  199.15  5038.7  205.68    5069  209.76  5079.1   206.9  5179.5  209.79
  5389.1   207.2  5867.5  212.03  6037.4  216.33  6231.3  221.29  6317.5   227.6
#Mann= 8 ,-1 , 0
  3473.9     .05       0  4433.9     .16       0  4918.9     .08       0
  4956.5     .16       0  4995.3     .07       0  5001.3     .16       0
  5012.5     .05       0  6037.4     .16       0
Bank Sta=4968,5069
XS Rating Curve= 0 ,0
Exp/Cntr=0.3,0.1

Type RM Length L Ch R = 1 ,17010   ,200,200,200
BEGIN DESCRIPTION:
BOX CREEK 24.0
END DESCRIPTION:
XS GIS Cut Line= 3
      3742830.33     10555182.45      3743253.95     10556154.68
      3743462.28     10557550.51
#Sta/Elev= 30
  3810.7  237.88  3887.1   230.3  3982.8  222.16  4364.5  211.68  4720.9  207.54
  4838.6  208.95  4886.4   208.9  4937.4  209.88  4967.8  205.17    4988  197.49
  5009.2  196.39    5012  195.89  5015.2  196.39  5028.4   205.9  5038.5  208.57
  5068.9  207.13  5089.1  200.79  5139.7  200.06  5145.3   202.4  5150.7  206.34
  5159.9  208.87  5180.1  209.35  5301.4  208.86  5331.8  206.79  5724.1  209.38
  5831.4  211.12  5843.4  211.34  5978.8  213.09  6120.4  217.77  6282.5  228.97
#Mann= 10 ,-1 , 0
  3810.7     .16       0  3887.1     .05       0  4838.6     .08       0
  4886.4     .05       0  5009.2     .03       0  5015.2     .05       0
  5145.3     .12       0  5724.1     .07       0  5831.4     .05       0
  5843.4     .12       0
Bank Sta=4937.4,5038.5
XS Rating Curve= 0 ,0
Exp/Cntr=0.3,0.1