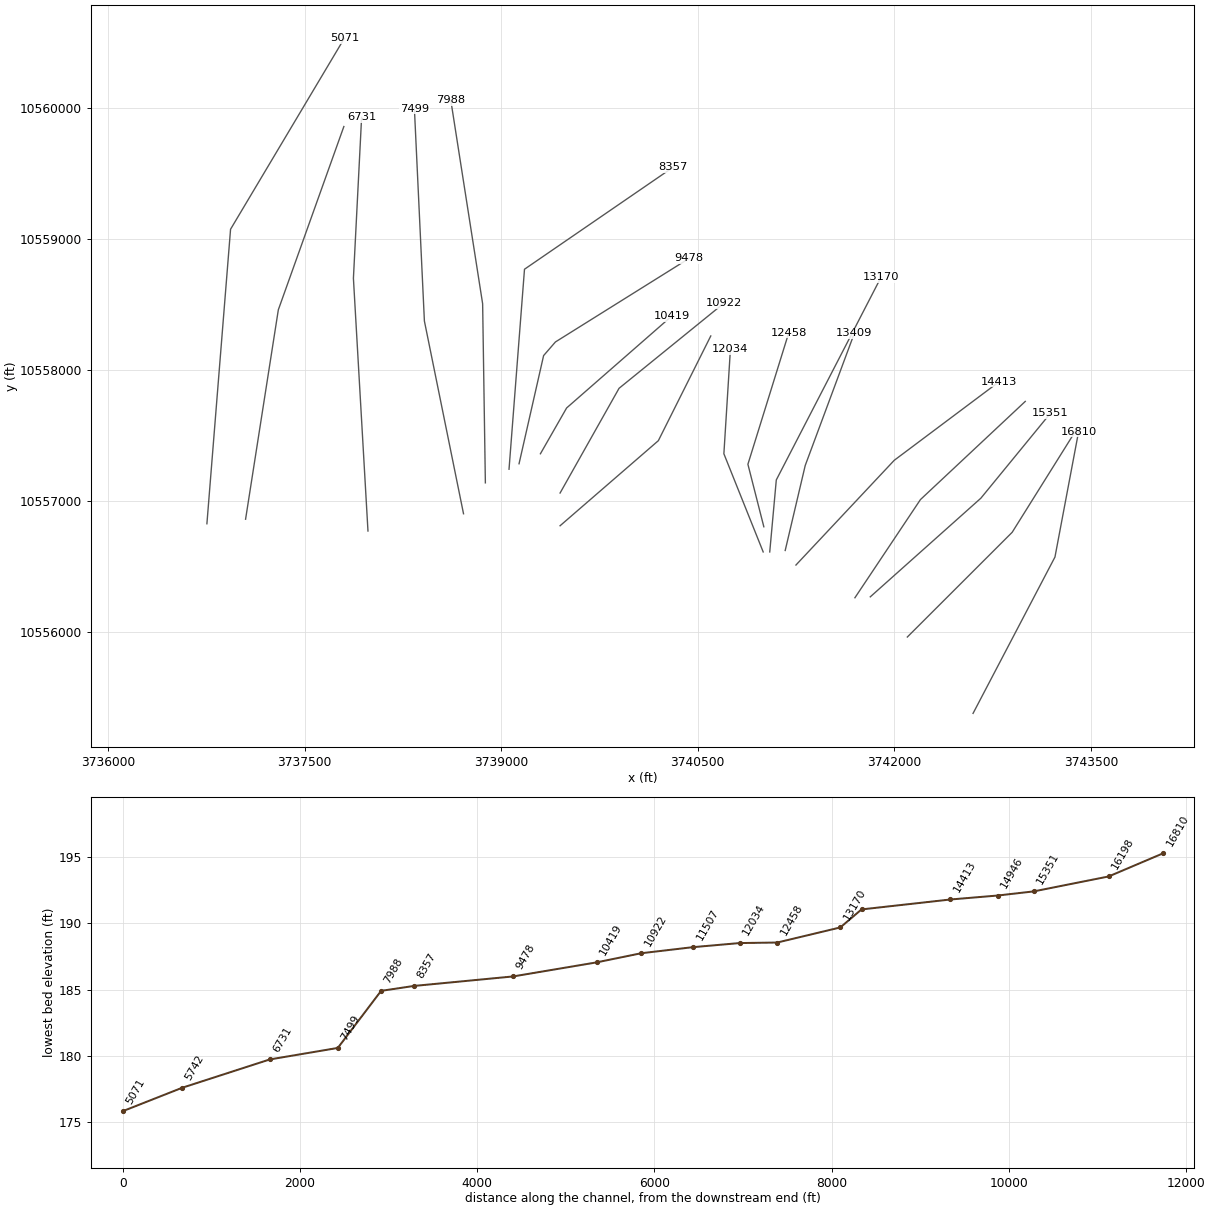
HEC-RAS study BOX CREEK.prj: BOX CREEK Base Level Engineering

--- BOX CREEK.g01 (geometry) --- (continued)

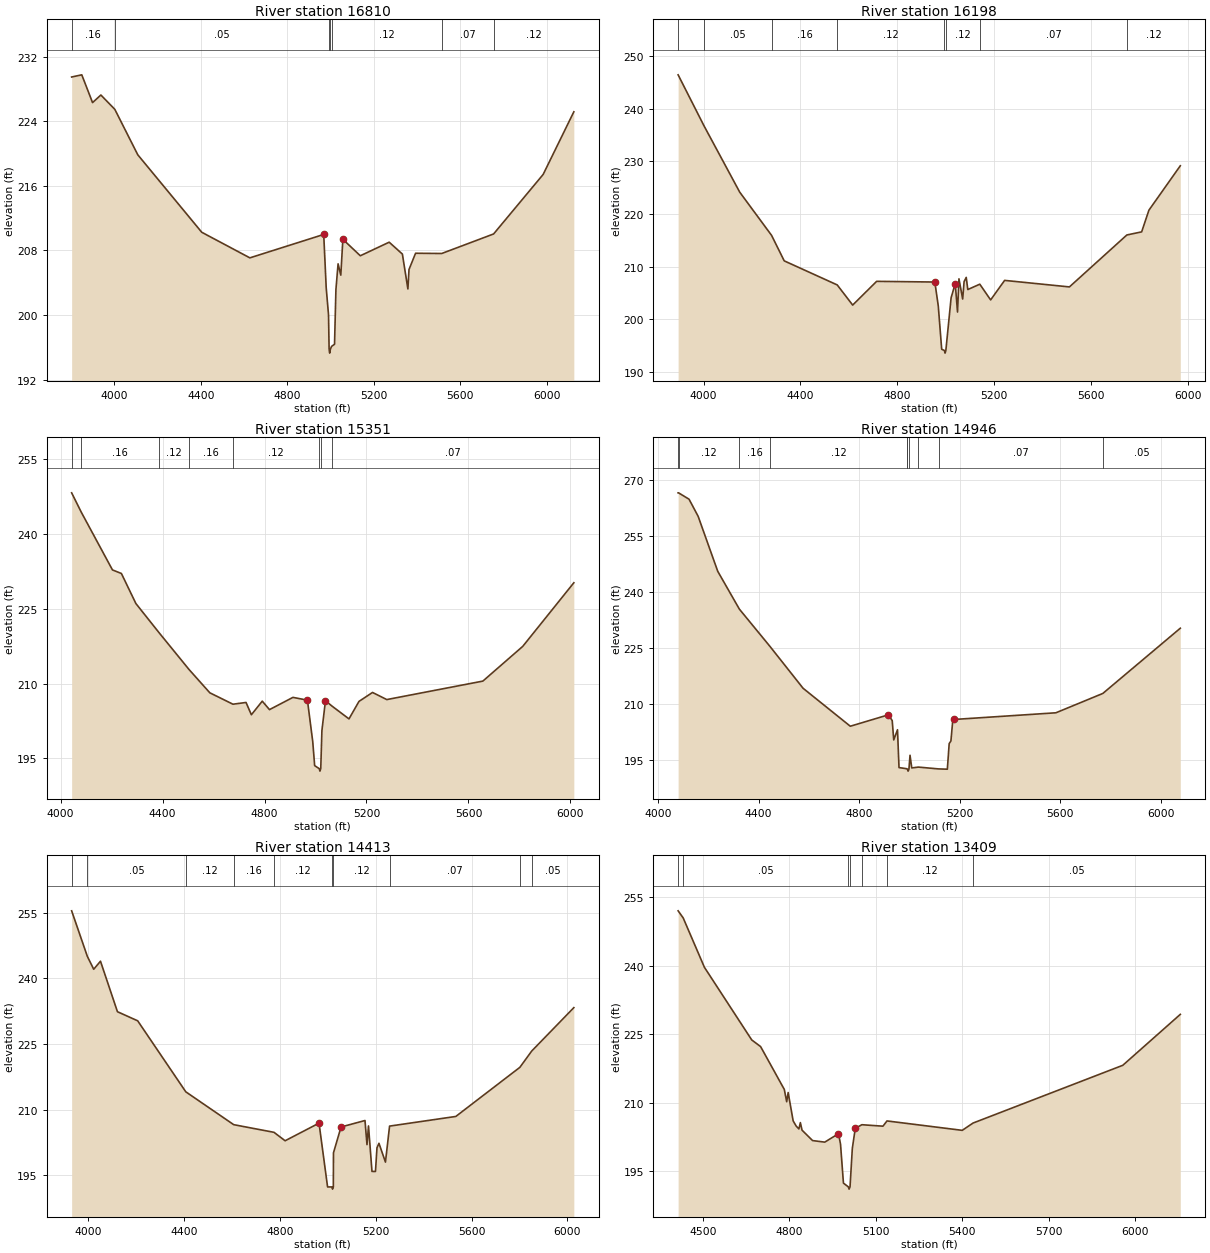
Type RM Length L Ch R = 1 ,16810   ,612,612,612
BEGIN DESCRIPTION:
Mapping XS 31294cce
END DESCRIPTION:
XS GIS Cut Line= 3
      3742601.16     10555376.89      3743226.17     10556571.34
      3743406.73     10557529.69
#Sta/Elev= 30
  3802.9  229.48  3849.8  229.75  3899.6  226.31  3938.1  227.25  4002.5  225.48
    4109  219.84  4404.8  210.25  4627.4  207.08  4969.1  209.98  4980.6  203.36
  4991.3  200.02    4994  195.78  4996.7  195.28    5000  195.78  5005.7  196.12
  5019.1  196.38  5025.5  203.14  5035.5  206.34  5048.1  204.94  5057.6  209.38
  5138.4  207.34  5271.9  209.02    5333  207.55  5358.5  203.23  5363.6  205.64
    5394  207.65    5515  207.62    5755  210.04  5984.2  217.41  6126.2  225.17
#Mann= 7 ,-1 , 0
  3802.9     .16       0  4002.5     .05       0    4994     .03       0
    5000     .05       0  5005.7     .12       0    5515     .07       0
    5755     .12       0
Bank Sta=4969.1,5057.6
XS Rating Curve= 0 ,0
Exp/Cntr=0.3,0.1

Type RM Length L Ch R = 1 ,16198   ,847,847,847
BEGIN DESCRIPTION:
BOX CREEK 23.0
END DESCRIPTION:
XS GIS Cut Line= 3
      3742099.63     10555960.21      3742899.61     10556760.19
      3743399.59     10557560.15
#Sta/Elev= 30
  3894.9  246.42  4002.1  236.71  4149.4  224.13  4281.1  215.91  4333.3  211.07
  4552.2   206.5  4616.1  202.67  4715.1  207.18  4955.5  207.05  4969.7  202.51
  4983.8  194.28    4995  194.04  4997.7  193.54    5001  194.04  5022.7  204.05
  5039.8  206.76  5049.2  201.35  5055.1  207.66  5070.5  203.82  5076.4  207.13
  5085.2  207.93  5091.7  205.62  5141.2  206.64    5186  203.65  5243.8  207.36
  5511.5  206.12  5748.8  215.99  5809.9  216.58  5839.9   220.7  5969.6  229.14
#Mann= 8 ,-1 , 0
  3894.9     .16       0  4002.1     .05       0  4281.1     .16       0
  4552.2     .12       0    4995     .07       0    5001     .12       0
  5141.2     .07       0  5748.8     .12       0
Bank Sta=4955.5,5039.8
XS Rating Curve= 0 ,0
Exp/Cntr=0.3,0.1

Type RM Length L Ch R = 1 ,15351   ,405,405,405
BEGIN DESCRIPTION:
BOX CREEK 22.0
END DESCRIPTION:
XS GIS Cut Line= 3
      3741816.83     10556267.14      3742660.59     10557020.62
      3743191.86     10557669.95
#Sta/Elev= 30
  4043.3   248.3  4080.7  244.45  4203.4  232.82  4238.5   232.1  4295.3  226.07
  4385.8  220.24  4503.5  212.84  4585.4  208.14  4676.1  205.85  4727.5   206.2
  4748.4  203.73  4791.1  206.46  4819.5  204.76  4911.5  207.22  4968.3  206.66
  4989.2  198.32  4996.7  193.51  5014.6  192.91  5017.4  192.41  5020.6  192.91
  5025.1  200.55  5039.1  206.55  5064.8  205.47  5131.3   202.9  5170.5  206.41
  5223.7  208.21  5279.7  206.78  5656.6  210.49    5813  217.46  6013.5  230.24
#Mann= 8 ,-1 , 0
  4043.3     .12       0  4080.7     .16       0  4385.8     .12       0
  4503.5     .16       0  4676.1     .12       0  5014.6     .07       0
  5020.6     .12       0  5064.8     .07       0
Bank Sta=4968.3,5039.1
XS Rating Curve= 0 ,0
Exp/Cntr=0.3,0.1

Type RM Length L Ch R = 1 ,14946   ,533,533,533
BEGIN DESCRIPTION:
BOX CREEK 21.0
END DESCRIPTION:
XS GIS Cut Line= 3
      3741699.63     10556260.22      3742199.61     10557010.19
      3742999.58     10557760.16
#Sta/Elev= 30
  4079.9  266.67  4081.6  266.67  4123.4  264.96  4159.5  260.39  4237.6  245.64
  4323.6  235.51  4444.6  225.58  4577.1   214.3  4764.9  204.13  4916.7  207.19
  4931.7  205.64  4937.7  200.46  4952.7  203.19  4958.7  193.05  4990.7  192.73
  4992.2   192.6  4994.9   192.1  4998.2   192.6  5002.5  196.35  5009.4  192.96
  5035.8  193.18  5116.6  192.69    5151  192.62  5158.3  199.48  5165.2  200.17
  5172.5  205.62  5179.3  205.95  5582.8  207.73  5769.7  212.92  6077.8  230.39
#Mann= 10 ,-1 , 0
  4079.9     .16       0  4081.6     .12       0  4323.6     .16       0
  4444.6     .12       0  4990.7     .07       0  4992.2     .07       0
  4998.2     .07       0  5035.8     .12       0  5116.6     .07       0
  5769.7     .05       0
Bank Sta=4916.7,5179.3
XS Rating Curve= 0 ,0
Exp/Cntr=0.3,0.1

Type RM Length L Ch R = 1 ,14413   ,1004,1004,1004
BEGIN DESCRIPTION:
BOX CREEK 20.0
END DESCRIPTION:
XS GIS Cut Line= 3
      3741249.62      10556510.2      3741999.61     10557310.19
      3742799.63     10557910.21
#Sta/Elev= 30
  3929.9  255.44  3995.4  245.03    4022  242.08  4050.3  243.92  4121.1  232.37
  4205.6  230.29  4406.5  214.05  4606.5  206.54  4774.7  204.79  4821.1  202.86
  4962.7  206.89  4998.4   192.3  5016.4   192.3  5019.1   191.8  5022.4   192.3
    5023  200.11  5054.6  206.01  5154.6  207.49  5162.9  201.97  5169.2  206.25
  5183.8  195.85  5198.3  195.84  5204.6  201.24  5212.9  202.28    5240  197.98
  5257.2  206.21  5533.8  208.42  5801.2  219.65  5850.7  223.38  6026.5   233.3
#Mann= 10 ,-1 , 0
  3929.9     .16       0  3995.4     .05       0  4406.5     .12       0
  4606.5     .16       0  4774.7     .12       0  5016.4     .07       0
  5022.4     .12       0  5257.2     .07       0  5801.2     .12       0
  5850.7     .05       0
Bank Sta=4962.7,5054.6
XS Rating Curve= 0 ,0
Exp/Cntr=0.3,0.1

Type RM Length L Ch R = 1 ,13409   ,239,239,239
BEGIN DESCRIPTION:
BOX CREEK 19.0
END DESCRIPTION:
XS GIS Cut Line= 3
      3741167.54     10556621.32      3741320.32     10557270.62
      3741694.97     10558280.11
#Sta/Elev= 30
  4413.6  251.98  4431.2  250.43  4504.9  239.62  4669.3  223.71  4700.1  222.25
  4782.3  212.88  4790.6  210.18  4795.7   212.2  4813.1  205.99  4823.4  204.87
    4833  204.23  4838.1  205.61  4843.9  203.96  4880.5  201.68  4922.8  201.34
  4970.4  203.18  4977.5  200.93  4987.7  192.36  5004.6  191.55  5007.3  191.05
  5010.6  191.55  5018.5  199.95  5028.8  204.38  5051.8  205.15  5124.9  204.83
  5138.9  205.98  5400.2  203.92  5437.5  205.51  5957.7  218.16  6157.4  229.31
#Mann= 7 ,-1 , 0
  4413.6     .16       0  4431.2     .05       0  5004.6     .03       0
  5010.6     .05       0  5051.8     .16       0  5138.9     .12       0
  5437.5     .05       0
Bank Sta=4970.4,5028.8
XS Rating Curve= 0 ,0
Exp/Cntr=0.3,0.1

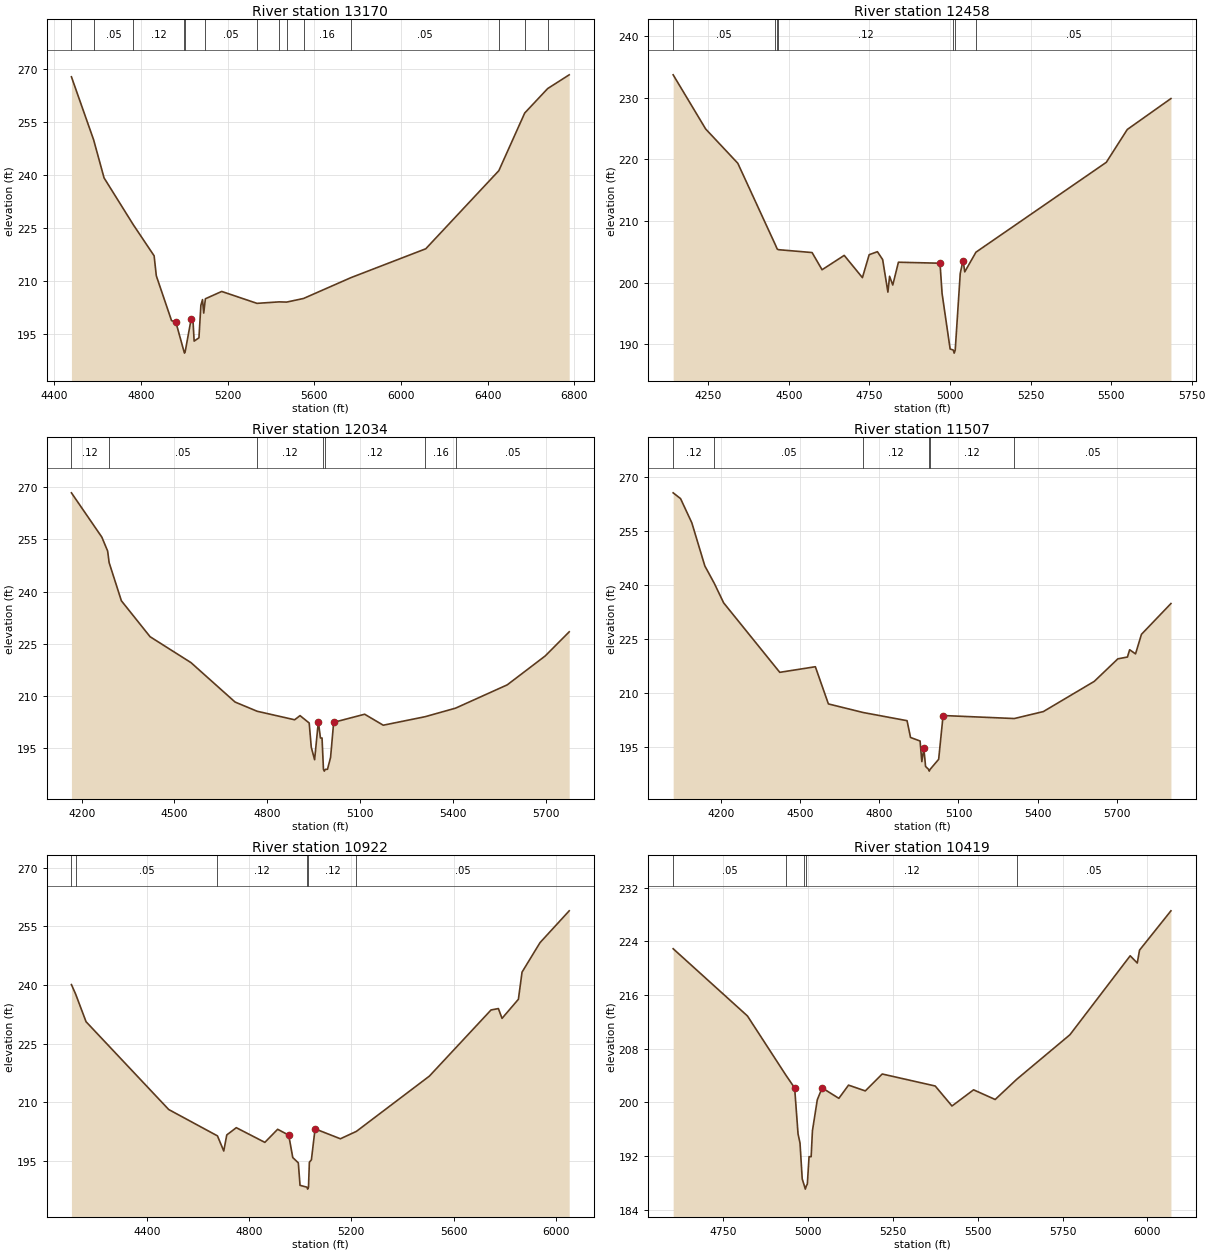
Type RM Length L Ch R = 1 ,13170   ,712,712,712
BEGIN DESCRIPTION:
BOX CREEK 18.0
END DESCRIPTION:
XS GIS Cut Line= 3
      3741049.61     10556610.22      3741099.61     10557160.19
       3741899.6     10558710.18
#Sta/Elev= 30
  4479.1  267.86  4581.5  250.04  4629.7  239.26  4764.6  226.01  4860.6  217.22
  4870.7  211.57    4941  198.88    4961  198.45  4998.2  190.19    5001  189.69
  5004.2  190.19  5031.3  199.29  5039.6  199.27  5045.2  193.09  5067.4  194.02
  5076.3  203.22  5083.9  204.83  5089.5  201.02  5097.1  205.07  5172.5  207.14
  5335.1  203.77  5437.3  204.19  5472.2  204.13  5549.9  205.15  5768.5  211.04
  6113.9  219.21  6450.9   241.3  6570.4  257.62  6676.2  264.53  6775.6  268.42
#Mann= 14 ,-1 , 0
  4479.1     .16       0  4581.5     .05       0  4764.6     .12       0
  4998.2     .07       0  5004.2     .12       0  5097.1     .05       0
  5335.1     .12       0  5437.3     .16       0  5472.2     .12       0
  5549.9     .16       0  5768.5     .05       0  6450.9     .12       0
  6570.4     .07       0  6676.2     .12       0
Bank Sta=4961,5031.3
XS Rating Curve= 0 ,0
Exp/Cntr=0.3,0.1

Type RM Length L Ch R = 1 ,12458   ,424,424,424
BEGIN DESCRIPTION:
BOX CREEK 17.0
END DESCRIPTION:
XS GIS Cut Line= 3
       3741004.5      10556802.4      3740882.96     10557279.88
      3741194.77      10558284.6
#Sta/Elev= 30
    4141  233.71  4241.9  224.92  4341.6  219.36  4457.7  206.18  4463.7  205.46
  4467.2  205.34  4572.1  204.87  4603.1  202.08  4671.8  204.41  4728.3   200.8
  4749.2  204.52  4774.8  205.01  4791.1  203.73  4807.4  198.45  4812.6  201.02
  4822.5   199.6    4840   203.3  4969.1  203.14  4975.5  198.23  5000.5  189.22
  5010.3  189.05  5013.1  188.55  5016.3  189.05  5031.9  201.51  5040.6  203.58
  5045.9  201.74  5080.6  204.93  5485.1  219.51  5550.2  224.84  5685.7  229.86
#Mann= 7 ,-1 , 0
    4141     .05       0  4457.7     .12       0  4463.7     .05       0
  4467.2     .12       0  5010.3     .07       0  5016.3     .12       0
  5080.6     .05       0
Bank Sta=4969.1,5040.6
XS Rating Curve= 0 ,0
Exp/Cntr=0.3,0.1

Type RM Length L Ch R = 1 ,12034   ,527,527,527
BEGIN DESCRIPTION:
BOX CREEK 16.0
END DESCRIPTION:
XS GIS Cut Line= 3
       3740999.6     10556610.22      3740699.61     10557360.19
      3740749.61     10558160.18
#Sta/Elev= 30
  4166.8  268.33    4265  255.64  4283.9  251.63  4288.7  248.31  4328.3  237.37
  4421.2  227.05  4553.2  219.64  4695.9  208.32  4767.3  205.68  4888.4  203.24
  4905.9  204.43  4935.5  202.31  4942.2  195.37    4953  191.78  4965.1  202.71
  4971.9  198.01    4977  198.01  4981.6  189.01  4984.3  188.51  4987.6  189.01
  4994.6  189.03  5004.6  192.43  5014.6   202.5  5114.8  204.83  5174.9  201.68
  5310.3  204.12  5408.9  206.58  5575.7  213.25  5698.5  221.54  5776.1  228.46
#Mann= 7 ,-1 , 0
  4166.8     .12       0  4288.7     .05       0  4767.3     .12       0
  4981.6     .07       0  4987.6     .12       0  5310.3     .16       0
  5408.9     .05       0
Bank Sta=4965.1,5014.6
XS Rating Curve= 0 ,0
Exp/Cntr=0.3,0.1

Type RM Length L Ch R = 1 ,11507   ,585,585,585
BEGIN DESCRIPTION:
BOX CREEK 15.0
END DESCRIPTION:
XS GIS Cut Line= 3
      3739449.61     10556810.19      3740199.61     10557460.19
      3740599.61     10558260.19
#Sta/Elev= 30
  4018.4  265.67  4046.4  264.06  4089.1  257.33  4138.5  245.31  4174.4  240.46
  4209.8  235.04  4422.5   215.7  4557.4  217.26  4606.8  206.91  4738.4  204.52
    4905  202.24  4918.2  197.57  4954.4  196.58    4961  190.85  4968.6  194.56
  4975.2   189.5  4986.5   188.7  4989.2   188.2  4992.5   188.7  5024.8  191.49
  5041.6  203.68  5311.5  202.84  5421.7  204.78  5614.6  213.18  5704.1  219.46
  5740.4  219.96  5748.8  221.99  5771.1  220.84  5793.5  226.28  5905.3  234.85
#Mann= 6 ,-1 , 0
  4018.4     .12       0  4174.4     .05       0  4738.4     .12       0
  4986.5     .07       0  4992.5     .12       0  5311.5     .05       0
Bank Sta=4968.6,5041.6
XS Rating Curve= 0 ,0
Exp/Cntr=0.3,0.1

Type RM Length L Ch R = 1 ,10922   ,503,503,503
BEGIN DESCRIPTION:
BOX CREEK 14.0
END DESCRIPTION:
XS GIS Cut Line= 3
      3739449.62     10557060.21      3739899.61     10557860.19
      3740699.59     10558510.17
#Sta/Elev= 30
  4104.3   240.1  4120.5  237.71  4161.6  230.59  4485.1  208.12    4676  201.37
  4700.6   197.5  4712.4  201.61  4749.7  203.47  4861.5  199.71  4911.6  203.06
  4954.9  201.56  4970.8  195.82  4992.5  194.46  4999.2  188.71  5026.3  188.24
  5029.1  187.74  5032.3  188.24  5035.8  194.61  5043.7  195.25  5058.1  203.17
  5157.2  200.63    5220  202.53  5505.6  216.67  5746.9   233.6  5775.7  233.96
    5790  231.45    5854  236.34  5868.3  243.29  5938.7  250.84  6052.9  258.98
#Mann= 6 ,-1 , 0
  4104.3     .16       0  4120.5     .05       0    4676     .12       0
  5026.3     .07       0  5032.3     .12       0    5220     .05       0
Bank Sta=4954.9,5058.1
XS Rating Curve= 0 ,0
Exp/Cntr=0.3,0.1

Type RM Length L Ch R = 1 ,10419   ,941,941,941
BEGIN DESCRIPTION:
BOX CREEK 13.0
END DESCRIPTION:
XS GIS Cut Line= 3
      3739299.61      10557360.2      3739499.61     10557710.19
       3740299.6     10558410.18
#Sta/Elev= 30
    4603  222.88  4821.8  212.86  4935.1  204.03  4960.8  202.13  4970.8  195.29
  4976.6  193.91  4983.1  188.58  4989.4  187.55  4992.2  187.05  4995.4  187.55
  4998.2  187.81  5003.2  191.88  5009.4  191.88  5013.2  195.75  5027.5  200.37
  5041.7  202.14    5091  200.58  5119.5  202.55  5168.9  201.69  5218.7  204.21
  5374.8  202.42  5424.2  199.44  5487.8  201.85  5551.4  200.41  5615.1  203.43
  5771.6  210.06  5949.1  221.83  5969.9  220.75  5976.6  222.67  6069.1  228.53
#Mann= 5 ,-1 , 0
    4603     .05       0  4935.1     .12       0  4989.4     .07       0
  4995.4     .12       0  5615.1     .05       0
Bank Sta=4960.8,5041.7
XS Rating Curve= 0 ,0
Exp/Cntr=0.3,0.1

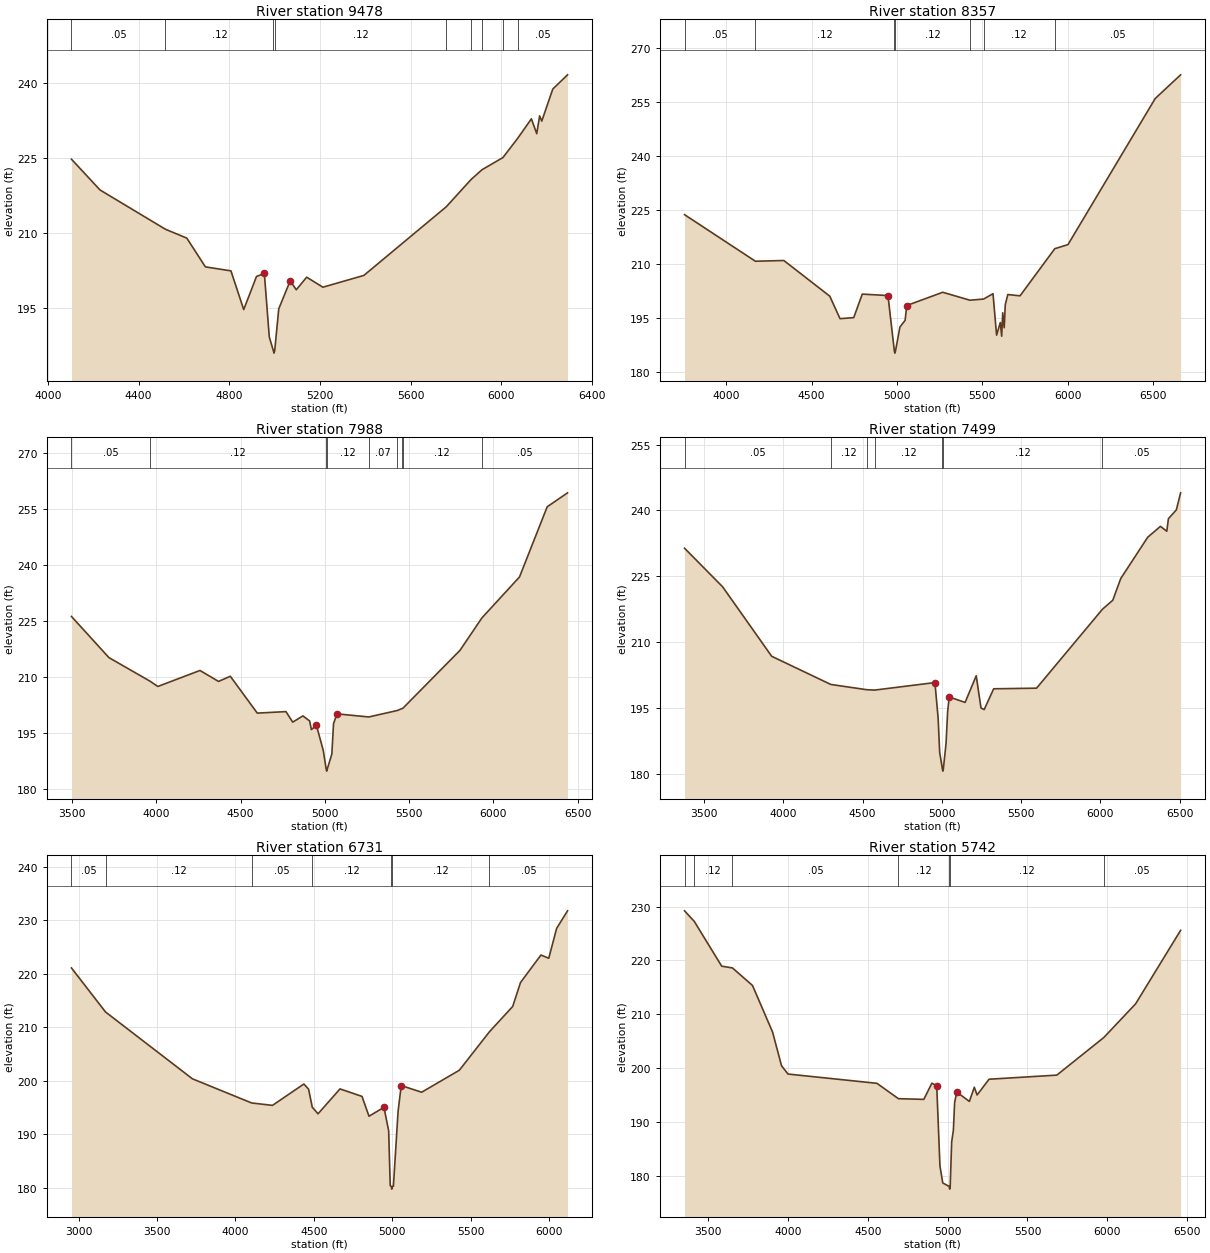
Type RM Length L Ch R = 1 ,9478    ,1121,1121,1121
BEGIN DESCRIPTION:
Mapping XS cf9119db
END DESCRIPTION:
XS GIS Cut Line= 4
      3739136.41      10557283.8      3739323.91     10558110.21
      3739414.19     10558214.38      3740434.82     10558853.14
#Sta/Elev= 30
  4103.6   224.7  4229.6  218.56  4518.5  210.71  4612.6  208.95  4694.6  203.21
  4807.4  202.41  4863.8  194.68  4920.2  201.29  4954.8   201.9  4976.7   189.2
  4994.6  186.49  4997.3  185.99  5000.6  186.49  5018.5  194.84  5068.8  200.41
  5095.8  198.64  5141.7  201.15  5213.2  199.15    5394   201.5  5757.9  215.21
    5867  220.64  5915.5   222.6  6007.9  225.03  6073.4   228.9  6133.4  232.76
    6157  229.79  6169.7  233.35  6179.2   232.3  6227.8   238.7  6292.9  241.54
#Mann= 9 ,-1 , 0
  4103.6     .05       0  4518.5     .12       0  4994.6     .07       0
  5000.6     .12       0  5757.9     .05       0    5867     .12       0
  5915.5     .05       0  6007.9     .16       0  6073.4     .05       0
Bank Sta=4954.8,5068.8
XS Rating Curve= 0 ,0
Exp/Cntr=0.3,0.1

Type RM Length L Ch R = 1 ,8357    ,369,369,369
BEGIN DESCRIPTION:
BOX CREEK 12.0
END DESCRIPTION:
XS GIS Cut Line= 3
      3739060.02     10557242.15      3739178.08     10558769.94
      3740309.98     10559547.69
#Sta/Elev= 30
  3755.9  223.74  4170.9   210.8  4337.7     211  4606.5   201.1  4666.7  194.84
  4746.9  195.14    4797  201.67  4947.5  201.26  4985.1  185.77  4987.9  185.27
  4991.1  185.77  5017.7  192.54  5047.8  194.37  5057.8   198.5  5268.4  202.18
  5427.7  199.97  5507.4  200.29  5562.7  201.78  5583.7  190.26  5605.6  193.78
  5613.5  189.98  5619.6  196.49  5628.4  192.32  5634.5  198.68  5649.4  201.55
  5721.1  201.19  5924.5  214.28  6001.9  215.42  6512.7     256  6661.6  262.59
#Mann= 7 ,-1 , 0
  3755.9     .05       0  4170.9     .12       0  4985.1     .07       0
  4991.1     .12       0  5427.7     .07       0  5507.4     .12       0
  5924.5     .05       0
Bank Sta=4947.5,5057.8
XS Rating Curve= 0 ,0
Exp/Cntr=0.3,0.1

Type RM Length L Ch R = 1 ,7988    ,489,489,489
BEGIN DESCRIPTION:
BOX CREEK 11.0
END DESCRIPTION:
XS GIS Cut Line= 3
      3738879.47     10557137.97      3738858.64     10558506.05
      3738615.57     10560061.64
#Sta/Elev= 30
  3496.7  226.25  3718.9  215.25  3962.4  208.95    4009  207.53    4259  211.81
    4369  208.88    4439  210.26    4599  200.41  4769.1  200.81  4809.1     198
  4869.6  199.66  4909.6  198.31  4919.7  196.01  4950.1  197.11  4990.6  190.38
  5007.8   185.4  5010.6   184.9  5013.8   185.4  5041.2  189.46  5051.3  197.58
  5071.6  200.21  5260.1  199.38  5430.1  201.11  5456.3  201.61  5462.3  201.69
  5801.6   217.2  5931.1  225.84  6154.5  236.81  6318.8  255.57  6439.4   259.3
#Mann= 9 ,-1 , 0
  3496.7     .05       0  3962.4     .12       0  5007.8     .07       0
  5013.8     .12       0  5260.1     .07       0  5430.1     .12       0
  5456.3     .07       0  5462.3     .12       0  5931.1     .05       0
Bank Sta=4950.1,5071.6
XS Rating Curve= 0 ,0
Exp/Cntr=0.3,0.1

Type RM Length L Ch R = 1 ,7499    ,768,768,768
BEGIN DESCRIPTION:
BOX CREEK 10.0
END DESCRIPTION:
XS GIS Cut Line= 3
      3738712.79     10556901.92      3738414.19      10558374.1
      3738337.89     10559997.15
#Sta/Elev= 30
    3378  231.38  3618.2  222.58  3927.3  206.76  4299.8  200.34  4527.1  199.14
  4575.7  199.05  4956.3  200.77  4976.4  192.71  4986.4  184.84  5003.4  181.09
  5006.1  180.59  5009.4  181.09  5026.4  186.91  5036.4  194.12  5046.4  197.49
  5146.5  196.24  5216.6  202.32  5246.7  194.98  5266.7  194.61  5326.7  199.35
    5597  199.49  6012.6  217.49  6077.6  219.53  6127.6  224.47  6297.8  233.89
  6377.9  236.36  6417.9  235.25    6428   238.1    6478  240.11    6505     244
#Mann= 7 ,-1 , 0
    3378     .05       0  4299.8     .12       0  4527.1     .07       0
  4575.7     .12       0  5003.4     .07       0  5009.4     .12       0
  6012.6     .05       0
Bank Sta=4956.3,5046.4
XS Rating Curve= 0 ,0
Exp/Cntr=0.3,0.1

Type RM Length L Ch R = 1 ,6731    ,989,989,989
BEGIN DESCRIPTION:
BOX CREEK 9.0
END DESCRIPTION:
XS GIS Cut Line= 3
      3737983.63     10556769.98      3737872.52     10558700.49
      3737935.03      10559929.7
#Sta/Elev= 30
  2953.7   221.1  3170.8  212.87  3725.2  200.36    4103  195.84    4236  195.39
  4436.4  199.39  4466.4  198.41  4489.8  195.05  4526.5  193.81  4666.7  198.47
    4807  197.07  4851.6  193.36  4947.2  195.03  4977.2  190.62  4987.2  180.36
  4994.2  180.22    4997  179.72  5000.2  180.22  5007.3  180.26  5037.3   194.3
  5057.3   199.1  5187.5  197.85  5427.8  201.96  5619.7  209.15  5768.2  213.89
  5818.3  218.38  5948.5  223.52  5998.5  222.92  6048.6   228.5  6118.2  231.79
#Mann= 7 ,-1 , 0
  2953.7     .05       0  3170.8     .12       0    4103     .05       0
  4489.8     .12       0  4994.2     .07       0  5000.2     .12       0
  5619.7     .05       0
Bank Sta=4947.2,5057.3
XS Rating Curve= 0 ,0
Exp/Cntr=0.3,0.1

Type RM Length L Ch R = 1 ,5742    ,671,671,671
BEGIN DESCRIPTION:
BOX CREEK 8.0
END DESCRIPTION:
XS GIS Cut Line= 3
      3737049.61     10556860.16      3737299.61     10558460.19
      3737799.59     10559860.15
#Sta/Elev= 30
  3352.7  229.21  3413.4  227.26  3585.5  218.94  3652.7  218.62  3778.3  215.36
  3903.8  206.73    3960  200.47  4000.5  198.93  4557.2  197.21  4691.9  194.36
  4850.7  194.23  4901.3  197.23  4931.7  196.76  4951.9  181.86  4969.6  178.72
    5010  178.08  5012.8  177.58    5016  178.08  5025.2  186.34  5035.9  188.49
  5043.8  193.63  5057.1  195.59  5136.2  193.85    5167  196.48  5184.5  195.05
  5259.4  197.97  5683.6  198.73    5978  205.71  6176.8  211.95  6458.7  225.59
#Mann= 7 ,-1 , 0
  3352.7     .05       0  3413.4     .12       0  3652.7     .05       0
  4691.9     .12       0    5010     .07       0    5016     .12       0
    5978     .05       0
Bank Sta=4931.7,5057.1
XS Rating Curve= 0 ,0
Exp/Cntr=0.3,0.1

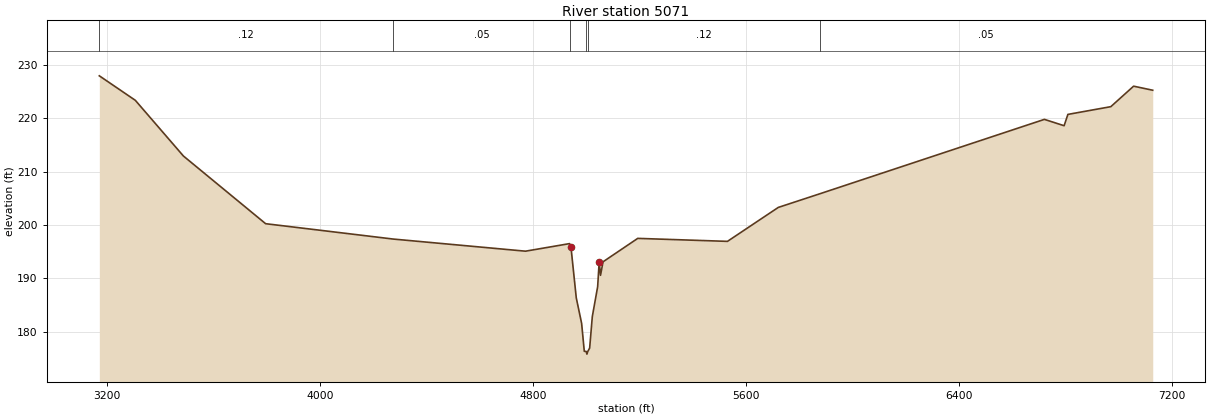
Type RM Length L Ch R = 1 ,5071    ,803,803,803
BEGIN DESCRIPTION:
BOX CREEK 7.0
END DESCRIPTION:
XS GIS Cut Line= 3
      3736754.47     10556825.49      3736935.02     10559075.49
       3737803.1     10560533.86
#Sta/Elev= 30
  3172.3  227.96  3307.4  223.37    3488  212.93  3796.6  200.25  4275.8  197.37
  4772.1   195.1  4937.6  196.52  4942.7  195.91  4962.7  186.34  4982.8  181.57
  4992.8  176.34  4999.9  176.31  5002.6  175.81  5005.9  176.31  5012.9  176.94
  5022.9  182.85    5043  188.46  5048.7  193.13  5053.7  190.58  5063.1  193.11
  5193.5   197.5  5530.2  196.94    5721   203.3  5875.9  205.84    6720   219.8
    6794  218.61  6808.2  220.73  6969.3  222.18  7054.9  226.02  7126.7  225.26
#Mann= 6 ,-1 , 0
  3172.3     .12       0  4275.8     .05       0  4937.6     .12       0
  4999.9     .07       0  5005.9     .12       0  5875.9     .05       0
Bank Sta=4942.7,5048.7
XS Rating Curve= 0 ,0
Exp/Cntr=0.3,0.1