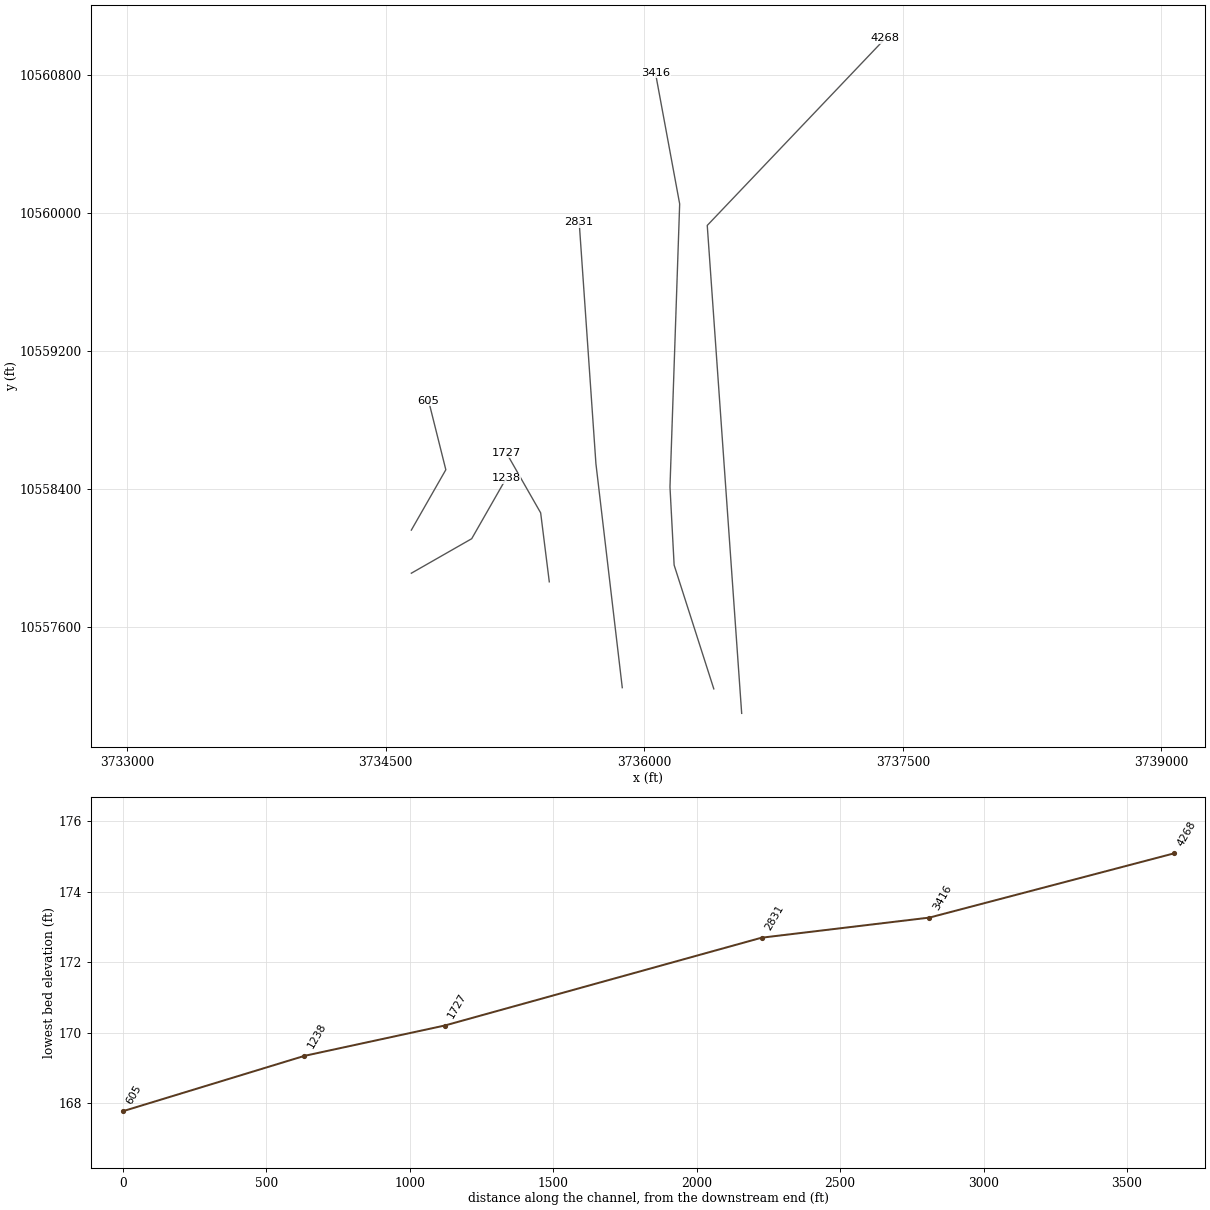
HEC-RAS study BOX CREEK.prj: BOX CREEK Base Level Engineering

--- BOX CREEK.g01 (geometry) --- (continued)

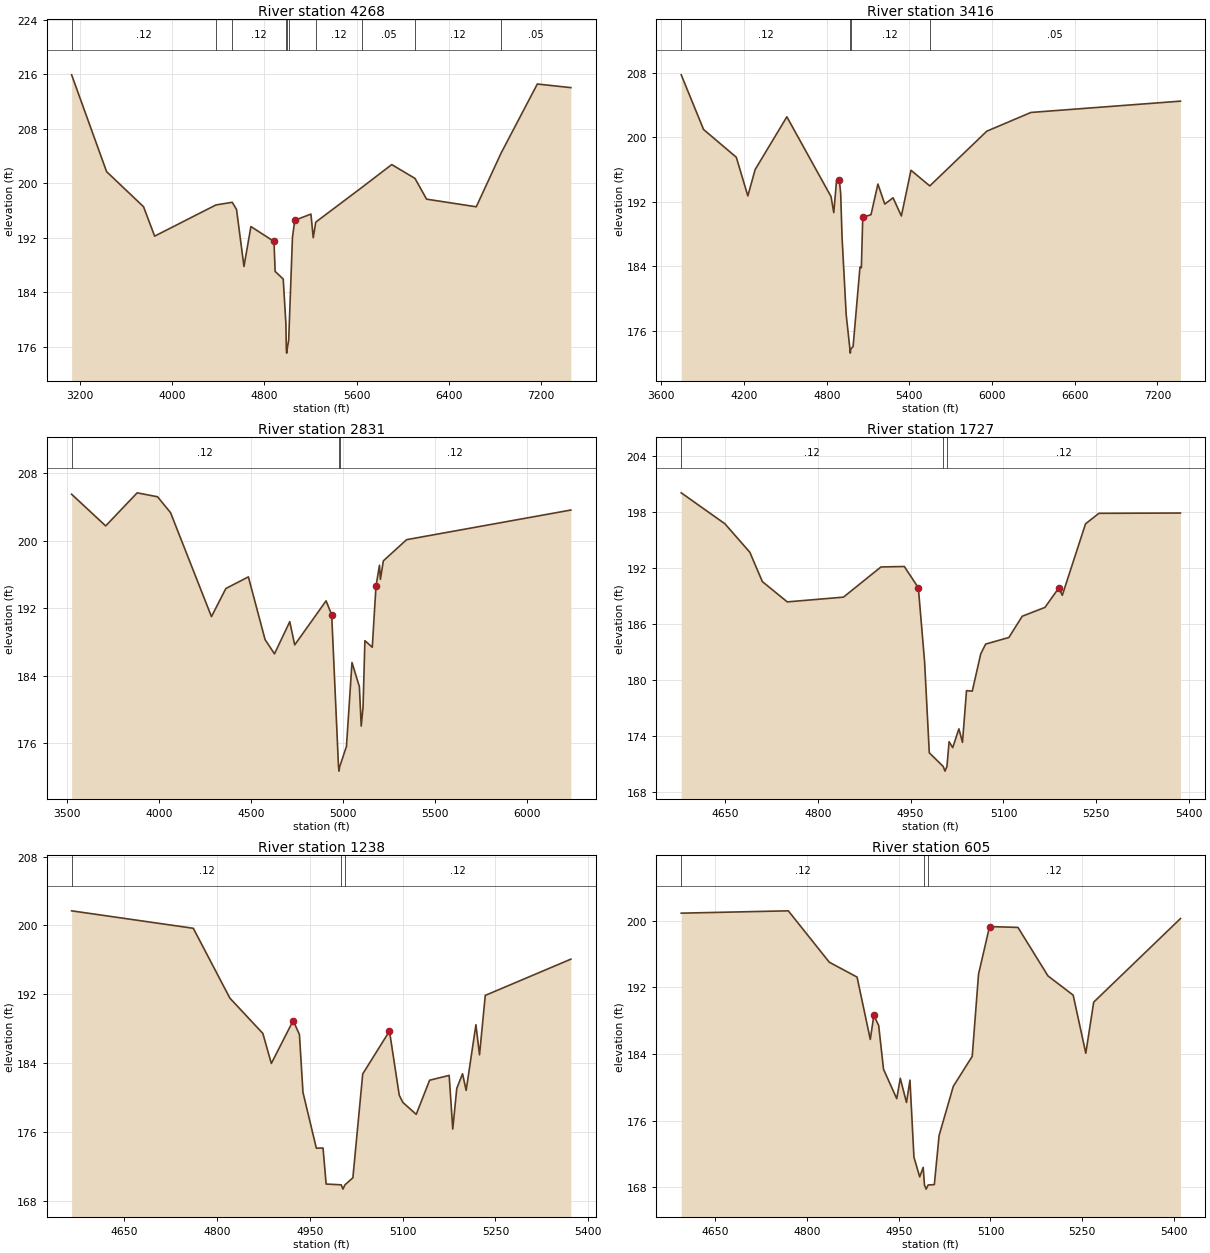
Type RM Length L Ch R = 1 ,4268    ,852,852,852
BEGIN DESCRIPTION:
BOX CREEK 6.0
END DESCRIPTION:
XS GIS Cut Line= 3
      3736565.43     10557097.25      3736365.77     10559927.14
      3737398.78     10561012.24
#Sta/Elev= 30
  3125.7  215.95  3429.4  201.73  3750.2  196.58  3846.6  192.26  4378.7  196.84
  4520.3  197.23  4557.7  196.18  4622.3   187.8  4682.5  193.67    4883  191.48
    4893  187.08  4963.2  185.96  4986.4  179.38  4990.3  175.58    4993  175.08
  4996.3  175.58  5010.6  176.98  5043.4  192.09  5063.4  194.59  5203.8   195.5
  5223.8  192.03  5245.8  194.32    5649  199.45  5905.5  202.77  6107.2  200.74
    6208  197.69  6639.5  196.57  6855.4  204.47  7169.8   214.6  7460.8  214.07
#Mann= 10 ,-1 , 0
  3125.7     .12       0  4378.7     .07       0  4520.3     .12       0
  4990.3     .07       0  4996.3     .12       0  5010.6     .05       0
  5245.8     .12       0    5649     .05       0  6107.2     .12       0
  6855.4     .05       0
Bank Sta=4883,5063.4
XS Rating Curve= 0 ,0
Exp/Cntr=0.3,0.1

Type RM Length L Ch R = 1 ,3416    ,585,585,585
BEGIN DESCRIPTION:
BOX CREEK 5.0
END DESCRIPTION:
XS GIS Cut Line= 5
      3736403.71     10557239.44      3736173.69     10557957.31
      3736149.61     10558410.19       3736205.8     10560051.92
      3736065.18     10560812.29
#Sta/Elev= 30
  3743.9  207.73  3906.1  200.96  4143.7  197.52  4227.5  192.73  4280.2  195.99
  4510.6  202.53  4831.1  192.65  4851.1  190.66  4871.1  194.63  4891.2  194.73
  4901.2  193.04  4911.2  187.61  4941.2  178.02  4968.3  173.76    4971  173.26
  4974.3  173.76  4991.3  174.08  5041.3  183.92  5051.3  183.83  5061.3  190.08
  5121.3  190.41  5171.4   194.2  5221.4  191.72  5281.4   192.5  5341.5  190.25
  5411.5  195.91  5547.8  193.97  5961.8  200.75    6282  203.07  7367.2  204.47
#Mann= 4 ,-1 , 0
  3743.9     .12       0  4968.3     .07       0  4974.3     .12       0
  5547.8     .05       0
Bank Sta=4891.2,5061.3
XS Rating Curve= 0 ,0
Exp/Cntr=0.3,0.1

Type RM Length L Ch R = 1 ,2831    ,1104,1104,1104
BEGIN DESCRIPTION:
Mapping XS 13ea5f53
END DESCRIPTION:
XS GIS Cut Line= 3
       3735872.9     10557246.39      3735720.12     10558544.97
      3735622.99     10559946.48
#Sta/Elev= 30
  3525.7   205.5  3710.8  201.75  3881.9  205.67  3992.7   205.2  4063.2  203.32
  4285.5     191  4363.6  194.33  4486.1  195.71  4576.7  188.28  4627.9  186.59
  4710.9   190.4  4737.8  187.65  4908.3  192.87  4938.7  191.21  4975.8  173.19
  4978.5  172.69  4981.8  173.19  5018.9  175.62    5049  185.56  5089.1   182.7
  5099.1  178.03  5109.1  180.28  5119.1  188.15  5159.2  187.37  5179.3  194.58
  5198.3  197.09  5203.3  195.41  5219.4  197.61  5345.8  200.12  6238.1  203.63
#Mann= 3 ,-1 , 0
  3525.7     .12       0  4975.8     .07       0  4981.8     .12       0
Bank Sta=4938.7,5179.3
XS Rating Curve= 0 ,0
Exp/Cntr=0.3,0.1

Type RM Length L Ch R = 1 ,1727    ,489,489,489
BEGIN DESCRIPTION:
BOX CREEK 3.0
END DESCRIPTION:
XS GIS Cut Line= 3
      3735449.61     10557860.22      3735399.61     10558260.19
      3735199.61     10558610.19
#Sta/Elev= 30
  4579.6  200.08  4650.1  196.76  4690.4   193.7  4710.6  190.55  4750.9  188.37
  4841.6  188.88  4902.1  192.12  4939.9  192.17  4962.5  189.89  4972.6  181.97
  4980.2  172.17  5002.7   170.7  5005.5   170.2  5008.7   170.7  5012.2  173.36
    5018  172.72    5028  174.74  5033.8  173.29  5040.3  178.84  5049.6  178.79
  5063.3  182.79  5071.2  183.84  5108.7  184.55  5130.3  186.83    5167  187.78
  5189.3  189.86    5195  189.08  5232.5  196.75  5254.1  197.88  5385.8  197.91
#Mann= 3 ,-1 , 0
  4579.6     .12       0  5002.7     .07       0  5008.7     .12       0
Bank Sta=4962.5,5189.3
XS Rating Curve= 0 ,0
Exp/Cntr=0.3,0.1

Type RM Length L Ch R = 1 ,1238    ,633,633,633
BEGIN DESCRIPTION:
BOX CREEK 2.0
END DESCRIPTION:
XS GIS Cut Line= 3
      3734649.59     10557910.18      3734999.61     10558110.19
      3735199.59     10558460.15
#Sta/Elev= 30
  4565.6  201.69  4762.1  199.66  4821.2  191.54  4874.4  187.44  4888.1  183.95
  4923.4  188.93  4933.5  187.31  4939.2  180.59  4960.8   174.1  4971.6  174.12
  4976.6  169.93    5001  169.84  5003.8  169.34    5007  169.84  5019.8  170.66
  5035.7  182.73  5078.9  187.71  5094.7  180.25  5100.5  179.42  5122.1  178.03
  5143.7     182  5175.3  182.56  5181.1  176.32  5187.6  181.06  5196.9  182.75
  5202.7  180.82  5218.5  188.45  5224.3  184.95  5233.6  191.86  5371.8  196.07
#Mann= 3 ,-1 , 0
  4565.6     .12       0    5001     .07       0    5007     .12       0
Bank Sta=4923.4,5078.9
XS Rating Curve= 0 ,0
Exp/Cntr=0.3,0.1

Type RM Length L Ch R = 1 ,605     ,0,0,0
BEGIN DESCRIPTION:
BOX CREEK 1.0
END DESCRIPTION:
XS GIS Cut Line= 3
       3734649.6     10558160.17      3734849.61     10558510.19
      3734749.62     10558910.15
#Sta/Elev= 30
  4594.9  200.89  4769.8  201.17  4836.8     195  4882.1  193.22  4903.7  185.74
  4909.5  188.61  4917.4  187.41  4925.3  182.16  4946.9  178.63  4952.7  181.07
  4962.8  178.17  4968.5  180.85    4975  171.61  4984.4  169.24  4990.1  170.38
  4992.2  168.27  4994.9  167.77  4998.2  168.27  5008.3  168.31  5016.1  174.21
  5039.3  180.11  5070.2  183.71  5080.5  193.57  5098.5  199.28  5144.9  199.18
  5193.9  193.36  5235.1  191.05  5255.7  184.08  5268.6  190.21  5410.3  200.24
#Mann= 3 ,-1 , 0
  4594.9     .12       0  4992.2     .07       0  4998.2     .12       0
Bank Sta=4909.5,5098.5
XS Rating Curve= 0 ,0
Exp/Cntr=0.3,0.1

Chan Stop Cuts=-1
Use User Specified Reach Order=0
Composite Channel Slope=5