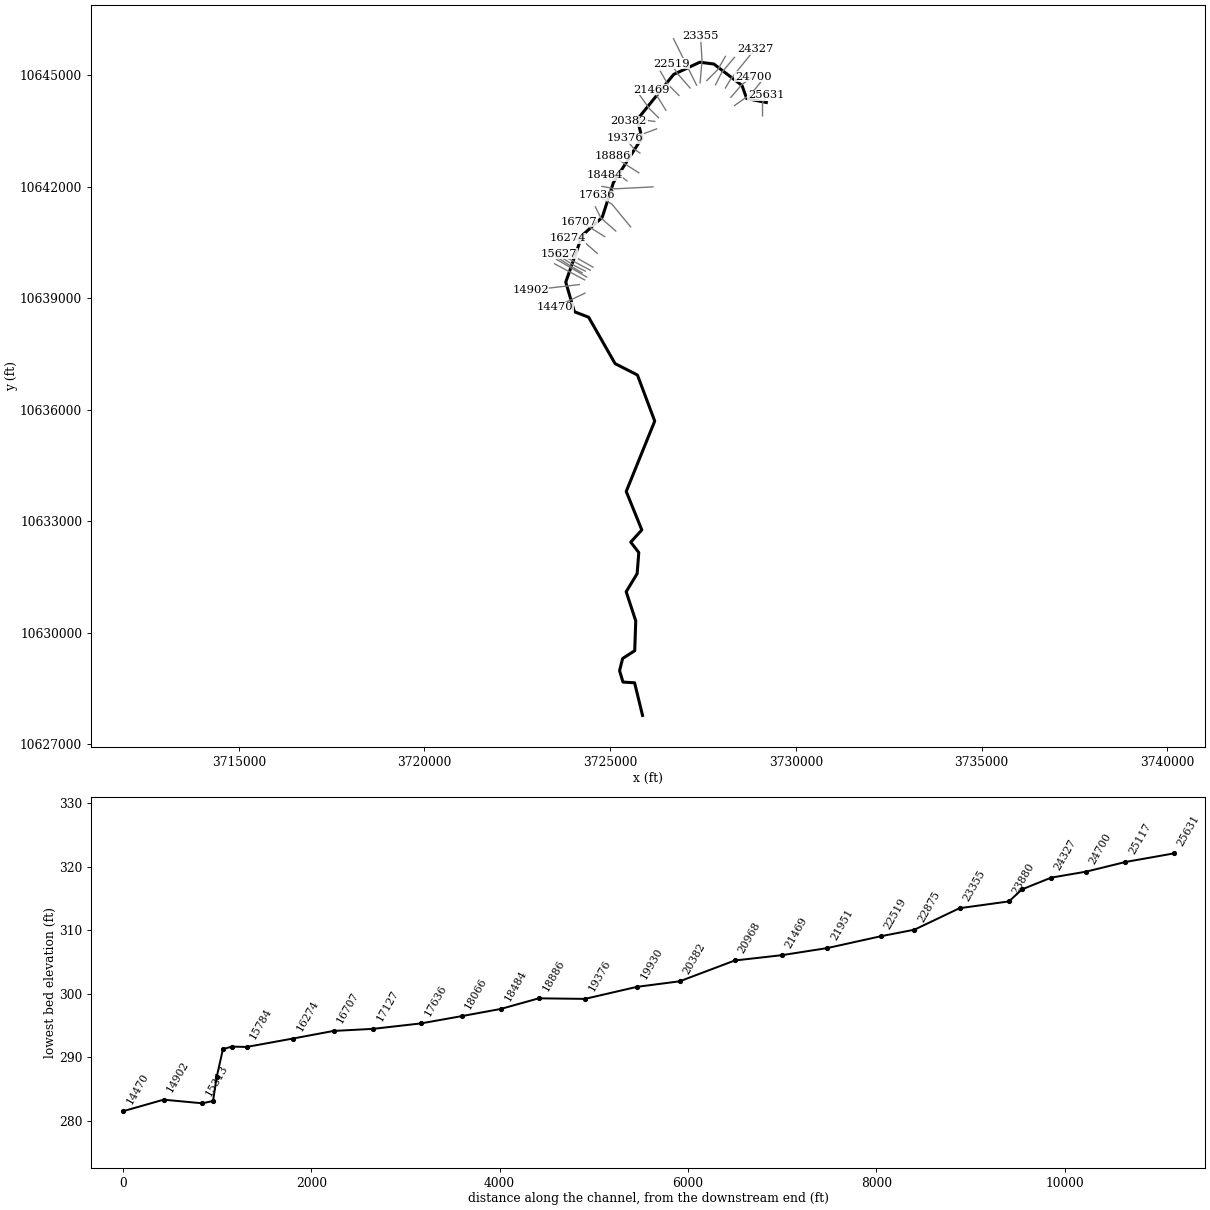
--- CHALYBEATE CREEK.prj (project) ---

Proj Title=CHALYBEATE CREEK Base Level Engineering
Current Plan=p01
Default Exp/Contr=0.3,0.1
English Units
Geom File=g01
Flow File=f01
Plan File=p01
Y Axis Title=Elevation
X Axis Title(PF)=Main Channel Distance
X Axis Title(XS)=Station
BEGIN DESCRIPTION:
CHALYBEATE CREEK
END DESCRIPTION:
DSS Export Rating Curves= 0
DSS Export Rating Curve Sorted= 0
DSS Export Volume Flow Curves= 0
DXF OffsetX= 0
DXF OffsetY= 0
DXF ScaleX= 1
DXF ScaleY= 10

--- CHALYBEATE CREEK.p01 (plan) ---

Plan Title=Multiple Run
Short Identifier=Multiple
Geom File=g01
Flow File=f01
Subcritical Flow
K Sum by GR= 0
Std Step Tol= 0.01
Critical Tol= 0.01
Num of Std Step Trials= 20
Max Error Tol= 0.3
Flow Tol Ratio= 0.001
Split Flow NTrial= 30
Split Flow Tol= 0.02
Split Flow Ratio= 0.02
Log Output Level= 0
Friction Slope Method= 1
Unsteady Friction Slope Method= 2
Unsteady Bridges Friction Slope Method= 1
Parabolic Critical Depth
Global Vel Dist=  1 , 1 , 1
Global Log Level= 0
CheckData=True
Encroach Param= -1, 0, 0, 0
BEGIN DESCRIPTION:
Multiple Run
END DESCRIPTION:

--- CHALYBEATE CREEK.f01 (steady flow) ---

Flow Title=Multiple
Program Version=4.10
Number of Profiles= 7
Profile Names=10-year,25-year,50-year,1pct_min,100-year,1pct_plu,500-year
River Rch & RM=CHALYBEATE CREEK,Reach-1         ,25631
     960    1327    1636    1479    2001    2706    3004
River Rch & RM=CHALYBEATE CREEK,Reach-1         ,17636
    1157    1610    1994    1811    2449    3312    3708
River Rch & RM=CHALYBEATE CREEK,Reach-1         ,11333
    1447    2029    2524    2299    3109    4205    4741
River Rch & RM=CHALYBEATE CREEK,Reach-1         ,5811
    1642    2311    2882    2632    3559    4813    5450
Boundary for River Rch & Prof#=CHALYBEATE CREEK,Reach-1         , 1
Up Type= 0
Dn Type= 3
Dn Slope=0.003
Boundary for River Rch & Prof#=CHALYBEATE CREEK,Reach-1         , 2
Up Type= 0
Dn Type= 3
Dn Slope=0.003
Boundary for River Rch & Prof#=CHALYBEATE CREEK,Reach-1         , 3
Up Type= 0
Dn Type= 3
Dn Slope=0.003
Boundary for River Rch & Prof#=CHALYBEATE CREEK,Reach-1         , 4
Up Type= 0
Dn Type= 3
Dn Slope=0.003
Boundary for River Rch & Prof#=CHALYBEATE CREEK,Reach-1         , 5
Up Type= 0
Dn Type= 3
Dn Slope=0.003
Boundary for River Rch & Prof#=CHALYBEATE CREEK,Reach-1         , 6
Up Type= 0
Dn Type= 3
Dn Slope=0.003
Boundary for River Rch & Prof#=CHALYBEATE CREEK,Reach-1         , 7
Up Type= 0
Dn Type= 3
Dn Slope=0.003
DSS Import GetInterval= 0
DSS Import GetPeak= 0
DSS Import FillOption= 0

--- CHALYBEATE CREEK.g01 (geometry) ---

Geom Title=Existing Conditions
Program Version=4.10

River Reach=CHALYBEATE CREEK,Reach-1
Reach XY= 30
      3729201.75       10644270.       3728673.5       10644375.
        3728547.       10644729.      3727788.25       10645306.
       3727409.5       10645354.      3726706.75       10645025.
      3725727.75       10643812.      3725856.25       10643321.
        3725085.       10642113.        3724784.       10641178.
      3724241.75       10640689.      3723802.75       10639435.
       3724034.5       10638638.      3724418.75       10638490.
       3725130.5       10637241.      3725732.25       10636934.
      3726197.75       10635694.       3725430.5       10633800.
        3725850.       10632763.      3725551.25       10632435.
      3725768.75       10632156.       3725724.5       10631587.
       3725429.5       10631100.        3725687.       10630314.
      3725659.25       10629513.      3725334.25       10629303.
        3725251.       10628975.      3725343.25       10628668.
      3725655.75       10628649.       3725869.5       10627770.

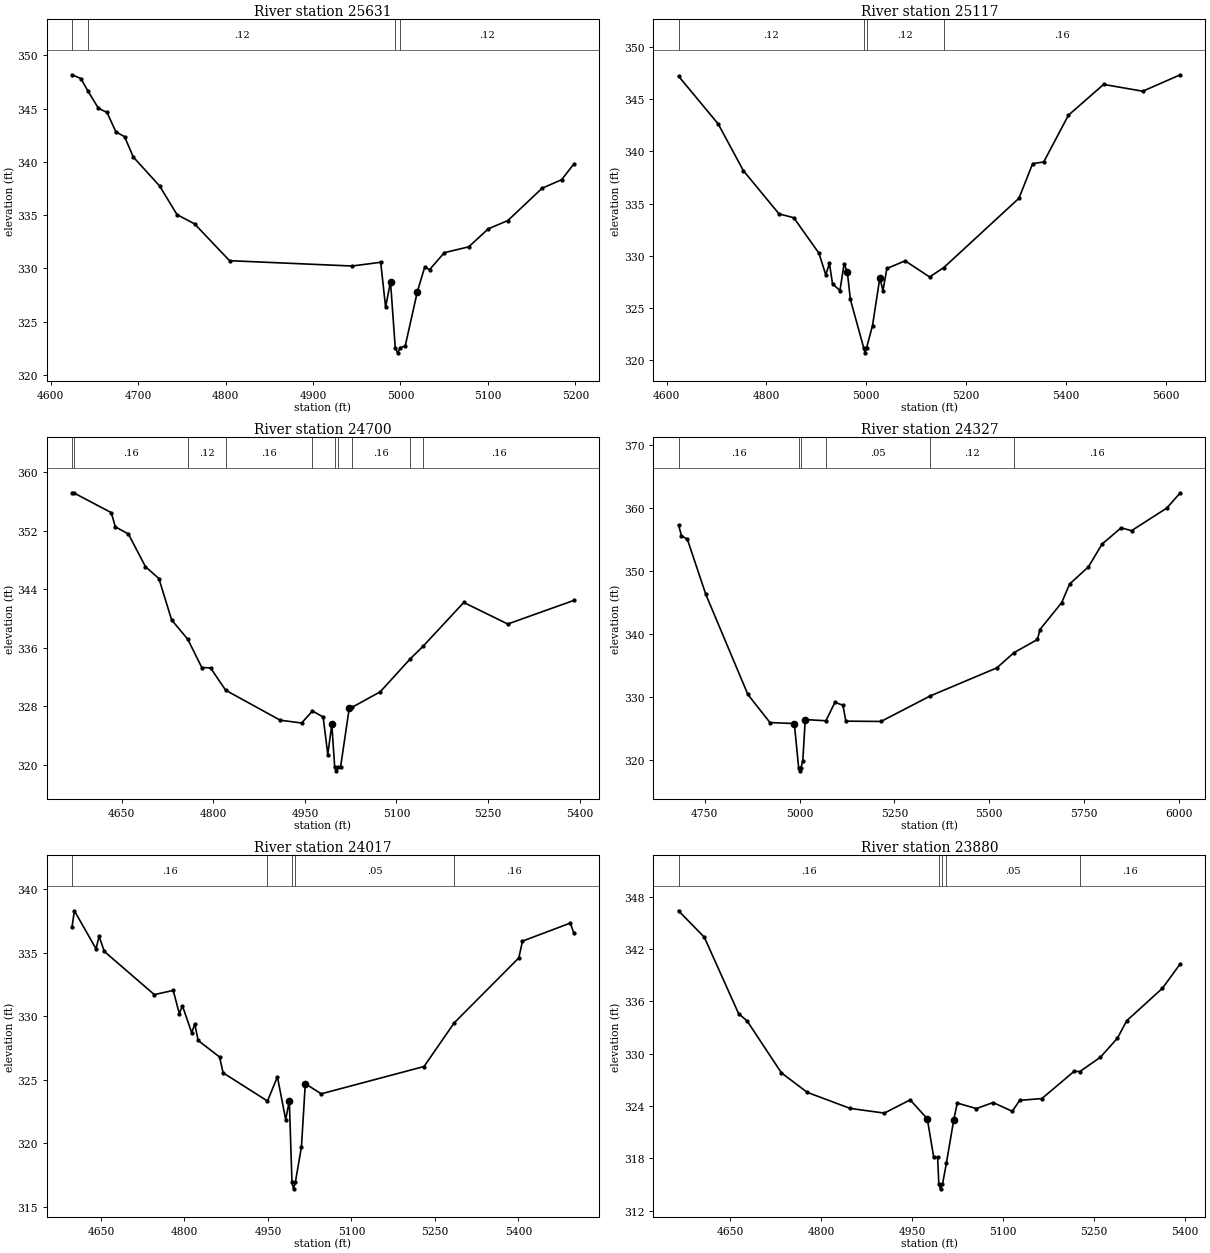
Type RM Length L Ch R = 1 ,25631   ,514,514,514
BEGIN DESCRIPTION:
CHALYBEATE CREEK 55.0
END DESCRIPTION:
XS GIS Cut Line= 3
      3729099.61     10643910.17      3729099.61     10644260.19
       3729199.6     10644460.17
#Sta/Elev= 30
  4624.6  348.18  4634.6  347.83  4642.5  346.69  4654.6  345.05  4664.6  344.64
  4674.6  342.83  4684.6  342.37  4694.6  340.46  4724.6  337.75  4744.6  335.05
  4764.6  334.19  4804.6  330.73  4944.6  330.23  4977.4  330.58    4983  326.36
  4988.6  328.76    4994  322.58  4996.7  322.08    5000  322.58  5005.4  322.72
  5019.3  327.82  5027.7  330.13  5033.3  329.89  5050.1  331.48    5078  332.03
  5100.4  333.72  5122.8   334.5  5161.9  337.53  5184.2  338.33  5198.2  339.81
#Mann= 4 ,-1 , 0
  4624.6     .05       0  4642.5     .12       0    4994     .07       0
    5000     .12       0
Bank Sta=4988.6,5019.3
XS Rating Curve= 0 ,0
Exp/Cntr=0.3,0.1

Type RM Length L Ch R = 1 ,25117   ,417,417,417
BEGIN DESCRIPTION:
CHALYBEATE CREEK 54.0
END DESCRIPTION:
XS GIS Cut Line= 3
      3728348.67     10644190.28      3728801.81     10644509.74
       3729084.7      10644860.3
#Sta/Elev= 30
    4624  347.17  4703.3  342.61  4753.8  338.14  4825.2  334.01  4854.8  333.64
  4905.3  330.24  4918.8  328.19  4926.2  329.27  4932.4  327.32  4947.2  326.68
  4955.5  329.21  4961.9   328.5  4968.1  325.84  4994.7  321.23  4997.4  320.73
  5000.7  321.23  5012.5  323.34  5027.2  327.92  5033.4  326.66  5041.2  328.79
  5077.8  329.52  5126.8  327.98  5155.3  328.88  5305.7   335.5  5333.2  338.81
  5355.3  338.97  5404.9  343.44  5475.3  346.38  5553.6  345.73  5628.9   347.3
#Mann= 4 ,-1 , 0
    4624     .12       0  4994.7     .07       0  5000.7     .12       0
  5155.3     .16       0
Bank Sta=4961.9,5027.2
XS Rating Curve= 0 ,0
Exp/Cntr=0.3,0.1

Type RM Length L Ch R = 1 ,24700   ,373,373,373
BEGIN DESCRIPTION:
CHALYBEATE CREEK 53.0
END DESCRIPTION:
XS GIS Cut Line= 3
      3728249.59     10644410.17      3728549.61     10644760.19
      3728849.65     10644960.21
#Sta/Elev= 30
  4568.8  357.16  4571.3  357.16    4633  354.45  4639.6  352.51    4661  351.54
    4689  347.07    4711  345.45  4731.8  339.81  4758.3  337.16  4781.2  333.31
  4795.5  333.26  4820.3  330.21  4909.6  326.12  4944.7  325.74  4962.4  327.38
  4979.9  326.56  4987.5  321.44  4994.1  325.54  4998.8  319.71  5001.6  319.21
  5004.8  319.71  5008.4  319.72  5022.7   327.8    5027  327.87  5073.4     330
  5122.8  334.52  5143.5  336.21  5210.1  342.19  5282.2  339.25  5390.4  342.47
#Mann= 10 ,-1 , 0
  4568.8     .12       0  4571.3     .16       0  4758.3     .12       0
  4820.3     .16       0  4962.4     .12       0  4998.8     .07       0
  5004.8     .12       0    5027     .16       0  5122.8     .05       0
  5143.5     .16       0
Bank Sta=4994.1,5022.7
XS Rating Curve= 0 ,0
Exp/Cntr=0.3,0.1

Type RM Length L Ch R = 1 ,24327   ,310,310,310
BEGIN DESCRIPTION:
CHALYBEATE CREEK 52.0
END DESCRIPTION:
XS GIS Cut Line= 3
      3728099.63     10644660.22      3728249.61     10644910.19
      3728899.62      10645710.2
#Sta/Elev= 30
  4681.1  357.34  4688.8  355.64  4704.4  355.06    4753   346.3  4863.8   330.4
  4922.1  325.93  4986.2  325.78  4997.6  318.76  5000.4  318.26  5003.6  318.76
  5008.5   319.8    5015  326.41  5069.4  326.22  5093.3  329.15  5114.3  328.69
    5122  326.16  5214.7  326.11  5344.1  330.16    5520  334.63  5564.9  337.04
    5627  339.14  5633.4  340.72  5690.9  345.01  5711.7  347.96  5761.3  350.69
  5797.2  354.31  5847.5  356.89  5874.8  356.43  5967.5  360.02  6003.4  362.46
#Mann= 6 ,-1 , 0
  4681.1     .16       0  4997.6     .07       0  5003.6     .16       0
  5069.4     .05       0  5344.1     .12       0  5564.9     .16       0
Bank Sta=4986.2,5015
XS Rating Curve= 0 ,0
Exp/Cntr=0.3,0.1

Type RM Length L Ch R = 1 ,24017   ,137,137,137
BEGIN DESCRIPTION:
Mapping XS 5f50def2
END DESCRIPTION:
XS GIS Cut Line= 3
       3727834.1      10644748.7      3728003.36     10645078.55
      3728344.84     10645484.87
#Sta/Elev= 30
  4598.2  337.05  4602.4   338.3  4641.2  335.31  4646.8  336.29  4656.1   335.1
    4746   331.7  4779.9  332.03  4790.9   330.2  4796.5  330.82  4813.1   328.7
  4818.7  329.38  4824.7  328.09  4863.1  326.79  4869.6  325.54  4949.3  323.32
  4967.1  325.23    4982  321.86  4988.5  323.34  4993.3  316.91  4996.1  316.41
  4999.3  316.91  5010.3  319.72  5017.2  324.69  5045.8  323.89  5230.5  326.04
  5284.8  329.48  5400.8  334.59  5407.4  335.91  5493.2  337.33  5499.7  336.55
#Mann= 5 ,-1 , 0
  4598.2     .16       0  4949.3     .05       0  4993.3     .03       0
  4999.3     .05       0  5284.8     .16       0
Bank Sta=4988.5,5017.2
XS Rating Curve= 0 ,0
Exp/Cntr=0.3,0.1

Type RM Length L Ch R = 1 ,23880   ,525,525,525
BEGIN DESCRIPTION:
CHALYBEATE CREEK 51.0
END DESCRIPTION:
XS GIS Cut Line= 3
      3727599.58     10644860.16      3727899.61     10645160.19
       3728099.6     10645510.18
#Sta/Elev= 30
  4564.5  346.39    4607  343.36  4663.5  334.61  4677.7  333.75  4734.2  327.81
  4776.7  325.58  4847.4  323.74  4903.9   323.2  4946.4  324.72  4974.7  322.55
  4985.3  318.12  4991.7  318.12  4993.7  315.02  4996.5  314.52  4999.7  315.02
  5006.1  317.44  5018.3  322.43  5024.1  324.35  5055.7  323.72  5083.1  324.41
  5114.8  323.41    5127  324.66  5163.7  324.87    5217     328    5226  327.95
  5260.2  329.61  5288.3   331.8  5303.4  333.78  5362.4  337.51  5391.9  340.32
#Mann= 5 ,-1 , 0
  4564.5     .16       0  4993.7     .07       0  4999.7     .16       0
  5006.1     .05       0    5226     .16       0
Bank Sta=4974.7,5018.3
XS Rating Curve= 0 ,0
Exp/Cntr=0.3,0.1

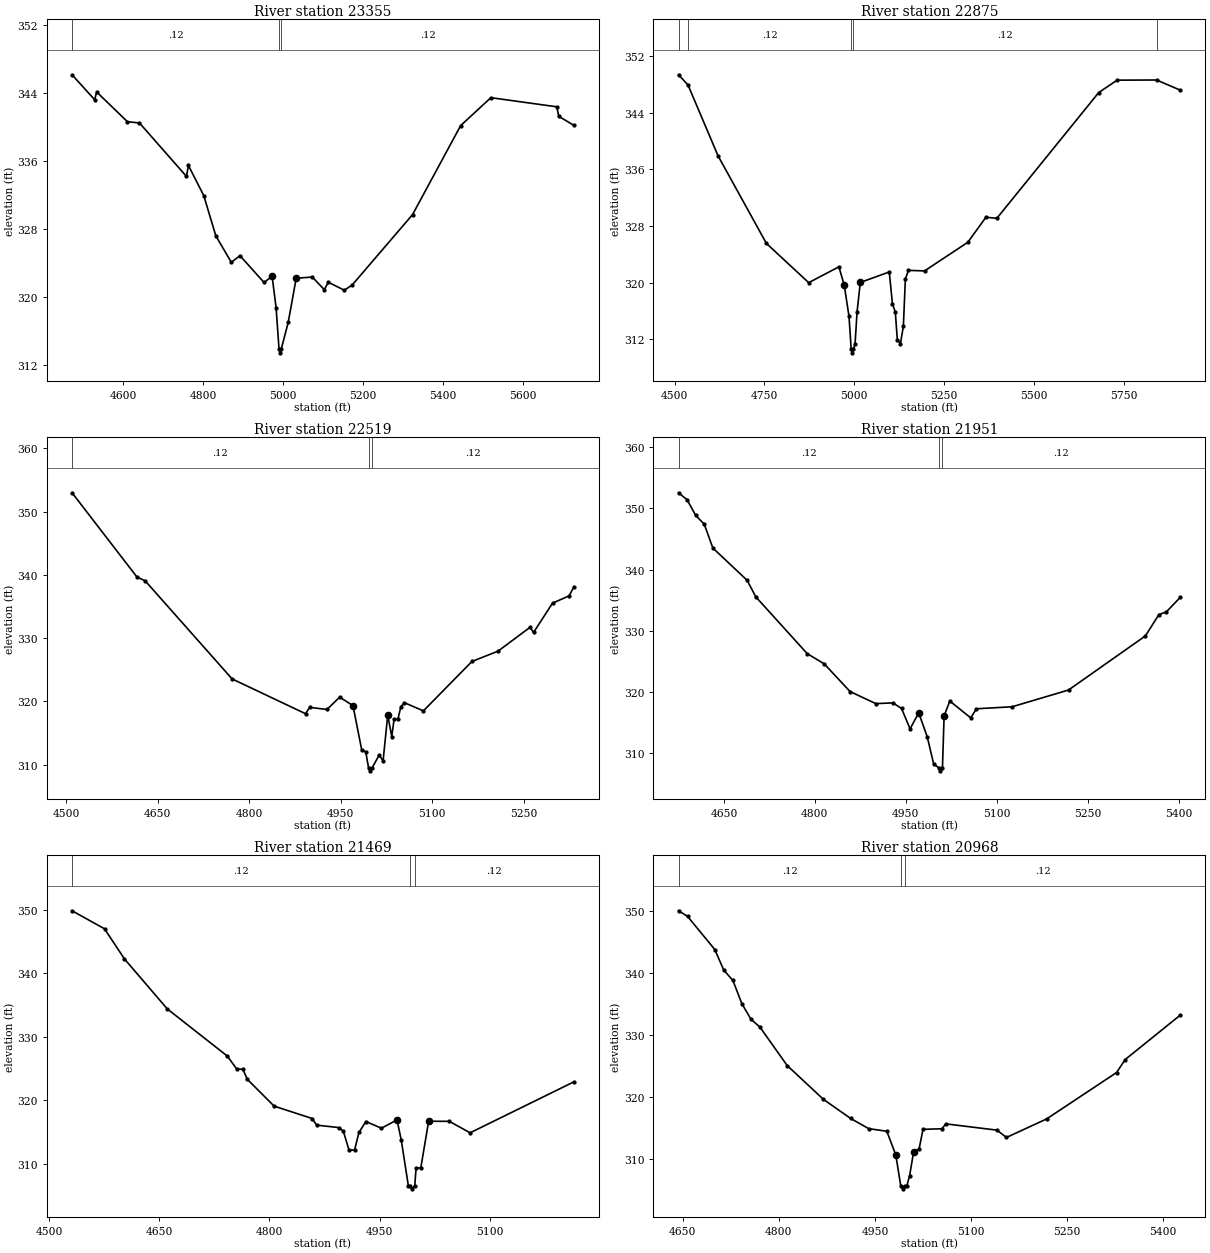
Type RM Length L Ch R = 1 ,23355   ,480,480,480
BEGIN DESCRIPTION:
CHALYBEATE CREEK 50.0
END DESCRIPTION:
XS GIS Cut Line= 3
      3727419.34     10644802.42      3727471.43     10645392.73
      3727432.36     10646052.47
#Sta/Elev= 30
  4472.9   346.1  4529.3  343.17  4534.4  344.08  4611.2  340.59  4641.3  340.44
  4758.6  334.17  4763.6  335.45  4801.9  331.91  4832.1  327.18  4870.7  324.08
  4892.3  324.86  4952.5  321.71  4972.6  322.44  4982.6  318.74  4989.8  313.95
  4992.6  313.45  4995.8  313.95  5012.8  317.02  5032.8  322.21    5073  322.35
    5103  320.87    5113  321.74  5153.1   320.8  5173.1  321.44  5323.4  329.68
  5443.6  340.13    5519  343.41  5683.7  342.34  5688.7  341.22  5726.4  340.16
#Mann= 3 ,-1 , 0
  4472.9     .12       0  4989.8     .07       0  4995.8     .12       0
Bank Sta=4972.6,5032.8
XS Rating Curve= 0 ,0
Exp/Cntr=0.3,0.1

Type RM Length L Ch R = 1 ,22875   ,356,356,356
BEGIN DESCRIPTION:
CHALYBEATE CREEK 49.0
END DESCRIPTION:
XS GIS Cut Line= 2
      3727323.84     10644737.38      3726703.18     10645987.38
#Sta/Elev= 30
  4511.1   349.4  4537.5  347.95    4621  337.93  4755.5  325.54  4873.1  319.99
  4957.2  322.23    4972  319.61  4985.2  315.23  4991.3  310.56  4994.1  310.06
  4997.3  310.56    5002  311.27  5007.6  315.83  5016.6  320.02  5097.2   321.5
    5106  316.98    5114  315.84  5119.6  311.91  5128.3  311.37  5136.4  313.82
    5142  320.51  5150.6  321.73  5195.3  321.65  5315.7   325.7  5366.1  329.25
  5396.3  329.09  5679.8  346.89  5731.2  348.64  5840.7  348.66  5906.7  347.22
#Mann= 5 ,-1 , 0
  4511.1     .16       0  4537.5     .12       0  4991.3     .07       0
  4997.3     .12       0  5840.7     .05       0
Bank Sta=4972,5016.6
XS Rating Curve= 0 ,0
Exp/Cntr=0.3,0.1

Type RM Length L Ch R = 1 ,22519   ,568,568,568
BEGIN DESCRIPTION:
CHALYBEATE CREEK 48.0
END DESCRIPTION:
XS GIS Cut Line= 3
      3727149.64     10644660.15      3726799.61     10645060.19
      3726649.61     10645310.19
#Sta/Elev= 30
  4509.4  352.99  4615.7  339.69  4629.5  339.05  4771.9  323.56  4892.4  318.06
  4899.1  319.07  4927.5  318.73  4948.4  320.68  4970.2  319.34  4984.5  312.34
  4991.1  312.04  4995.7  309.53  4998.5  309.03  5001.7  309.53    5013  311.49
  5019.6  310.63  5027.2  317.86  5033.8  314.44  5037.6   317.2  5043.9   317.2
  5048.7  319.16  5054.6   319.8  5085.7  318.51  5165.3  326.32  5208.1  327.95
  5260.6  331.72  5266.4  330.91  5297.5  335.54  5324.7  336.69  5332.5  338.11
#Mann= 3 ,-1 , 0
  4509.4     .12       0  4995.7     .07       0  5001.7     .12       0
Bank Sta=4970.2,5027.2
XS Rating Curve= 0 ,0
Exp/Cntr=0.3,0.1

Type RM Length L Ch R = 1 ,21951   ,482,482,482
BEGIN DESCRIPTION:
CHALYBEATE CREEK 47.0
END DESCRIPTION:
XS GIS Cut Line= 3
      3726849.61     10644460.19      3726549.61     10644760.19
      3726349.59     10645110.21
#Sta/Elev= 30
  4575.2  352.51  4589.3  351.38  4603.5  348.82  4617.6  347.39  4631.8   343.5
  4688.3  338.24  4702.5  335.55  4787.3  326.29  4815.6   324.6    4858   320.1
  4900.5  318.13  4928.7  318.25  4942.9  317.34    4957  314.01  4971.2  316.64
  4985.3  312.71  4995.9  308.28  5004.4  307.67  5007.1  307.17  5010.4  307.67
  5013.1  316.12  5022.5  318.55    5057  315.81  5066.4  317.29  5125.4  317.62
  5218.3  320.35    5345  329.17  5367.3  332.65  5379.5  333.08  5402.6  335.47
#Mann= 3 ,-1 , 0
  4575.2     .12       0  5004.4     .07       0  5010.4     .12       0
Bank Sta=4971.2,5013.1
XS Rating Curve= 0 ,0
Exp/Cntr=0.3,0.1

Type RM Length L Ch R = 1 ,21469   ,501,501,501
BEGIN DESCRIPTION:
CHALYBEATE CREEK 46.0
END DESCRIPTION:
XS GIS Cut Line= 3
      3726499.62     10644060.18      3726249.61     10644460.19
      3726099.64     10644610.16
#Sta/Elev= 30
    4531  349.87  4575.2  347.03  4602.4  342.28  4660.7  334.41  4742.7  326.96
  4755.1  324.97  4763.9  324.87  4769.8  323.31  4806.4  319.08  4858.3  317.13
  4864.2  316.09  4894.8   315.7  4900.7  315.12  4908.4  312.16    4916  312.17
  4921.9  314.93  4931.4  316.66  4952.6   315.6  4973.8  316.92  4979.7  313.67
  4989.2  306.57    4992  306.55  4994.8  306.05    4998  306.55  4999.8  309.34
  5006.2  309.34  5016.9   316.7  5045.1  316.69  5073.4  314.88  5214.8  322.91
#Mann= 3 ,-1 , 0
    4531     .12       0    4992     .07       0    4998     .12       0
Bank Sta=4973.8,5016.9
XS Rating Curve= 0 ,0
Exp/Cntr=0.3,0.1

Type RM Length L Ch R = 1 ,20968   ,586,586,586
BEGIN DESCRIPTION:
CHALYBEATE CREEK 45.0
END DESCRIPTION:
XS GIS Cut Line= 3
      3726299.61     10643860.19      3726049.61     10644110.19
      3725799.59     10644460.21
#Sta/Elev= 30
  4643.3  350.02  4657.4  349.12  4699.9  343.78    4714  340.45  4728.2  338.79
  4742.3  335.03  4756.4  332.55  4770.6  331.25    4813  325.08  4869.6  319.63
    4912  316.56  4940.3  314.91  4968.6  314.49  4982.7  310.64  4990.3  305.71
  4993.1  305.21  4996.3  305.71  4999.9  305.71  5004.2  307.32  5010.4  311.15
    5019  311.63  5025.1   314.8  5054.6  314.89  5060.8  315.68  5140.6  314.67
  5155.4  313.49  5218.1  316.47  5327.4  323.95  5340.9  326.05    5427  333.21
#Mann= 3 ,-1 , 0
  4643.3     .12       0  4990.3     .07       0  4996.3     .12       0
Bank Sta=4982.7,5010.4
XS Rating Curve= 0 ,0
Exp/Cntr=0.3,0.1

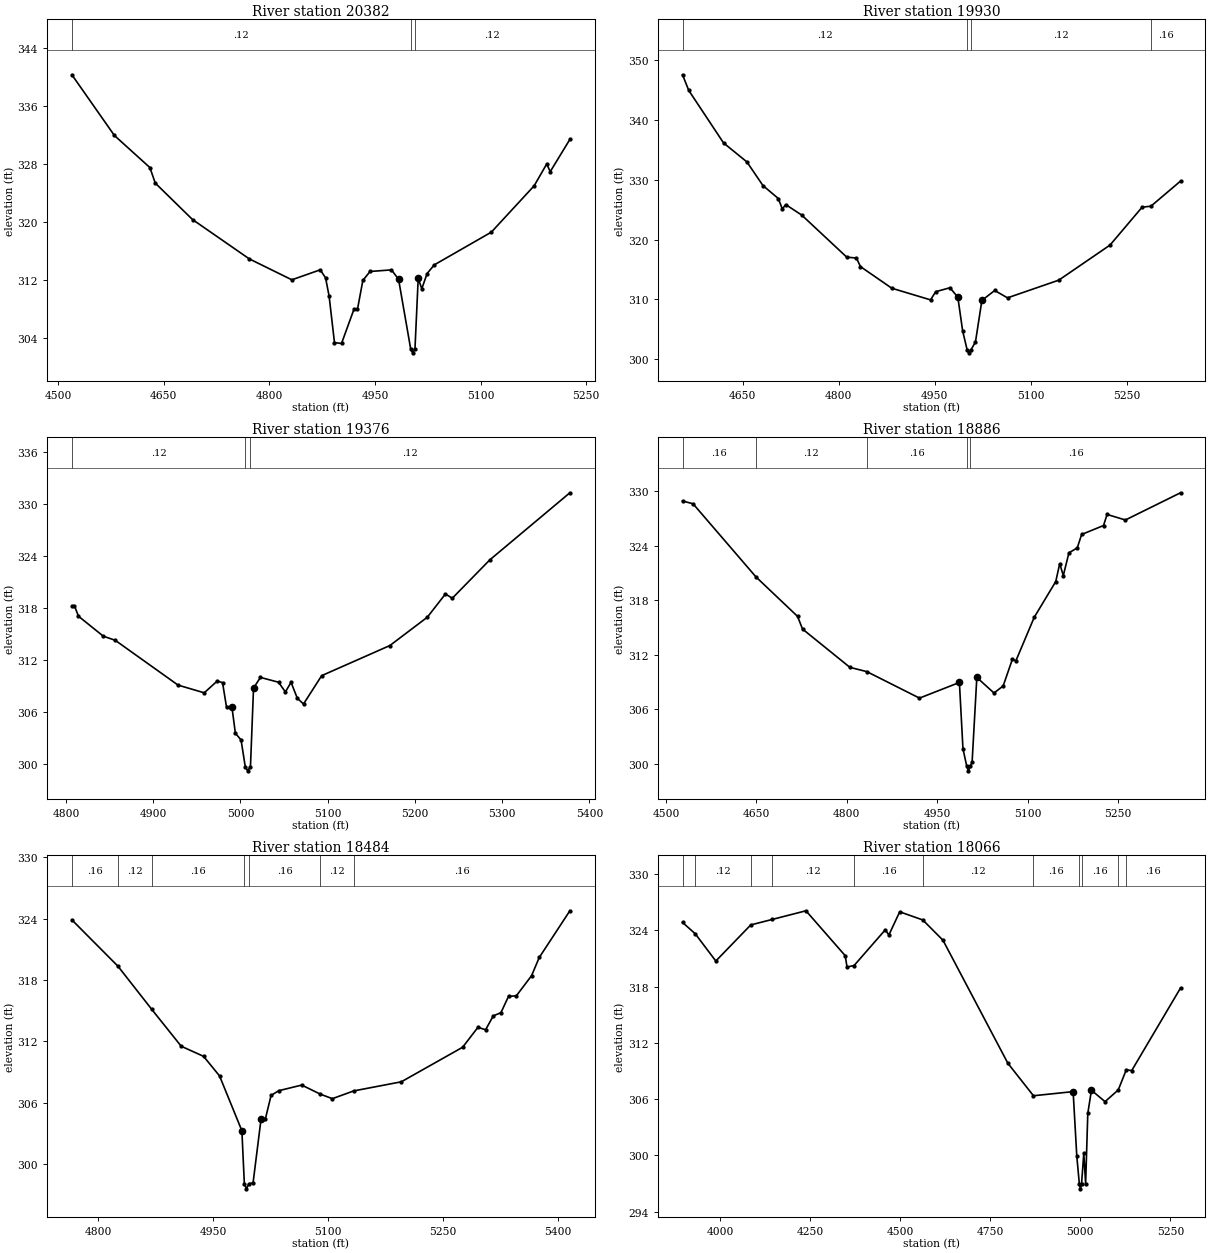
Type RM Length L Ch R = 1 ,20382   ,452,452,452
BEGIN DESCRIPTION:
CHALYBEATE CREEK 44.0
END DESCRIPTION:
XS GIS Cut Line= 3
      3726199.58     10643760.19      3725799.61     10643810.19
      3725499.63     10643760.19
#Sta/Elev= 30
  4519.7  340.31  4580.1  331.93  4630.5   327.5  4638.1  325.36    4691  320.33
  4771.6   314.9  4832.1  312.01  4872.4  313.39    4880  312.27    4885  309.75
  4892.6  303.35  4902.6  303.22  4920.3  307.95  4925.3  307.95  4932.9  311.92
  4943.1  313.16  4973.5  313.38  4983.6  312.09  5000.9  302.43  5003.6  301.93
  5006.9  302.43  5011.5   312.2  5016.6  310.78  5024.2  312.88  5034.3  314.07
  5115.4  318.59  5176.2  324.99    5194     328    5199  326.94  5226.9  331.39
#Mann= 3 ,-1 , 0
  4519.7     .12       0  5000.9     .07       0  5006.9     .12       0
Bank Sta=4983.6,5011.5
XS Rating Curve= 0 ,0
Exp/Cntr=0.3,0.1

Type RM Length L Ch R = 1 ,19930   ,554,554,554
BEGIN DESCRIPTION:
CHALYBEATE CREEK 43.0
END DESCRIPTION:
XS GIS Cut Line= 3
      3726249.59     10643560.18      3725849.61     10643410.19
      3725499.59     10643410.19
#Sta/Elev= 30
  4556.2  347.58    4566  344.95  4620.3  336.17  4656.7     333  4681.7  329.05
  4705.7  326.88  4711.9  325.13  4717.3  325.86  4742.2  324.11  4812.5  317.07
  4827.6  316.92  4833.9  315.49  4882.8  311.87  4943.3  309.92  4951.3  311.29
  4973.6  311.95  4985.9  310.36  4993.4  304.72  5000.4  301.56  5003.1  301.06
  5006.4  301.56  5013.4  302.88  5023.4  309.83  5043.4  311.49  5063.4  310.26
  5143.4  313.22  5223.4  319.09  5273.4  325.42  5287.3   325.6  5333.4  329.79
#Mann= 4 ,-1 , 0
  4556.2     .12       0  5000.4     .07       0  5006.4     .12       0
  5287.3     .16       0
Bank Sta=4985.9,5023.4
XS Rating Curve= 0 ,0
Exp/Cntr=0.3,0.1

Type RM Length L Ch R = 1 ,19376   ,490,490,490
BEGIN DESCRIPTION:
CHALYBEATE CREEK 42.0
END DESCRIPTION:
XS GIS Cut Line= 3
       3725799.6      10642910.2      3725649.61     10643010.19
      3725399.59     10643310.21
#Sta/Elev= 30
  4806.8  318.21  4809.8  318.21  4814.3  317.02  4842.8  314.71  4856.4  314.24
  4928.5  309.06  4958.5  308.17  4973.5  309.54  4979.5  309.34  4984.1  306.48
  4990.3  306.48  4994.2   303.5  5000.7  302.73  5005.5  299.66  5008.3  299.16
  5011.5  299.66    5015  308.71  5022.9  309.95  5043.7  309.39  5051.5  308.27
    5058  309.38  5065.2  307.54  5072.3  306.88  5093.1  310.15  5171.3  313.63
  5214.2   316.9    5235  319.59  5242.8  319.09  5285.8  323.52  5377.6  331.27
#Mann= 3 ,-1 , 0
  4806.8     .12       0  5005.5     .07       0  5011.5     .12       0
Bank Sta=4990.3,5015
XS Rating Curve= 0 ,0
Exp/Cntr=0.3,0.1

Type RM Length L Ch R = 1 ,18886   ,402,402,402
BEGIN DESCRIPTION:
CHALYBEATE CREEK 41.0
END DESCRIPTION:
XS GIS Cut Line= 2
      3725770.06     10642376.22      3725075.62     10642823.27
#Sta/Elev= 30
  4527.5   328.9    4545  328.59  4649.4  320.55  4718.3  316.22  4726.5  314.83
  4805.1  310.62  4833.2  310.15  4920.5  307.24  4986.7  308.96  4992.6  301.68
  4998.9  299.75  5001.6  299.25  5004.9  299.75  5007.8  300.24  5015.6  309.51
  5044.1   307.8  5059.3  308.58  5074.5   311.5  5080.4  311.34  5110.8  316.12
  5146.5  320.05  5153.1  322.02    5159   320.7  5168.3   323.2  5182.2  323.75
  5189.4  325.22  5225.7   326.2  5231.6  327.42    5262  326.81  5353.4   329.8
#Mann= 5 ,-1 , 0
  4527.5     .16       0  4649.4     .12       0  4833.2     .16       0
  4998.9     .07       0  5004.9     .16       0
Bank Sta=4986.7,5015.6
XS Rating Curve= 0 ,0
Exp/Cntr=0.3,0.1

Type RM Length L Ch R = 1 ,18484   ,418,418,418
BEGIN DESCRIPTION:
CHALYBEATE CREEK 40.0
END DESCRIPTION:
XS GIS Cut Line= 3
       3725449.6     10642160.19      3725249.61     10642310.19
       3724849.6     10642310.19
#Sta/Elev= 30
  4765.4  323.89  4825.5  319.36  4869.5  315.15  4908.1  311.53  4937.3  310.54
  4958.1  308.63  4987.3  303.26  4990.5  298.08  4993.3  297.58  4996.5  298.08
  5001.9  298.17  5012.3   304.4  5017.9   304.4  5025.4  306.72  5035.4  307.18
  5065.4  307.73  5089.8  306.84  5105.4   306.4  5133.3  307.16  5195.4  308.05
  5275.4  311.43  5295.4  313.38  5305.4  313.14  5315.4   314.5  5325.4  314.81
  5335.4  316.42  5345.4  316.45  5365.4  318.43  5375.4  320.21  5415.4  324.78
#Mann= 7 ,-1 , 0
  4765.4     .16       0  4825.5     .12       0  4869.5     .16       0
  4990.5     .07       0  4996.5     .16       0  5089.8     .12       0
  5133.3     .16       0
Bank Sta=4987.3,5012.3
XS Rating Curve= 0 ,0
Exp/Cntr=0.3,0.1

Type RM Length L Ch R = 1 ,18066   ,430,430,430
BEGIN DESCRIPTION:
Mapping XS bdaa6e94
END DESCRIPTION:
XS GIS Cut Line= 3
      3726151.97     10641998.63       3725140.7     10641946.55
      3724776.08     10642011.66
#Sta/Elev= 30
  3895.2  324.86  3930.5  323.65  3987.7  320.74  4084.7  324.59  4144.7  325.18
    4238   326.1    4347  321.31  4352.1   320.1  4371.7  320.26  4458.3  324.07
  4468.3  323.52  4498.4  325.99  4562.5  325.12  4618.5  322.96  4798.8  309.83
  4869.8  306.37    4980  306.81  4990.2   299.9  4997.3  296.94  5000.1  296.44
  5003.3  296.94  5009.6  300.21  5014.7     297  5020.7  304.48  5030.8  306.96
  5068.6  305.74  5105.3  306.99  5127.6  309.14  5142.6  309.05  5278.2  317.86
#Mann= 11 ,-1 , 0
  3895.2     .16       0  3930.5     .12       0  4084.7     .16       0
  4144.7     .12       0  4371.7     .16       0  4562.5     .12       0
  4869.8     .16       0  4997.3     .07       0  5003.3     .16       0
  5105.3     .12       0  5127.6     .16       0
Bank Sta=4980,5030.8
XS Rating Curve= 0 ,0
Exp/Cntr=0.3,0.1

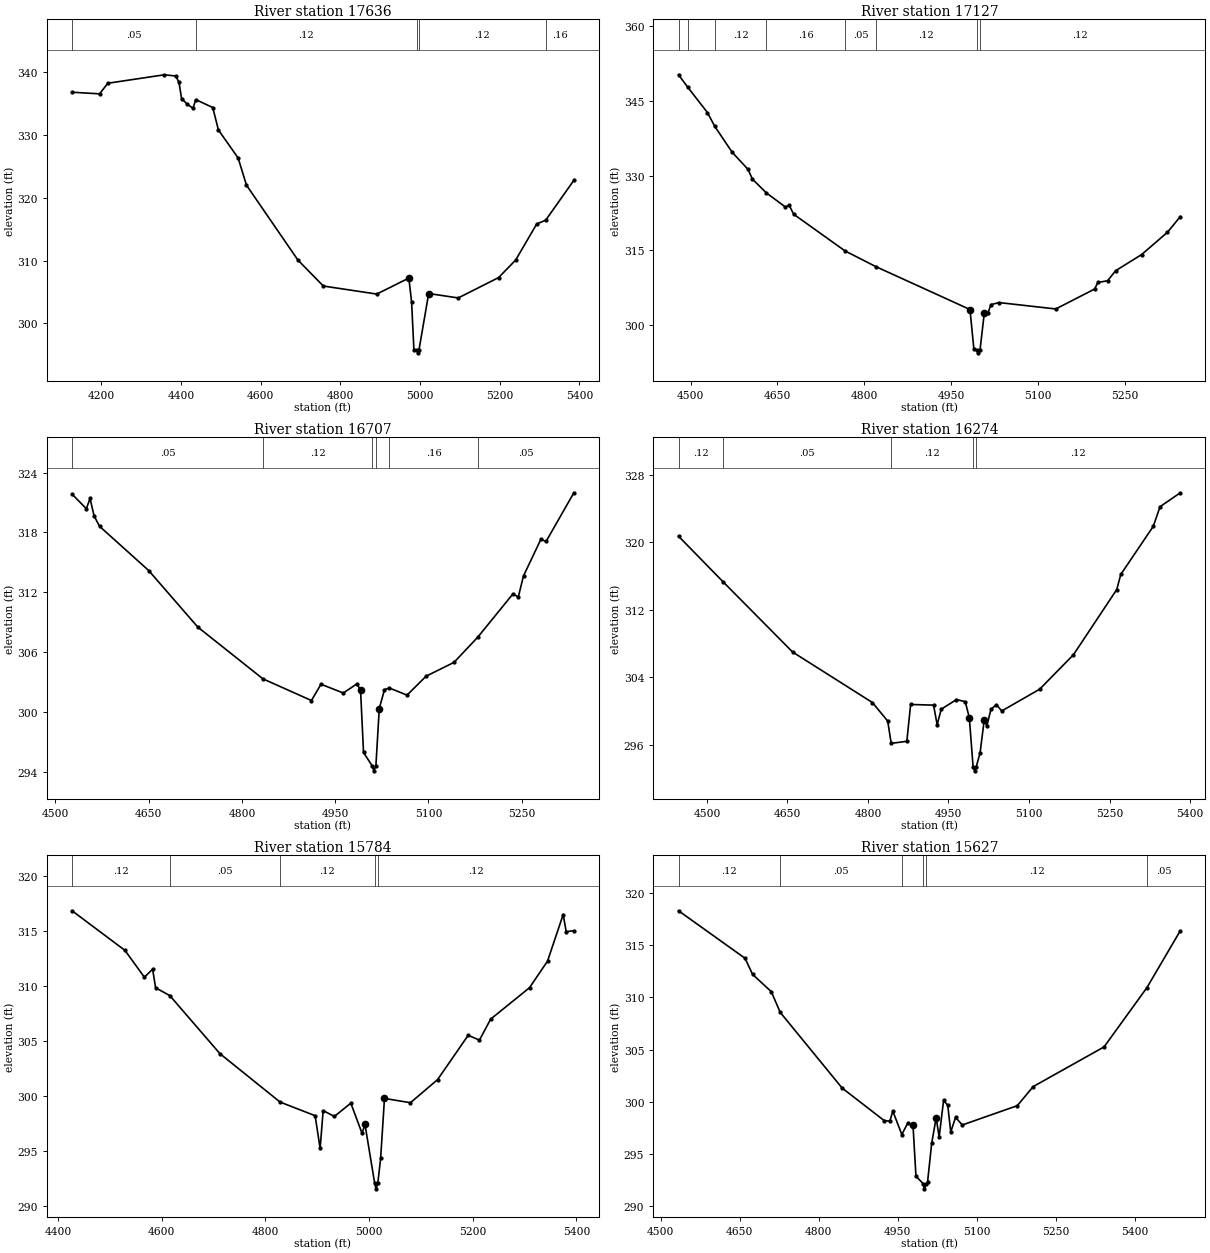
Type RM Length L Ch R = 1 ,17636   ,509,509,509
BEGIN DESCRIPTION:
Mapping XS c3541d23
END DESCRIPTION:
XS GIS Cut Line= 3
      3725548.68     10640922.24      3725045.21     10641534.22
      3724643.13     10641772.01
#Sta/Elev= 30
  4126.7  336.85  4195.7  336.59  4216.5  338.28  4358.5  339.63  4387.2  339.43
  4395.1  338.42  4401.6  335.83  4415.9  334.93  4430.3   334.3  4437.2  335.67
  4479.8  334.41  4494.1  330.83  4543.6  326.36  4564.4  322.04  4693.5   310.1
  4757.4  305.95  4891.6  304.67  4972.1  307.22    4979   303.4  4984.8   295.8
  4991.6   295.8  4994.4   295.3  4997.6   295.8  5021.9  304.76    5096  304.05
  5197.4   307.3  5240.3   310.1    5293  315.84  5315.6  316.45  5386.3   322.8
#Mann= 5 ,-1 , 0
  4126.7     .05       0  4437.2     .12       0  4991.6     .07       0
  4997.6     .12       0  5315.6     .16       0
Bank Sta=4972.1,5021.9
XS Rating Curve= 0 ,0
Exp/Cntr=0.3,0.1

Type RM Length L Ch R = 1 ,17127   ,420,420,420
BEGIN DESCRIPTION:
CHALYBEATE CREEK 37.0
END DESCRIPTION:
XS GIS Cut Line= 3
      3725149.63     10640810.17      3724749.61     10641160.19
      3724599.63     10641460.15
#Sta/Elev= 30
  4479.1  350.27  4494.7  347.82    4529  342.69  4541.7  339.91  4571.7  334.72
  4599.2  331.27  4606.8  329.31  4630.7  326.57  4663.7  323.72  4670.4  324.04
    4678  322.27  4766.8   314.9    4820  311.75  4982.6  303.14  4989.3  295.21
  4993.9  294.94  4996.6  294.44  4999.9  294.94  5007.3   302.4  5013.4   302.4
    5019  304.13    5033  304.53  5130.8  303.25  5197.9  307.25  5203.5  308.57
  5220.3  308.91  5234.2  310.93    5279  314.16  5323.7  318.64    5346   321.8
#Mann= 8 ,-1 , 0
  4479.1     .05       0  4494.7     .16       0  4541.7     .12       0
  4630.7     .16       0  4766.8     .05       0    4820     .12       0
  4993.9     .07       0  4999.9     .12       0
Bank Sta=4982.6,5007.3
XS Rating Curve= 0 ,0
Exp/Cntr=0.3,0.1

Type RM Length L Ch R = 1 ,16707   ,433,433,433
BEGIN DESCRIPTION:
CHALYBEATE CREEK 36.0
END DESCRIPTION:
XS GIS Cut Line= 3
      3724849.61     10640660.19      3724449.61     10640910.19
      3724149.62     10641060.18
#Sta/Elev= 30
  4526.8  321.84  4549.8  320.38  4555.7  321.42  4562.2  319.66    4571  318.62
    4650  314.19    4729  308.52  4833.8  303.33  4911.8  301.16  4927.2  302.79
  4963.1  301.91  4984.9  302.83  4990.8   302.2  4995.6  295.95  5009.5  294.61
  5012.2  294.11  5015.5  294.61  5020.9  300.35  5029.3  302.25  5037.2  302.41
  5065.6   301.7  5096.3   303.6  5141.1  304.98  5179.5  307.52  5236.1  311.86
  5244.5  311.53  5252.9  313.65  5280.8  317.31  5289.2   317.1  5333.9  321.98
#Mann= 6 ,-1 , 0
  4526.8     .05       0  4833.8     .12       0  5009.5     .07       0
  5015.5     .12       0  5037.2     .16       0  5179.5     .05       0
Bank Sta=4990.8,5020.9
XS Rating Curve= 0 ,0
Exp/Cntr=0.3,0.1

Type RM Length L Ch R = 1 ,16274   ,490,490,490
BEGIN DESCRIPTION:
CHALYBEATE CREEK 35.0
END DESCRIPTION:
XS GIS Cut Line= 3
      3724649.59      10640210.2      3724249.61     10640560.19
      3723849.61     10640610.19
#Sta/Elev= 30
  4447.2  320.73  4529.6  315.36  4659.8  306.99  4808.3  301.01  4836.8  298.81
  4843.3  296.17  4872.4  296.41  4879.5  300.78  4922.2   300.7  4928.9  298.38
  4936.5  300.22  4964.9  301.36  4981.2  301.11  4988.8  299.22  4995.8  293.41
  4998.6  292.91  5001.8  293.41  5008.9  295.07  5016.5  298.91  5021.5  298.25
  5029.1  300.21  5039.2  300.75  5049.2  300.01  5119.8  302.59  5182.8  306.68
  5263.4  314.41  5270.9   316.2  5331.4   321.9    5344  324.23  5381.8  325.88
#Mann= 5 ,-1 , 0
  4447.2     .12       0  4529.6     .05       0  4843.3     .12       0
  4995.8     .07       0  5001.8     .12       0
Bank Sta=4988.8,5016.5
XS Rating Curve= 0 ,0
Exp/Cntr=0.3,0.1

Type RM Length L Ch R = 1 ,15784   ,157,157,157
BEGIN DESCRIPTION:
Mapping XS a230113b
END DESCRIPTION:
XS GIS Cut Line= 2
      3724537.37     10639837.19       3723695.4     10640314.59
#Sta/Elev= 30
  4427.1  316.87  4529.1  313.27  4566.6  310.83  4582.5  311.56  4588.2  309.87
  4615.6  309.16  4712.3  303.88  4828.3  299.48  4895.9  298.24  4905.6  295.26
  4911.4  298.71    4933  298.17  4964.8  299.38  4986.4  296.64  4992.1  297.45
  5010.8  292.09  5013.5  291.59  5016.8  292.09  5022.3  294.37  5029.7  299.81
  5079.8  299.42  5132.1  301.52  5191.2  305.55  5212.9  305.11  5234.5  307.02
  5309.5  309.88  5344.2  312.29  5374.4  316.53  5380.2  314.97    5395  315.06
#Mann= 5 ,-1 , 0
  4427.1     .12       0  4615.6     .05       0  4828.3     .12       0
  5010.8     .07       0  5016.8     .12       0
Bank Sta=4992.1,5029.7
XS Rating Curve= 0 ,0
Exp/Cntr=0.3,0.1

Type RM Length L Ch R = 1 ,15627   ,95,95,95
BEGIN DESCRIPTION:
CHALYBEATE CREEK 34.0
END DESCRIPTION:
XS GIS Cut Line= 2
      3724463.64     10639754.69      3723623.07     10640200.98
#Sta/Elev= 30
  4534.2  318.32  4660.4  313.76  4674.6  312.22  4710.1  310.56  4727.1  308.57
  4844.5  301.31  4924.2  298.19  4934.9  298.13  4940.6   299.1  4957.7  296.85
    4969  297.96  4978.9  297.72  4984.5  292.86  4997.9  292.14  5000.6  291.64
  5003.9  292.14  5006.5  292.29  5014.3     296  5022.8  298.45  5028.5  296.61
  5036.9  300.13  5044.8  299.65  5050.5   297.1  5059.6  298.49  5072.5  297.77
  5176.7  299.62  5206.8  301.45  5341.3  305.26  5422.6  310.95  5485.9  316.41
#Mann= 6 ,-1 , 0
  4534.2     .12       0  4727.1     .05       0  4957.7     .12       0
  4997.9     .07       0  5003.9     .12       0  5422.6     .05       0
Bank Sta=4978.9,5022.8
XS Rating Curve= 0 ,0
Exp/Cntr=0.3,0.1

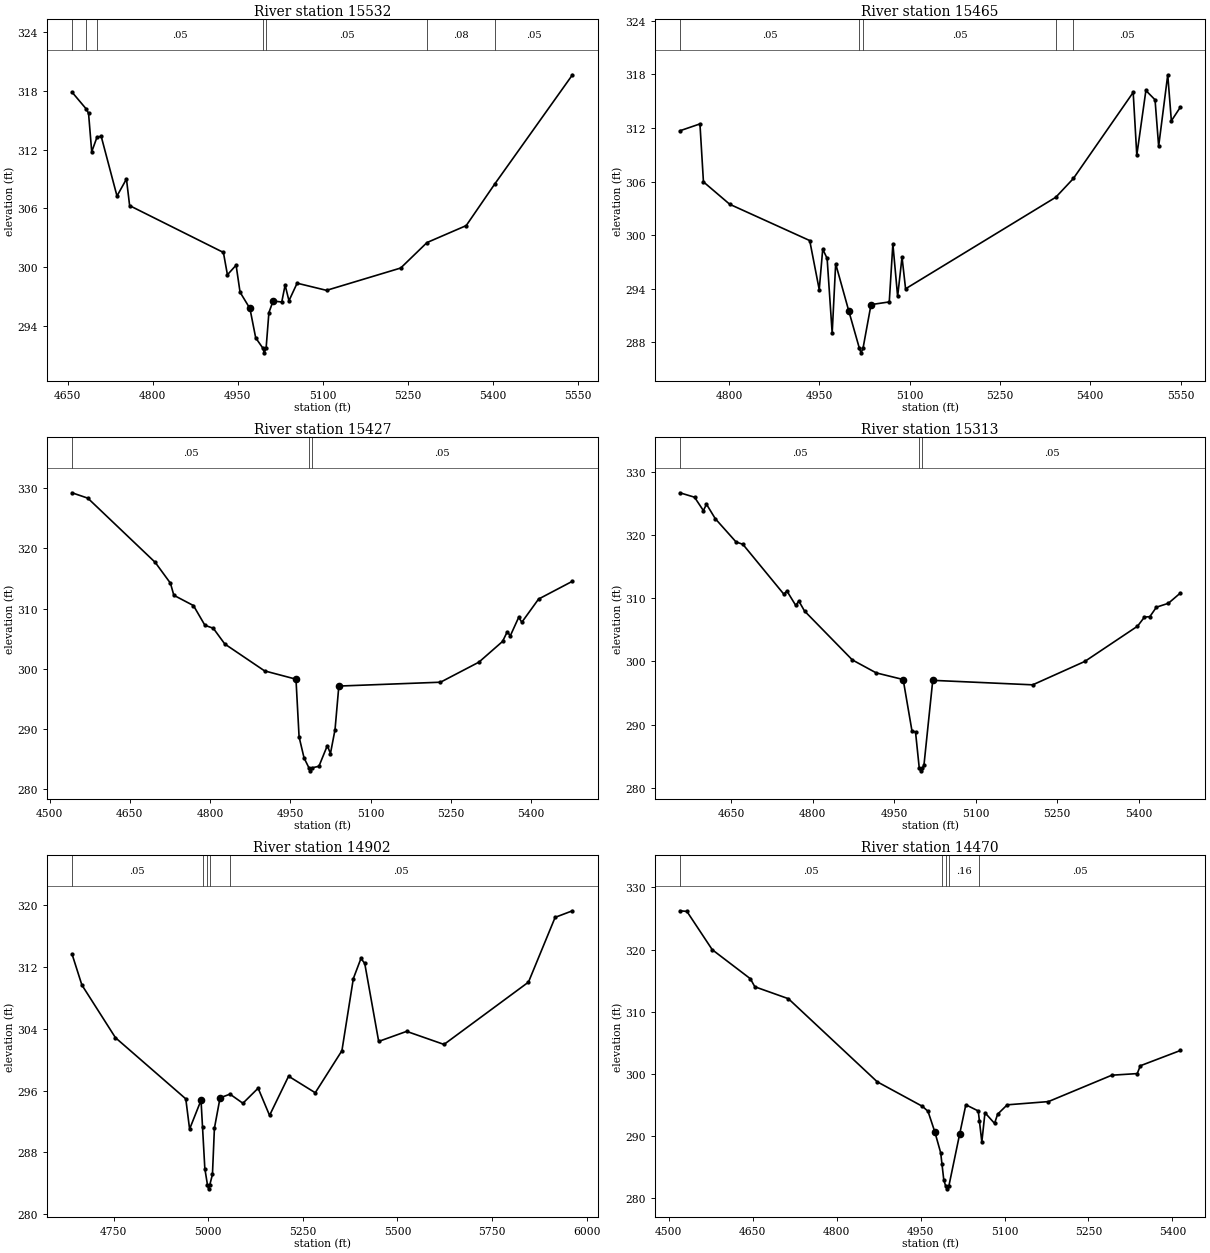
Type RM Length L Ch R = 1 ,15532   ,67,67,67
BEGIN DESCRIPTION:
Mapping XS c195475f
END DESCRIPTION:
XS GIS Cut Line= 3
      3724328.05     10639730.68      3724051.39     10639870.64
      3723565.27     10640174.46
#Sta/Elev= 30
  4657.3  317.87  4682.4  316.15  4686.5   315.7  4692.1  311.78  4701.3  313.25
  4708.8  313.36  4736.7  307.26  4753.4     309    4759  306.28  4924.5   301.5
  4931.6  299.22  4946.9   300.2  4953.9  297.44  4971.3  295.78  4981.5  292.78
  4993.9  291.75  4996.6  291.25  4999.9  291.75  5004.8  295.36  5012.2  296.54
  5027.5  296.44  5033.4  298.17  5040.2  296.57  5054.6  298.36  5106.5  297.63
  5237.4  299.91  5283.8  302.51    5353  304.24  5403.4  308.49  5540.6  319.64
#Mann= 7 ,-1 , 0
  4657.3     .08       0  4682.4     .12       0  4701.3     .05       0
  4993.9     .04       0  4999.9     .05       0  5283.8     .08       0
  5403.4     .05       0
Bank Sta=4971.3,5012.2
XS Rating Curve= 0 ,0
Exp/Cntr=0.3,0.1

Type RM Length L Ch R = 1 ,15465   ,38,38,38
BEGIN DESCRIPTION:
Mapping XS 53256b01
END DESCRIPTION:
XS GIS Cut Line= 3
      3724241.27     10639687.27      3723976.52     10639840.26
      3723535.21     10640125.43
#Sta/Elev= 30
  4718.6  311.68  4751.9  312.45  4757.7  305.96  4801.4  303.45  4934.2  299.39
    4950   293.9  4955.8  298.43  4963.1  297.39  4971.5  289.02  4977.3  296.79
  4998.9  291.55  5016.7  287.32  5019.4  286.82  5022.7  287.32    5036  292.22
  5066.3  292.52  5072.3  299.01  5080.2  293.14  5087.5  297.53  5093.4  293.99
  5342.9  304.24  5372.1  306.34  5471.4  315.98  5477.4  308.95  5492.5  316.19
  5507.7  315.15  5513.7  309.95  5528.8  317.95  5534.8  312.79  5549.8  314.33
#Mann= 5 ,-1 , 0
  4718.6     .05       0  5016.7     .04       0  5022.7     .05       0
  5342.9     .08       0  5372.1     .05       0
Bank Sta=4998.9,5036
XS Rating Curve= 0 ,0
Exp/Cntr=0.3,0.1

Type RM Length L Ch R = 1 ,15427   ,114,114,114
BEGIN DESCRIPTION:
CHALYBEATE CREEK 33.0
END DESCRIPTION:
XS GIS Cut Line= 2
      3724363.79     10639572.42      3723556.75     10640045.35
#Sta/Elev= 30
  4541.9  329.23  4571.4  328.34  4697.4  317.68  4725.9  314.22  4732.2  312.22
  4768.9  310.51  4790.3  307.24    4806  306.74  4827.5  304.13  4901.8  299.67
  4960.5  298.29  4966.3  288.72  4975.6  285.22  4984.7  283.58  4987.5  283.08
  4990.7  283.58  5003.4  283.84  5019.1  287.27  5024.9  285.94  5033.5  289.93
  5040.6  297.15  5230.6  297.79  5302.4  301.12  5346.5  304.55  5355.3  306.14
  5361.1   305.5  5376.8  308.57  5382.6  307.74  5413.9  311.59  5477.3  314.55
#Mann= 3 ,-1 , 0
  4541.9     .05       0  4984.7     .03       0  4990.7     .05       0
Bank Sta=4960.5,5040.6
XS Rating Curve= 0 ,0
Exp/Cntr=0.3,0.1

Type RM Length L Ch R = 1 ,15313   ,411,411,411
BEGIN DESCRIPTION:
Mapping XS 7e5be606
END DESCRIPTION:
XS GIS Cut Line= 2
       3724311.7     10639494.29      3723500.06     10639928.32
#Sta/Elev= 30
    4556  326.68  4582.9  325.98  4599.2  323.86  4604.9  324.87  4621.1  322.58
  4659.3   318.9  4671.8  318.53  4747.1  310.65  4752.8  311.15  4769.1  308.86
  4774.7  309.56  4785.2  307.98  4873.1  300.25    4917   298.2  4966.6  297.15
  4982.8  289.01  4989.3  288.86  4996.1  283.21  4998.8  282.71  5002.1  283.21
  5004.8  283.59    5021  297.02  5204.8  296.31  5300.6  300.01  5397.5  305.58
  5410.3  307.02  5420.2  307.09  5432.3  308.59  5454.2   309.2  5476.4  310.83
#Mann= 3 ,-1 , 0
    4556     .05       0  4996.1     .03       0  5002.1     .05       0
Bank Sta=4966.6,5021
XS Rating Curve= 0 ,0
Exp/Cntr=0.3,0.1

Type RM Length L Ch R = 1 ,14902   ,432,432,432
BEGIN DESCRIPTION:
CHALYBEATE CREEK 32.0
END DESCRIPTION:
XS GIS Cut Line= 2
      3724168.45     10639368.42      3722853.99     10639216.58
#Sta/Elev= 30
  4639.5  313.66  4665.6  309.65  4754.4  302.83  4940.3  294.92  4950.4  291.01
  4980.6  294.74  4984.6  291.24  4990.7  285.89  4997.7  283.78  5000.5  283.28
  5003.7  283.78  5010.8  285.14    5016  291.12  5030.9  295.05  5057.2  295.53
  5091.3  294.35  5131.6   296.3  5161.8  292.78  5212.1  297.85  5282.6  295.71
  5353.1  301.15  5383.3  310.48  5403.4  313.08  5413.4  312.45  5450.3  302.35
  5524.2  303.65    5623  301.96  5846.3  310.02  5916.8   318.4  5962.7  319.25
#Mann= 5 ,-1 , 0
  4639.5     .05       0  4984.6     .16       0  4997.7     .07       0
  5003.7     .16       0  5057.2     .05       0
Bank Sta=4980.6,5030.9
XS Rating Curve= 0 ,0
Exp/Cntr=0.3,0.1

Type RM Length L Ch R = 1 ,14470   ,481,481,481
BEGIN DESCRIPTION:
Mapping XS ab3994b3
END DESCRIPTION:
XS GIS Cut Line= 2
      3724320.39     10639138.39      3723513.87     10638752.47
#Sta/Elev= 30
  4520.1  326.24  4532.6  326.14  4577.9  319.97  4645.9   315.3    4654     314
  4713.9  312.08  4872.6   298.7  4953.3  294.75  4963.3  293.95  4975.5  290.63
    4986  287.26  4988.2  285.52  4991.5  282.91  4994.7  281.96  4997.4  281.46
  5000.7  281.96  5019.8  290.25  5030.9     295  5053.1     294  5055.2  292.36
  5059.5     289  5065.1  293.72  5082.2     292  5087.7  293.48  5104.8  294.99
  5178.4  295.51  5291.7  299.76  5337.1  300.02  5342.6  301.28  5414.2  303.74
#Mann= 5 ,-1 , 0
  4520.1     .05       0  4988.2     .16       0  4994.7     .07       0
  5000.7     .16       0  5055.2     .05       0
Bank Sta=4975.5,5019.8
XS Rating Curve= 0 ,0
Exp/Cntr=0.3,0.1