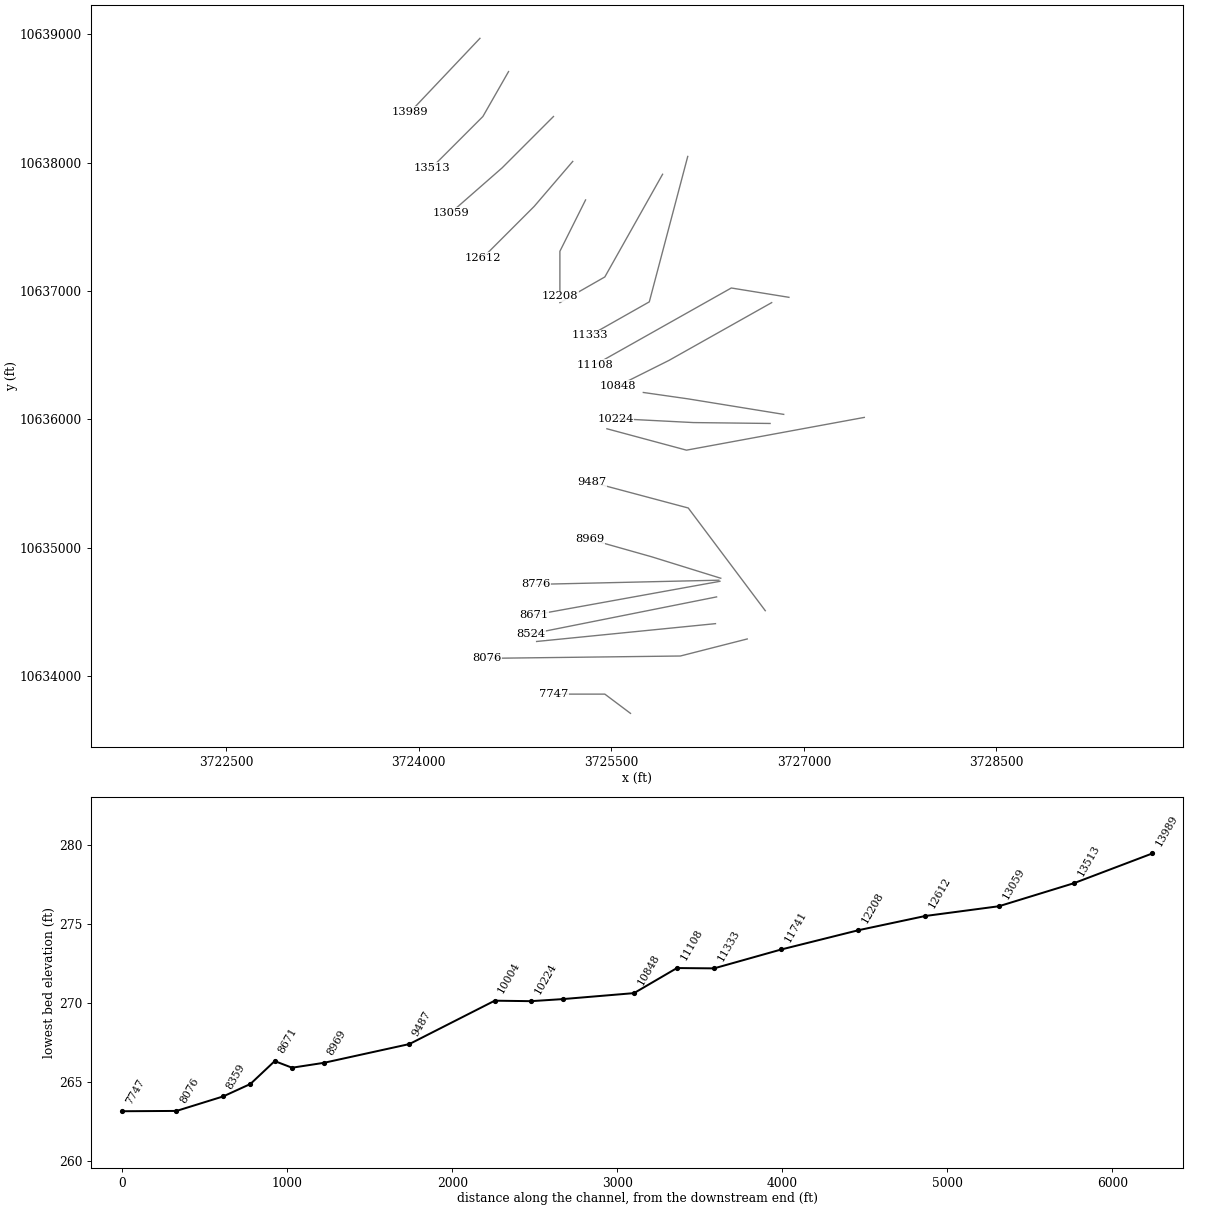
HEC-RAS study CHALYBEATE CREEK.prj: CHALYBEATE CREEK Base Level Engineering

--- CHALYBEATE CREEK.g01 (geometry) --- (continued)

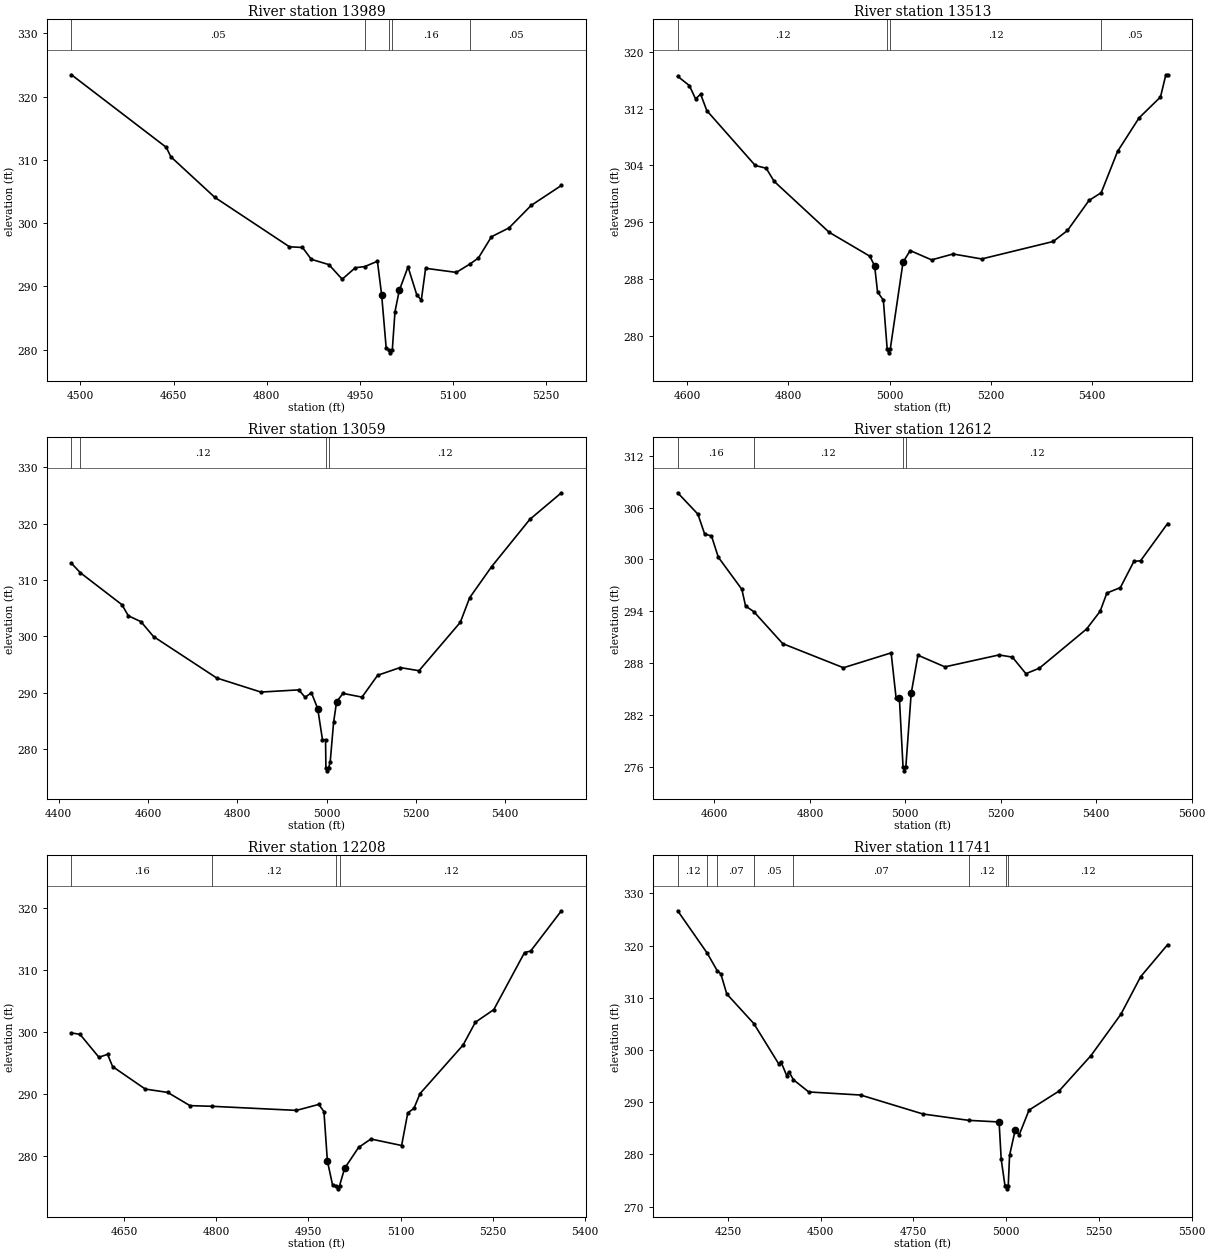
Type RM Length L Ch R = 1 ,13989   ,476,476,476
BEGIN DESCRIPTION:
Mapping XS 51e77e71
END DESCRIPTION:
XS GIS Cut Line= 2
      3724476.66     10638969.14      3723934.35     10638396.46
#Sta/Elev= 30
  4485.7  323.45  4638.4  311.97  4645.6  310.49  4716.4  304.07  4836.6  296.25
  4857.6  296.14  4871.8  294.27  4900.1  293.43  4921.5  291.12  4942.6  292.94
  4957.8  293.12  4978.2  293.96    4985  288.67  4992.3  280.27  4996.2  279.98
    4999  279.48  5002.2  279.98  5006.5  285.99  5013.4  289.35  5027.5  293.07
  5041.7  288.61  5048.9  287.83  5055.8  292.85  5105.2   292.2  5127.1  293.52
  5140.8  294.48  5161.8  297.84  5190.1  299.24  5225.7  302.79  5274.4  305.95
#Mann= 5 ,-1 , 0
  4485.7     .05       0  4957.8     .16       0  4996.2     .07       0
  5002.2     .16       0  5127.1     .05       0
Bank Sta=4985,5013.4
XS Rating Curve= 0 ,0
Exp/Cntr=0.3,0.1

Type RM Length L Ch R = 1 ,13513   ,454,454,454
BEGIN DESCRIPTION:
CHALYBEATE CREEK 29.0
END DESCRIPTION:
XS GIS Cut Line= 3
      3724699.63     10638710.22      3724499.61     10638360.19
      3724099.63     10637960.21
#Sta/Elev= 30
    4581  316.55  4604.1  315.25  4616.3  313.38  4626.4  314.03  4638.6  311.72
  4734.4  303.99    4756   303.6  4771.8  301.75  4880.5  294.58  4961.1   291.2
  4970.5  289.81  4976.2  286.18  4987.7  285.01  4995.3  278.09    4998  277.59
  5001.3  278.09  5026.6  290.36  5040.7     292  5083.1  290.69  5125.6  291.52
  5182.1  290.82  5323.6  293.28  5351.8  294.83  5394.3  299.06  5418.5  300.15
  5450.8  305.97  5493.3  310.69  5535.7  313.64  5546.3  316.77  5549.8  316.77
#Mann= 4 ,-1 , 0
    4581     .12       0  4995.3     .07       0  5001.3     .12       0
  5418.5     .05       0
Bank Sta=4970.5,5026.6
XS Rating Curve= 0 ,0
Exp/Cntr=0.3,0.1

Type RM Length L Ch R = 1 ,13059   ,447,447,447
BEGIN DESCRIPTION:
CHALYBEATE CREEK 28.0
END DESCRIPTION:
XS GIS Cut Line= 3
      3725049.59     10638360.17      3724649.61     10637960.19
      3724249.58     10637610.16
#Sta/Elev= 30
  4428.6  312.96  4448.6  311.28  4541.7  305.61  4555.9  303.65  4584.1  302.61
  4612.4  299.96  4753.8  292.61  4852.8  290.11  4937.7   290.5  4951.8  289.18
    4966  289.99  4980.1  287.15  4990.7  281.66  4997.6  281.66  4998.4  276.63
  5001.1  276.13  5004.4  276.63    5008   277.7  5015.6  284.73  5022.3  288.36
  5036.5  289.88  5079.2  289.21  5114.3  293.09  5164.6  294.46  5206.9   293.9
  5299.4  302.49  5320.3  306.85  5369.6  312.38  5455.1  320.76  5525.8  325.48
#Mann= 4 ,-1 , 0
  4428.6     .16       0  4448.6     .12       0  4998.4     .07       0
  5004.4     .12       0
Bank Sta=4980.1,5022.3
XS Rating Curve= 0 ,0
Exp/Cntr=0.3,0.1

Type RM Length L Ch R = 1 ,12612   ,404,404,404
BEGIN DESCRIPTION:
CHALYBEATE CREEK 27.0
END DESCRIPTION:
XS GIS Cut Line= 3
      3725199.64     10638010.22      3724899.61     10637660.19
      3724499.62     10637260.19
#Sta/Elev= 30
  4522.9  307.71  4565.2  305.24  4579.5  302.92  4593.7  302.72    4608  300.25
  4657.4  296.53  4665.1   294.6  4682.5  293.94    4743  290.24  4870.3  287.45
  4970.2  289.17  4980.6  283.95  4987.5  283.95  4995.1  276.01  4997.8  275.51
  5001.1  276.01  5012.2  284.47  5026.4   288.9  5082.9  287.55  5196.1  288.93
  5224.3  288.68  5252.6  286.76  5280.9   287.4  5379.9  291.94  5408.2  293.99
  5422.3   296.1  5450.6  296.73  5478.9  299.76    5493  299.84  5549.6  304.15
#Mann= 4 ,-1 , 0
  4522.9     .16       0  4682.5     .12       0  4995.1     .07       0
  5001.1     .12       0
Bank Sta=4987.5,5012.2
XS Rating Curve= 0 ,0
Exp/Cntr=0.3,0.1

Type RM Length L Ch R = 1 ,12208   ,467,467,467
BEGIN DESCRIPTION:
CHALYBEATE CREEK 26.0
END DESCRIPTION:
XS GIS Cut Line= 3
      3725299.59     10637710.15      3725099.61     10637310.19
      3725099.61     10636960.16
#Sta/Elev= 30
  4564.4  299.83  4578.3   299.6  4609.1  295.89  4623.1  296.37  4631.4  294.38
  4684.5  290.75  4720.9  290.21  4757.2  288.07  4793.6  287.96  4930.5   287.3
  4966.8  288.27  4975.2   287.1  4980.8  279.13  4989.2  275.25  4994.6  275.11
  4997.3  274.61  5000.6  275.11  5008.8  277.92  5031.6  281.31  5051.6  282.67
  5101.6  281.62  5111.6   286.9  5121.6  287.62  5131.6  290.02  5201.6  297.87
  5221.6  301.56  5251.6   303.6  5301.6  312.83  5311.6  313.08  5361.6  319.59
#Mann= 4 ,-1 , 0
  4564.4     .16       0  4793.6     .12       0  4994.6     .07       0
  5000.6     .12       0
Bank Sta=4980.8,5008.8
XS Rating Curve= 0 ,0
Exp/Cntr=0.3,0.1

Type RM Length L Ch R = 1 ,11741   ,408,408,408
BEGIN DESCRIPTION:
CHALYBEATE CREEK 25.0
END DESCRIPTION:
XS GIS Cut Line= 3
      3725899.61     10637910.19      3725449.61     10637110.19
       3725099.6     10636910.18
#Sta/Elev= 30
  4114.4  326.66  4194.1  318.53  4221.2  315.16  4230.7  314.59  4246.7  310.73
  4319.6  305.06  4386.9  297.32  4392.6  297.76  4408.6  295.04  4414.3  295.82
  4426.5  294.29  4467.8  291.95  4607.8  291.36  4775.7  287.73  4899.2  286.51
    4981   286.2  4986.7  279.04  4996.9     274  4999.6  273.89  5002.4  273.39
  5005.6  273.89  5009.3  279.82  5024.3   284.6  5035.2  283.73  5061.8  288.48
  5142.4  292.11  5228.8  298.92  5309.4  306.83  5362.7  314.03  5435.4  320.17
#Mann= 8 ,-1 , 0
  4114.4     .12       0  4194.1     .05       0  4221.2     .07       0
  4319.6     .05       0  4426.5     .07       0  4899.2     .12       0
  4999.6     .07       0  5005.6     .12       0
Bank Sta=4981,5024.3
XS Rating Curve= 0 ,0
Exp/Cntr=0.3,0.1

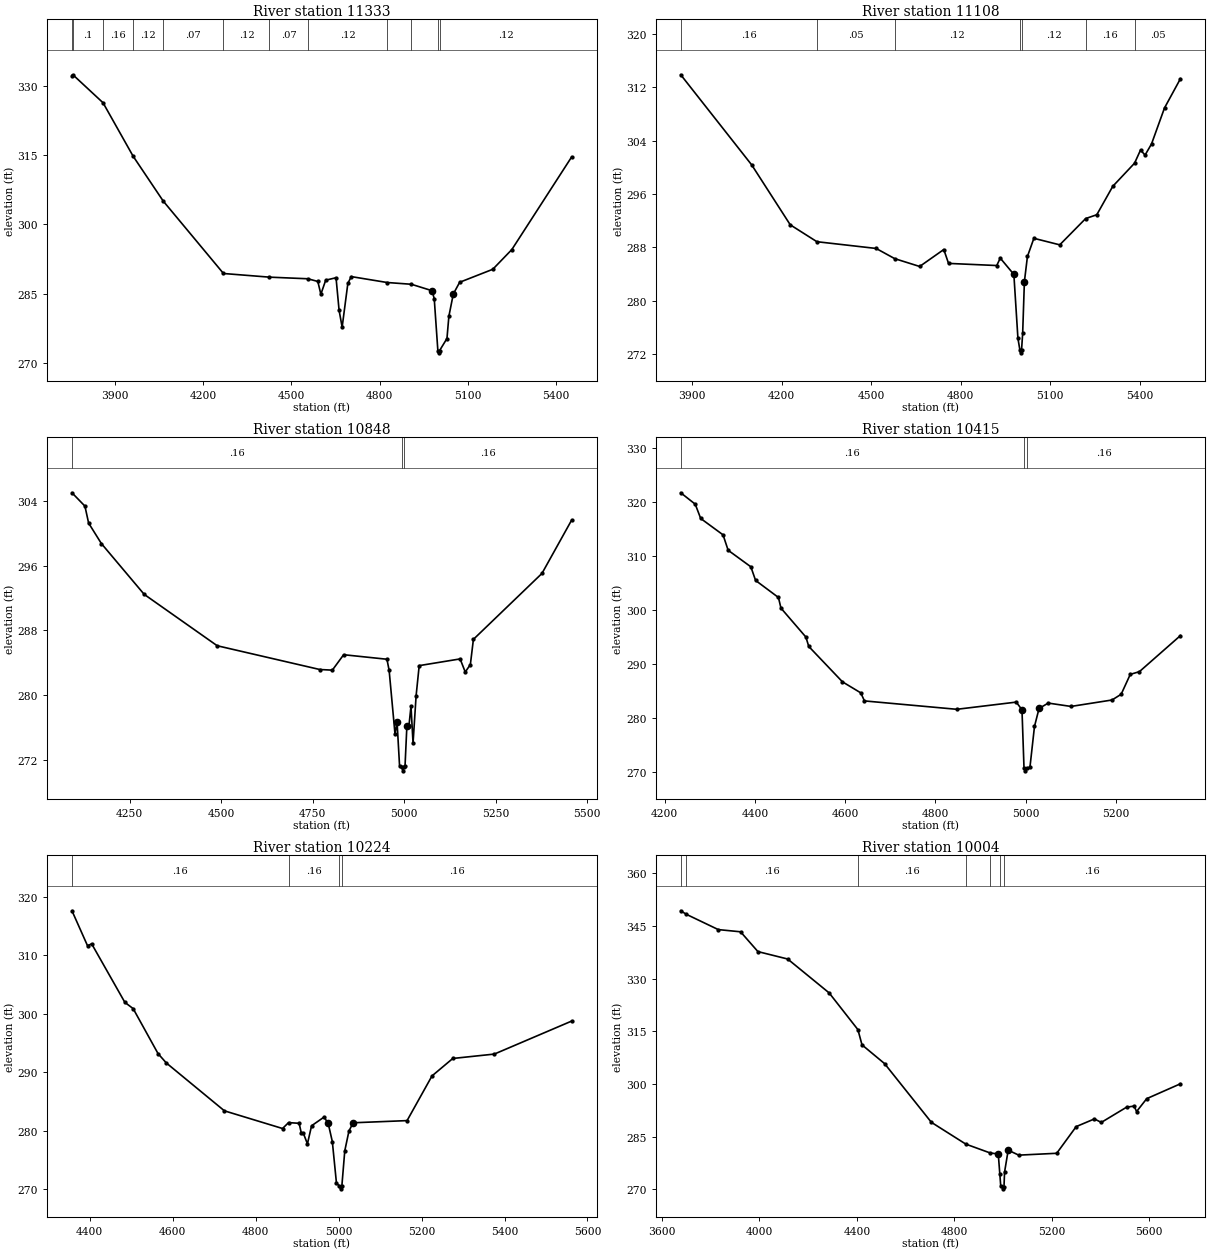
Type RM Length L Ch R = 1 ,11333   ,225,225,225
BEGIN DESCRIPTION:
CHALYBEATE CREEK 24.0
END DESCRIPTION:
XS GIS Cut Line= 3
      3726095.57     10638049.01      3725796.08     10636916.16
      3725336.03     10636655.76
#Sta/Elev= 30
    3753  332.17  3756.2  332.33  3858.7  326.28  3961.1  314.72  4063.6  305.01
  4268.6  289.35    4425  288.56  4555.6  288.21  4589.6  287.63    4600  284.87
  4616.5  287.91  4651.6  288.43    4662   281.4  4672.4  277.74  4691.8   287.2
  4703.4  288.68  4825.8   287.4  4908.1  287.02  4978.2  285.63  4985.8  283.92
  4998.1  272.69  5000.9  272.19  5004.1  272.69  5029.1  275.29  5035.6   280.1
  5050.7  284.92  5072.3  287.45    5185  290.26  5249.9  294.53  5453.4  314.56
#Mann= 12 ,-1 , 0
    3753     .05       0  3756.2      .1       0  3858.7     .16       0
  3961.1     .12       0  4063.6     .07       0  4268.6     .12       0
    4425     .07       0  4555.6     .12       0  4825.8     .16       0
  4908.1     .12       0  4998.1     .07       0  5004.1     .12       0
Bank Sta=4978.2,5050.7
XS Rating Curve= 0 ,0
Exp/Cntr=0.3,0.1

Type RM Length L Ch R = 1 ,11108   ,260,260,260
BEGIN DESCRIPTION:
Mapping XS 6f63784f
END DESCRIPTION:
XS GIS Cut Line= 3
     3726883.924      10636951.5       3726434.9     10637024.17
      3725373.06     10636426.07
#Sta/Elev= 30
 3861.26  313.87  4099.4  300.35  4228.4  291.39  4317.7  288.86  4516.3  287.85
  4578.7  286.32  4662.2  285.15  4743.1  287.69    4759  285.61  4920.6  285.29
  4932.4   286.4    4978  283.96  4991.6  274.39  4997.9  272.71  5000.7  272.21
  5003.9  272.71  5007.5  275.12  5013.3  282.87  5023.5  286.65  5045.1  289.37
  5131.8  288.39  5218.7  292.33    5256   292.9  5309.6  297.16  5382.7  300.63
  5402.6  302.59  5417.9  301.84  5439.6  303.52    5483   308.9  5536.4  313.28
#Mann= 7 ,-1 , 0
 3861.26     .16       0  4317.7     .05       0  4578.7     .12       0
  4997.9     .07       0  5003.9     .12       0  5218.7     .16       0
  5382.7     .05       0
Bank Sta=4978,5013.3
XS Rating Curve= 0 ,0
Exp/Cntr=0.3,0.1

Type RM Length L Ch R = 1 ,10848   ,433,433,433
BEGIN DESCRIPTION:
CHALYBEATE CREEK 23.0
END DESCRIPTION:
XS GIS Cut Line= 3
      3726749.59     10636910.18      3725949.61     10636460.19
      3725549.58     10636260.17
#Sta/Elev= 30
  4092.6  305.03    4128  303.38  4138.1  301.28  4172.9  298.75  4289.9  292.46
  4489.4   286.1  4769.5  283.16  4803.9  283.08  4834.8  284.99  4953.1  284.43
  4959.1  283.05  4975.1  275.18  4980.8  276.63  4987.5  271.28  4993.7  271.12
  4996.5  270.62  4999.7  271.12  5002.5  271.21  5007.6   276.2  5013.2   276.2
  5018.8  278.62  5024.4  274.04  5032.8  279.93  5041.2  283.64    5153  284.47
    5167  282.85    5181  283.77  5189.3  286.89  5376.6  295.05  5457.7  301.65
#Mann= 3 ,-1 , 0
  4092.6     .16       0  4993.7     .07       0  4999.7     .16       0
Bank Sta=4980.8,5007.6
XS Rating Curve= 0 ,0
Exp/Cntr=0.3,0.1

Type RM Length L Ch R = 1 ,10415   ,191,191,191
BEGIN DESCRIPTION:
CHALYBEATE CREEK 22.0
END DESCRIPTION:
XS GIS Cut Line= 3
      3726843.23     10636039.55      3726099.61     10636160.19
       3725749.6     10636210.19
#Sta/Elev= 30
  4235.7  321.66  4267.8  319.55  4279.9  316.91  4329.4  313.88  4340.7  311.03
    4391  307.97  4401.5  305.45  4452.1   302.3  4457.7  300.33  4512.9  294.98
  4519.3  293.24  4593.9   286.7  4634.5  284.66  4642.6  283.17  4847.2  281.62
  4978.9  282.95  4991.6  281.54  4996.1  270.74  4998.9  270.24  5002.1  270.74
  5009.2  270.87  5019.3  278.45  5029.4  281.77  5049.7  282.77  5100.2  282.15
  5191.1  283.34  5211.3   284.4  5231.5  288.08  5251.7  288.58  5342.6  295.25
#Mann= 3 ,-1 , 0
  4235.7     .16       0  4996.1     .07       0  5002.1     .16       0
Bank Sta=4991.6,5029.4
XS Rating Curve= 0 ,0
Exp/Cntr=0.3,0.1

Type RM Length L Ch R = 1 ,10224   ,220,220,220
BEGIN DESCRIPTION:
Mapping XS 7682331f
END DESCRIPTION:
XS GIS Cut Line= 3
      3726737.12     10635968.76      3726139.94      10635975.7
      3725533.47     10636006.89
#Sta/Elev= 30
  4357.3  317.63  4394.8  311.66  4404.8  311.98  4484.8  301.98  4504.8  300.91
  4564.8  293.22  4584.8  291.62  4724.8  283.44  4864.9  280.42  4879.4  281.43
  4904.9  281.31    4910  279.68    4915  279.62  4924.9   277.8  4934.9  280.89
  4964.9  282.37  4974.9  281.31  4984.9  278.19  4994.9  271.06  5001.9  270.61
  5004.7  270.11  5007.9  270.61  5014.9   276.6  5024.9  279.97    5035   281.4
  5165.1  281.77  5225.2  289.41  5275.3  292.39  5375.4  293.14  5561.8  298.78
#Mann= 4 ,-1 , 0
  4357.3     .16       0  4879.4     .16       0  5001.9     .07       0
  5007.9     .16       0
Bank Sta=4974.9,5035
XS Rating Curve= 0 ,0
Exp/Cntr=0.3,0.1

Type RM Length L Ch R = 1 ,10004   ,517,517,517
BEGIN DESCRIPTION:
CHALYBEATE CREEK 21.0
END DESCRIPTION:
XS GIS Cut Line= 3
      3727471.09     10636015.98      3726085.72     10635760.78
      3725465.92     10635927.45
#Sta/Elev= 30
  3677.4  349.36  3700.5  348.35  3831.4     344  3922.9  343.37  3994.1  337.73
  4116.1  335.62  4286.4  325.96  4404.4   315.5  4421.2  311.16  4513.8  305.82
  4705.9  289.09  4847.3  282.88  4947.2  280.36  4980.4  280.07  4986.6  274.48
  4990.6  270.87  5000.5  270.14  5003.8  270.64  5006.2  274.91  5021.1  281.16
  5064.3  279.74  5220.2  280.27  5300.1  287.87  5374.9  290.06  5403.1  289.06
  5506.6  293.39  5537.7  293.72    5548  292.16  5589.5  295.83  5727.9  300.07
#Mann= 7 ,-1 , 0
  3677.4     .16       0  3700.5     .16       0  4404.4     .16       0
  4847.3     .16       0  4947.2     .16       0  4986.6     .12       0
  5003.8     .16       0
Bank Sta=4980.4,5021.1
XS Rating Curve= 0 ,0
Exp/Cntr=0.3,0.1

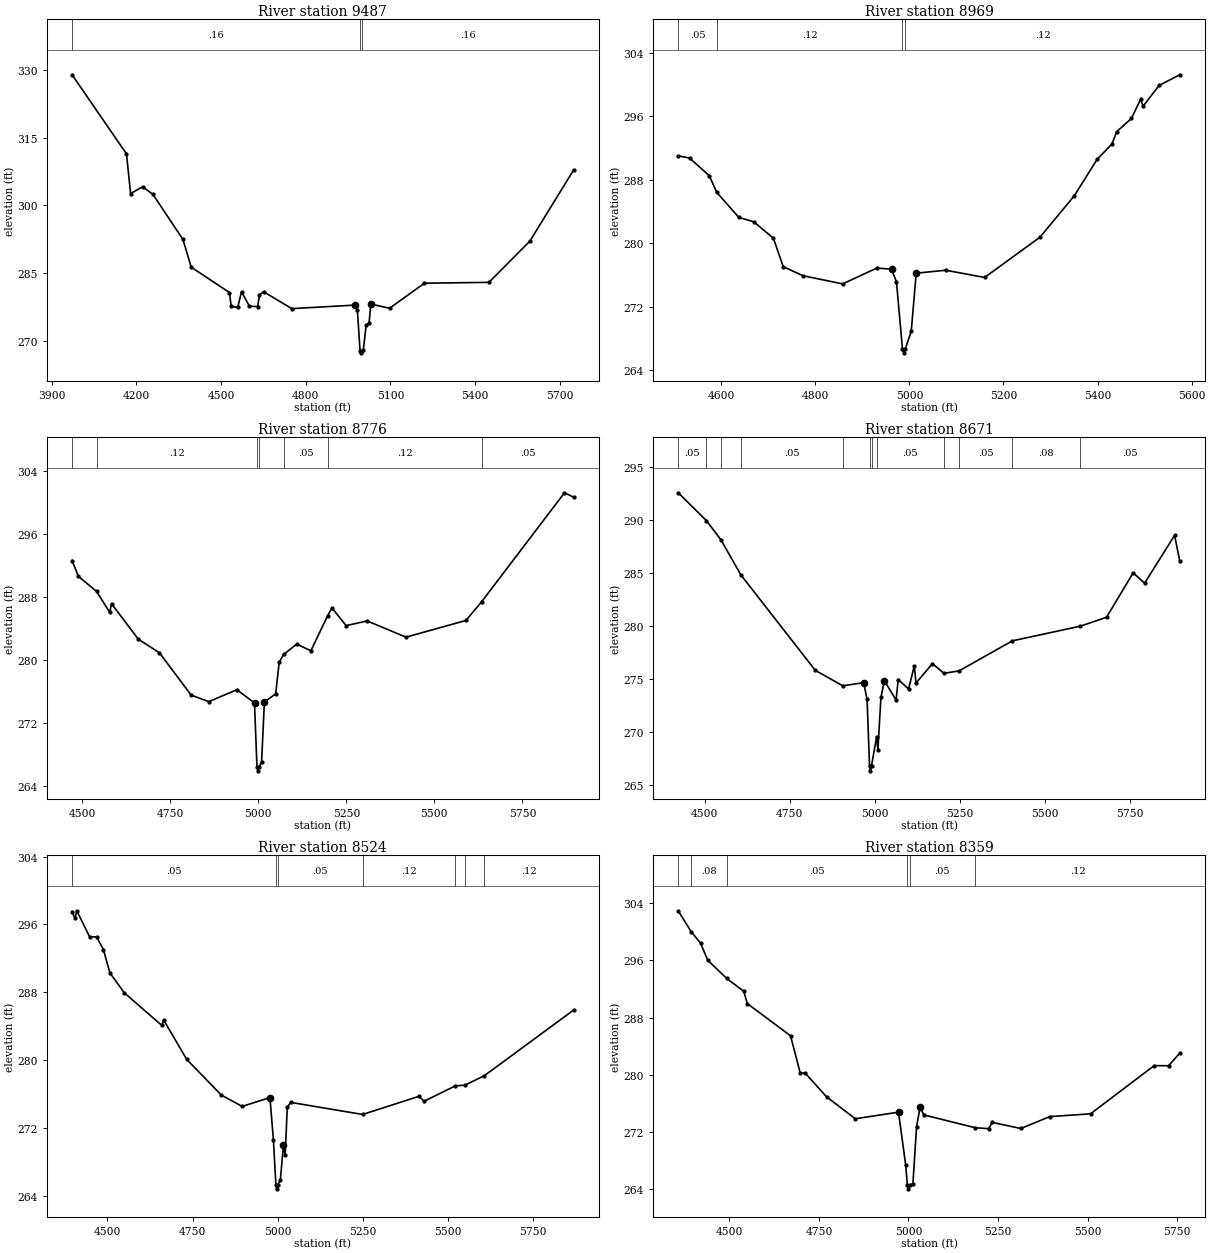
Type RM Length L Ch R = 1 ,9487    ,518,518,518
BEGIN DESCRIPTION:
CHALYBEATE CREEK 20.0
END DESCRIPTION:
XS GIS Cut Line= 3
      3726699.62     10634510.18      3726099.61     10635310.19
      3725349.63     10635510.18
#Sta/Elev= 30
  3972.5  328.89  4165.2   311.4  4179.8  302.63  4222.5  304.11    4259  302.43
  4365.2  292.46  4394.4  286.34  4529.8  280.73  4536.1  277.66    4559  277.44
  4572.5   280.9  4600.6  277.69  4629.8  277.63  4636.1  280.22  4650.6   280.9
  4750.6  277.17  4975.1  277.95  4982.9  276.76  4992.2  267.89  4994.9  267.39
  4998.2  267.89  5003.6  267.94  5013.9  273.46  5024.3  273.92  5030.1  278.18
  5096.7  277.25  5220.3  282.79  5448.6  282.98  5593.5  292.09  5748.7  307.85
#Mann= 3 ,-1 , 0
  3972.5     .16       0  4992.2     .07       0  4998.2     .16       0
Bank Sta=4975.1,5030.1
XS Rating Curve= 0 ,0
Exp/Cntr=0.3,0.1

Type RM Length L Ch R = 1 ,8969    ,193,193,193
BEGIN DESCRIPTION:
CHALYBEATE CREEK 19.0
END DESCRIPTION:
XS GIS Cut Line= 3
      3726352.85     10634762.91      3725814.62     10634930.02
      3725330.64     10635066.75
#Sta/Elev= 30
  4508.4  291.01  4532.7  290.72  4574.6  288.49  4590.2  286.41  4637.4  283.25
  4668.9   282.7  4710.7  280.64  4731.7  277.05  4773.6  275.91    4858  274.88
  4930.6  276.87    4962  276.74  4972.5  275.11  4985.2   266.7    4988   266.2
  4991.2   266.7  5003.9  268.92  5014.4  276.23  5077.2   276.6  5159.8  275.69
  5277.4  280.75  5350.5  285.97  5399.3  290.58  5430.5  292.49  5440.9  294.06
  5472.1  295.72  5491.6  298.14  5496.8  297.25  5530.8  299.87  5574.9  301.21
#Mann= 4 ,-1 , 0
  4508.4     .05       0  4590.2     .12       0  4985.2     .07       0
  4991.2     .12       0
Bank Sta=4962,5014.4
XS Rating Curve= 0 ,0
Exp/Cntr=0.3,0.1

Type RM Length L Ch R = 1 ,8776    ,105,105,105
BEGIN DESCRIPTION:
Mapping XS d4cc1686
END DESCRIPTION:
XS GIS Cut Line= 2
      3726337.62     10634747.73      3724913.49     10634715.21
#Sta/Elev= 30
  4471.1  292.65  4489.1  290.64  4540.7  288.72  4578.2  286.04  4583.2  287.16
  4659.2  282.64  4719.2  280.92  4809.2  275.53  4859.2  274.69  4939.2  276.21
  4989.2  274.53  4996.2  266.39    4999  265.89  5002.2  266.39  5009.3  267.01
  5017.3  274.66  5049.3  275.68  5059.3   279.7    5072   280.7  5109.3  282.02
  5149.3  281.16  5197.1  285.65  5209.3  286.61  5249.3  284.37  5309.3  284.96
  5419.4   282.9  5589.4  285.02  5633.9  287.39  5869.5  301.27  5895.6  300.71
#Mann= 7 ,-1 , 0
  4471.1     .05       0  4540.7     .12       0  4996.2     .07       0
  5002.2     .12       0    5072     .05       0  5197.1     .12       0
  5633.9     .05       0
Bank Sta=4989.2,5017.3
XS Rating Curve= 0 ,0
Exp/Cntr=0.3,0.1

Type RM Length L Ch R = 1 ,8671    ,147,147,147
BEGIN DESCRIPTION:
CHALYBEATE CREEK 18.0
END DESCRIPTION:
XS GIS Cut Line= 2
      3726346.26     10634739.04      3724894.51     10634476.47
#Sta/Elev= 30
  4422.1  292.53  4505.2   289.9  4547.5  288.11  4606.3  284.79  4825.2  275.79
  4905.8  274.33  4967.5  274.62  4977.6  273.06  4984.8  266.81  4987.5  266.31
  4990.8  266.81  5005.7  269.54  5009.4  268.26  5018.3  273.23  5028.4  274.81
  5062.9  272.98  5069.1  274.92  5099.6  274.03  5116.4  276.19  5121.5  274.59
  5169.9  276.42  5203.4  275.51  5247.9  275.73    5405  278.57  5604.7  279.95
  5681.9  280.79  5760.1  284.98  5793.9  284.01  5882.1  288.52  5897.4  286.06
#Mann= 12 ,-1 , 0
  4422.1     .05       0  4505.2     .12       0  4547.5     .08       0
  4606.3     .05       0  4905.8     .08       0  4984.8     .07       0
  4990.8     .08       0  5005.7     .05       0  5203.4     .12       0
  5247.9     .05       0    5405     .08       0  5604.7     .05       0
Bank Sta=4967.5,5028.4
XS Rating Curve= 0 ,0
Exp/Cntr=0.3,0.1

Type RM Length L Ch R = 1 ,8524    ,165,165,165
BEGIN DESCRIPTION:
Mapping XS d93d5ee3
END DESCRIPTION:
XS GIS Cut Line= 2
      3726320.26     10634617.52      3724873.73     10634329.08
#Sta/Elev= 30
  4395.8  297.52  4404.6  296.72  4409.7  297.61  4447.4  294.54  4467.8  294.54
  4488.2  293.02  4506.8  290.31  4549.4  287.95  4659.9   284.1    4665  284.76
    4733   280.1  4834.9   275.9  4896.1  274.57  4977.7  275.61  4987.9  270.59
  4995.1  265.36  4997.8  264.86  5001.1  265.36  5008.3  265.91  5017.4  269.98
  5022.5  268.82  5028.7   274.5  5038.9  275.04  5250.2  273.62  5416.1  275.76
    5431  275.17  5523.1     277  5550.5  277.06  5608.3  278.19  5870.8  285.92
#Mann= 7 ,-1 , 0
  4395.8     .05       0  4995.1     .03       0  5001.1     .05       0
  5250.2     .12       0  5523.1     .08       0  5550.5     .05       0
  5608.3     .12       0
Bank Sta=4977.7,5017.4
XS Rating Curve= 0 ,0
Exp/Cntr=0.3,0.1

Type RM Length L Ch R = 1 ,8359    ,283,283,283
BEGIN DESCRIPTION:
Mapping XS 3d60819a
END DESCRIPTION:
XS GIS Cut Line= 2
      3726311.61     10634409.19      3724918.32     10634270.29
#Sta/Elev= 30
  4357.2  302.95  4393.5  300.02  4419.5  298.43  4439.6  296.04  4492.5  293.49
  4540.1   291.7  4550.2  289.97  4670.8  285.47  4697.9  280.24  4710.9   280.3
  4771.2  276.94  4851.6  273.87  4972.2  274.79  4992.3  267.34  4996.9  264.57
  4999.6  264.07  5002.9  264.57  5012.4   264.8  5022.5  272.74  5032.5  275.52
  5042.6  274.41  5185.8  272.62  5223.5  272.48  5233.5  273.36  5313.9  272.51
  5394.3  274.17  5508.2  274.56  5685.8   281.3    5726  281.28  5757.4  283.05
#Mann= 6 ,-1 , 0
  4357.2     .05       0  4393.5     .08       0  4492.5     .05       0
  4996.9     .03       0  5002.9     .05       0  5185.8     .12       0
Bank Sta=4972.2,5032.5
XS Rating Curve= 0 ,0
Exp/Cntr=0.3,0.1

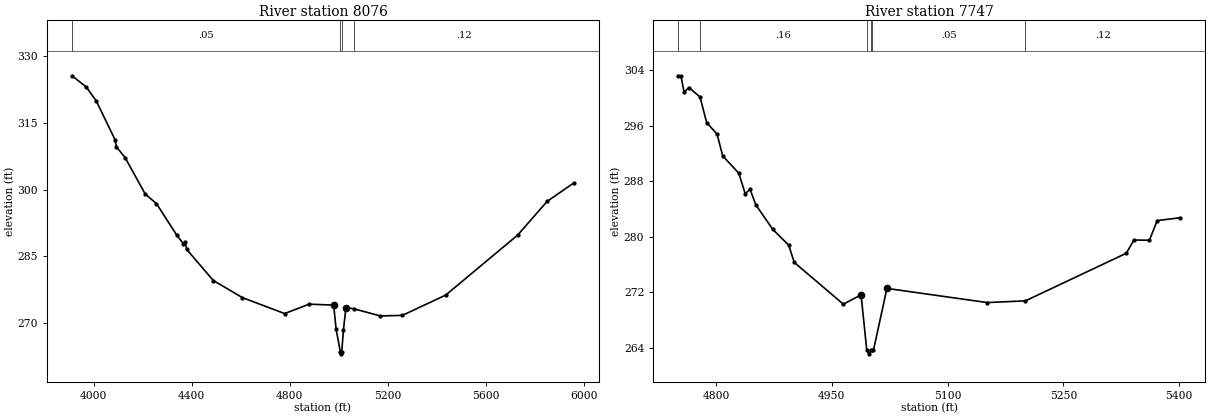
Type RM Length L Ch R = 1 ,8076    ,329,329,329
BEGIN DESCRIPTION:
CHALYBEATE CREEK 17.0
END DESCRIPTION:
XS GIS Cut Line= 3
      3726559.07     10634289.93      3726038.25     10634157.12
      3724530.45      10634138.9
#Sta/Elev= 30
  3912.3  325.56  3970.2  323.04  4011.1  319.89  4087.2  311.23  4092.9  309.62
  4128.5  307.19  4210.3  299.03  4256.4  296.86  4338.1  289.86  4365.8  287.88
  4373.8  288.34    4379  286.61  4488.4  279.59  4606.7  275.77  4778.5  272.19
  4878.5   274.3  4978.5  274.09  4988.5  268.67  5005.5  263.65  5008.2  263.15
  5011.5  263.65  5018.5  268.59  5028.5  273.54  5061.3  273.25  5168.5  271.66
  5258.5  271.78  5435.3  276.34  5728.5  289.81  5848.5  297.37  5957.7  301.52
#Mann= 4 ,-1 , 0
  3912.3     .05       0  5005.5     .03       0  5011.5     .05       0
  5061.3     .12       0
Bank Sta=4978.5,5028.5
XS Rating Curve= 0 ,0
Exp/Cntr=0.3,0.1

Type RM Length L Ch R = 1 ,7747    ,495,495,495
BEGIN DESCRIPTION:
CHALYBEATE CREEK 16.0
END DESCRIPTION:
XS GIS Cut Line= 3
      3725649.61     10633710.19      3725449.61     10633860.19
      3725049.61     10633860.19
#Sta/Elev= 30
  4751.5  303.16  4754.6  303.16  4758.8   300.8    4765  301.47  4779.4  300.11
    4788  296.43  4801.5  294.75  4808.8  291.63  4829.6  289.14    4838  286.16
  4844.2  286.84  4851.5  284.62  4873.4  281.08  4894.2  278.78  4901.5  276.29
    4965  270.28    4988  271.62  4995.4  263.63  4998.1  263.13  5001.4  263.63
  5001.7  263.63    5004  263.63  5021.5  272.55  5151.5  270.51  5200.9  270.76
  5331.5  277.61  5341.5  279.52  5361.5  279.48  5371.5  282.31  5401.5  282.73
#Mann= 6 ,-1 , 0
  4751.5     .05       0  4779.4     .16       0  4995.4     .07       0
  5001.4     .16       0  5001.7     .05       0  5200.9     .12       0
Bank Sta=4988,5021.5
XS Rating Curve= 0 ,0
Exp/Cntr=0.3,0.1