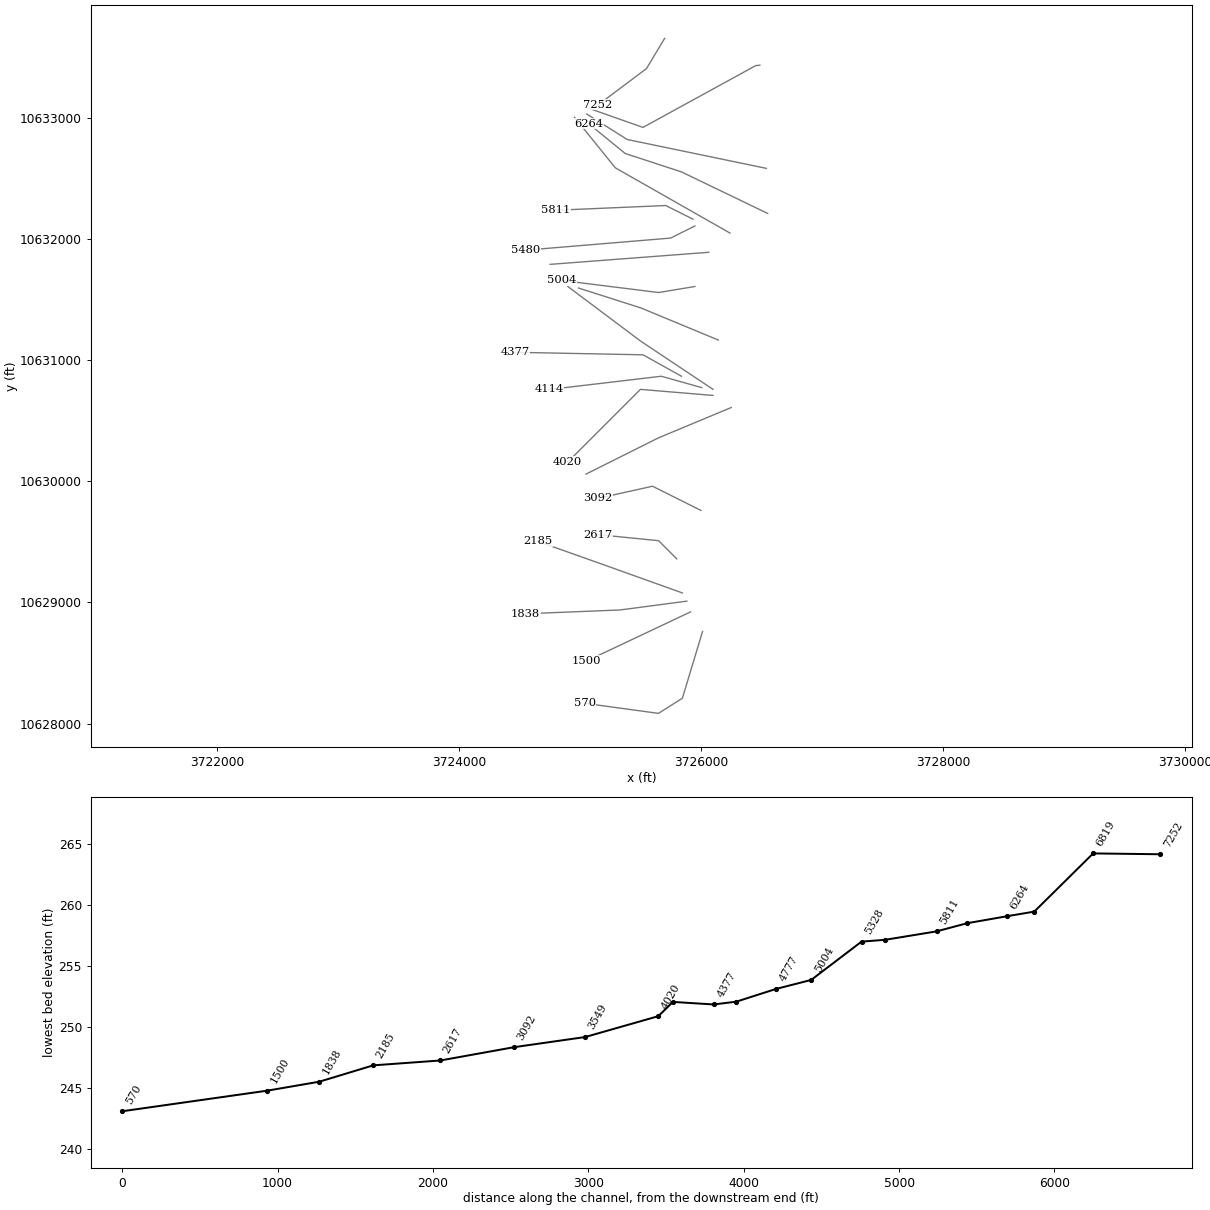
HEC-RAS study CHALYBEATE CREEK.prj: CHALYBEATE CREEK Base Level Engineering

--- CHALYBEATE CREEK.g01 (geometry) --- (continued)

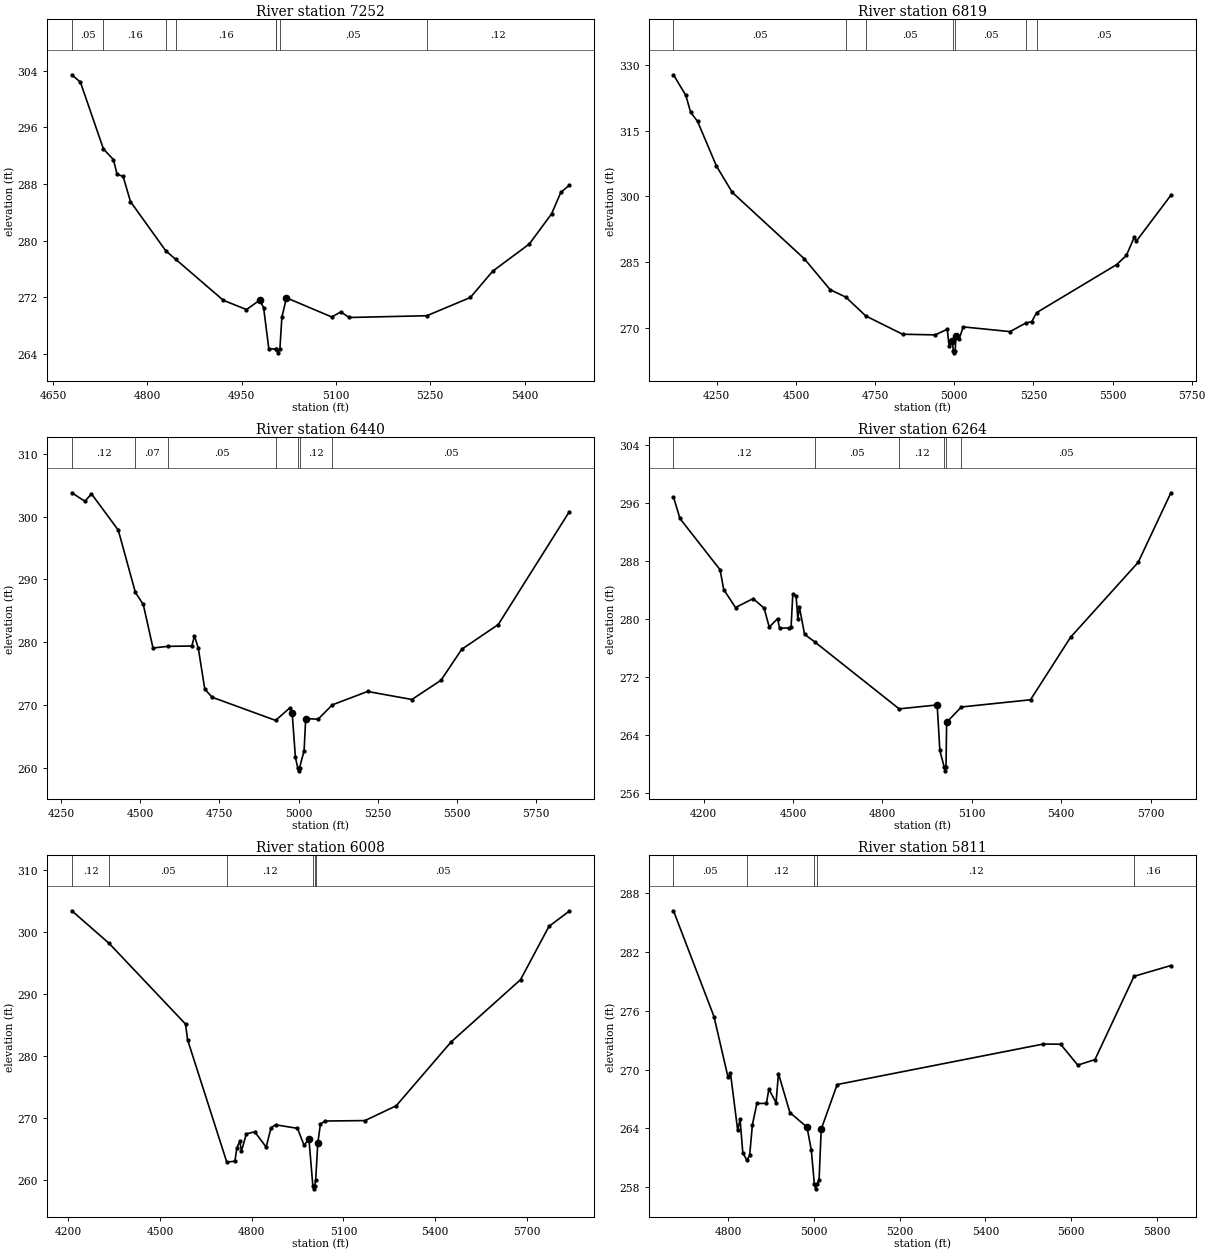
Type RM Length L Ch R = 1 ,7252    ,433,433,433
BEGIN DESCRIPTION:
CHALYBEATE CREEK 15.0
END DESCRIPTION:
XS GIS Cut Line= 3
       3725699.6     10633660.18      3725549.61     10633410.19
      3725149.64     10633110.21
#Sta/Elev= 30
  4679.7  303.43  4693.3  302.39    4730  292.95  4745.8  291.46  4751.6  289.39
  4761.3  289.07    4773  285.52  4829.2  278.57  4844.9  277.38  4920.7  271.59
  4957.6  270.28  4978.5   271.6  4984.8  270.57  4993.1  264.76  5004.2   264.7
  5004.7  264.67  5007.4  264.17  5010.7  264.67  5013.9  269.19  5021.2  271.94
  5093.1  269.24  5107.7  269.94  5121.2  269.16  5244.6  269.41  5313.9  271.99
  5349.4   275.7  5407.7  279.54  5443.1   283.8  5457.7  286.81  5471.2  287.84
#Mann= 8 ,-1 , 0
  4679.7     .05       0    4730     .16       0  4829.2     .05       0
  4844.9     .16       0  5004.2     .05       0  5004.7     .07       0
  5010.7     .05       0  5244.6     .12       0
Bank Sta=4978.5,5021.2
XS Rating Curve= 0 ,0
Exp/Cntr=0.3,0.1

Type RM Length L Ch R = 1 ,6819    ,379,379,379
BEGIN DESCRIPTION:
CHALYBEATE CREEK 14.0
END DESCRIPTION:
XS GIS Cut Line= 4
      3726486.12     10633438.74      3726451.37      10633434.4
      3725520.38     10632924.42      3725072.84     10633082.25
#Sta/Elev= 30
  4113.3  327.76  4152.2  323.06  4167.5  319.19  4189.3  317.12    4249  306.91
  4298.6  300.93  4526.8  285.71  4608.4  278.65  4657.4  276.98  4720.9  272.66
  4836.9  268.49  4940.2  268.34  4978.1  269.64  4983.8   265.8  4994.1  266.89
  4996.9  264.74  4999.7  264.24  5002.9  264.74  5005.6  268.14    5016  267.49
  5028.3  270.17  5176.5  269.09  5226.4  271.06    5245  271.38  5260.2  273.42
  5512.9  284.39  5543.8  286.48  5569.4  290.78  5574.7   289.7  5684.4  300.24
#Mann= 7 ,-1 , 0
  4113.3     .05       0  4657.4     .12       0  4720.9     .05       0
  4996.9     .03       0  5002.9     .05       0  5226.4     .16       0
  5260.2     .05       0
Bank Sta=4994.1,5005.6
XS Rating Curve= 0 ,0
Exp/Cntr=0.3,0.1

Type RM Length L Ch R = 1 ,6440    ,176,176,176
BEGIN DESCRIPTION:
CHALYBEATE CREEK 13.0
END DESCRIPTION:
XS GIS Cut Line= 3
      3726540.35     10632585.88      3725390.17     10632824.59
      3725055.93     10633035.12
#Sta/Elev= 30
  4284.6  303.79  4325.8  302.43  4346.6  303.62  4431.1  297.84  4485.1   287.9
    4510  285.99  4540.7  279.05  4586.9  279.31  4663.2  279.37  4671.6  280.98
  4683.7     279  4704.1   272.5  4726.9  271.21  4927.6  267.51  4972.4   269.5
  4979.8  268.76  4990.1  261.62  4997.3  259.97    5000  259.47  5003.3  259.97
  5017.5  262.68  5022.6   267.8  5061.6   267.7  5106.7  269.99    5218  272.12
  5357.7  270.84  5449.6  273.91  5514.9  278.84  5630.3  282.79  5854.3  300.76
#Mann= 7 ,-1 , 0
  4284.6     .12       0  4485.1     .07       0  4586.9     .05       0
  4927.6     .12       0  4997.3     .07       0  5003.3     .12       0
  5106.7     .05       0
Bank Sta=4979.8,5022.6
XS Rating Curve= 0 ,0
Exp/Cntr=0.3,0.1

Type RM Length L Ch R = 1 ,6264    ,256,256,256
BEGIN DESCRIPTION:
Mapping XS 279a728d
END DESCRIPTION:
XS GIS Cut Line= 4
      3726550.39     10632213.93      3725838.55     10632556.83
      3725374.14     10632708.74       3725070.9     10632955.66
#Sta/Elev= 30
  4098.4  296.78  4120.1  293.82  4254.7  286.77    4267  284.04  4306.6  281.57
  4365.7  282.79  4402.7  281.48  4419.8  278.87  4447.9  280.04  4454.5  278.74
  4487.6  278.75  4493.2  278.94  4498.9  283.42    4510  283.13  4515.8  280.01
  4521.3   281.6  4538.4  277.88  4572.1  276.85  4855.9  267.62  4983.6  268.16
  4992.6   261.9  5007.2  259.59  5009.9  259.09  5013.2  259.59  5015.4  265.77
  5064.9  267.88  5296.9  268.87  5431.5  277.48  5658.4  287.79  5768.2  297.36
#Mann= 6 ,-1 , 0
  4098.4     .12       0  4572.1     .05       0  4855.9     .12       0
  5007.2     .07       0  5013.2     .12       0  5064.9     .05       0
Bank Sta=4983.6,5015.4
XS Rating Curve= 0 ,0
Exp/Cntr=0.3,0.1

Type RM Length L Ch R = 1 ,6008    ,197,197,197
BEGIN DESCRIPTION:
CHALYBEATE CREEK 12.0
END DESCRIPTION:
XS GIS Cut Line= 3
      3726238.72     10632052.01      3725292.51     10632590.22
      3724954.29     10633008.65
#Sta/Elev= 30
    4212  303.42    4334  298.15  4583.7  285.13  4590.6  282.57  4718.6  262.84
  4745.1  262.98  4751.7  265.13    4761  266.21  4766.7  264.62  4782.6  267.39
    4810  267.73  4847.5  265.26  4863.3  268.39  4878.2  268.86  4949.8  268.29
  4971.4  265.56  4987.3  266.55  5000.1  259.02  5002.9  258.52  5006.1  259.02
  5009.3  259.87  5016.3  265.91  5024.8  268.94  5039.3  269.47  5170.3  269.54
  5272.7  271.93  5452.4  282.25  5679.4   292.3  5772.2   300.9  5838.6  303.36
#Mann= 6 ,-1 , 0
    4212     .12       0    4334     .05       0  4718.6     .12       0
  5000.1     .07       0  5006.1     .12       0  5009.3     .05       0
Bank Sta=4987.3,5016.3
XS Rating Curve= 0 ,0
Exp/Cntr=0.3,0.1

Type RM Length L Ch R = 1 ,5811    ,331,331,331
BEGIN DESCRIPTION:
Mapping XS 66587707
END DESCRIPTION:
XS GIS Cut Line= 3
      3725934.02     10632166.21      3725708.34     10632279.05
       3724802.9     10632240.06
#Sta/Elev= 30
  4673.3  286.19  4767.7   275.4  4800.4  269.21    4806  269.65  4822.8  263.83
  4828.4  264.95  4834.8   261.5  4844.3  260.78  4850.7  261.25  4857.1  264.38
  4867.5  266.55  4889.9  266.56  4895.4  268.02  4912.2  266.63  4917.8   269.6
  4944.4  265.63  4984.4  264.13  4994.4  261.76  5001.4  258.35  5004.2  257.85
  5007.4  258.35  5012.4  258.76  5017.4  263.93  5054.5  268.48  5534.9  272.61
    5575  272.59    5615  270.46    5655  271.02    5746  279.51  5831.9  280.61
#Mann= 5 ,-1 , 0
  4673.3     .05       0  4844.3     .12       0  5001.4     .07       0
  5007.4     .12       0    5746     .16       0
Bank Sta=4984.4,5017.4
XS Rating Curve= 0 ,0
Exp/Cntr=0.3,0.1

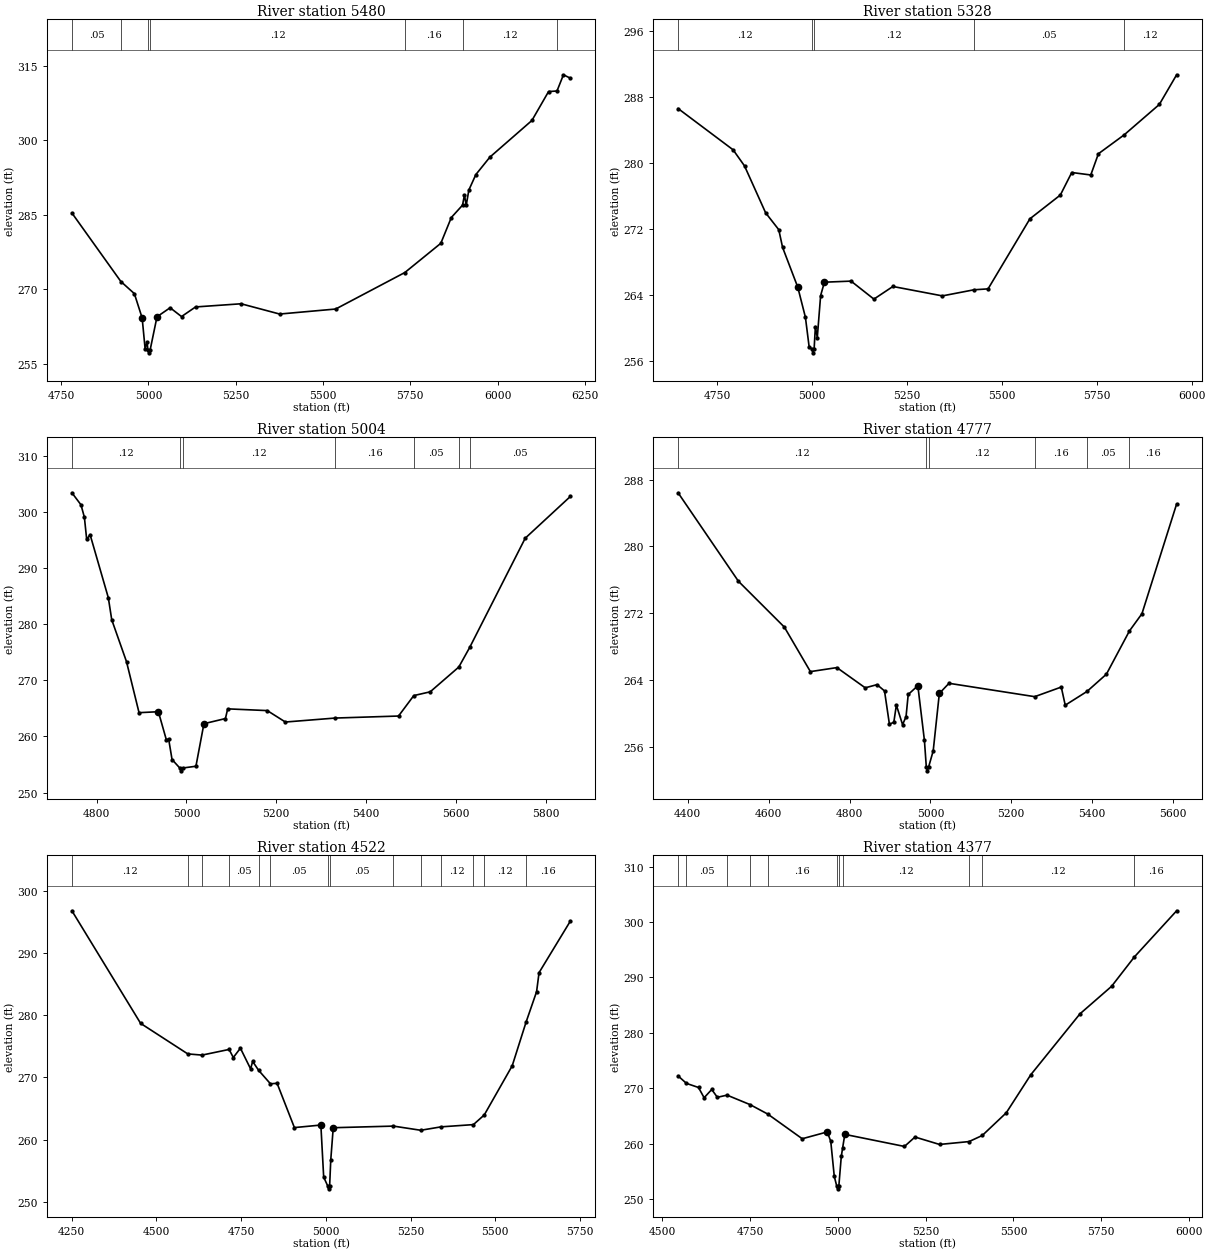
Type RM Length L Ch R = 1 ,5480    ,152,152,152
BEGIN DESCRIPTION:
CHALYBEATE CREEK 11.0
END DESCRIPTION:
XS GIS Cut Line= 3
      3725949.61     10632110.19      3725749.61     10632010.19
      3724549.58     10631910.19
#Sta/Elev= 30
  4780.8  285.35    4921  271.54  4959.7  269.09    4982  264.18  4990.4  258.01
    4996  259.35  4998.6  257.66  5001.4  257.16  5004.6  257.66  5024.5  264.43
  5062.1  266.25  5094.7  264.47  5134.9  266.41  5265.3  267.05  5375.7  264.98
  5536.2  265.99  5734.3  273.35  5837.3  279.24  5867.4  284.44  5899.5  286.93
    5905  288.98    5910  286.89  5917.6  289.98  5937.6  293.09  5977.8  296.61
  6098.2     304  6145.9  309.83    6170  309.94  6188.5  313.21  6208.6  312.51
#Mann= 7 ,-1 , 0
  4780.8     .05       0    4921     .12       0  4998.6     .07       0
  5004.6     .12       0  5734.3     .16       0  5899.5     .12       0
    6170     .05       0
Bank Sta=4982,5024.5
XS Rating Curve= 0 ,0
Exp/Cntr=0.3,0.1

Type RM Length L Ch R = 1 ,5328    ,324,324,324
BEGIN DESCRIPTION:
Mapping XS 3ab53ad7
END DESCRIPTION:
XS GIS Cut Line= 2
      3726064.21     10631892.76        3724754.     10631792.98
#Sta/Elev= 30
  4646.5  286.61  4791.5  281.61  4821.6  279.66  4877.3  273.97  4911.9  271.93
  4921.9  269.79    4962  264.96  4982.1  261.32  4992.1  257.67  4999.1  257.51
  5001.9  257.01  5005.1  257.51  5008.4   260.2  5013.4  258.86  5022.2  263.95
  5032.2  265.57  5102.4   265.7  5162.6  263.52  5212.7  265.05  5343.1  263.91
  5426.5  264.65  5463.5  264.76  5573.8  273.25    5654  276.13  5684.1  278.86
  5734.2  278.56  5754.3  281.13  5822.2  283.42  5914.8   287.1  5960.5   290.7
#Mann= 5 ,-1 , 0
  4646.5     .12       0  4999.1     .07       0  5005.1     .12       0
  5426.5     .05       0  5822.2     .12       0
Bank Sta=4962,5032.2
XS Rating Curve= 0 ,0
Exp/Cntr=0.3,0.1

Type RM Length L Ch R = 1 ,5004    ,227,227,227
BEGIN DESCRIPTION:
CHALYBEATE CREEK 10.0
END DESCRIPTION:
XS GIS Cut Line= 3
      3725949.57     10631610.18      3725649.61     10631560.19
      3724849.63     10631660.19
#Sta/Elev= 30
  4744.9  303.49  4765.1  301.34  4772.7  299.12  4777.8  295.18  4785.4  296.02
    4826  284.76  4833.6  280.83  4866.5  273.35  4894.4  264.25  4937.5  264.42
  4955.2  259.41  4960.3  259.57  4967.9  255.89  4985.2  254.37  4987.9  253.87
  4991.2  254.37  5021.1  254.69  5038.9  262.28  5086.8   263.2  5091.8  264.93
    5180  264.62  5220.3  262.58  5331.2  263.29  5472.3  263.65  5506.3   267.3
  5542.8  267.97  5606.5  272.39  5630.7  275.88  5754.4  295.38  5855.2  302.85
#Mann= 7 ,-1 , 0
  4744.9     .12       0  4985.2     .07       0  4991.2     .12       0
  5331.2     .16       0  5506.3     .05       0  5606.5     .16       0
  5630.7     .05       0
Bank Sta=4937.5,5038.9
XS Rating Curve= 0 ,0
Exp/Cntr=0.3,0.1

Type RM Length L Ch R = 1 ,4777    ,255,255,255
BEGIN DESCRIPTION:
Mapping XS 627d6594
END DESCRIPTION:
XS GIS Cut Line= 3
      3726142.33     10631167.95      3725504.34     10631432.69
      3724987.87     10631597.62
#Sta/Elev= 30
    4376  286.42  4525.2  275.83  4638.8  270.34  4703.2  265.01  4768.7  265.49
  4838.8  263.07    4868  263.45  4886.5   262.7  4898.6  258.72  4909.5  258.94
  4915.8     261  4931.1  258.67  4939.7   259.6  4945.1  262.27  4968.9  263.32
  4985.2  256.77  4989.8  253.63  4992.6  253.13  4995.8  253.63  5006.9  255.52
  5022.1   262.4    5046  263.61  5257.9  262.01  5323.6  263.16  5333.4  260.99
  5387.1  262.63  5435.2   264.7  5492.2  269.88  5523.1  271.94  5608.9  285.08
#Mann= 6 ,-1 , 0
    4376     .12       0  4989.8     .07       0  4995.8     .12       0
  5257.9     .16       0  5387.1     .05       0  5492.2     .16       0
Bank Sta=4968.9,5022.1
XS Rating Curve= 0 ,0
Exp/Cntr=0.3,0.1

Type RM Length L Ch R = 1 ,4522    ,145,145,145
BEGIN DESCRIPTION:
CHALYBEATE CREEK 9.0
END DESCRIPTION:
XS GIS Cut Line= 3
      3726099.58     10630760.21      3725499.61     10631160.19
      3724899.59      10631610.2
#Sta/Elev= 30
  4250.9  296.81  4453.7   278.7  4592.8  273.79  4634.9   273.6  4714.8  274.51
  4727.1  273.21  4748.1  274.71  4778.2  271.38  4784.2  272.58    4802  271.14
  4836.8  268.98  4856.3  269.07  4907.4  261.94  4985.5  262.35  4993.8  253.98
  5005.4  252.59  5008.2  252.09  5011.4  252.59  5014.7  256.74    5022  261.92
  5199.6  262.18  5280.2  261.51  5340.3  262.06  5435.6  262.42  5467.6  263.97
  5550.1  271.88  5591.1  278.92    5622  283.79  5629.3  286.86    5722  295.18
#Mann= 14 ,-1 , 0
  4250.9     .12       0  4592.8     .05       0  4634.9     .16       0
  4714.8     .05       0    4802     .16       0  4836.8     .05       0
  5005.4     .03       0  5011.4     .05       0  5199.6     .12       0
  5280.2     .05       0  5340.3     .12       0  5435.6     .05       0
  5467.6     .12       0  5591.1     .16       0
Bank Sta=4985.5,5022
XS Rating Curve= 0 ,0
Exp/Cntr=0.3,0.1

Type RM Length L Ch R = 1 ,4377    ,263,263,263
BEGIN DESCRIPTION:
Mapping XS 29211c16
END DESCRIPTION:
XS GIS Cut Line= 3
      3725838.66     10630868.68      3725520.99     10631045.74
      3724464.18     10631066.56
#Sta/Elev= 30
  4544.5  272.24  4568.4  270.89  4602.7  270.15  4618.7   268.3  4640.4  269.79
  4656.4  268.38  4684.1  268.77  4749.6  267.06  4799.9  265.36  4898.3   260.9
  4969.6  262.13  4979.6  260.43  4989.6  254.11  4996.6  252.36  4999.3  251.86
  5002.6  252.36  5009.6  257.73  5013.5  259.27  5019.6  261.69  5189.6  259.51
  5219.6  261.21  5289.6  259.87  5373.7  260.39  5411.3  261.49  5479.7  265.58
  5549.7  272.46  5689.7  283.44  5779.7   288.4  5844.6   293.7  5965.2  302.04
#Mann= 11 ,-1 , 0
  4544.5     .12       0  4568.4     .05       0  4684.1     .16       0
  4749.6     .05       0  4799.9     .16       0  4996.6     .07       0
  5002.6     .16       0  5013.5     .12       0  5373.7     .16       0
  5411.3     .12       0  5844.6     .16       0
Bank Sta=4969.6,5019.6
XS Rating Curve= 0 ,0
Exp/Cntr=0.3,0.1

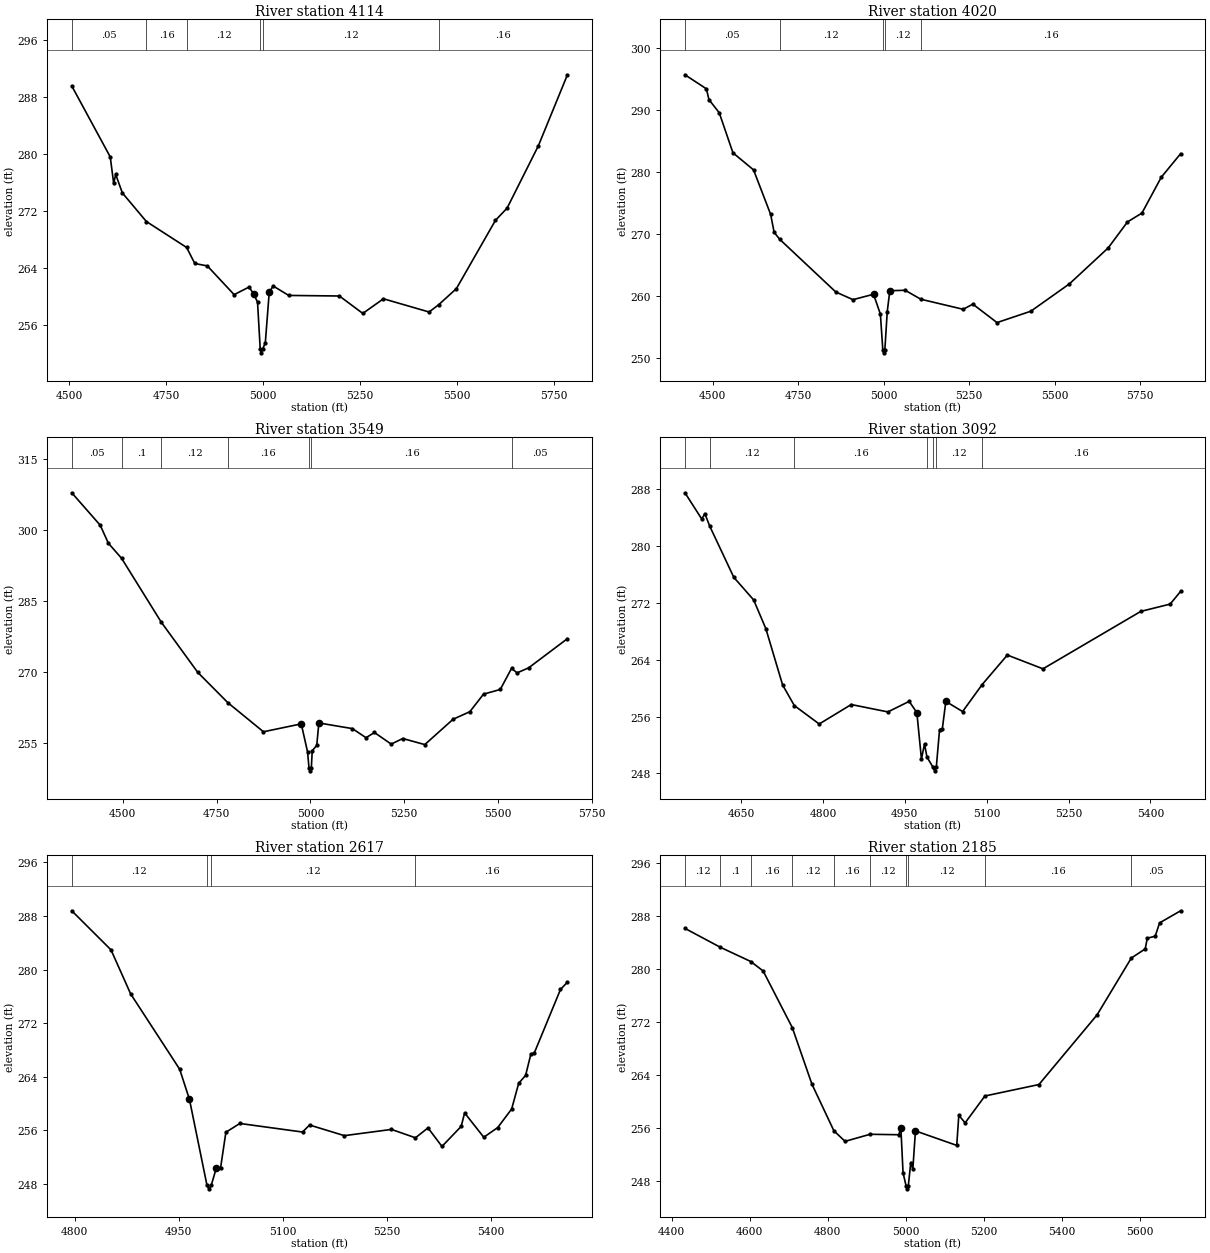
Type RM Length L Ch R = 1 ,4114    ,94,94,94
BEGIN DESCRIPTION:
Mapping XS 03d6875c
END DESCRIPTION:
XS GIS Cut Line= 3
      3726005.33     10630774.91      3725672.04     10630868.65
        3724745.     10630759.28
#Sta/Elev= 30
  4506.2  289.59  4605.6  279.61  4614.4  275.89  4619.6  277.15  4636.8  274.55
  4698.9  270.53  4802.8  266.88  4823.8  264.63  4856.2  264.29  4925.4  260.25
    4964  261.32  4975.7  260.36  4985.8   259.2  4992.8  252.57  4995.6  252.07
  4998.8  252.57  5005.9  253.48    5016  260.58  5026.1  261.47  5066.3  260.14
  5197.2  260.06  5257.6  257.61  5310.9  259.67  5428.8  257.81  5453.6  258.84
  5499.3   261.1    5600  270.69  5630.2  272.42  5710.8  281.17  5785.9  291.16
#Mann= 6 ,-1 , 0
  4506.2     .05       0  4698.9     .16       0  4802.8     .12       0
  4992.8     .07       0  4998.8     .12       0  5453.6     .16       0
Bank Sta=4975.7,5016
XS Rating Curve= 0 ,0
Exp/Cntr=0.3,0.1

Type RM Length L Ch R = 1 ,4020    ,471,471,471
BEGIN DESCRIPTION:
CHALYBEATE CREEK 8.0
END DESCRIPTION:
XS GIS Cut Line= 3
      3726099.57     10630710.19      3725499.61     10630760.19
      3724899.59     10630160.17
#Sta/Elev= 30
  4418.5  295.66  4481.2   293.4  4488.7  291.66  4518.8  289.55  4558.9   283.1
  4619.2  280.35  4669.3  273.18  4679.4  270.31  4695.5  269.19    4860  260.69
  4910.2  259.46  4970.4  260.33  4990.4  257.13  4997.5   251.4  5000.2   250.9
  5003.5   251.4  5010.5  257.54    5018   260.9    5063  260.97  5108.7  259.53
  5232.7  257.91    5261  258.74  5331.7  255.77  5430.7   257.6  5543.8  262.01
  5656.9  267.78  5713.5  271.97  5755.9   273.4  5812.5  279.17  5869.1  282.96
#Mann= 5 ,-1 , 0
  4418.5     .05       0  4695.5     .12       0  4997.5     .07       0
  5003.5     .12       0  5108.7     .16       0
Bank Sta=4970.4,5018
XS Rating Curve= 0 ,0
Exp/Cntr=0.3,0.1

Type RM Length L Ch R = 1 ,3549    ,457,457,457
BEGIN DESCRIPTION:
CHALYBEATE CREEK 7.0
END DESCRIPTION:
XS GIS Cut Line= 3
      3726249.58     10630610.18      3725649.61     10630360.19
       3725049.6     10630060.18
#Sta/Elev= 30
  4363.9  307.86  4439.7  301.02  4461.4  297.22  4496.7  294.03  4602.2  280.58
  4699.7  269.96  4779.7  263.58  4874.7  257.43  4975.4   259.1  4992.2  253.19
  4996.2  249.69    4999  249.19  5002.2  249.69  5004.7  253.43  5016.7  254.57
  5022.3  259.29  5111.7   258.1    5148  256.18  5170.4  257.28  5215.1  254.83
  5245.9  256.01  5304.6  254.73    5380  260.07  5424.7  261.67  5461.1  265.37
  5505.8  266.36  5535.9  270.83  5550.5  269.86  5581.3  270.92  5684.7  277.08
#Mann= 7 ,-1 , 0
  4363.9     .05       0  4496.7      .1       0  4602.2     .12       0
  4779.7     .16       0  4996.2     .07       0  5002.2     .16       0
  5535.9     .05       0
Bank Sta=4975.4,5022.3
XS Rating Curve= 0 ,0
Exp/Cntr=0.3,0.1

Type RM Length L Ch R = 1 ,3092    ,475,475,475
BEGIN DESCRIPTION:
CHALYBEATE CREEK 6.0
END DESCRIPTION:
XS GIS Cut Line= 3
      3725999.65     10629760.17      3725599.61     10629960.19
      3725149.64      10629860.2
#Sta/Elev= 30
  4547.1  287.53  4577.9  283.83  4583.5   284.6  4592.4  282.84  4636.6  275.62
  4672.9  272.44  4695.3  268.39    4726  260.46  4747.5  257.55  4793.1  254.96
  4851.8   257.7  4918.9  256.66    4958  258.15    4972  256.55  4980.4  250.02
    4986  252.13  4990.5  250.31  5001.6  248.86  5004.4  248.36  5007.6  248.86
  5013.6  254.17  5018.7  254.31  5025.1  258.14  5055.8  256.71  5091.6  260.51
  5137.8  264.67  5203.1  262.73  5382.3  270.82  5436.1  271.85  5455.3  273.64
#Mann= 7 ,-1 , 0
  4547.1     .16       0  4592.4     .12       0  4747.5     .16       0
  4990.5     .12       0  5001.6     .07       0  5007.6     .12       0
  5091.6     .16       0
Bank Sta=4972,5025.1
XS Rating Curve= 0 ,0
Exp/Cntr=0.3,0.1

Type RM Length L Ch R = 1 ,2617    ,432,432,432
BEGIN DESCRIPTION:
CHALYBEATE CREEK 5.0
END DESCRIPTION:
XS GIS Cut Line= 3
      3725799.61     10629360.19      3725649.61     10629510.19
      3725149.63     10629560.19
#Sta/Elev= 30
    4796  288.78  4852.6  282.94  4880.9  276.37  4951.6  265.12  4965.7  260.61
    4991  247.77  4993.7  247.27    4997  247.77  5004.6  250.44  5010.6  250.44
  5018.2  255.72  5038.3  257.03  5128.7  255.75  5138.8   256.8    5189  255.21
  5256.9  256.14  5291.5  254.89  5309.6  256.37  5329.7   253.6  5357.4  256.59
  5362.4   258.6    5390  254.97  5410.1  256.42  5430.2  259.19  5440.3  263.02
  5450.3  264.21  5457.9  267.39  5462.9  267.57  5500.6  277.04  5510.6  278.12
#Mann= 4 ,-1 , 0
    4796     .12       0    4991     .07       0    4997     .12       0
  5291.5     .16       0
Bank Sta=4965.7,5004.6
XS Rating Curve= 0 ,0
Exp/Cntr=0.3,0.1

Type RM Length L Ch R = 1 ,2185    ,347,347,347
BEGIN DESCRIPTION:
Mapping XS 29cdb0db
END DESCRIPTION:
XS GIS Cut Line= 3
       3725846.1     10629078.51      3725221.14     10629302.45
      3724648.72      10629505.4
#Sta/Elev= 30
    4434   286.2    4525  283.34  4602.8   281.2  4634.5  279.77  4709.3  271.21
  4759.6  262.68  4815.9  255.64  4844.6  254.04  4908.8  255.11  4982.4  255.04
  4987.7   256.1  4993.3   249.3  5000.9  247.37  5003.6  246.87  5006.9  247.37
  5013.1  250.84  5018.4  249.84  5025.1  255.62    5131  253.43  5136.3  257.98
  5152.5  256.83  5203.2  260.89  5341.8  262.62  5490.9  273.14  5578.8  281.73
  5614.4   283.1  5619.7  284.73    5640  285.01  5651.2  287.03  5705.2  288.86
#Mann= 10 ,-1 , 0
    4434     .12       0    4525      .1       0  4602.8     .16       0
  4709.3     .12       0  4815.9     .16       0  4908.8     .12       0
  5000.9     .07       0  5006.9     .12       0  5203.2     .16       0
  5578.8     .05       0
Bank Sta=4987.7,5025.1
XS Rating Curve= 0 ,0
Exp/Cntr=0.3,0.1

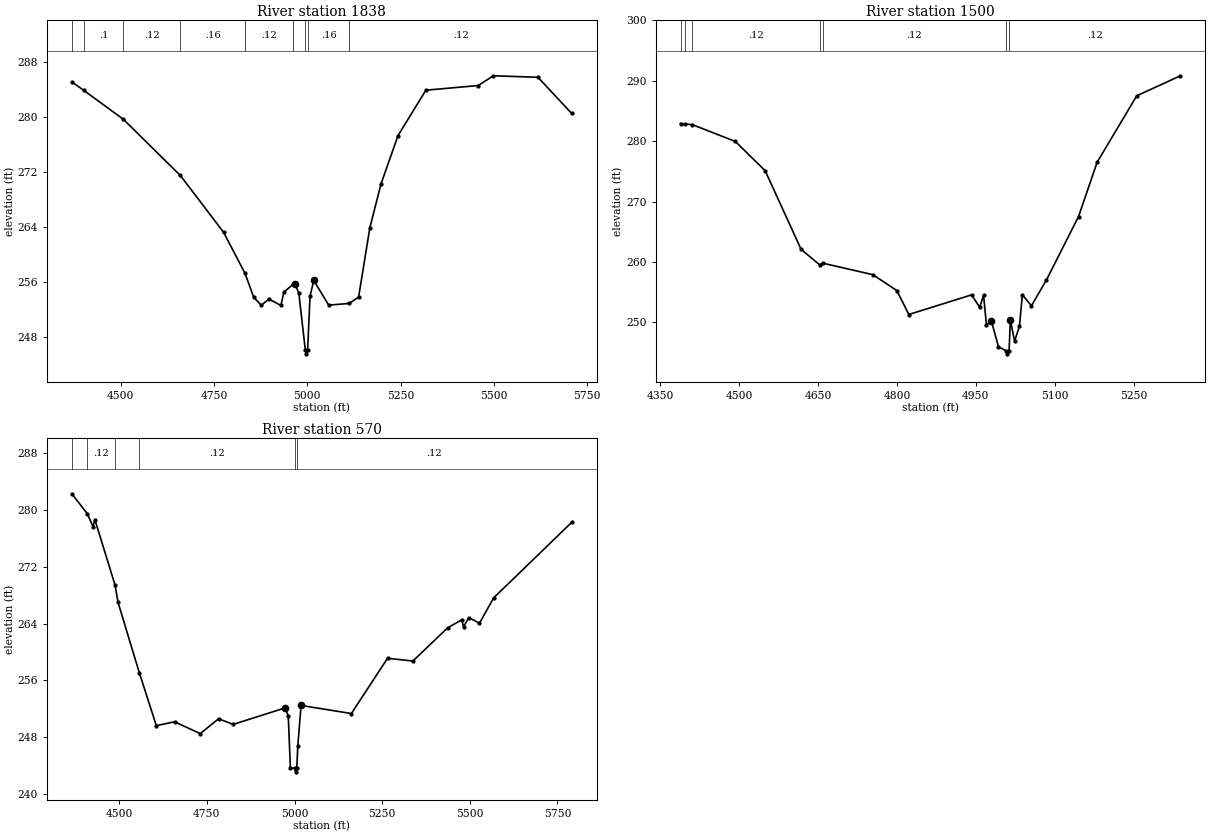
Type RM Length L Ch R = 1 ,1838    ,338,338,338
BEGIN DESCRIPTION:
Mapping XS a8ac386d
END DESCRIPTION:
XS GIS Cut Line= 3
      3725882.64     10629010.79      3725330.51     10628937.87
      3724549.26     10628906.61
#Sta/Elev= 30
  4369.6  285.11  4401.4  283.88  4507.4  279.67  4660.2  271.49  4776.1  263.21
  4833.4  257.24  4856.8  253.74    4877   252.6  4897.2  253.51  4929.5  252.58
  4937.4  254.51  4962.7  255.67  4967.5  255.67  4977.5  254.36    4995  246.03
  4997.7  245.53    5001  246.03  5007.5  253.93  5017.5  256.21  5057.5  252.62
  5112.9  252.87  5137.6  253.79  5167.6  263.85  5197.6  270.26  5243.2   277.3
  5317.7   283.9  5457.8  284.58  5498.4     286    5618  285.78  5708.4  280.51
#Mann= 9 ,-1 , 0
  4369.6     .12       0  4401.4      .1       0  4507.4     .12       0
  4660.2     .16       0  4833.4     .12       0  4962.7     .16       0
    4995     .07       0    5001     .16       0  5112.9     .12       0
Bank Sta=4967.5,5017.5
XS Rating Curve= 0 ,0
Exp/Cntr=0.3,0.1

Type RM Length L Ch R = 1 ,1500    ,930,930,930
BEGIN DESCRIPTION:
Mapping XS 5dcf6607
END DESCRIPTION:
XS GIS Cut Line= 2
      3725913.82     10628922.23       3725054.5       10628516.
#Sta/Elev= 30
  4388.6  282.89  4396.9  282.83  4410.9  282.73  4492.8  279.94  4549.6  275.09
  4617.8  262.09  4653.2  259.51  4658.8   259.8  4754.4  257.89  4799.9  255.26
  4822.7   251.3    4942  254.55  4957.4  252.51  4964.8  254.48  4970.3  249.51
  4979.5  250.27  4993.1  245.97  5007.3  245.29    5010  244.79  5013.3  245.29
  5015.8  250.42  5023.7  246.89    5033  249.33  5038.6  254.57  5055.8  252.74
  5084.1  256.98  5145.4  267.51  5180.7  276.49    5256  287.49  5339.1  290.81
#Mann= 7 ,-1 , 0
  4388.6     .12       0  4396.9      .1       0  4410.9     .12       0
  4653.2     .16       0  4658.8     .12       0  5007.3     .07       0
  5013.3     .12       0
Bank Sta=4979.5,5015.8
XS Rating Curve= 0 ,0
Exp/Cntr=0.3,0.1

Type RM Length L Ch R = 1 ,570     ,0,0,0
BEGIN DESCRIPTION:
CHALYBEATE CREEK 1.0
END DESCRIPTION:
XS GIS Cut Line= 4
       3726012.8     10628760.77      3725846.14      10628208.7
      3725648.22      10628083.7      3725038.86     10628167.03
#Sta/Elev= 30
  4364.9  282.31    4409   279.5  4425.4  277.67  4430.6  278.66  4488.2  269.43
  4496.6  267.01  4557.3  257.08  4605.9  249.62    4658  250.17  4731.1  248.49
  4783.3  250.59  4825.1   249.8    4973  252.12  4982.2  250.99  4988.2  243.67
  5000.4  243.61  5003.2  243.11  5006.4  243.61  5009.3  246.72  5018.7  252.47
  5162.2  251.33  5265.3  259.12  5337.5  258.73  5436.7  263.41    5477  264.54
    5482  263.55  5497.2  264.86  5527.5  264.06  5567.9  267.63  5790.7  278.29
#Mann= 6 ,-1 , 0
  4364.9     .16       0    4409     .12       0  4488.2     .16       0
  4557.3     .12       0  5000.4     .07       0  5006.4     .12       0
Bank Sta=4973,5018.7
XS Rating Curve= 0 ,0
Exp/Cntr=0.3,0.1

Chan Stop Cuts=-1
Use User Specified Reach Order=0
Composite Channel Slope=5