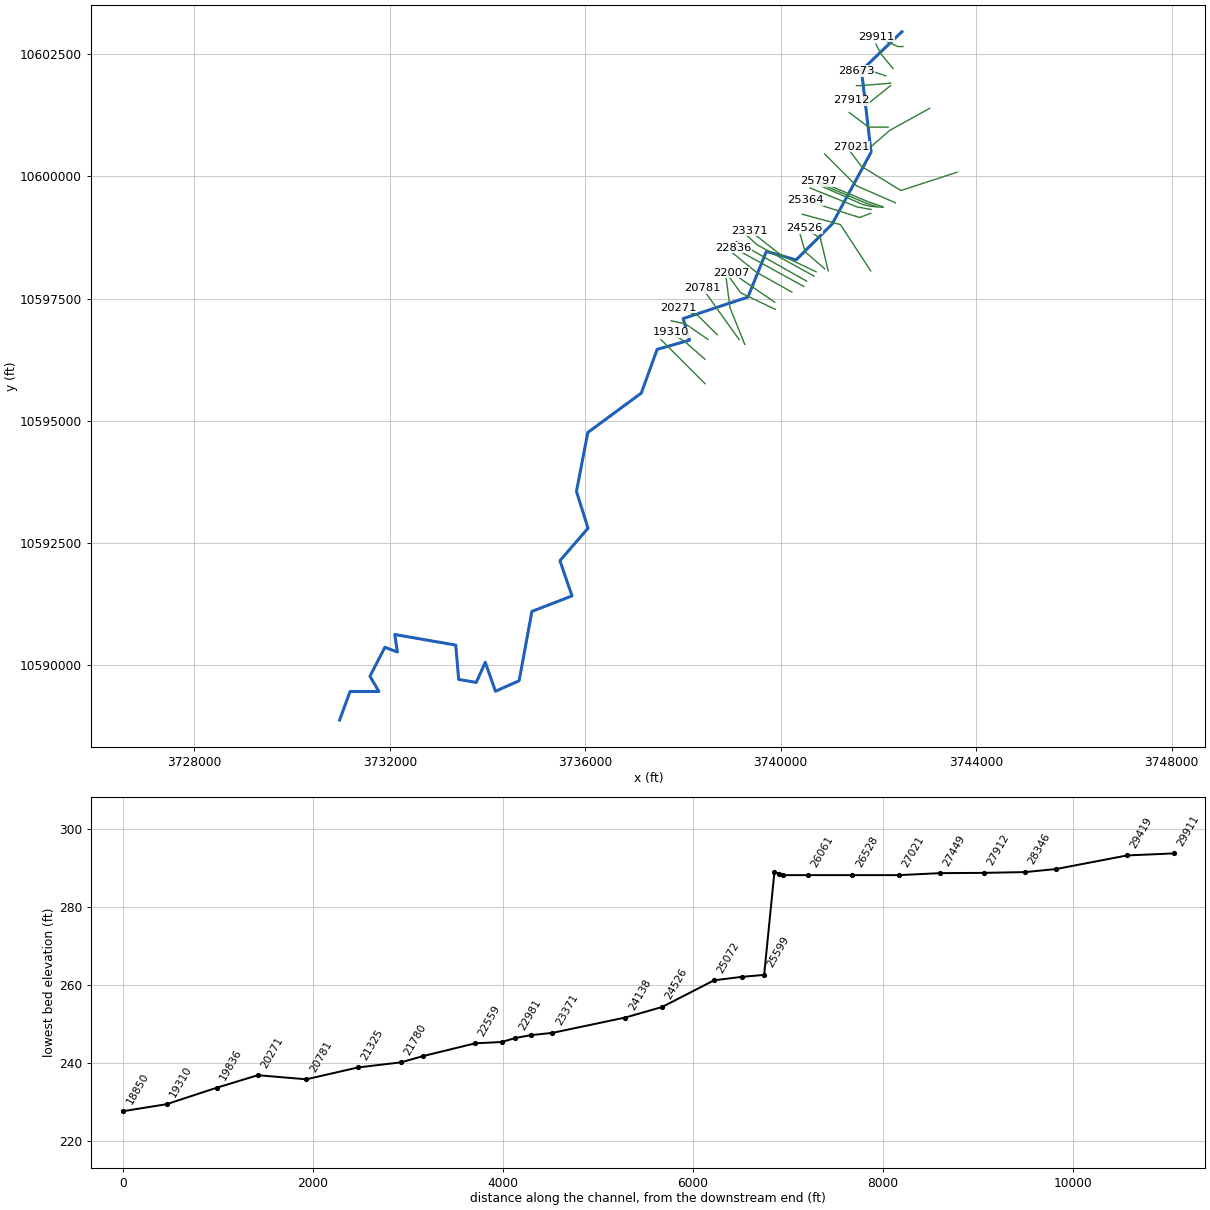
--- CROOKED CREEK.prj (project) ---

Proj Title=CROOKED CREEK Base Level Engineering
Current Plan=p01
Default Exp/Contr=0.3,0.1
English Units
Geom File=g01
Flow File=f01
Plan File=p01
Y Axis Title=Elevation
X Axis Title(PF)=Main Channel Distance
X Axis Title(XS)=Station
BEGIN DESCRIPTION:
CROOKED CREEK
END DESCRIPTION:
DSS File=dss
DSS Export Rating Curves= 0
DSS Export Rating Curve Sorted= 0
DSS Export Volume Flow Curves= 0
DXF OffsetX= 0
DXF OffsetY= 0
DXF ScaleX= 1
DXF ScaleY= 10

--- CROOKED CREEK.p01 (plan) ---

Plan Title=Multiple Run
Program Version=4.10
Short Identifier=Multiple Run
Geom File=g01
Flow File=f01
Subcritical Flow
K Sum by GR= 0
Std Step Tol= 0.01
Critical Tol= 0.01
Num of Std Step Trials= 20
Max Error Tol= 0.3
Flow Tol Ratio= 0.001
Split Flow NTrial= 30
Split Flow Tol= 0.02
Split Flow Ratio= 0.02
Log Output Level= 0
Friction Slope Method= 1
Unsteady Friction Slope Method= 2
Unsteady Bridges Friction Slope Method= 1
Parabolic Critical Depth
Global Vel Dist= 1 , 1 , 1
Global Log Level= 0
CheckData=True
Encroach Param=-1 ,0,0, 0
BEGIN DESCRIPTION:
Multiple Run
END DESCRIPTION:
Computation Interval=1HOUR
Output Interval=1HOUR
Run HTab= 0
Run UNet= 0
Run PostProcess= 0
Run WQNet= 0
UNET Theta= 1
UNET Theta Warmup= 1
UNET ZTol= 0.02
UNET ZSATol= 0.05
UNET MxIter= 20
UNET MaxInSteps= 0
UNET DtIC= 0
UNET DtMin= 0
UNET MaxCRTS= 20
UNET WFStab= 2
UNET SFStab= 1
UNET WFX= 1
UNET SFX= 1
UNET DSS MLevel= 4
UNET DZMax Abort= 100
UNET Convert EG Bridges= 0
UNET Use Existing IB Tables=-1
UNET Froude Reduction=False
UNET Froude Limit= 1
UNET Froude Power= 10
UNET Time Slicing=0,0, 5
UNET Junction Losses=0
Instantaneous Interval=1HOUR
DSS File=dss
Write IC File= 0
Write IC File at Sim End=0
Echo Input=False
Echo Parameters=False
Echo Output=False
Write Detailed= 0
WQ AD Non Conservative
WQ ULTIMATE=-1
WQ Max Comp Step=1HOUR
WQ Output Interval=15MIN
WQ Output Selected Increments= 0
WQ Output face flow=0
WQ Output face velocity=0
WQ Output face area=0
WQ Output face dispersion=0
WQ Output cell volume=0
WQ Output cell surface area=0
WQ Output cell continuity=0
WQ Output cumulative cell continuity=0
WQ Output face conc=0
WQ Output face dconc_dx=0
WQ Output face courant=0
WQ Output face peclet=0
WQ Output face adv mass=0
WQ Output face disp mass=0
WQ Output cell mass=0
WQ Output cell source sink temp=0
WQ Output cell source sink nsm=0
WQ Output MaxMinRange=-1
WQ Daily Max Min Mean=-1
WQ Daily Range=0
WQ Daily Time=0
WQ Create Restart=0
WQ Fixed Restart=0
WQ System Summary=0
WQ Use Fixed Temperature=0
Sorting and Armoring Iterations= 10
XS Update Threshold= 0.02
Hydraulics Update Threshold= 0.02
Energy Slope Method= 1
Volume Change Method= 0
XS Weighting Method= 0
Number of US Weighted Cross Sections= 1
Number of DS Weighted Cross Sections= 1
Upstream XS Weight=0.25
Main XS Weight=0.5
Downstream XS Weight=0.25
Number of DS XS's Weighted with US Boundary= 1
Upstream Boundary Weight= 1
Weight of XSs Associated with US Boundary= 0
Number of US XS's Weighted with DS Boundary= 1
Downstream Boundary Weight= 0.5
Weight of XSs Associated with DS Boundary= 0.5
Sediment Output Level= 4
Mass or Volume Output= 0
Output Increment Type= 1
Profile and TS Output Increment= 10
XS Output Flag= 0
XS Output Increment= 10
Disregard all LS=0
Disregard all Conn=0
Disregard all Breaches=0
Disregard all Pumps=0

--- CROOKED CREEK.f01 (steady flow) ---

Flow Title=Multiple
Program Version=4.10
Number of Profiles= 7
Profile Names=10-year,25-year,50-year,1pct_min,100-year,1pct_plu,500-year
River Rch & RM=CROOKED CREEK,Reach-1         ,29911
     619     842    1028     923    1249    1689    1847
River Rch & RM=CROOKED CREEK,Reach-1         ,26528
     901    1255    1555    1416    1915    2590    2915
River Rch & RM=CROOKED CREEK,Reach-1         ,26061
     901    1255    1555    1416    1915    2590    2915
River Rch & RM=CROOKED CREEK,Reach-1         ,25072
    1315    1867    2343    2158    2918    3946    4545
River Rch & RM=CROOKED CREEK,Reach-1         ,24138
    1315    1867    2343    2158    2918    3946    4545
River Rch & RM=CROOKED CREEK,Reach-1         ,21325
    1592    2276    2872    2657    3593    4859    5647
River Rch & RM=CROOKED CREEK,Reach-1         ,18182
    1620    2317    2922    2701    3653    4941    5736
River Rch & RM=CROOKED CREEK,Reach-1         ,16471
    1762    2517    3173    2930    3963    5359    6209
River Rch & RM=CROOKED CREEK,Reach-1         ,11206
    2307    3325    4216    3911    5289    7153    8365
River Rch & RM=CROOKED CREEK,Reach-1         ,7934
    2307    3325    4216    3911    5289    7153    8365
River Rch & RM=CROOKED CREEK,Reach-1         ,3070
    2352    3388    4294    3982    5385    7282    8508
River Rch & RM=CROOKED CREEK,Reach-1         ,2691
    2352    3388    4294    3982    5385    7282    8508
Boundary for River Rch & Prof#=CROOKED CREEK,Reach-1         , 1
Up Type= 0
Dn Type= 3
Dn Slope=0.004
Boundary for River Rch & Prof#=CROOKED CREEK,Reach-1         , 2
Up Type= 0
Dn Type= 3
Dn Slope=0.004
Boundary for River Rch & Prof#=CROOKED CREEK,Reach-1         , 3
Up Type= 0
Dn Type= 3
Dn Slope=0.004
Boundary for River Rch & Prof#=CROOKED CREEK,Reach-1         , 4
Up Type= 0
Dn Type= 3
Dn Slope=0.004
Boundary for River Rch & Prof#=CROOKED CREEK,Reach-1         , 5
Up Type= 0
Dn Type= 3
Dn Slope=0.004
Boundary for River Rch & Prof#=CROOKED CREEK,Reach-1         , 6
Up Type= 0
Dn Type= 3
Dn Slope=0.004
Boundary for River Rch & Prof#=CROOKED CREEK,Reach-1         , 7
Up Type= 0
Dn Type= 3
Dn Slope=0.004
DSS Import GetInterval= 0
DSS Import GetPeak= 0
DSS Import FillOption= 0

--- CROOKED CREEK.g01 (geometry) ---

Geom Title=Existing Conditions
Program Version=4.10

River Reach=CROOKED CREEK   ,Reach-1
Reach XY= 30
      3742480.79     10602963.08      3741652.75       10602170.
        3741850.       10600497.        3741053.       10599027.
        3740314.       10598292.      3739706.25       10598467.
        3739329.       10597531.      3738003.25       10597092.
      3738133.75       10596649.      3737470.25       10596460.
      3737146.25       10595566.      3736051.25       10594760.
      3735819.25       10593554.      3736055.75       10592801.
      3735481.25       10592135.        3735728.       10591415.
        3734907.       10591097.       3734645.5       10589678.
        3734161.       10589463.       3733952.5       10590056.
      3733768.25       10589643.        3733408.       10589706.
      3733348.75       10590408.      3732099.25       10590625.
      3732154.75       10590265.      3731898.75       10590364.
        3731592.       10589771.      3731775.75       10589459.
        3731184.       10589457.       3730971.5       10588875.

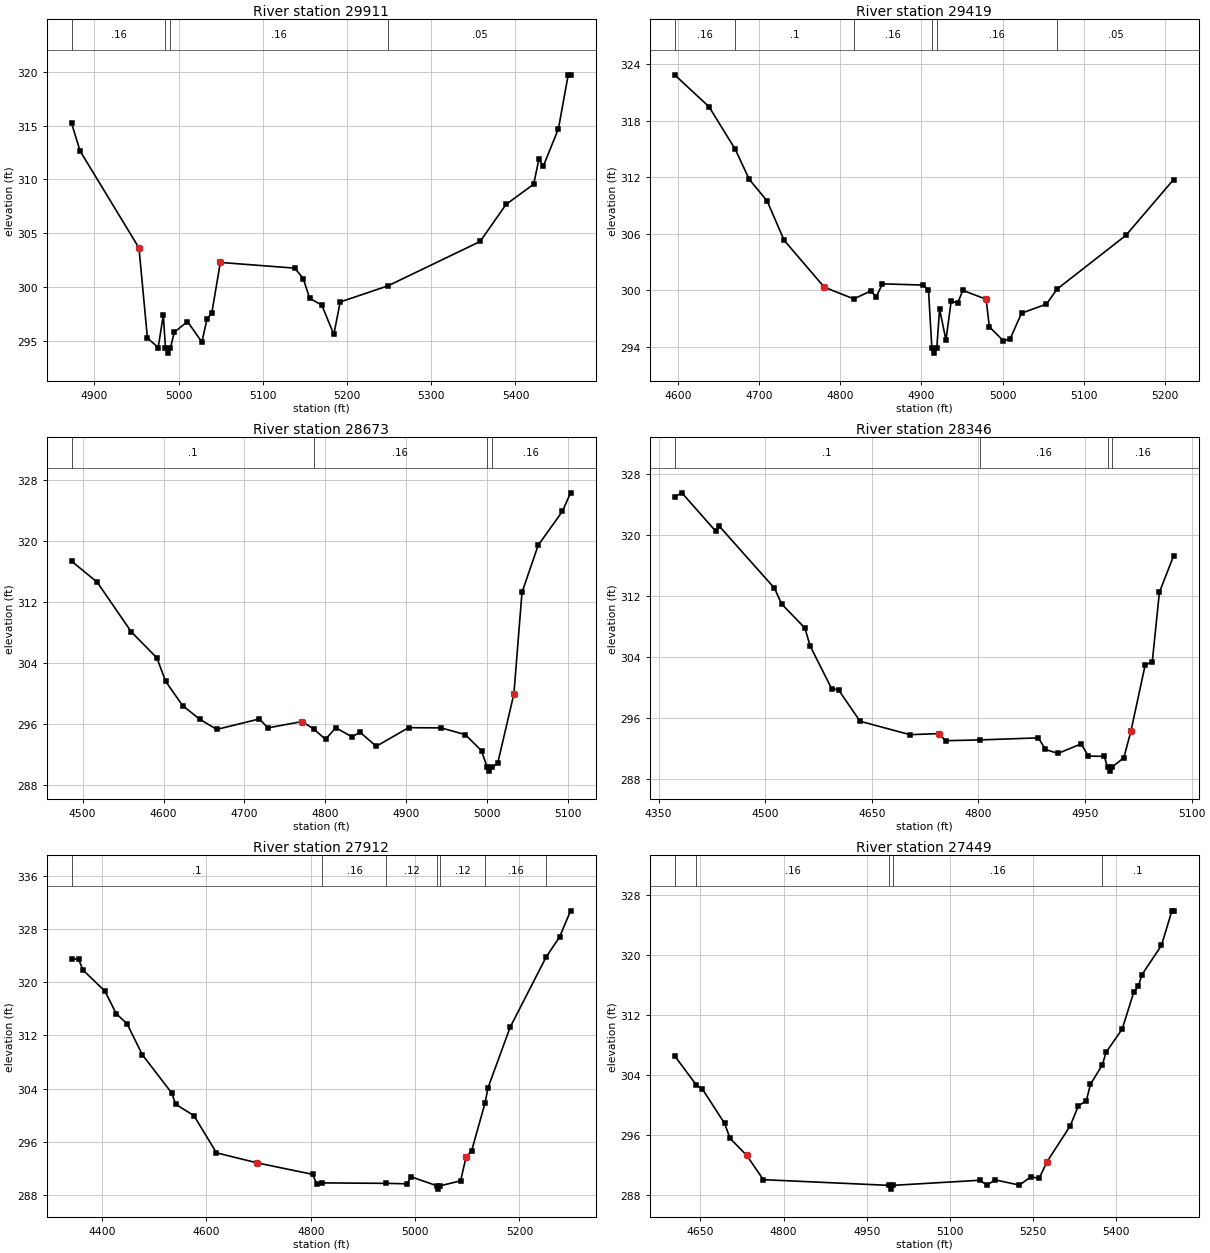
Type RM Length L Ch R = 1 ,29911   ,492,492,492
BEGIN DESCRIPTION:
CROOKED CREEK 55.0
END DESCRIPTION:
XS GIS Cut Line= 3
      3742499.63     10602660.19      3742399.61     10602660.19
      3741949.58      10602860.2
#Sta/Elev= 30
  4872.9  315.22  4882.9  312.65  4952.9  303.62  4962.9  295.24  4975.7  294.35
  4981.8  297.38  4984.3  294.33    4987  293.83  4990.3  294.33  4994.8  295.77
  5010.5  296.77  5027.6  294.86  5033.8  297.05  5039.3  297.53  5049.5  302.27
  5137.8  301.74    5148  300.77  5155.5  298.93  5169.9  298.31  5184.3  295.57
  5191.8  298.59  5248.8   300.1    5358  304.22  5388.8  307.67  5421.6  309.55
  5427.7  311.85  5433.2  311.26    5451  314.72  5462.6  319.73  5465.4  319.73
#Mann= 4 ,-1 , 0
  4872.9     .16       0  4984.3     .07       0  4990.3     .16       0
  5248.8     .05       0
Bank Sta=4952.9,5049.5
XS Rating Curve= 0 ,0
Exp/Cntr=0.3,0.1

Type RM Length L Ch R = 1 ,29419   ,746,746,746
BEGIN DESCRIPTION:
CROOKED CREEK 54.0
END DESCRIPTION:
XS GIS Cut Line= 3
      3742299.61     10602210.18      3742049.61     10602510.19
      3741949.62     10602710.16
#Sta/Elev= 30
  4596.2  322.87  4638.5  319.48  4670.7  314.97    4688  311.77  4710.1  309.46
  4730.9   305.3  4780.4  300.31  4816.7  299.07  4837.7  299.92  4844.2  299.28
    4852  300.67  4901.5  300.54  4908.6  300.04  4912.8  293.81  4915.5  293.31
  4918.8  293.81  4922.3     298  4930.1  294.69  4936.6  298.87  4944.4   298.6
  4950.9  299.98  4979.6  299.03  4983.5  296.11  5000.7  294.62  5009.1  294.82
  5023.1  297.55  5053.8  298.52  5066.9  300.11  5151.6  305.82  5210.3  311.75
#Mann= 6 ,-1 , 0
  4596.2     .16       0  4670.7      .1       0  4816.7     .16       0
  4912.8     .07       0  4918.8     .16       0  5066.9     .05       0
Bank Sta=4780.4,4979.6
XS Rating Curve= 0 ,0
Exp/Cntr=0.3,0.1

Type RM Length L Ch R = 1 ,28673   ,327,327,327
BEGIN DESCRIPTION:
CROOKED CREEK 53.0
END DESCRIPTION:
XS GIS Cut Line= 3
      3742149.61     10602060.19      3741849.61     10602160.19
      3741549.64     10602160.19
#Sta/Elev= 30
  4486.5  317.31  4518.1  314.56  4560.3  308.05  4591.9  304.64  4602.5   301.6
  4623.5  298.42  4644.6  296.63  4665.7  295.29  4718.4  296.66  4728.9  295.49
  4771.1  296.32  4785.3  295.36  4800.1  293.99  4812.7  295.51  4832.7  294.32
  4842.7  294.92  4862.7  293.08  4902.7  295.52  4942.7  295.49  4972.7  294.61
  4992.7   292.5  4999.7  290.33  5002.5  289.83  5005.7  290.33  5012.7  290.86
  5032.7  299.94  5042.7  313.22  5062.7   319.4  5092.7  323.85  5102.7  326.26
#Mann= 4 ,-1 , 0
  4486.5      .1       0  4785.3     .16       0  4999.7     .07       0
  5005.7     .16       0
Bank Sta=4771.1,5032.7
XS Rating Curve= 0 ,0
Exp/Cntr=0.3,0.1

Type RM Length L Ch R = 1 ,28346   ,434,434,434
BEGIN DESCRIPTION:
CROOKED CREEK 52.0
END DESCRIPTION:
XS GIS Cut Line= 3
      3742249.65     10601910.19      3741649.61     10601860.19
      3741549.63     10601860.19
#Sta/Elev= 30
  4372.5     325  4382.6  325.53  4430.2  320.51  4435.3  321.16    4513  313.02
  4523.1  310.95  4555.7  307.81  4563.2  305.44  4593.3  299.87  4603.3  299.67
  4633.4  295.58  4703.7  293.82  4743.8  293.96  4753.9  293.03  4801.5  293.13
  4884.3   293.4  4894.3  291.88  4911.9  291.36  4944.5  292.61  4954.6  291.01
  4977.1  290.98  4981.6  289.54  4984.4  289.04  4987.6  289.54  5004.6   290.8
  5014.6  294.31  5034.6  302.96  5044.6  303.38  5054.6  312.49  5074.6  317.26
#Mann= 4 ,-1 , 0
  4372.5      .1       0  4801.5     .16       0  4981.6     .07       0
  4987.6     .16       0
Bank Sta=4743.8,5014.6
XS Rating Curve= 0 ,0
Exp/Cntr=0.3,0.1

Type RM Length L Ch R = 1 ,27912   ,463,463,463
BEGIN DESCRIPTION:
CROOKED CREEK 51.0
END DESCRIPTION:
XS GIS Cut Line= 3
       3742249.6     10601860.18      3741749.61     10601460.19
      3741449.63     10601560.18
#Sta/Elev= 30
  4341.6  323.58  4355.2  323.46  4363.2  321.88  4405.6  318.67  4427.2  315.28
    4448  313.75  4476.9  309.13  4533.7  303.31  4540.9  301.64  4576.1  299.92
  4619.3  294.31  4697.8  292.79  4803.4  291.07  4811.4  289.64  4822.4  289.78
  4945.1  289.71  4984.5  289.64  4992.4   290.7  5042.1  289.34  5044.9  288.84
  5048.1  289.34  5087.3  290.09  5097.8  293.68  5108.4  294.61  5134.1  301.82
    5140  304.15  5182.2  313.23  5251.3  323.83    5277  326.84  5298.1  330.79
#Mann= 7 ,-1 , 0
  4341.6      .1       0  4822.4     .16       0  4945.1     .12       0
  5042.1     .07       0  5048.1     .12       0  5134.1     .16       0
  5251.3      .1       0
Bank Sta=4697.8,5097.8
XS Rating Curve= 0 ,0
Exp/Cntr=0.3,0.1

Type RM Length L Ch R = 1 ,27449   ,428,428,428
BEGIN DESCRIPTION:
CROOKED CREEK 50.0
END DESCRIPTION:
XS GIS Cut Line= 3
       3742199.6     10601010.19      3741799.61     10601010.19
       3741399.6     10601310.19
#Sta/Elev= 30
  4603.4  306.54  4642.3  302.67  4653.4  302.12  4693.4  297.54  4703.4  295.53
  4733.4  293.27  4763.4  290.03  4990.4  289.27  4993.1  288.77  4996.4  289.27
  5153.4  289.95  5166.9  289.32  5181.5     290  5225.3  289.31  5246.1  290.42
  5260.7  290.19  5275.3  292.45  5316.9   297.2  5331.5  299.85  5346.1  300.58
  5353.4  302.75  5374.9  305.33  5381.5     307  5410.7  310.11  5431.5  315.02
  5439.8   315.8  5446.1  317.34  5481.5  321.26  5500.3  325.87  5503.4  325.87
#Mann= 5 ,-1 , 0
  4603.4      .1       0  4642.3     .16       0  4990.4     .07       0
  4996.4     .16       0  5374.9      .1       0
Bank Sta=4733.4,5275.3
XS Rating Curve= 0 ,0
Exp/Cntr=0.3,0.1

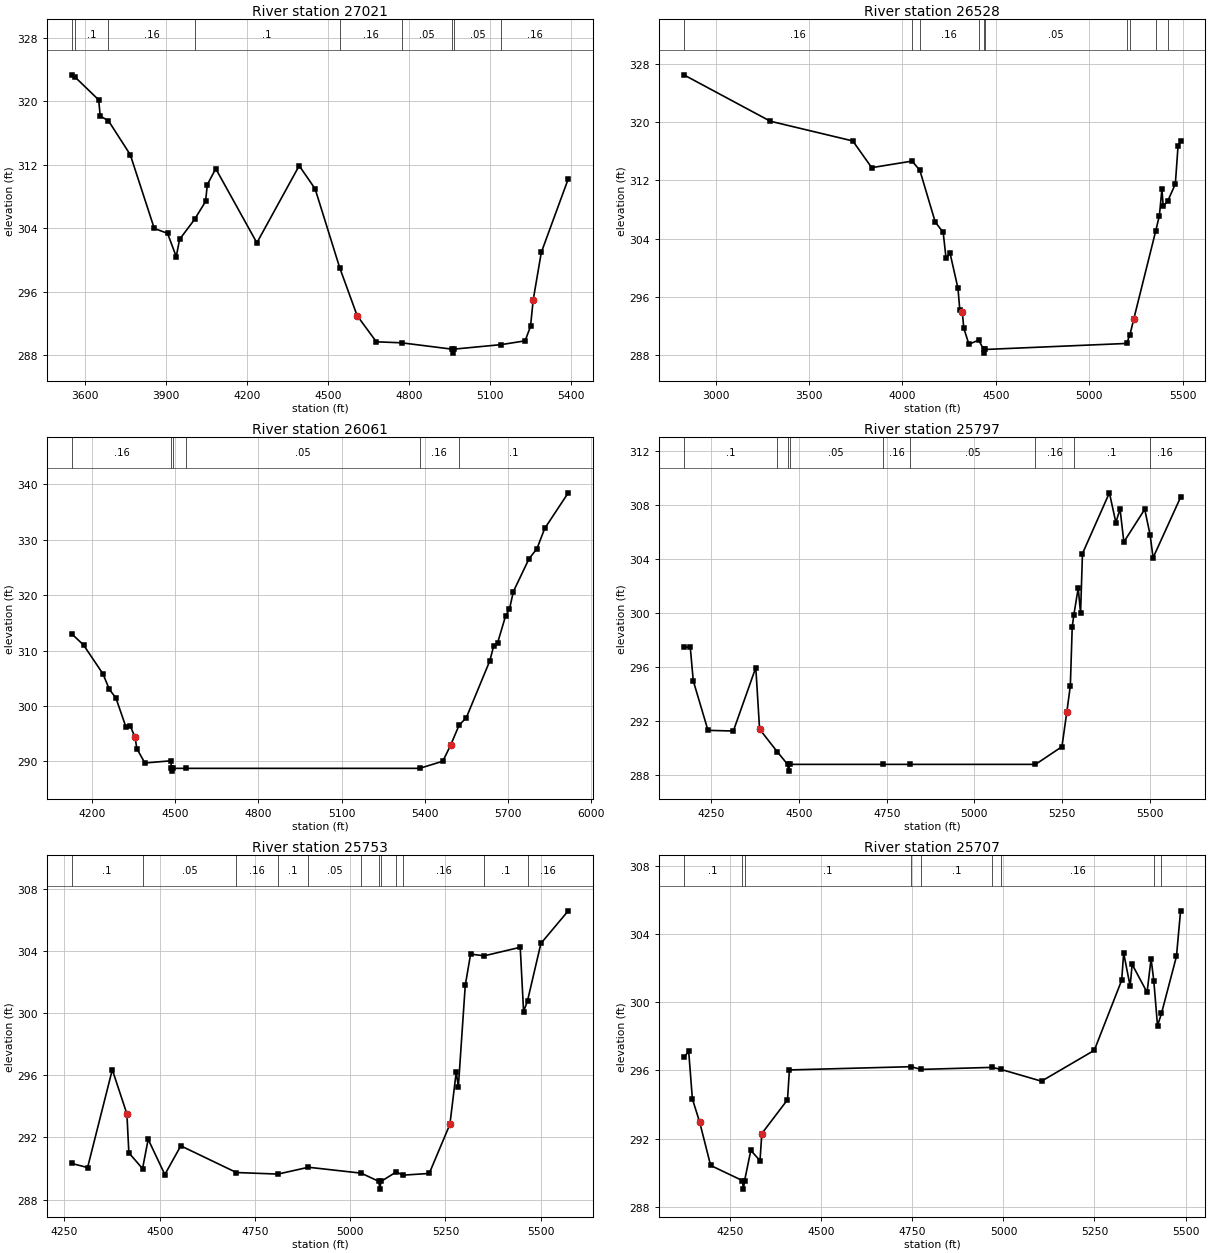
Type RM Length L Ch R = 1 ,27021   ,493,493,493
BEGIN DESCRIPTION:
CROOKED CREEK 49.0
END DESCRIPTION:
XS GIS Cut Line= 4
      3743050.45     10601395.19      3742227.19     10600940.57
      3741849.61     10600610.19      3741449.58     10600610.19
#Sta/Elev= 30
  3548.5  323.36  3560.9   323.1  3649.3   320.2    3655  318.15  3685.3  317.58
  3766.5  313.28  3855.5  303.98  3904.7  303.37  3936.9  300.43  3949.3  302.61
  4004.8  305.12  4045.7  307.39  4052.1  309.51  4083.5  311.52  4235.9  302.17
  4392.9   311.9  4451.9  308.98  4543.2  299.02  4607.7  292.99  4678.9  289.69
    4773  289.56  4959.7  288.76  4962.4  288.26  4965.7  288.76  5141.3  289.33
  5230.7  289.81  5250.7  291.63  5260.7  294.98  5290.7  300.96  5390.7  310.24
#Mann= 9 ,-1 , 0
  3548.5     .16       0  3560.9      .1       0  3685.3     .16       0
  4004.8      .1       0  4543.2     .16       0    4773     .05       0
  4959.7    .033       0  4965.7     .05       0  5141.3     .16       0
Bank Sta=4607.7,5260.7
XS Rating Curve= 0 ,0
Exp/Cntr=0.3,0.1

Type RM Length L Ch R = 1 ,26528   ,467,467,467
BEGIN DESCRIPTION:
CROOKED CREEK 48.0
END DESCRIPTION:
XS GIS Cut Line= 4
      3743610.08     10600087.01      3742459.88     10599712.77
      3741649.61     10600210.19      3741349.62     10600610.17
#Sta/Elev= 30
  2829.1  326.52  3292.5  320.14    3734  317.43  3835.4  313.76  4051.7  314.66
  4093.3  313.38  4175.5  306.28  4218.1  304.86  4233.5  301.28  4254.8     302
  4297.4  297.15  4306.9  294.24  4320.6  293.92  4328.2  291.72  4355.8  289.48
  4408.3  290.05  4434.9  288.76  4437.7  288.26  4440.9  288.76  5200.4  289.59
  5218.2  290.78  5239.4  293.02  5356.2  305.05  5375.9  307.16  5389.4  310.76
  5396.7  308.42  5421.8  309.24  5461.3   311.5  5475.9  316.76  5489.4  317.42
#Mann= 10 ,-1 , 0
  2829.1     .16       0  4051.7      .1       0  4093.3     .16       0
  4408.3     .05       0  4434.9    .033       0  4440.9     .05       0
  5200.4     .16       0  5218.2      .1       0  5356.2     .16       0
  5421.8      .1       0
Bank Sta=4320.6,5239.4
XS Rating Curve= 0 ,0
Exp/Cntr=0.3,0.1

Type RM Length L Ch R = 1 ,26061   ,264,264,264
BEGIN DESCRIPTION:
CROOKED CREEK 47.0
END DESCRIPTION:
XS GIS Cut Line= 3
      3742349.63     10599460.18      3741549.61     10599810.19
      3740899.59     10600460.21
#Sta/Elev= 30
  4125.3  313.06    4169     311  4238.8   305.8  4262.1  302.99  4285.5  301.46
  4321.8  296.21  4337.8  296.35  4354.5  294.37  4361.2   292.3    4390  289.73
  4483.6  290.12    4486  288.76  4488.8  288.26    4492  288.76  4539.5  288.76
  5381.3  288.76  5465.2  290.05  5493.5  292.96  5523.6  296.52  5550.1  297.92
  5634.9  308.18  5649.1  310.92  5663.2  311.46  5691.5  316.23  5705.6  317.48
  5719.8  320.66  5776.3  326.58  5804.6  328.37  5832.9  332.04  5917.8  338.46
#Mann= 6 ,-1 , 0
  4125.3     .16       0    4486    .033       0    4492     .16       0
  4539.5     .05       0  5381.3     .16       0  5523.6      .1       0
Bank Sta=4354.5,5493.5
XS Rating Curve= 0 ,0
Exp/Cntr=0.3,0.1

Type RM Length L Ch R = 1 ,25797   ,44,44,44
BEGIN DESCRIPTION:
Mapping XS 8e810629
END DESCRIPTION:
XS GIS Cut Line= 3
      3742095.18     10599380.53      3741827.25     10599467.14
      3740780.37     10599904.64
#Sta/Elev= 30
  4171.5  297.45  4189.9  297.43  4198.4  294.95  4240.4  291.28  4312.7  291.23
  4376.7  295.93  4387.5  291.37  4438.3  289.68  4467.4  288.76  4470.1  288.26
  4473.4  288.76  4738.3  288.76  4817.7  288.76  5174.1  288.76  5249.5  290.07
  5263.4  292.64  5273.4  294.57  5278.8  298.95  5283.4  299.83  5295.9  301.82
  5302.6  299.96    5308  304.37  5384.8  308.87  5403.2  306.67  5415.1  307.68
    5426  305.23  5485.5  307.65    5501  305.73  5509.3  304.06  5587.7  308.54
#Mann= 9 ,-1 , 0
  4171.5      .1       0  4438.3     .05       0  4467.4    .033       0
  4473.4     .05       0  4738.3     .16       0  4817.7     .05       0
  5174.1     .16       0  5283.4      .1       0    5501     .16       0
Bank Sta=4387.5,5263.4
XS Rating Curve= 0 ,0
Exp/Cntr=0.3,0.1

Type RM Length L Ch R = 1 ,25753   ,46,46,46
BEGIN DESCRIPTION:
CROOKED CREEK 46.0
END DESCRIPTION:
XS GIS Cut Line= 3
      3741971.95     10599381.82      3741767.35     10599445.01
      3740763.48      10599869.6
#Sta/Elev= 30
  4268.4  290.33  4310.6  290.06  4375.5  296.37  4413.8  293.52    4419  291.01
  4454.9  289.99  4469.7  291.88  4513.4  289.61  4555.3  291.46  4701.3  289.74
  4810.4  289.64  4890.4  290.08  5028.8   289.7  5075.1  289.17  5077.8  288.67
  5081.1  289.17  5121.2  289.78  5137.9  289.57  5207.5  289.68  5261.8  292.85
  5278.5  296.24  5283.9  295.24  5302.1  301.81  5316.1  303.82  5351.9  303.71
  5446.4  304.26  5455.2  300.11  5465.5  300.81  5500.7  304.51  5572.5  306.61
#Mann= 12 ,-1 , 0
  4268.4      .1       0  4454.9     .05       0  4701.3     .16       0
  4810.4      .1       0  4890.4     .05       0  5028.8     .16       0
  5075.1    .033       0  5081.1     .16       0  5121.2     .05       0
  5137.9     .16       0  5351.9      .1       0  5465.5     .16       0
Bank Sta=4413.8,5261.8
XS Rating Curve= 0 ,0
Exp/Cntr=0.3,0.1

Type RM Length L Ch R = 1 ,25707   ,108,108,108
BEGIN DESCRIPTION:
Mapping XS 97240043
END DESCRIPTION:
XS GIS Cut Line= 4
      3742093.01     10599368.98      3741824.75     10599389.82
       3741667.2     10599431.48      3740815.63     10599810.39
#Sta/Elev= 30
  4122.3  296.76  4135.7  297.12  4145.8  294.33  4165.8  292.97  4195.9  290.43
  4283.2  289.54  4285.9  289.04  4289.2  289.54  4306.3  291.31  4331.5  290.71
  4336.5   292.3    4407  294.28  4412.3  296.03  4746.7  296.22  4773.1  296.06
  4968.7  296.18  4993.4  296.06  5104.5  295.37  5249.5  297.18  5324.7  301.29
  5330.1  302.89  5347.9  300.94  5353.4  302.22  5394.4  300.58  5405.4  302.55
  5412.8  301.27  5423.1  298.62  5433.9  299.34  5475.1  302.69  5486.4  305.36
#Mann= 9 ,-1 , 0
  4122.3      .1       0  4283.2     .07       0  4289.2      .1       0
  4746.7     .16       0  4773.1      .1       0  4968.7     .05       0
  4993.4     .16       0  5412.8      .1       0  5433.9     .16       0
Bank Sta=4165.8,4336.5
XS Rating Curve= 0 ,0
Exp/Cntr=0.3,0.1

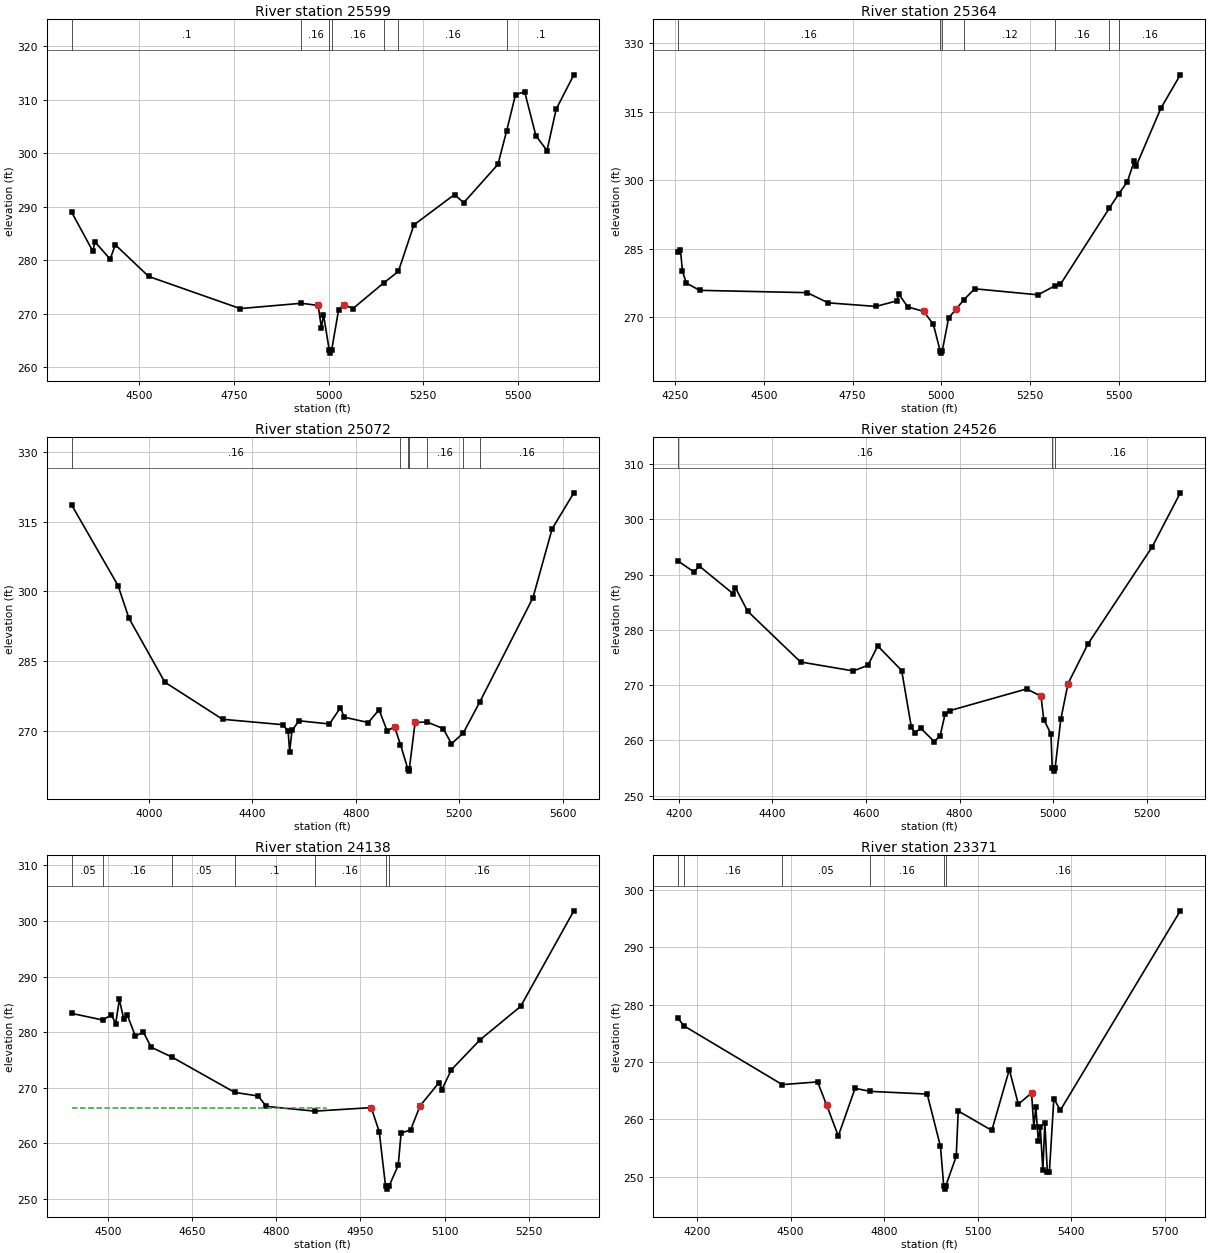
Type RM Length L Ch R = 1 ,25599   ,235,235,235
BEGIN DESCRIPTION:
Mapping XS 2b75f5e6
END DESCRIPTION:
XS GIS Cut Line= 3
      3741849.43     10599325.38      3741561.24     10599376.68
      3740603.95     10599763.75
#Sta/Elev= 30
    4322  288.94  4377.8  281.68  4382.9  283.47  4423.4  280.22  4436.8  282.91
    4525  276.99  4766.5  270.99  4928.3  271.98  4972.4  271.57    4981  267.37
  4986.4  269.87  5001.8  263.17  5004.5  262.67  5007.8  263.17  5026.4  270.76
  5040.1  271.71  5064.2  270.99    5145  275.76  5184.1  277.92  5225.1  286.62
  5332.4  292.29  5356.5  290.75    5447  297.92  5470.1  304.22  5493.3  310.94
  5517.5  311.47    5547  303.29  5576.5  300.49  5600.6  308.22  5647.3  314.64
#Mann= 7 ,-1 , 0
    4322      .1       0  4928.3     .16       0  5001.8     .07       0
  5007.8     .16       0    5145     .12       0  5184.1     .16       0
  5470.1      .1       0
Bank Sta=4972.4,5040.1
XS Rating Curve= 0 ,0
Exp/Cntr=0.3,0.1

Type RM Length L Ch R = 1 ,25364   ,292,292,292
BEGIN DESCRIPTION:
Mapping XS d45ee1bc
END DESCRIPTION:
XS GIS Cut Line= 4
      3741840.74     10599247.26      3741617.35     10599160.03
      3740577.85     10599487.72      3740497.52     10599513.78
#Sta/Elev= 30
  4259.1  284.23  4265.2  284.82  4271.1  280.06  4281.8  277.49  4319.6   275.9
  4622.4  275.39  4681.2  273.17  4815.9  272.38    4874  273.58  4880.6  275.04
  4905.5  272.28  4950.6  271.29  4977.7  268.46  4996.8  262.67  4999.6  262.17
  5002.8  262.67  5020.8  269.87  5041.8  271.78  5063.3  273.83  5094.2  276.24
  5272.4  274.92    5321  276.93  5335.4  277.19  5473.3  293.86  5500.2  297.04
  5524.1  299.64  5543.5  304.19  5548.7  303.03  5618.5  315.71  5673.3  323.03
#Mann= 7 ,-1 , 0
  4259.1     .16       0  4996.8     .07       0  5002.8     .16       0
  5063.3     .12       0    5321     .16       0  5473.3     .12       0
  5500.2     .16       0
Bank Sta=4950.6,5041.8
XS Rating Curve= 0 ,0
Exp/Cntr=0.3,0.1

Type RM Length L Ch R = 1 ,25072   ,546,546,546
BEGIN DESCRIPTION:
CROOKED CREEK 45.0
END DESCRIPTION:
XS GIS Cut Line= 3
      3741842.87     10598066.11      3741223.08     10599014.02
      3740443.24     10599227.18
#Sta/Elev= 30
    3702  318.54  3880.8  301.24    3923  294.21  4061.8  280.44    4285  272.45
  4517.2  271.29  4538.3  269.95  4544.3  265.51  4553.4  270.04  4580.5  272.13
  4698.2  271.44  4740.4  274.92  4755.5   272.9  4848.5  271.75    4890   274.5
  4921.1  269.96  4949.9  270.81  4972.7  267.01    5001  261.79  5003.8  261.29
    5007  261.79  5029.3  271.78  5076.3  271.85    5138  270.44  5169.9  267.18
  5215.4  269.47  5278.9  276.13  5484.9  298.61  5559.1  313.46    5643   321.2
#Mann= 7 ,-1 , 0
    3702     .16       0  4972.7     .12       0    5001     .07       0
    5007     .12       0  5076.3     .16       0  5215.4     .12       0
  5278.9     .16       0
Bank Sta=4949.9,5029.3
XS Rating Curve= 0 ,0
Exp/Cntr=0.3,0.1

Type RM Length L Ch R = 1 ,24526   ,388,388,388
BEGIN DESCRIPTION:
CROOKED CREEK 44.0
END DESCRIPTION:
XS GIS Cut Line= 3
      3740973.08     10598066.13      3740811.62     10598737.98
      3740488.68     10598941.12
#Sta/Elev= 30
  4198.9  292.43    4232   290.5  4244.2  291.51  4315.9  286.55    4321  287.62
  4347.1  283.38  4460.2  274.19  4572.9  272.57  4604.2   273.6  4625.1  277.09
  4676.2  272.64  4696.7   262.5  4703.9  261.42  4717.3  262.17  4745.9  259.79
  4758.5  260.87  4768.7  264.72    4779  265.39  4943.2  269.32  4973.8     268
  4979.7  263.77    4995  261.19  4997.9  254.95  5000.7  254.45  5003.9  254.95
  5016.2  263.85  5031.5  270.27  5073.9  277.42  5211.2  294.99  5271.4  304.78
#Mann= 3 ,-1 , 0
  4198.9     .16       0  4997.9     .07       0  5003.9     .16       0
Bank Sta=4973.8,5031.5
XS Rating Curve= 0 ,0
Exp/Cntr=0.3,0.1

Type RM Length L Ch R = 1 ,24138   ,767,767,767
BEGIN DESCRIPTION:
CROOKED CREEK 43.0
END DESCRIPTION:
XS GIS Cut Line= 3
      3740899.57     10598110.22      3740499.61     10598460.19
       3740399.6     10598810.22
#Sta/Elev= 30
  4435.2  283.37  4490.7  282.18  4505.9  283.15  4513.5  281.53  4520.1  285.88
  4527.7  282.42  4534.3  283.05  4548.6   279.3  4562.8     280    4577  277.28
  4614.1   275.5  4725.7  269.16  4767.8   268.5  4782.1  266.63  4868.4  265.78
  4969.3  266.41  4983.6  262.08  4994.9  252.24  4997.6  251.74  5000.9  252.24
  5017.4  256.02  5022.6  261.84  5039.5  262.39  5056.4  266.72  5090.2  270.92
  5095.4  269.67  5112.3  273.23    5163  278.58  5235.8  284.64  5330.7  301.84
#Mann= 7 ,-1 , 0
  4435.2     .05       0  4490.7     .16       0  4614.1     .05       0
  4725.7      .1       0  4868.4     .16       0  4994.9     .07       0
  5000.9     .16       0
#XS Ineff= 2 , 0
         4888.25  266.42
Permanent Ineff=
       F       F
Bank Sta=4969.3,5056.4
XS Rating Curve= 0 ,0
Exp/Cntr=0.3,0.1

Type RM Length L Ch R = 1 ,23371   ,225,225,225
BEGIN DESCRIPTION:
Mapping XS addfb507
END DESCRIPTION:
XS GIS Cut Line= 3
      3740723.07     10598050.48      3740009.54     10598389.02
      3739364.13      10598893.9
#Sta/Elev= 30
  4139.9  277.58  4157.4  276.31  4473.4  266.04  4586.5  266.51  4615.8  262.44
  4652.9  257.08  4706.7  265.39  4755.2  264.86  4937.8  264.39  4980.4  255.25
  4990.9  248.31  4993.6  247.81  4996.9  248.31  5030.9  253.53  5037.3  261.44
  5144.9  258.05    5201  268.65  5229.9  262.63  5272.4  264.57  5279.6  258.59
    5286  262.14  5294.1  256.16  5300.4  258.59  5308.5  251.09  5314.9  259.38
    5323  250.75  5329.4  250.75  5343.8   263.6  5364.6  261.57  5749.1  296.35
#Mann= 6 ,-1 , 0
  4139.9     .05       0  4157.4     .16       0  4473.4     .05       0
  4755.2     .16       0  4990.9     .07       0  4996.9     .16       0
Bank Sta=4615.8,5272.4
XS Rating Curve= 0 ,0
Exp/Cntr=0.3,0.1

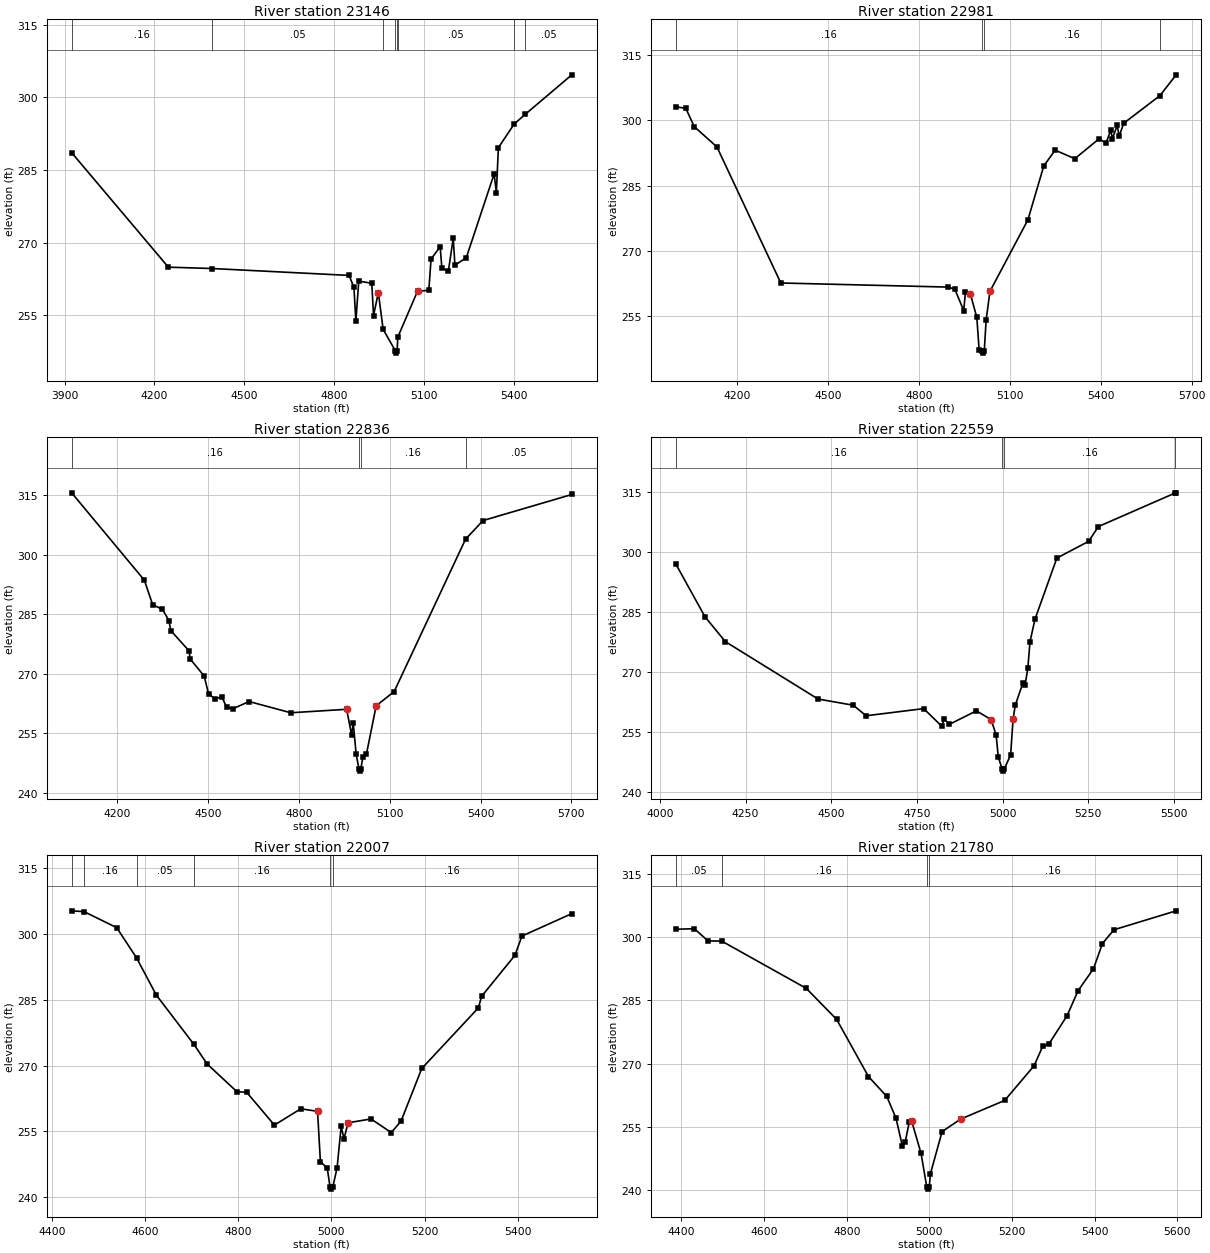
Type RM Length L Ch R = 1 ,23146   ,165,165,165
BEGIN DESCRIPTION:
CROOKED CREEK 42.0
END DESCRIPTION:
XS GIS Cut Line= 3
      3740681.43     10597961.93      3739514.75     10598602.56
      3739264.78      10598831.7
#Sta/Elev= 30
  3923.8  288.57  4246.6  264.96  4392.7  264.68  4850.2  263.26  4866.3   260.8
  4872.8  253.79  4882.4  262.08    4926  261.64  4931.7  254.97  4947.8  259.73
  4963.9  252.13  5004.5  247.73  5007.2  247.23  5010.5  247.73  5012.9  250.55
  5078.6  259.98  5116.4  260.19  5123.8  266.62  5154.3  269.19    5160  264.73
  5181.8  264.18  5197.9  270.94  5203.6  265.36  5241.5  266.91  5334.5   284.2
  5341.9  280.34  5348.7   289.6  5401.6   294.5  5437.7  296.45  5593.9  304.63
#Mann= 8 ,-1 , 0
  3923.8     .16       0  4392.7     .05       0  4963.9     .16       0
  5004.5     .07       0  5010.5     .16       0  5012.9     .05       0
  5401.6     .16       0  5437.7     .05       0
Bank Sta=4947.8,5078.6
XS Rating Curve= 0 ,0
Exp/Cntr=0.3,0.1

Type RM Length L Ch R = 1 ,22981   ,145,145,145
BEGIN DESCRIPTION:
CROOKED CREEK 41.0
END DESCRIPTION:
XS GIS Cut Line= 2
      3740530.34     10597857.79      3739093.74     10598669.78
#Sta/Elev= 30
  3998.7  303.11  4031.2  302.74  4058.6  298.56  4133.7  293.88  4344.4  262.61
  4895.5  261.67  4918.5  261.21  4947.9  256.27  4953.6  260.45  4969.5  260.18
  4991.2  254.69  4998.9  247.16  5009.8  246.99  5012.6  246.49  5015.8  246.99
  5021.9  254.08  5034.5  260.69  5159.7  277.12  5212.1  289.51  5249.6  293.13
  5314.6  291.18  5395.4  295.79  5417.1  294.69    5433  297.69  5438.7   295.8
  5454.6   298.9  5460.4  296.33  5476.3  299.34  5595.3  305.67  5648.9  310.45
#Mann= 4 ,-1 , 0
  3998.7     .16       0  5009.8     .07       0  5015.8     .16       0
  5595.3     .05       0
Bank Sta=4969.5,5034.5
XS Rating Curve= 0 ,0
Exp/Cntr=0.3,0.1

Type RM Length L Ch R = 1 ,22836   ,277,277,277
BEGIN DESCRIPTION:
Mapping XS cc7b1b55
END DESCRIPTION:
XS GIS Cut Line= 2
      3740473.12     10597748.37      3739025.22     10598545.24
#Sta/Elev= 30
  4048.7  315.55  4288.8  293.55  4316.3  287.38  4348.5   286.2  4370.3  283.37
    4376  280.87  4435.6  275.83  4441.3  273.61  4486.5  269.41    4501  264.95
  4522.8  263.58  4544.5  264.25  4560.6  261.54  4582.4   261.2  4634.8  262.99
  4772.8  260.16  4957.4  261.03  4973.5  254.63  4979.2   257.5  4988.7  249.76
    4998  245.96  5000.7  245.46    5004  245.96  5011.3  249.12  5022.9  249.81
  5054.9  261.92  5114.3  265.49  5350.2  303.87  5408.1  308.57  5701.4  315.13
#Mann= 4 ,-1 , 0
  4048.7     .16       0    4998     .07       0    5004     .16       0
  5350.2     .05       0
Bank Sta=4957.4,5054.9
XS Rating Curve= 0 ,0
Exp/Cntr=0.3,0.1

Type RM Length L Ch R = 1 ,22559   ,552,552,552
BEGIN DESCRIPTION:
CROOKED CREEK 40.0
END DESCRIPTION:
XS GIS Cut Line= 3
       3740228.3     10597633.81      3739493.92     10598045.27
      3739015.22     10598435.51
#Sta/Elev= 30
  4047.2   296.9  4131.8  283.77  4191.1  277.56  4461.6  263.18  4564.4  261.63
    4602  258.99  4769.8  260.78  4823.4  256.32  4829.2  258.21  4845.1  256.85
  4923.7  260.22  4966.8  258.02  4981.1  254.24  4987.6  248.65  4998.9  245.63
  5001.7  245.13  5004.9  245.63  5023.6  249.22  5030.7   258.1  5037.1   261.6
  5059.4  267.21  5065.8  266.69  5073.8  270.94  5080.2  277.56  5094.6  283.15
  5158.5  298.48  5251.1  302.65  5279.8  306.37  5503.5  314.76  5506.6  314.81
#Mann= 4 ,-1 , 0
  4047.2     .16       0  4998.9     .07       0  5004.9     .16       0
  5503.5     .05       0
Bank Sta=4966.8,5030.7
XS Rating Curve= 0 ,0
Exp/Cntr=0.3,0.1

Type RM Length L Ch R = 1 ,22007   ,227,227,227
BEGIN DESCRIPTION:
CROOKED CREEK 39.0
END DESCRIPTION:
XS GIS Cut Line= 2
      3739879.33     10597425.48      3738994.29      10598034.6
#Sta/Elev= 30
    4442  305.25  4468.8  305.06  4538.8  301.41  4581.3  294.55  4623.9  286.04
  4704.7  274.81    4733  270.35    4797  264.04    4818   263.9  4877.5  256.43
  4934.3  260.15  4970.2  259.56  4976.3  248.13  4991.1  246.59    4997  242.34
  4999.7  241.84    5003  242.34  5012.2  246.73  5020.9  256.12    5027  253.32
  5035.8  256.96  5085.1  257.83  5128.5  254.73  5149.4   257.3  5194.1  269.33
  5315.7  283.14  5322.6  285.77  5394.3  295.13  5409.2   299.5  5516.4  304.61
#Mann= 6 ,-1 , 0
    4442     .05       0  4468.8     .16       0  4581.3     .05       0
  4704.7     .16       0    4997     .07       0    5003     .16       0
Bank Sta=4970.2,5035.8
XS Rating Curve= 0 ,0
Exp/Cntr=0.3,0.1

Type RM Length L Ch R = 1 ,21780   ,455,455,455
BEGIN DESCRIPTION:
CROOKED CREEK 38.0
END DESCRIPTION:
XS GIS Cut Line= 3
      3739889.74     10597279.65      3739181.42     10597618.19
      3738931.42     10597961.93
#Sta/Elev= 30
    4387  301.89  4431.5  302.02  4464.3  299.12  4497.6  299.08  4702.2  287.87
  4775.7   280.5  4852.7  266.95    4897  262.23  4919.2   257.1  4934.5  250.57
  4941.3  251.33  4951.6  256.29  4957.2  256.38  4979.9  248.73  4993.7  240.76
  4996.5  240.26  4999.7  240.76  5002.5  243.89  5030.8  253.91  5076.1  256.89
  5182.2  261.29  5253.3  269.51  5274.1  274.11  5288.8  274.62  5332.9  281.34
    5360  287.35  5397.1  292.53  5418.7   298.5  5446.6  301.77  5597.1  306.26
#Mann= 4 ,-1 , 0
    4387     .05       0  4497.6     .16       0  4993.7     .07       0
  4999.7     .16       0
Bank Sta=4957.2,5076.1
XS Rating Curve= 0 ,0
Exp/Cntr=0.3,0.1

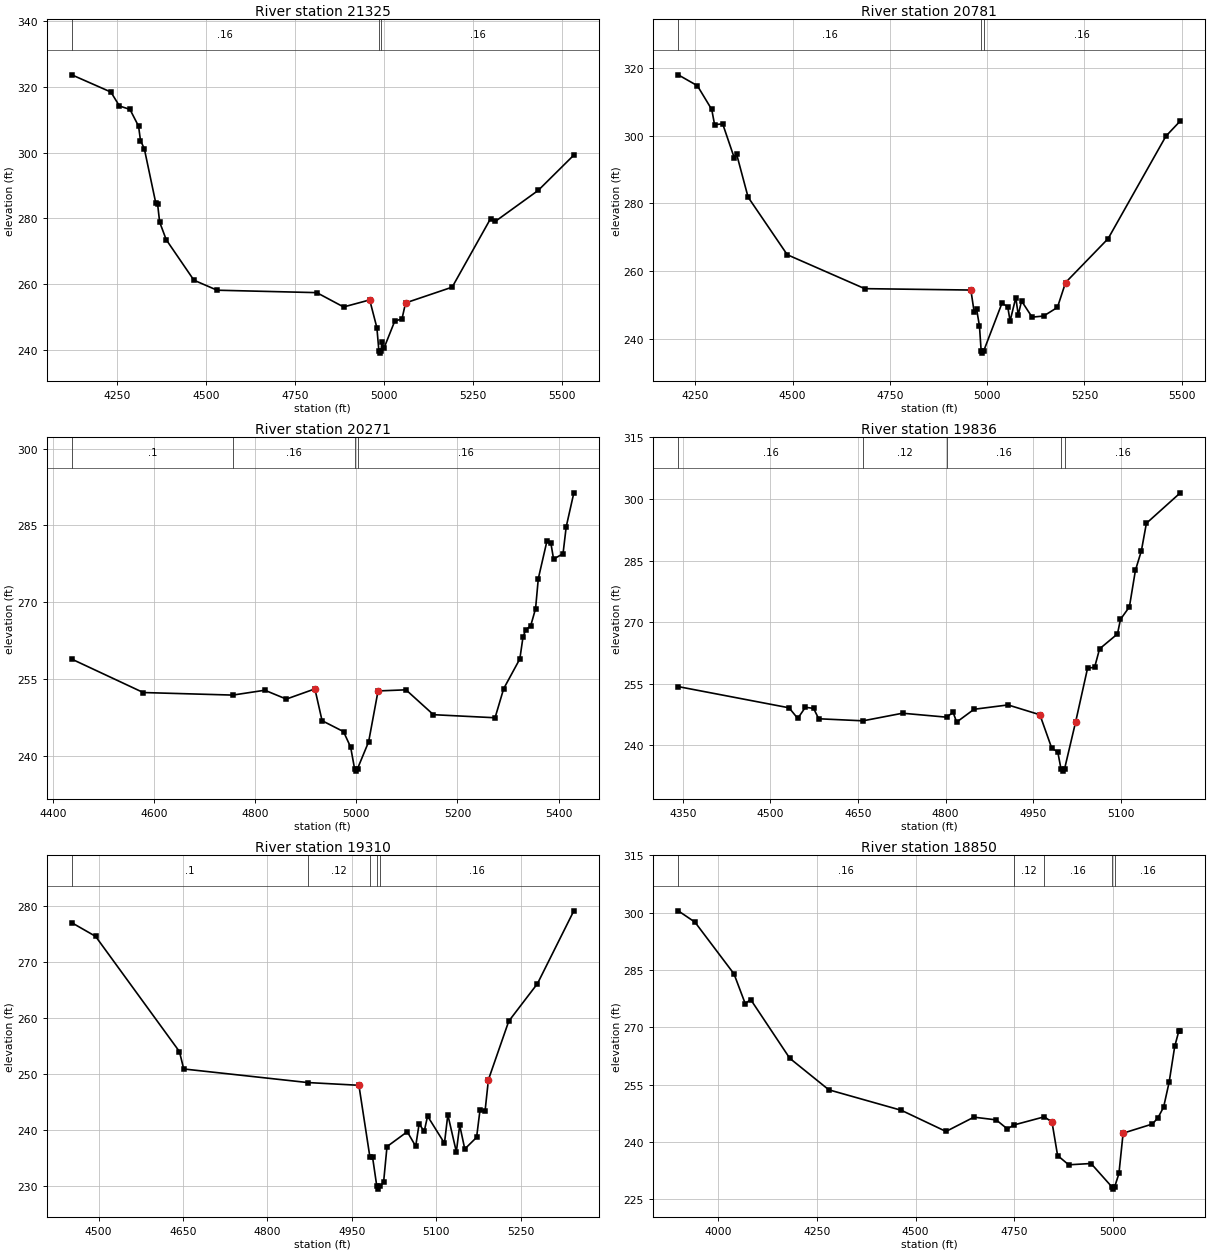
Type RM Length L Ch R = 1 ,21325   ,544,544,544
BEGIN DESCRIPTION:
CROOKED CREEK 37.0
END DESCRIPTION:
XS GIS Cut Line= 3
      3739264.76     10596560.86      3738962.67     10597310.89
      3738884.57     10597909.64
#Sta/Elev= 30
  4121.4  323.69  4231.4  318.45  4255.5   314.2  4285.1  313.16  4309.3  308.05
  4314.7  303.69  4325.5  301.18  4357.6   284.7    4363  284.21  4368.6  278.85
  4387.1  273.48    4465  261.15  4530.3   258.1  4810.6  257.36  4886.1     253
  4959.5  255.14  4979.7  246.69  4985.5  239.44  4988.3  238.94  4991.5  239.44
  4993.6  242.31  4999.9  240.51  5030.1  248.72  5050.3  249.34  5060.4  254.23
  5191.5  259.03  5299.5  279.89  5312.5  279.03  5433.5  288.49  5533.8  299.25
#Mann= 3 ,-1 , 0
  4121.4     .16       0  4985.5     .07       0  4991.5     .16       0
Bank Sta=4959.5,5060.4
XS Rating Curve= 0 ,0
Exp/Cntr=0.3,0.1

Type RM Length L Ch R = 1 ,20781   ,510,510,510
BEGIN DESCRIPTION:
CROOKED CREEK 36.0
END DESCRIPTION:
XS GIS Cut Line= 3
      3739149.63     10596660.16      3738649.61     10597360.19
       3738399.6      10597710.2
#Sta/Elev= 30
  4206.1  317.91  4255.3   314.7  4292.2   307.7  4299.5  303.24  4320.4  303.44
  4349.9  293.51  4356.1  294.55  4385.6  281.87  4486.3   264.9  4685.4   254.9
  4958.2  254.49  4966.8  247.92    4973  248.82  4980.3  243.87  4984.7   236.4
  4987.5   235.9  4990.7   236.4  5038.1   250.6  5052.9  249.59    5059  245.37
  5073.7  252.26  5079.9  247.16  5088.5  251.26  5115.5  246.51    5145  246.82
  5180.7  249.38  5201.6   256.7  5310.9  269.63  5459.6  299.85  5496.5  304.32
#Mann= 3 ,-1 , 0
  4206.1     .16       0  4984.7     .07       0  4990.7     .16       0
Bank Sta=4958.2,5201.6
XS Rating Curve= 0 ,0
Exp/Cntr=0.3,0.1

Type RM Length L Ch R = 1 ,20271   ,435,435,435
BEGIN DESCRIPTION:
CROOKED CREEK 35.0
END DESCRIPTION:
XS GIS Cut Line= 3
      3738699.61     10596760.19      3738299.61     10597160.19
       3737899.6     10597310.19
#Sta/Elev= 30
  4437.3  258.84  4578.7  252.31  4755.7  251.81  4819.1  252.76  4861.6  251.03
  4918.1  253.02  4932.3  246.81  4974.7  244.67  4988.8  241.64  4996.5  237.45
  4999.2  236.95  5002.5  237.45  5024.4  242.69    5043  252.62  5098.2  252.84
  5152.5  247.98  5274.4  247.38  5291.4  253.06  5323.4  258.88  5329.6  263.12
    5335  264.57  5344.8  265.33  5354.5   268.7  5359.9  274.56  5376.8  281.83
  5384.8  281.49  5390.1  278.39  5408.8  279.44  5415.1   284.7  5430.2  291.34
#Mann= 4 ,-1 , 0
  4437.3      .1       0  4755.7     .16       0  4996.5     .07       0
  5002.5     .16       0
Bank Sta=4918.1,5043
XS Rating Curve= 0 ,0
Exp/Cntr=0.3,0.1

Type RM Length L Ch R = 1 ,19836   ,526,526,526
BEGIN DESCRIPTION:
CROOKED CREEK 34.0
END DESCRIPTION:
XS GIS Cut Line= 3
      3738509.23     10596666.52      3738045.71     10596984.22
      3737754.37     10597046.65
#Sta/Elev= 30
    4342   254.3  4531.8  249.14  4546.7  246.55  4559.8  249.27  4573.8     249
  4582.6  246.47  4658.5  245.97  4726.1  247.82  4801.5  246.86  4812.8  248.03
  4818.8  245.65  4848.6  248.78  4906.8  249.84  4961.4  247.45  4981.8  239.27
    4992  238.42  4997.6  234.22  5000.3  233.72  5003.6  234.22  5022.7  245.76
  5043.1  258.82  5055.1  258.98  5063.6  263.49  5094.3  267.13  5099.4  270.68
  5114.7  273.71    5125  282.61  5135.2  287.36  5143.8  294.07  5201.9  301.49
#Mann= 5 ,-1 , 0
    4342     .16       0  4658.5     .12       0  4801.5     .16       0
  4997.6     .07       0  5003.6     .16       0
Bank Sta=4961.4,5022.7
XS Rating Curve= 0 ,0
Exp/Cntr=0.3,0.1

Type RM Length L Ch R = 1 ,19310   ,460,460,460
BEGIN DESCRIPTION:
CROOKED CREEK 33.0
END DESCRIPTION:
XS GIS Cut Line= 3
      3738449.62     10596260.18      3738049.61     10596610.19
      3737749.59      10596810.2
#Sta/Elev= 30
  4452.3     277  4494.6  274.57  4643.6  254.03  4651.2  250.93  4871.3  248.51
  4962.5  248.02  4982.1  235.18  4986.8  235.18  4994.3  230.01  4997.1  229.51
  5000.3  230.01  5006.4  230.79  5012.4  237.09  5048.4  239.74  5063.4  237.15
  5069.5  241.16  5078.5   239.8  5084.5  242.52  5114.5  237.69  5120.5  242.77
  5135.6  236.16  5141.6   240.9  5150.6  236.66  5171.6  238.74  5177.6  243.57
  5186.6  243.38  5192.6  249.01  5228.7  259.44  5279.8  266.15  5344.4  279.12
#Mann= 5 ,-1 , 0
  4452.3      .1       0  4871.3     .12       0  4982.1     .16       0
  4994.3     .07       0  5000.3     .16       0
Bank Sta=4962.5,5192.6
XS Rating Curve= 0 ,0
Exp/Cntr=0.3,0.1

Type RM Length L Ch R = 1 ,18850   ,668,668,668
BEGIN DESCRIPTION:
CROOKED CREEK 32.0
END DESCRIPTION:
XS GIS Cut Line= 3
       3738449.6      10595760.2      3737649.61     10596560.19
      3737549.59      10596660.2
#Sta/Elev= 30
  3898.5  300.49  3940.9  297.53  4039.9  283.99  4068.2  276.25  4082.3  277.27
  4181.3  261.92  4280.3  253.68  4464.2  248.32  4577.3  242.79    4648  246.53
  4704.6  245.82  4732.9  243.44  4748.8  244.47  4826.5  246.62    4846  245.25
  4860.2   236.5  4888.4  234.07    4945  234.41  4998.6  228.21  5001.3  227.71
  5004.6  228.21  5015.7   231.8  5026.3  242.34  5100.6  244.74  5114.7  246.39
  5128.9  249.13    5143  255.69  5157.1  265.02  5167.7  269.11  5171.3  269.11
#Mann= 5 ,-1 , 0
  3898.5     .16       0  4748.8     .12       0  4826.5     .16       0
  4998.6     .07       0  5004.6     .16       0
Bank Sta=4846,5026.3
XS Rating Curve= 0 ,0
Exp/Cntr=0.3,0.1