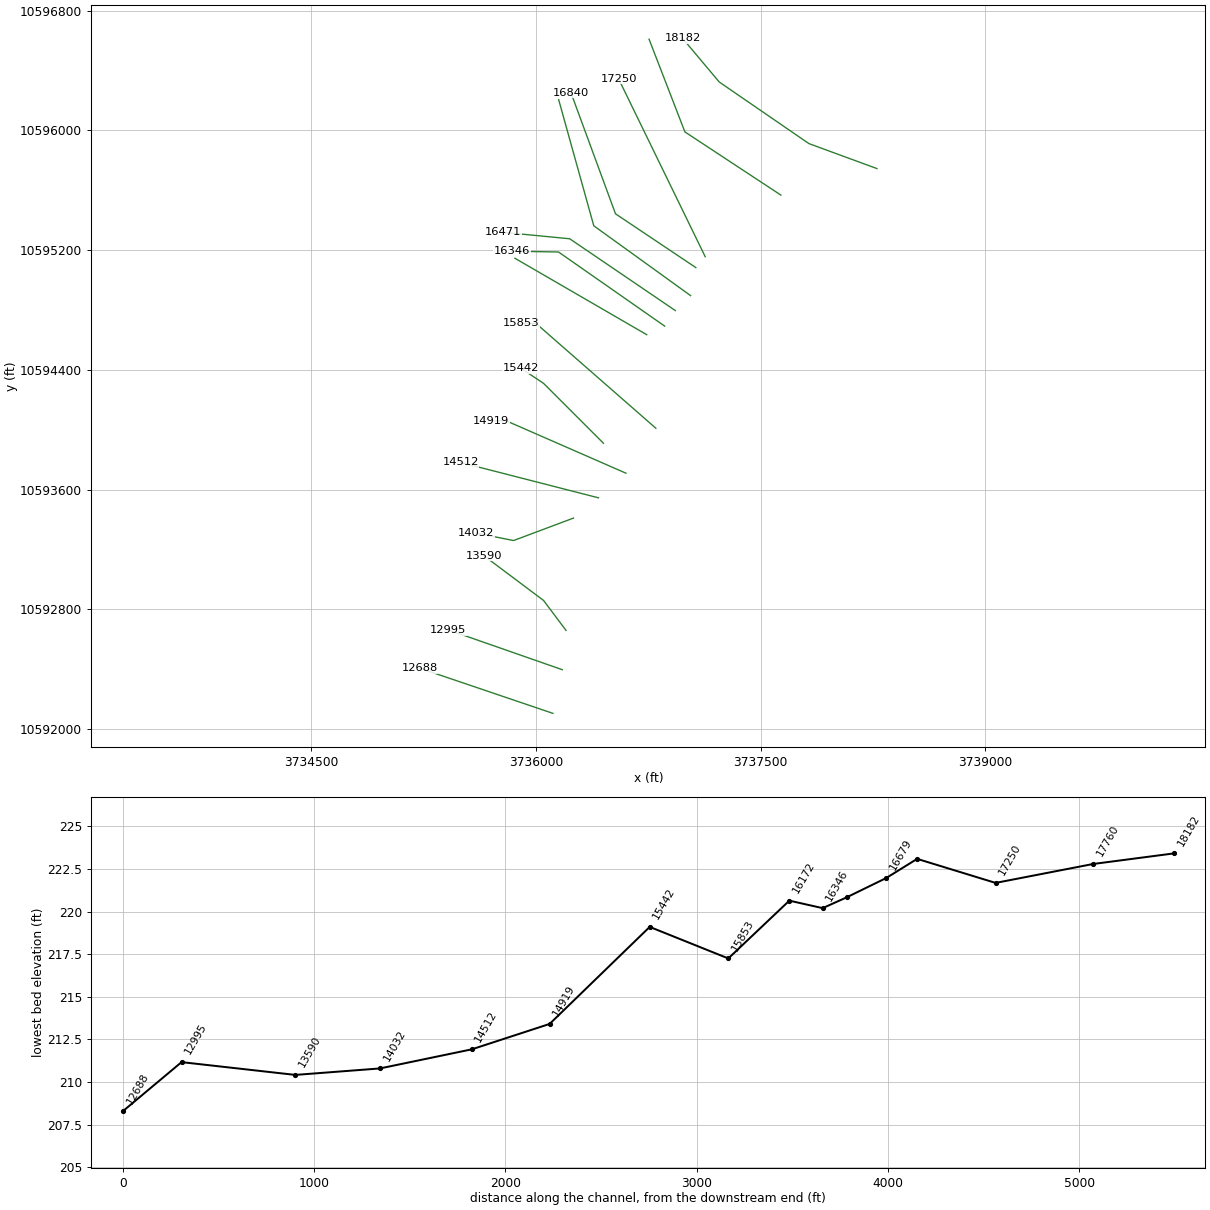
HEC-RAS study CROOKED CREEK.prj: CROOKED CREEK Base Level Engineering

--- CROOKED CREEK.g01 (geometry) --- (continued)

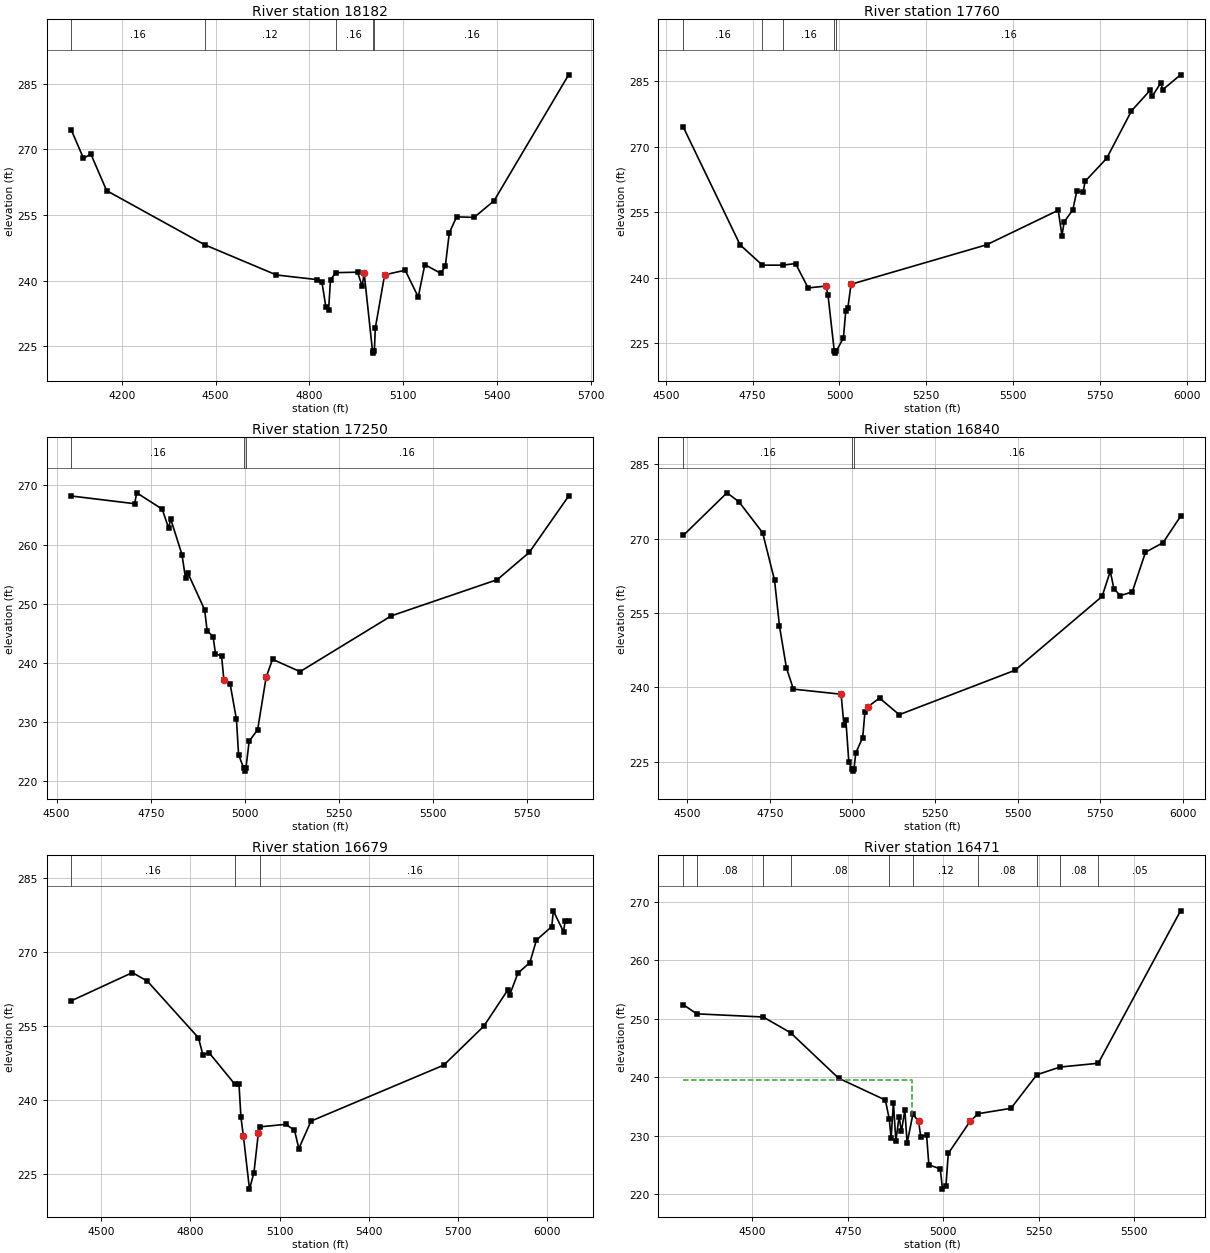
Type RM Length L Ch R = 1 ,18182   ,422,422,422
BEGIN DESCRIPTION:
Mapping XS 5093cbbe
END DESCRIPTION:
XS GIS Cut Line= 4
      3738275.79     10595744.54      3737821.75      10595911.3
      3737222.79     10596322.76      3736978.03     10596614.39
#Sta/Elev= 30
  4038.4  274.41  4076.9     268  4100.9  268.91  4151.2  260.58  4465.4  248.18
  4694.5  241.29  4825.6  240.22  4840.1  239.67  4852.6  233.96  4861.4  233.31
  4867.5  240.19  4884.4  241.82  4954.1  241.93    4969  238.68  4975.1  241.78
  5001.9  223.91  5004.6  223.41  5007.9  223.91  5010.9  229.14  5040.7  241.32
  5106.4  242.38  5148.3  236.26  5169.3  243.68    5220  241.67  5234.9  243.29
  5247.7  250.95    5271  254.59    5327  254.46  5390.7  258.25  5629.5  287.08
#Mann= 5 ,-1 , 0
  4038.4     .16       0  4465.4     .12       0  4884.4     .16       0
  5001.9     .07       0  5007.9     .16       0
Bank Sta=4975.1,5040.7
XS Rating Curve= 0 ,0
Exp/Cntr=0.3,0.1

Type RM Length L Ch R = 1 ,17760   ,510,510,510
BEGIN DESCRIPTION:
Mapping XS 28d1fc05
END DESCRIPTION:
XS GIS Cut Line= 3
      3737634.26     10595567.54      3736993.63     10595989.42
      3736754.32     10596608.51
#Sta/Elev= 30
  4550.7  274.42    4714  247.54  4778.1  242.89  4836.6  242.89  4873.6  243.26
  4909.8  237.69    4961  238.11    4967  236.07    4985  223.29  4987.8  222.79
    4991  223.29  5011.3  226.25  5018.2  232.49  5024.2  233.16  5033.3  238.52
  5423.2  247.54  5629.5  255.43  5640.2  249.66  5646.7  252.81  5671.3   255.5
  5683.1  259.86  5701.3  259.52  5706.6  262.02  5768.9   267.3  5840.3  278.14
  5894.8  282.92  5900.2  281.51  5924.8  284.56  5930.1  282.98  5981.5  286.38
#Mann= 5 ,-1 , 0
  4550.7     .16       0  4778.1     .12       0  4836.6     .16       0
    4985     .07       0    4991     .16       0
Bank Sta=4961,5033.3
XS Rating Curve= 0 ,0
Exp/Cntr=0.3,0.1

Type RM Length L Ch R = 1 ,17250   ,410,410,410
BEGIN DESCRIPTION:
Mapping XS 4639ebc3
END DESCRIPTION:
XS GIS Cut Line= 2
      3737129.06     10595156.06      3736550.91      10596343.6
#Sta/Elev= 30
  4539.1  268.22  4707.1  266.92  4712.6  268.76  4780.3     266  4797.3   262.8
  4802.8  264.35  4832.9  258.29  4842.3  254.27  4847.9  255.26    4893  248.98
  4899.6  245.46  4915.5  244.41  4921.8  241.57  4938.1   241.1  4944.1  237.11
  4960.6  236.47  4977.5  230.44  4983.2  224.47  4996.7  222.18  4999.4  221.68
  5002.7  222.18  5011.3  226.74  5033.8  228.69  5056.4  237.56  5073.4   240.6
  5146.5  238.51    5389  247.95  5670.6  254.08  5755.3  258.68  5859.9  268.21
#Mann= 3 ,-1 , 0
  4539.1     .16       0  4996.7     .07       0  5002.7     .16       0
Bank Sta=4944.1,5056.4
XS Rating Curve= 0 ,0
Exp/Cntr=0.3,0.1

Type RM Length L Ch R = 1 ,16840   ,161,161,161
BEGIN DESCRIPTION:
Mapping XS 8a0abfe3
END DESCRIPTION:
XS GIS Cut Line= 3
      3737066.55     10595083.17      3736530.09     10595442.55
       3736233.2     10596249.87
#Sta/Elev= 30
  4487.9  270.64    4620  279.22    4656  277.44    4728  271.18  4764.1   261.6
  4779.1  252.34  4800.1  243.93  4821.2  239.63  4965.7   238.6  4974.2  232.46
  4980.2  233.34  4989.2  224.87  4998.8  223.59  5001.5  223.09  5004.8  223.59
  5010.2  226.75  5031.2  229.87  5037.9  235.04  5046.2  236.04  5082.2  237.83
  5141.8  234.47  5492.6  243.44  5756.2  258.33    5781   263.4    5792  259.85
  5811.8  258.48  5847.6  259.25  5887.6  267.24  5940.9  269.17  5993.8  274.48
#Mann= 3 ,-1 , 0
  4487.9     .16       0  4998.8     .07       0  5004.8     .16       0
Bank Sta=4965.7,5046.2
XS Rating Curve= 0 ,0
Exp/Cntr=0.3,0.1

Type RM Length L Ch R = 1 ,16679   ,208,208,208
BEGIN DESCRIPTION:
Mapping XS c8d4bc2e
END DESCRIPTION:
XS GIS Cut Line= 3
       3737031.8     10594895.91      3736385.12     10595362.47
      3736150.76     10596204.44
#Sta/Elev= 30
  4399.9  260.18  4604.9  265.89  4655.2  264.16    4827  252.66  4841.7  249.25
  4862.6  249.64  4948.5  243.31  4963.2  243.33  4969.8   236.5  4977.9  232.81
  4998.5  221.97  5013.5  225.32  5028.2  233.27  5034.4  234.61  5120.2  235.11
  5149.7  233.95  5164.4  230.19  5205.3  235.77  5651.8  247.13  5786.6  255.05
  5867.5  262.43  5872.7  261.29  5900.8  265.77  5941.1  267.93  5963.1  272.49
  6014.7  275.23  6019.9  278.42  6054.1  274.19  6059.3  276.28  6071.3  276.32
#Mann= 3 ,-1 , 0
  4399.9     .16       0  4948.5     .16       0  5034.4     .16       0
Bank Sta=4977.9,5028.2
XS Rating Curve= 0 ,0
Exp/Cntr=0.3,0.1

Type RM Length L Ch R = 1 ,16471   ,125,125,125
BEGIN DESCRIPTION:
Mapping XS 3a0c29cc
END DESCRIPTION:
XS GIS Cut Line= 3
      3736929.81     10594796.07      3736224.53     10595275.67
      3735777.53     10595319.06
#Sta/Elev= 30
  4319.1  252.37  4354.2  250.81  4528.3  250.27  4599.9  247.58  4725.5  239.81
  4848.2  236.06  4858.4  232.79  4863.2  229.55  4869.2  235.64  4875.6  229.06
  4884.1  233.25  4890.2  230.69  4899.1  234.38  4905.1  228.71  4920.1   233.6
    4935  232.49    4941  229.71    4956  230.15    4962  224.98  4991.9   224.3
  4997.7  220.83  5006.8  221.38  5012.9  226.93  5069.8  232.41  5091.2  233.73
    5177  234.65  5244.9   240.4  5305.8  241.71  5405.6  242.36  5621.1  268.43
#Mann= 10 ,-1 , 0
  4319.1     .05       0  4354.2     .08       0  4528.3     .16       0
  4599.9     .08       0  4858.4     .05       0  4920.1     .12       0
  5091.2     .08       0  5244.9     .05       0  5305.8     .08       0
  5405.6     .05       0
#XS Ineff= 2 , 0
         4919.09  239.46
Permanent Ineff=
       F       F
Bank Sta=4935,5069.8
XS Rating Curve= 0 ,0
Exp/Cntr=0.3,0.1

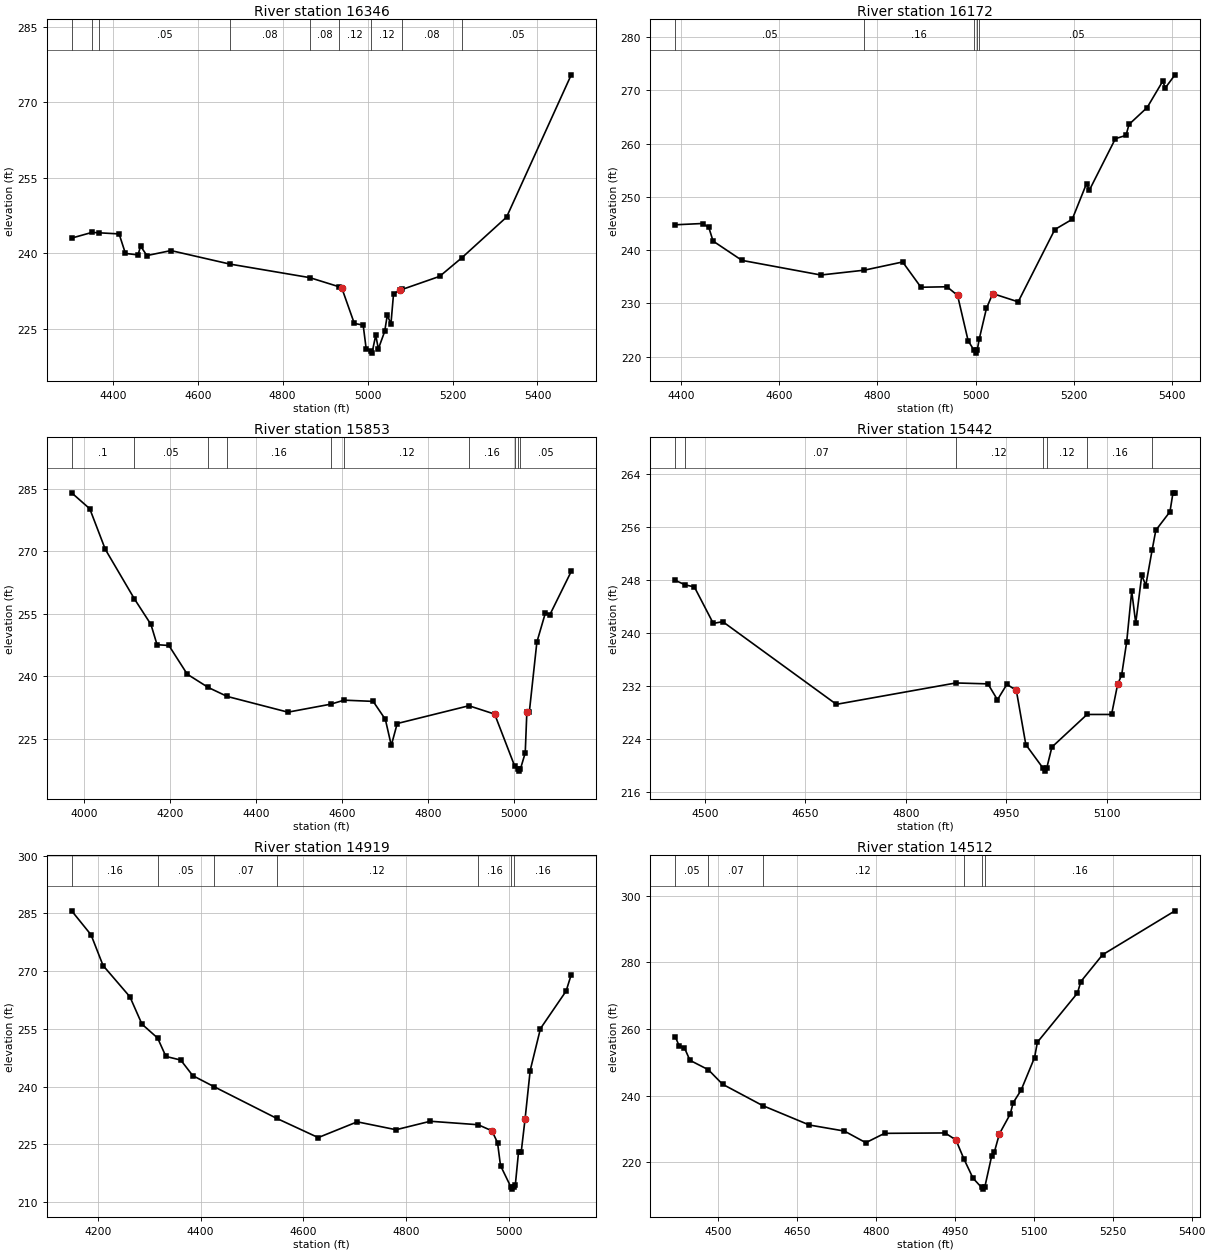
Type RM Length L Ch R = 1 ,16346   ,174,174,174
BEGIN DESCRIPTION:
CROOKED CREEK 27.0
END DESCRIPTION:
XS GIS Cut Line= 3
      3736858.23     10594692.54      3736149.88     10595187.34
      3735837.38     10595192.55
#Sta/Elev= 30
    4303  243.05  4350.9  244.18  4367.7   244.1  4414.8  243.88  4429.6  240.01
  4459.3  239.71  4465.4  241.45  4480.2  239.58  4536.9  240.57  4675.5  237.89
  4863.6   235.2  4932.9  233.38    4939  233.19  4968.7   226.1  4989.6  225.76
  4996.6  221.08  5007.5   220.7  5010.3   220.2  5019.2  223.77  5025.3  221.04
  5040.2   224.5  5046.3  227.71    5055  226.03  5061.1  231.99  5075.9  232.69
    5082  232.87  5169.7  235.45  5221.8  239.13  5327.3  247.22  5479.6  275.48
#Mann= 9 ,-1 , 0
    4303     .16       0  4350.9     .08       0  4367.7     .05       0
  4675.5     .08       0  4863.6     .08       0  4932.9     .12       0
  5007.5     .12       0    5082     .08       0  5221.8     .05       0
Bank Sta=4939,5075.9
XS Rating Curve= 0 ,0
Exp/Cntr=0.3,0.1

Type RM Length L Ch R = 1 ,16172   ,319,319,319
BEGIN DESCRIPTION:
Mapping XS e6accafd
END DESCRIPTION:
XS GIS Cut Line= 2
      3736738.44     10594635.24      3735858.66     10595145.41
#Sta/Elev= 30
  4388.6  244.76  4443.8     245  4456.6  244.27  4465.3   241.7  4524.1  238.07
  4684.8  235.32  4773.2  236.23  4851.2  237.77  4888.5  233.02  4941.5  233.11
    4963  231.49  4984.6  222.94  4996.9  221.14  4999.7  220.64  5002.9  221.14
  5007.1  223.27  5021.8  229.05  5034.6  231.83  5086.4  230.28    5161  243.87
  5196.4  245.79  5225.5  252.49  5231.3  251.26  5284.3  260.94  5305.9  261.56
    5312  263.62  5348.9  266.79  5380.4   271.7  5386.2  270.52  5405.6  272.94
#Mann= 5 ,-1 , 0
  4388.6     .05       0  4773.2     .16       0  4996.9     .07       0
  5002.9     .16       0  5007.1     .05       0
Bank Sta=4963,5034.6
XS Rating Curve= 0 ,0
Exp/Cntr=0.3,0.1

Type RM Length L Ch R = 1 ,15853   ,411,411,411
BEGIN DESCRIPTION:
CROOKED CREEK 26.0
END DESCRIPTION:
XS GIS Cut Line= 3
      3736799.61     10594010.19      3735999.61     10594710.19
      3735899.62     10594710.19
#Sta/Elev= 30
  3970.5  284.08  4012.7  280.25  4048.8  270.52  4116.3  258.66  4155.1  252.47
  4169.3  247.61  4196.9  247.42  4239.6  240.53  4288.5  237.34  4332.8  235.18
    4474  231.41  4573.8  233.33  4604.8  234.29  4672.4     234  4700.8  229.67
  4714.6  223.42  4728.4  228.68  4895.3  232.95  4955.2  230.94  5001.8  218.47
  5009.2  217.75  5011.9  217.25  5015.2  217.75  5026.4  221.64  5030.2  231.52
    5036  231.52  5053.5  248.23  5073.5  255.32  5083.5  254.76  5133.5  265.21
#Mann= 10 ,-1 , 0
  3970.5      .1       0  4116.3     .05       0  4288.5     .12       0
  4332.8     .16       0  4573.8     .05       0  4604.8     .12       0
  4895.3     .16       0  5001.8     .05       0  5009.2     .07       0
  5015.2     .05       0
Bank Sta=4955.2,5030.2
XS Rating Curve= 0 ,0
Exp/Cntr=0.3,0.1

Type RM Length L Ch R = 1 ,15442   ,523,523,523
BEGIN DESCRIPTION:
CROOKED CREEK 25.0
END DESCRIPTION:
XS GIS Cut Line= 3
      3736449.63     10593910.17      3736049.61     10594310.19
       3735899.6     10594410.19
#Sta/Elev= 30
  4455.9  247.91  4470.7  247.23  4484.2  246.93  4512.5  241.41  4526.6  241.68
  4696.3  229.19  4874.8  232.42  4922.6  232.28  4936.8  229.88  4950.9  232.21
    4965   231.3  4979.2   223.1  5004.5   219.6  5007.2   219.1  5010.5   219.6
  5018.1  222.73  5070.6  227.66  5107.2  227.66  5116.3  232.22  5122.3  233.63
  5129.8  238.64  5137.3  246.28  5143.3  241.46  5152.3   248.7  5158.3  247.14
  5167.9  252.57  5173.3  255.49  5194.4  258.28  5198.9  261.14  5201.9  261.14
#Mann= 7 ,-1 , 0
  4455.9     .05       0  4470.7     .07       0  4874.8     .12       0
  5004.5     .07       0  5010.5     .12       0  5070.6     .16       0
  5167.9     .05       0
Bank Sta=4965,5116.3
XS Rating Curve= 0 ,0
Exp/Cntr=0.3,0.1

Type RM Length L Ch R = 1 ,14919   ,407,407,407
BEGIN DESCRIPTION:
CROOKED CREEK 24.0
END DESCRIPTION:
XS GIS Cut Line= 3
      3736599.64     10593710.18      3735799.61     10594060.19
      3735699.66     10594060.19
#Sta/Elev= 30
  4148.9  285.66  4186.7  279.43  4210.1  271.46  4262.4  263.34  4285.8  256.25
  4316.4  252.63  4332.5  247.86  4361.4  246.92  4384.8  242.88  4426.2  240.01
  4548.2  231.79  4629.2  226.79  4705.2  230.88  4780.8  228.83  4847.5  231.03
  4940.7  230.13  4967.6  228.55  4978.5  225.48  4984.3  219.53  5004.7  213.91
  5007.5  213.41  5010.7  213.91  5013.2  214.54  5019.4  223.01  5024.6  223.01
  5032.1  231.53  5042.1   244.2  5062.1  255.08  5112.1  264.83  5122.1   269.1
#Mann= 7 ,-1 , 0
  4148.9     .16       0  4316.4     .05       0  4426.2     .07       0
  4548.2     .12       0  4940.7     .16       0  5004.7     .07       0
  5010.7     .16       0
Bank Sta=4967.6,5032.1
XS Rating Curve= 0 ,0
Exp/Cntr=0.3,0.1

Type RM Length L Ch R = 1 ,14512   ,480,480,480
BEGIN DESCRIPTION:
Mapping XS 1f36ccbb
END DESCRIPTION:
XS GIS Cut Line= 2
       3736416.4     10593545.48      3735496.21      10593781.6
#Sta/Elev= 30
  4418.3  257.59  4425.3  255.01  4435.6  254.31    4446   250.6    4481  247.77
  4507.9  243.43  4584.2  237.01  4673.1  231.17  4739.6  229.36  4780.4  225.86
    4816  228.67  4931.2  228.79  4951.8  226.68    4967  220.96  4984.2  215.22
  5000.5  212.42  5003.2  211.92  5006.5  212.42  5019.8  221.92  5024.9  223.09
  5034.4  228.51  5055.1  234.48  5060.5  237.83  5075.7  241.64  5101.3  251.44
  5106.7  256.05  5182.8  270.78  5189.3  274.25  5230.6   282.3  5368.3  295.49
#Mann= 6 ,-1 , 0
  4418.3     .05       0    4481     .07       0  4584.2     .12       0
    4967     .16       0  5000.5     .07       0  5006.5     .16       0
Bank Sta=4951.8,5034.4
XS Rating Curve= 0 ,0
Exp/Cntr=0.3,0.1

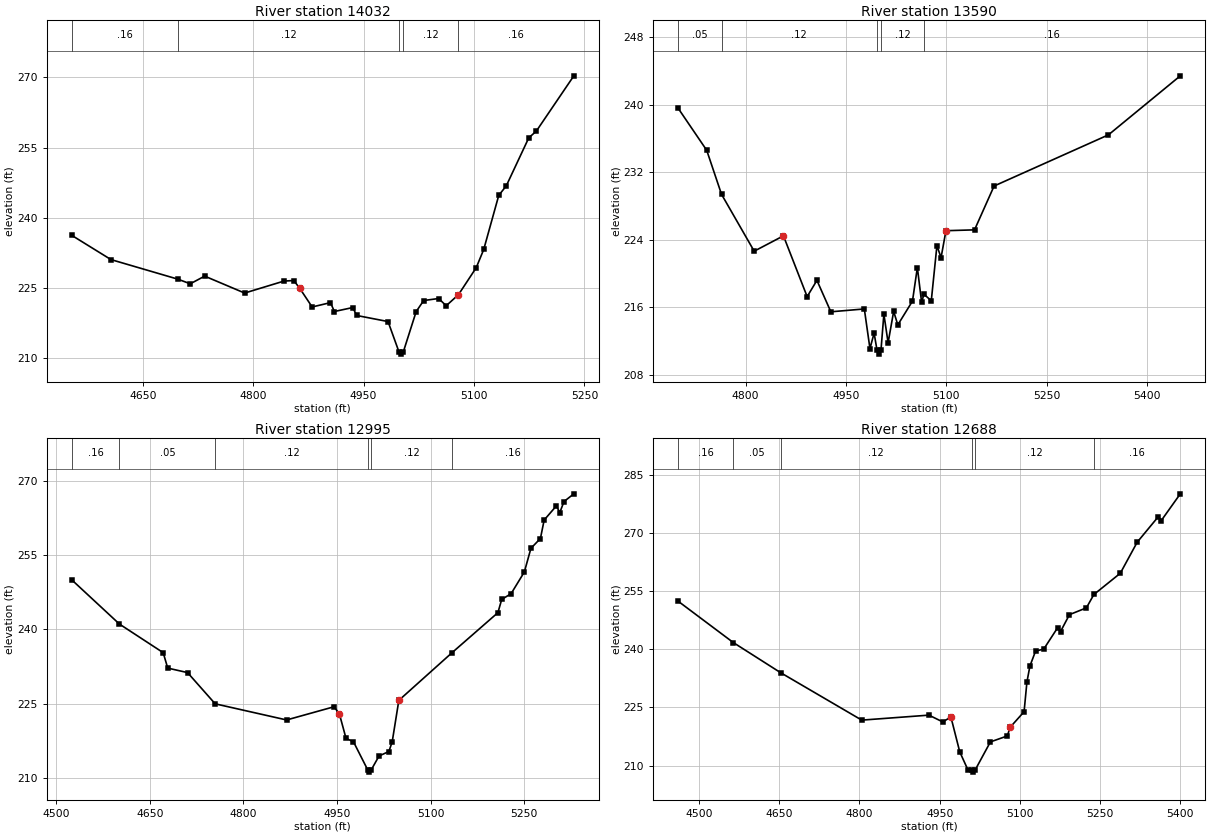
Type RM Length L Ch R = 1 ,14032   ,442,442,442
BEGIN DESCRIPTION:
CROOKED CREEK 22.0
END DESCRIPTION:
XS GIS Cut Line= 3
      3736249.65      10593410.2      3735849.61     10593260.19
      3735599.61     10593310.19
#Sta/Elev= 30
  4553.4  236.23  4606.8  231.03  4697.9  226.83  4714.5  225.85  4734.1  227.49
  4788.4  223.87  4841.8  226.43  4855.2  226.55  4863.2  224.89  4880.1  220.89
    4905  221.82  4910.3  219.92  4935.3  220.77  4940.6  219.07  4983.2  217.77
    4998   211.3  5000.8   210.8    5004   211.3  5021.4   219.9  5031.6  222.27
    5052   222.7  5062.2  221.15  5078.9  223.53    5103   229.3  5113.2   233.2
  5133.6  244.77  5143.8   246.8  5174.4  257.09  5184.6  258.51  5235.6  270.35
#Mann= 5 ,-1 , 0
  4553.4     .16       0  4697.9     .12       0    4998     .07       0
    5004     .12       0  5078.9     .16       0
Bank Sta=4863.2,5078.9
XS Rating Curve= 0 ,0
Exp/Cntr=0.3,0.1

Type RM Length L Ch R = 1 ,13590   ,595,595,595
BEGIN DESCRIPTION:
CROOKED CREEK 21.0
END DESCRIPTION:
XS GIS Cut Line= 3
      3736199.62     10592660.18      3736049.61     10592860.19
      3735649.62     10593160.18
#Sta/Elev= 30
  4699.3  239.59    4742   234.6  4764.1  229.38  4812.9  222.63  4856.6  224.45
    4892  217.24  4906.6  219.17  4927.4  215.44  4977.4  215.78  4985.8  211.08
    4992  212.91  4996.3  210.92  4999.1  210.42  5002.3  210.92  5006.6  215.17
  5012.9  211.76  5021.2  215.49  5027.4  213.89  5049.3  216.71  5056.6  220.69
  5062.9   216.6  5066.5  217.52  5077.4  216.75  5085.8  223.28    5092  221.87
  5099.3  225.06    5142  225.16  5171.2  230.36    5342  236.43  5449.3  243.43
#Mann= 5 ,-1 , 0
  4699.3     .05       0  4764.1     .12       0  4996.3     .07       0
  5002.3     .12       0  5066.5     .16       0
Bank Sta=4856.6,5099.3
XS Rating Curve= 0 ,0
Exp/Cntr=0.3,0.1

Type RM Length L Ch R = 1 ,12995   ,307,307,307
BEGIN DESCRIPTION:
Mapping XS a78f8693
END DESCRIPTION:
XS GIS Cut Line= 2
      3736175.09     10592397.47      3735414.65      10592663.1
#Sta/Elev= 30
  4524.4  250.04  4601.1  241.08  4671.2  235.31  4678.5  232.19  4710.3  231.28
  4754.6  224.97  4869.2  221.71  4945.3  224.38  4953.9  222.91  4964.5  217.98
  4976.4  217.31  4999.1  211.67  5001.9  211.17  5005.1  211.67  5017.5  214.44
  5033.2  215.33  5038.6  217.33  5049.2  225.67  5134.6  235.31  5208.1  243.39
  5214.2  246.06  5229.3  247.23  5250.5  251.61  5261.1   256.4  5276.3  258.37
  5282.3  262.11    5302  264.98  5307.3  263.59  5314.1  265.84  5329.9   267.4
#Mann= 6 ,-1 , 0
  4524.4     .16       0  4601.1     .05       0  4754.6     .12       0
  4999.1     .07       0  5005.1     .12       0  5134.6     .16       0
Bank Sta=4953.9,5049.2
XS Rating Curve= 0 ,0
Exp/Cntr=0.3,0.1

Type RM Length L Ch R = 1 ,12688   ,522,522,522
BEGIN DESCRIPTION:
Mapping XS b5e450d9
END DESCRIPTION:
XS GIS Cut Line= 2
      3736112.55     10592105.82      3735223.31     10592407.43
#Sta/Elev= 30
    4461  252.47  4564.3  241.77  4652.6     234  4804.4  221.73    4930  223.02
  4956.1  221.25    4971  222.57  4987.6  213.53  5002.6  208.96  5010.2  208.79
    5013  208.29  5016.2  208.79  5044.9   216.1  5076.5  217.64  5081.8  219.87
  5107.9  223.91  5113.2  231.58  5118.8  235.71  5129.4  239.59  5144.6  240.08
  5170.7  245.63    5176  244.61  5192.7  248.99  5224.4  250.75  5238.4   254.2
  5287.8  259.69  5319.4  267.72  5359.1  274.35  5364.4  273.31    5400  280.22
#Mann= 6 ,-1 , 0
    4461     .16       0  4564.3     .05       0  4652.6     .12       0
  5010.2     .07       0  5016.2     .12       0  5238.4     .16       0
Bank Sta=4971,5081.8
XS Rating Curve= 0 ,0
Exp/Cntr=0.3,0.1