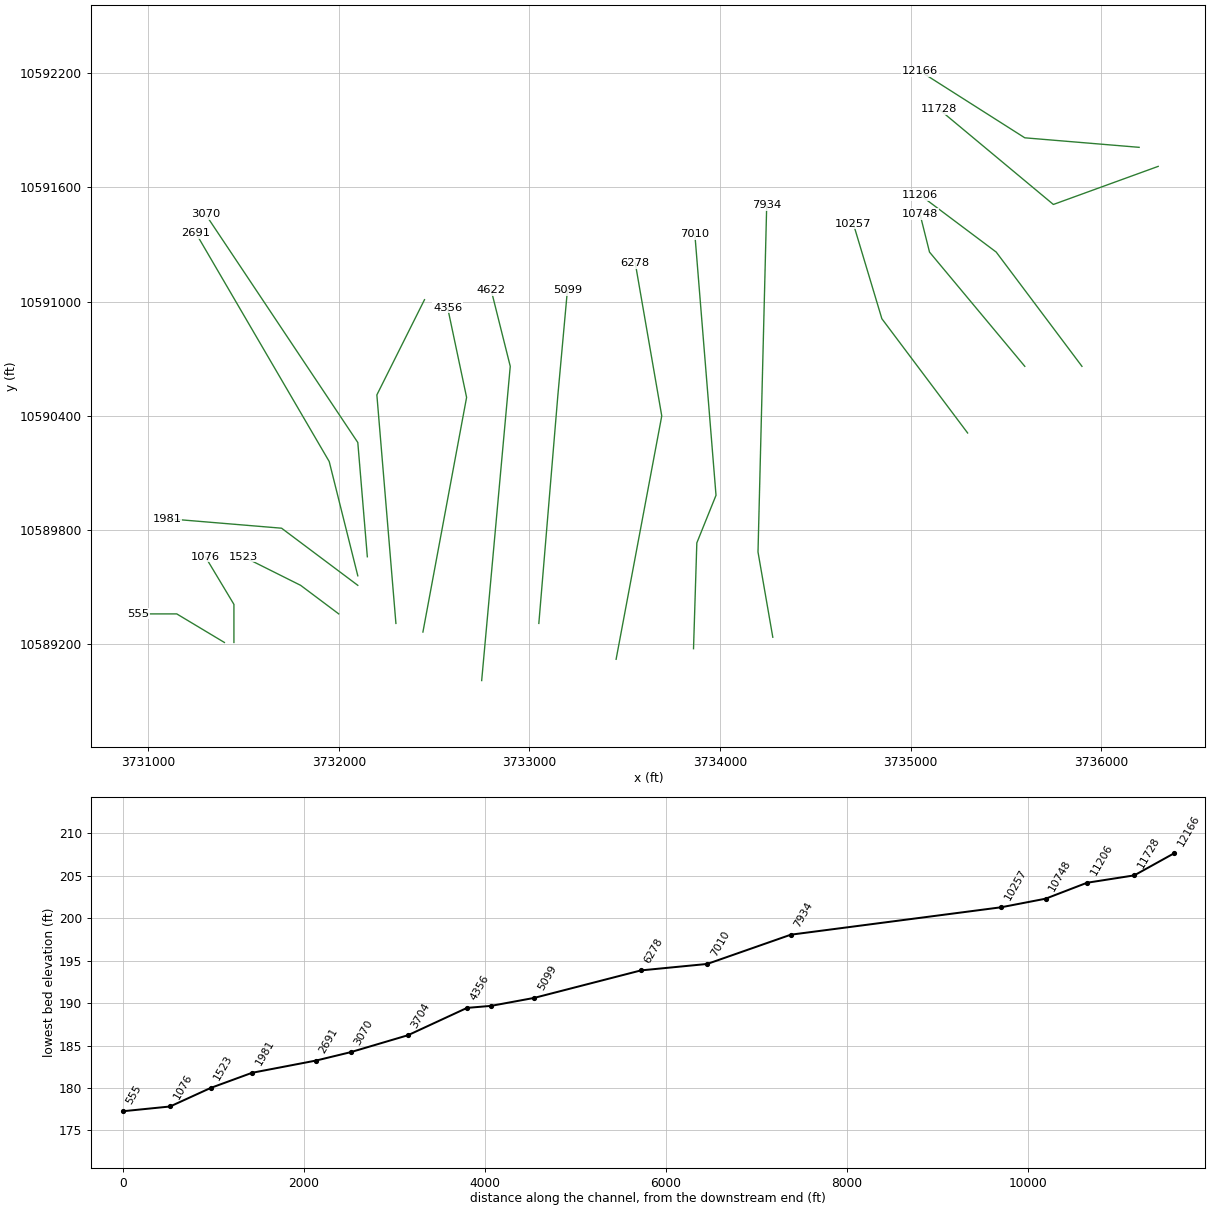
HEC-RAS study CROOKED CREEK.prj: CROOKED CREEK Base Level Engineering

--- CROOKED CREEK.g01 (geometry) --- (continued)

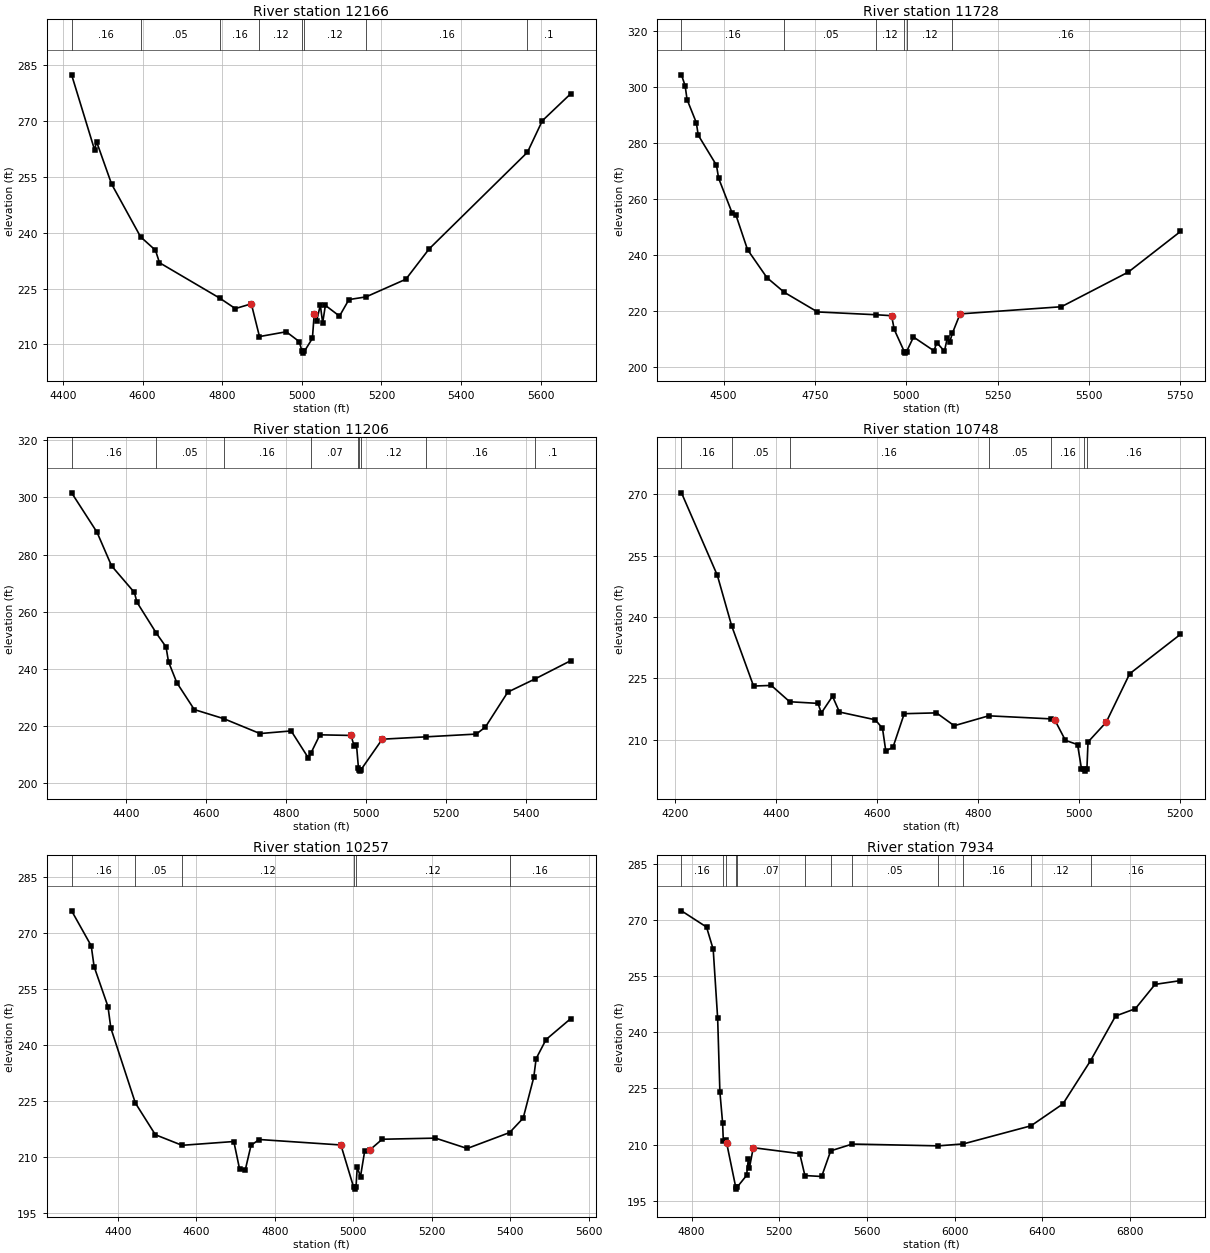
Type RM Length L Ch R = 1 ,12166   ,438,438,438
BEGIN DESCRIPTION:
CROOKED CREEK 18.0
END DESCRIPTION:
XS GIS Cut Line= 3
      3736199.63     10591810.19      3735599.61     10591860.19
      3735049.63     10592210.18
#Sta/Elev= 30
  4421.4  282.44  4479.1  262.28  4484.1  264.48  4521.8   253.1  4594.8  238.89
  4632.1   235.3  4642.2  231.95  4793.9  222.41  4832.8  219.62    4873   220.9
  4893.5   212.1  4960.8  213.39  4993.4  210.75  5000.4  208.15  5003.2  207.65
  5006.4  208.15  5026.5  211.62  5031.1  218.19    5037   216.2  5046.4  220.58
  5052.3  215.77  5059.1  220.49  5094.6   217.6  5118.3  222.04  5161.1  222.76
  5261.4  227.51  5319.8  235.65  5566.9  261.63  5604.3   270.1  5675.4  277.33
#Mann= 8 ,-1 , 0
  4421.4     .16       0  4594.8     .05       0  4793.9     .16       0
  4893.5     .12       0  5000.4     .07       0  5006.4     .12       0
  5161.1     .16       0  5566.9      .1       0
Bank Sta=4873,5031.1
XS Rating Curve= 0 ,0
Exp/Cntr=0.3,0.1

Type RM Length L Ch R = 1 ,11728   ,522,522,522
BEGIN DESCRIPTION:
CROOKED CREEK 17.0
END DESCRIPTION:
XS GIS Cut Line= 3
      3736299.61     10591710.19      3735749.61     10591510.19
      3735149.58     10592010.22
#Sta/Elev= 30
  4384.6   304.3  4394.6   300.4  4399.9  295.49  4425.2  287.26  4430.5  282.78
  4480.4  272.06  4486.3  267.44  4522.9  255.16  4533.6  254.34  4565.5  241.95
  4618.7  231.96  4666.2  226.74    4757  219.75  4918.2  218.74  4959.9  218.41
  4967.2  213.49  4994.8  205.56  4997.6  205.06  5000.8  205.56  5019.9   210.8
  5075.9  205.88  5083.7  208.82  5104.6  205.73  5112.4  210.43  5118.9  208.91
  5126.1  212.07  5147.5  219.05  5424.8   221.6  5608.3  233.98  5750.9  248.44
#Mann= 6 ,-1 , 0
  4384.6     .16       0  4666.2     .05       0  4918.2     .12       0
  4994.8     .07       0  5000.8     .12       0  5126.1     .16       0
Bank Sta=4959.9,5147.5
XS Rating Curve= 0 ,0
Exp/Cntr=0.3,0.1

Type RM Length L Ch R = 1 ,11206   ,458,458,458
BEGIN DESCRIPTION:
CROOKED CREEK 16.0
END DESCRIPTION:
XS GIS Cut Line= 3
      3735899.63     10590660.16      3735449.61     10591260.19
      3735049.64     10591560.17
#Sta/Elev= 30
  4262.6  301.61  4326.2  287.82  4362.6  276.06  4419.9  266.72  4426.2  263.33
  4475.2   252.4  4499.1  247.68  4505.3  242.47  4526.2  235.14  4569.9  225.74
  4643.8  222.55  4734.5  217.34  4812.6  218.26  4855.3  208.88  4862.1   210.5
  4884.5   216.9  4962.6  216.68  4969.9  213.11  4976.2  213.45  4981.2  205.19
  4981.5  204.69  4984.3  204.19  4987.5  204.69  5040.8  215.37  5149.8  216.19
  5276.2  217.16  5299.1  219.61  5355.3  231.86  5422.9  236.42  5512.6  242.83
#Mann= 9 ,-1 , 0
  4262.6     .16       0  4475.2     .05       0  4643.8     .16       0
  4862.1     .07       0  4981.2     .12       0  4981.5     .07       0
  4987.5     .12       0  5149.8     .16       0  5422.9      .1       0
Bank Sta=4962.6,5040.8
XS Rating Curve= 0 ,0
Exp/Cntr=0.3,0.1

Type RM Length L Ch R = 1 ,10748   ,491,491,491
BEGIN DESCRIPTION:
CROOKED CREEK 15.0
END DESCRIPTION:
XS GIS Cut Line= 3
      3735599.64     10590660.16      3735099.61     10591260.19
      3735049.61     10591460.17
#Sta/Elev= 30
    4213  270.34    4284  250.16  4312.3  237.83  4355.6  223.11  4390.7  223.26
  4427.1  219.27  4483.1  218.87  4489.7  216.52  4511.8  220.61  4525.5  216.76
  4596.4  214.86  4610.7  212.78  4617.2  207.24  4631.5  208.16  4653.7  216.35
  4717.5  216.55  4752.6  213.41  4820.8  215.83  4944.5  215.08  4951.8  214.76
  4972.6  209.83  4996.6   208.8  5004.4  202.86  5009.1  202.81  5011.9  202.31
  5015.1  202.81  5017.3  209.43  5053.3  214.27  5099.7  226.11  5200.2  235.75
#Mann= 7 ,-1 , 0
    4213     .16       0  4312.3     .05       0  4427.1     .16       0
  4820.8     .05       0  4944.5     .16       0  5009.1     .07       0
  5015.1     .16       0
Bank Sta=4951.8,5053.3
XS Rating Curve= 0 ,0
Exp/Cntr=0.3,0.1

Type RM Length L Ch R = 1 ,10257   ,2323,2323,2323
BEGIN DESCRIPTION:
CROOKED CREEK 14.0
END DESCRIPTION:
XS GIS Cut Line= 3
       3735299.6      10590310.2      3734849.61     10590910.19
      3734699.61     10591410.19
#Sta/Elev= 30
  4282.2     276  4332.2   266.6  4339.5  261.04  4374.9   250.3  4382.2  244.52
  4444.6  224.43  4495.7   215.9  4563.8  213.06  4695.7  214.08  4710.3  206.71
  4724.9  206.47  4739.5  213.05  4760.3  214.62  4968.6  213.15  5001.1   201.8
  5003.8   201.3  5007.1   201.8  5010.3  207.14  5018.6  204.68  5029.1  211.41
  5042.6  211.84  5073.9  214.69  5209.7  214.99  5290.6  212.21  5398.8  216.49
  5433.3  220.36  5460.2  231.27  5466.3  236.33  5491.6  241.45  5554.2  247.04
#Mann= 6 ,-1 , 0
  4282.2     .16       0  4444.6     .05       0  4563.8     .12       0
  5001.1     .07       0  5007.1     .12       0  5398.8     .16       0
Bank Sta=4968.6,5042.6
XS Rating Curve= 0 ,0
Exp/Cntr=0.3,0.1

Type RM Length L Ch R = 1 ,7934    ,924,924,924
BEGIN DESCRIPTION:
Mapping XS 30a4a733
END DESCRIPTION:
XS GIS Cut Line= 3
      3734277.28     10589237.61      3734199.66     10589685.08
      3734245.29     10591505.95
#Sta/Elev= 30
  4753.9  272.47  4868.2  268.13  4898.6  262.18  4918.9  243.74  4929.1  224.07
  4941.5  215.76  4944.7  210.99  4956.7  211.26  4959.5  210.53  5001.4  198.57
  5004.1  198.07  5007.4  198.57  5050.9  201.75    5059  206.17  5064.1   203.8
  5081.3  209.15  5293.2  207.56  5316.8   201.7  5393.2  201.45  5434.4   208.3
  5532.6  210.12  5925.4  209.64  6039.4  210.16  6347.9     215  6493.6  220.86
  6619.5  232.41  6733.6  244.35  6823.7   246.3  6913.7  252.81  7029.5  253.81
#Mann= 12 ,-1 , 0
  4753.9     .16       0  4941.5     .12       0  4956.7     .07       0
  5001.4     .07       0  5007.4     .07       0  5316.8     .12       0
  5434.4     .07       0  5532.6     .05       0  5925.4     .12       0
  6039.4     .16       0  6347.9     .12       0  6619.5     .16       0
Bank Sta=4959.5,5081.3
XS Rating Curve= 0 ,0
Exp/Cntr=0.3,0.1

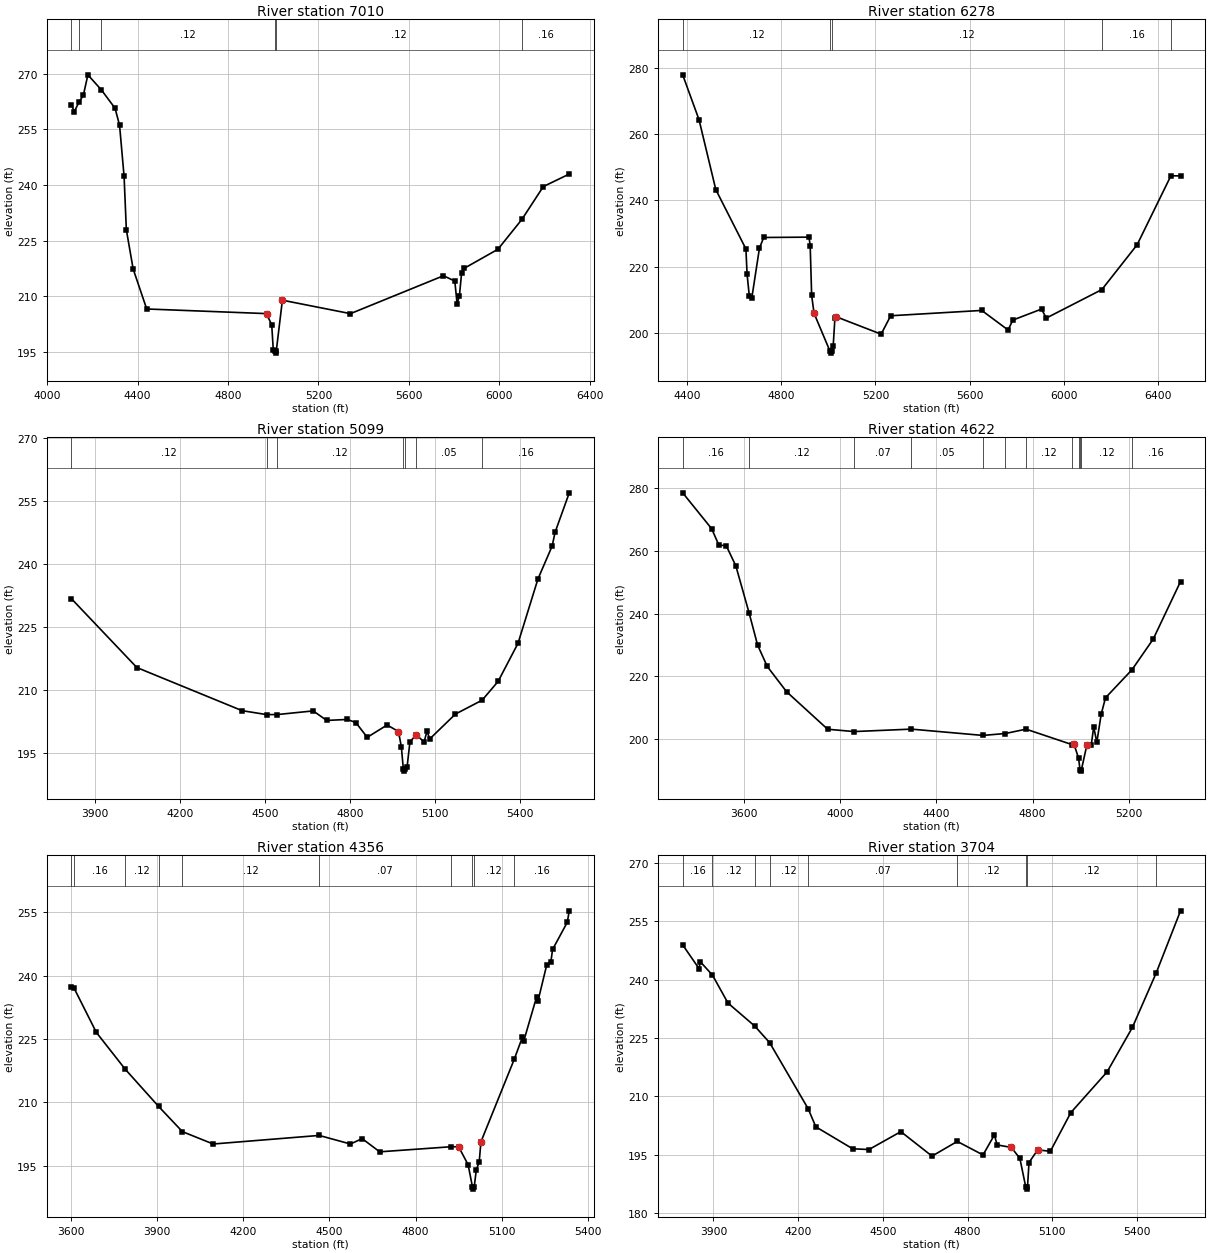
Type RM Length L Ch R = 1 ,7010    ,732,732,732
BEGIN DESCRIPTION:
Mapping XS cc6a5f9d
END DESCRIPTION:
XS GIS Cut Line= 4
      3733861.28     10589177.53      3733878.64     10589733.07
      3733979.33     10589983.07      3733868.22     10591354.64
#Sta/Elev= 30
  4107.5  261.67  4120.2  259.81  4141.5  262.47  4160.2  264.22  4180.2  269.76
  4239.8   265.7  4300.3  260.75  4320.3  256.16  4340.3  242.35  4350.3  227.95
  4380.3  217.37  4440.3  206.54  4970.1  205.29  4993.2  202.23  5000.2  195.35
  5007.2  195.12    5010  194.62  5013.2  195.12  5040.3  208.91  5341.3  205.28
  5752.6  215.51  5802.8  214.08  5812.8  207.98  5822.9  209.94  5832.9  216.32
  5842.9  217.47  5993.4  222.66  6099.5  230.73  6194.1  239.59  6308.9  242.97
#Mann= 6 ,-1 , 0
  4107.5     .05       0  4141.5      .1       0  4239.8     .12       0
  5007.2     .07       0  5013.2     .12       0  6099.5     .16       0
Bank Sta=4970.1,5040.3
XS Rating Curve= 0 ,0
Exp/Cntr=0.3,0.1

Type RM Length L Ch R = 1 ,6278    ,1179,1179,1179
BEGIN DESCRIPTION:
CROOKED CREEK 11.0
END DESCRIPTION:
XS GIS Cut Line= 3
      3733455.03       10589122.      3733694.61     10590399.74
      3733555.73     10591201.79
#Sta/Elev= 30
  4381.4  277.94  4450.8  264.37    4522  243.26  4649.8  225.35  4654.9  217.64
  4664.4  211.02  4674.6  210.37  4707.4  225.62  4725.5   228.8  4917.7   228.9
  4922.8  226.33    4929  211.31  4939.1  205.91  5007.4  194.36  5010.1  193.86
  5013.4  194.36  5020.5  196.01  5027.9  204.59    5033  204.85    5224  199.59
  5264.7  205.15  5651.3  206.76  5763.1  200.85  5783.4  203.85  5905.1  207.17
  5925.4  204.45  6161.4  213.06  6311.1   226.6  6454.6  247.45  6495.4   247.4
#Mann= 5 ,-1 , 0
  4381.4     .12       0  5007.4     .07       0  5013.4     .12       0
  6161.4     .16       0  6454.6     .05       0
Bank Sta=4939.1,5033
XS Rating Curve= 0 ,0
Exp/Cntr=0.3,0.1

Type RM Length L Ch R = 1 ,5099    ,477,477,477
BEGIN DESCRIPTION:
CROOKED CREEK 10.0
END DESCRIPTION:
XS GIS Cut Line= 3
      3733049.61     10589310.23      3733149.61     10590510.19
      3733199.61      10591060.2
#Sta/Elev= 30
  3816.4  231.73  4047.2  215.32  4418.4  205.04    4505   204.1  4542.7  204.11
  4669.3  204.98    4717  202.71  4789.7  202.94  4819.8  202.21    4860  198.68
  4930.2  201.62  4970.3  200.06  4980.4  196.41  4987.4  191.12  4990.2  190.62
  4993.4  191.12  5000.5  191.51  5010.5  197.53  5032.5  199.32  5060.7  197.56
  5070.7  200.13  5080.8  198.31  5171.1  204.22  5265.5  207.54  5321.8  212.02
    5392   221.1  5462.3  236.44  5512.5   244.3  5522.6  247.54  5572.8  256.98
#Mann= 7 ,-1 , 0
  3816.4     .12       0    4505     .05       0  4542.7     .12       0
  4987.4     .07       0  4993.4     .12       0  5032.5     .05       0
  5265.5     .16       0
Bank Sta=4970.3,5032.5
XS Rating Curve= 0 ,0
Exp/Cntr=0.3,0.1

Type RM Length L Ch R = 1 ,4622    ,266,266,266
BEGIN DESCRIPTION:
CROOKED CREEK 9.0
END DESCRIPTION:
XS GIS Cut Line= 3
      3732749.61     10589010.19      3732899.61     10590660.19
      3732799.61     10591060.18
#Sta/Elev= 30
  3345.7  278.53  3466.2  267.06  3496.3  261.79  3526.4   261.7  3566.6  255.21
  3621.5  240.24    3657  229.93  3697.1   223.1  3777.5  215.03  3948.2  203.05
    4058  202.31    4296  203.09  4593.3  201.08  4686.9  201.69  4772.7  203.08
    4965  198.12  4972.4  198.19    4991  193.83    4997  190.18  4999.7  189.68
    5003  190.18  5025.7  198.05  5043.7  198.02    5054   203.8  5066.9  198.86
    5085  207.84    5103  213.09  5213.2  222.06  5301.4  231.85  5414.8   250.2
#Mann= 12 ,-1 , 0
  3345.7     .16       0  3621.5     .12       0    4058     .07       0
    4296     .05       0  4593.3     .12       0  4686.9     .07       0
  4772.7     .12       0    4965     .07       0    4991     .12       0
    4997     .07       0    5003     .12       0  5213.2     .16       0
Bank Sta=4972.4,5025.7
XS Rating Curve= 0 ,0
Exp/Cntr=0.3,0.1

Type RM Length L Ch R = 1 ,4356    ,652,652,652
BEGIN DESCRIPTION:
CROOKED CREEK 8.0
END DESCRIPTION:
XS GIS Cut Line= 3
      3732441.31     10589264.89      3732670.49     10590497.14
      3732571.22     10590966.99
#Sta/Elev= 30
  3601.6  237.32  3611.3  236.95  3688.4  226.53  3788.8  217.83  3904.8  209.04
    3988  203.05  4095.2  200.12  4464.3  202.15  4573.3  200.12    4614   201.4
    4675  198.27  4924.8  199.48  4950.1  199.46    4983  195.21  4998.2  189.94
  5000.9  189.44  5004.2  189.94  5011.4  193.97  5021.6  195.88  5027.6  200.64
  5143.5  220.16  5171.8  225.37  5176.9  224.54  5221.5  234.95  5226.6  234.06
  5256.7  242.51  5271.2  243.29  5277.1  246.17  5328.2   252.6  5335.2  255.32
#Mann= 10 ,-1 , 0
  3601.6     .12       0  3611.3     .16       0  3788.8     .12       0
  3904.8     .16       0    3988     .12       0  4464.3     .07       0
  4924.8     .12       0  4998.2     .07       0  5004.2     .12       0
  5143.5     .16       0
Bank Sta=4950.1,5027.6
XS Rating Curve= 0 ,0
Exp/Cntr=0.3,0.1

Type RM Length L Ch R = 1 ,3704    ,634,634,634
BEGIN DESCRIPTION:
CROOKED CREEK 7.0
END DESCRIPTION:
XS GIS Cut Line= 3
      3732299.61     10589310.22      3732199.61     10590510.19
      3732449.59     10591010.15
#Sta/Elev= 30
  3791.3  248.88    3849  242.82    3854  244.53  3896.7  241.13  3951.8  233.95
  4046.2  228.07  4099.2   223.8  4235.3  206.89  4262.9   202.2  4393.3  196.57
    4451  196.38  4563.9  200.97  4674.3  194.69  4763.7  198.46  4854.9  194.99
  4895.1  200.11  4905.1  197.56  4955.3  196.92  4985.4  194.11  5006.4  186.72
  5009.1  186.22  5012.4  186.72  5017.8  193.04  5048.5   196.3  5093.3  195.92
  5165.9  205.85  5294.5  216.31  5383.9   227.7  5468.3  241.69  5554.4  257.62
#Mann= 9 ,-1 , 0
  3791.3     .16       0  3896.7     .12       0  4046.2     .16       0
  4099.2     .12       0  4235.3     .07       0  4763.7     .12       0
  5006.4     .07       0  5012.4     .12       0  5468.3     .16       0
Bank Sta=4955.3,5048.5
XS Rating Curve= 0 ,0
Exp/Cntr=0.3,0.1

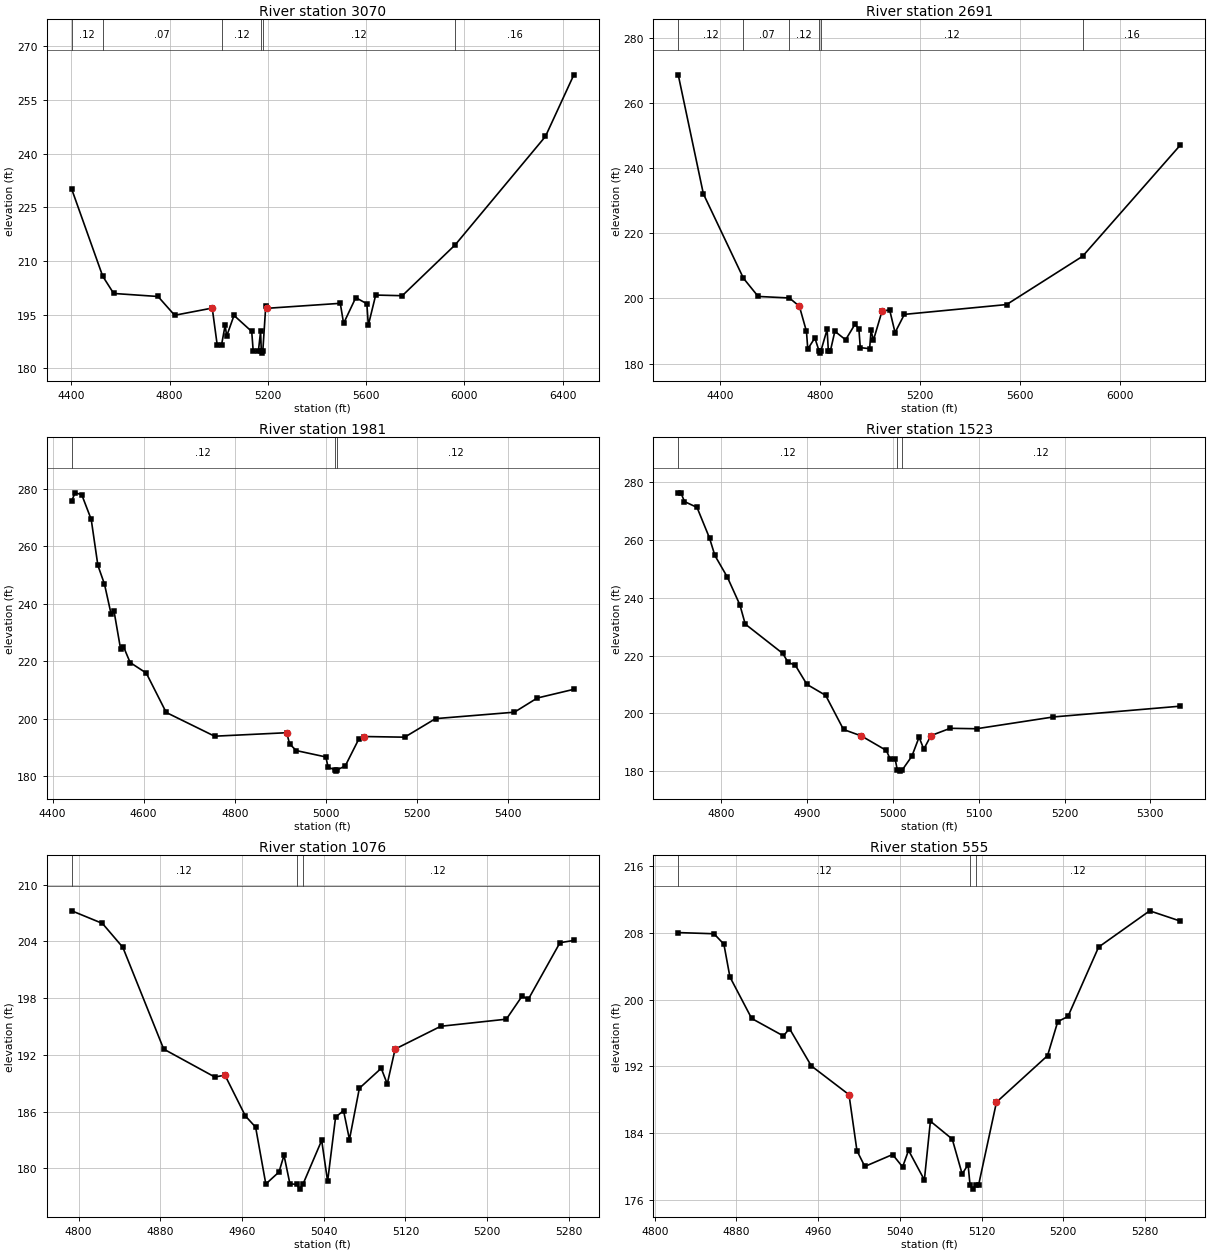
Type RM Length L Ch R = 1 ,3070    ,379,379,379
BEGIN DESCRIPTION:
CROOKED CREEK 6.0
END DESCRIPTION:
XS GIS Cut Line= 3
      3732149.61     10589660.22      3732099.61     10590260.19
      3731299.59     10591460.22
#Sta/Elev= 30
  4401.5  230.04  4527.4  205.75  4572.1  200.91  4752.7  200.06  4820.4  194.81
  4973.4  196.82  4993.5   186.6  5011.6  186.61  5026.1  192.06  5032.1  188.96
  5062.1  194.77  5134.2  190.27  5140.3  184.76  5161.3  184.74  5170.3   190.3
  5173.3  184.72  5176.1  184.22  5179.3  184.72  5191.3  197.36  5197.3  196.76
  5494.8  198.15  5508.3  192.54  5557.9  199.74    5603  198.03    5609  192.03
    5639  200.46  5747.2  200.28    5963  214.53  6330.1  244.82  6445.8  262.06
#Mann= 6 ,-1 , 0
  4401.5     .12       0  4527.4     .07       0  5011.6     .12       0
  5173.3     .07       0  5179.3     .12       0    5963     .16       0
Bank Sta=4973.4,5197.3
XS Rating Curve= 0 ,0
Exp/Cntr=0.3,0.1

Type RM Length L Ch R = 1 ,2691    ,710,710,710
BEGIN DESCRIPTION:
CROOKED CREEK 5.0
END DESCRIPTION:
XS GIS Cut Line= 3
      3732099.61     10589560.18      3731949.61     10590160.19
      3731249.62     10591360.17
#Sta/Elev= 30
  4233.7  268.57  4334.2  232.08  4494.4   206.2  4553.3  200.62  4678.1  200.15
  4718.2   197.6  4746.5  189.88  4751.7  184.49    4780   187.9  4797.6  183.74
  4800.4  183.24  4803.6  183.74    4829  190.51  4834.1  183.82  4841.9  183.85
    4860  189.94    4903  187.33  4940.2  192.04    4956  190.74  4961.7  184.93
    4999   184.6  5004.7   190.2  5014.3  187.22    5049   196.2  5079.2  196.47
  5100.7  189.53  5137.9  195.12  5546.8  198.13  5850.7  212.94  6241.4  247.02
#Mann= 6 ,-1 , 0
  4233.7     .12       0  4494.4     .07       0  4678.1     .12       0
  4797.6     .07       0  4803.6     .12       0  5850.7     .16       0
Bank Sta=4718.2,5049
XS Rating Curve= 0 ,0
Exp/Cntr=0.3,0.1

Type RM Length L Ch R = 1 ,1981    ,458,458,458
BEGIN DESCRIPTION:
CROOKED CREEK 4.0
END DESCRIPTION:
XS GIS Cut Line= 3
      3732099.59     10589510.21      3731699.61     10589810.19
      3731099.56     10589860.19
#Sta/Elev= 30
  4442.2  275.88  4449.5   278.6    4464  277.98  4484.9  269.34  4499.5  253.37
    4514  246.84  4528.6  236.38  4534.9   237.5  4549.5  224.13  4555.7  225.09
  4570.3  219.57  4605.7  215.91  4649.5   202.2  4755.7  193.94    4914  195.15
  4920.3  191.28  4934.9  188.94  4999.9  186.72  5004.9  183.13  5019.4  182.29
  5022.2  181.79  5025.4  182.29  5042.5  183.59  5072.6  193.05  5082.7  193.83
    5173   193.6  5240.7  200.05  5413.8  202.29    5464  207.22  5544.3  210.25
#Mann= 3 ,-1 , 0
  4442.2     .12       0  5019.4     .07       0  5025.4     .12       0
Bank Sta=4914,5082.7
XS Rating Curve= 0 ,0
Exp/Cntr=0.3,0.1

Type RM Length L Ch R = 1 ,1523    ,447,447,447
BEGIN DESCRIPTION:
CROOKED CREEK 3.0
END DESCRIPTION:
XS GIS Cut Line= 3
      3731999.62     10589360.18      3731799.61     10589510.19
      3731499.63     10589660.18
#Sta/Elev= 30
  4749.6  276.39  4752.7  276.39  4756.9  273.36  4771.5  271.34  4786.1  260.71
  4792.3   254.7  4806.9  247.17  4821.5  237.57  4827.7  230.94  4871.5  220.75
  4877.7  217.68  4886.1  216.67  4899.6  210.05  4921.5  206.24  4942.3  194.42
  4963.2  192.18  4992.3  187.15  4996.5  184.28  5002.4  184.28    5005   180.5
  5007.7     180    5011   180.5    5022  185.16  5030.4  191.74  5035.9  187.62
  5044.3  192.31  5066.7  194.83  5097.4  194.68  5186.9  198.76    5335   202.5
#Mann= 3 ,-1 , 0
  4749.6     .12       0    5005     .07       0    5011     .12       0
Bank Sta=4963.2,5044.3
XS Rating Curve= 0 ,0
Exp/Cntr=0.3,0.1

Type RM Length L Ch R = 1 ,1076    ,521,521,521
BEGIN DESCRIPTION:
CROOKED CREEK 2.0
END DESCRIPTION:
XS GIS Cut Line= 3
      3731449.61     10589210.18      3731449.61     10589410.19
      3731299.59     10589660.22
#Sta/Elev= 30
  4793.3  207.23  4823.3   205.9  4843.3  203.37  4883.3  192.62  4933.3  189.67
  4943.3  189.86  4963.3  185.55  4973.3  184.37  4983.3  178.36  4996.2  179.63
  5001.1   181.4  5006.9  178.38  5013.6  178.32  5016.4  177.82  5019.6  178.32
    5038  182.97  5043.8  178.64  5051.6  185.42  5059.4  186.12  5065.2  183.06
  5074.9  188.48  5096.3  190.59  5102.2  188.94  5109.9  192.62  5154.6  195.03
  5218.8  195.78  5234.3  198.23  5240.2  197.86  5271.3  203.86  5284.9   204.1
#Mann= 3 ,-1 , 0
  4793.3     .12       0  5013.6     .07       0  5019.6     .12       0
Bank Sta=4943.3,5109.9
XS Rating Curve= 0 ,0
Exp/Cntr=0.3,0.1

Type RM Length L Ch R = 1 ,555     ,0,0,0
BEGIN DESCRIPTION:
CROOKED CREEK 1.0
END DESCRIPTION:
XS GIS Cut Line= 3
      3731399.63     10589210.17      3731149.61     10589360.19
      3730949.59     10589360.19
#Sta/Elev= 30
    4823  208.03    4858  207.89  4867.7  206.64  4873.6  202.71  4894.9  197.73
    4926  195.63  4931.9  196.52  4953.3  192.04  4990.2  188.59    4998  181.86
  5005.7  179.98  5032.9  181.41  5042.7  179.92  5048.5  181.91    5064  178.36
  5069.9  185.41  5091.3  183.26    5101  179.07  5106.8   180.2  5108.7  177.76
  5111.4  177.26  5114.7  177.76  5117.1  177.76  5134.6  187.69  5184.6  193.27
  5194.6  197.35  5204.6  197.97  5234.6  206.29  5284.6  210.64  5314.6  209.41
#Mann= 3 ,-1 , 0
    4823     .12       0  5108.7     .07       0  5114.7     .12       0
Bank Sta=4990.2,5134.6
XS Rating Curve= 0 ,0
Exp/Cntr=0.3,0.1

Chan Stop Cuts=-1
Use User Specified Reach Order=0
Composite Channel Slope=5