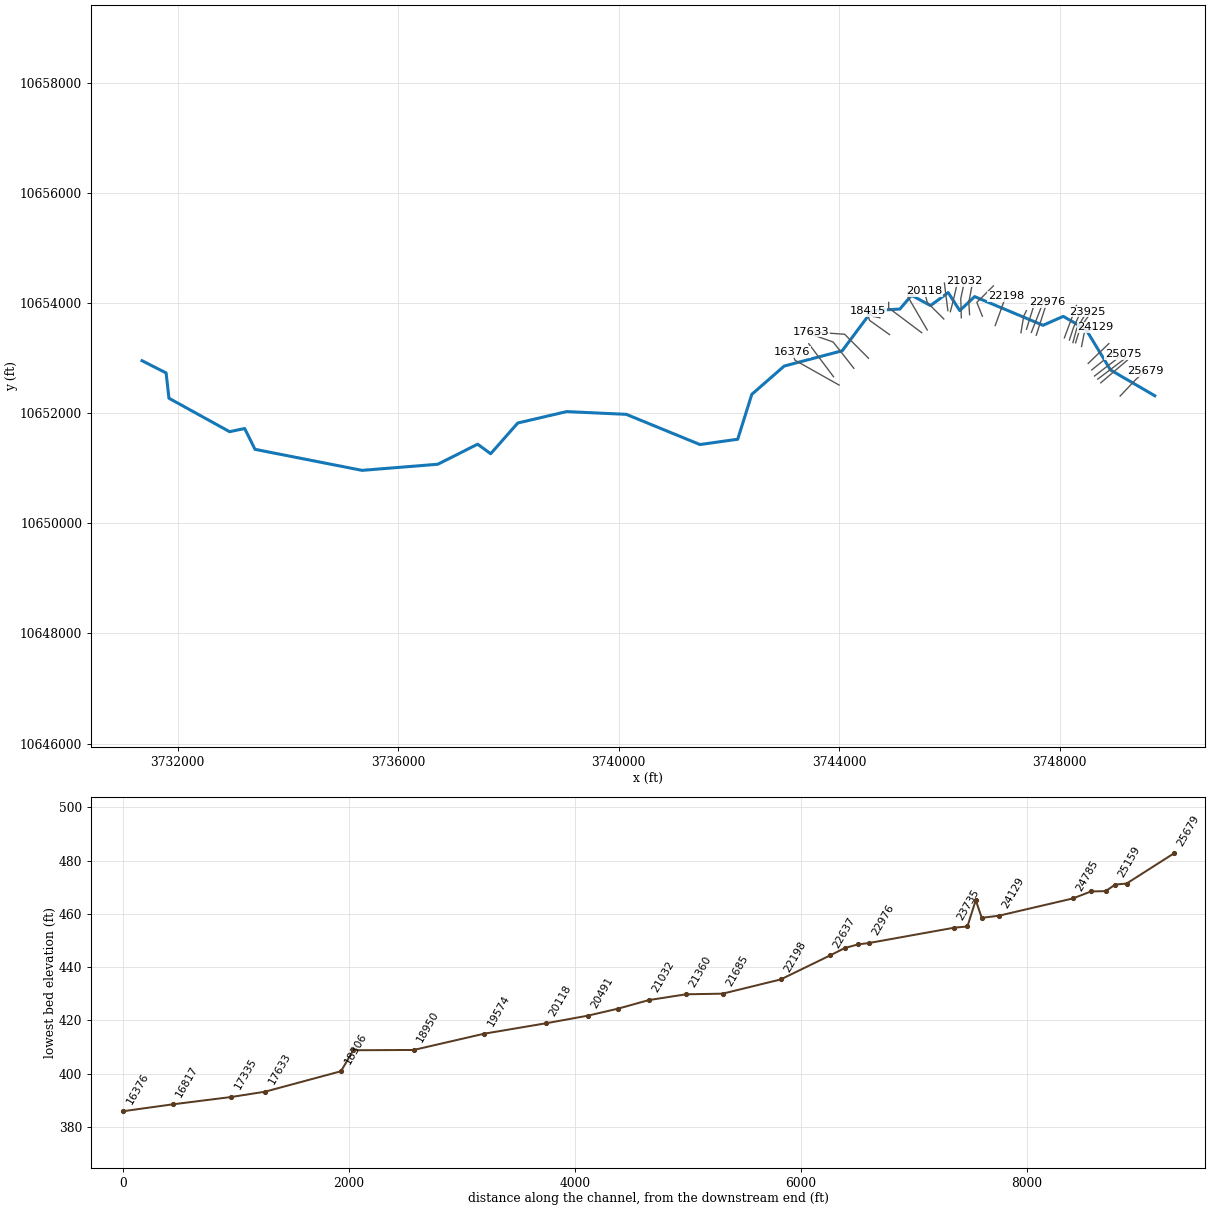
--- FIVEMILE BRANCH.prj (project) ---

Proj Title=FIVEMILE BRANCH Base Level Engineering
Current Plan=p01
Default Exp/Contr=0.3,0.1
English Units
Geom File=g01
Flow File=f01
Plan File=p01
Y Axis Title=Elevation
X Axis Title(PF)=Main Channel Distance
X Axis Title(XS)=Station
BEGIN DESCRIPTION:
FIVEMILE BRANCH
END DESCRIPTION:
DSS File=dss
DSS Export Rating Curves= 0
DSS Export Rating Curve Sorted= 0
DSS Export Volume Flow Curves= 0
DXF OffsetX= 0
DXF OffsetY= 0
DXF ScaleX= 1
DXF ScaleY= 10

--- FIVEMILE BRANCH.p01 (plan) ---

Plan Title=Multiple Run
Program Version=4.10
Short Identifier=Multiple Run
Geom File=g01
Flow File=f01
Subcritical Flow
K Sum by GR= 0
Std Step Tol= 0.01
Critical Tol= 0.01
Num of Std Step Trials= 20
Max Error Tol= 0.3
Flow Tol Ratio= 0.001
Split Flow NTrial= 30
Split Flow Tol= 0.02
Split Flow Ratio= 0.02
Log Output Level= 0
Friction Slope Method= 1
Unsteady Friction Slope Method= 2
Unsteady Bridges Friction Slope Method= 1
Parabolic Critical Depth
Global Vel Dist= 1 , 1 , 1
Global Log Level= 0
CheckData=True
Encroach Param=-1 ,0,0, 0
BEGIN DESCRIPTION:
Multiple Run
END DESCRIPTION:
Computation Interval=1HOUR
Output Interval=1HOUR
Run HTab= 0
Run UNet= 0
Run PostProcess= 0
Run WQNet= 0
UNET Theta= 1
UNET Theta Warmup= 1
UNET ZTol= 0.02
UNET ZSATol= 0.05
UNET MxIter= 20
UNET MaxInSteps= 0
UNET DtIC= 0
UNET DtMin= 0
UNET MaxCRTS= 20
UNET WFStab= 2
UNET SFStab= 1
UNET WFX= 1
UNET SFX= 1
UNET DSS MLevel= 4
UNET DZMax Abort= 100
UNET Convert EG Bridges= 0
UNET Use Existing IB Tables=-1
UNET Froude Reduction=False
UNET Froude Limit= 1
UNET Froude Power= 10
UNET Time Slicing=0,0, 5
UNET Junction Losses=0
Instantaneous Interval=1HOUR
DSS File=dss
Write IC File= 0
Write IC File at Sim End=0
Echo Input=False
Echo Parameters=False
Echo Output=False
Write Detailed= 0
WQ AD Non Conservative
WQ ULTIMATE=-1
WQ Max Comp Step=1HOUR
WQ Output Interval=15MIN
WQ Output Selected Increments= 0
WQ Output face flow=0
WQ Output face velocity=0
WQ Output face area=0
WQ Output face dispersion=0
WQ Output cell volume=0
WQ Output cell surface area=0
WQ Output cell continuity=0
WQ Output cumulative cell continuity=0
WQ Output face conc=0
WQ Output face dconc_dx=0
WQ Output face courant=0
WQ Output face peclet=0
WQ Output face adv mass=0
WQ Output face disp mass=0
WQ Output cell mass=0
WQ Output cell source sink temp=0
WQ Output cell source sink nsm=0
WQ Output MaxMinRange=-1
WQ Daily Max Min Mean=-1
WQ Daily Range=0
WQ Daily Time=0
WQ Create Restart=0
WQ Fixed Restart=0
WQ System Summary=0
WQ Use Fixed Temperature=0
Sorting and Armoring Iterations= 10
XS Update Threshold= 0.02
Hydraulics Update Threshold= 0.02
Energy Slope Method= 1
Volume Change Method= 0
XS Weighting Method= 0
Number of US Weighted Cross Sections= 1
Number of DS Weighted Cross Sections= 1
Upstream XS Weight=0.25
Main XS Weight=0.5
Downstream XS Weight=0.25
Number of DS XS's Weighted with US Boundary= 1
Upstream Boundary Weight= 1
Weight of XSs Associated with US Boundary= 0
Number of US XS's Weighted with DS Boundary= 1
Downstream Boundary Weight= 0.5
Weight of XSs Associated with DS Boundary= 0.5
Sediment Output Level= 4
Mass or Volume Output= 0
Output Increment Type= 1
Profile and TS Output Increment= 10
XS Output Flag= 0
XS Output Increment= 10
Disregard all LS=0
Disregard all Conn=0
Disregard all Breaches=0
Disregard all Pumps=0

--- FIVEMILE BRANCH.f01 (steady flow) ---

Flow Title=Multiple
Program Version=4.10
Number of Profiles= 7
Profile Names=10-year,25-year,50-year,1pct_min,100-year,1pct_plu,500-year
River Rch & RM=FIVEMILE BRANCH,Reach-1         ,25679
     656     903    1111    1006    1361    1840    2048
River Rch & RM=FIVEMILE BRANCH,Reach-1         ,17633
    1212    1725    2172    2009    2717    3674    4266
River Rch & RM=FIVEMILE BRANCH,Reach-1         ,16817
    1212    1725    2172    2009    2717    3674    4266
River Rch & RM=FIVEMILE BRANCH,Reach-1         ,13013
    1700    2449    3105    2888    3905    5281    6204
River Rch & RM=FIVEMILE BRANCH,Reach-1         ,4896
    1902    2746    3488    3248    4392    5940    6994
Boundary for River Rch & Prof#=FIVEMILE BRANCH,Reach-1         , 1
Up Type= 0
Dn Type= 3
Dn Slope=0.002
Boundary for River Rch & Prof#=FIVEMILE BRANCH,Reach-1         , 2
Up Type= 0
Dn Type= 3
Dn Slope=0.002
Boundary for River Rch & Prof#=FIVEMILE BRANCH,Reach-1         , 3
Up Type= 0
Dn Type= 3
Dn Slope=0.002
Boundary for River Rch & Prof#=FIVEMILE BRANCH,Reach-1         , 4
Up Type= 0
Dn Type= 3
Dn Slope=0.002
Boundary for River Rch & Prof#=FIVEMILE BRANCH,Reach-1         , 5
Up Type= 0
Dn Type= 3
Dn Slope=0.002
Boundary for River Rch & Prof#=FIVEMILE BRANCH,Reach-1         , 6
Up Type= 0
Dn Type= 3
Dn Slope=0.002
Boundary for River Rch & Prof#=FIVEMILE BRANCH,Reach-1         , 7
Up Type= 0
Dn Type= 3
Dn Slope=0.002
DSS Import GetInterval= 0
DSS Import GetPeak= 0
DSS Import FillOption= 0

--- FIVEMILE BRANCH.g01 (geometry) ---

Geom Title=Existing Conditions
Program Version=4.10

River Reach=FIVEMILE BRANCH ,Reach-1
Reach XY= 30
      3749728.28     10652316.07      3748924.75       10652784.
       3748479.5       10653521.      3748067.75       10653757.
      3747700.75       10653595.      3746459.25       10654116.
      3746189.25       10653862.      3745979.25       10654189.
      3745658.75       10653953.        3745315.       10654140.
      3745103.57     10653890.03      3744599.49     10653861.73
      3744057.25       10653133.      3743003.95     10652855.05
        3742416.       10652341.      3742160.25       10651526.
        3741475.       10651430.       3740138.5       10651978.
       3739057.5       10652028.      3738169.75       10651821.
      3737678.25       10651263.      3737440.75       10651436.
      3736718.25       10651072.      3735344.25       10650961.
        3733401.       10651343.       3733214.5       10651721.
      3732940.75       10651663.      3731839.75       10652271.
       3731788.5       10652730.        3731352.       10652952.

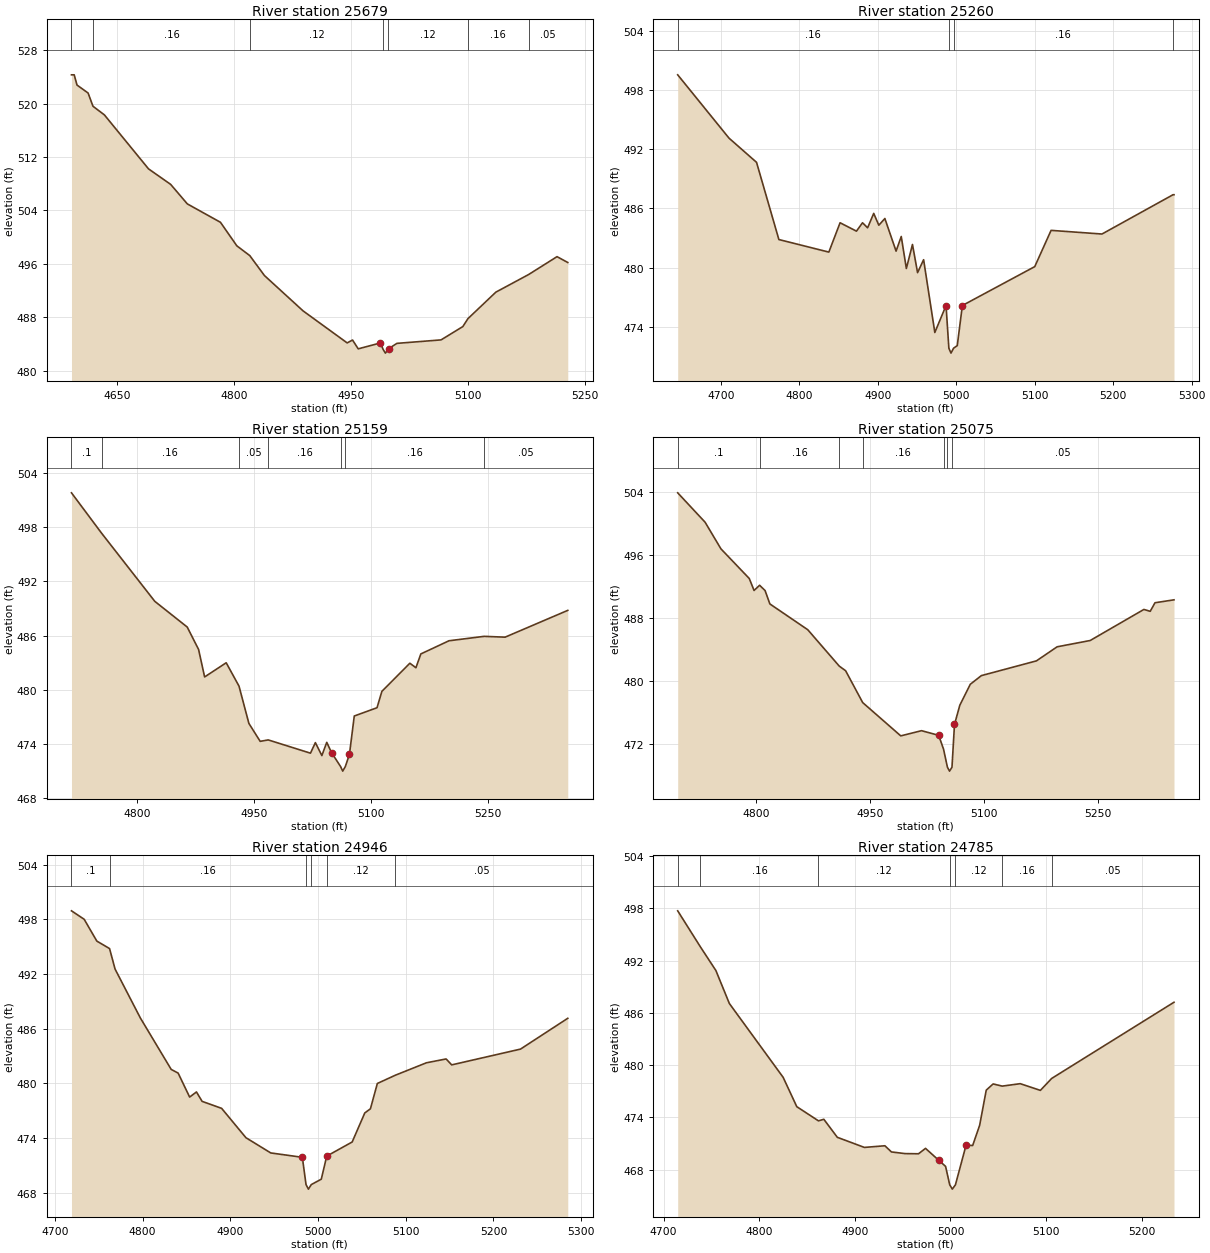
Type RM Length L Ch R = 1 ,25679   ,419,419,419
BEGIN DESCRIPTION:
FIVEMILE BRANCH 52.0
END DESCRIPTION:
XS GIS Cut Line= 3
      3749099.59     10652310.16      3749380.41     10652607.52
      3749549.61     10652760.19
#Sta/Elev= 30
    4591  524.29  4594.5  524.29  4598.1  522.76  4612.3  521.57  4618.6  519.59
  4633.3  518.29  4689.9  510.22  4718.3   507.9  4739.7  504.98  4782.2  502.23
  4803.2  498.71  4819.8  497.25  4838.6  494.27  4888.2  488.98  4944.8  484.19
  4951.7  484.62    4959   483.3  4987.3  484.18  4991.2  483.16  4993.9  482.66
  4997.2  483.16  4998.4  483.35  5008.6  484.12  5065.3  484.64  5093.2  486.63
  5099.8  487.82  5135.6  491.78  5177.7  494.42  5214.1  497.09  5227.9  496.22
#Mann= 7 ,-1 , 0
    4591     .12       0  4618.6     .16       0  4819.8     .12       0
  4991.2     .07       0  4997.2     .12       0  5099.8     .16       0
  5177.7     .05       0
Bank Sta=4987.3,4998.4
XS Rating Curve= 0 ,0
Exp/Cntr=0.3,0.1

Type RM Length L Ch R = 1 ,25260   ,101,101,101
BEGIN DESCRIPTION:
Mapping XS 11843953
END DESCRIPTION:
XS GIS Cut Line= 2
      3748747.63     10652550.44      3749229.39     10652960.59
#Sta/Elev= 30
  4644.8  499.53  4710.2  493.12  4745.3  490.67  4773.8  482.85  4837.5  481.58
  4851.8  484.55  4872.7   483.7  4880.4  484.55  4886.9  484.04  4894.7   485.5
  4901.2   484.3  4908.9  484.98  4923.2  481.68  4929.8  483.16  4936.3  479.92
  4944.1  482.35  4950.6   479.5  4958.3  480.81  4972.6  473.44  4986.9  476.17
  4990.5  471.85  4993.2  471.35  4996.5  471.85  5001.2  472.11  5007.7  476.17
    5100  480.11  5120.8  483.78  5185.7  483.41  5276.3  487.39  5277.5  487.39
#Mann= 4 ,-1 , 0
  4644.8     .16       0  4990.5     .07       0  4996.5     .16       0
  5276.3     .05       0
Bank Sta=4986.9,5007.7
XS Rating Curve= 0 ,0
Exp/Cntr=0.3,0.1

Type RM Length L Ch R = 1 ,25159   ,84,84,84
BEGIN DESCRIPTION:
Mapping XS 1084c077
END DESCRIPTION:
XS GIS Cut Line= 2
      3748693.37     10652617.71      3749201.16     10653001.81
#Sta/Elev= 30
    4716  501.82  4754.6  497.35  4822.9  489.79  4864.5  486.94  4879.1  484.45
  4886.8  481.41  4914.5  482.98  4930.9   480.4  4943.6  476.26  4958.1  474.27
  4968.4  474.43  5022.6  472.96  5028.9  474.13  5037.2  472.69  5043.5  474.16
  5049.8     473  5061.3  471.47    5064  470.97  5067.3  471.47  5072.6  472.83
  5078.8  477.08    5108     478  5114.2  479.81  5150.1  482.93  5157.9  482.43
  5164.2  483.96  5200.3  485.42  5245.4  485.91  5272.3  485.82  5352.7  488.79
#Mann= 7 ,-1 , 0
    4716      .1       0  4754.6     .16       0  4930.9     .05       0
  4968.4     .16       0  5061.3     .07       0  5067.3     .16       0
  5245.4     .05       0
Bank Sta=5049.8,5072.6
XS Rating Curve= 0 ,0
Exp/Cntr=0.3,0.1

Type RM Length L Ch R = 1 ,25075   ,129,129,129
BEGIN DESCRIPTION:
FIVEMILE BRANCH 51.0
END DESCRIPTION:
XS GIS Cut Line= 2
      3748634.78     10652674.14      3749153.41     10653071.25
#Sta/Elev= 30
  4697.1  503.87  4733.2  500.13    4754  496.75  4791.3  492.98  4797.6  491.46
  4804.9  492.12  4812.1  491.45  4818.4  489.75  4868.3  486.47  4909.8  481.84
  4918.1  481.26  4940.6  477.21  4990.7  472.98    5018  473.64  5040.6  473.05
    5047  471.29  5052.1     469  5054.9   468.5  5058.1     469  5061.4  474.43
  5068.4  476.87  5082.2  479.54  5096.8  480.64  5169.2  482.51  5196.5   484.3
    5240   485.1  5310.7  489.05    5319  488.81  5325.3   489.9  5350.3  490.27
#Mann= 7 ,-1 , 0
  4697.1      .1       0  4804.9     .16       0  4909.8     .05       0
  4940.6     .16       0    5047     .05       0  5052.1     .07       0
  5058.1     .05       0
Bank Sta=5040.6,5061.4
XS Rating Curve= 0 ,0
Exp/Cntr=0.3,0.1

Type RM Length L Ch R = 1 ,24946   ,161,161,161
BEGIN DESCRIPTION:
Mapping XS e7877361
END DESCRIPTION:
XS GIS Cut Line= 2
      3748584.86     10652784.81      3749024.97     10653140.37
#Sta/Elev= 30
    4719  498.94  4733.5  498.01  4747.9  495.62  4762.4   494.8  4768.7  492.55
  4797.5  487.19  4832.7  481.54  4840.6  481.14  4853.7  478.51  4861.5  479.07
  4867.9  478.04  4890.2  477.27  4917.9  474.05  4946.2  472.38  4982.2   471.9
  4986.4  468.91  4989.1  468.41  4992.4  468.91  5003.8   469.5    5010  472.03
    5039  473.58  5053.4  476.77  5059.8  477.22  5067.7     480  5088.1   480.9
  5123.7  482.27  5146.1  482.69  5152.5  482.04  5230.9  483.77  5284.8  487.15
#Mann= 6 ,-1 , 0
    4719      .1       0  4762.4     .16       0  4986.4     .07       0
  4992.4     .16       0    5010     .12       0  5088.1     .05       0
Bank Sta=4982.2,5010
XS Rating Curve= 0 ,0
Exp/Cntr=0.3,0.1

Type RM Length L Ch R = 1 ,24785   ,656,656,656
BEGIN DESCRIPTION:
FIVEMILE BRANCH 50.0
END DESCRIPTION:
XS GIS Cut Line= 2
      3748520.28     10652903.33      3748894.92     10653262.36
#Sta/Elev= 30
  4714.8  497.73  4738.6  493.58  4754.7  490.88  4768.8  487.09  4825.1   478.6
  4839.3  475.24    4862  473.61  4867.6  473.79  4881.7  471.72    4910  470.56
  4931.4  470.75  4938.3  470.04  4952.5  469.85  4966.6  469.83  4973.9  470.45
    4988  469.06  4994.9  468.38  4999.2  466.27  5001.9  465.77  5005.2  466.27
  5016.3  470.82  5023.2  470.78  5030.5   473.1  5037.4  477.14  5044.6  477.85
  5054.1   477.6  5072.9  477.88    5094  477.11  5105.8  478.48  5233.7  487.23
#Mann= 7 ,-1 , 0
  4714.8     .12       0  4738.6     .16       0    4862     .12       0
  4999.2     .07       0  5005.2     .12       0  5054.1     .16       0
  5105.8     .05       0
Bank Sta=4988,5016.3
XS Rating Curve= 0 ,0
Exp/Cntr=0.3,0.1

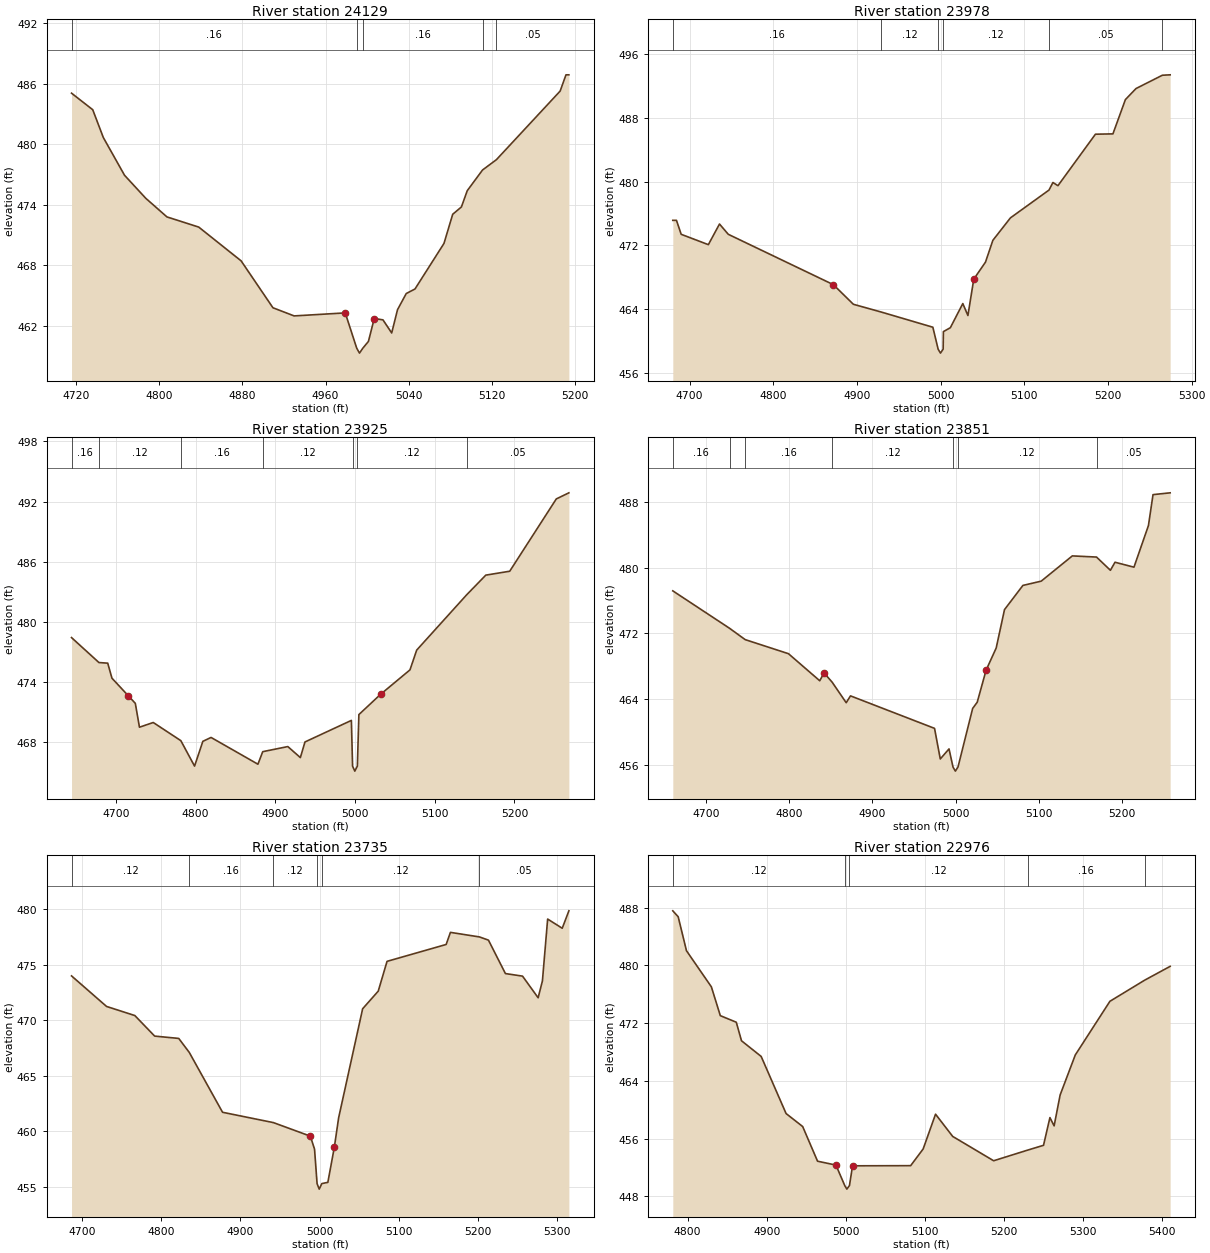
Type RM Length L Ch R = 1 ,24129   ,151,151,151
BEGIN DESCRIPTION:
FIVEMILE BRANCH 49.0
END DESCRIPTION:
XS GIS Cut Line= 3
       3748399.6     10653210.14      3748449.61     10653460.19
       3748649.6     10653560.19
#Sta/Elev= 30
  4715.5  485.07  4735.9  483.43  4746.1  480.67  4766.5  476.93  4786.9  474.65
  4807.3   472.8  4837.9  471.79  4878.7  468.44  4909.3  463.79  4929.7  462.98
  4978.9  463.28  4989.9  459.79  4992.6  459.29  4995.9  459.79  5001.2  460.45
  5006.8  462.72  5015.2  462.59  5023.6  461.29  5029.2   463.6  5037.6   465.2
    5046  465.65  5073.9  470.17  5082.3  473.06  5090.7  473.79  5096.3   475.4
    5111  477.45  5124.4  478.48  5185.7  485.28  5191.3  486.89  5194.1  486.89
#Mann= 5 ,-1 , 0
  4715.5     .16       0  4989.9     .07       0  4995.9     .16       0
    5111     .12       0  5124.4     .05       0
Bank Sta=4978.9,5006.8
XS Rating Curve= 0 ,0
Exp/Cntr=0.3,0.1

Type RM Length L Ch R = 1 ,23978   ,53,53,53
BEGIN DESCRIPTION:
Mapping XS 68fa5d23
END DESCRIPTION:
XS GIS Cut Line= 3
      3748291.27     10653276.88      3748374.62     10653545.16
       3748551.7     10653803.83
#Sta/Elev= 30
  4679.9  475.15  4684.3  475.15  4689.9   473.4  4722.4   472.1  4735.7  474.69
  4746.2   473.4  4871.8  467.08  4895.7  464.62  4929.2  463.64  4990.7  461.74
    4997  458.99  4999.8  458.49    5003  458.99  5003.3  461.19  5011.6  461.68
  5026.5  464.71  5032.6  463.21  5039.6  467.77  5053.6  469.91  5062.4  472.64
  5083.4  475.46  5129.5  478.95  5134.2   479.9  5140.2   479.5    5185  485.96
  5205.9     486  5220.8   490.3  5233.5  491.69    5265  493.36  5274.3  493.41
#Mann= 6 ,-1 , 0
  4679.9     .16       0  4929.2     .12       0    4997     .07       0
    5003     .12       0  5129.5     .05       0    5265     .16       0
Bank Sta=4871.8,5039.6
XS Rating Curve= 0 ,0
Exp/Cntr=0.3,0.1

Type RM Length L Ch R = 1 ,23925   ,74,74,74
BEGIN DESCRIPTION:
Mapping XS 5f36bf1d
END DESCRIPTION:
XS GIS Cut Line= 5
      3748242.69      10653281.3      3748311.25       10653533.
      3748335.56     10653574.67      3748367.68     10653625.89
      3748498.73     10653843.74
#Sta/Elev= 30
  4644.5  478.43  4678.9  475.94  4689.9  475.88  4695.2  474.38  4715.9  472.61
  4724.5  471.87  4729.7  469.49    4747  469.96  4781.6  468.15  4798.8  465.61
  4809.2  468.08  4819.5  468.47  4878.3   465.8  4884.3  467.05  4915.8  467.56
  4931.5  466.46  4937.3  468.02  4995.5  470.17    4997  465.61  4999.8  465.11
    5003  465.61  5004.9  470.75  5032.1  472.77    5069  475.21  5077.4  477.18
    5140  482.69  5164.1  484.66  5194.1  485.05  5252.5  492.26  5268.3  492.87
#Mann= 7 ,-1 , 0
  4644.5     .16       0  4678.9     .12       0  4781.6     .16       0
  4884.3     .12       0    4997     .07       0    5003     .12       0
    5140     .05       0
Bank Sta=4715.9,5032.1
XS Rating Curve= 0 ,0
Exp/Cntr=0.3,0.1

Type RM Length L Ch R = 1 ,23851   ,116,116,116
BEGIN DESCRIPTION:
Mapping XS 0878e95a
END DESCRIPTION:
XS GIS Cut Line= 3
       3748179.3     10653328.12       3748255.7     10653560.78
       3748404.8     10653880.66
#Sta/Elev= 30
  4660.2  477.17  4728.4  472.62  4747.2  471.24  4799.2  469.53  4836.8  466.24
    4842  467.19  4851.7  466.07  4868.6  463.57  4873.8   464.4  4974.8  460.45
  4981.7  456.73  4992.2  457.95    4997  455.75  4999.8  455.25    5003  455.75
  5020.6  462.87  5026.1  463.63  5036.8  467.53  5048.9  470.22  5058.9  474.89
    5081  477.83    5103  478.35  5140.4  481.42  5169.5  481.28  5186.2  479.67
  5191.7  480.65  5214.5  480.05  5231.9  485.11  5237.4  488.87    5258  489.09
#Mann= 7 ,-1 , 0
  4660.2     .16       0  4728.4     .12       0  4747.2     .16       0
  4851.7     .12       0    4997     .07       0    5003     .12       0
  5169.5     .05       0
Bank Sta=4842,5036.8
XS Rating Curve= 0 ,0
Exp/Cntr=0.3,0.1

Type RM Length L Ch R = 1 ,23735   ,759,759,759
BEGIN DESCRIPTION:
FIVEMILE BRANCH 48.0
END DESCRIPTION:
XS GIS Cut Line= 2
      3748088.02     10653366.93      3748306.71     10653955.31
#Sta/Elev= 30
  4686.9  474.01  4731.1  471.26  4766.8  470.44  4791.8  468.59  4822.2  468.38
  4835.5  467.12  4877.5  461.73  4941.7   460.8  4988.3  459.58  4993.6  458.41
  4996.8  455.31  4999.5  454.81  5002.8  455.31  5010.4  455.42  5018.6  458.59
    5024  461.23  5054.3  471.05    5074  472.64  5085.1  475.32  5159.7  476.84
  5165.1  477.93  5201.7  477.52  5213.1  477.23  5234.5  474.22  5256.1  473.99
  5275.8  472.04  5281.2  473.56  5287.8  479.13  5306.2   478.3  5314.6  479.87
#Mann= 6 ,-1 , 0
  4686.9     .12       0  4835.5     .16       0  4941.7     .12       0
  4996.8     .07       0  5002.8     .12       0  5201.7     .05       0
Bank Sta=4988.3,5018.6
XS Rating Curve= 0 ,0
Exp/Cntr=0.3,0.1

Type RM Length L Ch R = 1 ,22976   ,89,89,89
BEGIN DESCRIPTION:
FIVEMILE BRANCH 47.0
END DESCRIPTION:
XS GIS Cut Line= 2
      3747577.59     10653413.75       3747770.3     10654012.71
#Sta/Elev= 30
  4781.3  487.57  4788.1  486.75  4798.6  482.04  4830.1  477.04  4841.4  473.05
  4861.6  472.14  4868.2  469.57  4893.1   467.4  4924.6  459.49  4945.6  457.69
  4964.4  452.89  4987.7  452.35  4998.8  449.52  5001.5  449.02  5004.8  449.52
  5008.7  452.25  5082.2  452.27    5098  454.58  5113.7   459.4  5135.4  456.32
  5187.2  452.95  5230.7  454.44  5250.3  455.09  5258.4  458.93  5263.7  457.78
  5271.3  462.06  5290.5  467.61  5334.3  475.04  5378.2  477.96  5410.5  479.88
#Mann= 5 ,-1 , 0
  4781.3     .12       0  4998.8     .07       0  5004.8     .12       0
  5230.7     .16       0  5378.2     .05       0
Bank Sta=4987.7,5008.7
XS Rating Curve= 0 ,0
Exp/Cntr=0.3,0.1

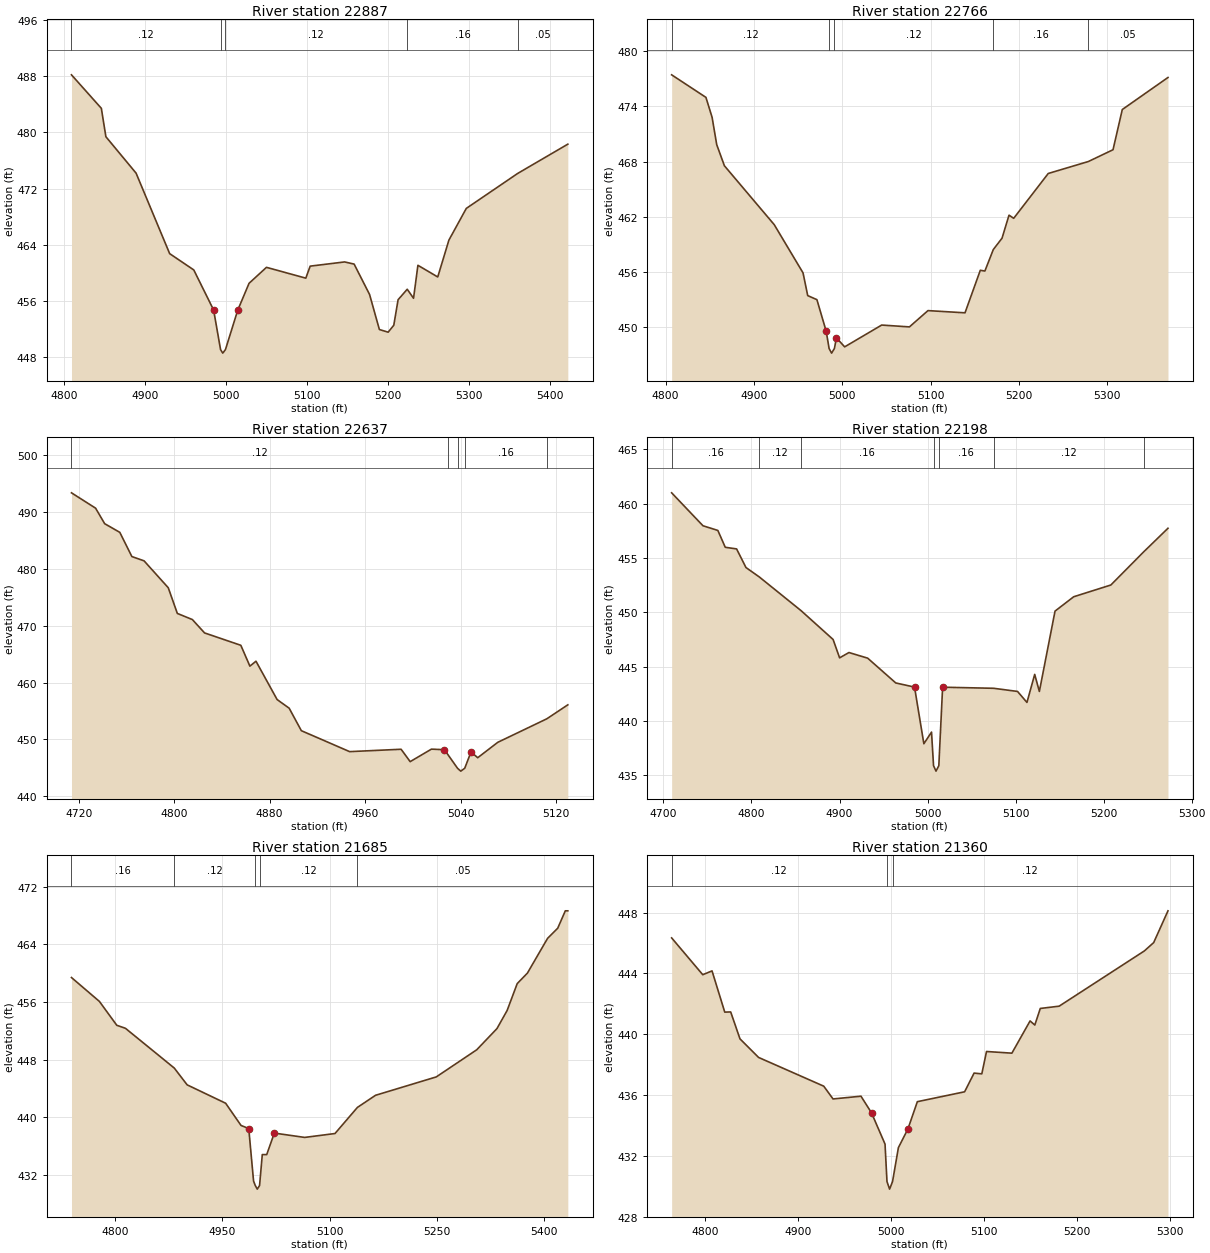
Type RM Length L Ch R = 1 ,22887   ,121,121,121
BEGIN DESCRIPTION:
Mapping XS f2acab58
END DESCRIPTION:
XS GIS Cut Line= 2
      3747489.05     10653465.86      3747712.31     10654036.98
#Sta/Elev= 30
  4808.7  488.19  4845.6  483.42  4851.2  479.38  4888.5   474.2    4930  462.74
  4959.8  460.42  4984.3  454.72  4992.9  449.08  4995.6  448.58  4998.9  449.08
  5014.1  454.69  5028.1  458.52  5049.6  460.79  5098.2  459.25  5103.6  460.96
  5146.2  461.56  5157.9  461.25    5177  456.92  5189.1  451.94  5199.9  451.56
  5206.9  452.55  5212.2  456.18  5223.5  457.67  5231.3  456.39  5236.7  461.08
  5261.2  459.42    5275  464.67  5296.5  469.18  5359.9  474.15  5421.9  478.32
#Mann= 5 ,-1 , 0
  4808.7     .12       0  4992.9     .07       0  4998.9     .12       0
  5223.5     .16       0  5359.9     .05       0
Bank Sta=4984.3,5014.1
XS Rating Curve= 0 ,0
Exp/Cntr=0.3,0.1

Type RM Length L Ch R = 1 ,22766   ,129,129,129
BEGIN DESCRIPTION:
Mapping XS 15e1dedd
END DESCRIPTION:
XS GIS Cut Line= 2
      3747400.51     10653523.16      3747567.17     10654059.57
#Sta/Elev= 30
  4806.9  477.42  4845.7  474.97  4852.7   472.8  4857.9  469.84  4866.6  467.54
    4923  461.14  4955.6   455.9  4960.9  453.43  4971.3  452.99  4981.8  449.56
  4985.1  447.68  4987.9  447.18  4991.1  447.68  4993.4  448.84  5002.7  447.86
  5044.6  450.23    5076  450.03    5097   451.8  5138.9  451.56  5156.2  456.18
  5161.4   456.1  5170.9  458.43  5180.8  459.67  5188.7  462.17    5194  461.83
  5233.1   466.7  5278.5     468  5306.4  469.28  5316.9  473.65  5368.6  477.13
#Mann= 5 ,-1 , 0
  4806.9     .12       0  4985.1     .07       0  4991.1     .12       0
  5170.9     .16       0  5278.5     .05       0
Bank Sta=4981.8,4993.4
XS Rating Curve= 0 ,0
Exp/Cntr=0.3,0.1

Type RM Length L Ch R = 1 ,22637   ,439,439,439
BEGIN DESCRIPTION:
FIVEMILE BRANCH 46.0
END DESCRIPTION:
XS GIS Cut Line= 3
      3747299.62     10653460.24      3747349.61     10653760.19
      3747399.61     10653860.19
#Sta/Elev= 30
    4714  493.42  4734.2  490.72  4741.8  487.99  4754.5  486.46  4764.6   482.2
  4774.8  481.45  4795.1  476.71  4802.7  472.19  4815.3  471.11  4825.5  468.76
  4855.9  466.58  4863.5  462.91  4868.6  463.78  4886.3  457.03  4896.4  455.51
  4906.6  451.55  4947.1  447.86  4990.2  448.28  4997.8   446.1  5015.6   448.3
  5026.5   448.2  5029.3  447.37  5037.5  444.93  5040.2  444.43  5043.5  444.93
  5048.8  447.81  5054.4  446.79  5071.2   449.5  5112.3  453.64  5129.9   456.1
#Mann= 5 ,-1 , 0
    4714     .12       0  5029.3     .16       0  5037.5     .07       0
  5043.5     .16       0  5112.3     .12       0
Bank Sta=5026.5,5048.8
XS Rating Curve= 0 ,0
Exp/Cntr=0.3,0.1

Type RM Length L Ch R = 1 ,22198   ,513,513,513
BEGIN DESCRIPTION:
FIVEMILE BRANCH 45.0
END DESCRIPTION:
XS GIS Cut Line= 2
      3746832.79     10653590.82      3747025.05     10654120.83
#Sta/Elev= 30
  4709.3  460.99  4744.9  457.96  4761.8  457.53  4770.2  455.98  4783.1  455.83
  4793.7  454.12  4808.9  453.25  4856.2  450.16  4892.7   447.5  4900.1  445.81
  4910.7   446.3    4932  445.78  4963.9   443.5  4985.2  443.12  4995.8  437.91
  5004.5  438.98  5006.8  435.89  5009.6  435.39  5012.8  435.89  5017.1  443.11
  5075.1  443.01  5102.2  442.72  5112.9  441.71  5121.7  444.29    5127  442.72
  5144.8  450.11    5166  451.43  5208.2  452.51  5245.5  455.56  5273.1  457.73
#Mann= 7 ,-1 , 0
  4709.3     .16       0  4808.9     .12       0  4856.2     .16       0
  5006.8     .07       0  5012.8     .16       0  5075.1     .12       0
  5245.5     .05       0
Bank Sta=4985.2,5017.1
XS Rating Curve= 0 ,0
Exp/Cntr=0.3,0.1

Type RM Length L Ch R = 1 ,21685   ,325,325,325
BEGIN DESCRIPTION:
FIVEMILE BRANCH 44.0
END DESCRIPTION:
XS GIS Cut Line= 3
      3746599.61     10653760.19      3746499.61     10654010.19
       3746799.6     10654310.18
#Sta/Elev= 30
  4739.4   459.4  4778.4  456.09  4802.7  452.78  4814.8  452.36    4883  446.85
    4901  444.52  4954.8  441.97  4976.3  438.89  4987.1  438.46  4993.8  431.18
  4996.2  430.56    4999  430.06  5002.2  430.56    5006  434.85  5012.2  434.85
  5022.8  437.83  5065.2  437.23  5107.6  437.77  5138.9  441.39  5164.2  443.07
  5249.1  445.62  5305.6  449.38  5333.9  452.32  5348.1  454.83  5362.2  458.56
  5376.4  460.01  5404.6  464.83  5418.8  466.24  5429.4  468.65  5432.9  468.65
#Mann= 5 ,-1 , 0
  4739.4     .16       0    4883     .12       0  4996.2     .07       0
  5002.2     .12       0  5138.9     .05       0
Bank Sta=4987.1,5022.8
XS Rating Curve= 0 ,0
Exp/Cntr=0.3,0.1

Type RM Length L Ch R = 1 ,21360   ,328,328,328
BEGIN DESCRIPTION:
Mapping XS 63104c02
END DESCRIPTION:
XS GIS Cut Line= 3
      3746368.19     10653786.74       3746353.7     10654012.12
      3746411.69     10654315.28
#Sta/Elev= 30
  4763.7  446.34  4797.2  443.92  4807.2  444.17  4820.9  441.46  4827.3  441.47
  4837.3   439.7  4857.3  438.48  4927.5  436.59  4937.5  435.75  4967.6  435.93
    4979  434.83  4993.5  432.78  4995.6  430.32  4998.4  429.82  5001.6  430.32
  5007.9  432.55  5018.1  433.77  5028.3  435.57  5079.2  436.22  5089.4  437.45
  5097.7   437.4  5102.8  438.87  5130.1  438.76  5149.7  440.88  5154.8  440.61
  5160.7   441.7    5181  441.85  5272.7  445.48  5282.8  446.03  5298.2  448.12
#Mann= 3 ,-1 , 0
  4763.7     .12       0  4995.6     .07       0  5001.6     .12       0
Bank Sta=4979,5018.1
XS Rating Curve= 0 ,0
Exp/Cntr=0.3,0.1

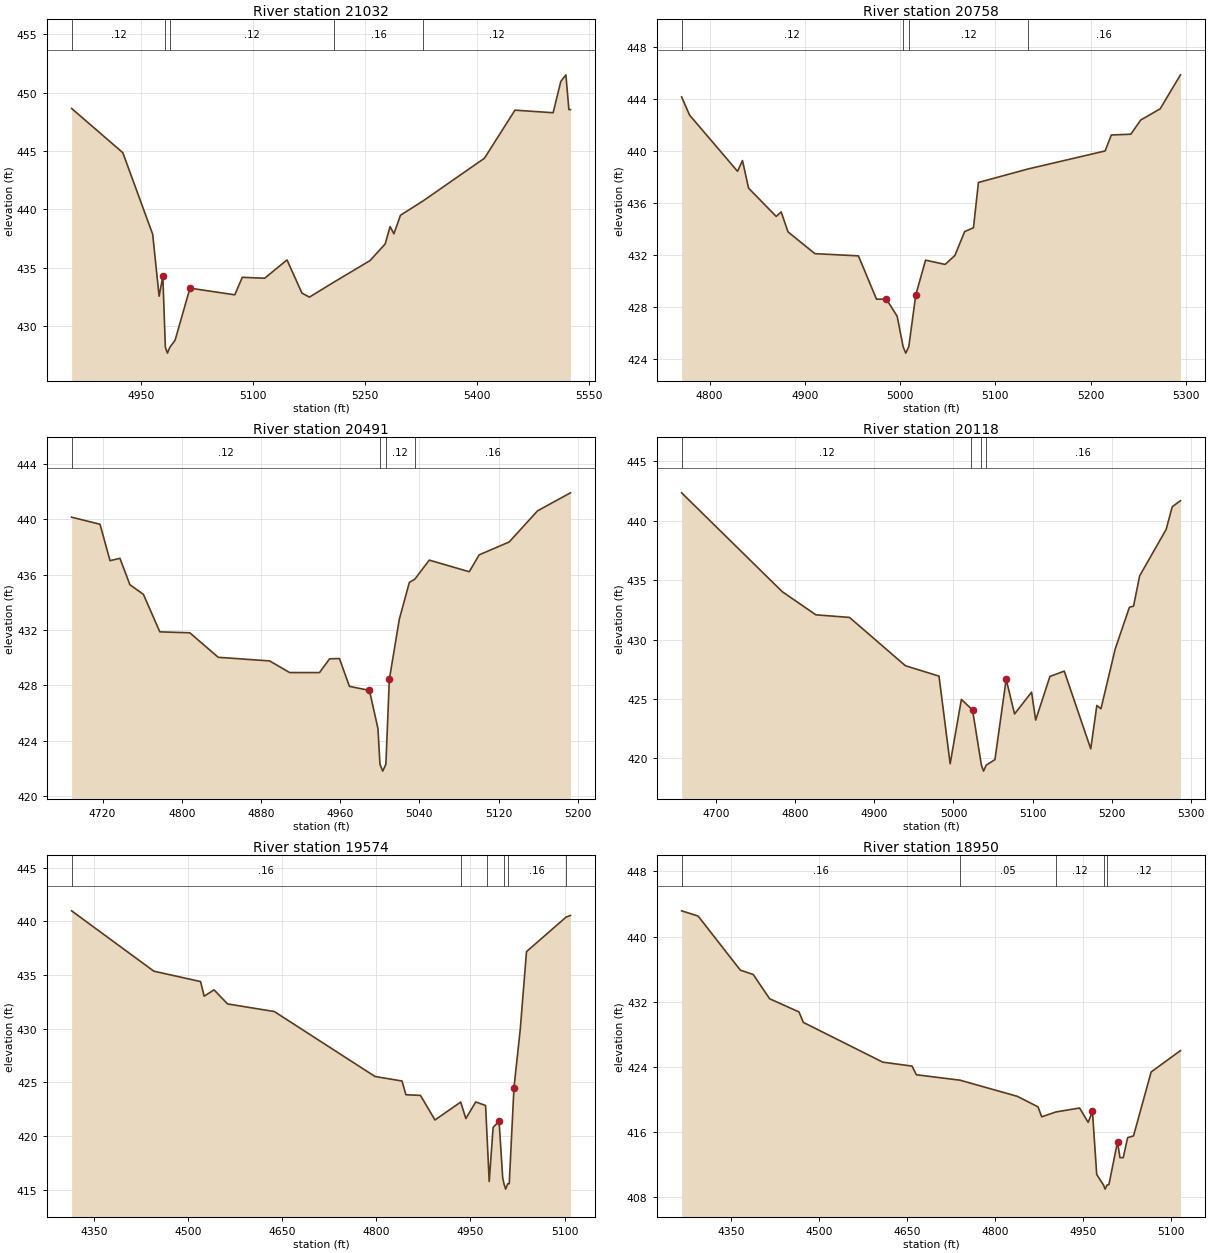
Type RM Length L Ch R = 1 ,21032   ,274,274,274
BEGIN DESCRIPTION:
FIVEMILE BRANCH 43.0
END DESCRIPTION:
XS GIS Cut Line= 3
      3746218.22     10653731.51       3746207.8     10654080.44
       3746275.5     10654392.91
#Sta/Elev= 30
  4856.7  448.64  4925.4  444.84  4965.4  437.85    4974  432.54    4979  434.23
  4982.4  428.16  4985.2  427.66  4988.4  428.16  4995.4  428.76  5015.4  433.23
  5075.5  432.66  5085.5  434.16  5115.5  434.08  5145.5  435.65  5165.5  432.81
  5175.5  432.46  5208.2  433.74  5256.7  435.59  5277.1  437.02  5283.7  438.51
  5288.8  437.89  5297.6  439.48  5328.4  440.73  5410.2  444.37  5451.1  448.49
  5502.3  448.27  5512.5  450.94  5519.4  451.52  5523.4  448.54  5525.5  448.54
#Mann= 5 ,-1 , 0
  4856.7     .12       0  4982.4     .07       0  4988.4     .12       0
  5208.2     .16       0  5328.4     .12       0
Bank Sta=4979,5015.4
XS Rating Curve= 0 ,0
Exp/Cntr=0.3,0.1

Type RM Length L Ch R = 1 ,20758   ,267,267,267
BEGIN DESCRIPTION:
Mapping XS f70f0c84
END DESCRIPTION:
XS GIS Cut Line= 3
       3746018.9     10653842.11      3746074.25     10654055.62
       3746142.8      10654350.9
#Sta/Elev= 30
  4770.6  444.19  4778.9  442.79  4829.3  438.45  4834.5  439.28  4840.9  437.15
  4869.9  434.97  4875.1  435.32  4882.3  433.78  4910.5   432.1  4956.2  431.93
  4975.2  428.59  4985.6  428.59  4996.9  427.27  5003.1  424.93  5005.9  424.43
  5009.1  424.93  5016.4  428.91  5026.7   431.6  5047.2  431.27  5057.5  431.96
  5067.7   433.8    5077   434.1  5082.2  437.59  5134.3  438.63  5215.2  440.02
  5221.7  441.25  5242.2  441.31  5252.5   442.4    5273  443.27  5294.3  445.89
#Mann= 4 ,-1 , 0
  4770.6     .12       0  5003.1     .07       0  5009.1     .12       0
  5134.3     .16       0
Bank Sta=4985.6,5016.4
XS Rating Curve= 0 ,0
Exp/Cntr=0.3,0.1

Type RM Length L Ch R = 1 ,20491   ,373,373,373
BEGIN DESCRIPTION:
FIVEMILE BRANCH 42.0
END DESCRIPTION:
XS GIS Cut Line= 2
      3745973.42     10653861.73      3745910.93     10654361.64
#Sta/Elev= 30
  4688.8  440.15  4717.5  439.64  4727.6  437.01  4737.6  437.18  4747.7  435.27
  4761.3  434.58  4777.9  431.87  4808.2   431.8  4836.9  430.03  4888.8  429.77
    4909  428.93  4939.2  428.93  4949.3  429.92  4959.3  429.94  4969.4  427.93
  4989.6  427.64  4998.2  424.88  5000.2  422.31    5003  421.81  5006.2  422.31
  5009.7  428.44  5019.8  432.79  5029.9  435.44  5035.4  435.67    5050  437.05
  5090.4  436.21  5100.4  437.43  5130.7  438.36  5159.4  440.61  5192.6  441.91
#Mann= 4 ,-1 , 0
  4688.8     .12       0  5000.2     .07       0  5006.2     .12       0
  5035.4     .16       0
Bank Sta=4989.6,5009.7
XS Rating Curve= 0 ,0
Exp/Cntr=0.3,0.1

Type RM Length L Ch R = 1 ,20118   ,544,544,544
BEGIN DESCRIPTION:
FIVEMILE BRANCH 41.0
END DESCRIPTION:
XS GIS Cut Line= 3
      3745899.64     10653710.16      3745599.61     10654010.19
       3745549.6     10654210.23
#Sta/Elev= 30
  4656.4  442.36  4783.7  434.03  4826.1  432.09  4868.6  431.87  4939.3   427.8
  4981.7  426.93  4995.8  419.55    5010  424.97  5022.6  424.17  5024.1  424.08
  5035.3  419.43    5038  418.93  5041.3  419.43  5052.4   419.9  5066.6  426.66
  5077.2  423.74  5098.7  425.58  5103.9  423.23  5121.9   426.9    5140  427.35
  5173.5  420.81  5181.2  424.46  5186.4  424.18  5204.4  429.21  5222.4  432.73
  5227.6  432.82  5235.3  435.37  5268.8  439.28  5276.5  441.19  5286.9   441.7
#Mann= 4 ,-1 , 0
  4656.4     .12       0  5022.6     .16       0  5035.3     .07       0
  5041.3     .16       0
Bank Sta=5024.1,5066.6
XS Rating Curve= 0 ,0
Exp/Cntr=0.3,0.1

Type RM Length L Ch R = 1 ,19574   ,624,624,624
BEGIN DESCRIPTION:
FIVEMILE BRANCH 40.0
END DESCRIPTION:
XS GIS Cut Line= 3
      3745599.59     10653510.23      3745249.61     10654110.19
      3745249.61     10654210.21
#Sta/Elev= 30
  4314.7  440.97  4445.7  435.35  4520.1  434.38  4525.9  433.02  4541.6  433.61
  4563.1   432.3  4637.6  431.59    4798  425.54    4841  425.12  4847.2  423.84
  4870.4  423.78  4893.5  421.49  4934.5  423.16  4942.7  421.62  4958.4  423.17
  4974.1  422.84  4976.7  419.67  4979.9  415.76  4986.1   420.8  4995.6  421.38
  5001.4   416.1  5003.4  415.55  5006.1  415.05  5009.4  415.55  5011.8  415.55
  5019.3  424.48  5029.3   429.9  5039.3  437.17  5102.4  440.39  5109.3  440.54
#Mann= 6 ,-1 , 0
  4314.7     .16       0  4934.5     .12       0  4976.7     .16       0
  5003.4     .07       0  5009.4     .16       0  5102.4     .05       0
Bank Sta=4995.6,5019.3
XS Rating Curve= 0 ,0
Exp/Cntr=0.3,0.1

Type RM Length L Ch R = 1 ,18950   ,535,535,535
BEGIN DESCRIPTION:
FIVEMILE BRANCH 39.0
END DESCRIPTION:
XS GIS Cut Line= 3
      3745499.61     10653460.19      3744899.61     10653910.19
      3744899.61     10654010.19
#Sta/Elev= 30
  4266.4  443.16  4294.5  442.52  4366.4  435.87  4388.3  435.34  4416.4  432.35
  4466.4  430.73  4473.7  429.45  4609.1  424.56  4659.1  424.07  4666.4  423.01
  4740.9  422.34  4838.3  420.36  4873.7  419.06  4879.9  417.84  4904.4  418.44
  4944.5  418.92  4959.1  417.16  4966.4   418.5  4973.7  410.75  4985.3  409.45
    4988  408.95  4991.3  409.45  4994.5  409.51  5009.1  414.76  5013.3  412.82
  5018.9  412.82  5026.4  415.28  5036.4  415.49  5066.4  423.35  5116.4  425.98
#Mann= 5 ,-1 , 0
  4266.4     .16       0  4740.9     .05       0  4904.4     .12       0
  4985.3     .07       0  4991.3     .12       0
Bank Sta=4966.4,5009.1
XS Rating Curve= 0 ,0
Exp/Cntr=0.3,0.1

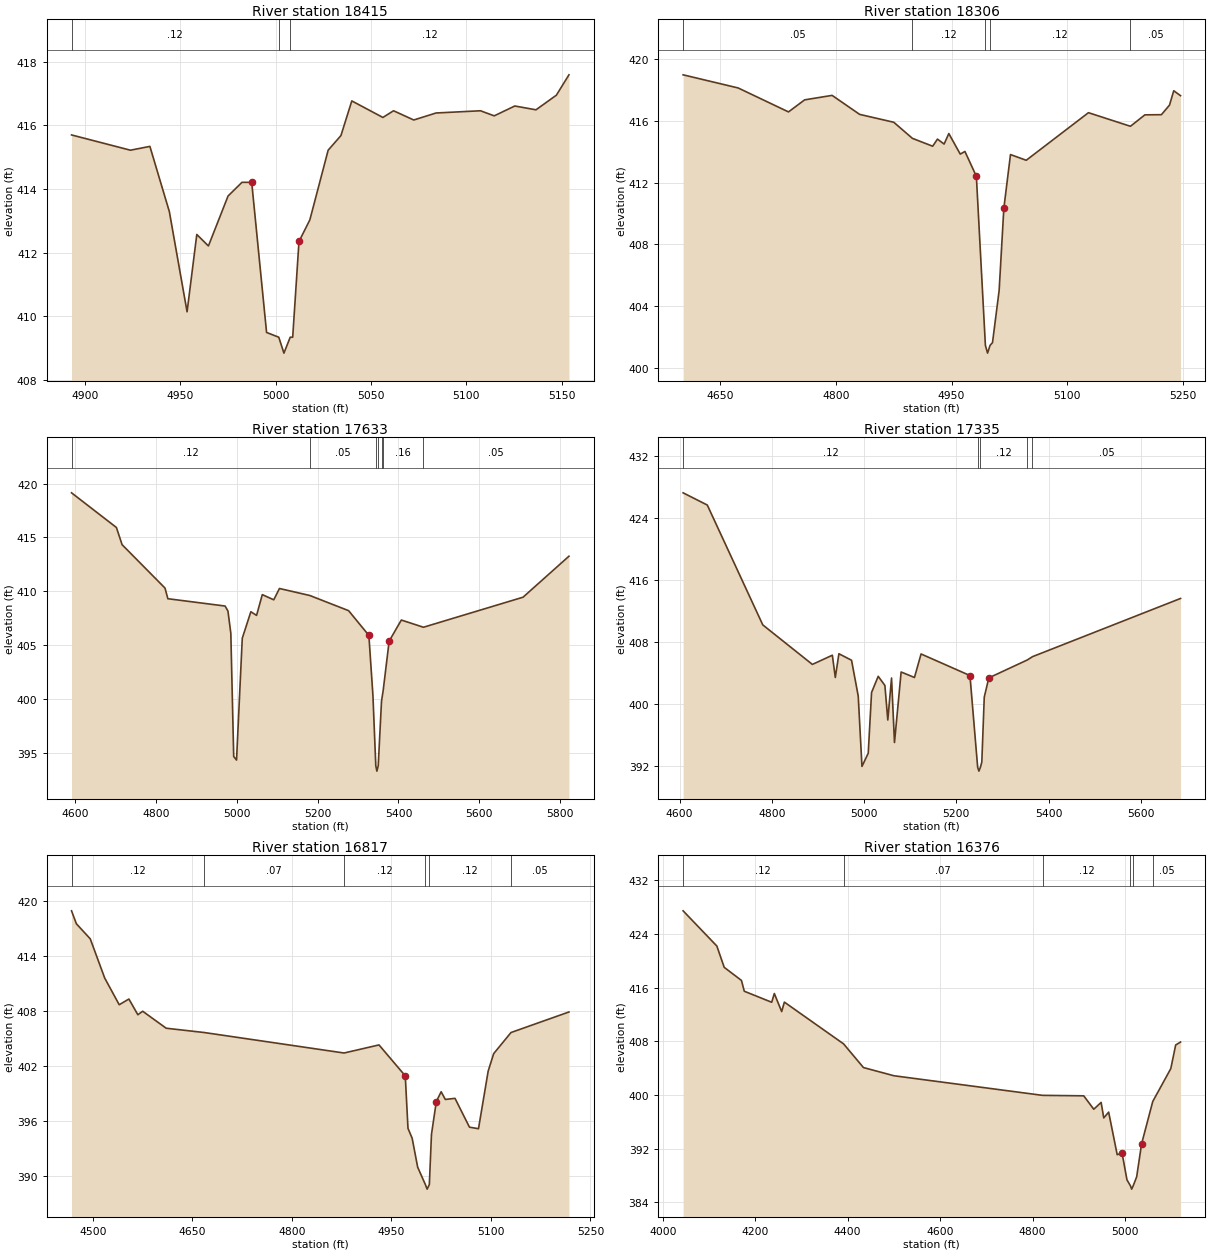
Type RM Length L Ch R = 1 ,18415   ,109,109,109
BEGIN DESCRIPTION:
Mapping XS bf179685
END DESCRIPTION:
XS GIS Cut Line= 5
      3744739.72     10653731.08      3744650.27     10653751.05
      3744625.97     10653752.79      3744547.84     10653794.46
      3744525.75     10653846.28
#Sta/Elev= 30
  4892.9   415.7  4923.8  415.22    4934  415.34  4944.2  413.29  4953.5  410.14
  4958.6  412.57  4964.7  412.21    4975  413.78  4982.3  414.21  4987.4  414.21
  4995.2  409.49  5001.6  409.34  5004.3  408.84  5007.6  409.34  5008.9  409.34
  5012.2  412.35  5017.9  413.03  5027.5  415.22  5034.2  415.68  5039.9  416.77
  5056.2  416.25  5061.8  416.46  5072.4  416.17  5084.1  416.39  5107.4  416.46
  5114.6   416.3  5125.4  416.61  5136.5  416.49  5147.2  416.95  5153.8  417.59
#Mann= 3 ,-1 , 0
  4892.9     .12       0  5001.6     .07       0  5007.6     .12       0
Bank Sta=4987.4,5012.2
XS Rating Curve= 0 ,0
Exp/Cntr=0.3,0.1

Type RM Length L Ch R = 1 ,18306   ,673,673,673
BEGIN DESCRIPTION:
FIVEMILE BRANCH 38.0
END DESCRIPTION:
XS GIS Cut Line= 3
      3744915.59     10653425.85      3744552.73     10653684.54
      3744491.96     10653873.79
#Sta/Elev= 30
  4602.3  418.98  4673.6  418.13  4738.8  416.58  4759.7  417.36  4795.3  417.65
    4831  416.42  4875.2  415.91  4899.3  414.87  4925.6  414.36  4931.8  414.82
  4940.4   414.5  4946.5  415.18  4961.3  413.85  4967.4  414.02  4982.2  412.41
  4993.9  401.47  4996.7  400.97  4999.9  401.47  5003.1  401.65  5011.7  405.03
  5017.8  410.35  5026.4  413.82  5046.8  413.45  5127.4  416.53  5181.8  415.65
  5200.5  416.39  5221.9   416.4  5232.4  417.02  5237.9  417.95  5246.7  417.63
#Mann= 5 ,-1 , 0
  4602.3     .05       0  4899.3     .12       0  4993.9     .07       0
  4999.9     .12       0  5181.8     .05       0
Bank Sta=4982.2,5017.8
XS Rating Curve= 0 ,0
Exp/Cntr=0.3,0.1

Type RM Length L Ch R = 1 ,17633   ,298,298,298
BEGIN DESCRIPTION:
FIVEMILE BRANCH 37.0
END DESCRIPTION:
XS GIS Cut Line= 3
      3744533.31     10652997.12      3744101.03       10653432.
      3743486.41     10653476.27
#Sta/Elev= 30
  4591.9  419.15  4702.8  415.93  4716.9  414.33  4822.9   410.3    4830  409.31
  4971.5  408.63  4978.5  408.16  4985.6   406.1  4992.7  394.65  4999.7  394.32
  5013.9  405.64  5035.1   408.1  5049.2  407.76  5063.4  409.69  5091.7  409.21
  5105.8  410.26  5180.8  409.61  5276.7   408.2  5326.8   405.9  5336.8  400.33
  5343.9  393.79  5346.6  393.29  5349.9  393.79    5358  399.78  5362.2   400.8
  5376.9  405.37    5407  407.33  5461.7  406.66  5707.8  409.45  5821.3  413.26
#Mann= 7 ,-1 , 0
  4591.9     .12       0  5180.8     .05       0  5343.9     .07       0
  5349.9     .05       0    5358     .12       0  5362.2     .16       0
  5461.7     .05       0
Bank Sta=5326.8,5376.9
XS Rating Curve= 0 ,0
Exp/Cntr=0.3,0.1

Type RM Length L Ch R = 1 ,17335   ,518,518,518
BEGIN DESCRIPTION:
FIVEMILE BRANCH 36.0
END DESCRIPTION:
XS GIS Cut Line= 3
       3744267.7     10652814.81       3743892.7     10653291.38
      3743447.43     10653447.61
#Sta/Elev= 30
  4607.8   427.3  4660.2  425.72  4780.5  410.22    4888  405.11  4931.3   406.3
  4937.7  403.42  4945.5  406.49  4972.9  405.65  4987.4  401.02  4995.5  391.92
  5009.1  393.63  5016.3  401.48  5030.7  403.57  5045.2  402.39  5051.5  397.92
  5059.6  403.35    5066  395.01  5080.4  404.13  5109.3  403.42  5123.6  406.46
  5229.6  403.67  5246.3  391.81    5249  391.31  5252.3  391.81  5255.3  392.49
  5260.6  400.88  5270.5  403.37  5354.1  405.69  5365.1  406.11  5686.1  413.64
#Mann= 5 ,-1 , 0
  4607.8     .12       0  5246.3     .07       0  5252.3     .12       0
  5354.1     .16       0  5365.1     .05       0
Bank Sta=5229.6,5270.5
XS Rating Curve= 0 ,0
Exp/Cntr=0.3,0.1

Type RM Length L Ch R = 1 ,16817   ,441,441,441
BEGIN DESCRIPTION:
FIVEMILE BRANCH 35.0
END DESCRIPTION:
XS GIS Cut Line= 3
      3743899.62     10652660.17      3743599.61     10653060.19
      3743449.62     10653260.17
#Sta/Elev= 30
  4467.7  418.88    4475  417.47  4495.9  415.83  4517.7  411.56  4539.6  408.65
  4554.2  409.27  4567.7  407.56    4575  407.94  4610.4  406.09  4667.9  405.62
  4878.6  403.39  4931.3  404.27  4970.9   400.9    4975  395.18  4981.3   394.1
  4989.6  390.95  5001.2  389.06  5003.9  388.56  5007.2  389.06  5010.4  394.52
  5017.7   398.1    5025  399.17  5031.3  398.33  5045.9  398.45  5067.7  395.31
  5081.3  395.14  5095.9  401.42  5104.2  403.32  5130.3  405.62  5217.7  407.86
#Mann= 6 ,-1 , 0
  4467.7     .12       0  4667.9     .07       0  4878.6     .12       0
  5001.2     .07       0  5007.2     .12       0  5130.3     .05       0
Bank Sta=4970.9,5017.7
XS Rating Curve= 0 ,0
Exp/Cntr=0.3,0.1

Type RM Length L Ch R = 1 ,16376   ,449,449,449
BEGIN DESCRIPTION:
FIVEMILE BRANCH 34.0
END DESCRIPTION:
XS GIS Cut Line= 3
      3743999.62     10652510.18      3743199.61     10652960.19
      3743149.61     10653110.18
#Sta/Elev= 30
  4044.2  427.43  4117.2  422.18  4133.1  419.01  4170.4  417.06  4176.5  415.45
  4235.8  413.81  4241.5  415.11  4257.4  412.42  4263.2  413.83  4391.3  407.61
  4434.3  404.08  4500.3  402.86  4821.6  399.94  4910.8  399.87  4932.5  397.87
  4948.4  398.89  4954.1  396.58  4964.7  397.44  4983.2   391.1  4993.7  391.34
  5004.3  387.35  5011.8  386.47  5014.5  385.97  5017.8  386.47  5025.3   387.8
  5035.9   392.7  5060.1  399.03  5099.1  403.92  5109.7  407.45  5120.2  407.88
#Mann= 6 ,-1 , 0
  4044.2     .12       0  4391.3     .07       0  4821.6     .12       0
  5011.8     .07       0  5017.8     .12       0  5060.1     .05       0
Bank Sta=4993.7,5035.9
XS Rating Curve= 0 ,0
Exp/Cntr=0.3,0.1