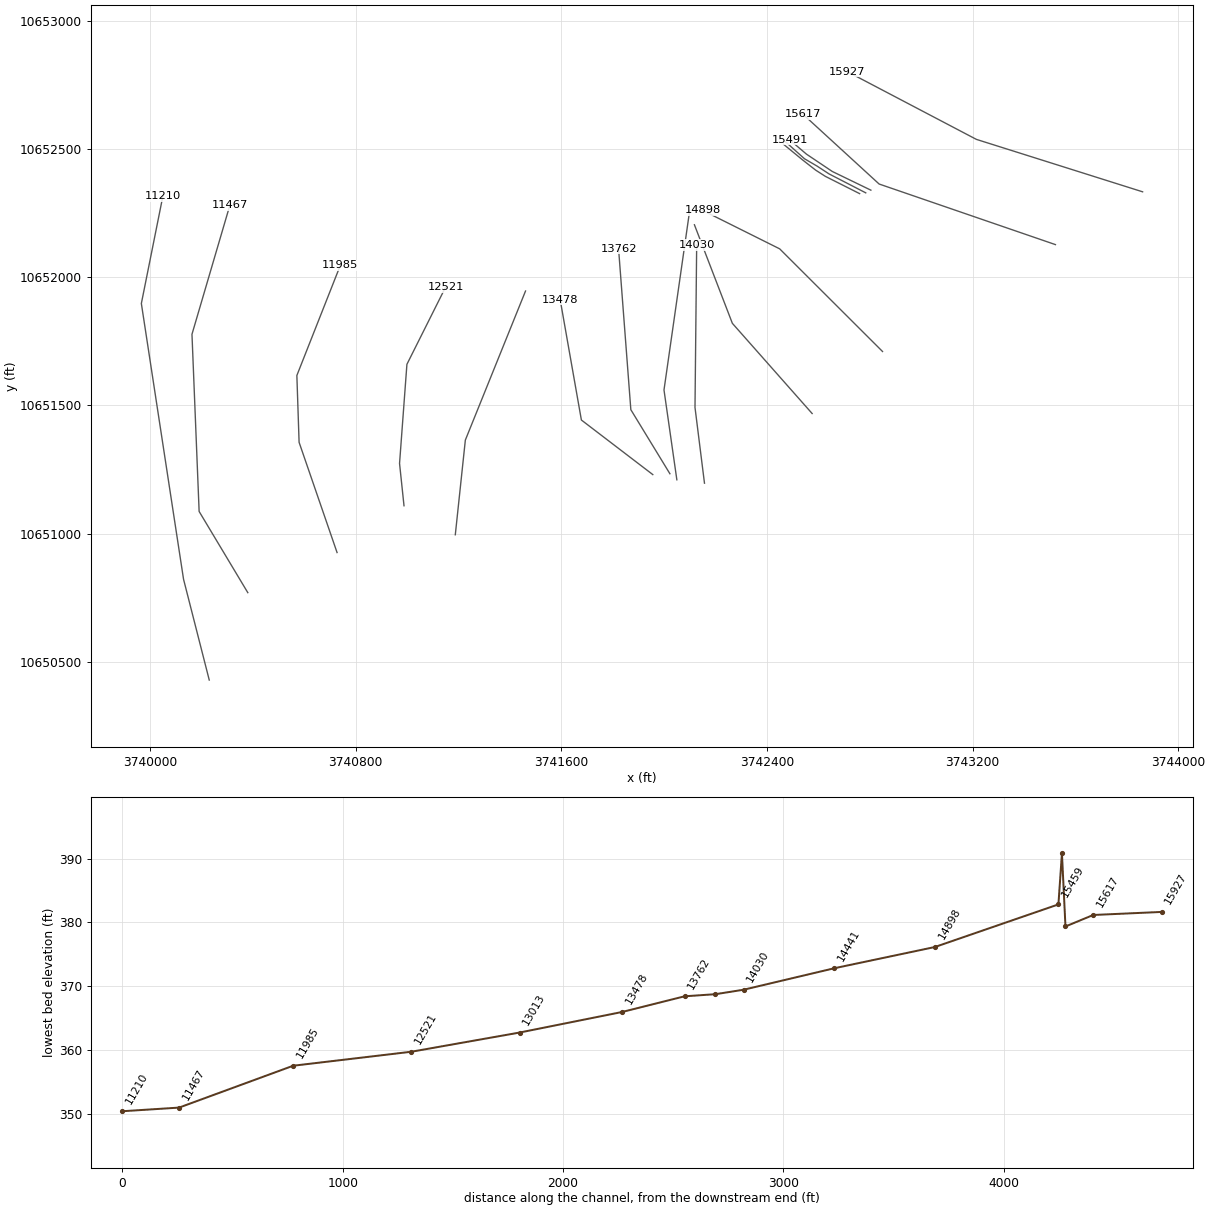
HEC-RAS study FIVEMILE BRANCH.prj: FIVEMILE BRANCH Base Level Engineering

--- FIVEMILE BRANCH.g01 (geometry) --- (continued)

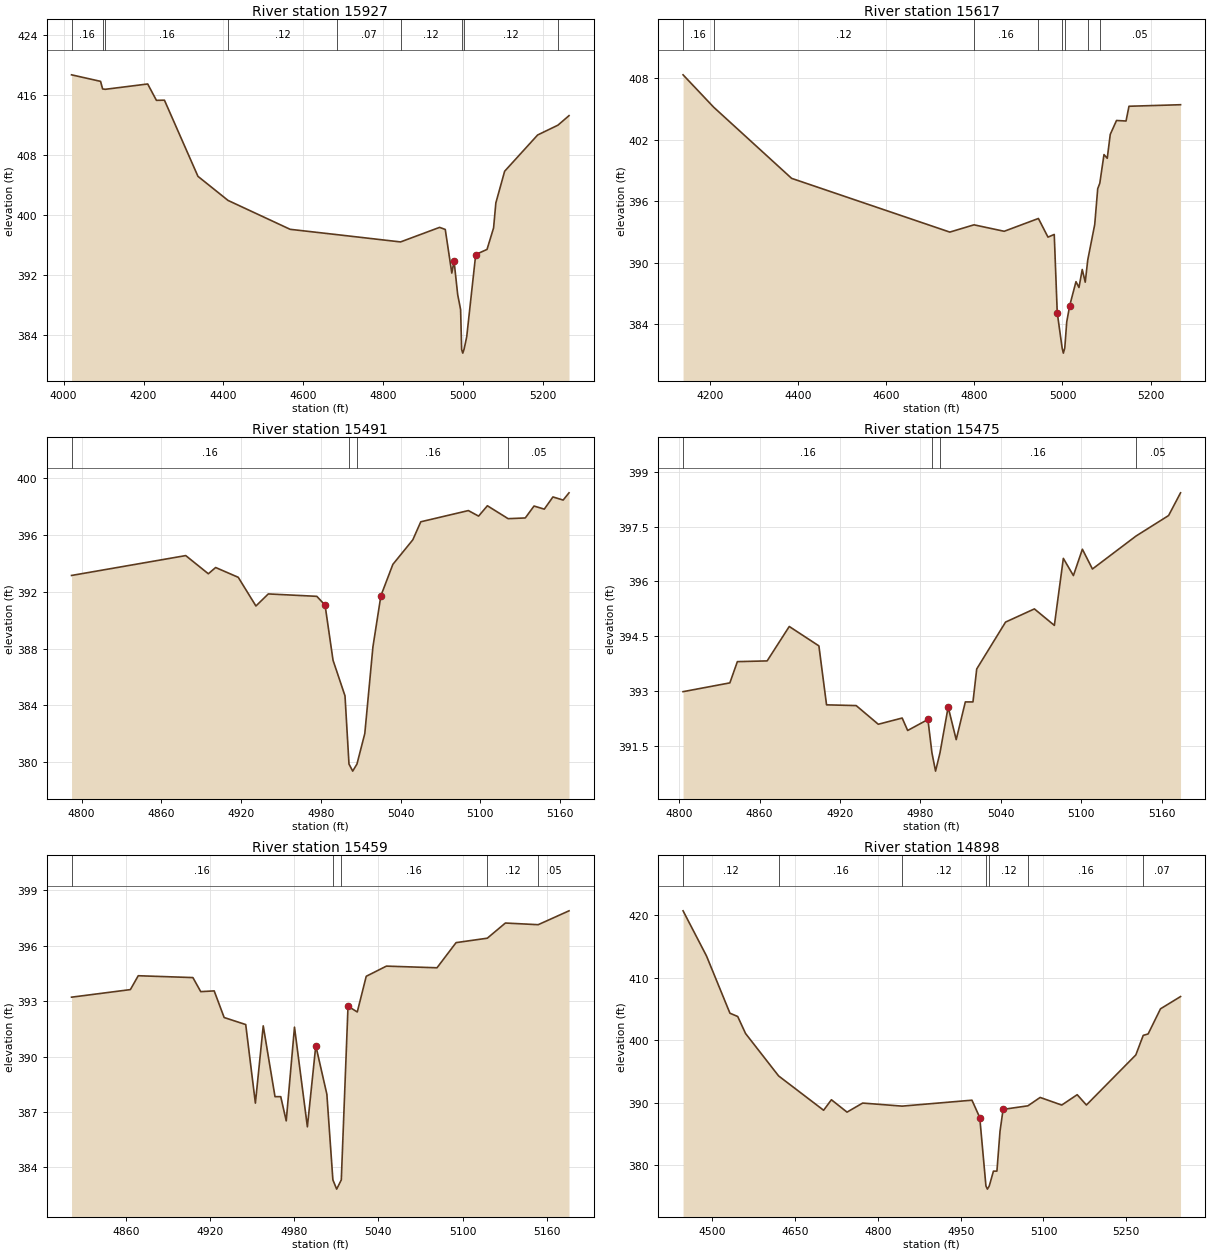
Type RM Length L Ch R = 1 ,15927   ,310,310,310
BEGIN DESCRIPTION:
FIVEMILE BRANCH 33.0
END DESCRIPTION:
XS GIS Cut Line= 3
      3743861.32     10652332.49      3743214.75     10652536.82
      3742712.98     10652800.68
#Sta/Elev= 30
  4019.8  418.74  4092.4  417.87  4097.6  416.86  4104.2  416.81  4210.4  417.52
  4232.2  415.34  4252.3  415.36  4336.2  405.21  4411.5     402  4566.9  398.15
  4684.3  397.44  4843.2  396.47    4941  398.41  4955.1  398.13  4971.5  392.32
  4977.1  393.93  4986.2  389.45  4993.5  387.46  4996.1  382.15  4998.9  381.65
  5002.1  382.15  5008.8  383.83  5031.3  394.79  5059.6  395.47    5076  398.33
  5081.7  401.67  5103.7  405.89  5186.2  410.72  5237.1  412.03  5264.8   413.3
#Mann= 9 ,-1 , 0
  4019.8     .16       0  4097.6     .12       0  4104.2     .16       0
  4411.5     .12       0  4684.3     .07       0  4843.2     .12       0
  4996.1     .07       0  5002.1     .12       0  5237.1     .05       0
Bank Sta=4977.1,5031.3
XS Rating Curve= 0 ,0
Exp/Cntr=0.3,0.1

Type RM Length L Ch R = 1 ,15617   ,126,126,126
BEGIN DESCRIPTION:
FIVEMILE BRANCH 32.0
END DESCRIPTION:
XS GIS Cut Line= 3
      3743522.17     10652126.73      3742836.41     10652362.84
      3742539.68     10652635.28
#Sta/Elev= 30
  4139.7  408.35  4209.1  405.19  4385.8  398.24  4744.6  392.99  4799.4   393.7
  4867.9  393.07  4945.5  394.32  4967.2   392.5  4981.4  392.76  4988.2  385.13
  4999.3  381.67  5002.1  381.17  5005.3  381.67  5009.7  384.21  5016.5  385.82
  5030.7  388.15  5037.5  387.58  5044.9  389.34  5051.7   388.1  5057.4  390.27
  5073.2  393.73    5080  397.23  5084.7  397.76  5094.2  400.56  5101.6   400.2
  5108.4  402.53  5122.6  403.89  5144.2  403.84  5150.9  405.28  5267.8  405.43
#Mann= 8 ,-1 , 0
  4139.7     .16       0  4209.1     .12       0  4799.4     .16       0
  4945.5     .12       0  4999.3     .07       0  5005.3     .12       0
  5057.4     .16       0  5084.7     .05       0
Bank Sta=4988.2,5016.5
XS Rating Curve= 0 ,0
Exp/Cntr=0.3,0.1

Type RM Length L Ch R = 1 ,15491   ,16,16,16
BEGIN DESCRIPTION:
Mapping XS f99dd111
END DESCRIPTION:
XS GIS Cut Line= 4
      3742804.34     10652338.89      3742654.15     10652411.81
      3742553.46     10652479.52      3742488.14     10652535.32
#Sta/Elev= 30
  4792.5  393.15  4878.4  394.55  4895.4  393.27  4900.9  393.71  4917.9  393.02
  4931.2     391  4940.5  391.85    4977  391.68  4983.2  391.06  4989.2  387.18
  4998.2  384.67  5001.2  379.87    5004  379.37  5007.2  379.87  5013.1  382.02
  5019.2  388.12  5025.2  391.72  5034.2  393.93  5049.2  395.66  5055.2  396.93
    5091  397.72  5098.7  397.33  5105.3  398.06  5120.9  397.15  5133.8   397.2
  5140.4  398.04  5148.1  397.82  5154.6  398.68  5162.3  398.46  5166.7  398.97
#Mann= 4 ,-1 , 0
  4792.5     .16       0  5001.2     .07       0  5007.2     .16       0
  5120.9     .05       0
Bank Sta=4983.2,5025.2
XS Rating Curve= 0 ,0
Exp/Cntr=0.3,0.1

Type RM Length L Ch R = 1 ,15475   ,16,16,16
BEGIN DESCRIPTION:
Mapping XS bec4d9d9
END DESCRIPTION:
XS GIS Cut Line= 5
      3742784.32      10652328.5      3742641.56     10652402.27
      3742595.12     10652432.65      3742546.08     10652461.29
      3742473.18     10652526.81
#Sta/Elev= 30
    4803  392.99  4837.9  393.23  4843.5  393.81  4865.7  393.83  4882.2  394.77
  4904.3  394.24    4910  392.63  4932.1  392.61  4948.6   392.1  4966.4  392.27
  4970.5  391.93  4985.6  392.23  4988.6  391.32  4991.3  390.82  4994.6  391.32
  5000.7  392.57  5006.7  391.68  5013.5  392.71  5019.2  392.71    5022  393.61
  5043.5  394.89    5065  395.25  5079.9   394.8  5086.6  396.63  5094.1  396.16
  5100.8  396.88  5108.3  396.34  5140.8  397.24  5165.1   397.8    5174  398.42
#Mann= 4 ,-1 , 0
    4803     .16       0  4988.6     .07       0  4994.6     .16       0
  5140.8     .05       0
Bank Sta=4985.6,5000.7
XS Rating Curve= 0 ,0
Exp/Cntr=0.3,0.1

Type RM Length L Ch R = 1 ,15459   ,561,561,561
BEGIN DESCRIPTION:
Mapping XS 4597a2f8
END DESCRIPTION:
XS GIS Cut Line= 5
      3742760.53     10652325.42      3742627.24     10652392.72
      3742589.48     10652417.02      3742539.57     10652456.08
      3742464.32     10652517.93
#Sta/Elev= 30
    4821  393.21    4863  393.62  4868.6  394.37  4907.6  394.27  4913.2  393.51
  4922.8  393.55  4929.9  392.11  4945.3  391.73  4952.2  387.48  4957.8  391.66
  4966.2  387.83  4970.3  387.83  4974.2  386.52  4980.1  391.59  4989.3   386.2
  4995.3  390.59  5003.2  387.96  5007.5  383.33  5010.2  382.83  5013.5  383.33
  5018.3  392.72  5024.9  392.41  5031.3  394.34  5045.7  394.89  5081.8   394.8
  5095.4  396.16  5117.7   396.4  5130.6  397.22    5154  397.13    5176  397.88
#Mann= 5 ,-1 , 0
    4821     .16       0  5007.5     .07       0  5013.5     .16       0
  5117.7     .12       0    5154     .05       0
Bank Sta=4995.3,5018.3
XS Rating Curve= 0 ,0
Exp/Cntr=0.3,0.1

Type RM Length L Ch R = 1 ,14898   ,457,457,457
BEGIN DESCRIPTION:
FIVEMILE BRANCH 31.0
END DESCRIPTION:
XS GIS Cut Line= 3
      3742849.64     10651710.16      3742449.61     10652110.19
      3742149.64     10652260.17
#Sta/Elev= 30
  4447.2  420.68  4489.7  413.45  4532.1   404.3  4546.2  403.77  4560.4  401.05
  4620.3  394.26  4701.8  388.77  4715.9  390.45  4744.2  388.47  4772.5  389.92
    4844  389.43  4970.5  390.38  4984.6  387.61  4995.8  376.65  4998.5  376.15
  5001.8  376.65  5009.4  379.03  5015.7  379.03  5021.3   385.4  5026.9  388.91
  5071.8  389.48    5094  390.82  5133.1   389.6  5161.1  391.26  5177.8  389.61
  5267.3  397.62  5280.7  400.75  5289.6  400.98    5312     405  5348.3  406.96
#Mann= 7 ,-1 , 0
  4447.2     .12       0  4620.3     .16       0    4844     .12       0
  4995.8     .07       0  5001.8     .12       0  5071.8     .16       0
  5280.7     .07       0
Bank Sta=4984.6,5026.9
XS Rating Curve= 0 ,0
Exp/Cntr=0.3,0.1

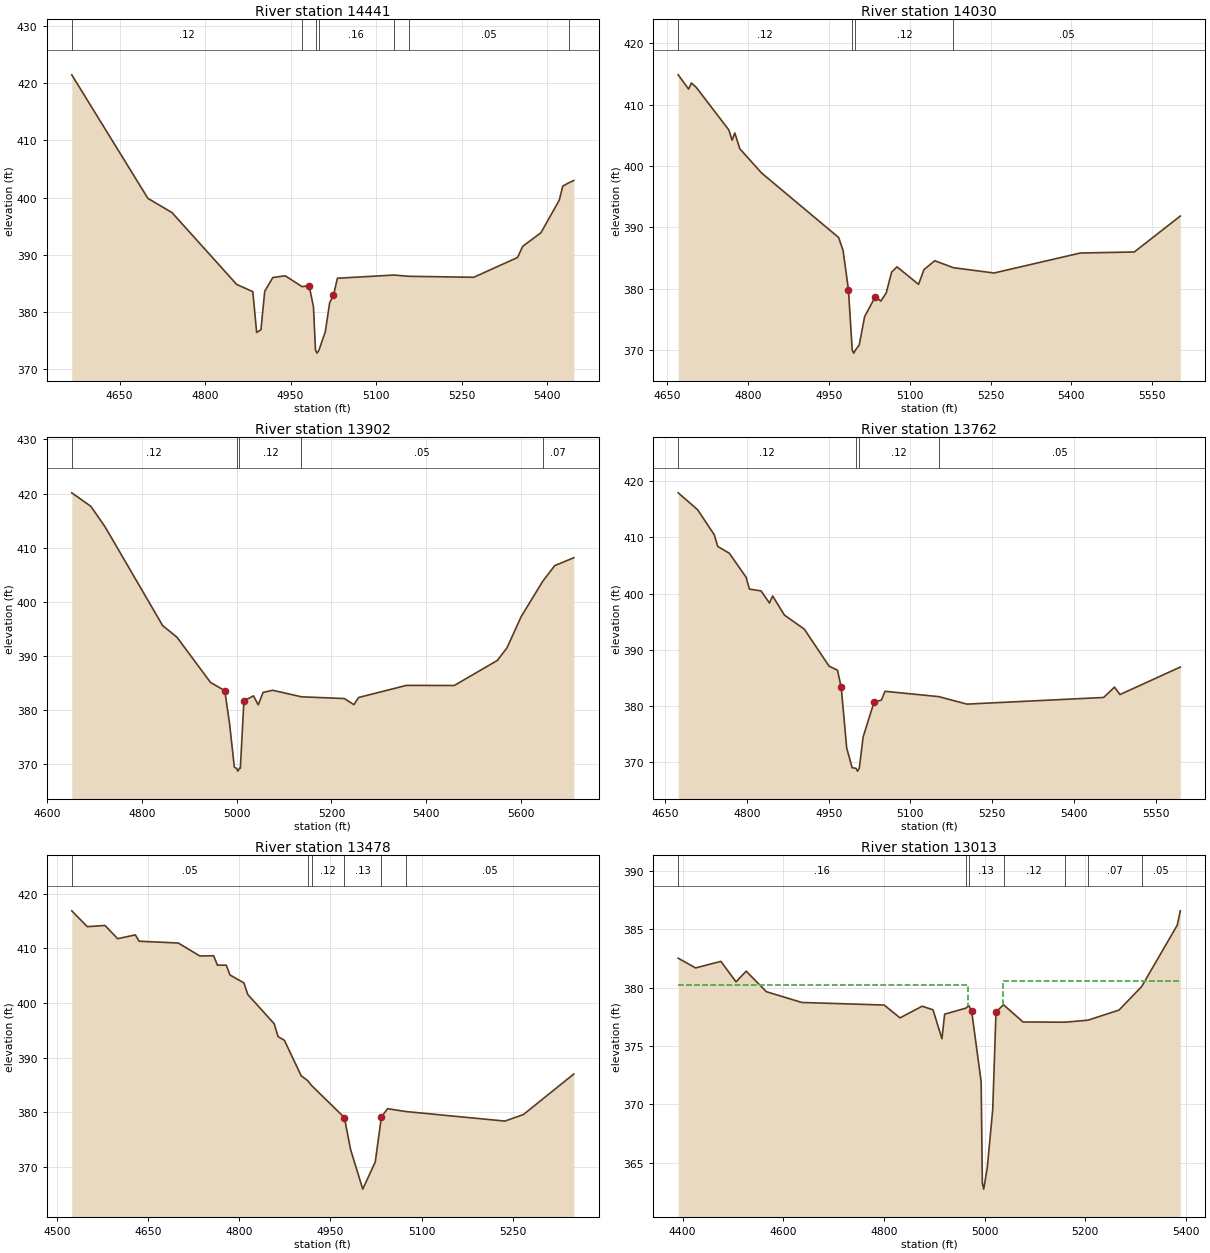
Type RM Length L Ch R = 1 ,14441   ,411,411,411
BEGIN DESCRIPTION:
FIVEMILE BRANCH 30.0
END DESCRIPTION:
XS GIS Cut Line= 3
      3742575.83      10651468.4      3742265.51     10651819.95
      3742117.94     10652204.05
#Sta/Elev= 30
  4566.3  421.44  4699.8  399.86  4742.1  397.37  4855.4  384.83  4883.8  383.56
  4890.5  376.43    4898  376.91  4904.7  383.64  4918.9  386.03  4940.7  386.33
    4970  384.44  4982.5   384.6  4990.1  380.94  4993.7  373.32  4996.5  372.82
  4999.7  373.32  5010.9  376.56  5018.5  381.63  5025.2  382.91  5032.1   385.9
    5131  386.46  5158.1  386.24  5271.2  386.07    5348  389.53  5356.9  391.47
    5389  393.85  5421.1  399.54  5427.3     402    5438  402.58  5446.7  402.98
#Mann= 7 ,-1 , 0
  4566.3     .12       0    4970     .16       0  4993.7     .07       0
  4999.7     .16       0    5131     .12       0  5158.1     .05       0
    5438     .07       0
Bank Sta=4982.5,5025.2
XS Rating Curve= 0 ,0
Exp/Cntr=0.3,0.1

Type RM Length L Ch R = 1 ,14030   ,128,128,128
BEGIN DESCRIPTION:
Mapping XS f0eeff2e
END DESCRIPTION:
XS GIS Cut Line= 3
      3742157.09     10651196.87       3742120.2     10651492.01
      3742126.71     10652125.44
#Sta/Elev= 30
    4671  414.85  4690.2  412.52  4695.3  413.52  4704.6  412.79    4765  405.84
  4770.9  404.18  4775.9  405.37  4785.2  402.79  4825.5  398.84  4968.4  388.32
  4976.6  386.21  4986.6  379.81  4993.6  369.96  4996.4  369.46  4999.6  369.96
  5006.6   370.8  5016.6  375.43  5036.6  378.68  5046.6  377.95  5056.6  379.27
  5066.6  382.66  5076.6  383.53  5116.6  380.68  5126.6  383.08  5146.6  384.53
  5181.3  383.39  5256.6  382.53  5416.6  385.79  5516.6  385.96  5601.9  391.82
#Mann= 4 ,-1 , 0
    4671     .12       0  4993.6     .07       0  4999.6     .12       0
  5181.3     .05       0
Bank Sta=4986.6,5036.6
XS Rating Curve= 0 ,0
Exp/Cntr=0.3,0.1

Type RM Length L Ch R = 1 ,13902   ,140,140,140
BEGIN DESCRIPTION:
FIVEMILE BRANCH 29.0
END DESCRIPTION:
XS GIS Cut Line= 3
      3742049.61     10651210.15      3741999.61     10651560.19
      3742099.61     10652260.19
#Sta/Elev= 30
  4651.5  420.14  4691.9  417.64  4722.2  413.82  4843.5  395.63  4873.8  393.48
  4944.5  385.15  4974.8  383.61  4984.9   377.5    4995  369.49  4999.6  369.26
  5002.3  368.76  5005.6  369.26  5007.6  369.26  5015.2  381.74  5035.4  382.66
  5045.5     381  5055.6  383.29  5075.8  383.69  5136.8  382.48  5227.3  382.16
  5247.5  381.04  5257.6  382.36  5358.6  384.59  5459.7  384.57  5550.6   389.2
  5570.8   391.5  5601.1  397.31  5646.1  403.76  5671.8   406.7  5712.2  408.16
#Mann= 5 ,-1 , 0
  4651.5     .12       0  4999.6     .07       0  5005.6     .12       0
  5136.8     .05       0  5646.1     .07       0
Bank Sta=4974.8,5015.2
XS Rating Curve= 0 ,0
Exp/Cntr=0.3,0.1

Type RM Length L Ch R = 1 ,13762   ,284,284,284
BEGIN DESCRIPTION:
Mapping XS bdb41a56
END DESCRIPTION:
XS GIS Cut Line= 3
      3742022.56     10651233.74      3741870.63     10651483.33
      3741822.89     10652110.52
#Sta/Elev= 30
    4674  417.93  4709.7  414.91  4740.1  410.47  4746.5   408.4  4767.8  407.18
  4798.6   402.9  4804.6  400.81  4825.9  400.49  4841.4  398.33  4847.2  399.58
  4868.9  396.18  4905.3  393.69  4950.8   387.1  4966.2  386.38  4973.1  383.31
  4983.1  372.52  4993.1  369.04  5000.2  368.93  5002.9  368.43  5006.2  368.93
  5013.2  374.49  5033.2  380.68  5046.9  381.08  5053.3  382.63    5152  381.68
  5203.7  380.35  5454.5  381.53  5474.5  383.37  5484.5  382.05  5595.2  386.94
#Mann= 4 ,-1 , 0
    4674     .12       0  5000.2     .07       0  5006.2     .12       0
    5152     .05       0
Bank Sta=4973.1,5033.2
XS Rating Curve= 0 ,0
Exp/Cntr=0.3,0.1

Type RM Length L Ch R = 1 ,13478   ,465,465,465
BEGIN DESCRIPTION:
FIVEMILE BRANCH 28.0
END DESCRIPTION:
XS GIS Cut Line= 3
      3741956.03     10651230.42      3741678.29     10651443.07
      3741595.81     10651911.87
#Sta/Elev= 30
  4524.7  416.89  4550.3  413.99  4579.4  414.21  4600.2  411.79  4629.2  412.49
  4635.5  411.33  4699.9     411  4735.3  408.63    4758  408.67  4764.3  406.95
  4778.8  406.94  4785.1  405.14  4807.9   403.7  4814.2  401.58  4857.7  396.22
    4864  393.89  4874.5  393.19    4902  386.72  4912.8  385.82  4919.2  384.92
  4973.1  379.07  4983.3  373.22  5003.3  365.97  5023.9  370.95    5034   379.2
  5044.2  380.69    5074  380.17    5237  378.42  5267.6  379.62  5350.5  387.04
#Mann= 6 ,-1 , 0
  4524.7     .05       0  4912.8     .16       0  4919.2     .12       0
  4973.1     .13       0    5034     .12       0    5074     .05       0
Bank Sta=4973.1,5034
XS Rating Curve= 0 ,0
Exp/Cntr=0.3,0.1

Type RM Length L Ch R = 1 ,13013   ,492,492,492
BEGIN DESCRIPTION:
FIVEMILE BRANCH 27.0
END DESCRIPTION:
XS GIS Cut Line= 3
      3741187.83     10650995.98       3741226.9     10651364.94
      3741460.99     10651945.83
#Sta/Elev= 30
  4391.4  382.53  4425.8   381.7  4476.1  382.26  4506.2  380.51  4526.4  381.42
  4566.6  379.66    4637  378.74  4800.4  378.52    4832  377.42  4875.9  378.42
  4897.5  378.11  4915.2  375.63  4920.6  377.74  4962.6  378.25  4968.9  378.46
  4974.3  377.98  4993.1  371.95  4995.5  363.25  4998.2  362.75  5005.3   364.6
  5016.1  369.59  5022.6  377.93  5037.6  378.54  5076.3  377.07  5159.3  377.05
  5205.2  377.22    5267  378.09  5311.9   380.1  5382.6  385.36  5388.7  386.59
#Mann= 7 ,-1 , 0
  4391.4     .16       0  4962.6     .12       0  4968.9     .13       0
  5037.6     .12       0  5159.3     .05       0  5205.2     .07       0
  5311.9     .05       0
#XS Ineff= 2 , 0
         4967.73   380.2 5037.27          380.61
Permanent Ineff=
       F       F
Bank Sta=4974.3,5022.6
XS Rating Curve= 0 ,0
Exp/Cntr=0.3,0.1

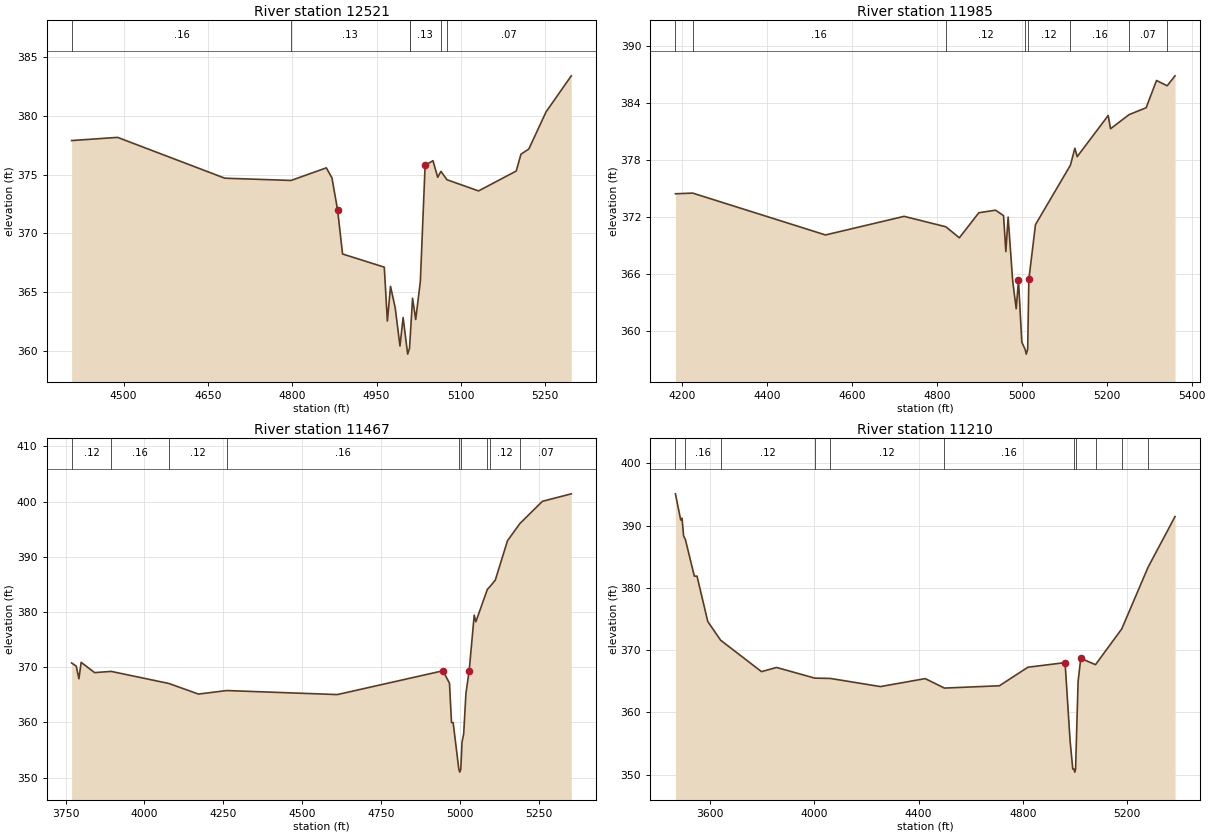
Type RM Length L Ch R = 1 ,12521   ,536,536,536
BEGIN DESCRIPTION:
FIVEMILE BRANCH 26.0
END DESCRIPTION:
XS GIS Cut Line= 4
      3740988.31      10651108.9      3740970.95     10651273.81
      3740999.61     10651660.19      3741149.62     10651960.22
#Sta/Elev= 30
  4407.6  377.89  4489.3  378.16  4680.1  374.69    4798   374.5  4860.6  375.57
  4870.6  374.72  4880.6  372.01  4889.5  368.25  4963.7  367.13  4969.2  362.55
  4974.8   365.5  4983.2  363.66  4991.6  360.43  4997.2  362.85  5005.3  359.74
  5008.6  360.24    5014  364.49  5019.6  362.68  5027.9  365.95  5036.3  375.77
  5050.3  376.18  5058.7  374.77  5064.5  375.27  5075.2  374.56  5131.4  373.61
  5198.4   375.3  5206.8  376.73  5220.8  377.17  5251.5  380.33  5296.3  383.39
#Mann= 6 ,-1 , 0
  4407.6     .16       0    4798     .13       0  5008.6     .07       0
  5008.6     .13       0  5064.5     .16       0  5075.2     .07       0
Bank Sta=4880.6,5036.3
XS Rating Curve= 0 ,0
Exp/Cntr=0.3,0.1

Type RM Length L Ch R = 1 ,11985   ,518,518,518
BEGIN DESCRIPTION:
FIVEMILE BRANCH 25.0
END DESCRIPTION:
XS GIS Cut Line= 4
      3740727.89      10650926.6       3740580.2     10651356.26
      3740571.52     10651616.68      3740740.56     10652045.78
#Sta/Elev= 30
  4184.8  374.45  4225.5  374.52  4538.1  370.11  4723.1  372.07  4821.5  370.97
  4853.2  369.81    4899  372.45  4938.3  372.72  4957.2  372.15  4962.6  368.36
    4968  371.99  4978.7  365.27    4987  362.33  4992.4  365.32  5000.2  358.81
    5008  358.05  5010.7  357.55    5014  358.05  5016.8  365.43  5032.4   371.2
  5114.7  377.47  5125.1  379.25  5130.5  378.36  5203.6   382.7    5209   381.3
  5252.7  382.79  5292.9  383.52  5317.3  386.39  5342.4  385.83  5360.9  386.88
#Mann= 8 ,-1 , 0
  4184.8     .05       0  4225.5     .16       0  4821.5     .12       0
    5008     .07       0    5014     .12       0  5114.7     .16       0
  5252.7     .07       0  5342.4     .05       0
Bank Sta=4992.4,5016.8
XS Rating Curve= 0 ,0
Exp/Cntr=0.3,0.1

Type RM Length L Ch R = 1 ,11467   ,257,257,257
BEGIN DESCRIPTION:
FIVEMILE BRANCH 24.0
END DESCRIPTION:
XS GIS Cut Line= 4
      3740380.68     10650770.33      3740191.37     10651086.72
      3740163.53     10651777.27      3740311.11     10652280.77
#Sta/Elev= 30
    3769  370.77  3783.6  370.19  3792.1  367.91  3799.1  370.88  3841.9  369.02
  3894.5  369.24  4077.4  367.05  4171.2  365.13  4260.8  365.77  4611.6  365.04
  4946.5  369.35  4967.3   367.1  4973.7  359.98  4978.9  359.95    4997  351.49
  4999.8  350.99    5003  351.49  5007.1  356.42  5012.3  357.92  5019.4  365.24
  5029.8  369.39  5045.7  379.43  5050.9  378.23  5087.3  384.09  5096.7  384.68
  5112.5  385.77  5151.2  392.91  5190.6  396.03  5261.8  400.05  5353.5  401.41
#Mann= 9 ,-1 , 0
    3769     .12       0  3894.5     .16       0  4077.4     .12       0
  4260.8     .16       0    4997     .07       0    5003     .16       0
  5087.3     .07       0  5096.7     .12       0  5190.6     .07       0
Bank Sta=4946.5,5029.8
XS Rating Curve= 0 ,0
Exp/Cntr=0.3,0.1

Type RM Length L Ch R = 1 ,11210   ,137,137,137
BEGIN DESCRIPTION:
Mapping XS f8bd88e0
END DESCRIPTION:
XS GIS Cut Line= 4
      3740230.72     10650429.75      3740130.72     10650822.57
      3739966.63     10651897.19      3740050.25     10652315.29
#Sta/Elev= 30
  3466.2  395.12  3486.6  390.92  3491.7   391.2  3497.6  388.36  3504.4  387.79
  3538.9   381.9  3549.2   381.9  3590.5  374.61  3639.8  371.61  3796.9  366.56
  3854.7  367.23  4001.4  365.52    4061  365.47  4253.5  364.16  4425.5  365.44
  4499.3  363.92  4710.4  364.29    4820  367.27  4962.7  368.01  4982.1  355.37
  4992.3  350.92    4997  350.92  4999.8  350.42    5003  350.92  5012.7  364.98
  5022.9  368.69  5079.6  367.68  5180.4  373.43  5281.2  383.31    5385  391.47
#Mann= 11 ,-1 , 0
  3466.2     .12       0  3504.4     .16       0  3639.8     .12       0
  4001.4     .16       0    4061     .12       0  4499.3     .16       0
    4997     .07       0    5003     .16       0  5079.6     .12       0
  5180.4     .07       0  5281.2     .05       0
Bank Sta=4962.7,5022.9
XS Rating Curve= 0 ,0
Exp/Cntr=0.3,0.1