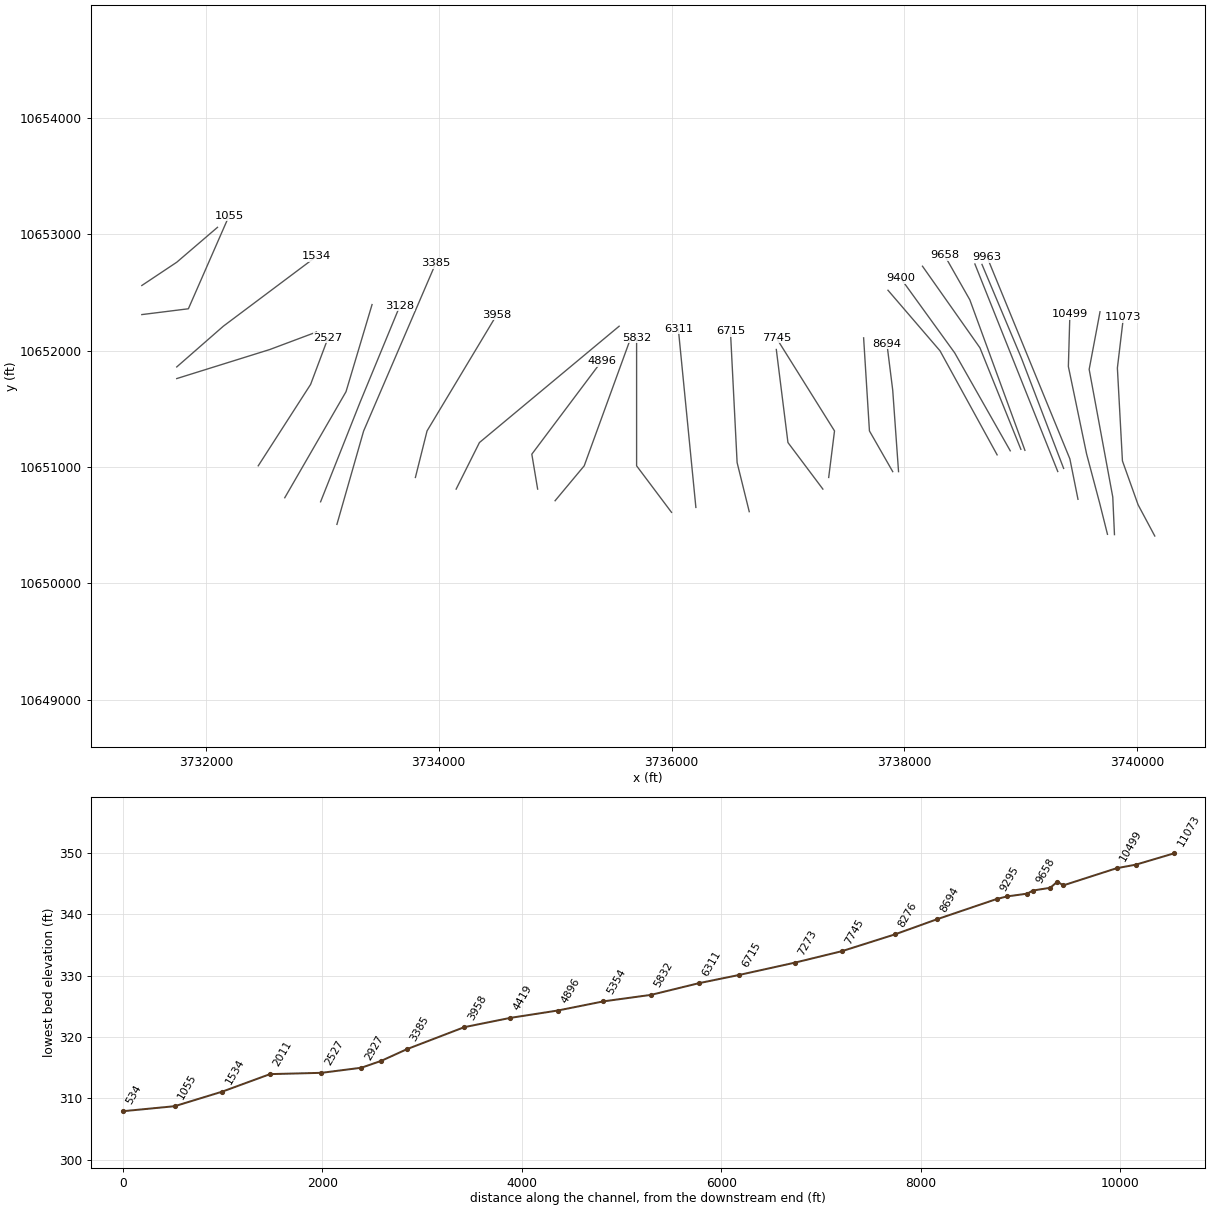
HEC-RAS study FIVEMILE BRANCH.prj: FIVEMILE BRANCH Base Level Engineering

--- FIVEMILE BRANCH.g01 (geometry) --- (continued)

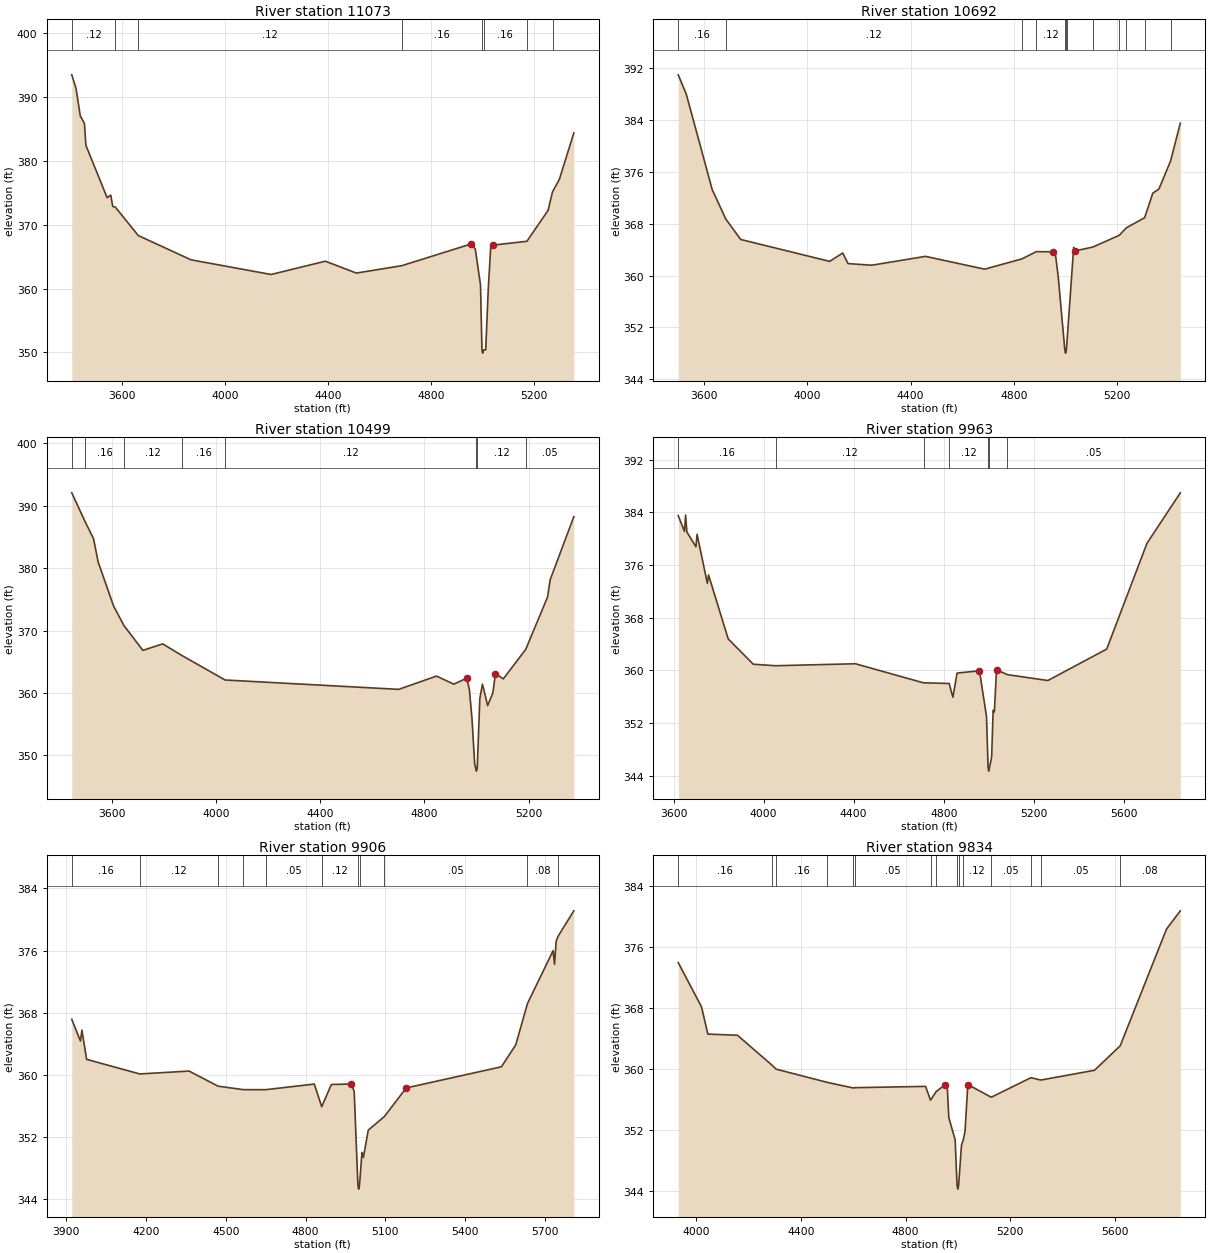
Type RM Length L Ch R = 1 ,11073   ,381,381,381
BEGIN DESCRIPTION:
FIVEMILE BRANCH 23.0
END DESCRIPTION:
XS GIS Cut Line= 5
      3740150.46     10650406.89      3740007.41     10650674.86
      3739872.73     10651052.44      3739829.33     10651851.05
      3739881.41     10652289.44
#Sta/Elev= 30
  3407.2  393.48  3423.8  391.35  3440.1  387.06  3456.3  385.86    3462  382.43
  3544.2  374.24  3558.3  374.63  3566.1  372.85  3575.7  372.77    3665   368.3
  3869.3   364.5  4179.7   362.2    4390  364.28  4510.2  362.42  4686.5  363.58
  4956.2     367  4971.2  366.18  4991.3  360.58    4997  350.38  4999.8  349.88
    5003  350.38  5011.5  350.38  5021.5  359.97  5031.6  366.94  5038.9   366.8
  5171.2   367.4  5253.2  372.24  5270.4  375.14  5296.9  377.09  5353.1  384.38
#Mann= 8 ,-1 , 0
  3407.2     .12       0  3575.7     .16       0    3665     .12       0
  4686.5     .16       0    4997     .07       0    5003     .16       0
  5171.2     .07       0  5270.4     .05       0
Bank Sta=4956.2,5038.9
XS Rating Curve= 0 ,0
Exp/Cntr=0.3,0.1

Type RM Length L Ch R = 1 ,10692   ,193,193,193
BEGIN DESCRIPTION:
Mapping XS 4b06a930
END DESCRIPTION:
XS GIS Cut Line= 4
       3739804.3     10650418.83      3739789.67     10650742.13
      3739586.97     10651839.27      3739680.27     10652334.72
#Sta/Elev= 30
  3500.5  390.94  3531.9  387.93    3632  373.25  3684.6  368.72  3742.1  365.57
  4086.6  362.19  4137.4  363.48  4157.7  361.85  4249.3   361.6  4457.6  362.96
  4686.5  360.99  4830.8  362.57  4886.6  363.69    4951  363.66  4961.1  363.12
  4971.3  359.86    4997  348.55  4999.8  348.05    5003  348.55  5006.7  350.58
  5031.2  364.34  5036.3   363.8  5104.9  364.39  5207.8  366.21    5235  367.36
  5305.9  368.92  5337.6  372.71  5361.2  373.33  5406.4  377.67    5444  383.49
#Mann= 12 ,-1 , 0
  3500.5     .16       0  3684.6     .12       0  4830.8     .16       0
  4886.6     .12       0    4997     .07       0    5003     .12       0
  5006.7     .16       0  5104.9     .05       0  5207.8     .07       0
    5235     .05       0  5305.9     .07       0  5406.4     .05       0
Bank Sta=4951,5036.3
XS Rating Curve= 0 ,0
Exp/Cntr=0.3,0.1

Type RM Length L Ch R = 1 ,10499   ,536,536,536
BEGIN DESCRIPTION:
Mapping XS e80f1be5
END DESCRIPTION:
XS GIS Cut Line= 5
      3739744.18     10650421.48      3739677.55     10650687.88
      3739564.57     10651113.21      3739408.32     10651864.08
      3739421.34     10652311.15
#Sta/Elev= 30
  3445.3  392.09  3497.9  387.35  3528.8  384.75    3547  380.96  3606.1  373.93
  3645.5  370.83  3718.5  366.83  3794.7  367.87  3869.7  365.98  4034.5  362.08
  4701.5  360.58  4846.7  362.71  4912.8  361.41  4963.1  362.38  4973.1  360.45
  4983.1  355.79  4993.1  348.66    4997  347.97  4999.8  347.47    5003  347.97
  5013.1  359.12  5023.1  361.42  5043.1  357.98  5063.1  360.02  5073.1  363.12
  5103.1  362.26  5189.2  366.98  5273.2  375.38  5283.2  378.15  5374.2  388.27
#Mann= 8 ,-1 , 0
  3445.3     .12       0  3497.9     .16       0  3645.5     .12       0
  3869.7     .16       0  4034.5     .12       0    4997     .07       0
    5003     .12       0  5189.2     .05       0
Bank Sta=4963.1,5073.1
XS Rating Curve= 0 ,0
Exp/Cntr=0.3,0.1

Type RM Length L Ch R = 1 ,9963    ,57,57,57
BEGIN DESCRIPTION:
Mapping XS ef591cb2
END DESCRIPTION:
XS GIS Cut Line= 3
      3739490.92     10650722.56      3739421.34      10651069.8
       3738709.7     10652805.53
#Sta/Elev= 30
  3620.7   383.5  3648.3  381.11  3653.4  383.59  3659.1  381.01  3699.3  378.77
  3704.4  380.66  3750.2   373.2  3755.3   374.5  3842.7  364.76    3954  360.92
  4053.2  360.69  4407.6  360.99  4710.1  358.09    4824  357.99  4840.7  355.91
  4859.3  359.57  4958.8  359.92  4990.1  352.95    4997  345.17  4999.8  344.67
    5003  345.17  5012.8  346.83  5019.4  353.91  5024.9  353.66  5034.4  360.08
  5082.1  359.34  5262.4  358.44  5523.9  363.22  5702.6  379.29  5850.8  386.97
#Mann= 7 ,-1 , 0
  3620.7     .16       0  4053.2     .12       0  4710.1     .05       0
    4824     .12       0    4997     .07       0    5003     .12       0
  5082.1     .05       0
Bank Sta=4958.8,5034.4
XS Rating Curve= 0 ,0
Exp/Cntr=0.3,0.1

Type RM Length L Ch R = 1 ,9906    ,72,72,72
BEGIN DESCRIPTION:
Mapping XS cb57b9a5
END DESCRIPTION:
XS GIS Cut Line= 3
      3739367.58       10650988.      3739006.47     10651932.43
      3738666.19     10652741.47
#Sta/Elev= 30
  3920.5  367.15  3953.2  364.35  3958.6  365.76  3976.4     362  4176.2  360.12
  4361.8  360.49  4470.8  358.55  4565.8   358.1  4651.7   358.1  4832.9  358.82
  4860.8   355.9  4897.1  358.76  4972.6  358.83    4983  357.87    4997   345.8
  4999.8   345.3    5003   345.8  5012.2  350.03  5017.6  349.38  5035.9  352.89
  5096.8  354.65  5178.7  358.32  5536.7  361.04  5590.9  363.87  5634.9  369.18
  5731.3  375.99  5736.7  374.23  5742.8   377.2  5749.8  377.83  5809.3  381.11
#Mann= 11 ,-1 , 0
  3920.5     .16       0  4176.2     .12       0  4470.8     .05       0
  4565.8     .12       0  4651.7     .05       0  4860.8     .12       0
    4997     .07       0    5003     .12       0  5096.8     .05       0
  5634.9     .08       0  5749.8     .05       0
Bank Sta=4972.6,5178.7
XS Rating Curve= 0 ,0
Exp/Cntr=0.3,0.1

Type RM Length L Ch R = 1 ,9834    ,176,176,176
BEGIN DESCRIPTION:
Mapping XS 56eb6e77
END DESCRIPTION:
XS GIS Cut Line= 2
      3739317.17     10650961.31      3738605.38     10652745.14
#Sta/Elev= 30
  3930.4  373.97  4019.5  368.17  4043.7   364.6  4156.9  364.45  4288.8  360.54
  4304.7  360.01  4501.2  358.27  4600.1  357.54  4605.2  357.58  4876.5  357.75
  4895.5  355.95  4917.1  357.07    4952  357.99    4960  357.42  4965.4  353.67
  4989.7  350.75    4997  344.79  4999.8  344.29    5003  344.79  5013.9  350.05
  5021.1  350.77  5027.4  351.84  5038.2  357.99  5127.8  356.33  5279.6  358.89
  5317.2  358.58  5522.7  359.86    5621  363.06  5798.2  378.36    5851  380.75
#Mann= 15 ,-1 , 0
  3930.4     .16       0  4288.8     .12       0  4304.7     .16       0
  4501.2     .05       0  4600.1     .08       0  4605.2     .05       0
  4895.5     .08       0  4917.1     .05       0    4997     .03       0
    5003     .05       0  5021.1     .12       0  5127.8     .05       0
  5279.6     .08       0  5317.2     .05       0    5621     .08       0
Bank Sta=4952,5038.2
XS Rating Curve= 0 ,0
Exp/Cntr=0.3,0.1

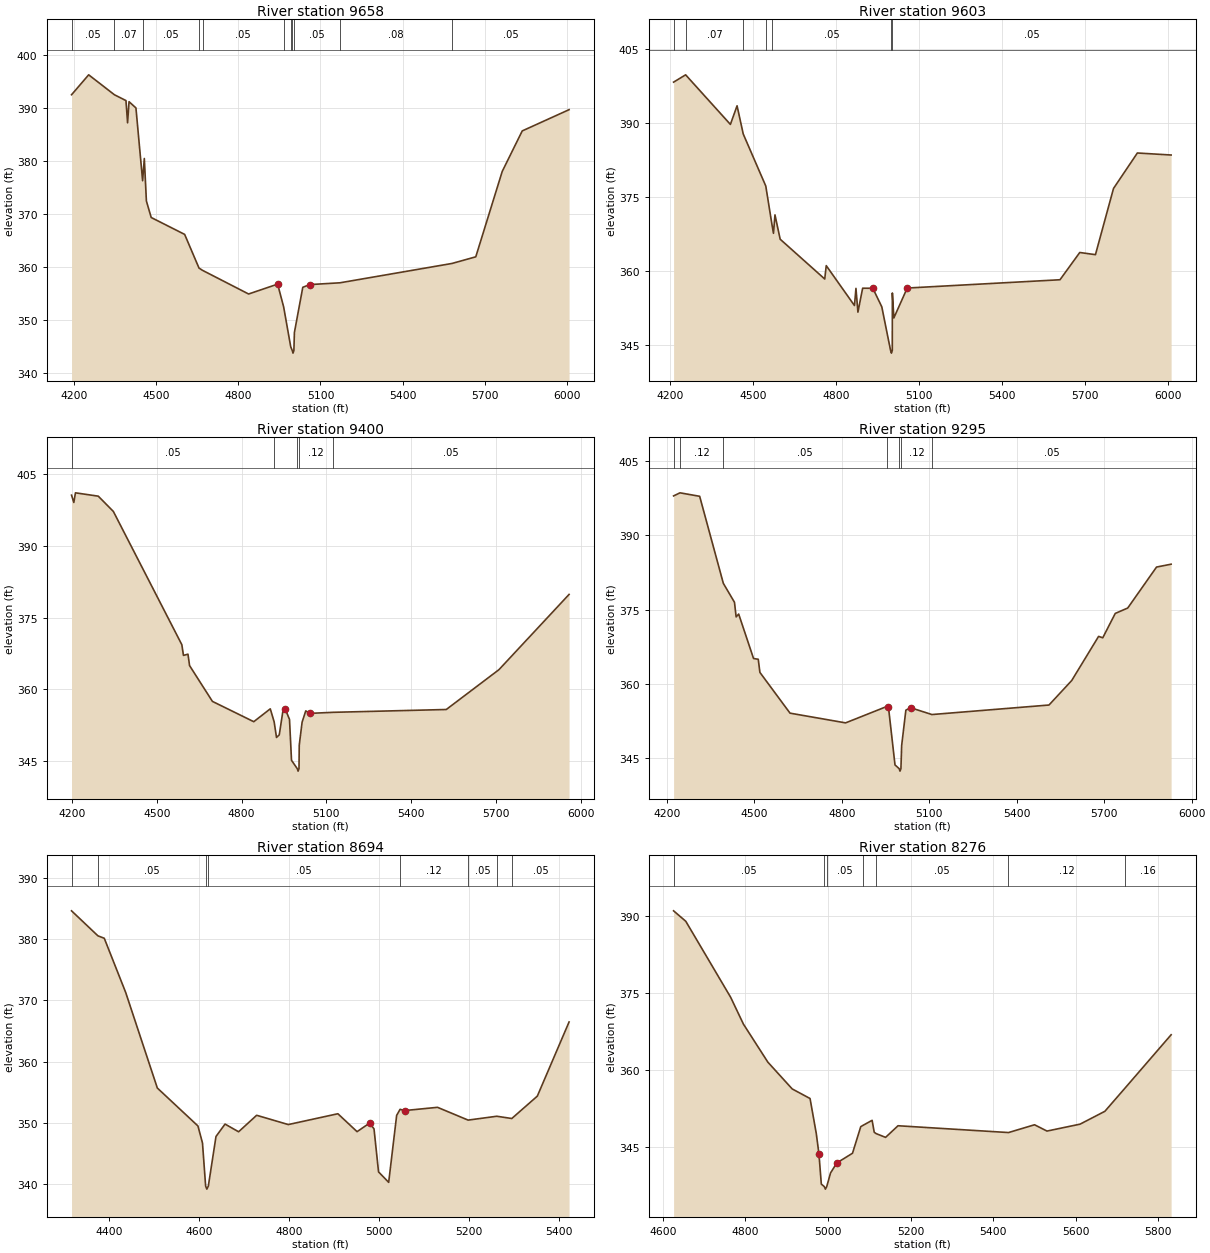
Type RM Length L Ch R = 1 ,9658    ,55,55,55
BEGIN DESCRIPTION:
Mapping XS d041fd07
END DESCRIPTION:
XS GIS Cut Line= 3
      3739035.08     10651143.54      3738561.97     10652436.99
      3738344.98      10652818.9
#Sta/Elev= 30
  4191.2  392.47  4253.8  396.22  4347.7  392.47  4389.9  391.37  4395.8  387.19
  4401.1  391.16  4426.3  389.99  4450.7  376.29  4456.9  380.47  4464.5  372.46
  4482.1  369.36  4604.2  366.18  4656.6  359.84  4669.6  359.41  4837.7  354.96
  4943.6  356.82  4965.5  352.56  4991.5  345.02    4997  344.33  4999.8  343.83
    5003  344.33  5004.9  347.72  5035.5  356.22  5060.7  356.73  5171.4  357.07
  5580.3  360.71  5667.1  361.96  5763.7  378.04  5836.7  385.66  6007.7  389.66
#Mann= 11 ,-1 , 0
  4191.2     .05       0  4347.7     .07       0  4450.7     .05       0
  4656.6     .08       0  4669.6     .05       0  4965.5     .08       0
  4991.5     .05       0    4997     .03       0    5003     .05       0
  5171.4     .08       0  5580.3     .05       0
Bank Sta=4943.6,5060.7
XS Rating Curve= 0 ,0
Exp/Cntr=0.3,0.1

Type RM Length L Ch R = 1 ,9603    ,203,203,203
BEGIN DESCRIPTION:
Mapping XS 7872e693
END DESCRIPTION:
XS GIS Cut Line= 3
      3739000.33     10651152.28      3738648.77     10652024.67
      3738155.21     10652726.05
#Sta/Elev= 30
  4212.6  398.21  4256.1  399.69  4417.9  389.65    4442  393.42  4464.3  387.71
  4545.8  377.17  4568.4  369.27  4573.6  367.59    4579  371.33  4597.8   366.4
  4758.9  358.34  4764.3  361.05  4866.3  352.97  4871.7  356.44  4878.8  351.63
  4895.9  356.48  4932.7  356.46  4965.1  352.71    4997  343.83  4999.8  343.33
    5003  343.83  5003.3  355.51  5008.7  350.46    5057  356.51  5609.2  358.19
  5680.6  363.71  5737.3  363.27  5802.6  376.68  5888.8  383.86  6010.8  383.45
#Mann= 7 ,-1 , 0
  4212.6     .05       0  4256.1     .07       0  4464.3     .05       0
  4545.8     .07       0  4568.4     .05       0    4997     .03       0
    5003     .05       0
Bank Sta=4932.7,5057
XS Rating Curve= 0 ,0
Exp/Cntr=0.3,0.1

Type RM Length L Ch R = 1 ,9400    ,105,105,105
BEGIN DESCRIPTION:
Mapping XS 12504e11
END DESCRIPTION:
XS GIS Cut Line= 3
      3738909.19     10651139.25      3738431.76     10651981.26
      3737967.36     10652623.62
#Sta/Elev= 30
  4198.1  400.65  4206.2  399.12  4211.9  401.14  4292.7  400.44  4346.1  397.24
  4588.4  369.35  4594.2  367.11  4610.1  367.36  4615.8  364.97  4696.6  357.48
  4842.9  353.23  4901.4  355.92  4915.1  353.19  4923.4  349.93  4933.2  350.48
  4946.4  355.59  4954.8   355.8  4969.4  353.71  4976.5  345.15    4997  343.38
  4999.8  342.88    5003  343.38  5003.9  348.32    5014  353.13  5026.9  355.49
  5041.4  354.97  5123.4  355.19  5524.2  355.78  5710.6  364.12  5958.7  379.87
#Mann= 5 ,-1 , 0
  4198.1     .05       0  4915.1     .12       0    4997     .07       0
    5003     .12       0  5123.4     .05       0
Bank Sta=4954.8,5041.4
XS Rating Curve= 0 ,0
Exp/Cntr=0.3,0.1

Type RM Length L Ch R = 1 ,9295    ,601,601,601
BEGIN DESCRIPTION:
Mapping XS 29b0e4d0
END DESCRIPTION:
XS GIS Cut Line= 3
      3738796.36      10651104.5      3738305.89     10651998.62
      3737858.84     10652519.46
#Sta/Elev= 30
  4223.4  397.95  4245.4  398.57  4312.8  397.87    4394  380.31  4432.2   376.5
  4437.9  373.55  4446.6  374.12  4497.6  365.16  4513.7  365.01  4519.4  362.36
  4622.7  354.14  4813.3  352.18  4953.9  355.47  4960.2   355.4  4982.7   343.7
    4997  342.95  4999.8  342.45    5003  342.95  5005.5   347.6  5019.9  354.74
    5036  355.24  5109.3  353.86  5510.8  355.78  5588.7  360.72  5680.9  369.62
  5695.2  369.34    5738  374.25  5780.8  375.34  5879.6   383.6  5929.6  384.18
#Mann= 7 ,-1 , 0
  4223.4     .05       0  4245.4     .12       0    4394     .05       0
  4953.9     .12       0    4997     .07       0    5003     .12       0
  5109.3     .05       0
Bank Sta=4960.2,5036
XS Rating Curve= 0 ,0
Exp/Cntr=0.3,0.1

Type RM Length L Ch R = 1 ,8694    ,418,418,418
BEGIN DESCRIPTION:
FIVEMILE BRANCH 18.0
END DESCRIPTION:
XS GIS Cut Line= 3
      3737949.61     10650960.16      3737899.61     10651660.19
      3737849.61     10652060.16
#Sta/Elev= 30
  4317.5  384.66  4376.1  380.57  4390.2  380.17  4437.8   371.3    4508  355.68
  4598.2  349.47  4608.3  346.69  4615.3  339.64    4618  339.14  4621.3  339.64
  4638.3  347.75  4658.4  349.78  4688.5  348.52  4728.6  351.22  4798.8   349.7
    4909  351.47  4951.6  348.54  4979.2  349.93  4989.2  349.01  4999.3  341.96
  5021.8  340.25  5039.5   351.2  5047.1  352.19  5057.1  351.99  5130.2  352.52
  5198.2  350.43  5261.9  351.06  5295.2  350.69  5351.9  354.35  5422.4  366.48
#Mann= 8 ,-1 , 0
  4317.5     .12       0  4376.1     .05       0  4615.3     .03       0
  4621.3     .05       0  5047.1     .12       0  5198.2     .05       0
  5261.9     .16       0  5295.2     .05       0
Bank Sta=4979.2,5057.1
XS Rating Curve= 0 ,0
Exp/Cntr=0.3,0.1

Type RM Length L Ch R = 1 ,8276    ,531,531,531
BEGIN DESCRIPTION:
FIVEMILE BRANCH 17.0
END DESCRIPTION:
XS GIS Cut Line= 3
       3737899.6     10650960.21      3737699.61     10651310.19
      3737649.61     10652110.24
#Sta/Elev= 30
  4626.1  391.06  4655.6  389.02  4764.3  374.17  4795.2  368.93  4854.3  361.51
  4913.3  356.27  4956.5   354.4  4971.6  347.56  4978.1  343.53  4983.8  337.68
  4990.9   337.2  4993.7   336.7  4996.9   337.2  5006.2  339.87  5021.3  341.81
  5059.3  343.71  5079.3   348.9  5084.6  349.15  5106.8  350.14  5111.9  347.81
  5116.4  347.55  5139.4  346.81  5169.5  349.08    5437  347.75  5500.1  349.27
  5530.2  348.04  5610.3  349.39  5670.4   351.9  5718.4  356.36  5830.8  366.85
#Mann= 7 ,-1 , 0
  4626.1     .05       0  4990.9     .03       0  4996.9     .05       0
  5084.6     .08       0  5116.4     .05       0    5437     .12       0
  5718.4     .16       0
Bank Sta=4978.1,5021.3
XS Rating Curve= 0 ,0
Exp/Cntr=0.3,0.1

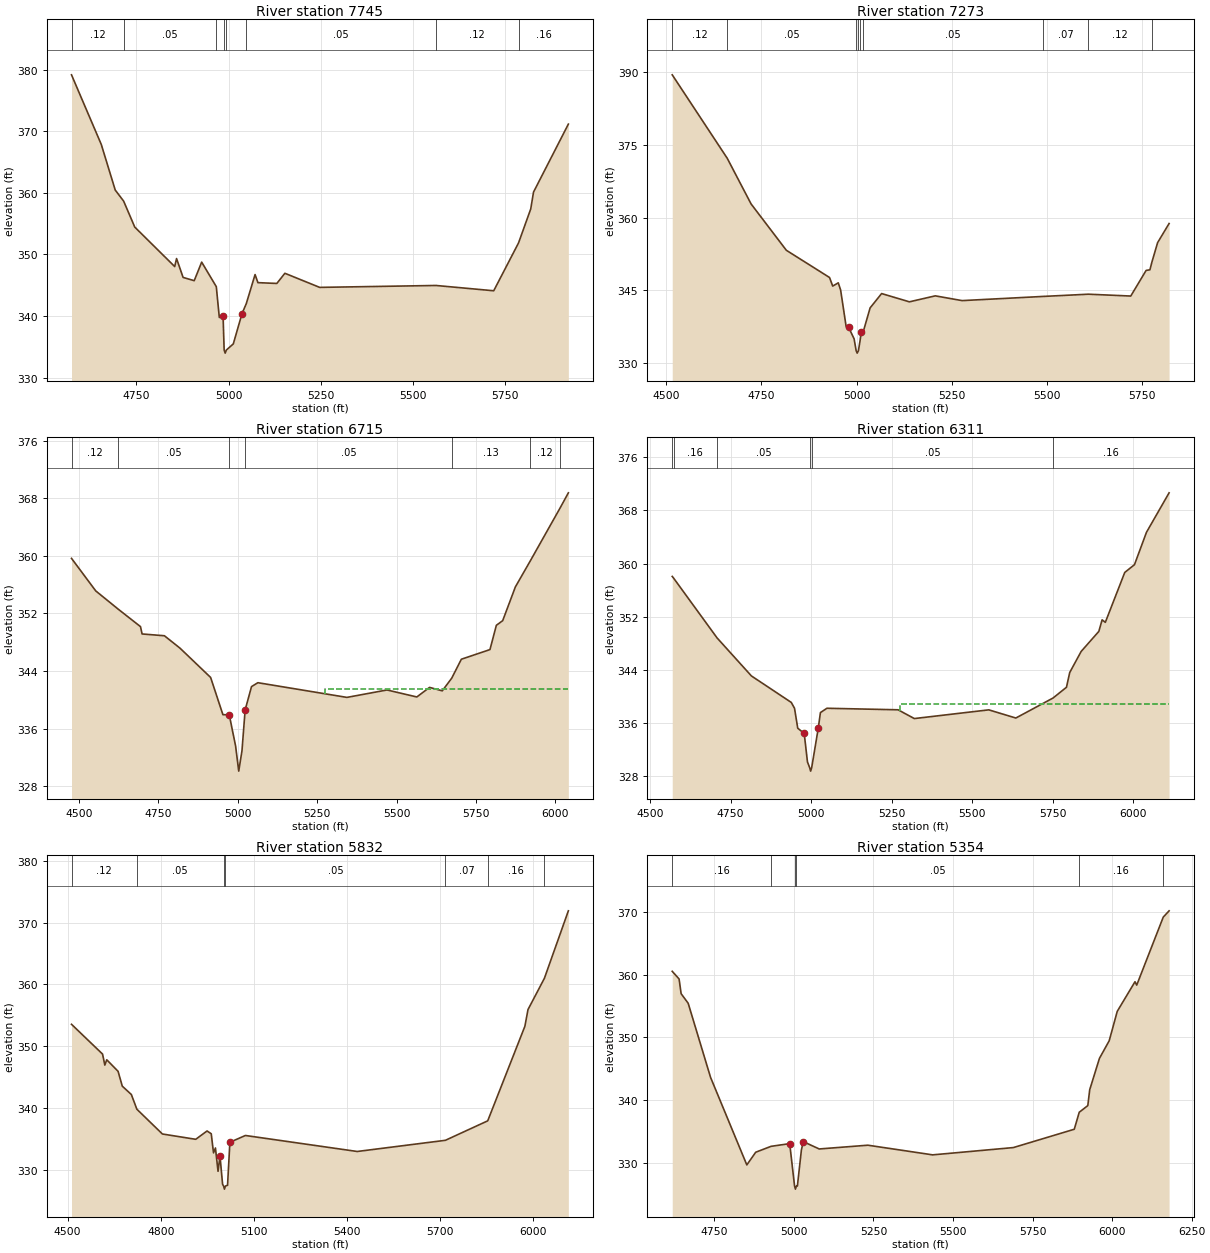
Type RM Length L Ch R = 1 ,7745    ,472,472,472
BEGIN DESCRIPTION:
FIVEMILE BRANCH 16.0
END DESCRIPTION:
XS GIS Cut Line= 3
       3737349.6     10650910.14      3737399.61     10651310.19
      3736899.59     10652110.22
#Sta/Elev= 30
  4574.3  379.14    4655  367.84  4692.8  360.44  4715.6  358.64  4745.7  354.43
    4854  348.02    4859  349.32  4876.7  346.26  4906.9  345.73  4927.1  348.74
  4966.7  344.76  4974.9  339.76  4985.1  339.97    4988  334.47  4990.8  333.97
    4994  334.47  5012.8  335.47  5036.4  340.38    5048     342  5071.8  346.72
  5079.5  345.41  5130.8  345.28  5152.6  346.93  5246.9  344.64  5562.2  344.95
  5718.6  344.09  5785.9  351.86  5818.9  357.37  5826.5  360.11  5920.9  371.14
#Mann= 8 ,-1 , 0
  4574.3     .12       0  4715.6     .05       0  4966.7     .16       0
    4988     .07       0    4994     .16       0    5048     .05       0
  5562.2     .12       0  5785.9     .16       0
Bank Sta=4985.1,5036.4
XS Rating Curve= 0 ,0
Exp/Cntr=0.3,0.1

Type RM Length L Ch R = 1 ,7273    ,558,558,558
BEGIN DESCRIPTION:
FIVEMILE BRANCH 15.0
END DESCRIPTION:
XS GIS Cut Line= 3
      3737299.61     10650810.19      3736999.61     10651210.19
      3736899.61     10652010.16
#Sta/Elev= 30
  4515.4  389.39    4660  372.21  4722.7  362.81  4815.4  353.27  4928.9  347.67
  4937.3   345.9  4951.9  346.57  4958.1  345.09  4972.7  337.51  4978.9  337.44
  4993.5  335.05  4998.9   332.6  5001.6   332.1  5004.9   332.6  5009.3  334.71
  5012.3  336.55  5017.7  336.55  5035.6  341.41  5065.8  344.36  5138.9  342.66
  5206.9  343.89  5277.4  342.91  5490.3  343.77  5609.5  344.23  5720.8  343.85
  5761.2  349.13  5771.2  349.25  5776.4  350.84  5791.4  354.84  5821.6  358.78
#Mann= 9 ,-1 , 0
  4515.4     .12       0    4660     .05       0  4998.9     .03       0
  5004.9     .05       0  5009.3     .16       0  5017.7     .05       0
  5490.3     .07       0  5609.5     .12       0  5776.4     .16       0
Bank Sta=4978.9,5012.3
XS Rating Curve= 0 ,0
Exp/Cntr=0.3,0.1

Type RM Length L Ch R = 1 ,6715    ,404,404,404
BEGIN DESCRIPTION:
FIVEMILE BRANCH 14.0
END DESCRIPTION:
XS GIS Cut Line= 3
      3736667.12     10650616.15      3736562.96     10651037.98
      3736505.75     10652166.73
#Sta/Elev= 30
  4476.5  359.65  4552.8  355.13  4623.7  352.59  4693.7  350.17  4698.8  349.15
  4769.1   348.9  4818.1  347.18  4914.6  343.11  4953.3  337.94  4973.3  337.92
  4993.3  333.58  5003.1   330.1  5013.3  332.92  5023.3  338.59  5043.4  341.84
  5063.4  342.38  5343.8  340.34    5470  341.37    5564   340.4  5604.1  341.73
  5644.1  341.25  5673.9  343.01  5704.2  345.64  5794.3  346.98  5814.4  350.35
  5834.4     351  5874.4  355.69  5921.6  359.32  6015.6  366.68  6041.2  368.75
#Mann= 7 ,-1 , 0
  4476.5     .12       0  4623.7     .05       0  4973.3     .05       0
  5023.3     .05       0  5673.9     .13       0  5921.6     .12       0
  6015.6     .13       0
#XS Ineff= 2 , 0
                         5273.29          341.45
Permanent Ineff=
       F       F
Bank Sta=4973.3,5023.3
XS Rating Curve= 0 ,0
Exp/Cntr=0.3,0.1

Type RM Length L Ch R = 1 ,6311    ,479,479,479
BEGIN DESCRIPTION:
FIVEMILE BRANCH 13.0
END DESCRIPTION:
XS GIS Cut Line= 2
       3736208.8     10650652.52      3736057.94     10652187.12
#Sta/Elev= 30
  4568.7  358.06    4573   357.8  4707.8  348.81  4814.3  343.09  4938.1   339.1
  4948.2  338.22  4958.2  335.22  4978.3  334.43  4988.4  330.14  4995.4  329.26
  4998.2  328.76  5001.4  329.26    5022  335.25  5028.6  337.57  5048.7  338.22
  5269.7  337.99    5320  336.67  5551.1  337.98  5635.1  336.75  5750.5  339.76
  5792.2  341.38  5802.3   343.6  5837.8  346.77  5892.7  349.79  5902.8  351.53
  5912.8  351.15  5973.1  358.66  6003.3  359.83  6040.5   364.7  6110.7  370.64
#Mann= 6 ,-1 , 0
  4568.7     .12       0    4573     .16       0  4707.8     .05       0
  4995.4     .03       0  5001.4     .05       0  5750.5     .16       0
#XS Ineff= 2 , 0
                         5274.43          338.92
Permanent Ineff=
       F       F
Bank Sta=4978.3,5022
XS Rating Curve= 0 ,0
Exp/Cntr=0.3,0.1

Type RM Length L Ch R = 1 ,5832    ,478,478,478
BEGIN DESCRIPTION:
FIVEMILE BRANCH 12.0
END DESCRIPTION:
XS GIS Cut Line= 3
      3735999.61     10650610.19      3735699.61     10651010.19
      3735699.61      10652110.2
#Sta/Elev= 30
  4512.7  353.53  4612.7  348.71    4620  346.93  4626.2  347.79  4662.7  345.92
  4676.2  343.52  4705.4  342.17  4723.2  339.79  4805.4  335.78  4912.7  334.92
  4949.2  336.27  4962.7  335.82    4970  332.72  4976.2  333.52  4984.6  329.75
  4990.8  332.23  4999.2  327.66  5002.4  327.36  5005.2  326.86  5008.4  327.36
  5015.2  327.48  5022.7  334.44  5072.7  335.54  5432.7  332.95  5716.8  334.76
    5853  337.91  5972.7  353.21  5982.7  355.91  6035.5  360.97  6112.7  371.89
#Mann= 7 ,-1 , 0
  4512.7     .12       0  4723.2     .05       0  5002.4     .03       0
  5008.4     .05       0  5716.8     .07       0    5853     .16       0
  6035.5     .05       0
Bank Sta=4990.8,5022.7
XS Rating Curve= 0 ,0
Exp/Cntr=0.3,0.1

Type RM Length L Ch R = 1 ,5354    ,458,458,458
BEGIN DESCRIPTION:
FIVEMILE BRANCH 11.0
END DESCRIPTION:
XS GIS Cut Line= 3
      3734999.59     10650710.16      3735249.61     10651010.19
       3735649.6     10652110.17
#Sta/Elev= 30
  4617.9  360.51  4639.4  359.29  4645.9  356.94    4668  355.42  4738.3  343.61
  4852.2  329.66  4880.2  331.68  4928.4  332.62    4987  333.05  5002.2   326.3
  5004.9   325.8  5008.2   326.3  5011.1   326.3  5023.7  332.04  5029.7  333.37
  5079.6   332.2  5232.6   332.8  5436.1  331.26  5689.4  332.42    5881  335.34
  5896.6  338.05  5923.5  339.11  5929.5  341.64  5960.1  346.64  5990.7  349.44
    6016  354.13  6071.8  358.85  6077.2  358.31  6160.6  369.15  6178.9  370.15
#Mann= 6 ,-1 , 0
  4617.9     .16       0  4928.4     .05       0  5002.2     .03       0
  5008.2     .05       0  5896.6     .16       0  6160.6     .05       0
Bank Sta=4987,5029.7
XS Rating Curve= 0 ,0
Exp/Cntr=0.3,0.1

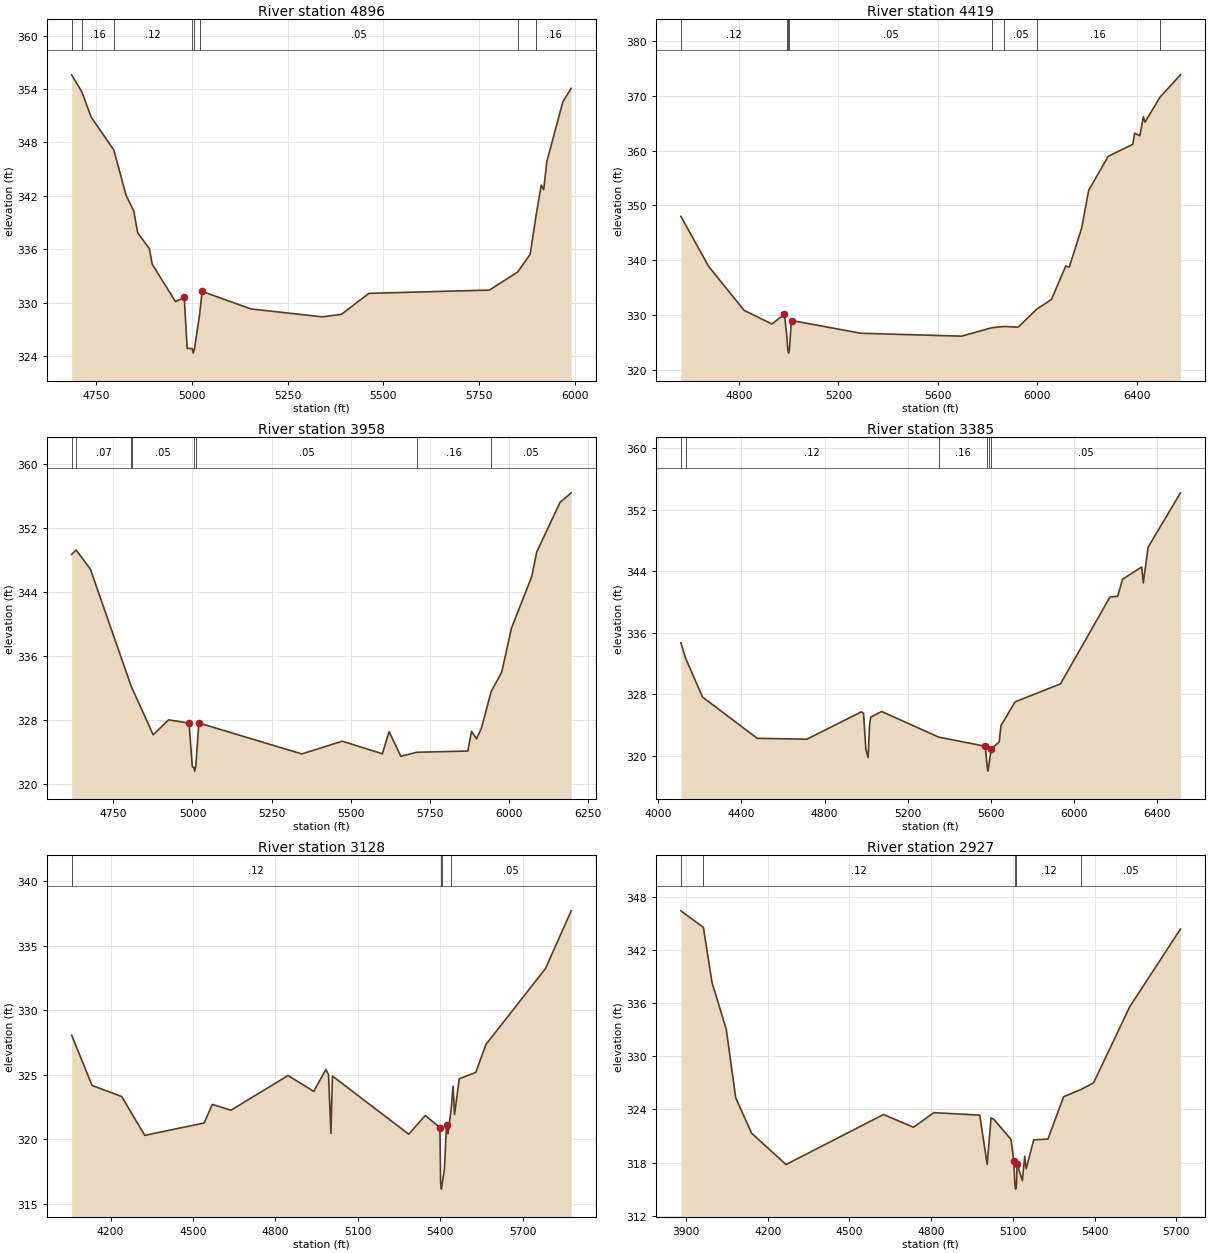
Type RM Length L Ch R = 1 ,4896    ,477,477,477
BEGIN DESCRIPTION:
FIVEMILE BRANCH 10.0
END DESCRIPTION:
XS GIS Cut Line= 3
      3734849.61     10650810.18      3734799.61     10651110.19
      3735399.58     10651910.15
#Sta/Elev= 30
  4686.1   355.6  4713.3  353.64  4736.8  350.87  4796.4  347.14    4828  342.08
  4848.3  340.29  4858.5  337.84  4888.9  336.07  4896.5   334.3  4957.3   330.1
  4980.1  330.58  4987.7  324.85  5000.8  324.81  5003.5  324.31  5006.8  324.81
  5019.9  328.56  5026.7  331.25  5153.8  329.28  5340.2  328.39  5390.2  328.67
  5462.1  331.03  5776.7   331.4  5850.5  333.43    5883  335.41  5898.5  339.77
  5912.1  343.21  5918.4  342.69  5926.7  345.86  5968.4  352.57  5990.2  354.08
#Mann= 8 ,-1 , 0
  4686.1     .12       0  4713.3     .16       0  4796.4     .12       0
  5000.8     .07       0  5006.8     .12       0  5019.9     .05       0
  5850.5     .07       0  5898.5     .16       0
Bank Sta=4980.1,5026.7
XS Rating Curve= 0 ,0
Exp/Cntr=0.3,0.1

Type RM Length L Ch R = 1 ,4419    ,461,461,461
BEGIN DESCRIPTION:
FIVEMILE BRANCH 9.0
END DESCRIPTION:
XS GIS Cut Line= 3
      3734149.63     10650810.22      3734349.61     10651210.19
      3735549.59     10652210.17
#Sta/Elev= 30
  4566.4  348.02  4678.2   338.9  4820.7   330.9  4932.5  328.42  4982.8  330.17
  4991.9  326.47  4996.6  323.61  4999.4  323.11  5002.6  323.61  5010.8  329.04
  5013.6  329.04  5290.2  326.73    5695   326.2  5816.5  327.73  5867.8  327.97
  5922.8  327.83  5997.4  331.11  6056.9  332.88  6114.2  338.98  6128.5  338.78
    6178  345.84  6206.6  352.76  6284.7  358.94  6383.6  361.14  6391.4  363.16
  6412.3   362.7  6426.6  366.18  6433.1  365.18  6493.6  369.74  6575.6   373.8
#Mann= 8 ,-1 , 0
  4566.4     .12       0  4991.9     .05       0  4996.6     .03       0
  5002.6     .05       0  5816.5     .07       0  5867.8     .05       0
  5997.4     .16       0  6493.6     .05       0
Bank Sta=4982.8,5013.6
XS Rating Curve= 0 ,0
Exp/Cntr=0.3,0.1

Type RM Length L Ch R = 1 ,3958    ,573,573,573
BEGIN DESCRIPTION:
FIVEMILE BRANCH 8.0
END DESCRIPTION:
XS GIS Cut Line= 3
      3733799.61     10650910.21      3733899.61     10651310.19
      3734499.62     10652310.21
#Sta/Elev= 30
  4618.3   348.7  4632.4  349.25  4677.5  346.85  4805.9  332.27  4808.5  332.03
    4876  326.14  4924.9  328.01  4989.4   327.6  4999.7  322.13  5004.4   322.1
  5007.1   321.6  5010.4   322.1  5020.3  327.62  5345.5  323.75  5473.7  325.34
  5600.1  323.77  5621.5  326.54  5658.4  323.46  5709.8  323.96  5870.2  324.11
  5881.9  326.58  5897.5  325.64    5913  326.95    5944  331.56  5977.1  333.96
  6008.2  339.49  6072.4  345.94  6087.9     349  6161.8  355.21  6196.8  356.39
#Mann= 8 ,-1 , 0
  4618.3     .12       0  4632.4     .07       0  4805.9     .12       0
  4808.5     .05       0  5004.4     .03       0  5010.4     .05       0
  5709.8     .16       0    5944     .05       0
Bank Sta=4989.4,5020.3
XS Rating Curve= 0 ,0
Exp/Cntr=0.3,0.1

Type RM Length L Ch R = 1 ,3385    ,257,257,257
BEGIN DESCRIPTION:
FIVEMILE BRANCH 7.0
END DESCRIPTION:
XS GIS Cut Line= 3
      3733125.46     10650506.71      3733354.63     10651308.81
      3733974.42     10652751.51
#Sta/Elev= 30
  4108.4   334.7  4131.2  332.69  4212.7  327.65    4476  322.29  4715.2  322.18
  4976.8  325.73  4987.6  325.54  4998.6  320.87  5009.4   319.8  5016.7  324.01
  5022.1  325.04  5074.7  325.78  5349.2  322.45  5572.9  321.26  5583.2  318.53
    5586  318.03  5589.2  318.53  5601.5  320.78  5601.9  320.88  5640.7  321.84
    5649  323.95  5716.8  327.03  5935.3  329.36    6174  340.66  6210.7  340.74
  6234.2  342.95  6326.3  344.55  6333.9  342.48  6357.4  347.13  6512.8  354.18
#Mann= 6 ,-1 , 0
  4108.4     .16       0  4131.2     .12       0  5349.2     .16       0
  5583.2     .07       0  5589.2     .16       0  5601.5     .05       0
Bank Sta=5572.9,5601.9
XS Rating Curve= 0 ,0
Exp/Cntr=0.3,0.1

Type RM Length L Ch R = 1 ,3128    ,201,201,201
BEGIN DESCRIPTION:
Mapping XS 4678429b
END DESCRIPTION:
XS GIS Cut Line= 3
      3732985.24     10650700.92      3733323.77     10651555.04
      3733666.87     10652386.79
#Sta/Elev= 30
  4058.3  328.07  4132.7  324.17  4240.4  323.31  4324.5   320.3  4540.6  321.26
  4570.4   322.7  4638.4  322.25  4845.9  324.94  4939.6  323.71  4983.7   325.4
  4993.4  325.02  5002.2  320.45  5007.6   324.9  5285.5  320.39  5345.7  321.84
    5399   320.9  5401.5  316.63  5404.3  316.13  5407.5  316.63  5415.3  317.65
  5422.9   321.1  5428.3  320.42  5439.2  322.21  5446.8  324.12  5452.2  321.93
  5469.4  324.69  5529.4  325.18  5566.8  327.36  5783.1  333.23  5876.8  337.71
#Mann= 4 ,-1 , 0
  4058.3     .12       0  5401.5     .07       0  5407.5     .12       0
  5439.2     .05       0
Bank Sta=5399,5422.9
XS Rating Curve= 0 ,0
Exp/Cntr=0.3,0.1

Type RM Length L Ch R = 1 ,2927    ,400,400,400
BEGIN DESCRIPTION:
FIVEMILE BRANCH 6.0
END DESCRIPTION:
XS GIS Cut Line= 3
      3732677.54     10650735.89      3733203.59     10651647.36
      3733427.23      10652396.3
#Sta/Elev= 30
  3881.4  346.44    3964  344.57  3995.8  338.34    4048  333.06  4082.6  325.32
  4140.9  321.32  4267.4  317.78  4625.3  323.43  4735.4  321.99    4810  323.64
  4978.5  323.36  5005.9   317.8  5020.2  323.05  5030.7  322.88  5093.3  320.61
  5103.7  318.18  5107.5   315.5  5110.3     315  5113.5   315.5  5115.7  317.87
    5135  315.95  5143.6  318.71  5148.9   317.3  5176.8  320.57    5229  320.65
  5286.6  325.44  5348.9  326.24  5396.4     327  5528.9  335.59  5715.4  344.38
#Mann= 5 ,-1 , 0
  3881.4     .16       0    3964     .12       0  5107.5     .07       0
  5113.5     .12       0  5348.9     .05       0
Bank Sta=5103.7,5115.7
XS Rating Curve= 0 ,0
Exp/Cntr=0.3,0.1

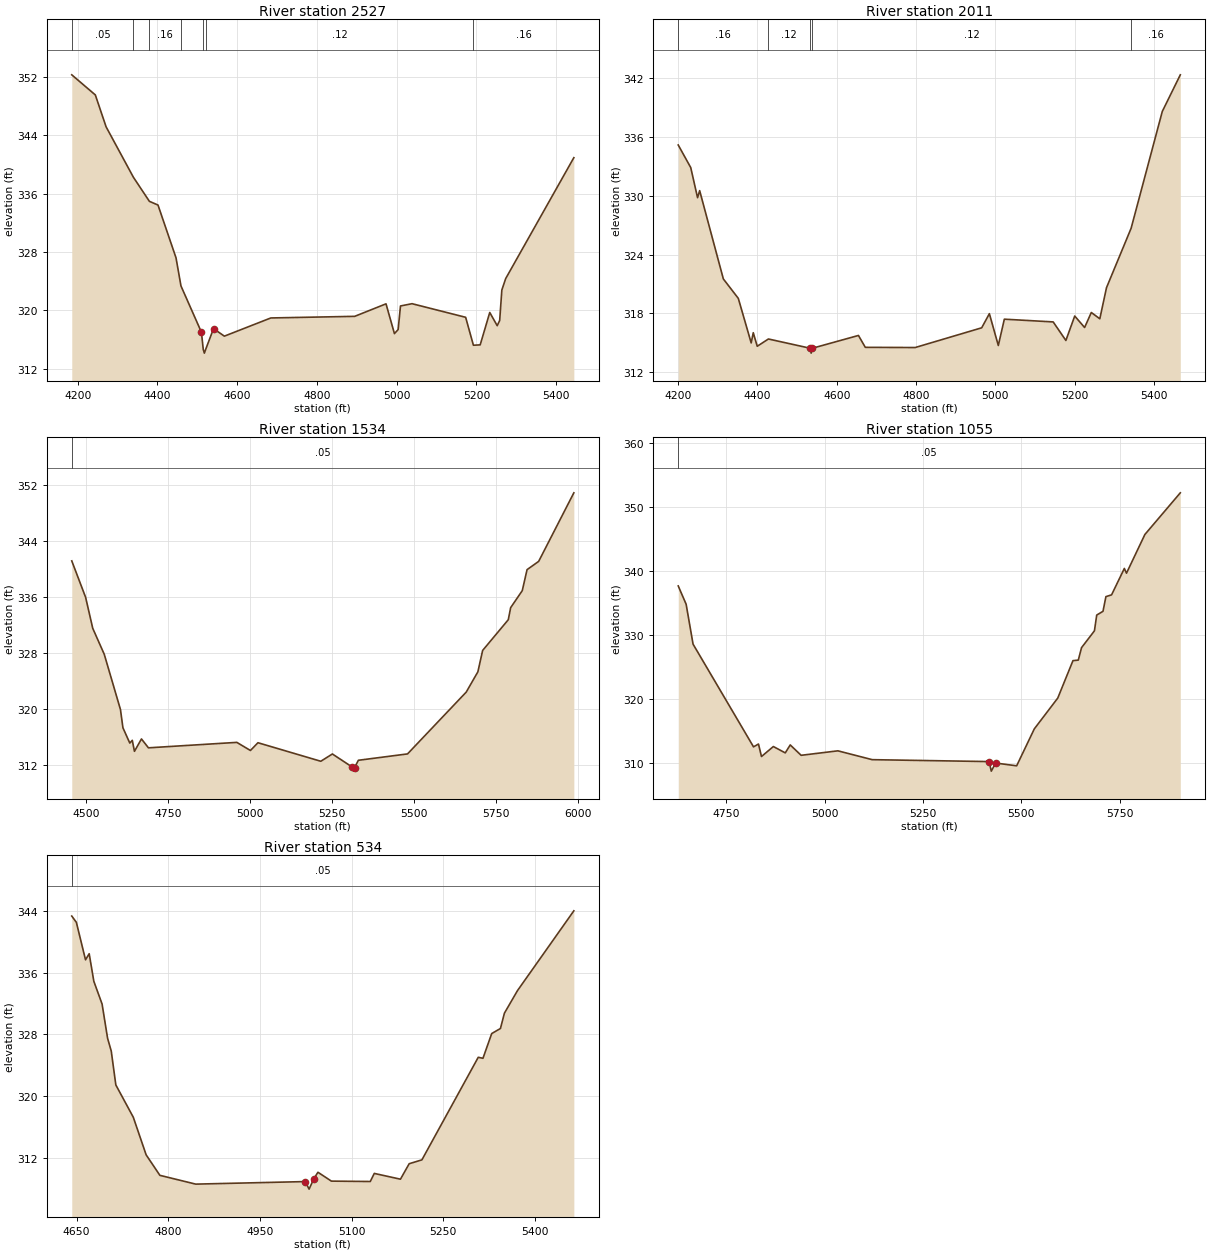
Type RM Length L Ch R = 1 ,2527    ,516,516,516
BEGIN DESCRIPTION:
FIVEMILE BRANCH 5.0
END DESCRIPTION:
XS GIS Cut Line= 3
      3732449.63     10651010.23      3732899.61     10651710.19
       3733049.6     10652110.17
#Sta/Elev= 30
  4185.1  352.23  4244.2  349.48  4271.2  345.12  4339.5  338.24  4379.8  334.93
  4401.4  334.42  4446.6   327.2    4459  323.36  4510.3  317.03  4514.9  314.67
  4517.7  314.17  4520.9  314.67  4540.7  317.52  4567.8  316.49  4684.4  318.98
  4894.7   319.2  4973.3  320.91  4994.4  316.84  5003.7  317.39  5009.6  320.62
  5038.6  320.93    5173  319.07  5192.5  315.25  5209.5   315.3  5233.5  319.73
  5252.2  317.92  5258.4  318.64  5263.8   322.8  5273.5  324.37  5444.4   340.9
#Mann= 7 ,-1 , 0
  4185.1     .05       0  4339.5      .1       0  4379.8     .16       0
    4459     .12       0  4514.9     .07       0  4520.9     .12       0
  5192.5     .16       0
Bank Sta=4510.3,4540.7
XS Rating Curve= 0 ,0
Exp/Cntr=0.3,0.1

Type RM Length L Ch R = 1 ,2011    ,477,477,477
BEGIN DESCRIPTION:
FIVEMILE BRANCH 4.0
END DESCRIPTION:
XS GIS Cut Line= 3
      3731749.59     10651760.18      3732549.61     10652010.19
      3732949.63      10652160.2
#Sta/Elev= 30
  4200.6  335.17  4232.1  332.87  4249.3   329.8  4254.6  330.52  4314.3  321.52
    4352  319.54  4384.5     315  4389.7  316.04  4399.7  314.66  4427.9   315.4
  4532.9  314.46  4535.6  313.96  4538.9  314.46  4654.8  315.76  4672.1  314.55
  4797.8  314.53  4965.4  316.54  4984.8  317.98  5007.3  314.74  5022.5  317.42
  5145.6  317.14  5177.6  315.25  5199.9  317.74  5224.8  316.57  5241.7   318.1
  5263.1  317.46    5280  320.63    5342  326.68  5420.6  338.59    5466  342.32
#Mann= 5 ,-1 , 0
  4200.6     .16       0  4427.9     .12       0  4532.9     .07       0
  4538.9     .12       0    5342     .16       0
Bank Sta=4532.9,4538.9
XS Rating Curve= 0 ,0
Exp/Cntr=0.3,0.1

Type RM Length L Ch R = 1 ,1534    ,479,479,479
BEGIN DESCRIPTION:
FIVEMILE BRANCH 3.0
END DESCRIPTION:
XS GIS Cut Line= 3
      3731749.64     10651860.22      3732149.61     10652210.19
      3732949.64     10652810.21
#Sta/Elev= 30
  4455.8  341.17    4498  335.97  4519.8  331.53  4554.9  327.82  4604.3  319.93
  4611.9  317.31  4632.8  315.13  4640.4  315.52    4647  313.95  4668.4  315.72
  4689.7  314.45  4959.3  315.23  5000.8  314.07  5023.7  315.18  5215.4  312.53
  5250.8  313.57  5309.1  311.77  5315.1  311.12  5318.4  311.62    5330  312.67
    5480  313.58  5659.1  322.42  5694.6  325.32  5709.1  328.37  5787.3  332.76
  5794.6  334.49    5830  336.92  5844.6  339.92    5880   341.1  5987.3   350.9
#Mann= 1 ,-1 , 0
  4455.8     .05       0
Bank Sta=5309.1,5318.4
XS Rating Curve= 0 ,0
Exp/Cntr=0.3,0.1

Type RM Length L Ch R = 1 ,1055    ,521,521,521
BEGIN DESCRIPTION:
FIVEMILE BRANCH 2.0
END DESCRIPTION:
XS GIS Cut Line= 3
      3731449.65     10652310.19      3731849.61     10652360.19
      3732199.62     10653160.21
#Sta/Elev= 30
  4627.8  337.66  4647.9   334.8  4665.5  328.57  4819.2  312.53  4831.8  312.97
  4839.4  311.02  4869.6  312.58  4899.9  311.59  4912.5  312.83  4940.2  311.21
  5033.6  311.91  5120.9  310.53    5418  310.23  5423.6  308.74  5434.7     310
  5488.1  309.57    5533  315.34  5592.6  320.15  5631.2  325.99  5644.8  326.08
    5653  328.02  5685.8  330.65  5691.6  333.11  5707.6   333.7    5715  335.99
  5729.4  336.27  5761.8  340.39  5767.3  339.65    5814  345.69  5904.1   352.2
#Mann= 1 ,-1 , 0
  4627.8     .05       0
Bank Sta=5418,5434.7
XS Rating Curve= 0 ,0
Exp/Cntr=0.3,0.1

Type RM Length L Ch R = 1 ,534     ,0,0,0
BEGIN DESCRIPTION:
FIVEMILE BRANCH 1.0
END DESCRIPTION:
XS GIS Cut Line= 3
       3731449.6     10652560.19      3731749.61     10652760.19
      3732099.58     10653060.16
#Sta/Elev= 30
  4642.1  343.38  4649.6  342.57  4664.6   337.7  4670.6  338.49  4678.2  334.91
  4691.7  331.96  4700.7  327.51  4706.7  325.85  4714.2  321.45  4742.8  317.25
  4763.8  312.37  4786.3  309.71  4844.9  308.57  5024.1   308.9  5030.4  307.92
  5038.3  309.29  5044.9  310.11  5066.9  308.96  5130.5  308.91  5137.1  309.96
  5179.9  309.21  5194.2  311.22    5215  311.72  5307.2  325.04  5314.9  324.91
  5329.2  328.12  5343.5  328.78    5350  330.77  5371.4   333.7  5463.6  344.06
#Mann= 1 ,-1 , 0
  4642.1     .05       0
Bank Sta=5024.1,5038.3
XS Rating Curve= 0 ,0
Exp/Cntr=0.3,0.1

Chan Stop Cuts=-1
Use User Specified Reach Order=0
Composite Channel Slope=5