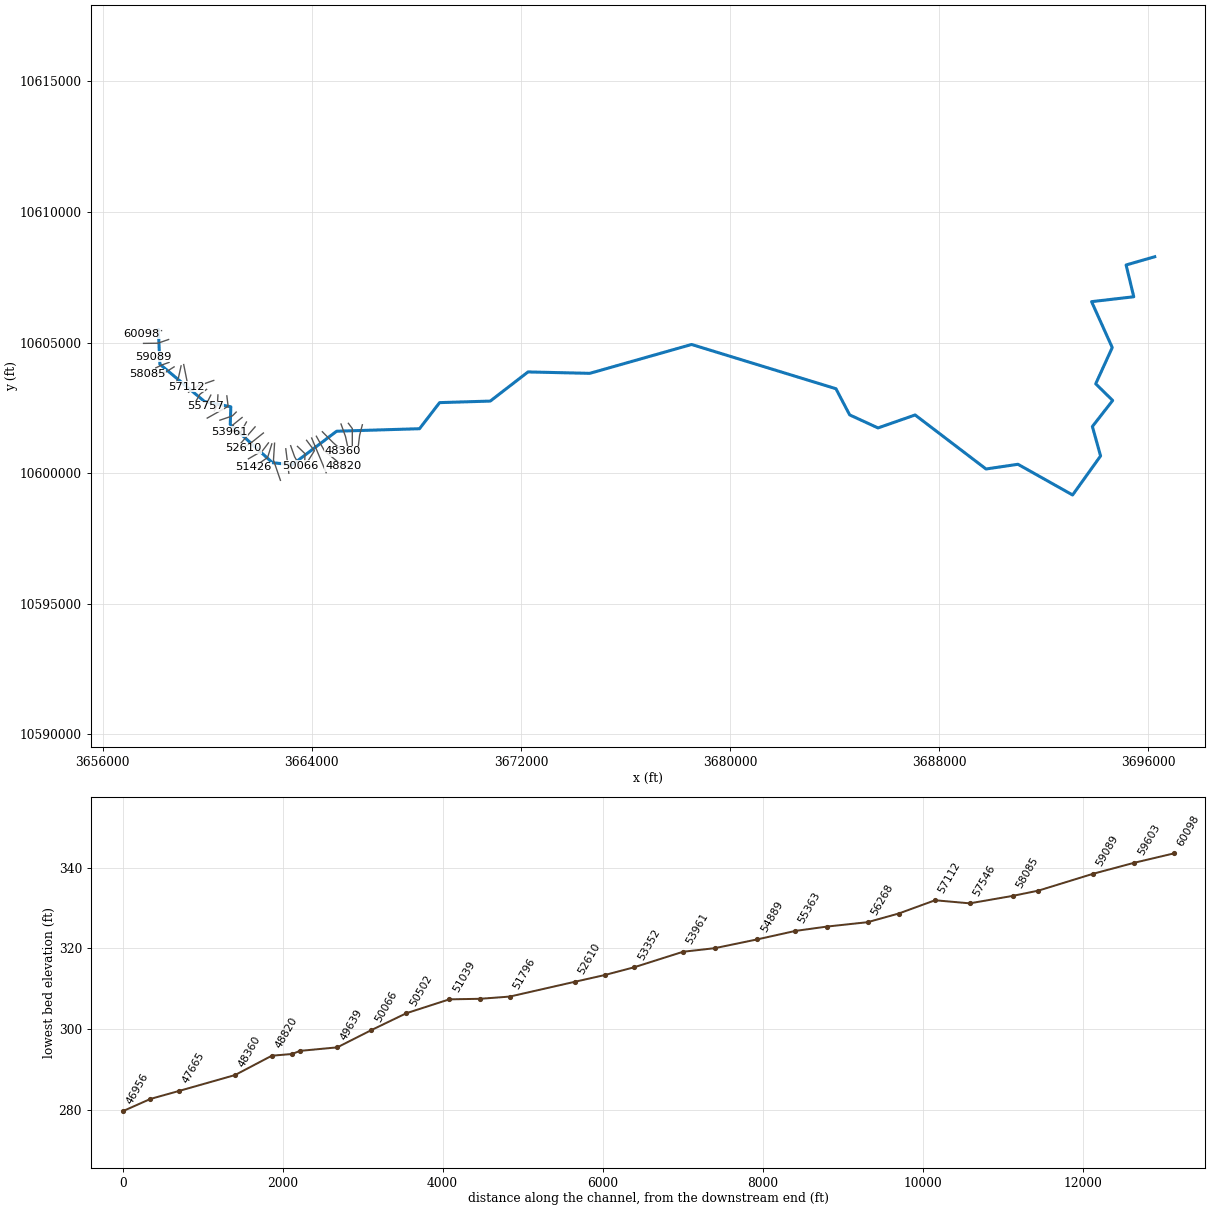
--- GASTON BRANCH.prj (project) ---

Proj Title=GASTON BRANCH Base Level Engineering
Current Plan=p01
Default Exp/Contr=0.3,0.1
English Units
Geom File=g01
Flow File=f01
Plan File=p01
Y Axis Title=Elevation
X Axis Title(PF)=Main Channel Distance
X Axis Title(XS)=Station
BEGIN DESCRIPTION:
GASTON BRANCH
END DESCRIPTION:
DSS File=dss
DSS Export Rating Curves= 0
DSS Export Rating Curve Sorted= 0
DSS Export Volume Flow Curves= 0
DXF OffsetX= 0
DXF OffsetY= 0
DXF ScaleX= 1
DXF ScaleY= 10

--- GASTON BRANCH.p01 (plan) ---

Plan Title=Multiple Run
Program Version=4.10
Short Identifier=Multiple Run
Geom File=g01
Flow File=f01
Subcritical Flow
K Sum by GR= 0
Std Step Tol= 0.01
Critical Tol= 0.01
Num of Std Step Trials= 20
Max Error Tol= 0.3
Flow Tol Ratio= 0.001
Split Flow NTrial= 30
Split Flow Tol= 0.02
Split Flow Ratio= 0.02
Log Output Level= 0
Friction Slope Method= 1
Unsteady Friction Slope Method= 2
Unsteady Bridges Friction Slope Method= 1
Parabolic Critical Depth
Global Vel Dist= 1 , 1 , 1
Global Log Level= 0
CheckData=True
Encroach Param=-1 ,0,0, 0
BEGIN DESCRIPTION:
Multiple Run
END DESCRIPTION:
Computation Interval=1HOUR
Output Interval=1HOUR
Run HTab= 0
Run UNet= 0
Run PostProcess= 0
Run WQNet= 0
UNET Theta= 1
UNET Theta Warmup= 1
UNET ZTol= 0.02
UNET ZSATol= 0.05
UNET MxIter= 20
UNET MaxInSteps= 0
UNET DtIC= 0
UNET DtMin= 0
UNET MaxCRTS= 20
UNET WFStab= 2
UNET SFStab= 1
UNET WFX= 1
UNET SFX= 1
UNET DSS MLevel= 4
UNET DZMax Abort= 100
UNET Convert EG Bridges= 0
UNET Use Existing IB Tables=-1
UNET Froude Reduction=False
UNET Froude Limit= 1
UNET Froude Power= 10
UNET Time Slicing=0,0, 5
UNET Junction Losses=0
Instantaneous Interval=1HOUR
DSS File=dss
Write IC File= 0
Write IC File at Sim End=0
Echo Input=False
Echo Parameters=False
Echo Output=False
Write Detailed= 0
WQ AD Non Conservative
WQ ULTIMATE=-1
WQ Max Comp Step=1HOUR
WQ Output Interval=15MIN
WQ Output Selected Increments= 0
WQ Output face flow=0
WQ Output face velocity=0
WQ Output face area=0
WQ Output face dispersion=0
WQ Output cell volume=0
WQ Output cell surface area=0
WQ Output cell continuity=0
WQ Output cumulative cell continuity=0
WQ Output face conc=0
WQ Output face dconc_dx=0
WQ Output face courant=0
WQ Output face peclet=0
WQ Output face adv mass=0
WQ Output face disp mass=0
WQ Output cell mass=0
WQ Output cell source sink temp=0
WQ Output cell source sink nsm=0
WQ Output MaxMinRange=-1
WQ Daily Max Min Mean=-1
WQ Daily Range=0
WQ Daily Time=0
WQ Create Restart=0
WQ Fixed Restart=0
WQ System Summary=0
WQ Use Fixed Temperature=0
Sorting and Armoring Iterations= 10
XS Update Threshold= 0.02
Hydraulics Update Threshold= 0.02
Energy Slope Method= 1
Volume Change Method= 0
XS Weighting Method= 0
Number of US Weighted Cross Sections= 1
Number of DS Weighted Cross Sections= 1
Upstream XS Weight=0.25
Main XS Weight=0.5
Downstream XS Weight=0.25
Number of DS XS's Weighted with US Boundary= 1
Upstream Boundary Weight= 1
Weight of XSs Associated with US Boundary= 0
Number of US XS's Weighted with DS Boundary= 1
Downstream Boundary Weight= 0.5
Weight of XSs Associated with DS Boundary= 0.5
Sediment Output Level= 4
Mass or Volume Output= 0
Output Increment Type= 1
Profile and TS Output Increment= 10
XS Output Flag= 0
XS Output Increment= 10
Disregard all LS=0
Disregard all Conn=0
Disregard all Breaches=0
Disregard all Pumps=0

--- GASTON BRANCH.f01 (steady flow) ---

Flow Title=Multiple
Program Version=4.10
Number of Profiles= 7
Profile Names=10-year,25-year,50-year,1pct_min,100-year,1pct_plu,500-year
River Rch & RM=GASTON BRANCH,Reach-1         ,60098
     348     461     553     488     660     893     944
River Rch & RM=GASTON BRANCH,Reach-1         ,59603
     751    1041    1285    1165    1576    2132    2383
River Rch & RM=GASTON BRANCH,Reach-1         ,57546
     868    1205    1490    1351    1827    2471    2764
River Rch & RM=GASTON BRANCH,Reach-1         ,51796
    1168    1647    2057    1884    2548    3446    3930
River Rch & RM=GASTON BRANCH,Reach-1         ,50502
    1161    1632    2034    1859    2514    3399    3857
River Rch & RM=GASTON BRANCH,Reach-1         ,49076
    1379    1952    2444    2242    3032    4101    4692
River Rch & RM=GASTON BRANCH,Reach-1         ,46392
    1379    1952    2444    2242    3032    4101    4692
River Rch & RM=GASTON BRANCH,Reach-1         ,44386
    1752    2506    3160    2916    3944    5334    6178
River Rch & RM=GASTON BRANCH,Reach-1         ,43392
    1752    2506    3160    2916    3944    5334    6178
River Rch & RM=GASTON BRANCH,Reach-1         ,42023
    2173    3131    3966    3676    4971    6723    7852
River Rch & RM=GASTON BRANCH,Reach-1         ,35506
    2226    3203    4056    3756    5079    6869    8010
River Rch & RM=GASTON BRANCH,Reach-1         ,34276
    2903    4216    5370    4999    6760    9143   10772
River Rch & RM=GASTON BRANCH,Reach-1         ,33339
    2903    4216    5370    4999    6760    9143   10772
River Rch & RM=GASTON BRANCH,Reach-1         ,27329
    2927    4240    5391    5008    6773    9160   10748
River Rch & RM=GASTON BRANCH,Reach-1         ,23353
    4615    6767    8677    8122   10984   14854   17686
River Rch & RM=GASTON BRANCH,Reach-1         ,21755
    4615    6767    8677    8122   10984   14854   17686
River Rch & RM=GASTON BRANCH,Reach-1         ,17033
    4741    6942    8893    8314   11244   15206   18061
River Rch & RM=GASTON BRANCH,Reach-1         ,12029
    4679    6830    8730    8143   11012   14892   17606
River Rch & RM=GASTON BRANCH,Reach-1         ,3020
    4666    6798    8679    8085   10934   14787   17436
Boundary for River Rch & Prof#=GASTON BRANCH,Reach-1         , 1
Up Type= 0
Dn Type= 3
Dn Slope=0.002
Boundary for River Rch & Prof#=GASTON BRANCH,Reach-1         , 2
Up Type= 0
Dn Type= 3
Dn Slope=0.002
Boundary for River Rch & Prof#=GASTON BRANCH,Reach-1         , 3
Up Type= 0
Dn Type= 3
Dn Slope=0.002
Boundary for River Rch & Prof#=GASTON BRANCH,Reach-1         , 4
Up Type= 0
Dn Type= 3
Dn Slope=0.002
Boundary for River Rch & Prof#=GASTON BRANCH,Reach-1         , 5
Up Type= 0
Dn Type= 3
Dn Slope=0.002
Boundary for River Rch & Prof#=GASTON BRANCH,Reach-1         , 6
Up Type= 0
Dn Type= 3
Dn Slope=0.002
Boundary for River Rch & Prof#=GASTON BRANCH,Reach-1         , 7
Up Type= 0
Dn Type= 3
Dn Slope=0.002
DSS Import GetInterval= 0
DSS Import GetPeak= 0
DSS Import FillOption= 0

--- GASTON BRANCH.g01 (geometry) ---

Geom Title=Existing Conditions
Program Version=4.10

River Reach=GASTON BRANCH   ,Reach-1
Reach XY= 30
        3658129.       10605495.      3658187.75       10604174.
       3659896.5       10602744.      3660901.25       10602544.
       3660880.5       10601870.      3662495.25       10600402.
      3663248.25       10600323.      3664950.75       10601608.
        3668121.       10601704.       3668889.5       10602703.
        3670828.       10602762.        3672272.       10603878.
       3674634.5       10603824.      3678529.75       10604929.
      3684052.25       10603235.        3684576.       10602234.
      3685661.25       10601734.      3687081.25       10602230.
      3689793.25       10600162.       3691015.5       10600342.
      3693106.25       10599167.       3694176.5       10600661.
        3693863.       10601788.      3694639.75       10602785.
      3693989.75       10603424.        3694623.       10604811.
        3693832.       10606569.      3695445.75       10606756.
      3695153.25       10607973.      3696249.59     10608288.65

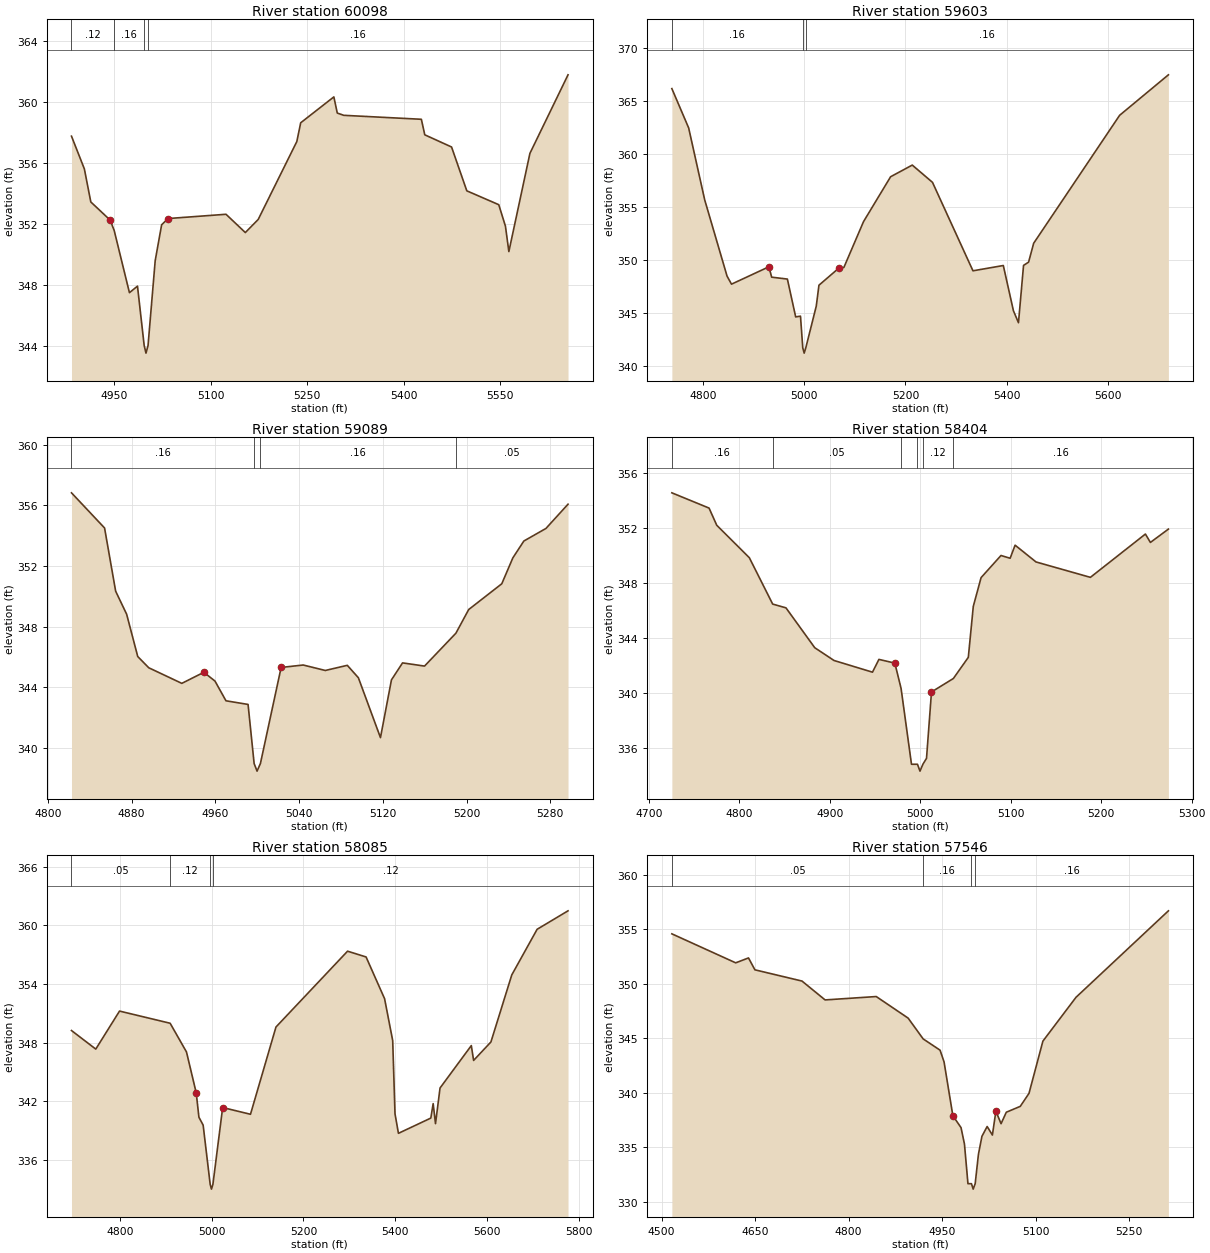
Type RM Length L Ch R = 1 ,60098   ,495,495,495
BEGIN DESCRIPTION:
GASTON BRANCH 96.0
END DESCRIPTION:
XS GIS Cut Line= 4
      3658249.56     10605460.19      3658149.61     10605460.19
       3657892.6     10605460.19      3657496.75     10605338.14
#Sta/Elev= 30
  4884.1  357.75  4904.1   355.6  4914.1  353.43  4944.1  352.24  4950.4351.5596
  4974.1  347.47  4986.6   347.9    4997     344  4999.8   343.5    5003     344
  5014.1  349.57  5024.1  351.93  5034.1  352.34  5124.1  352.62  5154.1  351.42
  5174.1  352.28  5234.1   357.4  5240.1  358.63  5291.6  360.33  5296.9  359.27
    5307  359.12  5427.5  358.86  5432.8  357.84  5474.4  357.04  5498.1  354.16
  5547.7  353.25  5558.1  351.84  5563.4  350.17  5596.1  356.62  5655.3  361.78
#Mann= 4 ,-1 , 0
  4884.1     .12       0  4950.4     .16       0    4997     .07       0
    5003     .16       0
Bank Sta=4944.1,5034.1
XS Rating Curve= 0 ,0
Exp/Cntr=0.3,0.1

Type RM Length L Ch R = 1 ,59603   ,514,514,514
BEGIN DESCRIPTION:
GASTON BRANCH 95.0
END DESCRIPTION:
XS GIS Cut Line= 3
      3658520.99     10605119.74        3658110.     10604977.47
      3657563.25     10604970.97
#Sta/Elev= 30
  4738.2  366.16  4771.4  362.45  4803.1  355.66  4847.3  348.46  4856.1   347.7
  4930.1  349.34  4935.5  348.36  4966.6  348.18    4983  344.61  4992.5  344.68
    4997  341.69  4999.8  341.19    5003  341.69  5023.7  345.63    5029   347.6
  5067.7  349.19  5078.3  349.28  5117.1   353.6  5170.7  357.84  5213.5  358.94
  5253.5  357.31  5333.5  348.96  5393.5  349.46  5413.5  345.19  5423.5  344.06
  5433.5  349.47  5443.5  349.78  5453.5  351.56  5623.5  363.64  5719.9  367.46
#Mann= 3 ,-1 , 0
  4738.2     .16       0    4997     .07       0    5003     .16       0
Bank Sta=4930.1,5067.7
XS Rating Curve= 0 ,0
Exp/Cntr=0.3,0.1

Type RM Length L Ch R = 1 ,59089   ,685,685,685
BEGIN DESCRIPTION:
GASTON BRANCH 94.0
END DESCRIPTION:
XS GIS Cut Line= 3
      3658399.63     10604510.18      3658249.61     10604560.19
      3657949.58     10604460.18
#Sta/Elev= 30
  4822.5  356.83  4854.1  354.51  4864.7  350.34  4875.2  348.82  4885.8  346.03
  4896.3  345.29  4927.9  344.26    4949  344.99  4959.6  344.41  4970.1  343.11
  4991.2  342.87    4997  338.97  4999.8  338.47    5003  338.97  5022.8  345.31
  5043.9  345.47    5065  345.11    5086  345.45  5096.6  344.63  5117.7  340.68
  5128.2  344.49  5138.8  345.61  5159.8   345.4  5189.8347.5712    5202  349.13
  5233.6  350.83  5244.2  352.54  5254.7  353.65  5275.8  354.48  5296.9  356.08
#Mann= 4 ,-1 , 0
  4822.5     .16       0    4997     .07       0    5003     .16       0
  5189.8     .05       0
Bank Sta=4949,5022.8
XS Rating Curve= 0 ,0
Exp/Cntr=0.3,0.1

Type RM Length L Ch R = 1 ,58404   ,319,319,319
BEGIN DESCRIPTION:
GASTON BRANCH 93.0
END DESCRIPTION:
XS GIS Cut Line= 3
      3658538.29     10604242.98      3658308.29     10604160.53
      3658031.06     10604034.91
#Sta/Elev= 30
  4725.6  354.55  4766.7  353.44  4775.2  352.19  4811.2  349.83    4837346.4546
  4851.7  346.18  4883.5  343.28  4904.8  342.35  4947.3   341.5  4954.4  342.43
    4972  342.16  4978.9340.3154  4990.4   334.8    4997   334.8  4999.8   334.3
    5003   334.8    5007  335.23  5012.5  340.06  5036.7 341.041  5053.2  342.58
  5058.7  346.29  5067.3  348.38  5089.3  349.99  5099.4  349.79  5104.9  350.74
    5128  349.52  5188.1   348.4  5248.9  351.55  5254.4  350.94  5274.3  351.91
#Mann= 6 ,-1 , 0
  4725.6     .16       0    4837     .05       0  4978.9     .12       0
    4997     .07       0    5003     .12       0  5036.7     .16       0
Bank Sta=4972,5012.5
XS Rating Curve= 0 ,0
Exp/Cntr=0.3,0.1

Type RM Length L Ch R = 1 ,58085   ,539,539,539
BEGIN DESCRIPTION:
GASTON BRANCH 92.0
END DESCRIPTION:
XS GIS Cut Line= 3
      3658731.84     10604071.93      3658419.34     10603874.01
      3657712.81     10603790.89
#Sta/Elev= 30
    4695  349.24  4747.9  347.34  4799.6  351.23  4909.8349.9861  4945.4  347.05
  4966.6  342.87  4972.5  340.37  4981.7  339.56    4997  333.51  4999.8  333.01
    5003  333.51  5024.2  341.36  5084.8  340.67  5140.3   349.6  5296.2  357.36
  5336.5  356.77  5376.8   352.5  5394.5  348.21  5399.5  340.72    5407  338.72
  5477.5  340.28  5482.6  341.76  5487.7  339.71  5497.6  343.36  5565.7   347.7
  5570.7  346.18  5608.4  348.07  5653.8  354.93    5709   359.6  5776.3  361.49
#Mann= 4 ,-1 , 0
    4695     .05       0  4909.8     .12       0    4997     .07       0
    5003     .12       0
Bank Sta=4966.6,5024.2
XS Rating Curve= 0 ,0
Exp/Cntr=0.3,0.1

Type RM Length L Ch R = 1 ,57546   ,434,434,434
BEGIN DESCRIPTION:
GASTON BRANCH 91.0
END DESCRIPTION:
XS GIS Cut Line= 3
       3658999.6     10604110.17      3658899.61     10603660.19
       3658749.6     10603360.16
#Sta/Elev= 30
  4516.5  354.57  4618.9  351.91  4639.4  352.36  4649.7  351.27  4725.2  350.24
  4762.3  348.51  4844.3  348.82  4895.5  346.84  4919.5344.9373  4946.7   343.9
  4953.1  342.82  4967.2  337.89  4980.3   336.8  4985.8  335.29  4991.4  331.66
    4997  331.66  4999.8  331.16    5003  331.66  5008.2  334.35  5013.8     336
  5022.2   336.9  5030.6  336.12  5036.2  338.31  5044.5  337.16  5052.9  338.21
  5075.3  338.75  5089.3  339.94  5111.6  344.73  5164.7  348.75  5312.9  356.68
#Mann= 4 ,-1 , 0
  4516.5     .05       0  4919.5     .16       0    4997     .07       0
    5003     .16       0
Bank Sta=4967.2,5036.2
XS Rating Curve= 0 ,0
Exp/Cntr=0.3,0.1

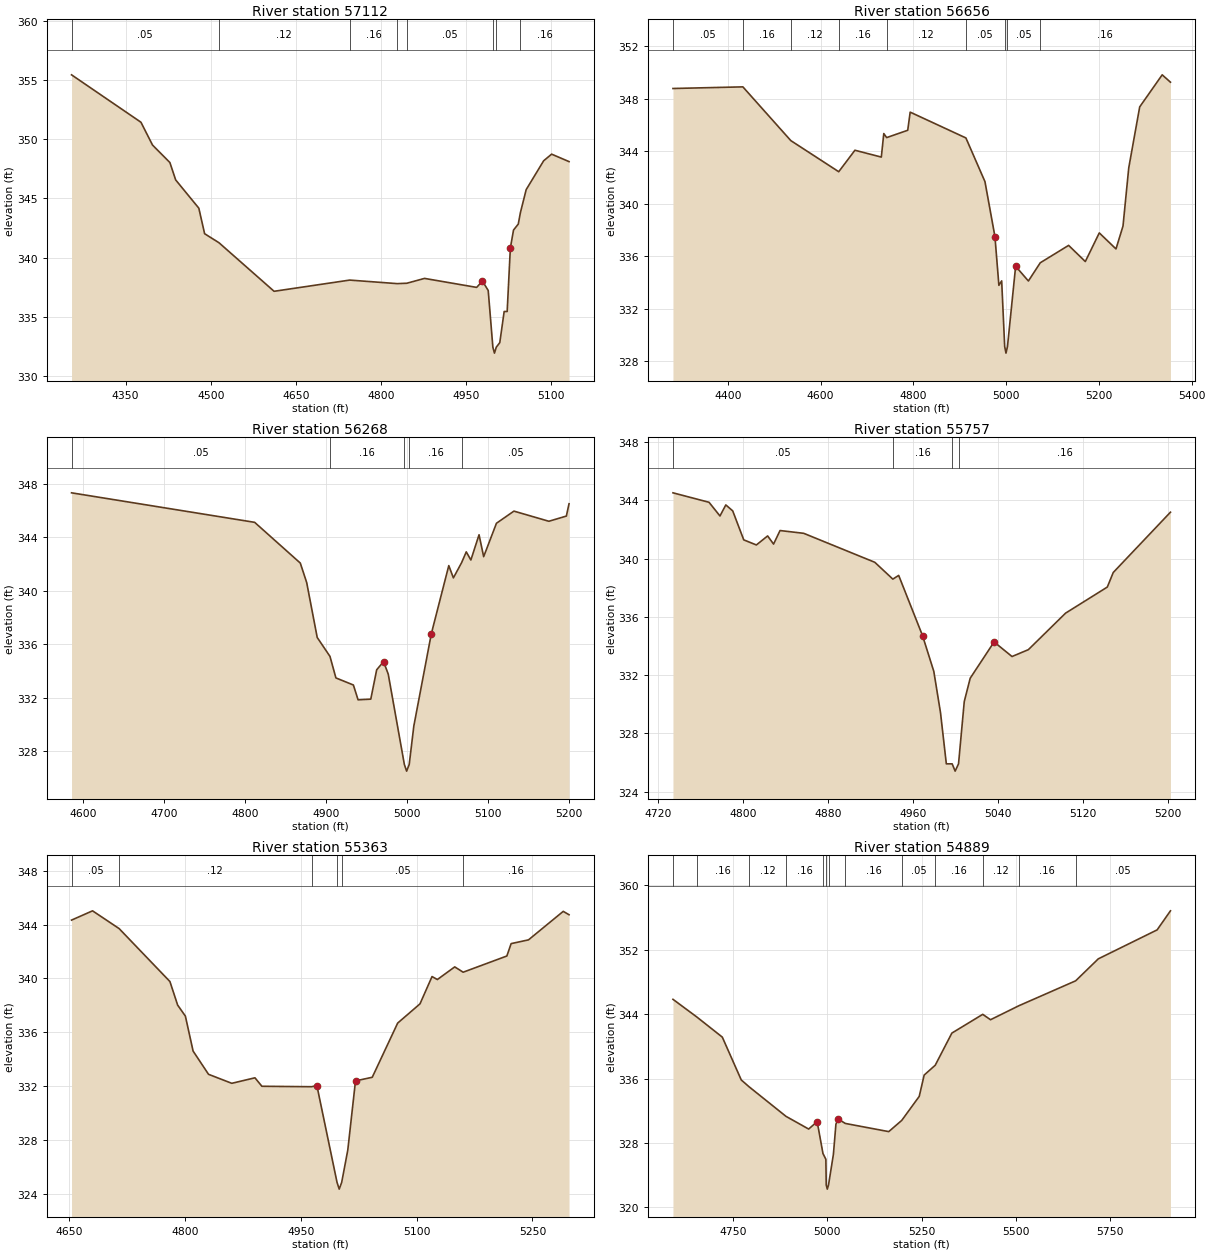
Type RM Length L Ch R = 1 ,57112   ,456,456,456
BEGIN DESCRIPTION:
GASTON BRANCH 90.0
END DESCRIPTION:
XS GIS Cut Line= 3
      3659099.62     10604160.15      3659249.61     10603410.19
      3659199.61      10603310.2
#Sta/Elev= 30
  4254.6  355.46  4376.9  351.45  4397.3  349.52  4427.9  348.04  4438.1  346.57
  4478.9  344.18  4489.1  342.02  4514.3341.2612  4611.5  337.15  4744.8338.0979
  4828.4337.7988  4845.4337.8312  4876.6  338.24  4968.4  337.48  4978.6  338.01
  4988.8  337.22    4997  332.42  4999.8  331.92    5003  332.42  5009.2  332.81
  5016.9  335.44  5022.2  335.44  5027.8  340.81  5033.4  342.33  5041.8  342.84
  5045.4343.7786  5055.7  345.75  5086.5  348.19  5100.5  348.75  5131.2  348.12
#Mann= 8 ,-1 , 0
  4254.6     .05       0  4514.3     .12       0  4744.8     .16       0
  4828.4     .12       0  4845.4     .05       0    4997     .03       0
    5003     .05       0  5045.4     .16       0
Bank Sta=4978.6,5027.8
XS Rating Curve= 0 ,0
Exp/Cntr=0.3,0.1

Type RM Length L Ch R = 1 ,56656   ,388,388,388
BEGIN DESCRIPTION:
GASTON BRANCH 89.0
END DESCRIPTION:
XS GIS Cut Line= 3
      3660248.35     10603552.87      3659649.43     10603344.55
      3659284.84     10603101.49
#Sta/Elev= 30
    4282  348.77  4432.7348.8936    4536344.8042  4639.3342.4357  4674.2  344.07
  4731.1  343.55  4736.4  345.34  4742.6345.0331    4788  345.59  4793.3  346.97
  4913.4345.0067  4954.5  341.68    4976   337.5  4984.5  333.79  4990.5  334.13
    4997  329.13  4999.8  328.63    5003  329.13  5020.6  335.24  5048.1  334.12
  5073.7335.5067  5134.8  336.83  5170.8   335.6  5200.9  337.78  5236.9  336.56
    5252   338.3  5264.4  342.73    5288  347.37  5336.5  349.81  5354.3  349.25
#Mann= 9 ,-1 , 0
    4282     .05       0  4432.7     .16       0    4536     .12       0
  4639.3     .16       0  4742.6     .12       0  4913.4     .05       0
    4997     .03       0    5003     .05       0  5073.7     .16       0
Bank Sta=4976,5020.6
XS Rating Curve= 0 ,0
Exp/Cntr=0.3,0.1

Type RM Length L Ch R = 1 ,56268   ,511,511,511
BEGIN DESCRIPTION:
GASTON BRANCH 88.0
END DESCRIPTION:
XS GIS Cut Line= 3
      3659974.96     10603210.01      3659723.22     10603027.71
      3659571.93     10602764.04
#Sta/Elev= 30
  4585.7  347.34    4812  345.13  4868.4  342.08  4876.3  340.62  4889.3  336.51
  4905.1335.0887  4912.4  333.48    4934  332.95  4939.8  331.84  4955.5  331.89
  4962.8  334.09  4971.3   334.7  4977.1  333.76    4997     327  4999.8   326.5
    5003     327  5008.7  329.88  5030.3  336.78  5051.9  341.89  5057.6  340.97
  5067.8342.1187  5073.5  342.92  5079.2  342.31  5089.3   344.2    5095  342.56
  5110.8  345.06  5132.4  345.97  5175.6  345.21  5197.2   345.6  5200.5  346.52
#Mann= 5 ,-1 , 0
  4585.7     .05       0  4905.1     .16       0    4997     .07       0
    5003     .16       0  5067.8     .05       0
Bank Sta=4971.3,5030.3
XS Rating Curve= 0 ,0
Exp/Cntr=0.3,0.1

Type RM Length L Ch R = 1 ,55757   ,394,394,394
BEGIN DESCRIPTION:
GASTON BRANCH 87.0
END DESCRIPTION:
XS GIS Cut Line= 2
      3660136.25     10602990.68       3659929.2     10602570.08
#Sta/Elev= 30
  4733.9  344.52  4767.9  343.87  4778.2  342.93  4783.7  343.69  4790.2  343.28
  4800.6  341.29  4812.5  340.94  4823.1  341.56  4828.7     341  4834.8  341.93
  4857.1  341.74  4924.1  339.75  4941.1338.5947  4946.6  338.85  4969.1  334.71
  4979.7  332.26    4986  329.43  4991.5  325.91    4997  325.91  4999.8  325.41
    5003  325.91  5008.4  330.19    5014  331.79  5036.5  334.28  5053.4  333.28
  5068.8  333.75  5103.9  336.26  5143.2  338.05  5148.8  339.05  5202.7  343.19
#Mann= 4 ,-1 , 0
  4733.9     .05       0  4941.1     .16       0    4997     .07       0
    5003     .16       0
Bank Sta=4969.1,5036.5
XS Rating Curve= 0 ,0
Exp/Cntr=0.3,0.1

Type RM Length L Ch R = 1 ,55363   ,474,474,474
BEGIN DESCRIPTION:
GASTON BRANCH 86.0
END DESCRIPTION:
XS GIS Cut Line= 3
      3660408.98     10602997.33      3660387.28     10602619.73
      3660270.07     10602380.97
#Sta/Elev= 30
  4653.2  344.34  4680.4  345.03  4714.8  343.71  4780.6  339.77  4790.6  338.02
  4800.6   337.2  4810.6   334.6  4830.6  332.87  4860.7   332.2  4890.7  332.61
  4899.7  331.98    4964331.9472  4970.9  332.03    4997  324.83  4999.8  324.33
    5003  324.83  5010.9  327.23  5020.9  332.38  5042.6  332.65  5075.5  336.68
  5104.4  338.11    5120  340.14  5126.9  339.92  5149.4  340.86  5160.3340.4642
  5216.9  341.67  5222.4  342.59  5244.9  342.87  5289.9  344.99  5297.4  344.74
#Mann= 6 ,-1 , 0
  4653.2     .05       0  4714.8     .12       0    4964     .05       0
    4997     .03       0    5003     .05       0  5160.3     .16       0
Bank Sta=4970.9,5020.9
XS Rating Curve= 0 ,0
Exp/Cntr=0.3,0.1

Type RM Length L Ch R = 1 ,54889   ,530,530,530
BEGIN DESCRIPTION:
GASTON BRANCH 85.0
END DESCRIPTION:
XS GIS Cut Line= 3
      3660749.61     10602960.18      3660799.61     10602560.19
      3659999.59     10602110.18
#Sta/Elev= 30
    4590  345.85  4653.3343.6524    4721  341.15  4771.4  335.82  4791.6334.9951
  4889.9331.3052  4950.3  329.72  4972.9  330.64  4988.3326.6773    4996  325.96
    4997  322.75  4999.8  322.25    5003  322.75    5016  326.57  5022.7  330.32
  5028.5  330.98  5047.5330.4178    5163   329.4  5197.5330.7951  5243.9  333.78
    5257  336.43  5286.4337.6539  5330.6  341.65  5412.5343.9795  5433.2  343.31
  5508.5  345.05  5659.3348.1483  5719.4  350.88  5875.6  354.48    5911  356.85
#Mann= 13 ,-1 , 0
    4590     .05       0  4653.3     .16       0  4791.6     .12       0
  4889.9     .16       0  4988.3     .12       0    4997     .07       0
    5003     .12       0  5047.5     .16       0  5197.5     .05       0
  5286.4     .16       0  5412.5     .12       0  5508.5     .16       0
  5659.3     .05       0
Bank Sta=4972.9,5028.5
XS Rating Curve= 0 ,0
Exp/Cntr=0.3,0.1

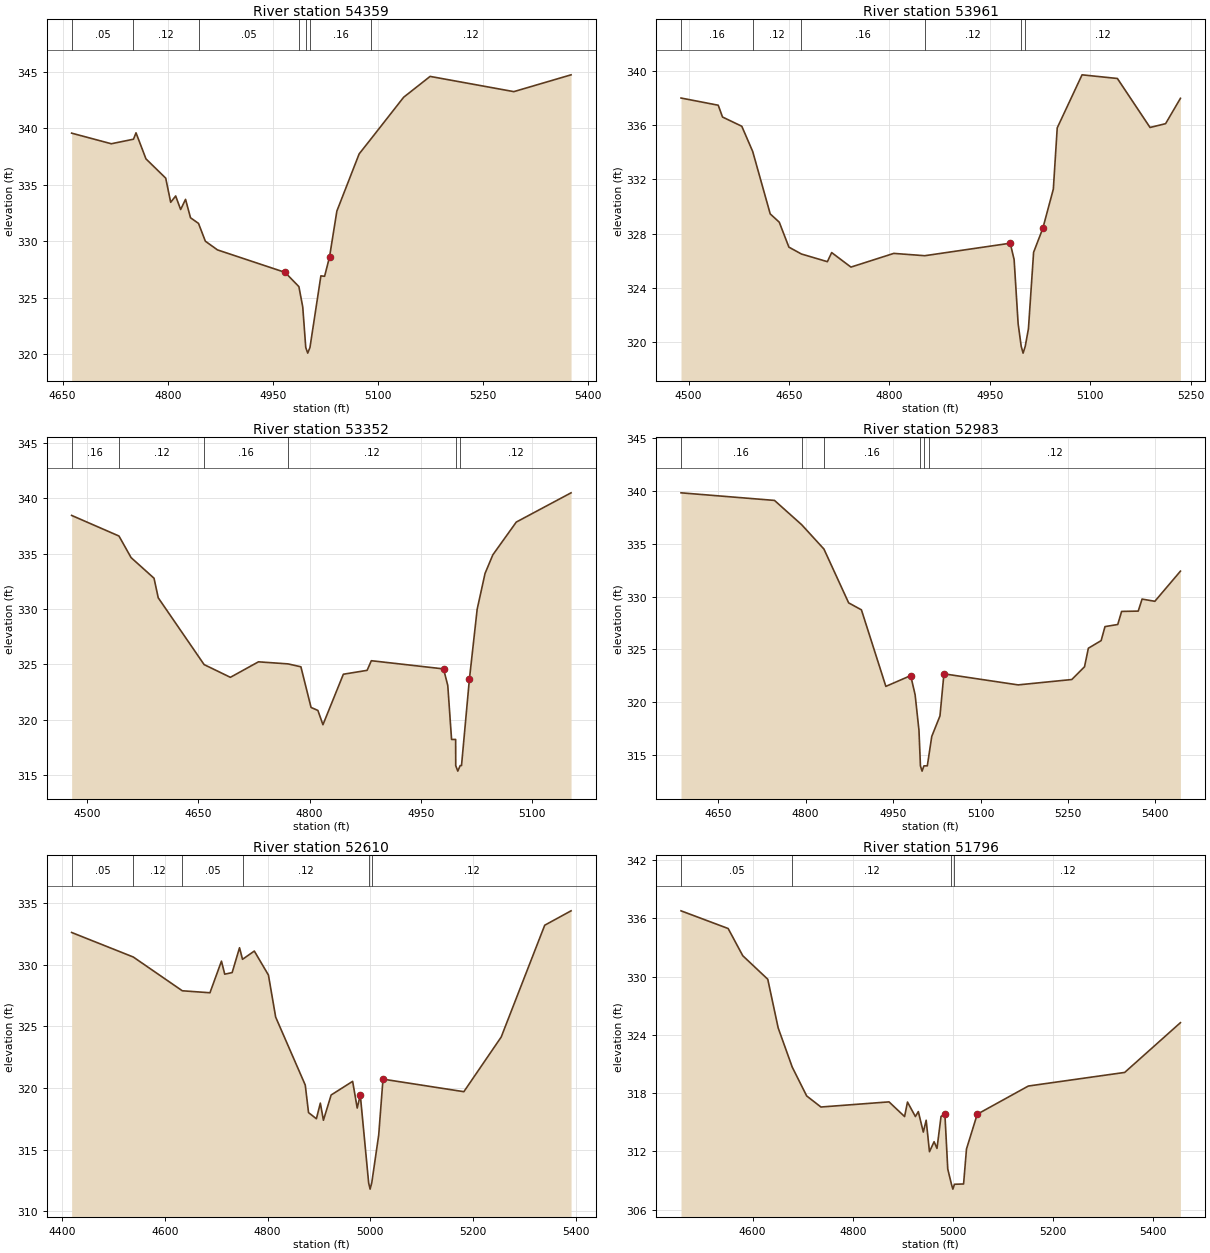
Type RM Length L Ch R = 1 ,54359   ,398,398,398
BEGIN DESCRIPTION:
GASTON BRANCH 84.0
END DESCRIPTION:
XS GIS Cut Line= 3
       3661107.8     10602341.98       3660960.2     10602194.38
      3660483.67     10602029.76
#Sta/Elev= 30
  4662.8  339.58  4719.4  338.64  4751.1339.0421  4754.7  339.61  4768.9   337.3
  4797.1  335.59  4804.2  333.45  4811.3  334.01  4818.4  332.81  4825.4  333.71
  4832.5  332.08  4843.9331.5796  4853.7     330    4871  329.23  4967.4  327.24
  4987.2325.9759  4992.7  324.17    4997  320.58  4999.8  320.08    5003  320.58
  5018.6  326.93  5023.9  326.89  5030.9   328.6  5041.4  332.67  5073.2  337.74
  5090.5339.0998  5136.7  342.76  5174.5  344.61    5294  343.26  5375.7  344.75
#Mann= 7 ,-1 , 0
  4662.8     .05       0  4751.1     .12       0  4843.9     .05       0
  4987.2     .16       0    4997     .07       0    5003     .16       0
  5090.5     .12       0
Bank Sta=4967.4,5030.9
XS Rating Curve= 0 ,0
Exp/Cntr=0.3,0.1

Type RM Length L Ch R = 1 ,53961   ,609,609,609
BEGIN DESCRIPTION:
GASTON BRANCH 83.0
END DESCRIPTION:
XS GIS Cut Line= 3
      3661333.44      10602133.6      3660999.26     10601864.52
      3660838.65     10601591.04
#Sta/Elev= 30
  4488.7  337.99  4544.3  337.46  4550.7  336.59  4579.5  335.91  4595.8334.0515
    4622  329.45  4635.5  328.84  4649.9     327  4668.6326.4953  4707.4  325.93
  4713.8   326.6  4742.6  325.53  4806.6  326.54  4852.9326.3694  4980.6  327.29
  4986.4  326.08  4992.4  321.35    4997  319.69  4999.8  319.19    5003  319.69
  5007.8  320.99  5015.5  326.62  5029.3  328.39    5045  331.28  5050.8  335.79
  5087.9   339.7  5140.7  339.43  5189.5  335.82  5212.7   336.1  5234.9  337.97
#Mann= 6 ,-1 , 0
  4488.7     .16       0  4595.8     .12       0  4668.6     .16       0
  4852.9     .12       0    4997     .07       0    5003     .12       0
Bank Sta=4980.6,5029.3
XS Rating Curve= 0 ,0
Exp/Cntr=0.3,0.1

Type RM Length L Ch R = 1 ,53352   ,369,369,369
BEGIN DESCRIPTION:
GASTON BRANCH 82.0
END DESCRIPTION:
XS GIS Cut Line= 3
      3661499.62      10601960.2      3661249.61     10601510.19
      3661099.62     10601460.19
#Sta/Elev= 30
  4479.5  338.46  4543.3336.5983  4559.6  334.65  4590.5  332.79  4596.2  331.02
    4658  324.99  4693.4  323.84  4731.2  325.24  4771.1325.0526  4788.4  324.79
  4802.1  321.12  4811.3  320.85  4818.1  319.56  4845.6  324.12  4877.6  324.47
  4883.3  325.34  4980.6   324.6  4986.3   323.1  4991.4  318.23  4996.9  318.23
    4997  315.87  4999.8  315.37    5003  315.87  5004.8  315.87  5015.4  323.65
  5025.9  329.99  5036.5  333.22    5047   334.9  5078.6  337.86  5152.4   340.5
#Mann= 6 ,-1 , 0
  4479.5     .16       0  4543.3     .12       0    4658     .16       0
  4771.1     .12       0    4997     .07       0    5003     .12       0
Bank Sta=4980.6,5015.4
XS Rating Curve= 0 ,0
Exp/Cntr=0.3,0.1

Type RM Length L Ch R = 1 ,52983   ,373,373,373
BEGIN DESCRIPTION:
GASTON BRANCH 81.0
END DESCRIPTION:
XS GIS Cut Line= 2
      3661830.81     10601775.07      3661268.28      10601129.2
#Sta/Elev= 30
  4586.4  339.84  4746.7  339.12  4793.3336.8164  4831.5334.5063  4873.9   329.4
  4895.8  328.74  4937.7  321.48  4980.3   322.5  4987.9  320.68  4994.5   317.3
    4997  313.94  4999.8  313.44    5003  313.94  5008.8  313.94  5011.6 314.968
  5016.4  316.73  5030.5  318.68  5037.3  322.67  5164.5  321.62  5256.6  322.13
  5278.4  323.34    5285   325.1  5306.9  325.82  5313.5  327.15  5335.4  327.35
    5342  328.59  5370.5  328.62  5377.1  329.76    5399  329.55  5442.9  332.41
#Mann= 6 ,-1 , 0
  4586.4     .16       0  4793.3     .05       0  4831.5     .16       0
    4997     .07       0    5003     .16       0  5011.6     .12       0
Bank Sta=4980.3,5037.3
XS Rating Curve= 0 ,0
Exp/Cntr=0.3,0.1

Type RM Length L Ch R = 1 ,52610   ,814,814,814
BEGIN DESCRIPTION:
GASTON BRANCH 80.0
END DESCRIPTION:
XS GIS Cut Line= 3
      3662148.54     10601540.71      3661778.72      10601243.8
      3661367.22     10600962.53
#Sta/Elev= 30
  4418.5  332.64  4538.6330.6451    4634327.9019  4687.9  327.74  4710.3  330.31
  4716.7  329.25  4731.1  329.38  4745.5   331.4  4751.3330.4575  4774.3  331.13
  4801.8  329.18  4815.9  325.76  4873.5  320.24  4879.9     318  4895.2   317.5
  4902.9  318.77  4908.9  317.38  4923.9  319.43  4965.8  320.54  4974.7  318.37
  4980.7  319.43    4997  312.28  4999.8  311.78    5003  312.28  5016.6  316.19
  5024.9  320.72  5182.4   319.7  5255.1  324.14  5339.9  333.23  5391.2   334.4
#Mann= 6 ,-1 , 0
  4418.5     .05       0  4538.6     .12       0    4634     .05       0
  4751.3     .12       0    4997     .07       0    5003     .12       0
Bank Sta=4980.7,5024.9
XS Rating Curve= 0 ,0
Exp/Cntr=0.3,0.1

Type RM Length L Ch R = 1 ,51796   ,370,370,370
BEGIN DESCRIPTION:
GASTON BRANCH 79.0
END DESCRIPTION:
XS GIS Cut Line= 3
       3662341.2     10601160.45      3662117.26     10600863.59
      3661575.59     10600551.09
#Sta/Elev= 30
    4457  336.76  4551.1  334.94  4580.3  332.14  4630.2  329.72    4651  324.71
  4679.1320.6725  4707.9  317.71  4736.4  316.57  4872.3   317.1  4903.4  315.59
  4909.2  317.08    4925  315.59  4930.8   316.1  4940.8  313.99  4946.5  315.21
  4953.1  311.97  4962.3     313  4968.1  312.31  4976.2  315.61  4983.9  315.82
  4989.6  310.19    4997  308.62  4999.8  308.12    5003  308.62  5021.2  308.65
    5027  312.25  5048.5  315.83  5150.5  318.73  5342.9  320.13  5454.2  325.25
#Mann= 4 ,-1 , 0
    4457     .05       0  4679.1     .12       0    4997     .07       0
    5003     .12       0
Bank Sta=4983.9,5048.5
XS Rating Curve= 0 ,0
Exp/Cntr=0.3,0.1

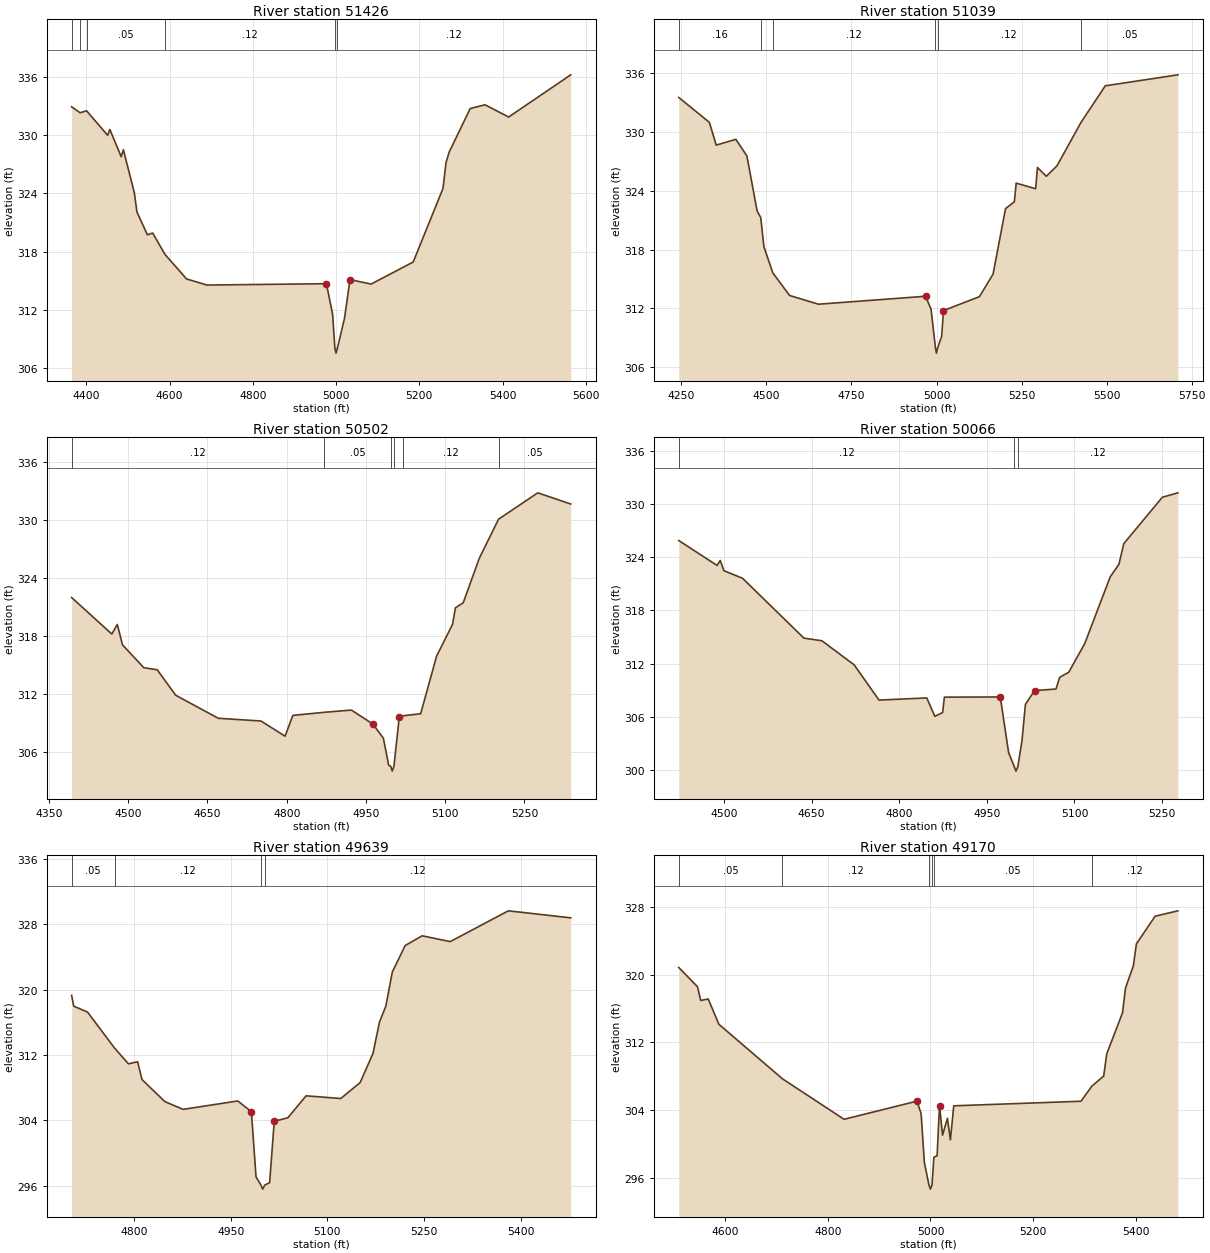
Type RM Length L Ch R = 1 ,51426   ,387,387,387
BEGIN DESCRIPTION:
GASTON BRANCH 78.0
END DESCRIPTION:
XS GIS Cut Line= 3
      3662471.43     10601124.02      3662309.97     10600603.18
      3661774.03     10600228.54
#Sta/Elev= 30
  4364.5   332.9    4385  332.29  4400.4332.4948  4451.1  329.97  4456.3  330.57
  4483.6  327.77  4488.9  328.48  4515.1  324.08  4521.5  322.08  4546.5  319.74
  4559.3  319.92  4588.8317.7204  4640.7   315.2  4689.7  314.57  4976.7  314.71
  4991.6  311.56    4997  308.07  4999.8  307.57    5003  308.07    5020  311.13
  5033.4  315.13    5084  314.67  5185.2  316.94  5256.7   324.5  5264.1  327.18
  5271.5  328.23  5322.1  332.72  5357.8  333.11  5414.5  331.85  5563.7  336.19
#Mann= 6 ,-1 , 0
  4364.5     .05       0    4385     .16       0  4400.4     .05       0
  4588.8     .12       0    4997     .07       0    5003     .12       0
Bank Sta=4976.7,5033.4
XS Rating Curve= 0 ,0
Exp/Cntr=0.3,0.1

Type RM Length L Ch R = 1 ,51039   ,537,537,537
BEGIN DESCRIPTION:
GASTON BRANCH 77.0
END DESCRIPTION:
XS GIS Cut Line= 3
      3662575.59       10601150.      3662533.92     10600504.22
      3662799.56     10599728.15
#Sta/Elev= 30
  4242.3  333.51  4332.3  330.97  4352.3  328.65  4410.1  329.24  4442.5  327.55
  4472.6  321.93  4483.3321.2561  4492.6  318.28  4518.7  315.62    4568  313.31
    4653  312.42  4967.7  313.23  4983.9  311.93    4997  307.93  4999.8  307.43
    5003  307.93  5015.1  309.13  5020.5  311.77  5126.2  313.19  5166.3  315.49
  5202.9  322.17  5228.9  322.87  5234.2  324.77  5291.5   324.2  5296.8  326.37
  5322.8  325.47  5354.1  326.53  5424.3 330.936  5496.2   334.7  5709.7  335.82
#Mann= 6 ,-1 , 0
  4242.3     .16       0  4483.3     .05       0  4518.7     .12       0
    4997     .07       0    5003     .12       0  5424.3     .05       0
Bank Sta=4967.7,5020.5
XS Rating Curve= 0 ,0
Exp/Cntr=0.3,0.1

Type RM Length L Ch R = 1 ,50502   ,436,436,436
BEGIN DESCRIPTION:
GASTON BRANCH 76.0
END DESCRIPTION:
XS GIS Cut Line= 2
      3663004.46     10600935.74      3663121.65     10599998.23
#Sta/Elev= 30
  4392.9  321.97    4469  318.19  4479.4  319.18  4489.2  317.08  4529.5  314.71
    4555  314.49    4590  311.85  4670.6  309.47  4751.2  309.19  4796.9  307.62
  4811.7  309.77  4871.1  310.09  4922.5  310.32  4963.2  308.87    4983  307.41
  4993.1  304.61    4997   304.5  4999.8     304    5003   304.5  5013.2  309.64
  5019.6309.7287  5053.6  309.94  5083.8  315.91    5114   319.2  5119.4  320.91
  5134.2  321.43  5164.4  326.01    5201 330.076  5275.3  332.81  5337.7  331.65
#Mann= 6 ,-1 , 0
  4392.9     .12       0  4871.1     .05       0    4997     .03       0
    5003     .05       0  5019.6     .12       0    5201     .05       0
Bank Sta=4963.2,5013.2
XS Rating Curve= 0 ,0
Exp/Cntr=0.3,0.1

Type RM Length L Ch R = 1 ,50066   ,427,427,427
BEGIN DESCRIPTION:
GASTON BRANCH 75.0
END DESCRIPTION:
XS GIS Cut Line= 3
      3663191.11     10601052.86      3663343.01     10600627.54
      3663546.98     10600280.36
#Sta/Elev= 30
  4422.7   325.9  4488.3  323.08  4493.6  323.65  4499.9  322.49  4531.7  321.64
  4636.9  314.87  4667.7  314.57  4722.9  311.85  4765.4  307.87  4847.2  308.11
  4860.9  306.03  4874.3  306.46  4877.3   308.2    4973  308.22  4987.2  301.95
    4997  300.34  4999.8  299.84    5003  300.34  5010.2  303.32    5016  307.38
  5031.6  308.94  5068.4  309.12  5074.6  310.44  5090.2  311.02  5117.5  314.25
  5161.2   321.8  5176.1  323.22  5184.4  325.55  5250.4  330.79    5277  331.29
#Mann= 3 ,-1 , 0
  4422.7     .12       0    4997     .07       0    5003     .12       0
Bank Sta=4973,5031.6
XS Rating Curve= 0 ,0
Exp/Cntr=0.3,0.1

Type RM Length L Ch R = 1 ,49639   ,469,469,469
BEGIN DESCRIPTION:
GASTON BRANCH 74.0
END DESCRIPTION:
XS GIS Cut Line= 3
      3663451.53     10601026.84      3663737.98     10600749.07
      3663729.34     10600373.28
#Sta/Elev= 30
  4703.1  319.29  4706.4  317.98  4727.8  317.26    4770312.8259  4791.3  310.92
  4805.5  311.17  4812.4  308.99  4847.9  306.29  4876.2  305.34  4961.1  306.37
  4982.2  305.05  4989.4  297.08    4997  296.07  4999.8  295.57    5003  296.07
  5010.5  296.36  5017.7  303.88  5038.8  304.31  5067.1     307    5121  306.67
    5151  308.62    5171  312.19    5181  316.01    5191     318    5201  322.17
    5221  325.41  5247.3   326.6    5291  325.89  5381.1  329.66    5478   328.8
#Mann= 4 ,-1 , 0
  4703.1     .05       0    4770     .12       0    4997     .07       0
    5003     .12       0
Bank Sta=4982.2,5017.7
XS Rating Curve= 0 ,0
Exp/Cntr=0.3,0.1

Type RM Length L Ch R = 1 ,49170   ,94,94,94
BEGIN DESCRIPTION:
GASTON BRANCH 73.0
END DESCRIPTION:
XS GIS Cut Line= 3
      3663799.63     10601260.15      3664099.61     10600860.19
      3663849.59     10600460.15
#Sta/Elev= 30
    4510  320.84  4546.4  318.58  4552.7  316.95  4567.3  317.13  4588.1  314.14
  4711.9307.7062  4831.8  302.93  4973.5  305.07  4981.8   303.6  4988.1  297.84
    4997  295.19  4999.8  294.69    5003  295.19  5006.6298.4492  5012.9  298.63
  5017.6  304.53  5023.5  301.06    5033  303.05  5038.8  300.51  5045.3  304.52
    5293  305.06  5314.3306.8514  5337.2  308.03  5343.1  310.64  5373.8  315.49
  5379.7  318.42    5395  321.05  5400.9  323.63  5437.4   326.9  5481.7  327.53
#Mann= 6 ,-1 , 0
    4510     .05       0  4711.9     .12       0    4997     .07       0
    5003     .12       0  5006.6     .05       0  5314.3     .12       0
Bank Sta=4973.5,5017.6
XS Rating Curve= 0 ,0
Exp/Cntr=0.3,0.1

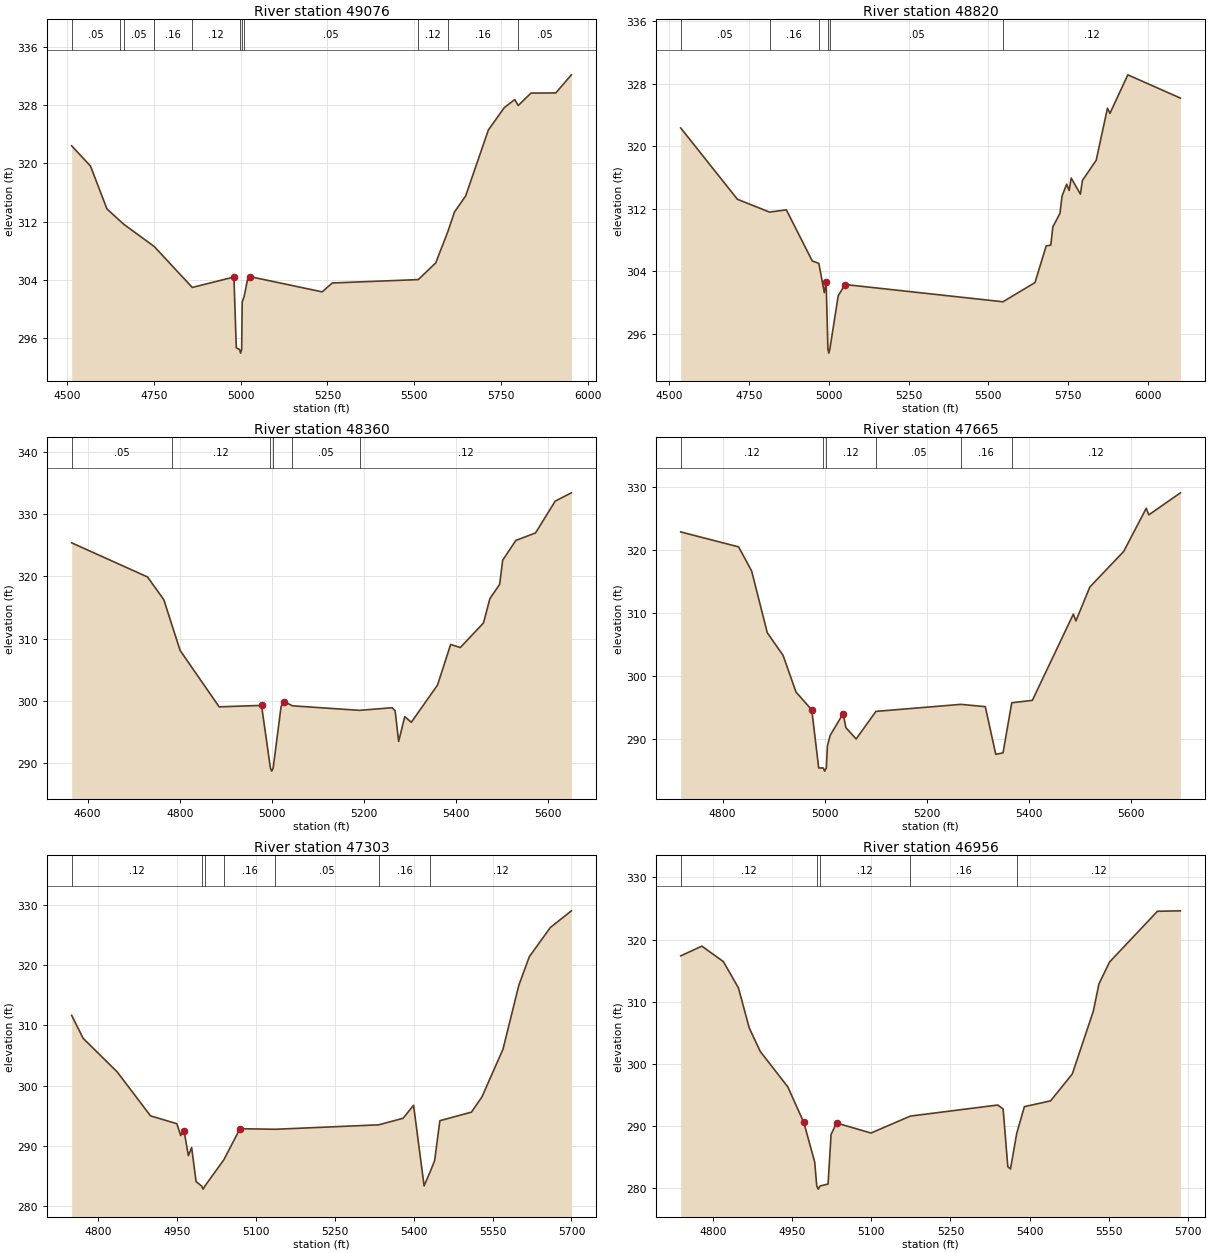
Type RM Length L Ch R = 1 ,49076   ,256,256,256
BEGIN DESCRIPTION:
Mapping XS 0048708d
END DESCRIPTION:
XS GIS Cut Line= 2
      3663994.73     10601347.71      3664550.27     10600019.62
#Sta/Elev= 30
  4513.2  322.42  4567.4  319.65    4615  313.74  4651.5312.1554  4664.1311.6158
    4751308.5879  4860.7302.9569  4980.7  304.39  4987.5  294.66    4997  294.43
  4999.8  293.93    5003  294.43  5004.5  300.95  5010.2301.7314    5020  304.06
  5028.3  304.43  5234.9  302.35  5264.1  303.57  5511.8304.0367    5562  306.33
  5596.9310.6203  5616.2  313.34  5648.2  315.53  5713.7   324.6  5759.6  327.68
  5789.6  328.78  5799.7327.9664  5836.4  329.67  5907.8  329.69  5952.8  332.18
#Mann= 11 ,-1 , 0
  4513.2     .05       0  4651.5     .16       0  4664.1     .05       0
    4751     .16       0  4860.7     .12       0    4997     .07       0
    5003     .12       0  5010.2     .05       0  5511.8     .12       0
  5596.9     .16       0  5799.7     .05       0
Bank Sta=4980.7,5028.3
XS Rating Curve= 0 ,0
Exp/Cntr=0.3,0.1

Type RM Length L Ch R = 1 ,48820   ,460,460,460
BEGIN DESCRIPTION:
GASTON BRANCH 72.0
END DESCRIPTION:
XS GIS Cut Line= 3
      3664174.57     10601415.64      3664492.26     10600842.76
      3665200.59     10600269.84
#Sta/Elev= 30
  4535.6  322.32  4713.4  313.19    4814  311.55  4866.7  311.84  4947.9   305.3
  4968.5304.9855  4985.7  301.24  4991.4  302.61    4997     294  4999.8   293.5
    5003     294  5029.2  300.84  5050.9  302.28  5545.6 300.073  5645.9  302.53
  5681.1  307.23  5695.5  307.32  5701.9  309.66  5724.2  311.39  5730.7   313.6
  5745.1  315.12    5753  314.32  5759.4  315.91  5788.2  313.85  5794.6   315.6
  5837.8  318.19    5873  324.85  5880.9  324.19  5936.9  329.12  6101.7  326.14
#Mann= 6 ,-1 , 0
  4535.6     .05       0    4814     .16       0  4968.5     .05       0
    4997     .03       0    5003     .05       0  5545.6     .12       0
Bank Sta=4991.4,5050.9
XS Rating Curve= 0 ,0
Exp/Cntr=0.3,0.1

Type RM Length L Ch R = 1 ,48360   ,695,695,695
BEGIN DESCRIPTION:
GASTON BRANCH 71.0
END DESCRIPTION:
XS GIS Cut Line= 3
      3664403.73     10601587.54      3664815.17     10601170.89
      3665193.58     10600844.32
#Sta/Elev= 30
  4565.3  325.37  4730.2  319.89  4765.6  316.23  4782.9312.2224  4800.9   308.1
  4885.7  299.04  4977.7  299.27    4997  289.22  4999.8  288.72    5003  289.22
  5020.2   299.1  5027.2  299.87  5044.9299.2056  5190.5298.4776  5261.3   298.9
  5267.9  298.42  5275.5  293.48  5288.8  297.47    5303  296.56    5360  302.54
  5388.5  309.06  5409.4  308.56  5459.8  312.51  5473.7  316.41  5494.9  318.71
  5501.5  322.58  5530.1  325.76  5572.8  326.96  5615.6  332.07  5650.7   333.4
#Mann= 6 ,-1 , 0
  4565.3     .05       0  4782.9     .12       0    4997     .07       0
    5003     .12       0  5044.9     .05       0  5190.5     .12       0
Bank Sta=4977.7,5027.2
XS Rating Curve= 0 ,0
Exp/Cntr=0.3,0.1

Type RM Length L Ch R = 1 ,47665   ,362,362,362
BEGIN DESCRIPTION:
GASTON BRANCH 70.0
END DESCRIPTION:
XS GIS Cut Line= 3
      3665117.25     10601884.44      3665289.13     10601405.26
       3665388.1      10600946.9
#Sta/Elev= 30
    4718  322.82  4831.4  320.44  4856.8  316.62  4887.5   306.8  4918.3  303.22
  4943.7  297.38  4974.5  294.55  4988.1  285.32    4997  285.32  4999.8  284.82
    5003  285.32  5005.2  288.85  5010.5  290.49  5035.9  293.96  5041.3  291.72
  5061.4  289.93  5100.1294.3104  5266.4295.4267  5314.1  295.06  5334.6  287.49
  5348.8  287.72  5365.9295.6823  5406.2  296.06  5486.4  309.75  5491.5  308.69
  5518.7  314.07    5585  319.72  5629.1  326.58  5634.2  325.53    5696  329.03
#Mann= 6 ,-1 , 0
    4718     .12       0    4997     .07       0    5003     .12       0
  5100.1     .05       0  5266.4     .16       0  5365.9     .12       0
Bank Sta=4974.5,5035.9
XS Rating Curve= 0 ,0
Exp/Cntr=0.3,0.1

Type RM Length L Ch R = 1 ,47303   ,347,347,347
BEGIN DESCRIPTION:
GASTON BRANCH 69.0
END DESCRIPTION:
XS GIS Cut Line= 3
       3665399.6      10601910.2      3665549.61     10601710.19
      3665549.61      10601010.2
#Sta/Elev= 30
  4749.8  311.64  4771.7  307.83  4836.3  302.27  4899.8  294.97  4949.8  293.67
  4957.1  291.71  4963.4  292.53  4971.7  288.37  4977.9  289.73  4986.3  284.09
    4997  283.32  4999.8  282.82    5003  283.32  5039.2287.6978  5069.8  292.84
  5137.2292.7478  5333.4293.4832  5379.8  294.57  5399.8  296.73  5419.8  283.36
  5431.5285.7289  5439.8  287.53  5449.8  294.17  5509.8  295.59  5529.8  298.12
  5569.8  306.03  5599.8   316.6  5619.8  321.36  5659.8  326.21  5699.8  328.98
#Mann= 7 ,-1 , 0
  4749.8     .12       0    4997     .07       0    5003     .12       0
  5039.2     .16       0  5137.2     .05       0  5333.4     .16       0
  5431.5     .12       0
Bank Sta=4963.4,5069.8
XS Rating Curve= 0 ,0
Exp/Cntr=0.3,0.1

Type RM Length L Ch R = 1 ,46956   ,564,564,564
BEGIN DESCRIPTION:
GASTON BRANCH 68.0
END DESCRIPTION:
XS GIS Cut Line= 3
      3665934.17     10601855.88      3665829.99     10601452.19
      3665764.89     10600927.03
#Sta/Elev= 30
  4739.4  317.36  4779.5  318.93  4820.2  316.44  4848.6  312.22  4869.2  305.75
  4889.9  301.98  4942.2  296.25  4972.5  290.52  4993.1  284.14    4997  280.28
  4999.8  279.78    5003  280.28  5018.4   280.6  5024.1  288.59  5034.5  290.43
  5099.7  288.82  5174.3 291.551  5339.7  293.33  5349.8   292.7  5358.7   283.4
  5363.8  283.03  5375.6 288.777  5390.1  293.07  5439.7     294  5480.8  298.34
  5520.6  308.45  5531.2  312.83  5551.3  316.37    5642  324.55  5685.5  324.62
#Mann= 5 ,-1 , 0
  4739.4     .12       0    4997     .07       0    5003     .12       0
  5174.3     .16       0  5375.6     .12       0
Bank Sta=4972.5,5034.5
XS Rating Curve= 0 ,0
Exp/Cntr=0.3,0.1