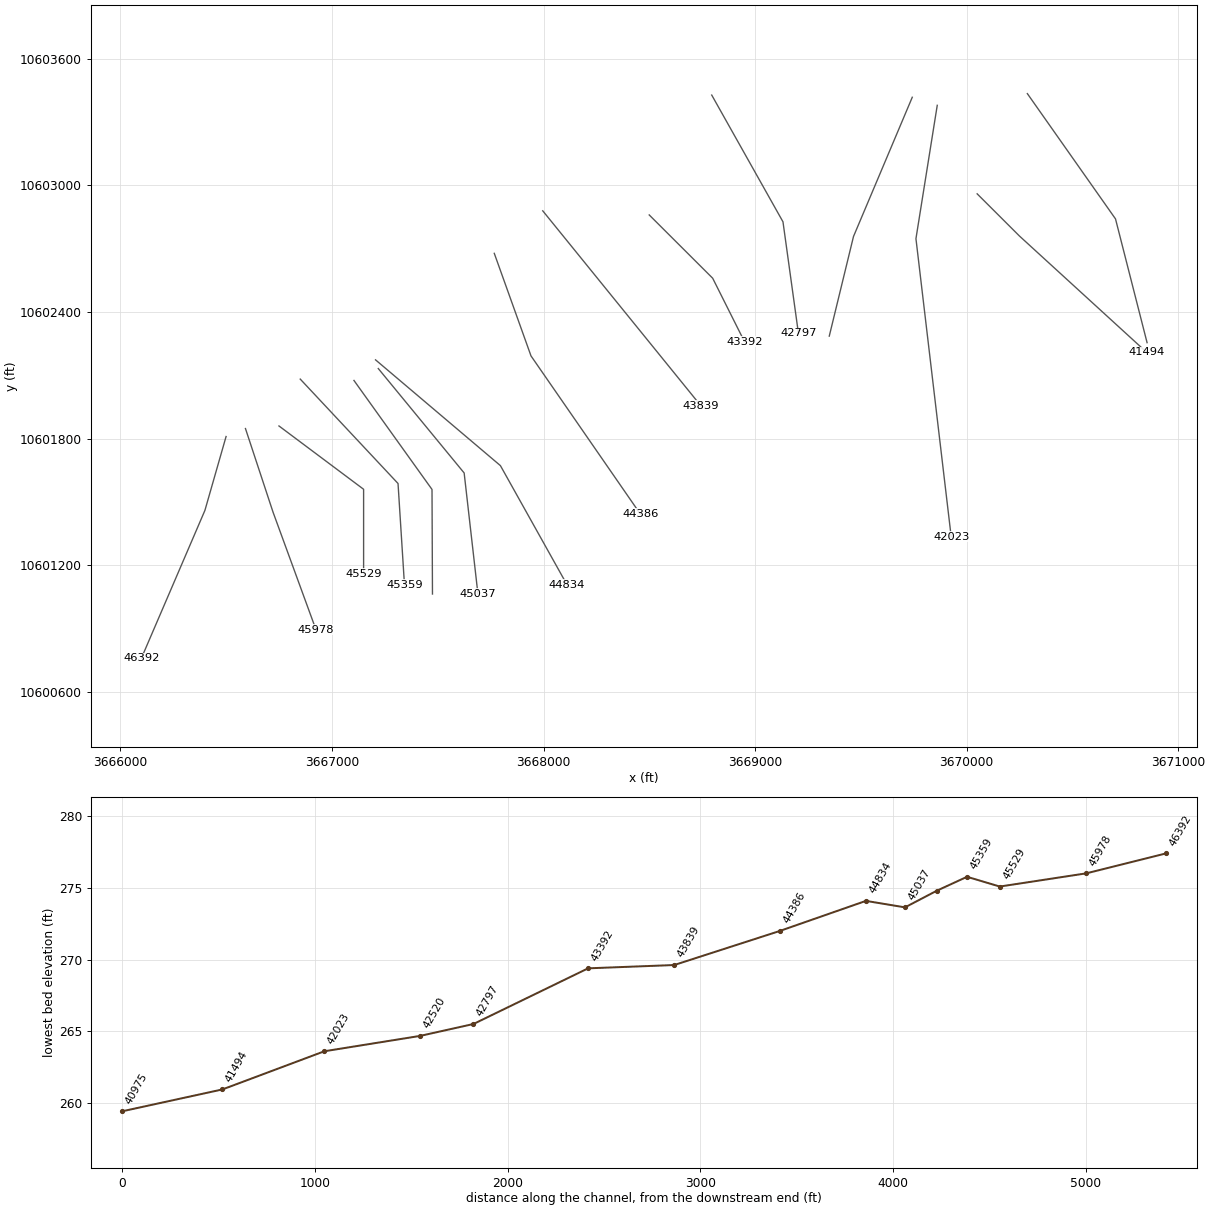
HEC-RAS study GASTON BRANCH.prj: GASTON BRANCH Base Level Engineering

--- GASTON BRANCH.g01 (geometry) --- (continued)

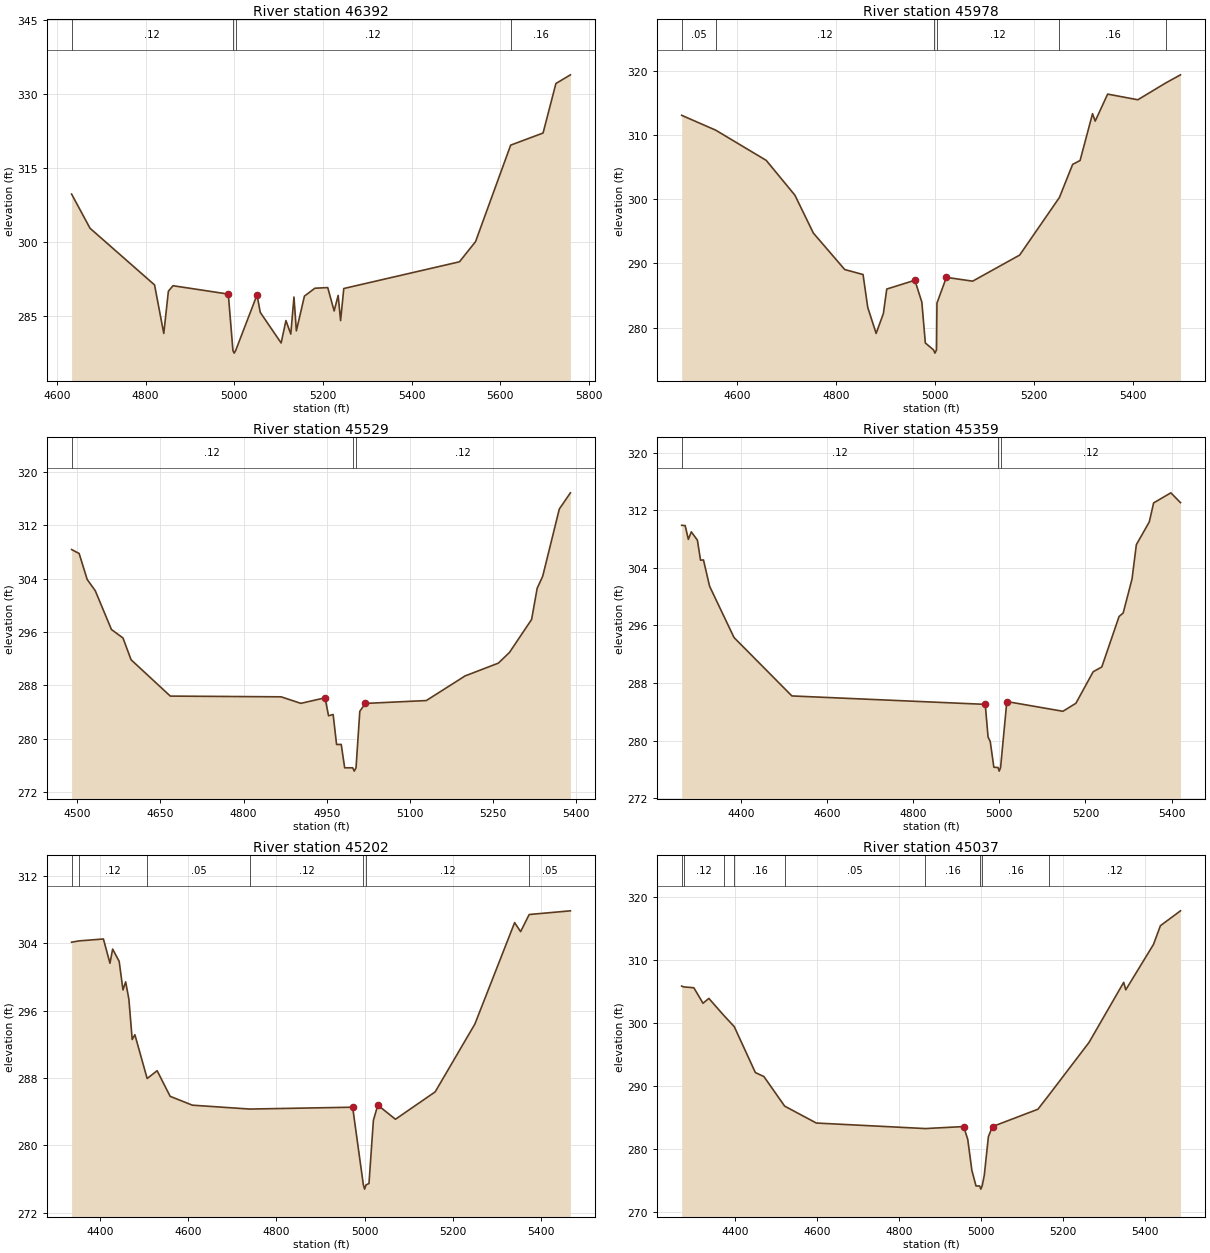
Type RM Length L Ch R = 1 ,46392   ,414,414,414
BEGIN DESCRIPTION:
GASTON BRANCH 67.0
END DESCRIPTION:
XS GIS Cut Line= 3
      3666499.61     10601810.18      3666399.61     10601460.19
       3666099.6     10600760.17
#Sta/Elev= 30
  4632.9  309.66  4674.5  302.73  4820.1  291.24  4840.9   281.4  4851.3  289.96
  4861.7  291.08  4986.5  289.38    4997  277.91  4999.8  277.41    5003  277.91
  5051.3  289.21  5058.6  285.68  5105.7  279.47  5116.6  284.01  5127.5  281.28
  5134.7  288.79  5140.1  281.93  5158.3  288.97  5181.9  290.57  5210.9   290.7
  5225.4  285.96  5234.4  289.12  5239.9  284.01  5247.1  290.51  5508.2  295.93
  5544.5  300.03  5623.7319.5817  5696.8  322.04  5725.8  332.08  5758.5  333.84
#Mann= 4 ,-1 , 0
  4632.9     .12       0    4997     .07       0    5003     .12       0
  5623.7     .16       0
Bank Sta=4986.5,5051.3
XS Rating Curve= 0 ,0
Exp/Cntr=0.3,0.1

Type RM Length L Ch R = 1 ,45978   ,449,449,449
BEGIN DESCRIPTION:
GASTON BRANCH 66.0
END DESCRIPTION:
XS GIS Cut Line= 3
      3666591.23     10601847.93      3666721.42     10601452.14
      3666924.47     10600895.05
#Sta/Elev= 30
  4487.2  313.03  4556.1310.7169  4658.3  306.02  4716.4   300.6  4753.7  294.71
  4817.2  289.03  4854.3  288.25  4863.8  283.14  4880.8  279.09  4895.4  282.17
  4902.3  285.99  4959.2  287.36  4973.3  283.96  4980.4   277.6    4997  276.52
  4999.8  276.02    5003  276.52  5003.9  283.81    5023  287.81  5076.2  287.22
  5171.3  291.28  5251.8300.2466  5278.5  305.39  5293.6     306  5318.8  313.28
  5324.2  312.13  5349.4  316.33  5410.5  315.45  5466.9318.0613  5496.8  319.33
#Mann= 6 ,-1 , 0
  4487.2     .05       0  4556.1     .12       0    4997     .07       0
    5003     .12       0  5251.8     .16       0  5466.9     .12       0
Bank Sta=4959.2,5023
XS Rating Curve= 0 ,0
Exp/Cntr=0.3,0.1

Type RM Length L Ch R = 1 ,45529   ,170,170,170
BEGIN DESCRIPTION:
GASTON BRANCH 65.0
END DESCRIPTION:
XS GIS Cut Line= 3
       3666749.6      10601860.2      3667149.61     10601560.19
      3667149.61      10601160.2
#Sta/Elev= 30
  4489.8  308.38  4503.4  307.79  4517.9  303.89  4532.5   302.2  4561.7  296.37
  4582.5   295.1  4597.1  291.83  4667.9  286.37  4867.9  286.26  4903.4  285.28
  4947.1  286.11  4953.4  283.41  4961.7  283.61  4967.9   279.1  4976.3  279.11
  4982.5   275.6    4997   275.6  4999.8   275.1    5003   275.6  5009.8  284.08
  5019.8  285.27  5129.8   285.7  5199.8   289.4  5259.8  291.32  5279.8  292.92
  5319.8  297.88  5329.8  302.55  5339.8  304.37  5369.8  314.47  5389.8   316.9
#Mann= 3 ,-1 , 0
  4489.8     .12       0    4997     .07       0    5003     .12       0
Bank Sta=4947.1,5019.8
XS Rating Curve= 0 ,0
Exp/Cntr=0.3,0.1

Type RM Length L Ch R = 1 ,45359   ,157,157,157
BEGIN DESCRIPTION:
Mapping XS 550f83e4
END DESCRIPTION:
XS GIS Cut Line= 3
      3666850.15     10602082.31      3667312.35     10601587.55
      3667342.73     10601107.98
#Sta/Elev= 30
  4262.9  309.91    4271  309.87  4278.4  307.96  4285.2     309  4299.4  307.85
  4306.7  305.07  4313.5   305.1  4327.7  301.45  4384.4  294.33  4518.7  286.22
  4967.4  285.05    4974  280.51    4979   279.9  4987.4  276.32    4997  276.28
  4999.8  275.78    5003  276.28  5017.5  285.44  5147.7  284.09  5177.8   285.2
  5217.9  289.58  5237.9  290.24    5278  297.25  5287.5  297.73  5308.1  302.47
  5318.1  307.22  5348.1  310.38  5358.2  313.02  5398.2  314.42  5420.5  313.06
#Mann= 3 ,-1 , 0
  4262.9     .12       0    4997     .07       0    5003     .12       0
Bank Sta=4967.4,5017.5
XS Rating Curve= 0 ,0
Exp/Cntr=0.3,0.1

Type RM Length L Ch R = 1 ,45202   ,165,165,165
BEGIN DESCRIPTION:
GASTON BRANCH 64.0
END DESCRIPTION:
XS GIS Cut Line= 3
      3667104.04     10602075.81      3667472.94     10601559.34
      3667475.11     10601063.83
#Sta/Elev= 30
  4335.9  304.11  4353.7304.2674    4408  304.49  4422.8  301.61  4428.9  303.29
  4443.7  301.83  4452.3  298.45  4458.4   299.4  4465.7  297.34  4473.2  292.56
  4479.3  293.13  4507.1287.9337  4529.7  288.86  4559.2  285.82  4609.6  284.77
  4739.6  284.31  4972.7  284.53    4997  275.31  4999.8  274.81    5003  275.31
  5009.7  275.48  5019.7  282.97  5029.7  284.78  5069.7   283.1  5159.7  286.35
  5249.7   294.4  5339.7  306.43  5353.3  305.36  5372.7 307.393  5466.1  307.83
#Mann= 7 ,-1 , 0
  4335.9     .05       0  4353.7     .12       0  4507.1     .05       0
  4739.6     .12       0    4997     .07       0    5003     .12       0
  5372.7     .05       0
Bank Sta=4972.7,5029.7
XS Rating Curve= 0 ,0
Exp/Cntr=0.3,0.1

Type RM Length L Ch R = 1 ,45037   ,203,203,203
BEGIN DESCRIPTION:
GASTON BRANCH 63.0
END DESCRIPTION:
XS GIS Cut Line= 3
      3667219.06     10602132.23      3667624.85     10601637.47
      3667689.92     10601064.84
#Sta/Elev= 30
  4270.4  305.87  4275.7305.7459  4300.1  305.61  4322.4  303.15  4336.7  303.92
  4373.3301.2094  4398.6299.4413  4450.1  292.15  4470.9  291.52  4521.5286.8259
  4598.7  284.14  4864.5283.2625  4957.9  283.58  4967.9  281.56    4978  276.62
  4988.1  274.15    4997  274.15  4999.8  273.65    5003  274.15  5008.2  275.83
  5018.3  281.99  5028.3  283.58    5139  286.33  5165.7288.5679  5263.6  296.93
  5348.2  306.47  5353.2  305.28  5420.8  312.49  5437.7  315.46  5486.6  317.82
#Mann= 9 ,-1 , 0
  4270.4     .05       0  4275.7     .12       0  4373.3     .05       0
  4398.6     .16       0  4521.5     .05       0  4864.5     .16       0
    4997     .07       0    5003     .16       0  5165.7     .12       0
Bank Sta=4957.9,5028.3
XS Rating Curve= 0 ,0
Exp/Cntr=0.3,0.1

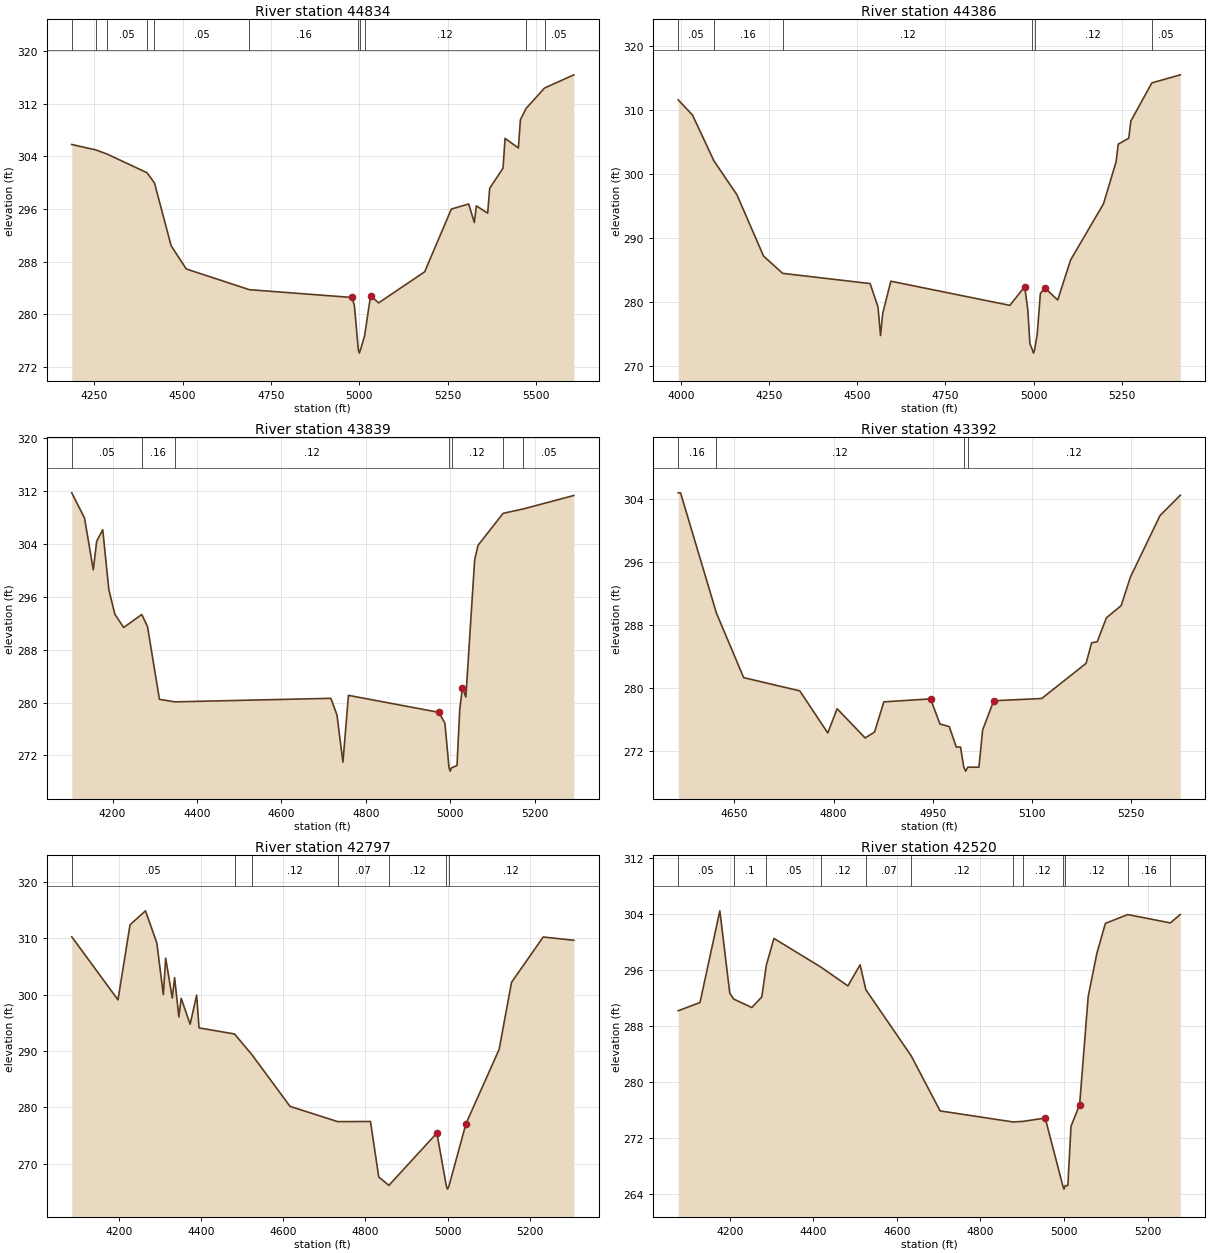
Type RM Length L Ch R = 1 ,44834   ,448,448,448
BEGIN DESCRIPTION:
Mapping XS 4cefcfc1
END DESCRIPTION:
XS GIS Cut Line= 3
      3667206.04     10602173.47      3667796.29     10601672.19
      3668110.95     10601107.98
#Sta/Elev= 30
  4186.3  305.78  4254.2304.9609  4286.1 304.331    4399301.4986  4420.3299.9426
  4467.4  290.41  4510.2  286.88  4688.7283.7339    4979  282.55  4985.9  281.32
    4997   274.6  4999.8   274.1    5003   274.6  5014.6276.6997  5031.7  282.82
  5054.4  281.73  5184.7  286.45  5260.1  295.97  5309.2  296.75  5325.2  293.93
  5330.9  296.46  5362.9  295.36  5368.7  299.14  5406.4  302.19  5412.1  306.71
  5449.8  305.25  5455.5  309.53  5471.6311.2578  5523.8314.3542  5606.7  316.36
#Mann= 11 ,-1 , 0
  4186.3     .05       0  4254.2     .12       0  4286.1     .05       0
    4399     .16       0  4420.3     .05       0  4688.7     .16       0
    4997     .07       0    5003     .16       0  5014.6     .12       0
  5471.6     .16       0  5523.8     .05       0
Bank Sta=4979,5031.7
XS Rating Curve= 0 ,0
Exp/Cntr=0.3,0.1

Type RM Length L Ch R = 1 ,44386   ,547,547,547
BEGIN DESCRIPTION:
GASTON BRANCH 62.0
END DESCRIPTION:
XS GIS Cut Line= 3
      3667767.22     10602678.24      3667940.83     10602192.15
      3668457.11     10601443.71
#Sta/Elev= 30
  3991.3  311.61  4031.7  309.25  4092.8302.0621  4157.9  296.77  4233.5  287.18
  4287.7  284.48    4536  282.88  4558.4  279.24  4565.7  274.75  4571.8  278.21
  4594.9  283.25  4932.9  279.47  4974.8  282.39  4983.6  278.89  4989.7  273.48
    4997   272.5  4999.8     272    5003   272.5  5010.6  274.99  5019.4  281.32
  5032.2  282.19  5068.7  280.31  5105.1  286.56  5198.6  295.35  5234.4  301.93
  5240.5  304.69  5270.3  305.61  5276.3   308.3  5335.8314.2637  5416.7  315.53
#Mann= 6 ,-1 , 0
  3991.3     .05       0  4092.8     .16       0  4287.7     .12       0
    4997     .07       0    5003     .12       0  5335.8     .05       0
Bank Sta=4974.8,5032.2
XS Rating Curve= 0 ,0
Exp/Cntr=0.3,0.1

Type RM Length L Ch R = 1 ,43839   ,447,447,447
BEGIN DESCRIPTION:
GASTON BRANCH 61.0
END DESCRIPTION:
XS GIS Cut Line= 2
      3667996.38     10602879.66      3668744.45     10601954.96
#Sta/Elev= 30
  4103.3  311.71  4133.5  307.91  4154.3  300.07  4162.3  304.39  4176.7  306.13
  4191.1  297.08  4205.4  293.35  4226.2  291.35  4269.1293.3119  4282.7   291.5
    4311  280.49  4347.2280.1025  4717.1  280.64  4731.5  278.14  4745.7  270.99
  4758.7  281.09  4972.9  278.52  4987.3  276.88    4997  270.13  4999.8  269.63
    5003  270.13  5015.9  270.48  5022.5  279.03  5028.9  282.25  5036.9  280.83
  5057.7  301.56  5065.6  303.76  5125.2 308.611  5173.2309.2775  5292.7  311.31
#Mann= 7 ,-1 , 0
  4103.3     .05       0  4269.1     .16       0  4347.2     .12       0
    4997     .07       0    5003     .12       0  5125.2     .07       0
  5173.2     .05       0
Bank Sta=4972.9,5028.9
XS Rating Curve= 0 ,0
Exp/Cntr=0.3,0.1

Type RM Length L Ch R = 1 ,43392   ,595,595,595
BEGIN DESCRIPTION:
GASTON BRANCH 60.0
END DESCRIPTION:
XS GIS Cut Line= 3
      3668499.61     10602860.19      3668799.61     10602560.19
      3668949.62     10602260.17
#Sta/Elev= 30
  4564.9  304.76  4568.4  304.76  4622.6289.5005  4663.9  281.28  4748.8   279.6
  4791.2  274.25  4805.3  277.33  4847.7  273.62  4861.9  274.36    4876   278.2
  4946.7  278.58  4960.9  275.39    4975  275.06  4985.6  272.46    4992  272.46
    4997   269.9  4999.8   269.4    5003   269.9  5019.9   269.9  5025.5  274.63
  5042.3  278.34  5114.9  278.63    5182  283.09  5190.4   285.7  5198.8  285.83
  5212.8  288.88  5235.1  290.43  5249.1  294.06  5293.8  301.86  5324.6  304.46
#Mann= 4 ,-1 , 0
  4564.9     .16       0  4622.6     .12       0    4997     .07       0
    5003     .12       0
Bank Sta=4946.7,5042.3
XS Rating Curve= 0 ,0
Exp/Cntr=0.3,0.1

Type RM Length L Ch R = 1 ,42797   ,277,277,277
BEGIN DESCRIPTION:
GASTON BRANCH 59.0
END DESCRIPTION:
XS GIS Cut Line= 3
      3668795.01     10603428.23       3669131.8     10602827.57
      3669204.66     10602300.21
#Sta/Elev= 30
  4085.9  310.25  4198.3  299.07  4227.6  312.37  4265.2  314.85  4292.7  309.17
  4308.6     300  4314.3  306.45  4330.3  299.39    4336  303.01  4346.3  296.05
    4352  299.35  4373.7  294.75  4389.6   299.9  4395.4   294.1  4481.7293.0219
  4523.4289.4112  4616.7  280.19  4732.6277.4854  4812.3  277.51  4832.5  267.66
  4857.2266.1905  4973.8  275.46    4997  266.02  4999.8  265.52    5003  266.02
  5044.5  277.11  5125.2  290.28  5155.4  302.18  5232.4  310.21  5306.9  309.63
#Mann= 7 ,-1 , 0
  4085.9     .05       0  4481.7     .16       0  4523.4     .12       0
  4732.6     .07       0  4857.2     .12       0    4997     .07       0
    5003     .12       0
Bank Sta=4973.8,5044.5
XS Rating Curve= 0 ,0
Exp/Cntr=0.3,0.1

Type RM Length L Ch R = 1 ,42520   ,497,497,497
BEGIN DESCRIPTION:
GASTON BRANCH 58.0
END DESCRIPTION:
XS GIS Cut Line= 3
      3669742.91     10603417.84      3669465.13     10602758.12
      3669350.56     10602285.94
#Sta/Elev= 30
  4076.6  290.16  4128.7  291.34  4176.2  304.43  4199.9   292.7    4209291.8401
  4252.8  290.62  4276.6  292.14  4287.6296.7061  4305.7  300.49  4417.5296.4145
  4482.7  293.71  4511.9  296.72  4525.7293.1622  4633.9283.7526  4703.4  275.86
    4878 274.281  4901.8274.3638  4954.9  274.84    4997  265.19  4999.8  264.69
    5003  265.19  5009.1  265.19  5016.7  273.67  5037.3  276.74  5057.8  292.18
  5078.4  298.31    5099  302.64  5152.5303.8943  5254.4302.7042  5278.3  303.91
#Mann= 12 ,-1 , 0
  4076.6     .05       0    4209      .1       0  4287.6     .05       0
  4417.5     .12       0  4525.7     .07       0  4633.9     .12       0
    4878     .07       0  4901.8     .12       0    4997     .07       0
    5003     .12       0  5152.5     .16       0  5254.4     .05       0
Bank Sta=4954.9,5037.3
XS Rating Curve= 0 ,0
Exp/Cntr=0.3,0.1

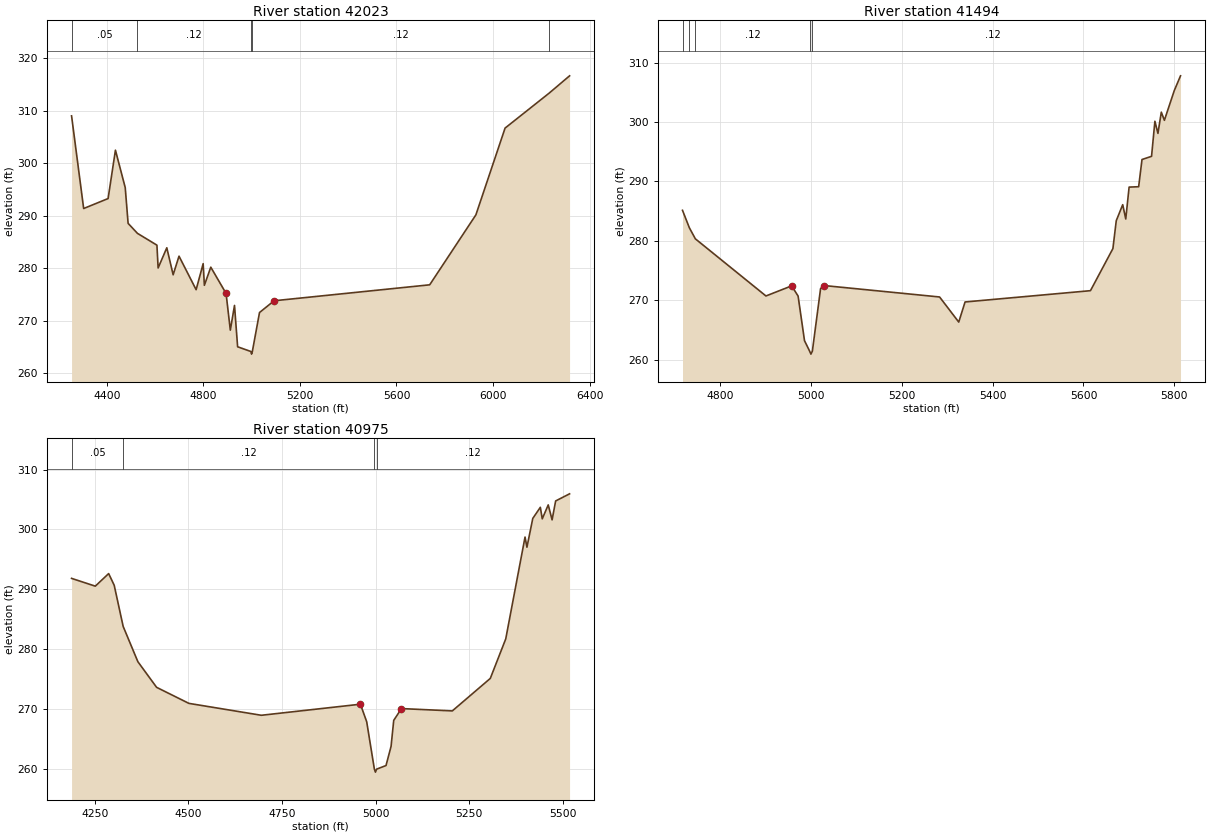
Type RM Length L Ch R = 1 ,42023   ,529,529,529
BEGIN DESCRIPTION:
GASTON BRANCH 57.0
END DESCRIPTION:
XS GIS Cut Line= 3
      3669860.96     10603379.64      3669760.27     10602747.71
      3669926.89      10601334.9
#Sta/Elev= 30
  4254.3  309.03  4304.4  291.37  4405.6  293.27    4436  302.49  4476.5  295.37
  4488.5  288.54  4527.1  286.64  4607.8  284.39  4612.8  280.04  4648.7  283.89
    4675  278.74  4699.3  282.29  4770.2   275.9  4799.3  280.86  4804.3  276.74
  4830.9  280.19  4894.2  275.19  4911.8  268.19  4929.1   272.9    4942  265.02
    4997  264.12  4999.8  263.62    5003  264.12  5032.7  271.55  5093.1  273.79
  5737.5  276.83  5928.8  290.16  6049.7   306.7  6231.9313.3495  6316.8  316.66
#Mann= 5 ,-1 , 0
  4254.3     .05       0  4527.1     .12       0    4997     .07       0
    5003     .12       0  6231.9     .05       0
Bank Sta=4894.2,5093.1
XS Rating Curve= 0 ,0
Exp/Cntr=0.3,0.1

Type RM Length L Ch R = 1 ,41494   ,519,519,519
BEGIN DESCRIPTION:
GASTON BRANCH 56.0
END DESCRIPTION:
XS GIS Cut Line= 3
      3670049.61     10602960.19      3670249.61     10602760.19
      3670849.62     10602210.18
#Sta/Elev= 30
    4717  285.14  4732.1282.2092  4745.3  280.35  4900.8  270.74  4957.4  272.44
  4971.6  270.72  4985.7  263.22    4997  261.46  4999.8  260.96    5003  261.46
  5021.1  271.98  5027.9   272.5  5283.2  270.57  5325.4  266.35  5339.3  269.73
  5615.5  271.63  5664.9  278.71  5672.3   283.4  5686.5  286.09  5693.2  283.69
  5700.6  289.05  5721.6  289.11    5729  293.69    5750  294.22  5757.4  300.12
  5764.1  298.08  5771.5  301.65  5778.3  300.28    5800305.2631  5813.8  307.76
#Mann= 6 ,-1 , 0
    4717     .12       0  4732.1     .16       0  4745.3     .12       0
    4997     .07       0    5003     .12       0    5800     .16       0
Bank Sta=4957.4,5027.9
XS Rating Curve= 0 ,0
Exp/Cntr=0.3,0.1

Type RM Length L Ch R = 1 ,40975   ,89,89,89
BEGIN DESCRIPTION:
Mapping XS 7774a1bf
END DESCRIPTION:
XS GIS Cut Line= 3
      3670286.83     10603435.13       3670703.5     10602841.37
      3670852.71     10602254.92
#Sta/Elev= 30
    4188  291.82  4251.4  290.52  4287.1  292.62  4301.9  290.67  4325.8283.8031
  4365.1   277.9  4415.2  273.61  4501.5  270.93    4695  268.94  4959.7  270.79
  4976.5  267.86    4997  259.94  4999.8  259.44    5003  259.94  5028.1  260.54
  5041.6  263.75  5048.7  268.09  5069.4  270.06  5205.2  269.67  5306.7   275.1
    5348  281.71  5399.5  298.72  5404.6  297.03  5420.2  301.84  5440.4   303.7
  5445.5  301.77  5461.5   304.1  5471.8   301.6  5481.3  304.76  5518.5  305.95
#Mann= 4 ,-1 , 0
    4188     .05       0  4325.8     .12       0    4997     .07       0
    5003     .12       0
Bank Sta=4959.7,5069.4
XS Rating Curve= 0 ,0
Exp/Cntr=0.3,0.1