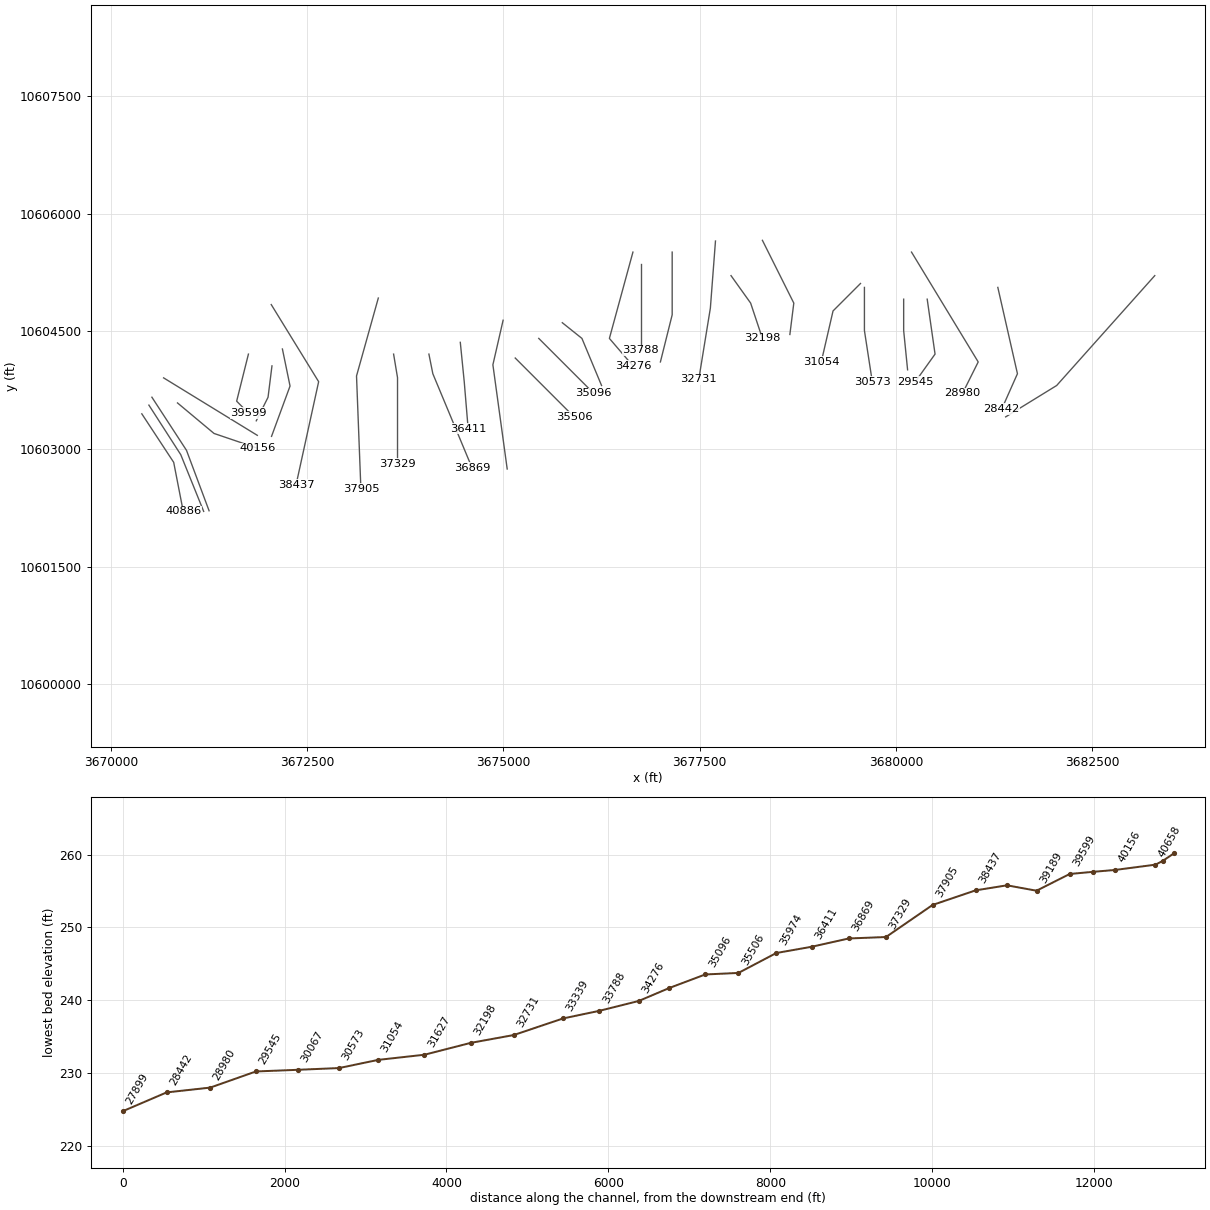
HEC-RAS study GASTON BRANCH.prj: GASTON BRANCH Base Level Engineering

--- GASTON BRANCH.g01 (geometry) --- (continued)

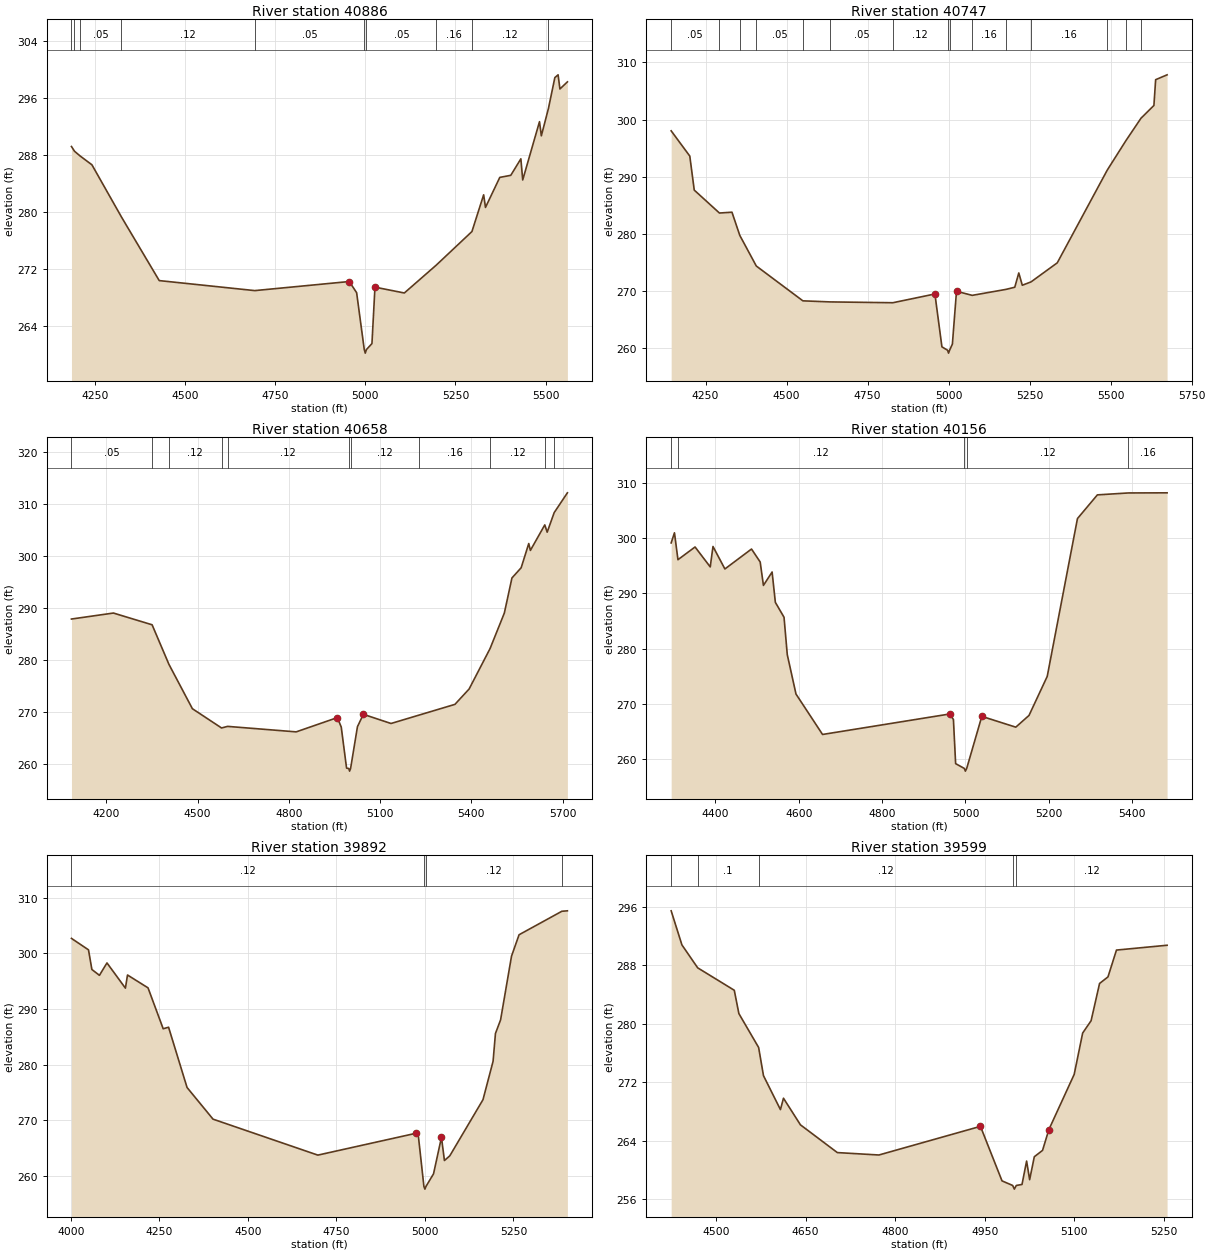
Type RM Length L Ch R = 1 ,40886   ,139,139,139
BEGIN DESCRIPTION:
GASTON BRANCH 55.0
END DESCRIPTION:
XS GIS Cut Line= 3
      3670390.99     10603449.03      3670797.25     10602830.95
      3670918.77       10602206.
#Sta/Elev= 30
  4184.4  289.21  4192.8288.5487  4208.7 287.866  4241.2  286.64  4323.1279.3109
    4428  270.37  4693.1268.9634  4955.4  270.24  4975.8  268.67    4997  260.68
  4999.8  260.18    5003  260.68  5018.3  261.52  5026.7  269.45  5108.2  268.63
  5196.7272.5398  5295.8277.2628  5328.3  282.42  5333.4  280.65  5373.1  284.87
  5403.6  285.16  5431.6  287.48  5436.7  284.51  5483.3   292.7  5488.4  290.71
  5508.1294.5537  5525.9  298.89  5534.9  299.28    5540  297.29  5560.7  298.29
#Mann= 10 ,-1 , 0
  4184.4     .05       0  4192.8     .08       0  4208.7     .05       0
  4323.1     .12       0  4693.1     .05       0    4997     .04       0
    5003     .05       0  5196.7     .16       0  5295.8     .12       0
  5508.1     .16       0
Bank Sta=4955.4,5026.7
XS Rating Curve= 0 ,0
Exp/Cntr=0.3,0.1

Type RM Length L Ch R = 1 ,40747   ,89,89,89
BEGIN DESCRIPTION:
GASTON BRANCH 54.0
END DESCRIPTION:
XS GIS Cut Line= 3
      3670481.28     10603560.12      3670887.53     10602928.18
      3671179.21     10602205.91
#Sta/Elev= 30
    4144  298.04  4201.5  293.62  4215.2  287.67  4292.9283.6555  4331.6   283.8
  4355.7 279.749  4406.7274.3824  4550.4268.2904  4634.2268.1028    4828267.9589
  4957.8  269.49  4979.4  260.24    4997  259.64  4999.8  259.14    5003  259.64
  5011.7  260.72  5024.4  269.97  5072.8269.2489  5176.9270.2918  5204.2  270.67
  5216.6  273.17  5227.4  271.02  5254.3271.6029  5335.3  274.94  5489.4291.1504
  5546.6296.2776  5593.5300.2346  5633.5  302.48  5638.9  306.99  5674.2  307.84
#Mann= 15 ,-1 , 0
    4144     .05       0  4292.9     .08       0  4355.7      .1       0
  4406.7     .05       0  4550.4     .16       0  4634.2     .05       0
    4828     .12       0    4997     .07       0    5003     .12       0
  5072.8     .16       0  5176.9     .05       0  5254.3     .16       0
  5489.4     .05       0  5546.6     .12       0  5593.5     .16       0
Bank Sta=4957.8,5024.4
XS Rating Curve= 0 ,0
Exp/Cntr=0.3,0.1

Type RM Length L Ch R = 1 ,40658   ,502,502,502
BEGIN DESCRIPTION:
Mapping XS 0572cb1f
END DESCRIPTION:
XS GIS Cut Line= 3
      3670519.46     10603660.83      3670960.44     10602983.73
      3671248.22     10602214.01
#Sta/Elev= 30
  4085.7  287.84  4223.6  288.99  4350.7286.7364    4406279.1442  4483.1  270.62
    4579266.9174  4598.8267.2231  4824.2  266.17  4959.5  268.91  4972.3   267.1
  4989.8  259.21    4997  259.13  4999.8  258.63    5003  259.13  5025.6  267.17
    5045  269.54  5135.9  267.78  5228.4269.3962  5345.9  271.45  5392.5   274.4
  5461.4282.1709  5508.3  288.99  5533.3  295.73  5563.6  297.69  5588.5  302.34
  5593.9  301.02  5641.2 305.924  5649.1  304.52  5672.1308.2765  5715.5  312.08
#Mann= 11 ,-1 , 0
  4085.7     .05       0  4350.7      .1       0    4406     .12       0
    4579     .16       0  4598.8     .12       0    4997     .07       0
    5003     .12       0  5228.4     .16       0  5461.4     .12       0
  5641.2     .16       0  5672.1     .12       0
Bank Sta=4959.5,5045
XS Rating Curve= 0 ,0
Exp/Cntr=0.3,0.1

Type RM Length L Ch R = 1 ,40156   ,264,264,264
BEGIN DESCRIPTION:
Mapping XS ee8e3bb1
END DESCRIPTION:
XS GIS Cut Line= 3
      3670845.82     10603587.93      3671311.14     10603199.01
      3671863.22     10603011.51
#Sta/Elev= 30
  4294.1  299.11    4302  300.94  4310.4296.0859  4351.4  298.38  4387.8  294.78
  4394.4  298.47    4423  294.41  4486.8  298.01  4507.6  295.67  4515.4  291.44
  4536.2  293.86    4544  288.38  4564.8  285.69  4572.6  278.93  4593.5  271.82
  4657.2  264.52  4962.3  268.22  4971.1  267.22  4976.4  259.25    4997   258.4
  4999.8   257.9    5003   258.4  5039.2  267.79  5120.7  265.84  5152.4  267.96
  5196.1  275.01  5268.6  303.51  5316.4  307.79  5390.6308.1366  5483.6  308.16
#Mann= 5 ,-1 , 0
  4294.1     .05       0  4310.4     .12       0    4997     .07       0
    5003     .12       0  5390.6     .16       0
Bank Sta=4962.3,5039.2
XS Rating Curve= 0 ,0
Exp/Cntr=0.3,0.1

Type RM Length L Ch R = 1 ,39892   ,293,293,293
BEGIN DESCRIPTION:
GASTON BRANCH 53.0
END DESCRIPTION:
XS GIS Cut Line= 2
      3670668.74     10603907.36      3671862.82     10603174.95
#Sta/Elev= 30
  4001.5   302.7  4049.6  300.64  4059.2  297.11  4080.5  296.06  4101.8  298.29
  4153.9  293.76  4159.8  296.12  4217.8  293.81  4260.6  286.46  4275.8  286.74
    4328  275.91  4401.4  270.22  4697.4  263.76  4975.7   267.7  4981.6  267.06
    4997  258.15  4999.8  257.65    5003  258.15  5024.2   260.4  5046.6  266.95
    5055  262.79  5070.1  263.63  5163.9  273.72  5192.4  280.62  5199.1  285.61
  5213.6  288.06  5244.5  299.51  5265.8  303.35  5386.8307.5722  5402.3  307.65
#Mann= 4 ,-1 , 0
  4001.5     .12       0    4997     .07       0    5003     .12       0
  5386.8     .16       0
Bank Sta=4975.7,5046.6
XS Rating Curve= 0 ,0
Exp/Cntr=0.3,0.1

Type RM Length L Ch R = 1 ,39599   ,410,410,410
BEGIN DESCRIPTION:
GASTON BRANCH 52.0
END DESCRIPTION:
XS GIS Cut Line= 3
      3671749.61      10604210.2      3671599.61     10603610.19
       3671749.6     10603460.19
#Sta/Elev= 30
    4425  295.43    4443  290.77  4469.4287.6316  4530.7  284.56  4538.4  281.37
  4571.5276.7285  4579.6  272.88    4608  268.23  4613.1  269.79  4641.5  266.15
  4703.3  262.35  4772.9  262.02    4943  265.94  4979.1  258.48    4997  257.85
  4999.8  257.35    5003  257.85  5012.6  257.99  5020.3  261.19  5025.4  258.64
  5033.2  261.78    5047  262.65  5057.6   265.5    5100  273.05  5114.2  278.71
  5128.3  280.39  5142.5  285.49  5156.6  286.39  5170.8  290.06  5255.6  290.72
#Mann= 5 ,-1 , 0
    4425     .05       0  4469.4      .1       0  4571.5     .12       0
    4997     .07       0    5003     .12       0
Bank Sta=4943,5057.6
XS Rating Curve= 0 ,0
Exp/Cntr=0.3,0.1

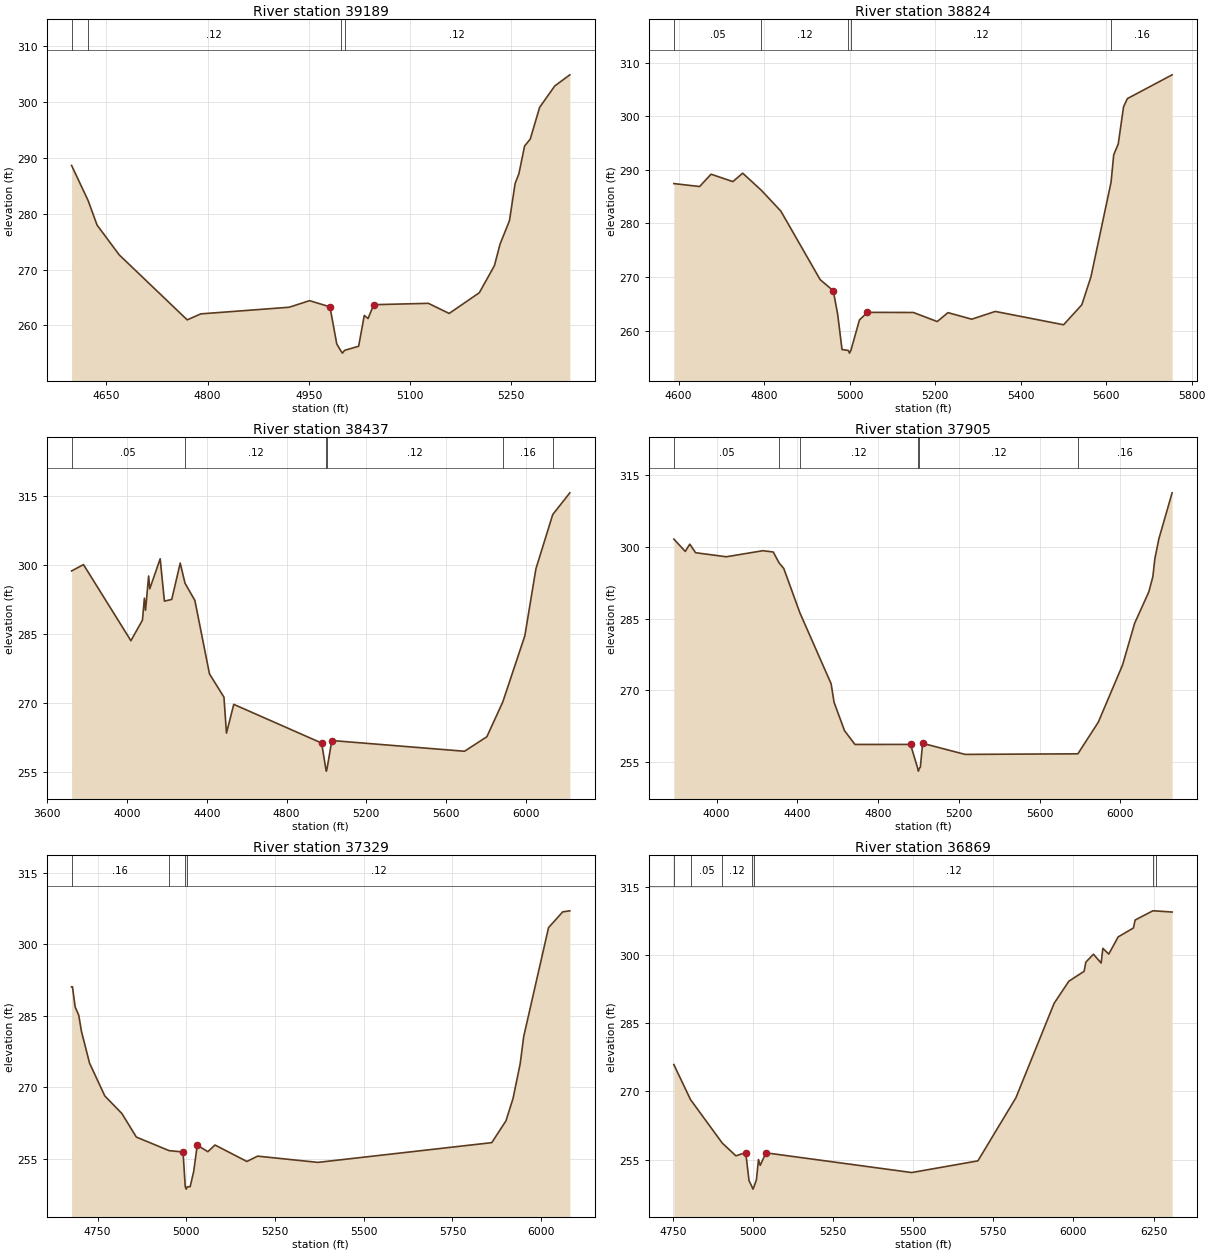
Type RM Length L Ch R = 1 ,39189   ,365,365,365
BEGIN DESCRIPTION:
GASTON BRANCH 51.0
END DESCRIPTION:
XS GIS Cut Line= 3
      3672049.61     10604060.22      3671999.61     10603660.19
      3671849.59     10603360.15
#Sta/Elev= 30
  4598.3  288.68  4622.8282.3896  4636.1  277.99  4668.9  272.66  4769.7  261.01
  4789.8  262.08  4920.8  263.27  4951.1  264.45  4981.3  263.34  4991.4   256.7
    4997  255.55  4999.8  255.05    5003  255.55  5023.8  256.28  5032.2   261.8
  5037.8  261.25  5046.2  263.73  5127.2  263.97    5158  262.16  5202.7  265.87
  5225.1  270.72  5233.4  274.56  5247.4  278.78  5255.8  285.46  5261.4  287.19
  5269.8  292.15  5278.2   293.4  5292.1  299.08  5314.5  302.91  5336.9  304.91
#Mann= 4 ,-1 , 0
  4598.3     .05       0  4622.8     .12       0    4997     .07       0
    5003     .12       0
Bank Sta=4981.3,5046.2
XS Rating Curve= 0 ,0
Exp/Cntr=0.3,0.1

Type RM Length L Ch R = 1 ,38824   ,387,387,387
BEGIN DESCRIPTION:
GASTON BRANCH 50.0
END DESCRIPTION:
XS GIS Cut Line= 3
      3672182.67     10604275.39      3672279.89     10603803.18
      3672044.19     10603161.94
#Sta/Elev= 30
    4589  287.42  4649.3  286.87    4676  289.17    4727  287.79    4750  289.36
  4793.8286.1595  4839.3  282.28  4931.2   269.5  4961.9  267.42  4972.1  263.06
  4982.3  256.46    4997  256.29  4999.8  255.79    5003  256.29  5023.1  261.98
  5041.7   263.4  5149.3  263.37  5204.9  261.68  5230.1  263.34  5285.7  262.12
  5340.7  263.57  5500.5  261.08  5543.1  264.81  5564.4  270.01  5611.5287.6777
  5617.7  292.78  5628.3  294.82  5640.7  301.74  5649.6  303.27  5754.3  307.71
#Mann= 5 ,-1 , 0
    4589     .05       0  4793.8     .12       0    4997     .07       0
    5003     .12       0  5611.5     .16       0
Bank Sta=4961.9,5041.7
XS Rating Curve= 0 ,0
Exp/Cntr=0.3,0.1

Type RM Length L Ch R = 1 ,38437   ,532,532,532
BEGIN DESCRIPTION:
GASTON BRANCH 49.0
END DESCRIPTION:
XS GIS Cut Line= 3
      3672040.32     10604841.35      3672644.47     10603858.73
      3672356.54     10602543.98
#Sta/Elev= 30
  3721.7  298.73  3781.5  300.11  4019.3  283.52  4077.3  288.02  4086.9  292.79
  4092.7  290.16  4108.2  297.63    4114  294.84  4166.1  301.38  4187.4  292.15
  4224.1  292.52  4266.7  300.44  4290.8296.0398  4340.1  292.31  4413.5  276.29
  4486.1  271.22  4498.6  263.38  4535.3  269.65  4976.1  261.22    4997   255.6
  4999.8   255.1    5003   255.6  5027.2  261.77  5692.7  259.43  5804.8  262.59
    5885270.2038  5995.5  284.62  6050.9  299.19  6135.2311.0113  6221.1  315.75
#Mann= 6 ,-1 , 0
  3721.7     .05       0  4290.8     .12       0    4997     .07       0
    5003     .12       0    5885     .16       0  6135.2     .05       0
Bank Sta=4976.1,5027.2
XS Rating Curve= 0 ,0
Exp/Cntr=0.3,0.1

Type RM Length L Ch R = 1 ,37905   ,576,576,576
BEGIN DESCRIPTION:
GASTON BRANCH 48.0
END DESCRIPTION:
XS GIS Cut Line= 3
      3673404.89     10604924.72      3673127.11     10603931.65
      3673182.64     10602494.71
#Sta/Elev= 30
  3787.9  301.64  3844.5  299.06  3866.8  300.58  3895.8  298.79  4047.9  297.94
  4228.7  299.21  4280.6  298.94  4309.4296.6592  4332.6   295.5  4412.3286.2325
  4567.4  271.36  4581.8   267.5  4633.7  261.55  4685.6  258.67  4960.7  258.68
    4997  253.59  4999.8  253.09    5003  253.59  5009.5  253.92  5020.7  258.91
  5230.9  256.59  5790.1256.7098  5891.4  263.34  6011.4  275.29  6071.5  284.04
  6141.5  290.58  6161.6  293.77  6171.6  297.53  6191.6  301.72  6257.1  311.32
#Mann= 6 ,-1 , 0
  3787.9     .05       0  4309.4     .16       0  4412.3     .12       0
    4997     .07       0    5003     .12       0  5790.1     .16       0
Bank Sta=4960.7,5020.7
XS Rating Curve= 0 ,0
Exp/Cntr=0.3,0.1

Type RM Length L Ch R = 1 ,37329   ,460,460,460
BEGIN DESCRIPTION:
GASTON BRANCH 47.0
END DESCRIPTION:
XS GIS Cut Line= 3
      3673599.61     10604210.16      3673649.61     10603910.19
      3673649.61      10602810.2
#Sta/Elev= 30
  4676.7  291.12  4679.2  291.12  4686.8   286.9  4696.9  285.15  4704.6  281.74
  4727.4   275.1  4770.4  268.22  4818.6  264.53  4859.2   259.6  4951.5256.7528
  4990.8  256.47    4997  249.18  4999.8  248.68    5003  249.18  5010.8  249.18
  5020.8  252.38  5030.8   257.9  5060.8  256.53  5080.8  257.93  5170.8  254.48
  5200.8   255.6  5370.8  254.29  5860.8  258.43  5900.8  263.01  5920.8  267.72
  5940.8  274.96  5950.8  280.68  6020.8  303.53  6060.8  306.84  6080.8  307.05
#Mann= 4 ,-1 , 0
  4676.7     .16       0  4951.5     .12       0    4997     .07       0
    5003     .12       0
Bank Sta=4990.8,5030.8
XS Rating Curve= 0 ,0
Exp/Cntr=0.3,0.1

Type RM Length L Ch R = 1 ,36869   ,458,458,458
BEGIN DESCRIPTION:
GASTON BRANCH 46.0
END DESCRIPTION:
XS GIS Cut Line= 3
      3674049.61     10604210.16      3674099.61     10603960.19
       3674599.6     10602760.21
#Sta/Elev= 30
    4753   275.9    4805268.1927  4904.2258.6083  4946.7  255.81  4977.3  256.53
  4987.5  250.38    4997  248.98  4999.8  248.48    5003  248.98  5010.6  250.52
  5017.1     255  5022.5  253.71  5040.4  256.47  5495.4  252.13  5701.8   254.7
  5820.4  268.59  5939.6  289.37  5985.6  294.25  6033.3  296.43  6038.7  298.46
  6062.5  300.19  6086.4  298.25  6091.8  301.48  6110.2  300.23  6139.5     304
  6187.1  305.97  6192.5  307.72  6247.6309.7454  6257.9309.7161  6307.9  309.48
#Mann= 7 ,-1 , 0
    4753     .16       0    4805     .05       0  4904.2     .12       0
    4997     .07       0    5003     .12       0  6247.6     .16       0
  6257.9     .12       0
Bank Sta=4977.3,5040.4
XS Rating Curve= 0 ,0
Exp/Cntr=0.3,0.1

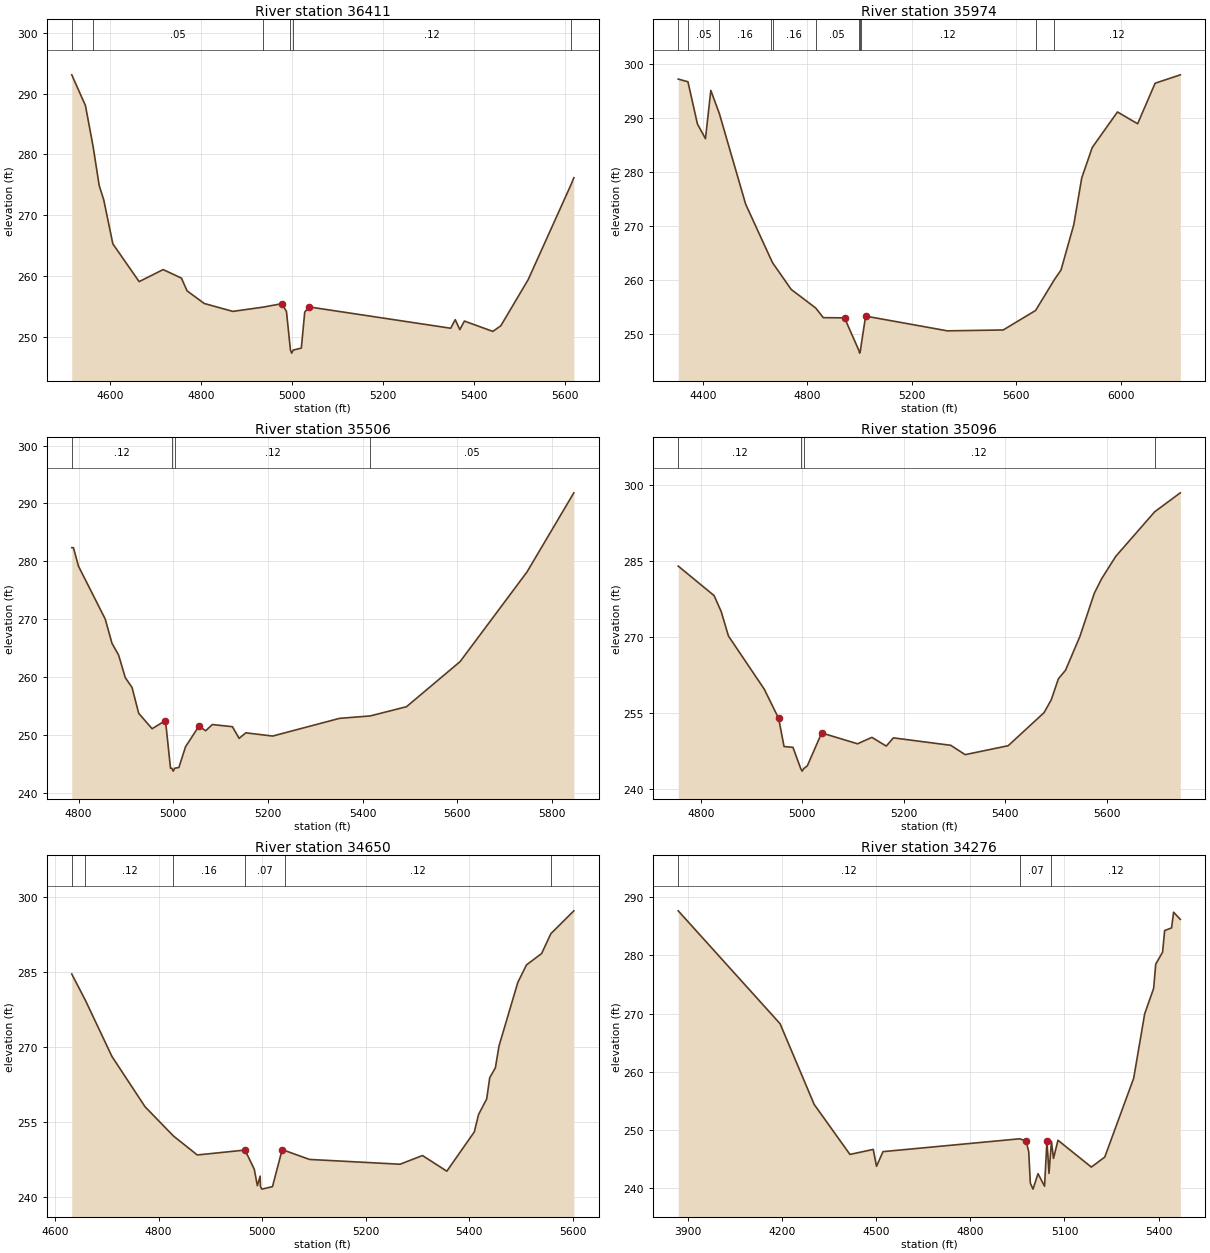
Type RM Length L Ch R = 1 ,36411   ,437,437,437
BEGIN DESCRIPTION:
GASTON BRANCH 45.0
END DESCRIPTION:
XS GIS Cut Line= 3
      3674449.61     10604360.15      3674499.61     10603860.19
      3674549.61     10603260.22
#Sta/Elev= 30
  4515.9  293.08    4546  288.03  4562.8281.3226  4576.2   274.9  4586.2  272.54
  4606.3   265.3  4664.1  259.09  4716.9  261.07  4757.1  259.67  4769.6  257.57
  4807.3   255.5  4870.1   254.2    4937254.9013  4978.2  255.47  4988.2  254.18
    4997  247.84  4999.8  247.34    5003  247.84  5020.9  248.17  5028.4  254.08
  5038.4  254.93  5349.5  251.43  5359.5  252.84  5369.6   251.2  5379.6  252.61
  5442.3  250.91  5459.9  251.85  5520.1  259.44  5614.8275.1325  5620.4  276.17
#Mann= 6 ,-1 , 0
  4515.9     .16       0  4562.8     .05       0    4937     .12       0
    4997     .07       0    5003     .12       0  5614.8     .16       0
Bank Sta=4978.2,5038.4
XS Rating Curve= 0 ,0
Exp/Cntr=0.3,0.1

Type RM Length L Ch R = 1 ,35974   ,468,468,468
BEGIN DESCRIPTION:
GASTON BRANCH 44.0
END DESCRIPTION:
XS GIS Cut Line= 3
      3674995.17     10604641.86      3674864.96     10604074.15
      3675047.25     10602746.06
#Sta/Elev= 30
  4305.1  297.26  4342.3296.7636  4378.6  288.95  4409.4  286.22  4429.9  295.16
  4462.6290.8721  4563.3  274.09  4660.1  263.87  4667.3263.1665  4737.7  258.29
  4831.7254.8393  4860.8  253.05    4942  253.02    4997  246.98  4999.8  246.48
    5003  246.98  5004.9247.6831  5022.8  253.34  5335.7  250.61  5549.8  250.77
  5673.8254.3835  5745.8 260.094  5771.1  261.87  5820.2   270.3  5850.5  278.94
  5890.8  284.58  5987.4  291.17  6064.6  288.98  6131.6  296.49  6228.1  298.05
#Mann= 11 ,-1 , 0
  4305.1     .12       0  4342.3     .05       0  4462.6     .16       0
  4660.1     .12       0  4667.3     .16       0  4831.7     .05       0
    4997     .03       0    5003     .05       0  5004.9     .12       0
  5673.8     .16       0  5745.8     .12       0
Bank Sta=4942,5022.8
XS Rating Curve= 0 ,0
Exp/Cntr=0.3,0.1

Type RM Length L Ch R = 1 ,35506   ,410,410,410
BEGIN DESCRIPTION:
GASTON BRANCH 43.0
END DESCRIPTION:
XS GIS Cut Line= 3
       3675149.6      10604160.2      3675299.61     10604010.19
      3675899.63     10603410.17
#Sta/Elev= 30
  4785.5  282.36    4789  282.36  4799.7  279.16  4856.2  270.02  4870.4  265.85
  4884.5  263.79  4898.6  259.89  4912.8  258.21  4926.9  253.73  4955.2  251.07
  4983.5  252.48  4994.1  244.24    4997  244.24  4999.8  243.74    5003  244.24
  5011.8  244.37  5025.9  247.96  5054.2  251.52  5068.4  250.72  5082.5  251.79
  5124.9  251.42  5139.1   249.4  5153.2  250.36  5209.8   249.8  5351.2  252.86
  5415.9253.2782  5492.6  254.87  5605.8  262.66  5747.2  278.16  5846.2  291.84
#Mann= 4 ,-1 , 0
  4785.5     .12       0    4997     .07       0    5003     .12       0
  5415.9     .05       0
Bank Sta=4983.5,5054.2
XS Rating Curve= 0 ,0
Exp/Cntr=0.3,0.1

Type RM Length L Ch R = 1 ,35096   ,446,446,446
BEGIN DESCRIPTION:
GASTON BRANCH 42.0
END DESCRIPTION:
XS GIS Cut Line= 3
      3675449.63     10604410.17      3675599.61     10604260.19
      3676149.59      10603710.2
#Sta/Elev= 30
  4755.5  283.96  4826.2  278.15  4840.3  274.97  4854.5  270.18  4925.2  259.68
  4953.5  253.92  4964.1  248.38  4981.7  248.22    4997  244.03  4999.8  243.53
    5003  244.03    5010  244.57  5038.3  251.06    5109  248.92  5137.3  250.19
  5165.6  248.47  5179.7  250.09  5292.9  248.62  5321.2  246.78    5406  248.54
  5476.7  255.06  5490.9  257.58    5505  261.73  5519.1  263.43  5547.4  270.08
  5575.7  278.57  5589.9  281.41  5618.1  285.88  5694.9294.6742  5745.4  298.41
#Mann= 4 ,-1 , 0
  4755.5     .12       0    4997     .07       0    5003     .12       0
  5694.9     .05       0
Bank Sta=4953.5,5038.3
XS Rating Curve= 0 ,0
Exp/Cntr=0.3,0.1

Type RM Length L Ch R = 1 ,34650   ,374,374,374
BEGIN DESCRIPTION:
GASTON BRANCH 41.0
END DESCRIPTION:
XS GIS Cut Line= 3
      3675749.64     10604610.17      3675999.61     10604410.19
       3676249.6     10603810.21
#Sta/Elev= 30
  4632.4  284.61  4658.9279.3286    4710  268.16    4774  258.11  4828.7252.2867
  4874.9  248.48  4967.1  249.46    4985  245.65    4991  242.34  4996.4  244.26
    4997  242.16  4999.8  241.66  5020.2  242.16  5038.6  249.41  5044.1  249.36
  5091.7  247.59  5266.7  246.63    5310  248.37  5357.1  245.24  5410.2  253.09
  5418.4  256.56  5434.1  259.67    5440  263.91  5450.9  265.89  5457.9  270.24
  5494.2  282.92    5511  286.43  5540.2   288.7  5558.1292.6623  5602.5  297.23
#Mann= 6 ,-1 , 0
  4632.4     .16       0  4658.9     .12       0  4828.7     .16       0
  4967.1     .07       0  5044.1     .12       0  5558.1     .05       0
Bank Sta=4967.1,5038.6
XS Rating Curve= 0 ,0
Exp/Cntr=0.3,0.1

Type RM Length L Ch R = 1 ,34276   ,488,488,488
BEGIN DESCRIPTION:
GASTON BRANCH 40.0
END DESCRIPTION:
XS GIS Cut Line= 3
      3676649.61     10605510.18      3676349.61     10604410.19
      3676649.58     10604060.22
#Sta/Elev= 30
  3868.4  287.62  4193.2  268.26    4302  254.41    4416  245.84  4490.3   246.7
  4500.7   243.8  4521.4  246.32  4956.7  248.52  4977.5  248.17  4986.1  246.31
  4991.3  240.91  4999.8  239.89  5015.7  242.54  5036.6  240.39  5044.2  248.18
  5050.8  242.59  5058.5  248.09  5065.1  245.16  5079.4  248.27  5185.8  243.67
  5228.6  245.39  5320.8  258.91  5355.9  269.96  5384.5  274.33  5391.1  278.48
    5413  280.53  5419.6  284.24  5441.6  284.69  5448.1  287.38  5469.5  286.16
#Mann= 3 ,-1 , 0
  3868.4     .12       0  4956.7     .07       0  5058.5     .12       0
Bank Sta=4977.5,5044.2
XS Rating Curve= 0 ,0
Exp/Cntr=0.3,0.1

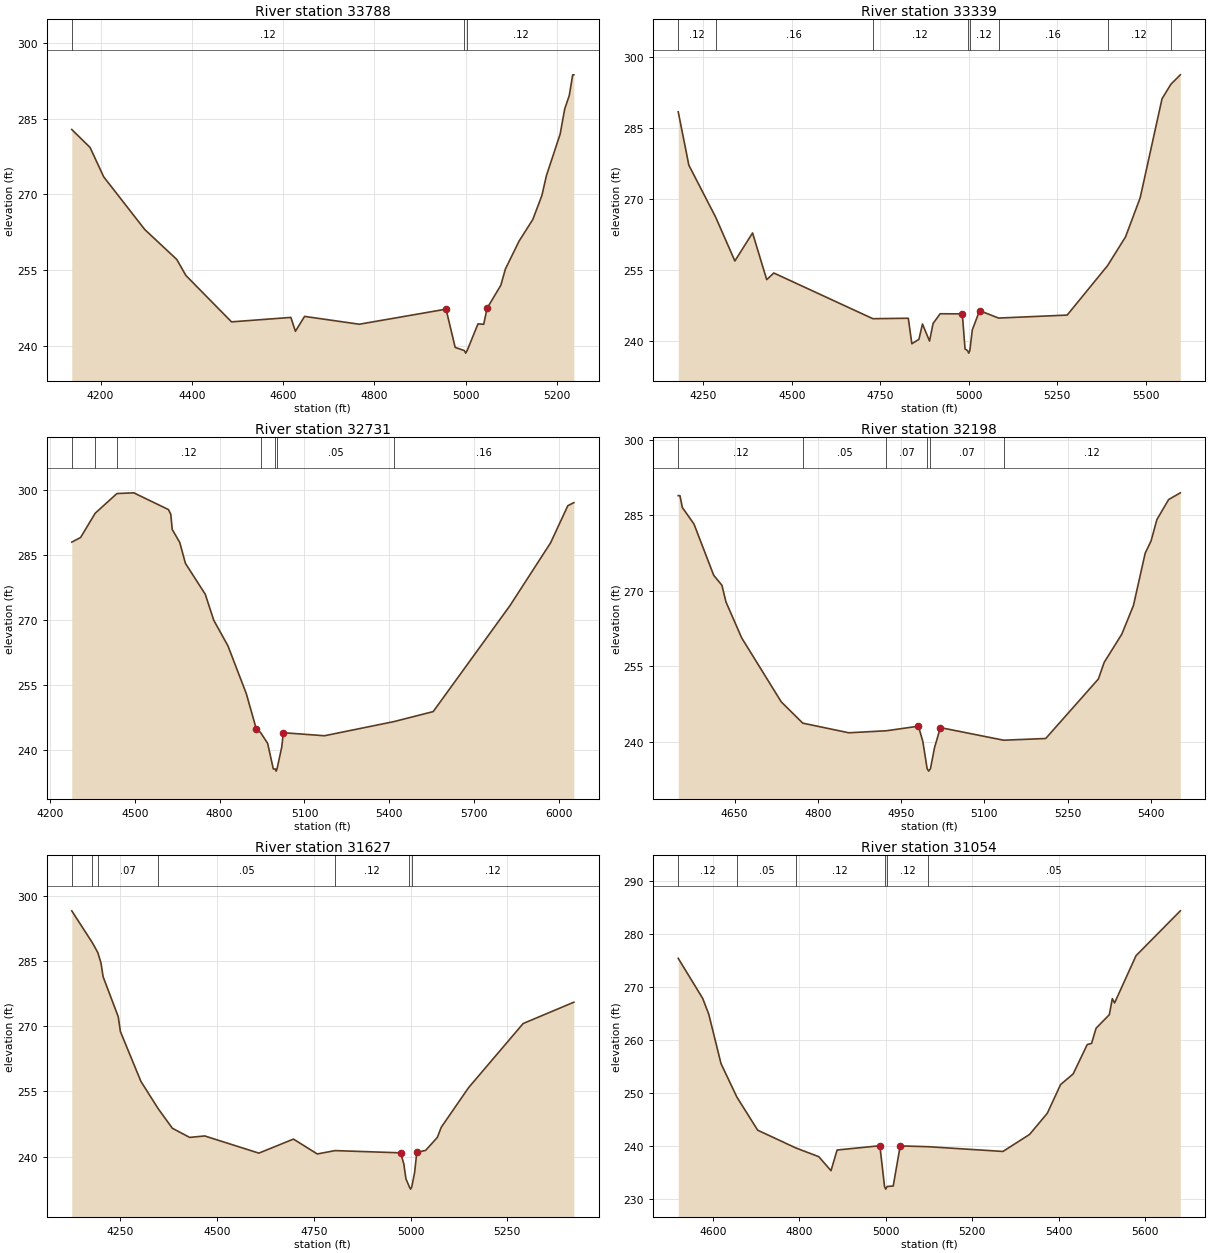
Type RM Length L Ch R = 1 ,33788   ,449,449,449
BEGIN DESCRIPTION:
GASTON BRANCH 39.0
END DESCRIPTION:
XS GIS Cut Line= 3
      3676749.61     10605360.16      3676749.61     10604460.19
      3676749.61     10604260.16
#Sta/Elev= 30
  4136.8  282.87  4176.8  279.32  4206.8  273.48  4296.8  263.03  4366.8  257.11
  4386.8  253.93  4486.8  244.73  4616.8  245.61  4626.8  242.86  4646.8  245.81
  4766.8  244.26  4956.8  247.25  4976.8  239.67    4997  239.03  4999.8  238.53
    5003  239.03  5026.8  244.33  5039.3  244.25  5046.8  247.44  5076.8  251.98
  5086.8   255.2  5116.8  260.74  5146.8  265.01  5166.8  269.78  5176.8  273.75
  5206.8  281.96  5216.8  286.95  5226.8  289.62  5234.3  293.71  5236.8  293.71
#Mann= 3 ,-1 , 0
  4136.8     .12       0    4997     .07       0    5003     .12       0
Bank Sta=4956.8,5046.8
XS Rating Curve= 0 ,0
Exp/Cntr=0.3,0.1

Type RM Length L Ch R = 1 ,33339   ,608,608,608
BEGIN DESCRIPTION:
GASTON BRANCH 38.0
END DESCRIPTION:
XS GIS Cut Line= 3
      3677149.61     10605510.18      3677149.61     10604710.19
       3676999.6     10604110.15
#Sta/Elev= 30
  4179.2   288.4  4209.2  277.14  4285.1266.1476  4339.2  256.93  4389.2  262.84
  4429.2  252.98  4449.2  254.39  4729.1244.7455  4829.2  244.84  4839.2  239.46
  4859.2  240.39  4869.2  243.62  4889.2  240.03  4899.2  243.74  4919.2  245.79
  4981.8  245.76  4989.5  238.37    4997  237.98  4999.8  237.48    5003  237.98
  5010.1  242.41  5030.7  246.45  5084.2244.8794  5278.1  245.51  5392.2255.9489
    5443  262.02  5484.3  270.26  5546.1  291.17  5571.4294.2546  5597.7  296.21
#Mann= 8 ,-1 , 0
  4179.2     .12       0  4285.1     .16       0  4729.1     .12       0
    4997     .07       0    5003     .12       0  5084.2     .16       0
  5392.2     .12       0  5571.4     .05       0
Bank Sta=4981.8,5030.7
XS Rating Curve= 0 ,0
Exp/Cntr=0.3,0.1

Type RM Length L Ch R = 1 ,32731   ,533,533,533
BEGIN DESCRIPTION:
GASTON BRANCH 37.0
END DESCRIPTION:
XS GIS Cut Line= 3
      3677701.47     10605651.25      3677636.37      10604796.2
      3677488.79     10603889.05
#Sta/Elev= 30
  4276.7   287.9  4307.9  288.96  4359.7294.5529  4436.5299.0773  4496.1  299.24
  4618.8  295.39  4627.2  294.27  4632.2  290.81  4658.9  287.81  4678.9  283.01
  4749.1   275.9  4779.2  269.91  4829.4  264.02  4894.3  253.03  4929.6  244.93
  4944.8244.0789  4969.8   241.6  4989.8   235.7    4997   235.7  4999.8   235.2
    5003   235.7  5019.9   240.8  5025.3  244.04  5170.7  243.34  5416.3 246.589
  5555.7   248.9  5827.2  273.28  5971.1  287.74  6031.9  296.27  6053.3  296.98
#Mann= 7 ,-1 , 0
  4276.7     .12       0  4359.7     .16       0  4436.5     .12       0
  4944.8     .05       0    4997     .03       0    5003     .05       0
  5416.3     .16       0
Bank Sta=4929.6,5025.3
XS Rating Curve= 0 ,0
Exp/Cntr=0.3,0.1

Type RM Length L Ch R = 1 ,32198   ,571,571,571
BEGIN DESCRIPTION:
GASTON BRANCH 36.0
END DESCRIPTION:
XS GIS Cut Line= 3
       3677899.6      10605210.2      3678149.61     10604860.19
      3678299.62     10604410.17
#Sta/Elev= 30
  4548.6  288.93  4551.7  288.93    4556  286.57  4576.9   283.3  4612.5  273.09
  4627.3   271.1  4634.6  267.78  4662.9  260.63  4734.2   247.9  4772.9243.6678
  4855.8  241.75  4923.5 242.149  4981.4  243.06  4989.3  239.98    4997  234.62
  4999.8  234.12    5003  234.62  5010.4  238.83  5020.9  242.78  5134.8240.2714
  5210.6  240.61  5305.5  252.45    5316  255.77  5347.7  261.37  5368.7  267.08
  5389.8  277.47  5400.4  279.91  5410.9  284.16    5432  288.15  5453.1  289.49
#Mann= 6 ,-1 , 0
  4548.6     .12       0  4772.9     .05       0  4923.5     .07       0
    4997     .07       0    5003     .07       0  5134.8     .12       0
Bank Sta=4981.4,5020.9
XS Rating Curve= 0 ,0
Exp/Cntr=0.3,0.1

Type RM Length L Ch R = 1 ,31627   ,573,573,573
BEGIN DESCRIPTION:
GASTON BRANCH 35.0
END DESCRIPTION:
XS GIS Cut Line= 3
      3678299.63     10605660.15      3678699.61     10604860.19
      3678649.61     10604460.18
#Sta/Elev= 30
  4124.4  296.57  4177.8289.1964  4191.7286.9524  4199.8  284.59  4205.4   281.4
  4244.5  272.19  4250.1  268.77  4303.2  257.28  4347.5251.0458  4384.3  246.51
    4429   244.4  4468.1  244.73  4607.9  240.78  4697.3  244.01  4758.8  240.59
  4804.8241.3587  4974.1  240.85  4982.4  238.35    4988  234.86    4997  232.99
  4999.8  232.49    5003  232.99  5010.4  236.32    5016  240.95  5038.9  241.41
  5069.2  244.41  5079.2  246.73  5149.8  255.85  5290.9  270.62  5421.9  275.53
#Mann= 7 ,-1 , 0
  4124.4     .07       0  4177.8     .12       0  4191.7     .07       0
  4347.5     .05       0  4804.8     .12       0    4997     .07       0
    5003     .12       0
Bank Sta=4974.1,5016
XS Rating Curve= 0 ,0
Exp/Cntr=0.3,0.1

Type RM Length L Ch R = 1 ,31054   ,481,481,481
BEGIN DESCRIPTION:
GASTON BRANCH 34.0
END DESCRIPTION:
XS GIS Cut Line= 3
      3679549.64     10605110.22      3679199.61     10604760.19
      3679049.61     10604110.18
#Sta/Elev= 30
  4519.5  275.45  4576.1  267.87  4590.2  264.87  4618.5  255.53  4655.2249.2025
  4703.4  242.93  4792.2239.5565  4844.8  237.92  4873.1  235.27  4887.2  239.18
  4986.2  239.99    4997  232.28  4999.8  231.78    5003  232.28  5017.1  232.37
  5033.3  239.96  5098.2239.8067  5271.1  238.91  5332.7  242.13  5373.7  246.13
  5404.5  251.57  5433.6  253.58  5466.1  259.13  5476.3  259.36  5486.6  262.22
  5517.4   264.8  5524.2  267.83  5529.4     267    5579  275.94  5681.6  284.44
#Mann= 6 ,-1 , 0
  4519.5     .12       0  4655.2     .05       0  4792.2     .12       0
    4997     .07       0    5003     .12       0  5098.2     .05       0
Bank Sta=4986.2,5033.3
XS Rating Curve= 0 ,0
Exp/Cntr=0.3,0.1

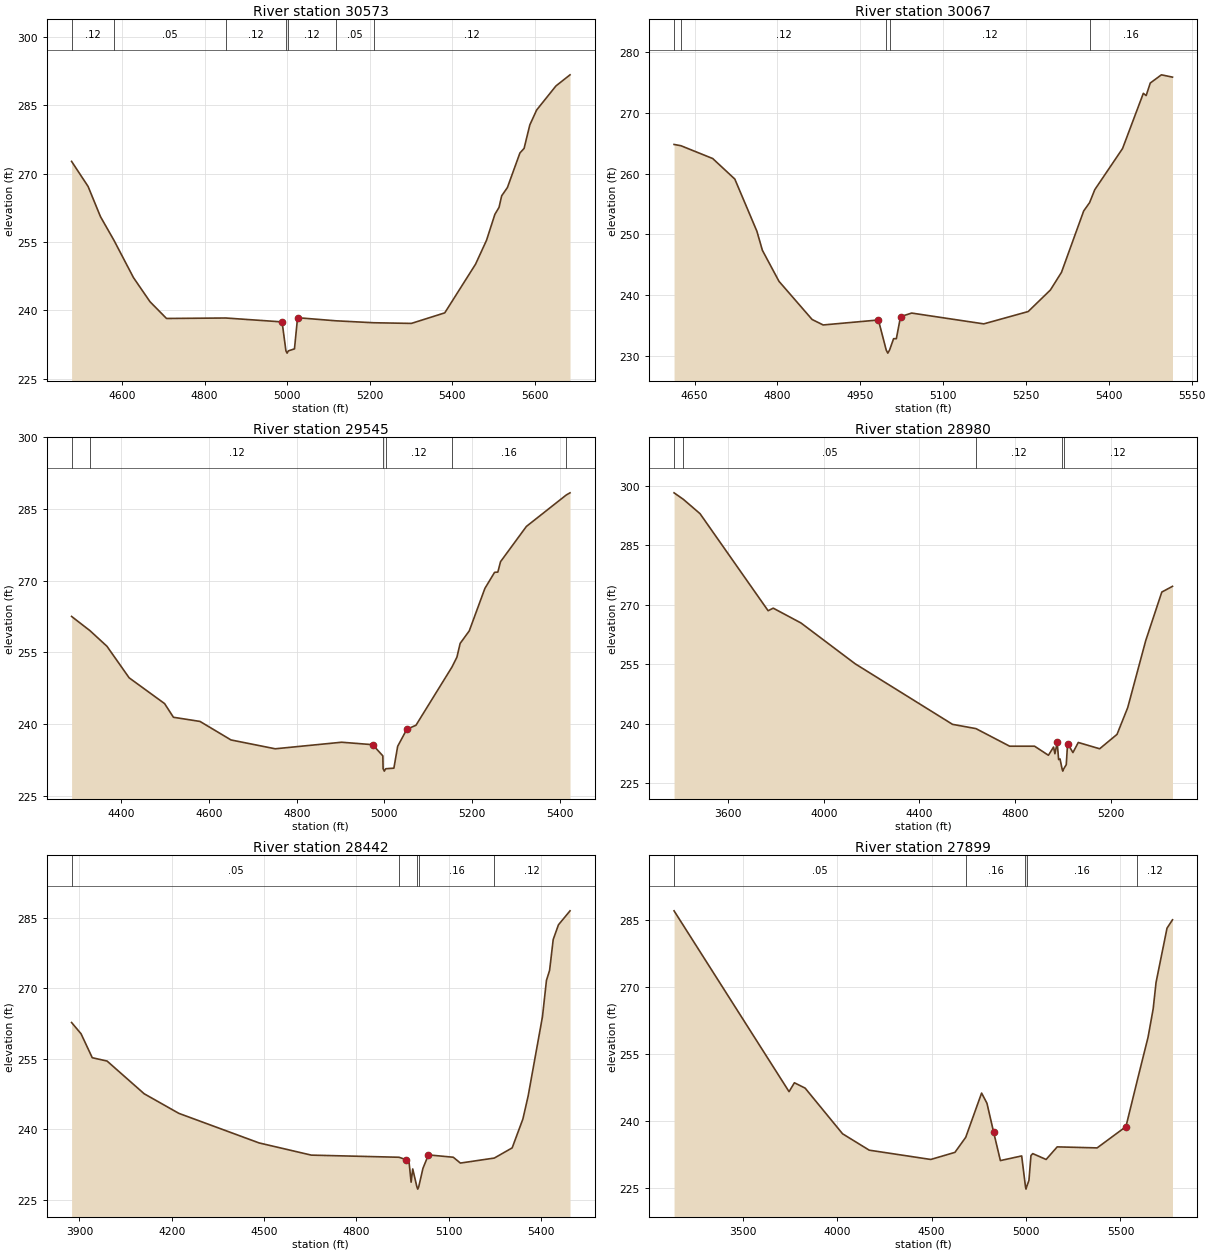
Type RM Length L Ch R = 1 ,30573   ,506,506,506
BEGIN DESCRIPTION:
GASTON BRANCH 33.0
END DESCRIPTION:
XS GIS Cut Line= 3
      3679599.61     10605060.17      3679599.61     10604510.19
       3679699.6     10603860.22
#Sta/Elev= 30
  4477.7  272.66  4517.7  267.17  4547.7  260.55  4580.2255.4025  4627.7  247.19
  4667.7  241.92  4707.7  238.25  4851.3238.3524  4987.7   237.5    4997  231.16
  4999.8  230.66    5003  231.16  5017.7  231.59  5025.2  238.42  5118.2237.7389
  5209.6237.3139  5300.9  237.17  5381.8  239.48  5456.4  250.14    5483  255.38
  5503.2  261.05  5513.3  262.59  5519.7  265.12  5533.6  266.93  5563.9   274.5
    5574  275.51  5587.9  280.65  5604.4  283.91  5651.2  289.19  5685.3  291.62
#Mann= 7 ,-1 , 0
  4477.7     .12       0  4580.2     .05       0  4851.3     .12       0
    4997     .07       0    5003     .12       0  5118.2     .05       0
  5209.6     .12       0
Bank Sta=4987.7,5025.2
XS Rating Curve= 0 ,0
Exp/Cntr=0.3,0.1

Type RM Length L Ch R = 1 ,30067   ,522,522,522
BEGIN DESCRIPTION:
GASTON BRANCH 32.0
END DESCRIPTION:
XS GIS Cut Line= 3
      3680099.61      10604910.2      3680099.61     10604510.19
      3680149.61     10604010.19
#Sta/Elev= 30
  4612.8   264.8  4625.3264.5875  4682.8  262.48  4722.8   259.1  4762.8   250.5
  4772.8  247.35  4802.8  242.25  4862.8  235.96  4882.8  235.06  4982.8  235.88
    4997  230.92  4999.8  230.42    5003  230.92  5010.3   232.8  5015.3   232.8
  5022.9  236.43    5043  237.02  5173.6  235.24    5254  237.27  5294.2  240.82
  5314.3  243.73  5354.5  253.84  5365.2255.2145  5374.6  257.35  5424.9  264.13
  5462.5  273.22  5467.6  272.85  5475.1  274.92  5495.2  276.27  5515.3  275.89
#Mann= 5 ,-1 , 0
  4612.8     .05       0  4625.3     .12       0    4997     .07       0
    5003     .12       0  5365.2     .16       0
Bank Sta=4982.8,5022.9
XS Rating Curve= 0 ,0
Exp/Cntr=0.3,0.1

Type RM Length L Ch R = 1 ,29545   ,565,565,565
BEGIN DESCRIPTION:
GASTON BRANCH 31.0
END DESCRIPTION:
XS GIS Cut Line= 3
       3680399.6     10604910.22      3680499.61     10604210.19
      3680249.58     10603860.15
#Sta/Elev= 30
  4286.2  262.53  4328.5259.5283    4367  256.28  4417.6  249.69  4498.4  244.31
  4518.6  241.45  4579.2  240.58  4649.9  236.71  4750.9  234.86  4902.4  236.23
  4973.1  235.72  4996.4  233.38    4997  230.69  4999.8  230.19    5003  230.69
  5021.6  230.81  5030.2  235.37  5051.1  238.94    5072  239.78    5154251.9313
  5165.4  254.01  5172.8  256.89  5193.6  259.51  5229.3   268.4  5251.4  271.75
  5258.8   271.8  5264.9  273.97  5323.9  281.34  5414.7287.9045  5423.5  288.37
#Mann= 6 ,-1 , 0
  4286.2     .05       0  4328.5     .12       0    4997     .07       0
    5003     .12       0    5154     .16       0  5414.7     .05       0
Bank Sta=4973.1,5051.1
XS Rating Curve= 0 ,0
Exp/Cntr=0.3,0.1

Type RM Length L Ch R = 1 ,28980   ,538,538,538
BEGIN DESCRIPTION:
GASTON BRANCH 30.0
END DESCRIPTION:
XS GIS Cut Line= 3
      3680199.59     10605510.23      3681049.61     10604110.19
      3680849.61     10603710.18
#Sta/Elev= 30
  3373.6  298.29  3412.3296.6533  3482.2  293.03  3767.1   268.5  3788.4  269.15
  3904.7   265.4  4131.5  255.08  4538.5  239.79  4636.4238.7159  4777.5  234.27
  4881.6  234.27  4939.7  231.98  4961.1  234.05  4966.9  232.37  4976.4  235.21
  4982.4  230.89  4988.3  231.05    4997  228.47  4999.8  227.97    5003  228.47
  5014.3  229.61  5019.9  234.94  5042.2  232.66  5064.6  235.21    5154  233.62
  5226.7  237.26  5271.4  244.02  5346.9  260.99    5414  273.22  5458.7  274.66
#Mann= 5 ,-1 , 0
  3373.6     .12       0  3412.3     .05       0  4636.4     .12       0
    4997     .07       0    5003     .12       0
Bank Sta=4976.4,5019.9
XS Rating Curve= 0 ,0
Exp/Cntr=0.3,0.1

Type RM Length L Ch R = 1 ,28442   ,543,543,543
BEGIN DESCRIPTION:
GASTON BRANCH 29.0
END DESCRIPTION:
XS GIS Cut Line= 3
      3681299.61     10605060.18      3681549.61     10603960.19
       3681349.6     10603510.17
#Sta/Elev= 30
  3874.4  262.73  3905.2  260.34  3941.6  255.25  3989.8  254.54  4110.3  247.59
  4223.1  243.42  4484.1  237.13  4653.8  234.54    4939234.0841  4961.4  233.58
  4971.7  232.97  4978.3  228.79  4983.5   231.6    4997  227.81  4999.8  227.31
    5003  227.81  5016.8  231.75  5034.6  234.59  5115.3  234.09  5138.5  232.85
  5248.8233.9162  5306.8  236.08  5341.7  242.23  5358.8  247.13  5405.3  263.98
  5418.3   271.7  5428.5  273.83  5440.2  280.38  5457.3  283.51  5494.9  286.48
#Mann= 5 ,-1 , 0
  3874.4     .05       0    4939     .16       0    4997     .07       0
    5003     .16       0  5248.8     .12       0
Bank Sta=4961.4,5034.6
XS Rating Curve= 0 ,0
Exp/Cntr=0.3,0.1

Type RM Length L Ch R = 1 ,27899   ,570,570,570
BEGIN DESCRIPTION:
GASTON BRANCH 28.0
END DESCRIPTION:
XS GIS Cut Line= 3
      3683299.63     10605210.21      3682049.61     10603810.19
      3681399.59     10603410.18
#Sta/Elev= 30
  3135.5  287.02  3744.6  246.54    3773  248.53  3829.8  247.33    4028  237.11
  4169.3  233.44  4495.3  231.36  4623.2  232.95  4680.4236.3188  4764.5  246.22
  4792.9  243.94    4828  237.51    4864  231.11  4976.8  232.15    4997  225.22
  4999.8  224.72    5003  225.22  5015.3  226.69  5025.9  232.23  5035.5  232.67
  5106.3  231.36    5165  234.18  5376.4  233.95    5529  238.71  5589.4249.1084
  5646.1  258.71  5673.2  265.05  5688.6  271.01  5746.6  283.14  5775.6  285.01
#Mann= 5 ,-1 , 0
  3135.5     .05       0  4680.4     .16       0    4997     .07       0
    5003     .16       0  5589.4     .12       0
Bank Sta=4828,5529
XS Rating Curve= 0 ,0
Exp/Cntr=0.3,0.1