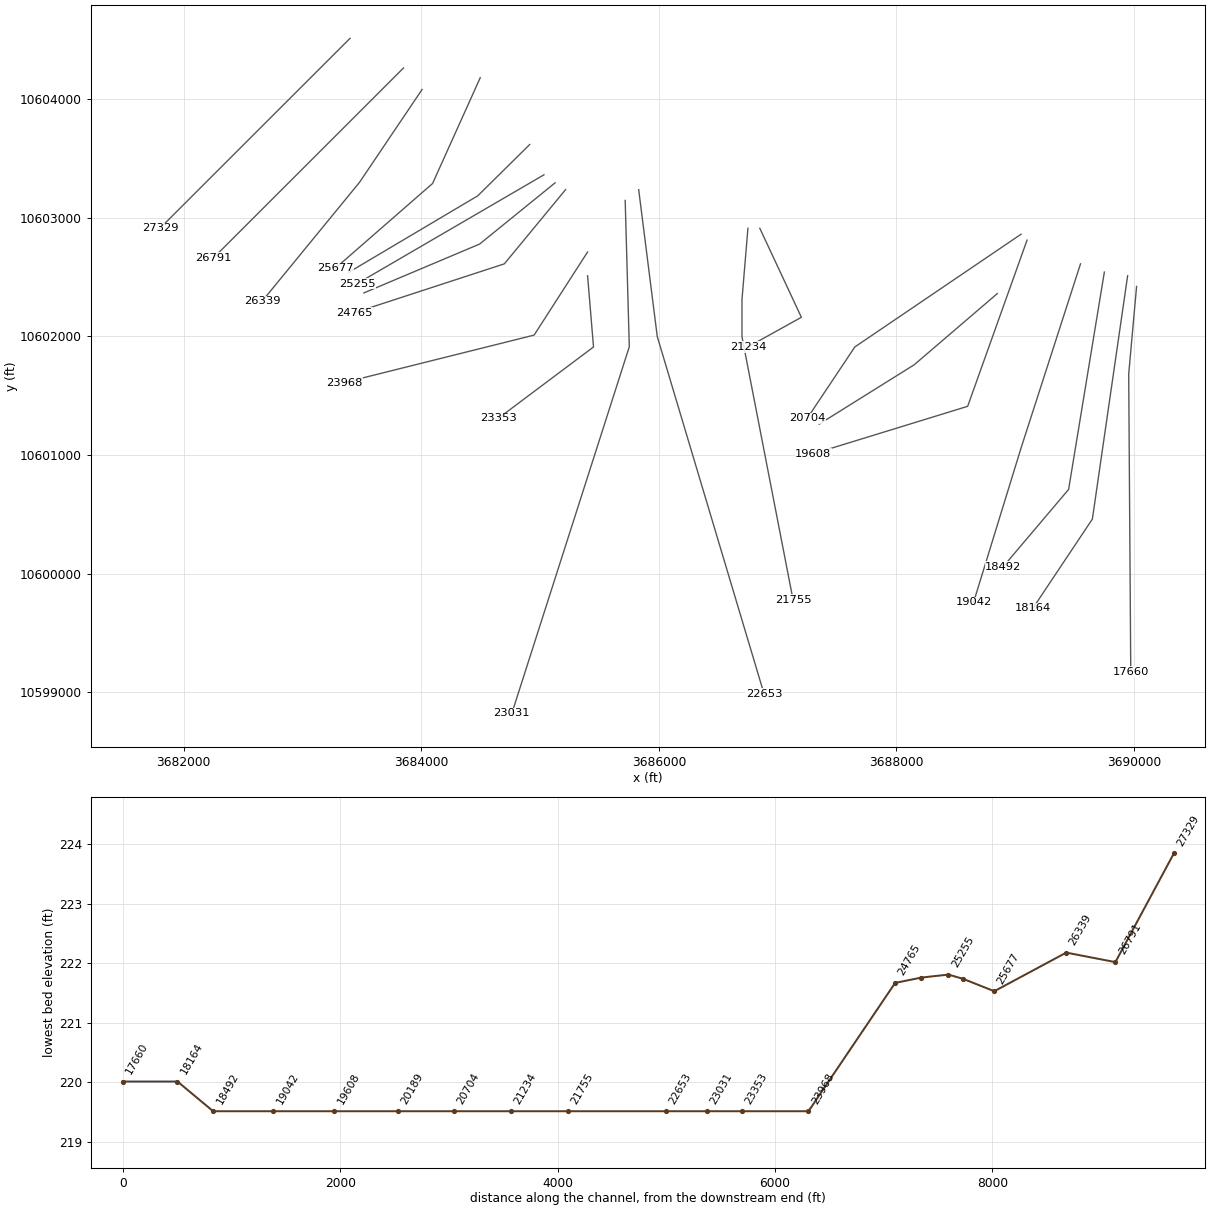
HEC-RAS study GASTON BRANCH.prj: GASTON BRANCH Base Level Engineering

--- GASTON BRANCH.g01 (geometry) --- (continued)

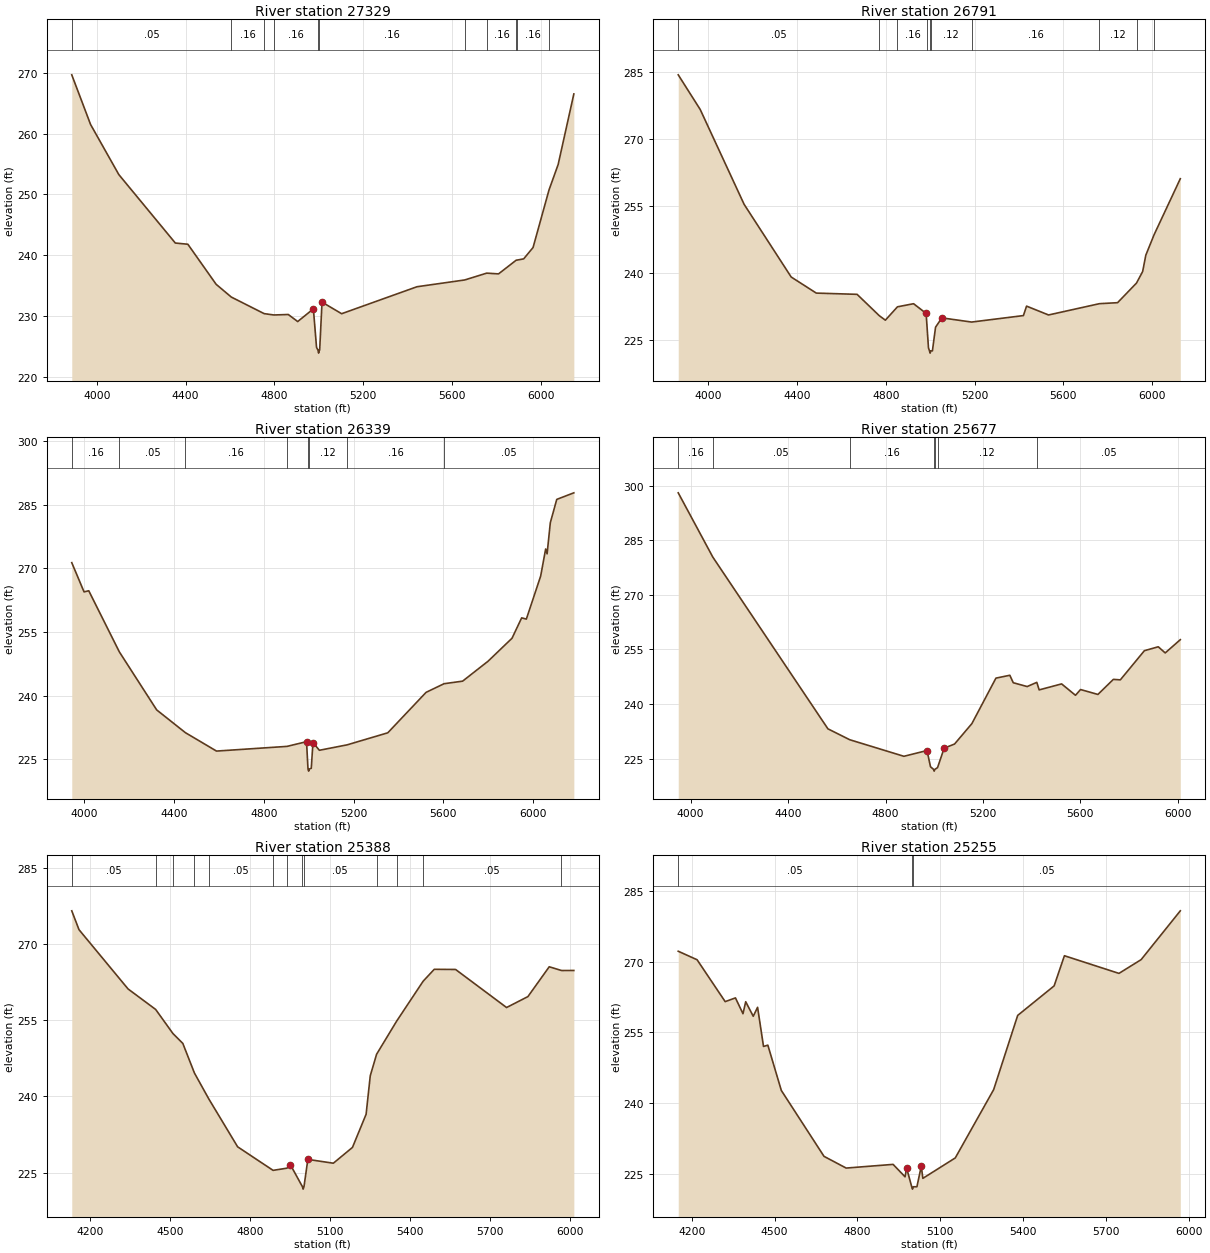
Type RM Length L Ch R = 1 ,27329   ,538,538,538
BEGIN DESCRIPTION:
GASTON BRANCH 27.0
END DESCRIPTION:
XS GIS Cut Line= 3
       3683399.6     10604510.18      3682599.61     10603710.19
      3681799.63     10602910.21
#Sta/Elev= 30
  3887.4  269.68  3972.2   261.5  4099.5  253.25  4354.1  241.98  4410.6  241.78
  4537.9  235.19  4606.1233.0885  4754.4230.3529  4798.4230.1321  4863.2  230.21
  4905.6  229.05  4976.3  231.14  4990.5  224.79    4997  224.35  4999.8  223.85
    5003  224.35  5004.6  224.35  5015.2  232.25  5103.6  230.34    5443  234.78
  5658.3235.8987  5757.3237.0216  5810.7   236.9  5890.7239.1635  5892.8 239.162
  5923.9  239.37  5966.3  241.24  6038.2250.7232  6079.4  254.91  6150.1  266.53
#Mann= 11 ,-1 , 0
  3887.4     .05       0  4606.1     .16       0  4754.4     .12       0
  4798.4     .16       0    4997     .07       0    5003     .16       0
  5658.3     .12       0  5757.3     .16       0  5890.7     .12       0
  5892.8     .16       0  6038.2     .12       0
Bank Sta=4976.3,5015.2
XS Rating Curve= 0 ,0
Exp/Cntr=0.3,0.1

Type RM Length L Ch R = 1 ,26791   ,452,452,452
BEGIN DESCRIPTION:
GASTON BRANCH 26.0
END DESCRIPTION:
XS GIS Cut Line= 3
       3683849.6     10604260.18      3683049.61     10603460.19
      3682249.63     10602660.21
#Sta/Elev= 30
  3864.6  284.37  3963.6  276.61  4161.6  255.35  4373.7  239.07  4486.8  235.47
  4670.7  235.19  4770.6230.4119    4798   229.4  4852.6232.3945  4925.2  233.09
  4981.8  230.92  4987.3226.9092  4992.4  223.19    4997  222.52  4999.8  222.02
    5003  222.52  5010.1  222.52  5024.2  227.82  5052.5  229.92  5186.8228.9813
  5420.2  230.43  5434.4  232.55  5533.4  230.57  5762.9233.0986  5844.5  233.32
  5929.9237.7166  5957.6   240.3  5971.8  243.96  6009.1248.5389  6127.3   261.1
#Mann= 10 ,-1 , 0
  3864.6     .05       0  4770.6     .12       0  4852.6     .16       0
  4987.3     .12       0    4997     .07       0    5003     .12       0
  5186.8     .16       0  5762.9     .12       0  5929.9     .16       0
  6009.1     .05       0
Bank Sta=4981.8,5052.5
XS Rating Curve= 0 ,0
Exp/Cntr=0.3,0.1

Type RM Length L Ch R = 1 ,26339   ,662,662,662
BEGIN DESCRIPTION:
GASTON BRANCH 25.0
END DESCRIPTION:
XS GIS Cut Line= 3
      3684006.18     10604079.22      3683480.12     10603297.94
       3682658.2     10602293.95
#Sta/Elev= 30
  3943.3  271.37  3998.1  264.48  4019.1  264.74  4155.7 250.302    4322  236.63
  4450.2231.2528  4588.9  226.91  4903.3228.0179  4990.4  229.13    4997  222.68
  4999.8  222.18    5003  222.68  5011.5  222.85  5019.1  228.92  5047.8   227.1
  5171.2228.3765  5352.8  231.22  5523.7  240.77  5603.9242.8077  5686.6  243.41
    5800  248.11    5907  253.54    5950  258.35  5970.8  258.05  6034.7   268.2
    6057   274.6  6063.4  273.45  6077.8  280.81  6106.5   286.3  6182.7  287.85
#Mann= 8 ,-1 , 0
  3943.3     .16       0  4155.7     .05       0  4450.2     .16       0
  4903.3     .12       0    4997     .07       0    5003     .12       0
  5171.2     .16       0  5603.9     .05       0
Bank Sta=4990.4,5019.1
XS Rating Curve= 0 ,0
Exp/Cntr=0.3,0.1

Type RM Length L Ch R = 1 ,25677   ,289,289,289
BEGIN DESCRIPTION:
Mapping XS 583b1f43
END DESCRIPTION:
XS GIS Cut Line= 3
      3684495.75     10604178.15       3684094.7     10603287.52
      3683277.69     10602574.59
#Sta/Elev= 30
  3949.1  298.07  4091.2280.3797  4563.6  233.16  4652.9230.1701  4875.5  225.61
  4970.4   227.2  4984.7  222.73    4997  222.03  4999.8  221.53    5003  222.03
  5013.6 222.493  5040.7  227.84  5083.4  228.98  5154.6   234.6  5253.3  247.11
  5310.3  247.89  5324.5  245.84  5381.5  244.79  5421.1245.9424  5430.8  243.87
  5522.9  245.52  5579.9  242.39  5600.7  243.97  5671.9  242.62  5735.5  246.77
    5764  246.63  5862.7  254.65  5919.7  255.73  5948.2  254.04  6010.2  257.68
#Mann= 7 ,-1 , 0
  3949.1     .16       0  4091.2     .05       0  4652.9     .16       0
    4997     .07       0    5003     .16       0  5013.6     .12       0
  5421.1     .05       0
Bank Sta=4970.4,5040.7
XS Rating Curve= 0 ,0
Exp/Cntr=0.3,0.1

Type RM Length L Ch R = 1 ,25388   ,133,133,133
BEGIN DESCRIPTION:
GASTON BRANCH 24.0
END DESCRIPTION:
XS GIS Cut Line= 3
      3684912.44     10603615.68      3684474.91     10603183.36
      3683386.37     10602537.53
#Sta/Elev= 30
  4133.1  276.51  4160.2   272.8  4344.1  261.13  4447.4257.1014    4512252.3677
  4549.1  250.42  4592.6244.5934    4646 239.533  4754.4  230.07  4887.2225.4333
  4939.2225.8631    4952  226.54    4997  222.24  4999.8  221.74    5003  222.24
  5017.5  227.59    5113  226.84  5184.6  229.95  5235.7  236.47  5251.3  244.05
    5275248.2852  5350.5 254.831  5449.4  262.66    5491     265  5570.9  264.97
  5761.9  257.48  5841.8  259.63  5921.7   265.5  5967.5264.7643  6013.9  264.77
#Mann= 13 ,-1 , 0
  4133.1     .05       0  4447.4     .08       0    4512     .05       0
  4592.6     .08       0    4646     .05       0  4887.2     .16       0
  4939.2     .05       0    4997     .04       0    5003     .05       0
    5275     .12       0  5350.5     .08       0  5449.4     .05       0
  5967.5     .08       0
Bank Sta=4952,5017.5
XS Rating Curve= 0 ,0
Exp/Cntr=0.3,0.1

Type RM Length L Ch R = 1 ,25255   ,249,249,249
BEGIN DESCRIPTION:
GASTON BRANCH 23.0
END DESCRIPTION:
XS GIS Cut Line= 2
      3685032.19     10603360.43      3683460.51     10602444.49
#Sta/Elev= 30
  4151.1  272.19  4219.4  270.39  4321.2  261.52  4358.4  262.31  4385.7  258.96
  4395.6   261.5  4422.9  258.42  4438.6  260.32  4460.1  252.03  4475.8   252.3
  4524.6  242.71  4679.3  228.75  4759.5  226.27  4929.6  227.05  4972.9  224.42
  4978.7  226.26    4997  222.31  4999.8  221.81    5003  222.31  5015.9  222.31
  5031.7  226.68  5037.4  224.09  5154.9  228.42  5293.9  242.88    5381   258.6
    5513  264.85  5550.3  271.24  5747.9   267.5  5828.2  270.41  5970.2  280.75
#Mann= 3 ,-1 , 0
  4151.1     .05       0    4997     .03       0    5003     .05       0
Bank Sta=4978.7,5031.7
XS Rating Curve= 0 ,0
Exp/Cntr=0.3,0.1

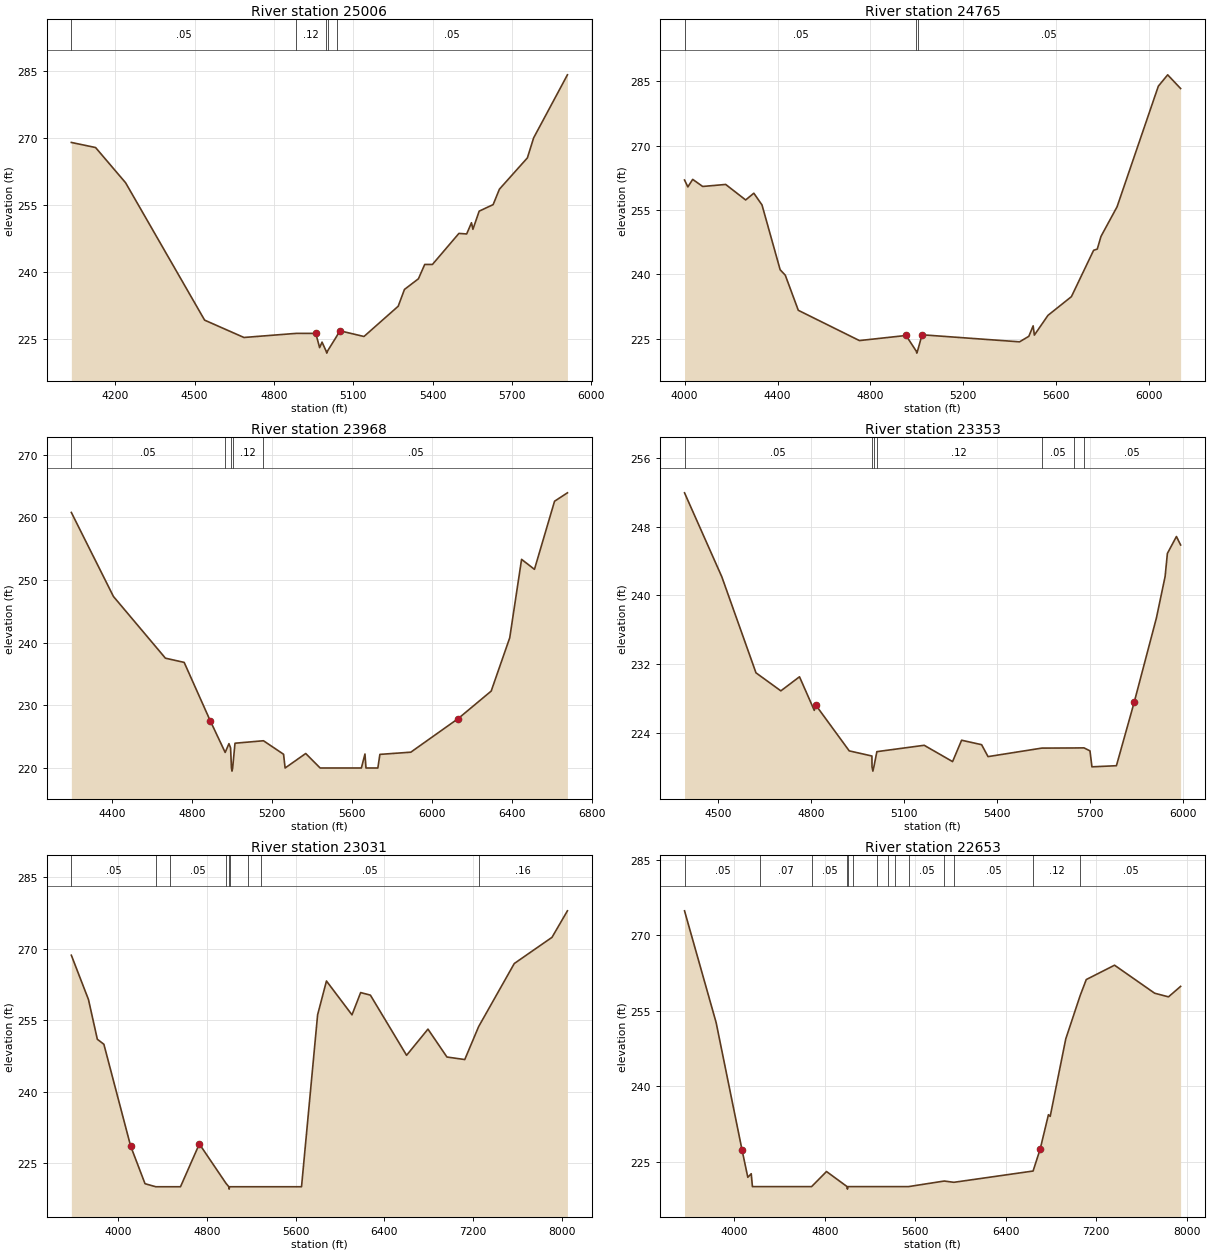
Type RM Length L Ch R = 1 ,25006   ,241,241,241
BEGIN DESCRIPTION:
Mapping XS e4c91d0f
END DESCRIPTION:
XS GIS Cut Line= 3
      3685125.94     10603292.72      3684490.54     10602777.11
      3683516.57     10602365.65
#Sta/Elev= 30
  4034.1  269.02  4125.7  267.88  4239.2  259.98    4538  229.16  4686.7  225.27
  4884.3226.1922  4958.3  226.18  4972.8  222.99    4982  224.23    4997  222.26
  4999.8  221.76    5003  222.26  5037.4225.5432  5048.8  226.78  5140.5  225.49
  5269.9  232.28  5293.6  236.05  5346.4  238.44  5370.1  241.65  5399.3  241.65
  5499.5  248.62  5528.7  248.49  5546.9  251.01  5552.4  249.54  5576.1  253.61
  5628.9  255.08  5652.6  258.54  5758.3  265.56    5782  270.05  5909.7  284.19
#Mann= 5 ,-1 , 0
  4034.1     .05       0  4884.3     .12       0    4997     .07       0
    5003     .12       0  5037.4     .05       0
Bank Sta=4958.3,5048.8
XS Rating Curve= 0 ,0
Exp/Cntr=0.3,0.1

Type RM Length L Ch R = 1 ,24765   ,797,797,797
BEGIN DESCRIPTION:
GASTON BRANCH 22.0
END DESCRIPTION:
XS GIS Cut Line= 3
      3685214.48     10603235.42      3684698.87     10602610.44
      3683438.44     10602198.98
#Sta/Elev= 30
  3999.6  261.97    4014  260.37  4034.8  262.12  4077.8  260.47  4176.8  260.94
  4262.8  257.33    4298   258.9  4333.2  256.17  4411.3  241.09  4433.5  239.81
  4489.5  231.64  4752.7  224.59  4953.3  225.78    4997  222.17  4999.8  221.67
    5003  222.17  5022.4  225.94  5442.2   224.3  5482.3  225.59  5500.7  228.02
    5506  225.87  5564.5  230.46  5665.5  234.82  5761.1  245.61  5776.8  245.89
    5793  248.86  5862.1  255.74  6039.8  283.82    6080  286.46  6135.7  283.27
#Mann= 3 ,-1 , 0
  3999.6     .05       0    4997     .03       0    5003     .05       0
Bank Sta=4953.3,5022.4
XS Rating Curve= 0 ,0
Exp/Cntr=0.3,0.1

Type RM Length L Ch R = 1 ,23968   ,615,615,615
BEGIN DESCRIPTION:
GASTON BRANCH 21.0
END DESCRIPTION:
XS GIS Cut Line= 3
      3685399.62     10602710.21      3684949.61     10602010.19
      3683349.64      10601610.2
#Sta/Elev= 30
  4196.1  260.76  4406.5  247.37  4666.7  237.52  4760.5  236.85  4890.6  227.56
  4965.6 222.492  4984.4  223.89  4992.6  223.23    4997  220.01  4999.8  219.51
    5003  220.01  5014.7  223.96  5157.1224.3543  5257.6   222.2  5265.4  220.01
  5368.4  222.32  5440.6  220.01  5646.8  220.01  5664.8  222.24  5669.9  220.01
  5729.2  220.01  5739.5  222.18  5894.1  222.53  6131.2  227.89  6296.1  232.27
  6388.9  240.77  6448.2  253.28  6512.6  251.69  6613.1  262.55  6677.5  263.89
#Mann= 5 ,-1 , 0
  4196.1     .05       0  4965.6     .12       0    4997     .07       0
    5003     .12       0  5157.1     .05       0
Bank Sta=4890.6,6131.2
XS Rating Curve= 0 ,0
Exp/Cntr=0.3,0.1

Type RM Length L Ch R = 1 ,23353   ,322,322,322
BEGIN DESCRIPTION:
GASTON BRANCH 20.0
END DESCRIPTION:
XS GIS Cut Line= 3
      3685399.61     10602510.22      3685449.61     10601910.19
      3684649.62      10601310.2
#Sta/Elev= 30
  4391.5  251.93  4511.9  242.15  4622.3  230.96  4702.6  228.86  4762.8   230.5
  4810.5  226.59  4815.5   227.2  4923.4  221.87  4996.7  221.27    4997  220.01
  4999.8  219.51    5003  220.01  5012.7221.7782  5165.5  222.52  5257.2  220.62
  5286.3  223.11  5350.9  222.59  5371.7   221.2  5545.3222.1914  5649.7222.2077
  5681.5  222.22  5700.9  221.87  5707.2  220.01  5786.3  220.14  5843.6  227.52
  5915.5  237.36  5943.6  242.19  5950.9  244.87  5980.1  246.84  5993.6  245.86
#Mann= 7 ,-1 , 0
  4391.5     .05       0    4997     .03       0    5003     .05       0
  5012.7     .12       0  5545.3     .05       0  5649.7     .12       0
  5681.5     .05       0
Bank Sta=4815.5,5843.6
XS Rating Curve= 0 ,0
Exp/Cntr=0.3,0.1

Type RM Length L Ch R = 1 ,23031   ,378,378,378
BEGIN DESCRIPTION:
GASTON BRANCH 19.0
END DESCRIPTION:
XS GIS Cut Line= 3
      3685716.23      10603144.7      3685750.95     10601912.09
      3684761.91     10598823.49
#Sta/Elev= 30
  3575.7  268.64  3730.3  259.33  3810.3  250.99  3869.3  249.94  4110.4  228.58
  4240.5  220.65  4337.7  220.01  4462.1  220.01  4560.6  220.01  4730.7     229
  4971.9220.7014    4997  220.01  4999.8  219.51    5003  220.01  5169.8  220.01
    5283  220.01  5652.7  220.01  5797.8  256.13  5877.7  263.23    6108  256.12
  6186.3   260.8    6274  260.26  6600.7  247.62  6793.5  253.12  6964.8  247.26
  7125.5  246.73  7250.9253.6547  7572.4   266.9  7912.7   272.4  8051.9  277.97
#Mann= 9 ,-1 , 0
  3575.7     .05       0  4337.7     .07       0  4462.1     .05       0
  4971.9     .12       0    4997     .07       0    5003     .12       0
  5169.8      .1       0    5283     .05       0  7250.9     .16       0
Bank Sta=4110.4,4730.7
XS Rating Curve= 0 ,0
Exp/Cntr=0.3,0.1

Type RM Length L Ch R = 1 ,22653   ,898,898,898
BEGIN DESCRIPTION:
GASTON BRANCH 18.0
END DESCRIPTION:
XS GIS Cut Line= 3
      3685829.95     10603235.26       3685986.2     10601998.32
      3686884.63      10598990.5
#Sta/Elev= 30
  3559.6  274.83    3839  252.62  4068.7  227.23  4119.1  221.86  4149.3  222.57
  4159.9  220.01  4229.4  220.01  4683.1  220.01  4814.9  223.01    4997  220.01
  4999.8  219.51    5003  220.01  5047.2  220.01  5257.4  220.01  5359.4  220.01
    5423  220.01  5539.8  220.01  5855.5221.1177  5940.9220.8658  6641.2223.1068
  6703.9  227.47  6776.9   234.3  6792.5  233.97  6930.2  249.38  7057.6257.9937
  7111.5  261.17  7361.4  264.02  7716.2  258.45  7838.4  257.73  7945.5  259.81
#Mann= 14 ,-1 , 0
  3559.6     .05       0  4229.4     .07       0  4683.1     .05       0
    4997     .03       0    5003     .05       0  5047.2     .12       0
  5257.4     .07       0  5359.4     .05       0    5423     .07       0
  5539.8     .05       0  5855.5     .12       0  5940.9     .05       0
  6641.2     .12       0  7057.6     .05       0
Bank Sta=4068.7,6703.9
XS Rating Curve= 0 ,0
Exp/Cntr=0.3,0.1

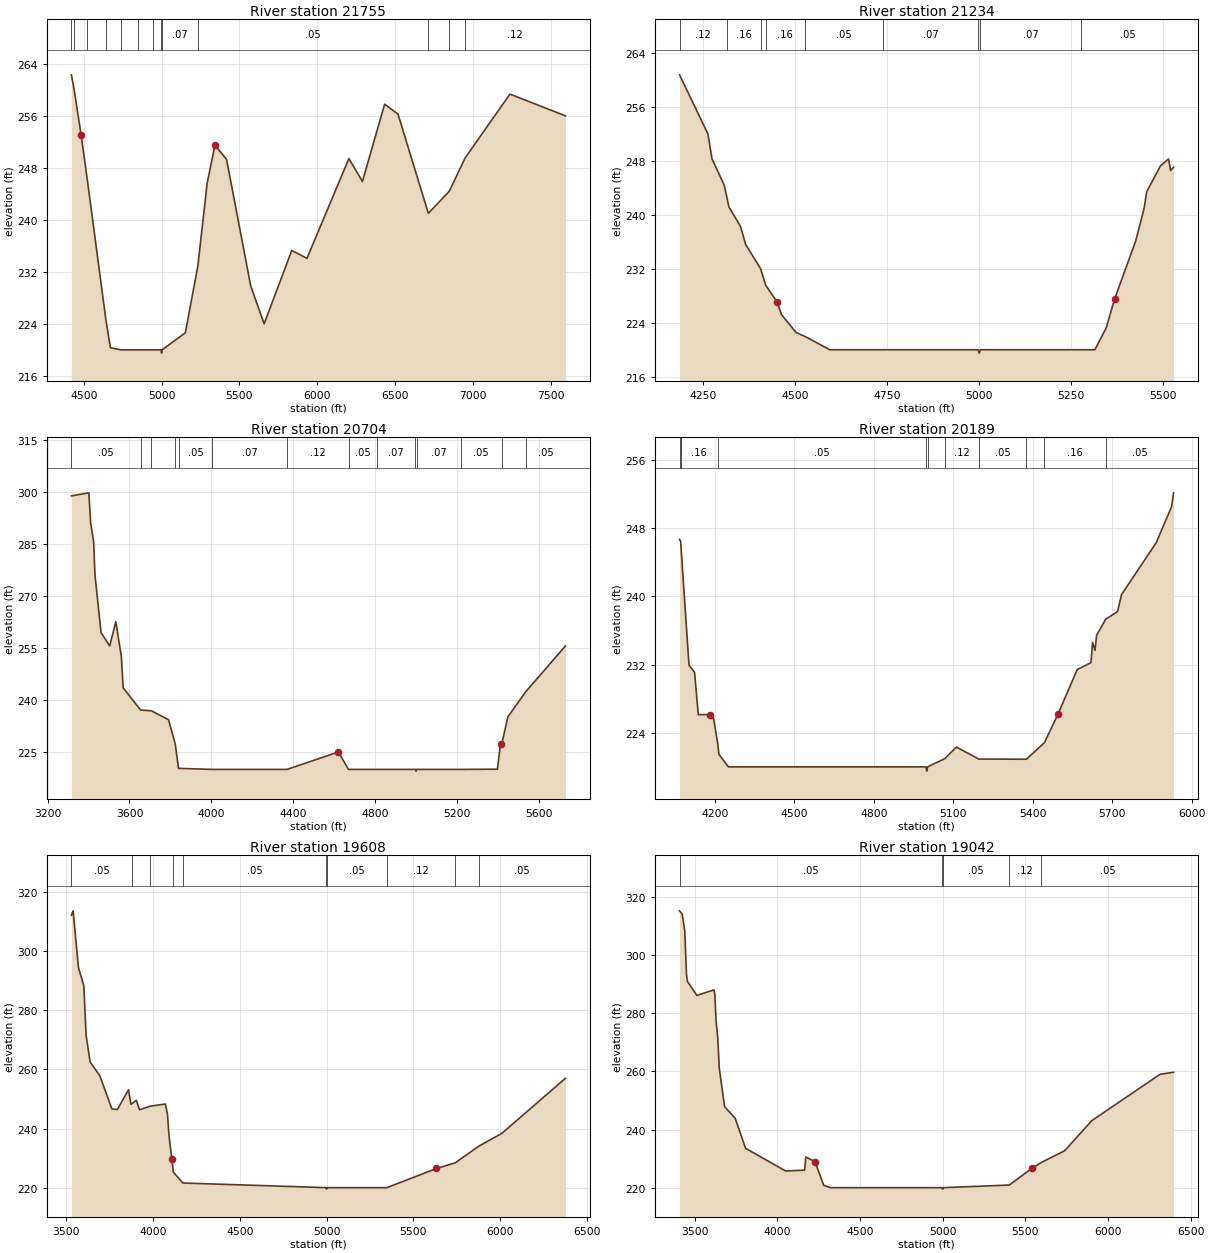
Type RM Length L Ch R = 1 ,21755   ,521,521,521
BEGIN DESCRIPTION:
GASTON BRANCH 17.0
END DESCRIPTION:
XS GIS Cut Line= 4
      3686749.61     10602910.17      3686699.61     10602310.19
      3686699.61     10601995.73      3687129.64      10599780.5
#Sta/Elev= 30
  4420.6  262.33  4437.8260.1389  4483.3  253.07  4523.3246.1454  4642.2224.6628
  4671.4  220.34  4740.9  220.01  4850.8  220.01  4942.9  220.01    4997  220.01
  4999.8  219.51    5003  220.01  5152.7  222.64  5233.2232.9435  5292.7  245.65
  5342.8   251.5  5417.5  249.31  5572.6  229.84  5658.6  224.02  5836.2  235.31
  5933.6  234.09  6203.2  249.45  6290.1  245.92  6432.7  257.81  6518.6  256.28
  6713.3241.0274    6848244.4147  6950.1249.5611  7237.5  259.36  7593.7  256.02
#Mann= 13 ,-1 , 0
  4420.6     .16       0  4437.8     .12       0  4523.3     .16       0
  4642.2     .05       0  4740.9     .07       0  4850.8     .05       0
  4942.9     .07       0    4997     .07       0    5003     .07       0
  5233.2     .05       0  6713.3     .12       0    6848     .05       0
  6950.1     .12       0
Bank Sta=4483.3,5342.8
XS Rating Curve= 0 ,0
Exp/Cntr=0.3,0.1

Type RM Length L Ch R = 1 ,21234   ,530,530,530
BEGIN DESCRIPTION:
GASTON BRANCH 16.0
END DESCRIPTION:
XS GIS Cut Line= 3
      3686849.63     10602910.14      3687199.61     10602160.19
      3686749.59     10601910.18
#Sta/Elev= 30
  4185.6  260.79  4262.8  252.01  4273.8  248.33  4306.9  244.44  4313.6242.7697
  4319.6  241.21  4351.1  238.32  4365.3  235.62  4405.6232.0652  4419.9229.5624
  4450.4   227.1  4462.2  225.25  4502.4  222.56  4526.2221.9955  4593.9  220.01
  4738.8  220.01    4997  220.01  4999.8  219.51    5003  220.01    5277  220.01
  5314.1  220.01  5344.9  223.26  5367.8  227.54    5425  236.14  5447.9  240.98
  5454.8  243.43  5492.5   247.3  5514.3  248.31    5520  246.61    5528  247.09
#Mann= 9 ,-1 , 0
  4185.6     .12       0  4313.6     .16       0  4405.6     .05       0
  4419.9     .16       0  4526.2     .05       0  4738.8     .07       0
    4997     .07       0    5003     .07       0    5277     .05       0
Bank Sta=4450.4,5367.8
XS Rating Curve= 0 ,0
Exp/Cntr=0.3,0.1

Type RM Length L Ch R = 1 ,20704   ,515,515,515
BEGIN DESCRIPTION:
GASTON BRANCH 15.0
END DESCRIPTION:
XS GIS Cut Line= 3
      3689049.63      10602860.2      3687649.61     10601910.19
      3687249.63     10601310.21
#Sta/Elev= 30
  3316.3  298.97  3401.7  299.85  3410.6  291.09  3425.1  285.74  3431.6  276.14
  3461.3  259.49  3503.5  255.64  3533.4  262.67  3560.4  252.58  3569.3  243.56
  3654.4237.1512  3707.6236.9324    3791  234.35  3824.1227.2127  3839.7220.3093
  4004.8  220.01  4369.8  220.01  4620.4  225.04  4669.9  220.01  4808.6  220.01
    4997  220.01  4999.8  219.51    5003  220.01  5217.9  220.01  5397.3  220.07
  5412.3  227.42  5418.7227.4158  5448.4  235.18  5536.2242.4674  5729.3  255.64
#Mann= 14 ,-1 , 0
  3316.3     .05       0  3654.4     .08       0  3707.6     .05       0
  3824.1     .16       0  3839.7     .05       0  4004.8     .07       0
  4369.8     .12       0  4669.9     .05       0  4808.6     .07       0
    4997     .07       0    5003     .07       0  5217.9     .05       0
  5418.7     .16       0  5536.2     .05       0
Bank Sta=4620.4,5412.3
XS Rating Curve= 0 ,0
Exp/Cntr=0.3,0.1

Type RM Length L Ch R = 1 ,20189   ,581,581,581
BEGIN DESCRIPTION:
GASTON BRANCH 14.0
END DESCRIPTION:
XS GIS Cut Line= 3
      3688849.63     10602360.21      3688149.61     10601760.19
       3687349.6     10601260.18
#Sta/Elev= 30
  4066.4  246.67  4070.5246.4485  4102.1  231.92    4123  231.11  4137.2  226.13
    4180  226.14  4194.3  225.81  4210.4222.7719  4215.2  221.47  4250.8  220.01
    4997  220.01  4999.8  219.51    5003  220.01  5067.5220.9624  5111.6  222.33
  5196.8220.9209  5376.1220.9058  5444.2222.8501  5495.5   226.2    5568  231.42
  5619.9  232.23  5625.8  234.59  5635.2  233.67  5641.1  235.41  5675.2237.3073
  5720.1  238.21  5735.4  240.21  5866.3  246.29  5924.1   250.5  5931.8  252.13
#Mann= 10 ,-1 , 0
  4066.4     .05       0  4070.5     .16       0  4210.4     .05       0
    4997    .035       0    5003     .05       0  5067.5     .12       0
  5196.8     .05       0  5376.1     .12       0  5444.2     .16       0
  5675.2     .05       0
Bank Sta=4180,5495.5
XS Rating Curve= 0 ,0
Exp/Cntr=0.3,0.1

Type RM Length L Ch R = 1 ,19608   ,566,566,566
BEGIN DESCRIPTION:
GASTON BRANCH 13.0
END DESCRIPTION:
XS GIS Cut Line= 3
       3689099.6     10602810.17      3688599.61     10601410.19
      3687299.64      10601010.2
#Sta/Elev= 30
  3529.4  312.14  3539.5  313.64  3570.3  294.43  3601.1  288.31  3614.3  271.63
  3637.2  262.55  3693.4  257.87    3763  246.63  3794.8  246.45  3858.6  253.11
  3872.9  248.21  3881.5248.5347  3903.7  249.55  3922.3  246.35    3983247.5572
  4070.9   248.3  4083.1   244.9  4092.2  237.41  4108.6  229.61    4117225.2564
  4171.5221.5783    4997  220.01  4999.8  219.51    5003  220.01  5347.5  220.01
  5633.3  226.49  5741.4228.4008  5877.7234.0656  6009.9  238.37  6376.1  256.99
#Mann= 10 ,-1 , 0
  3529.4     .05       0  3881.5      .1       0    3983     .05       0
    4117     .16       0  4171.5     .05       0    4997    .033       0
    5003     .05       0  5347.5     .12       0  5741.4     .16       0
  5877.7     .05       0
Bank Sta=4108.6,5633.3
XS Rating Curve= 0 ,0
Exp/Cntr=0.3,0.1

Type RM Length L Ch R = 1 ,19042   ,550,550,550
BEGIN DESCRIPTION:
GASTON BRANCH 12.0
END DESCRIPTION:
XS GIS Cut Line= 3
      3689549.62     10602610.22      3689049.61     10601060.19
      3688649.62     10599760.21
#Sta/Elev= 30
  3407.7   315.2  3423.8  314.03  3439.3  308.27  3449.8  293.28  3455.8  290.88
  3512.8   286.1    3616  288.03  3621.3  286.42  3628.4   277.6  3638.9  271.42
  3648.1  261.01  3680.1  247.88    3744   243.9    3807  233.56  4048.7  225.76
  4164.3  226.02  4171.4  230.57  4227.3  228.96  4279.8  220.82  4321.9  220.01
    4997  220.01  4999.8  219.51    5003  220.01  5402.4220.9141  5538.6  226.63
  5595.7228.6581    5738  232.73  5901.5  243.04  6314.8  259.01  6396.5  259.68
#Mann= 5 ,-1 , 0
  3407.7     .05       0    4997    .033       0    5003     .05       0
  5402.4     .12       0  5595.7     .05       0
Bank Sta=4227.3,5538.6
XS Rating Curve= 0 ,0
Exp/Cntr=0.3,0.1

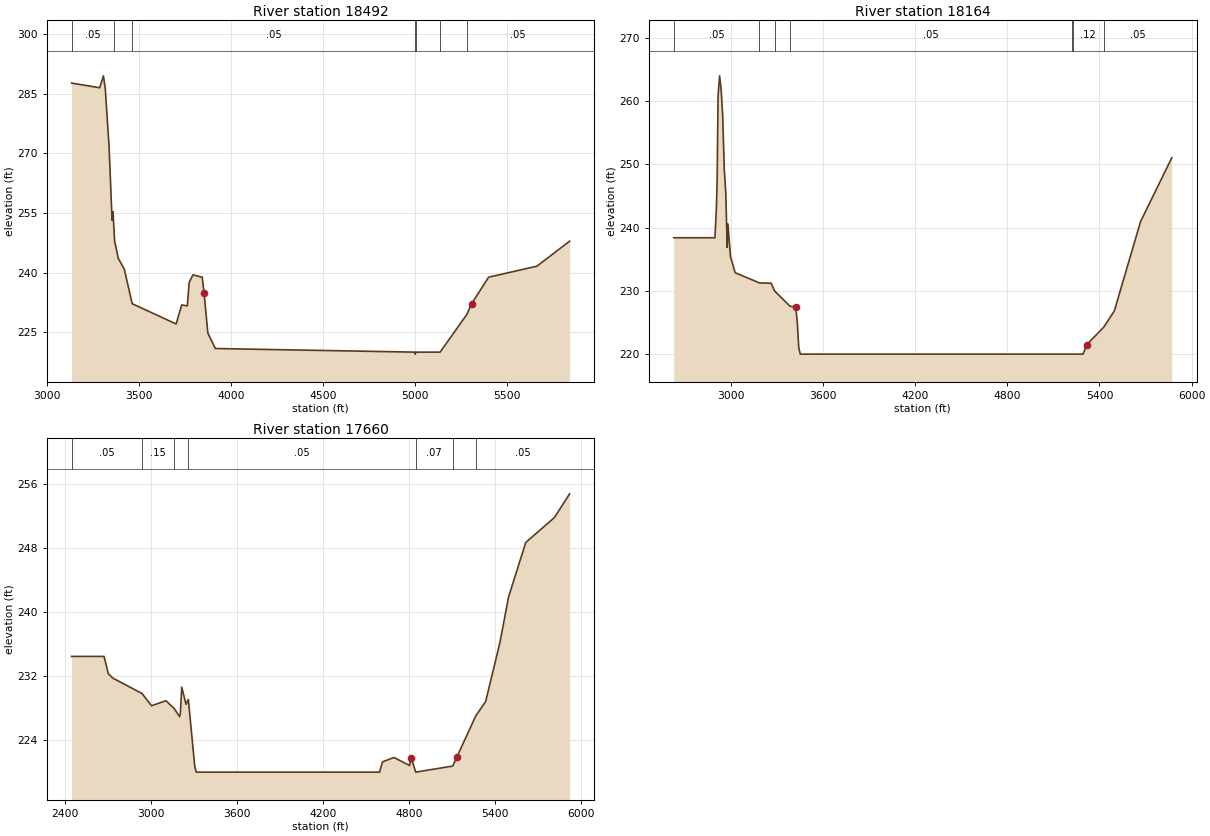
Type RM Length L Ch R = 1 ,18492   ,328,328,328
BEGIN DESCRIPTION:
GASTON BRANCH 11.0
END DESCRIPTION:
XS GIS Cut Line= 3
       3689750.6     10602541.05      3689449.61     10600710.19
      3688899.61     10600060.19
#Sta/Elev= 30
  3131.8  287.64  3284.7  286.46    3305  289.46  3315.1  286.27  3335.4  271.85
  3352.1  253.14  3357.2  255.31  3361.3  251.79  3365.8  247.92    3386  243.55
  3418.4  240.87  3461.3  232.18  3700.2  227.09  3730.6  231.88    3761  231.62
  3771.1  237.54  3791.4  239.43  3841.9  238.85  3852.2  234.75  3872.5  224.82
  3913.3  220.92    4997  220.01  4999.8  219.51    5003  220.01  5134.9  220.01
  5280.3  229.48  5306.4  232.22  5398.7  238.85  5661.3  241.62  5838.7   247.9
#Mann= 7 ,-1 , 0
  3131.8     .05       0  3361.3      .1       0  3461.3     .05       0
    4997    .033       0    5003     .05       0  5134.9     .12       0
  5280.3     .05       0
Bank Sta=3852.2,5306.4
XS Rating Curve= 0 ,0
Exp/Cntr=0.3,0.1

Type RM Length L Ch R = 1 ,18164   ,504,504,504
BEGIN DESCRIPTION:
GASTON BRANCH 10.0
END DESCRIPTION:
XS GIS Cut Line= 3
3689946.5517578910602510.2179532      3689649.61     10600460.19
      3689149.61      10599710.2
#Sta/Elev= 30
  2629.9  238.41  2897.9  238.41  2907.2  242.97  2912.3   247.5  2918.1   260.7
  2928.2  264.01  2938.3  261.86  2948.4  257.77  2958.6  249.25  2968.7  245.43
  2977.5  236.88  2982.5  240.59    2999  235.46  3029.3  232.89  3187.1  231.27
  3263.5  231.22  3286.8  229.99  3386.5  227.58  3423.4  227.45  3433.5  225.22
  3443.6  220.96  3453.7  220.01  5219.6  220.01  5225.5  220.01  5293.8  220.01
  5316.4  221.49  5427.9  224.27  5496.6  226.82  5667.9  240.98  5870.7  251.05
#Mann= 7 ,-1 , 0
  2629.9     .05       0  3187.1      .1       0  3286.8     .15       0
  3386.5     .05       0  5219.6     .07       0  5225.5     .12       0
  5427.9     .05       0
Bank Sta=3423.4,5316.4
XS Rating Curve= 0 ,0
Exp/Cntr=0.3,0.1

Type RM Length L Ch R = 1 ,17660   ,255,255,255
BEGIN DESCRIPTION:
Mapping XS 1a6ad100
END DESCRIPTION:
XS GIS Cut Line= 3
3690021.9285697810602420.2040976      3689955.46     10601682.38
      3689972.82     10599174.45
#Sta/Elev= 30
  2445.1  234.48  2671.7  234.48  2701.8  232.31    2732  231.78  2937.6  229.83
    3003  228.31  3103.5  228.94  3161.3  227.96    3199  226.94    3204   227.3
  3213.9  230.63    3244  228.49  3260.1  229.09  3304.3  220.83  3314.9  220.01
  4594.7  220.01  4614.7  221.29  4694.7  221.84  4804.7  220.83  4814.7  221.83
  4846.9  220.01    5105  220.77  5134.7  221.93  5265.7  227.04  5334.7  228.84
  5434.7  236.24  5494.7  241.92  5614.8  248.73  5814.8  251.85  5920.5  254.81
#Mann= 7 ,-1 , 0
  2445.1     .05       0  2937.6     .15       0  3161.3      .1       0
  3260.1     .05       0  4846.9     .07       0    5105     .12       0
  5265.7     .05       0
Bank Sta=4814.7,5134.7
XS Rating Curve= 0 ,0
Exp/Cntr=0.3,0.1