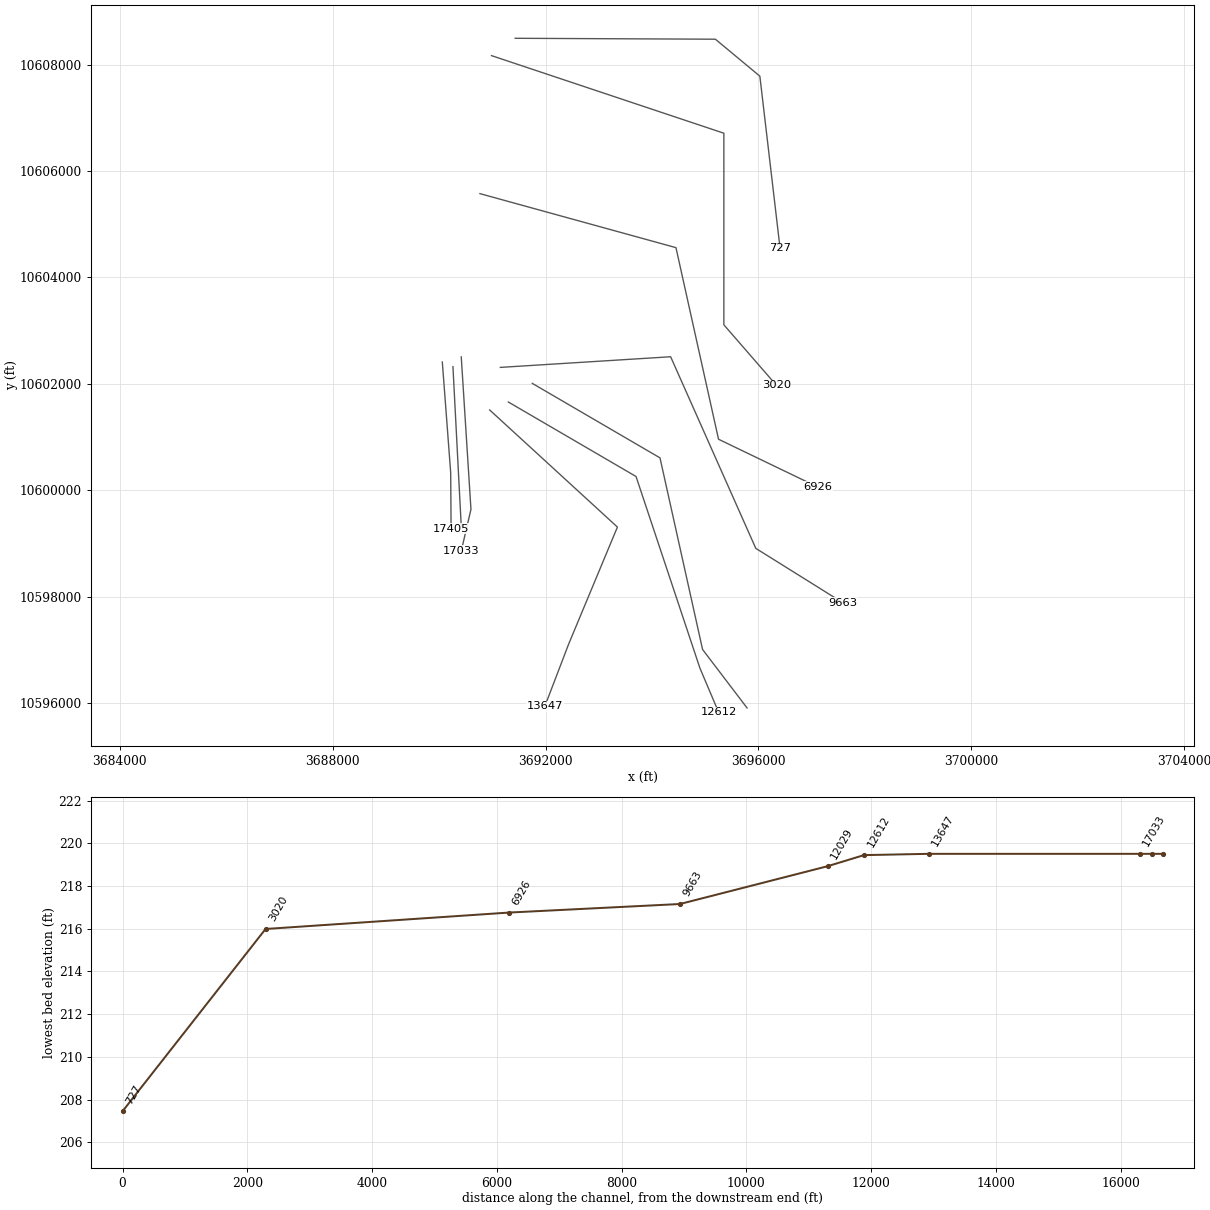
HEC-RAS study GASTON BRANCH.prj: GASTON BRANCH Base Level Engineering

--- GASTON BRANCH.g01 (geometry) --- (continued)

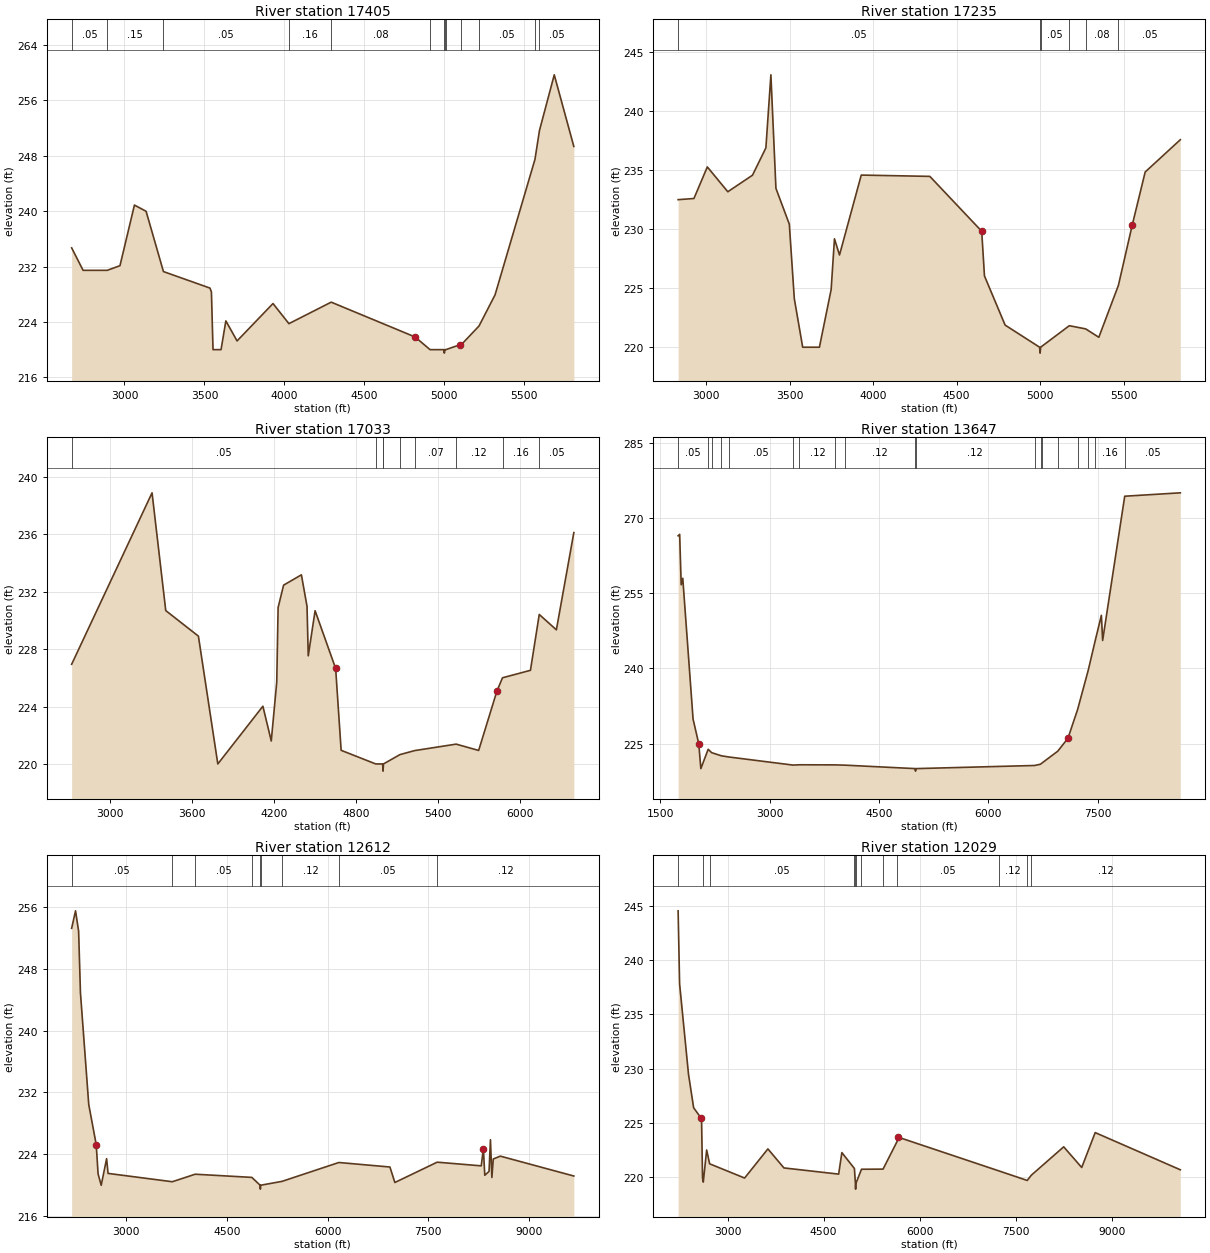
Type RM Length L Ch R = 1 ,17405   ,170,170,170
BEGIN DESCRIPTION:
GASTON BRANCH 9.0
END DESCRIPTION:
XS GIS Cut Line= 3
      3690059.63     10602411.55       3690216.9     10600334.95
      3690224.56     10599277.82
#Sta/Elev= 30
  2669.7  234.69  2741.3  231.45  2892.4  231.45  2971.9  232.12  3062.2  240.86
  3135.2  239.96  3243.6  231.27  3534.4  228.89  3543.6  228.33  3553.6  220.01
  3603.7  220.01  3633.8  224.16    3704  221.27  3928.5  226.66  4028.1  223.76
  4292.4  226.86    4817  221.84  4910.7  220.01    4997  220.01  4999.8  219.51
    5003  220.01  5008.8  220.01    5097  220.71  5106.8  220.75  5216.8  223.43
    5317  227.92  5566.5  247.46  5594.4   251.6    5687  259.64  5809.4  249.31
#Mann= 13 ,-1 , 0
  2669.7     .05       0  2892.4     .15       0  3243.6     .05       0
  4028.1     .16       0  4292.4     .08       0  4910.7      .1       0
    4997     .07       0    5003      .1       0  5008.8     .08       0
  5106.8     .12       0  5216.8     .05       0  5566.5      .1       0
  5594.4     .05       0
Bank Sta=4817,5097
XS Rating Curve= 0 ,0
Exp/Cntr=0.3,0.1

Type RM Length L Ch R = 1 ,17235   ,202,202,202
BEGIN DESCRIPTION:
Mapping XS ef28e0fa
END DESCRIPTION:
XS GIS Cut Line= 2
      3690259.28     10602324.76      3690415.43     10599323.22
#Sta/Elev= 30
  2833.3  232.49    2928  232.59  3008.1  235.26  3130.8  233.16  3278.5  234.56
  3358.6  236.87  3388.6  243.05  3418.7  233.45  3498.8  230.42  3528.8  224.11
  3578.9  220.01    3679  220.01  3749.1  224.88  3769.1  229.18  3799.2  227.81
  3929.4  234.57  4339.9  234.46  4650.3  229.82  4666.8  226.04  4790.5  221.88
    4997  220.01  4999.8  219.51    5003  220.01  5174.6  221.83  5272.6  221.56
  5351.3  220.85  5468.6  225.25  5551.5  230.36  5628.7  234.83  5838.9  237.56
#Mann= 6 ,-1 , 0
  2833.3     .05       0    4997    .033       0    5003     .05       0
  5174.6      .1       0  5272.6     .08       0  5468.6     .05       0
Bank Sta=4650.3,5551.5
XS Rating Curve= 0 ,0
Exp/Cntr=0.3,0.1

Type RM Length L Ch R = 1 ,17033   ,3386,3386,3386
BEGIN DESCRIPTION:
Mapping XS bece4859
END DESCRIPTION:
XS GIS Cut Line= 3
      3690415.53     10602507.02      3690597.82     10599642.45
      3690415.53      10598861.2
#Sta/Elev= 30
  2722.6  226.95  3310.6  238.89  3410.8  230.69  3649.6  228.91  3791.6  220.01
  4121.2  224.03  4182.4  221.61  4222.5  225.71  4232.5   230.9  4272.6  232.46
  4402.8  233.18    4444  230.98  4452.9  227.54    4503  230.68  4653.3  226.66
  4693.4  220.96  4946.4  220.01    4997  220.01  4999.8  219.51    5003  220.01
  5123.4  220.66  5231.2  220.94  5534.6  221.39  5699.1  220.95  5831.9  225.06
  5873.5  226.01  6077.9  226.53  6142.3  230.42  6267.5  229.35  6395.2  236.12
#Mann= 9 ,-1 , 0
  2722.6     .05       0  4946.4     .07       0    4997     .07       0
    5003     .07       0  5123.4     .12       0  5231.2     .07       0
  5534.6     .12       0  5873.5     .16       0  6142.3     .05       0
Bank Sta=4653.3,5831.9
XS Rating Curve= 0 ,0
Exp/Cntr=0.3,0.1

Type RM Length L Ch R = 1 ,13647   ,1035,1035,1035
BEGIN DESCRIPTION:
GASTON BRANCH 7.0
END DESCRIPTION:
XS GIS Cut Line= 4
      3690949.61     10601510.19      3693349.61     10599310.19
       3692433.5     10597111.53      3691987.24     10595945.66
#Sta/Elev= 30
  1744.8  266.42  1766.1  266.71    1787  256.66  1808.6  257.96  1949.8   229.9
  2028.1  224.94  2056.5  220.01  2156.7223.8609  2205.7223.1847  2337.1222.5697
  2442.8222.3249  3319.7 220.715  3408.8220.7747  3902.2 220.754  4033.7220.6994
    4997  220.01  4999.8  219.51    5003  220.01    6634220.6345  6714.2220.8932
  6735.6221.1421  6950.6223.4871  7089.8  226.05  7222.3231.7757  7368.9239.6542
  7462.7245.4481  7548.5  250.57  7565.9  245.56  7868.7 274.315  8630.8  274.99
#Mann= 19 ,-1 , 0
  1744.8     .05       0  2156.7     .12       0  2205.7     .05       0
  2337.1     .16       0  2442.8     .05       0  3319.7     .07       0
  3408.8     .12       0  3902.2     .08       0  4033.7     .12       0
    4997     .07       0    5003     .12       0    6634     .16       0
  6714.2     .12       0  6735.6     .16       0  6950.6     .05       0
  7222.3     .16       0  7368.9     .12       0  7462.7     .16       0
  7868.7     .05       0
Bank Sta=2028.1,7089.8
XS Rating Curve= 0 ,0
Exp/Cntr=0.3,0.1

Type RM Length L Ch R = 1 ,12612   ,583,583,583
BEGIN DESCRIPTION:
GASTON BRANCH 6.0
END DESCRIPTION:
XS GIS Cut Line= 4
      3691299.58      10601660.2      3693699.61     10600260.19
      3694899.61     10596660.19      3695252.47     10595827.63
#Sta/Elev= 30
  2189.9  253.29  2247.8  255.56  2293.7  252.92    2321  244.92  2444.6  230.42
  2555.8  225.23  2583.5  221.43  2629.9  219.95  2710.5   223.4    2732  221.49
    3689220.4089  4029.1221.3838  4873.1220.9724    4997  219.95  4999.8  219.45
    5003  219.95  5323.4220.4595  6168.5222.9044    6929  222.32  7002.8  220.31
  7632.3222.9474  8288.8  222.47  8320.4  224.71  8341.5  221.25  8404.8  221.75
  8425.8  225.86  8446.9  220.96    8468  223.36  8573.4  223.73  9667.4  221.15
#Mann= 9 ,-1 , 0
  2189.9     .05       0    3689     .12       0  4029.1     .05       0
  4873.1     .16       0    4997     .07       0    5003     .16       0
  5323.4     .12       0  6168.5     .05       0  7632.3     .12       0
Bank Sta=2555.8,8320.4
XS Rating Curve= 0 ,0
Exp/Cntr=0.3,0.1

Type RM Length L Ch R = 1 ,12029   ,2366,2366,2366
BEGIN DESCRIPTION:
GASTON BRANCH 5.0
END DESCRIPTION:
XS GIS Cut Line= 4
      3691749.62     10602010.18      3694149.61     10600610.19
      3694949.61     10597010.19      3695785.24     10595911.69
#Sta/Elev= 30
  2226.6  244.53  2249.7  237.82  2388.7  229.51  2469.3  226.41  2585.5  225.47
  2592.5   225.5  2608.2  219.96  2619.6219.5751  2672.7  222.53  2719.1221.2603
  3265.6  219.95  3629.5  222.63    3880  220.88  4735.1  220.31  4785.1  222.29
  4981.1220.8282    4997  219.43  4999.8  218.93    5003  219.43  5091.6220.7582
  5428.7220.7711  5645.2223.2794  5669.7   223.7    7242220.6004  7681.5219.7277
  7744.4220.2051  8251.1  222.82  8532.8  220.92  8743.2  224.13 10073.1  220.71
#Mann= 12 ,-1 , 0
  2226.6     .05       0  2619.6     .07       0  2719.1     .05       0
  4981.1      .1       0    4997     .07       0    5003      .1       0
  5091.6     .16       0  5428.7     .12       0  5645.2     .05       0
    7242     .12       0  7681.5     .07       0  7744.4     .12       0
Bank Sta=2585.5,5669.7
XS Rating Curve= 0 ,0
Exp/Cntr=0.3,0.1

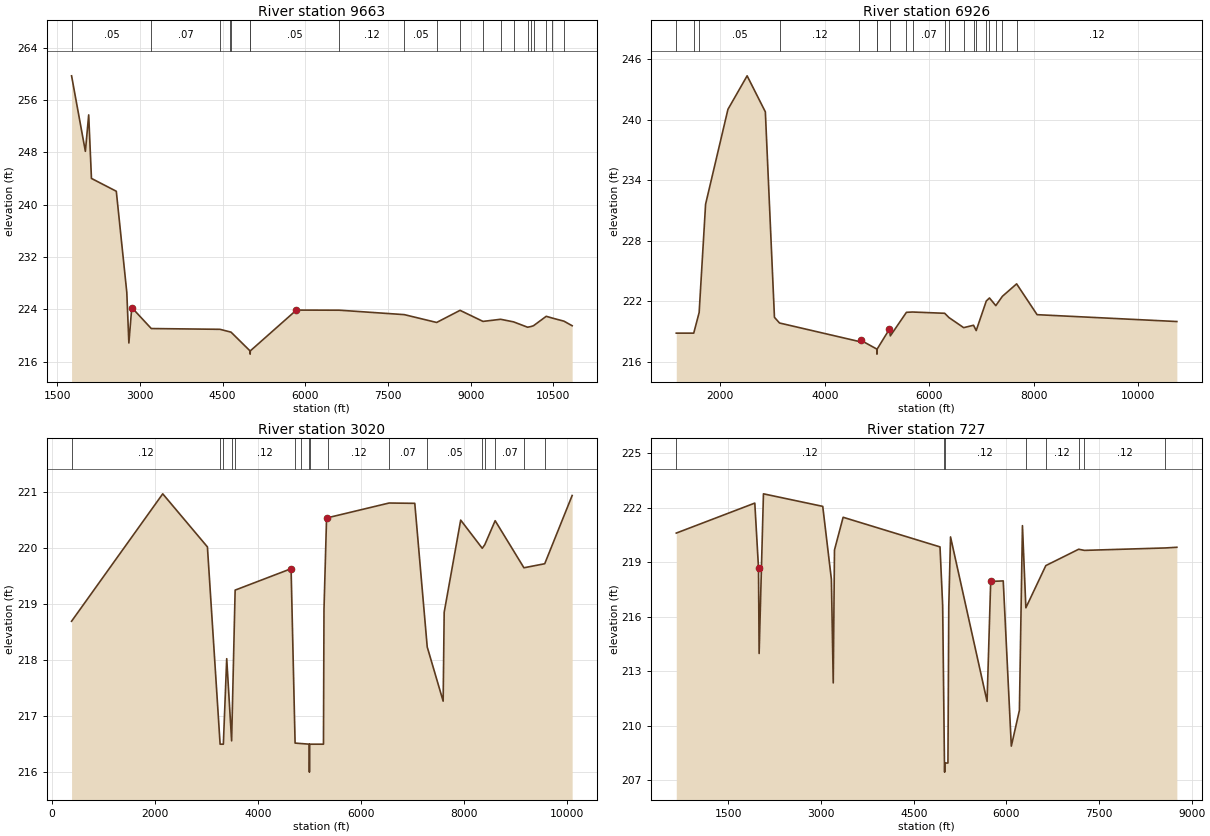
Type RM Length L Ch R = 1 ,9663    ,2737,2737,2737
BEGIN DESCRIPTION:
GASTON BRANCH 4.0
END DESCRIPTION:
XS GIS Cut Line= 4
      3691149.64     10602310.19      3694349.61     10602510.19
      3695949.61     10598910.19      3697591.14     10597885.02
#Sta/Elev= 30
    1760  259.69  2010.5  248.15  2070.6  253.72  2120.7  244.01  2571.5  242.05
  2761.9   226.6  2799.5  218.86  2852.1  224.28  3205.9221.0696    4452220.9521
  4639.5220.5487  4652.6220.5205    4997  217.66  4999.8  217.16    5003  217.66
  5838.2  223.89  6619.1223.8734  7796.9223.1945    8383221.9978  8807.6223.8522
  9223.8222.1596  9543.4222.4845    9779222.0879 10032.5221.2729 10095.6221.3785
 10140.1221.5012 10371.2  222.94 10483.8222.6632 10692.2222.1974 10841.1   221.5
#Mann= 20 ,-1 , 0
    1760     .05       0  3205.9     .07       0    4452     .05       0
  4639.5     .07       0  4652.6     .05       0    4997     .03       0
    5003     .05       0  6619.1     .12       0  7796.9     .05       0
    8383     .12       0  8807.6     .16       0  9223.8     .12       0
  9543.4     .05       0    9779     .12       0 10032.5     .16       0
 10095.6     .05       0 10140.1     .12       0 10371.2     .07       0
 10483.8     .12       0 10692.2     .05       0
Bank Sta=2852.1,5838.2
XS Rating Curve= 0 ,0
Exp/Cntr=0.3,0.1

Type RM Length L Ch R = 1 ,6926    ,3906,3906,3906
BEGIN DESCRIPTION:
GASTON BRANCH 3.0
END DESCRIPTION:
XS GIS Cut Line= 4
      3690766.31     10605574.97      3694449.61     10604560.19
      3695249.61     10600960.19      3697114.75     10600061.99
#Sta/Elev= 30
  1159.3  218.84  1493.5  218.84  1597.2220.8881  1720.4  231.62  2148.1  241.02
  2515.1  244.34  2863.8  240.77  3037.9  220.41  3134.7219.8446  4664.2218.0041
    4696  218.12    4997  217.26  4999.8  216.76    5003  217.26  5237.2  219.23
  5255.3218.5674  5563.6 220.903  5679.6220.9329  6295.2220.8075  6376.9220.3839
  6658.7219.3831  6847.4219.6217  6898.4219.0964  7091.3222.0217  7152.3222.3247
  7273.4221.5652  7399.5  222.49  7671.8223.7229  8063.3  220.67 10737.8  219.99
#Mann= 20 ,-1 , 0
  1159.3     .05       0  1493.5     .07       0  1597.2     .05       0
  3134.7     .12       0  4664.2     .05       0    4997    .033       0
    5003     .05       0  5255.3     .07       0  5563.6     .05       0
  5679.6     .07       0  6295.2     .07       0  6376.9     .05       0
  6658.7     .07       0  6847.4      .1       0  6898.4     .05       0
  7091.3     .12       0  7152.3     .05       0  7273.4     .16       0
  7399.5     .16       0  7671.8     .12       0
Bank Sta=4696,5237.2
XS Rating Curve= 0 ,0
Exp/Cntr=0.3,0.1

Type RM Length L Ch R = 1 ,3020    ,2293,2293,2293
BEGIN DESCRIPTION:
GASTON BRANCH 2.0
END DESCRIPTION:
XS GIS Cut Line= 4
      3690983.34     10608168.27      3695349.61     10606710.19
      3695349.61     10603110.19      3696334.01     10601977.32
#Sta/Elev= 30
     389  218.69  2156.3  220.97  3022.6  220.02  3268.6  216.49  3331.5  216.49
  3396.5  218.02  3491.7216.5493  3559.9219.2469  4644.4  219.63  4722.1216.5097
  4827.7 216.502    4997  216.49  4999.8  215.99    5003  216.49  5272.3  216.49
  5282.3   218.9  5332.3  220.54  5362.6 220.544  6544.6220.8055  7042.3   220.8
  7283.7218.2295  7592.3  217.26  7612.3  218.85  7932.3   220.5  8350.2219.9957
    8400220.0609  8600.5220.4892  9158.2219.6467  9561.4 219.719 10093.1  220.94
#Mann= 17 ,-1 , 0
     389     .12       0  3268.6     .16       0  3331.5     .12       0
  3491.7     .05       0  3559.9     .12       0  4722.1     .07       0
  4827.7     .05       0    4997    .033       0    5003     .05       0
  5362.6     .12       0  6544.6     .07       0  7283.7     .05       0
  8350.2     .07       0    8400     .05       0  8600.5     .07       0
  9158.2     .05       0  9561.4     .12       0
Bank Sta=4644.4,5332.3
XS Rating Curve= 0 ,0
Exp/Cntr=0.3,0.1

Type RM Length L Ch R = 1 ,727     ,0,0,0
BEGIN DESCRIPTION:
GASTON BRANCH 1.0
END DESCRIPTION:
XS GIS Cut Line= 4
      3691428.19      10608493.8      3695190.49     10608476.45
        3696026.     10607782.01      3696405.77      10604548.5
#Sta/Elev= 30
   655.1   220.6  1926.5  222.25  1986.5  218.68  1996.5  213.98  2066.5  222.76
  3026.5  222.07  3166.5  218.06  3196.5  212.36  3216.5  219.67  3356.5  221.47
    4925  219.84    4968  216.62    4997  207.95  4999.8  207.45    5003  207.95
  5053.5  207.95  5066.9  216.54  5095.5  220.39  5686.9  211.34  5745.7  217.94
  5948.7  217.97  6079.6  208.88  6210.5  210.85  6259.7  221.01  6315.1  216.49
  6638.1218.8117  7170.1219.7116  7262.6 219.649  8574.2219.7826  8759.6  219.82
#Mann= 8 ,-1 , 0
   655.1     .12       0    4997     .07       0    5003     .12       0
  6315.1     .05       0  6638.1     .12       0  7170.1     .05       0
  7262.6     .12       0  8574.2     .05       0
Bank Sta=1986.5,5745.7
XS Rating Curve= 0 ,0
Exp/Cntr=0.3,0.1

Chan Stop Cuts=-1
Use User Specified Reach Order=0
Composite Channel Slope=5