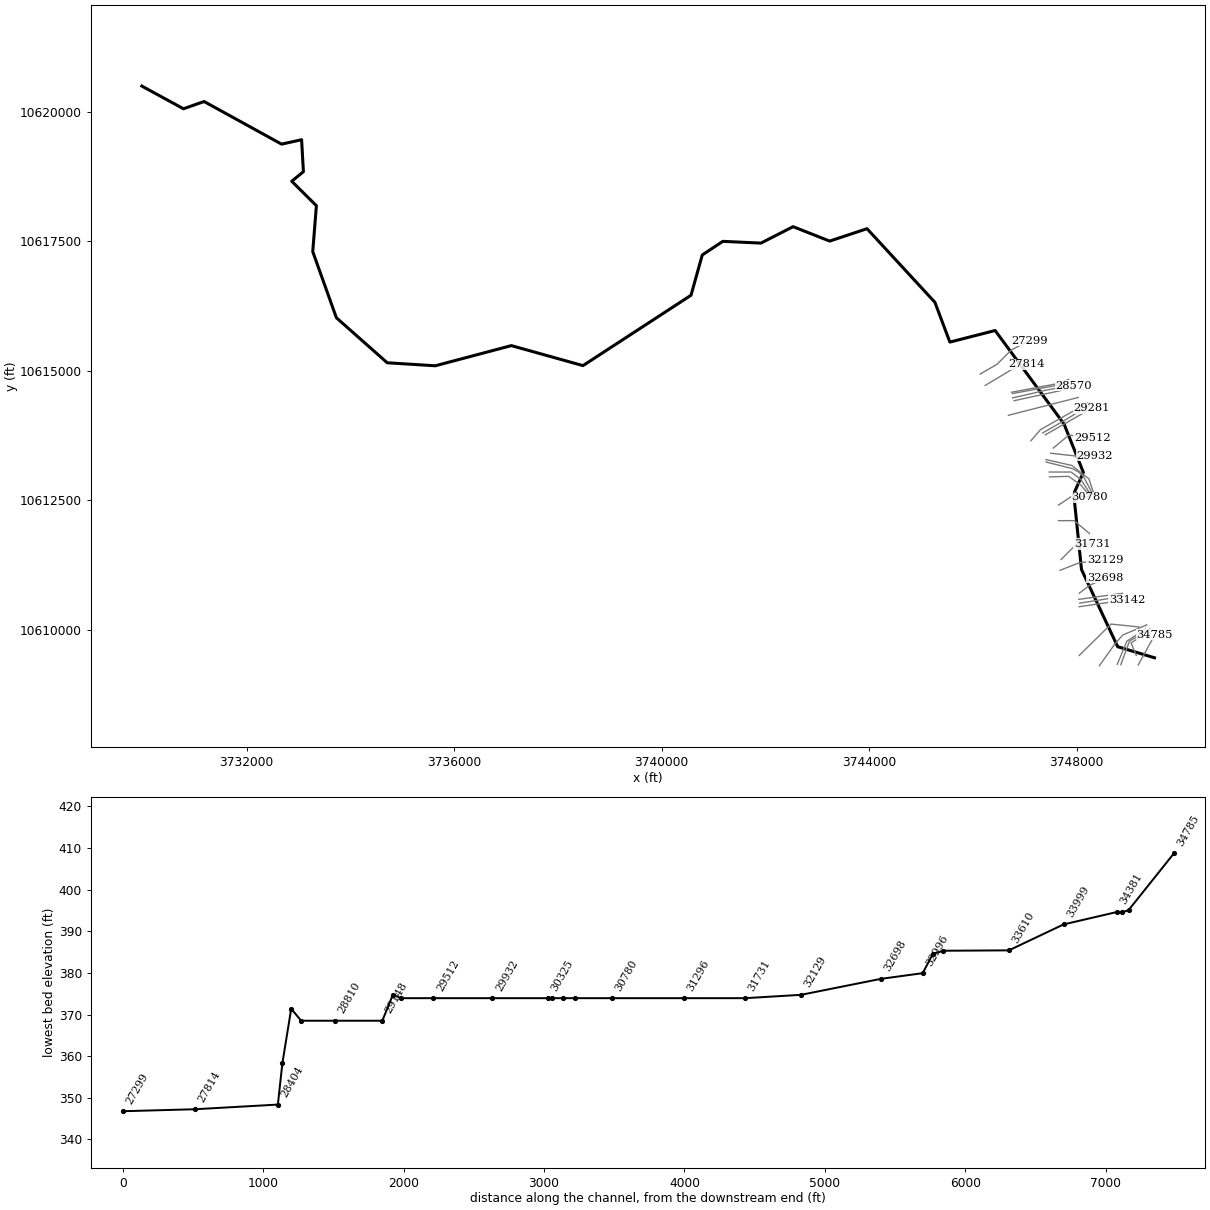
--- GUM CREEK.prj (project) ---

Proj Title=GUM CREEK Base Level Engineering
Current Plan=p01
Default Exp/Contr=0.3,0.1
English Units
Geom File=g01
Flow File=f01
Plan File=p01
Y Axis Title=Elevation
X Axis Title(PF)=Main Channel Distance
X Axis Title(XS)=Station
BEGIN DESCRIPTION:
GUM CREEK
END DESCRIPTION:
DSS Export Rating Curves= 0
DSS Export Rating Curve Sorted= 0
DSS Export Volume Flow Curves= 0
DXF OffsetX= 0
DXF OffsetY= 0
DXF ScaleX= 1
DXF ScaleY= 10

--- GUM CREEK.p01 (plan) ---

Plan Title=Multiple Run
Short Identifier=Multiple
Geom File=g01
Flow File=f01
Subcritical Flow
K Sum by GR= 0
Std Step Tol= 0.01
Critical Tol= 0.01
Num of Std Step Trials= 20
Max Error Tol= 0.3
Flow Tol Ratio= 0.001
Split Flow NTrial= 30
Split Flow Tol= 0.02
Split Flow Ratio= 0.02
Log Output Level= 0
Friction Slope Method= 1
Unsteady Friction Slope Method= 2
Unsteady Bridges Friction Slope Method= 1
Parabolic Critical Depth
Global Vel Dist=  1 , 1 , 1
Global Log Level= 0
CheckData=True
Encroach Param= -1, 0, 0, 0
BEGIN DESCRIPTION:
Multiple Run
END DESCRIPTION:

--- GUM CREEK.f01 (steady flow) ---

Flow Title=Multiple
Program Version=4.10
Number of Profiles= 7
Profile Names=10-year,25-year,50-year,1pct_min,100-year,1pct_plu,500-year
River Rch & RM=GUM CREEK,Reach-1         ,34785
     377     500     600     531     717     970    1029
River Rch & RM=GUM CREEK,Reach-1         ,30325
     633     864    1057     952    1288    1741    1915
River Rch & RM=GUM CREEK,Reach-1         ,27299
    1172    1671    2106    1950    2638    3567    4153
River Rch & RM=GUM CREEK,Reach-1         ,27017
    1172    1671    2106    1950    2638    3567    4153
River Rch & RM=GUM CREEK,Reach-1         ,26789
    1431    2046    2583    2393    3236    4377    5101
River Rch & RM=GUM CREEK,Reach-1         ,26310
    1431    2046    2583    2393    3236    4377    5101
River Rch & RM=GUM CREEK,Reach-1         ,20200
    1503    2146    2705    2501    3382    4574    5310
River Rch & RM=GUM CREEK,Reach-1         ,14867
    1899    2729    3456    3206    4335    5863    6852
River Rch & RM=GUM CREEK,Reach-1         ,8327
    1966    2822    3570    3307    4472    6048    7051
River Rch & RM=GUM CREEK,Reach-1         ,1685
    2014    2892    3659    3390    4584    6200    7228
Boundary for River Rch & Prof#=GUM CREEK,Reach-1         , 1
Up Type= 0
Dn Type= 3
Dn Slope=0.004
Boundary for River Rch & Prof#=GUM CREEK,Reach-1         , 2
Up Type= 0
Dn Type= 3
Dn Slope=0.004
Boundary for River Rch & Prof#=GUM CREEK,Reach-1         , 3
Up Type= 0
Dn Type= 3
Dn Slope=0.004
Boundary for River Rch & Prof#=GUM CREEK,Reach-1         , 4
Up Type= 0
Dn Type= 3
Dn Slope=0.004
Boundary for River Rch & Prof#=GUM CREEK,Reach-1         , 5
Up Type= 0
Dn Type= 3
Dn Slope=0.004
Boundary for River Rch & Prof#=GUM CREEK,Reach-1         , 6
Up Type= 0
Dn Type= 3
Dn Slope=0.004
Boundary for River Rch & Prof#=GUM CREEK,Reach-1         , 7
Up Type= 0
Dn Type= 3
Dn Slope=0.004
DSS Import GetInterval= 0
DSS Import GetPeak= 0
DSS Import FillOption= 0

--- GUM CREEK.g01 (geometry) ---

Geom Title=Existing Conditions
Program Version=4.10

River Reach=GUM CREEK       ,Reach-1
Reach XY= 30
      3749500.32     10609465.14      3748790.75       10609679.
      3748093.25       10611168.       3747943.5       10612628.
      3748129.25       10613041.       3747757.5       10613973.
      3746428.75       10615777.      3745556.25       10615554.
      3745268.25       10616321.      3743959.75       10617741.
      3743239.75       10617502.      3742534.75       10617780.
      3741914.75       10617463.      3741180.75       10617497.
        3740784.       10617234.      3740567.25       10616457.
        3738485.       10615100.       3737104.5       10615486.
        3735639.       10615097.        3734712.       10615155.
      3733732.25       10616023.       3733276.5       10617299.
      3733346.75       10618184.      3732871.75       10618656.
      3733096.75       10618841.       3733061.5       10619457.
       3732675.5       10619372.      3731182.25       10620194.
       3730784.5       10620054.        3729982.       10620492.

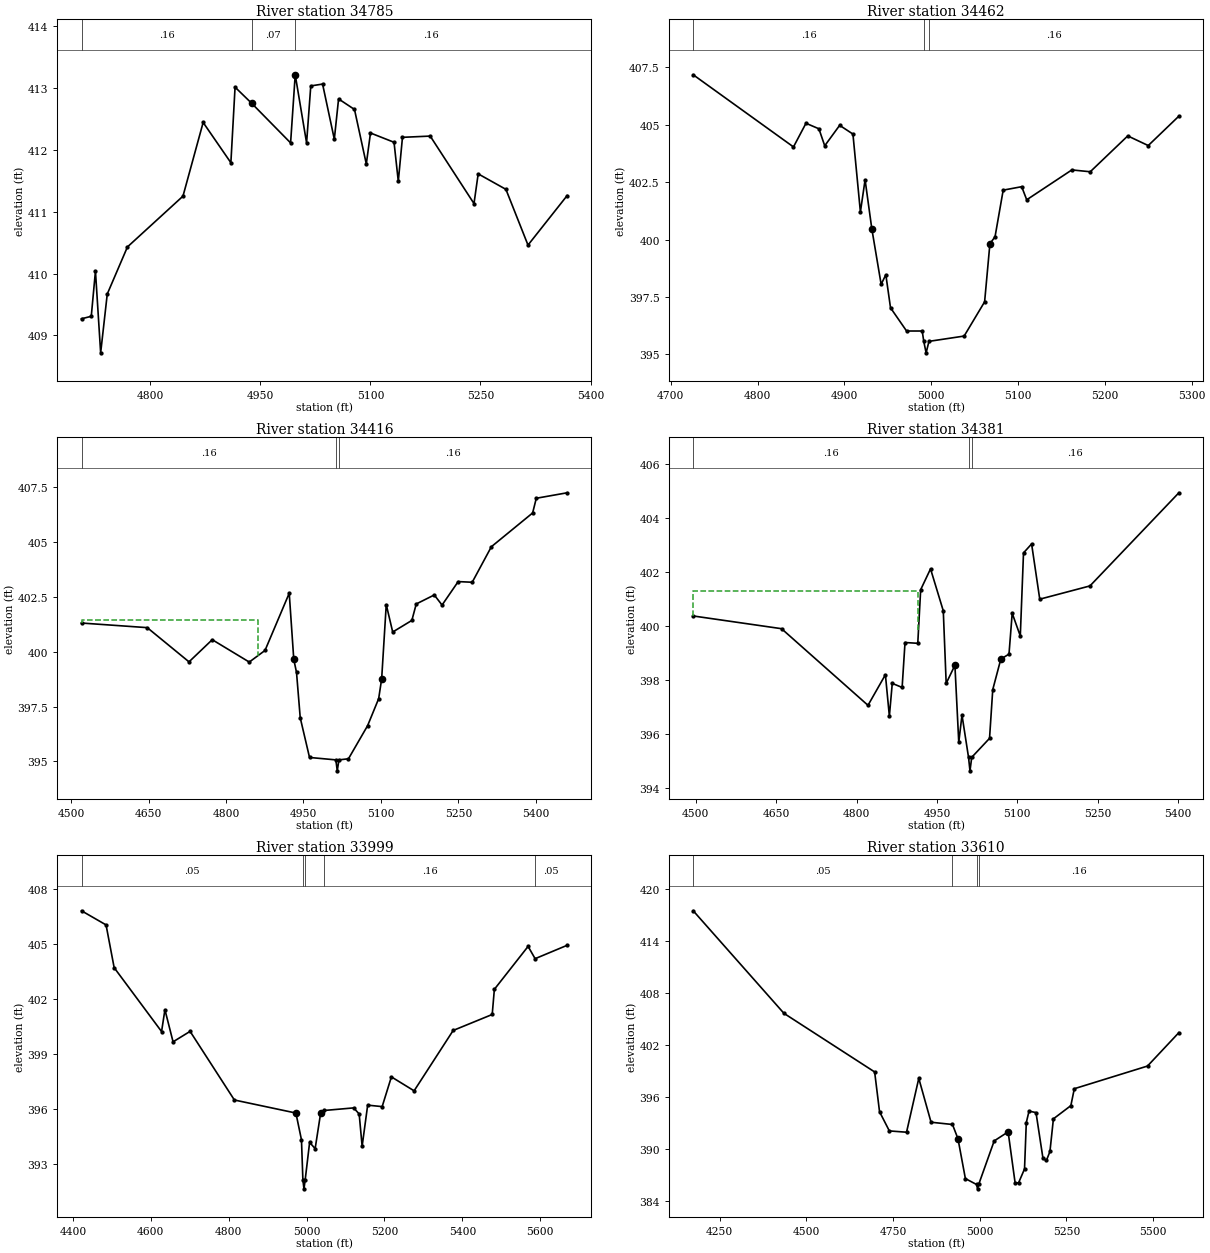
Type RM Length L Ch R = 1 ,34785   ,323,323,323
BEGIN DESCRIPTION:
Mapping XS a6f41992
END DESCRIPTION:
XS GIS Cut Line= 2
      3749186.23      10609327.1      3749505.66     10609906.94
#Sta/Elev= 30
  4706.2  409.27  4719.5  409.31  4725.2  410.04  4732.3  408.72  4741.3  409.67
  4768.8  410.43  4844.5  411.25    4872  412.44  4909.8  411.79  4915.5  413.01
  4938.1  412.75  4991.2  412.11  4997.5  413.21    5013  412.11  5018.7  413.03
  5034.8  413.06  5050.8  412.17  5056.6  412.82  5078.3  412.65  5094.4  411.77
  5100.1  412.27  5132.2  412.12    5138  411.49  5143.7   412.2  5181.5  412.22
  5241.2  411.13  5246.9  411.61  5284.7  411.36  5314.8  410.46  5368.2  411.26
#Mann= 3 , 0 , 0
  4706.2     .16       0  4938.1     .07       0  4997.5     .16       0
Bank Sta=4938.1,4997.5
XS Rating Curve= 0 ,0
Exp/Cntr=0.3,0.1

Type RM Length L Ch R = 1 ,34462   ,46,46,46
BEGIN DESCRIPTION:
GUM CREEK 71.0
END DESCRIPTION:
XS GIS Cut Line= 3
       3749149.6     10609510.21      3749048.55     10609753.85
      3749299.59     10609910.18
#Sta/Elev= 30
  4725.8  407.17  4841.3  404.03  4855.7  405.06  4870.6  404.82  4877.3  404.08
  4894.5  404.97  4909.8  404.59  4918.4   401.2  4923.8   402.6  4931.5  400.48
  4942.3  398.05  4947.7  398.47  4953.1  397.03  4971.6  396.02  4989.6  396.02
  4991.4  395.57  4994.1  395.07  4997.4  395.57  5037.9   395.8  5061.5  397.29
  5067.6  399.82  5073.5  400.12  5082.9  402.15  5104.2   402.3    5110  401.73
    5162  403.03  5183.2  402.95  5226.4  404.51    5250  404.09  5285.3  405.37
#Mann= 3 ,-1 , 0
  4725.8     .16       0  4991.4     .07       0  4997.4     .16       0
Bank Sta=4931.5,5067.6
XS Rating Curve= 0 ,0
Exp/Cntr=0.3,0.1

Type RM Length L Ch R = 1 ,34416   ,35,35,35
BEGIN DESCRIPTION:
Mapping XS ed40f18b
END DESCRIPTION:
XS GIS Cut Line= 3
      3748851.98     10609332.49      3749018.66     10609787.37
      3749411.01     10610020.01
#Sta/Elev= 30
  4520.1  401.31  4647.4   401.1  4728.3  399.54  4773.3  400.55    4845  399.53
  4875.5  400.06  4922.4  402.67  4931.2  399.65  4936.5  399.06  4943.7  396.99
  4961.7  395.18  5012.7  395.07  5015.4  394.57  5018.7  395.07  5037.1  395.12
  5074.2  396.63  5095.6  397.86  5101.4  398.76  5110.3  402.15  5122.8   400.9
  5159.9  401.43  5168.4  402.18  5203.3  402.59  5218.4  402.13  5249.6   403.2
  5276.8  403.17  5313.9  404.79  5393.8  406.33  5400.9     407  5460.7  407.25
#Mann= 3 ,-1 , 0
  4520.1     .16       0  5012.7     .07       0  5018.7     .16       0
#XS Ineff= 2 , 0
         4861.59  401.43
Permanent Ineff=
       F       F
Bank Sta=4931.2,5101.4
XS Rating Curve= 0 ,0
Exp/Cntr=0.3,0.1

Type RM Length L Ch R = 1 ,34381   ,382,382,382
BEGIN DESCRIPTION:
Mapping XS d71cf050
END DESCRIPTION:
XS GIS Cut Line= 3
      3748782.53     10609339.41      3748970.04     10609787.37
      3749323.15     10610015.85
#Sta/Elev= 30
  4495.3  400.37  4660.1   399.9  4821.4  397.07  4853.9   398.2  4861.3  396.67
  4866.7  397.88  4885.1  397.73  4890.5  399.39  4914.3  399.36  4919.7  401.34
  4938.1  402.11  4961.9  400.56  4967.3  397.88  4983.6  398.55  4990.8   395.7
  4996.8  396.71    5009  395.15  5011.7  394.65    5015  395.15  5048.2  395.85
  5054.2  397.65  5069.3  398.78  5084.5  398.96  5090.5  400.47  5105.6  399.63
  5111.6   402.7  5126.7  403.03  5141.9  400.99  5235.6  401.48  5401.5  404.92
#Mann= 3 ,-1 , 0
  4495.3     .16       0    5009     .07       0    5015     .16       0
#XS Ineff= 2 , 0
         4915.45   401.3
Permanent Ineff=
       F       F
Bank Sta=4983.6,5069.3
XS Rating Curve= 0 ,0
Exp/Cntr=0.3,0.1

Type RM Length L Ch R = 1 ,33999   ,389,389,389
BEGIN DESCRIPTION:
Mapping XS 34639560
END DESCRIPTION:
XS GIS Cut Line= 4
      3748438.48     10609313.34      3748730.17     10609722.23
      3748889.02     10609904.52      3749352.03     10610099.89
#Sta/Elev= 30
  4422.3   406.8  4485.3  406.03  4506.1   403.7  4627.8  400.22  4636.4  401.41
  4657.3  399.66    4701  400.23  4814.7  396.49  4972.6  395.78  4986.9  394.32
  4990.5  392.15  4993.3  391.65  4996.5  392.15  5007.8  394.18    5022  393.84
  5036.2  395.79  5045.5  395.92  5120.8  396.06    5135  395.73  5142.6  393.97
  5156.8  396.21    5194  396.13  5217.7  397.75    5276  396.99  5376.3  400.28
  5476.5  401.15    5482  402.52  5568.6  404.86  5586.6  404.19  5668.9  404.92
#Mann= 5 ,-1 , 0
  4422.3     .05       0  4990.5     .03       0  4996.5     .05       0
  5045.5     .16       0  5586.6     .05       0
Bank Sta=4972.6,5036.2
XS Rating Curve= 0 ,0
Exp/Cntr=0.3,0.1

Type RM Length L Ch R = 1 ,33610   ,468,468,468
BEGIN DESCRIPTION:
GUM CREEK 70.0
END DESCRIPTION:
XS GIS Cut Line= 3
      3748049.57     10609510.15      3748663.13     10610114.97
       3749199.6     10610060.19
#Sta/Elev= 30
  4173.8  417.44  4435.5  405.63  4697.1  398.88  4711.2   394.3  4739.5  392.09
  4789.1  391.94  4824.4  398.14  4859.8  393.09  4921.6  392.83  4937.5  391.18
  4958.8   386.6  4991.1  385.92  4993.9  385.42  4997.1  385.92  5041.9  390.94
  5082.1  391.98  5102.2  386.12  5112.2  386.11  5129.4  387.71  5134.5  393.05
  5142.4  394.37  5162.5   394.2  5182.6  388.93  5192.6  388.69  5202.7  389.72
  5212.7  393.48    5263     395    5273  396.95  5484.1  399.56  5574.6  403.41
#Mann= 4 ,-1 , 0
  4173.8     .05       0  4921.6     .16       0  4991.1     .07       0
  4997.1     .16       0
Bank Sta=4937.5,5082.1
XS Rating Curve= 0 ,0
Exp/Cntr=0.3,0.1

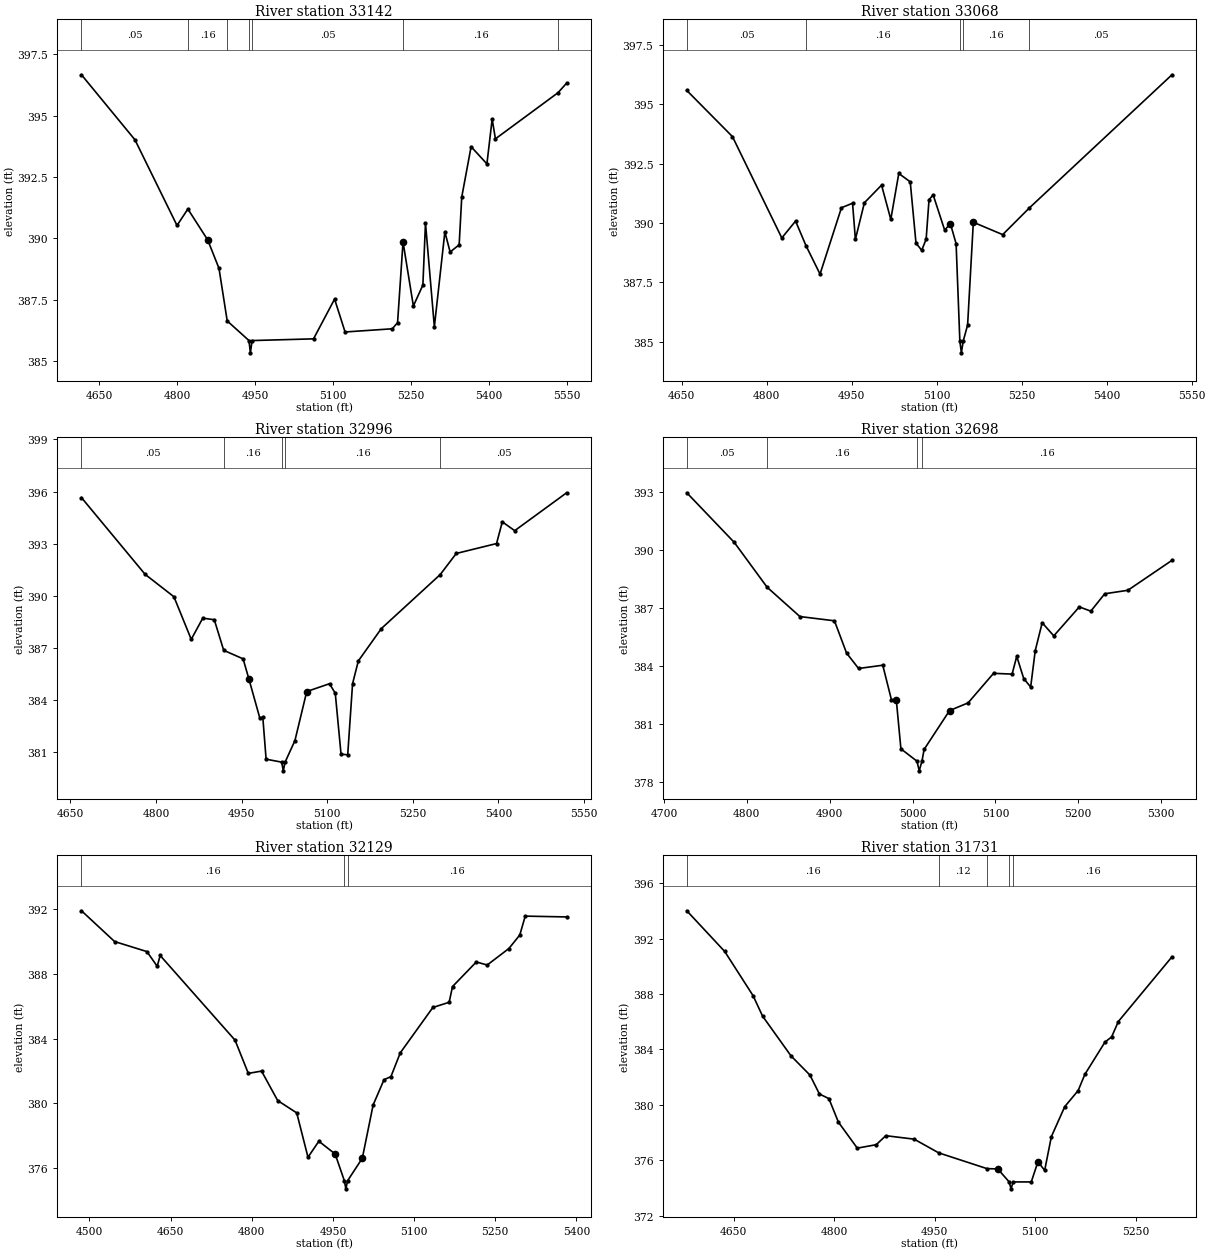
Type RM Length L Ch R = 1 ,33142   ,74,74,74
BEGIN DESCRIPTION:
GUM CREEK 69.0
END DESCRIPTION:
XS GIS Cut Line= 2
       3748047.8     10610449.45      3748971.42     10610584.87
#Sta/Elev= 30
  4615.4  396.66  4718.3  394.01  4799.2  390.52  4820.1  391.19  4858.3  389.93
    4880  388.77  4895.8  386.63  4937.7  385.83  4940.4  385.33  4943.7  385.83
  5061.9   385.9  5102.4  387.52  5122.6  386.18  5213.5  386.31  5223.6  386.56
  5234.1  389.85    5254  387.24  5272.3  388.09  5277.3  390.62  5294.4  386.39
  5314.6  390.26  5324.7  389.44  5342.1  389.73  5347.1  391.68  5365.1  393.73
  5395.5  393.03  5405.6  394.85  5411.9  394.05  5532.4  395.93  5548.9  396.32
#Mann= 7 ,-1 , 0
  4615.4     .05       0  4820.1     .16       0  4895.8     .05       0
  4937.7    .033       0  4943.7     .05       0  5234.1     .16       0
  5532.4     .05       0
Bank Sta=4858.3,5234.1
XS Rating Curve= 0 ,0
Exp/Cntr=0.3,0.1

Type RM Length L Ch R = 1 ,33068   ,72,72,72
BEGIN DESCRIPTION:
Mapping XS 7b01985c
END DESCRIPTION:
XS GIS Cut Line= 2
      3748059.98      10610518.9      3748905.92     10610652.37
#Sta/Elev= 30
  4658.8  395.57  4739.4  393.63  4826.5  389.37  4850.8  390.08  4869.3  389.04
    4894  387.85  4931.8  390.64  4951.4  390.83  4956.4  389.31  4972.3  390.85
  5002.6  391.59  5018.9  390.15    5033  392.08  5053.2  391.73  5063.4  389.15
  5073.5  388.85  5081.3  389.32  5086.4  390.98  5093.7  391.18    5114   389.7
  5124.1  389.97  5134.2  389.13  5140.8  385.04  5143.5  384.54  5146.8  385.04
  5154.5  385.71  5164.6  390.03  5216.4  389.51  5263.4  390.63  5515.2  396.23
#Mann= 5 ,-1 , 0
  4658.8     .05       0  4869.3     .16       0  5140.8     .07       0
  5146.8     .16       0  5263.4     .05       0
Bank Sta=5124.1,5164.6
XS Rating Curve= 0 ,0
Exp/Cntr=0.3,0.1

Type RM Length L Ch R = 1 ,32996   ,298,298,298
BEGIN DESCRIPTION:
Mapping XS 218cfbd2
END DESCRIPTION:
XS GIS Cut Line= 2
      3748039.12     10610591.81      3748881.22     10610708.14
#Sta/Elev= 30
  4669.4  395.65  4780.9  391.24  4831.4  389.95  4861.7   387.5  4881.9  388.72
  4902.1  388.63  4918.6  386.87  4952.6  386.38  4962.6  385.24  4982.1  382.95
  4987.1  383.03  4992.9  380.61  5020.2  380.44    5023  379.94  5026.2  380.44
  5043.4  381.68  5064.1   384.5    5104  384.95  5114.1   384.4  5124.2   380.9
  5135.9  380.86  5144.4  384.95  5154.5  386.26  5194.8  388.12  5298.1  391.23
  5326.1  392.44  5396.7  393.01  5406.8  394.26  5428.5  393.75  5519.5  395.93
#Mann= 5 ,-1 , 0
  4669.4     .05       0  4918.6     .16       0  5020.2     .07       0
  5026.2     .16       0  5298.1     .05       0
Bank Sta=4962.6,5064.1
XS Rating Curve= 0 ,0
Exp/Cntr=0.3,0.1

Type RM Length L Ch R = 1 ,32698   ,569,569,569
BEGIN DESCRIPTION:
GUM CREEK 68.0
END DESCRIPTION:
XS GIS Cut Line= 3
      3748049.57     10610710.16      3748249.61     10610860.19
      3748549.65     10611010.21
#Sta/Elev= 30
  4727.5  392.97  4784.8   390.4  4824.4  388.08    4864  386.56  4905.7  386.34
  4920.3  384.67  4934.8  383.87    4964  384.04  4974.4  382.26  4980.3  382.26
  4985.9  379.71  5005.3  379.07    5008  378.57  5011.3  379.07  5013.9  379.68
  5044.6  381.69    5067  382.09  5097.7  383.62  5120.1  383.58  5125.7   384.5
  5134.1  383.35  5142.5  382.91    5148  384.79  5156.4  386.24  5170.4  385.56
  5201.2  387.06  5215.1  386.84  5231.9  387.74  5259.8  387.92    5313  389.47
#Mann= 4 ,-1 , 0
  4727.5     .05       0  4824.4     .16       0  5005.3     .07       0
  5011.3     .16       0
Bank Sta=4980.3,5044.6
XS Rating Curve= 0 ,0
Exp/Cntr=0.3,0.1

Type RM Length L Ch R = 1 ,32129   ,398,398,398
BEGIN DESCRIPTION:
GUM CREEK 67.0
END DESCRIPTION:
XS GIS Cut Line= 3
       3747679.2     10611152.26      3748061.12     10611301.56
      3748545.88     10611343.11
#Sta/Elev= 30
  4485.4   391.9  4546.6     390  4606.3  389.38  4625.4  388.47  4630.8  389.14
  4769.2  383.91  4793.7  381.86  4818.2     382    4848  380.18  4883.2  379.42
    4904  376.68  4924.1  377.67  4954.2  376.88  4971.2  375.23    4974  374.73
  4977.2  375.23  5004.4  376.62  5024.4  379.91  5044.5  381.47  5057.3  381.66
  5074.6  383.13  5134.8  385.93  5164.9  386.25  5171.1  387.22  5215.1  388.74
  5235.2  388.55  5275.3  389.57  5295.4   390.4  5305.5  391.57    5382  391.52
#Mann= 3 ,-1 , 0
  4485.4     .16       0  4971.2     .07       0  4977.2     .16       0
Bank Sta=4954.2,5004.4
XS Rating Curve= 0 ,0
Exp/Cntr=0.3,0.1

Type RM Length L Ch R = 1 ,31731   ,435,435,435
BEGIN DESCRIPTION:
GUM CREEK 66.0
END DESCRIPTION:
XS GIS Cut Line= 3
      3747699.62      10611360.2      3747999.61     10611660.19
      3748299.56     10611660.19
#Sta/Elev= 30
  4579.8  394.02  4636.4  391.08  4678.8  387.88  4692.9  386.41  4735.3  383.54
  4763.6  382.15  4777.8  380.78  4791.9  380.45  4806.1  378.75  4834.3  376.87
  4862.6  377.12  4876.8  377.77  4919.2  377.52  4955.8  376.53  5027.9  375.39
    5044  375.37    5061  374.43  5063.8  373.93    5067  374.43    5094  374.43
    5104  375.89    5114  375.26    5124   377.7    5144  379.87    5164  381.03
    5174   382.2    5204  384.53    5214  384.91    5224  386.02    5304  390.69
#Mann= 5 ,-1 , 0
  4579.8     .16       0  4955.8     .12       0  5027.9     .16       0
    5061     .07       0    5067     .16       0
Bank Sta=5044,5104
XS Rating Curve= 0 ,0
Exp/Cntr=0.3,0.1

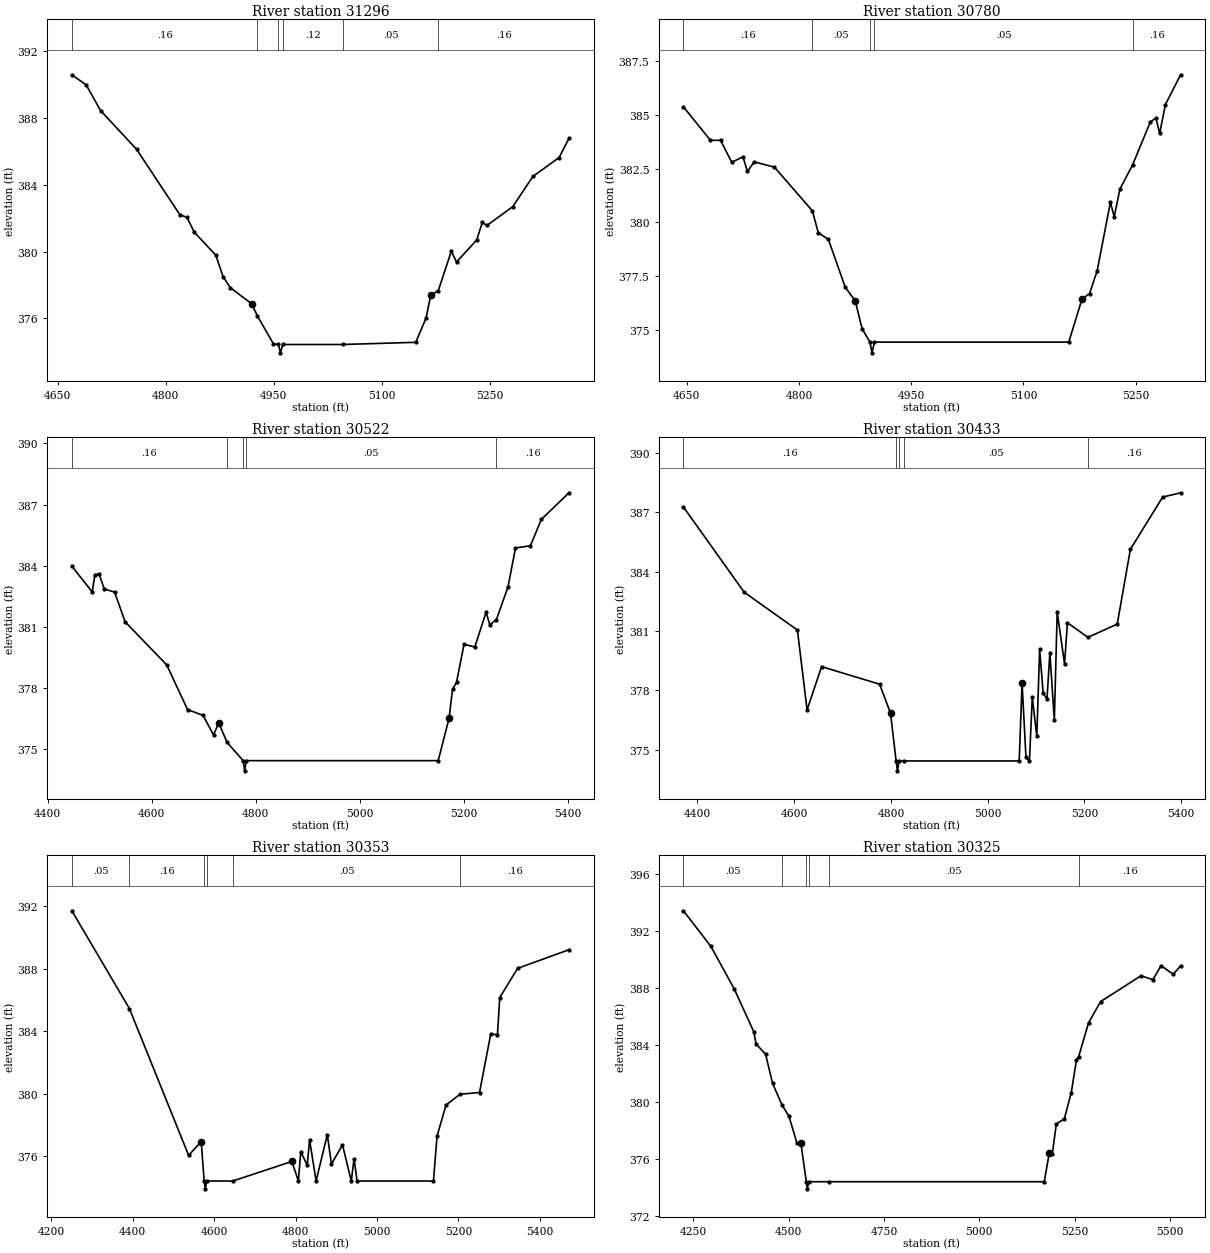
Type RM Length L Ch R = 1 ,31296   ,516,516,516
BEGIN DESCRIPTION:
GUM CREEK 65.0
END DESCRIPTION:
XS GIS Cut Line= 3
      3747649.62     10612110.19      3747949.61     10612110.19
      3748249.61     10611860.19
#Sta/Elev= 30
  4669.6  390.59  4689.6  389.98  4709.6  388.44  4759.6  386.12  4819.6  382.21
  4829.6  382.04  4839.6  381.16  4869.6  379.78  4879.6   378.5  4889.6  377.84
  4919.6  376.86  4927.2  376.15  4949.6  374.47  4956.6  374.43  4959.3  373.93
  4962.6  374.43  5045.6  374.43  5147.3  374.56  5161.6  376.01  5168.1  377.38
  5178.6  377.66  5196.7  380.02  5203.9  379.37  5231.9  380.69  5239.7  381.74
  5246.2  381.56    5282  382.69    5310   384.5  5346.4  385.63  5360.1  386.78
#Mann= 6 ,-1 , 0
  4669.6     .16       0  4927.2     .12       0  4956.6     .07       0
  4962.6     .12       0  5045.6     .05       0  5178.6     .16       0
Bank Sta=4919.6,5168.1
XS Rating Curve= 0 ,0
Exp/Cntr=0.3,0.1

Type RM Length L Ch R = 1 ,30780   ,258,258,258
BEGIN DESCRIPTION:
GUM CREEK 64.0
END DESCRIPTION:
XS GIS Cut Line= 3
      3747649.61     10612410.19      3747949.61     10612610.19
      3748249.62     10612560.19
#Sta/Elev= 30
  4645.4  385.38  4681.5  383.82    4695  383.82    4710   382.8    4725  383.05
    4731  382.37    4740  382.82  4767.1  382.57  4817.8  380.54  4825.7  379.52
  4839.2  379.21  4861.7  376.99  4875.2  376.34  4884.3  375.05  4894.8  374.43
  4897.5  373.93  4900.8  374.43  5160.6  374.43  5178.3  376.43  5188.4  376.69
  5198.6  377.75  5216.3  380.94  5221.4  380.26    5229  381.55  5245.9  382.67
  5269.5  384.66  5277.1  384.86  5282.2  384.14  5289.8  385.48  5310.1  386.87
#Mann= 5 ,-1 , 0
  4645.4     .16       0  4817.8     .05       0  4894.8    .033       0
  4900.8     .05       0  5245.9     .16       0
Bank Sta=4875.2,5178.3
XS Rating Curve= 0 ,0
Exp/Cntr=0.3,0.1

Type RM Length L Ch R = 1 ,30522   ,89,89,89
BEGIN DESCRIPTION:
Mapping XS fd46a809
END DESCRIPTION:
XS GIS Cut Line= 4
      3747477.32     10612954.03      3747845.37     10612964.44
      3748083.21     10612796.04       3748270.7     10612566.89
#Sta/Elev= 30
  4446.3  383.98  4485.5  382.71  4490.5  383.55  4498.6   383.6  4508.6  382.86
  4528.6   382.7  4548.6  381.25  4628.7  379.13  4668.7  376.94  4698.7  376.65
  4718.7  375.69  4728.7  376.29  4744.6  375.33  4775.7  374.43  4778.5  373.93
  4781.7  374.43  5150.6  374.43  5171.5  376.51  5178.1  377.93  5185.8  378.27
  5200.2  380.14    5221  380.01  5242.7  381.72  5249.7   381.1  5262.3  381.34
  5284.9  382.97  5299.2  384.87  5327.9  384.98  5348.8  386.27    5402  387.58
#Mann= 5 ,-1 , 0
  4446.3     .16       0  4744.6     .05       0  4775.7    .033       0
  4781.7     .05       0  5262.3     .16       0
Bank Sta=4728.7,5171.5
XS Rating Curve= 0 ,0
Exp/Cntr=0.3,0.1

Type RM Length L Ch R = 1 ,30433   ,80,80,80
BEGIN DESCRIPTION:
Mapping XS 26e82deb
END DESCRIPTION:
XS GIS Cut Line= 4
      3747473.88     10613047.78      3747892.24     10613047.78
      3748083.21     10612901.94      3748282.86     10612591.19
#Sta/Elev= 30
  4370.9  387.27  4496.6  382.96  4606.6  381.05  4626.6  377.01  4656.6   379.2
  4776.6  378.31  4799.2  376.84  4810.7  374.43  4813.5  373.93  4816.7  374.43
  4827.6  374.43  5065.2  374.43  5071.2  378.35  5079.2  374.62  5086.4  374.43
  5092.3  377.65  5101.6  375.68  5107.5  380.07  5114.8  377.86  5122.7  377.56
  5128.6  379.89  5137.9  376.49  5143.8  381.96    5159  379.34    5165  381.42
  5207.3  380.68    5268  381.35  5295.1  385.13  5361.8  387.77  5398.9  387.99
#Mann= 5 ,-1 , 0
  4370.9     .16       0  4810.7    .033       0  4816.7     .16       0
  4827.6     .05       0  5207.3     .16       0
Bank Sta=4799.2,5071.2
XS Rating Curve= 0 ,0
Exp/Cntr=0.3,0.1

Type RM Length L Ch R = 1 ,30353   ,28,28,28
BEGIN DESCRIPTION:
Mapping XS 7857f87a
END DESCRIPTION:
XS GIS Cut Line= 5
      3747411.33     10613240.49      3747921.76     10613112.01
      3748031.13     10613051.25      3748131.83     10612959.23
      3748334.76     10612575.91
#Sta/Elev= 30
  4250.2  391.71  4391.6  385.46  4537.2  376.07  4568.1  376.95  4575.4  374.43
  4578.2  373.93  4581.4  374.43  4645.7  374.43  4790.9  375.68  4806.9  374.43
  4812.7   376.3  4828.7  375.44  4834.4  377.07  4850.4  374.43  4877.9  377.39
  4888.2  375.51  4915.3  376.74  4936.9  374.43  4943.7  375.86  4951.1  374.43
  5138.8  374.43  5147.7  377.31  5169.7  379.29  5204.3  379.98    5252  380.09
  5279.7  383.85    5296  383.77  5301.7  386.16  5345.7  388.03  5471.8  389.22
#Mann= 6 ,-1 , 0
  4250.2     .05       0  4391.6     .16       0  4575.4    .033       0
  4581.4     .16       0  4645.7     .05       0  5204.3     .16       0
Bank Sta=4568.1,4790.9
XS Rating Curve= 0 ,0
Exp/Cntr=0.3,0.1

Type RM Length L Ch R = 1 ,30325   ,393,393,393
BEGIN DESCRIPTION:
GUM CREEK 63.0
END DESCRIPTION:
XS GIS Cut Line= 4
      3747409.59     10613287.36      3747907.87     10613174.51
      3748235.99     10612915.83       3748355.2     10612561.68
#Sta/Elev= 30
  4224.7  393.43  4296.5  390.94    4358  387.94  4409.3  384.93    4415  384.09
    4440  383.37  4458.2  381.33  4482.8  379.82  4501.3  379.01  4522.1  377.13
  4532.3  377.16  4546.6  374.43  4549.3  373.93  4552.6  374.43  4606.1  374.43
  5169.9  374.43  5183.1  376.42    5191  376.36  5201.6  378.48  5222.7  378.84
  5240.8  380.68  5254.3  382.96  5260.2  383.21    5286  385.57  5317.6  387.06
  5423.2  388.87  5454.8   388.6  5475.9  389.58  5507.6  388.98  5527.1  389.56
#Mann= 6 ,-1 , 0
  4224.7     .05       0  4482.8     .16       0  4546.6    .033       0
  4552.6     .16       0  4606.1     .05       0  5260.2     .16       0
Bank Sta=4532.3,5183.1
XS Rating Curve= 0 ,0
Exp/Cntr=0.3,0.1

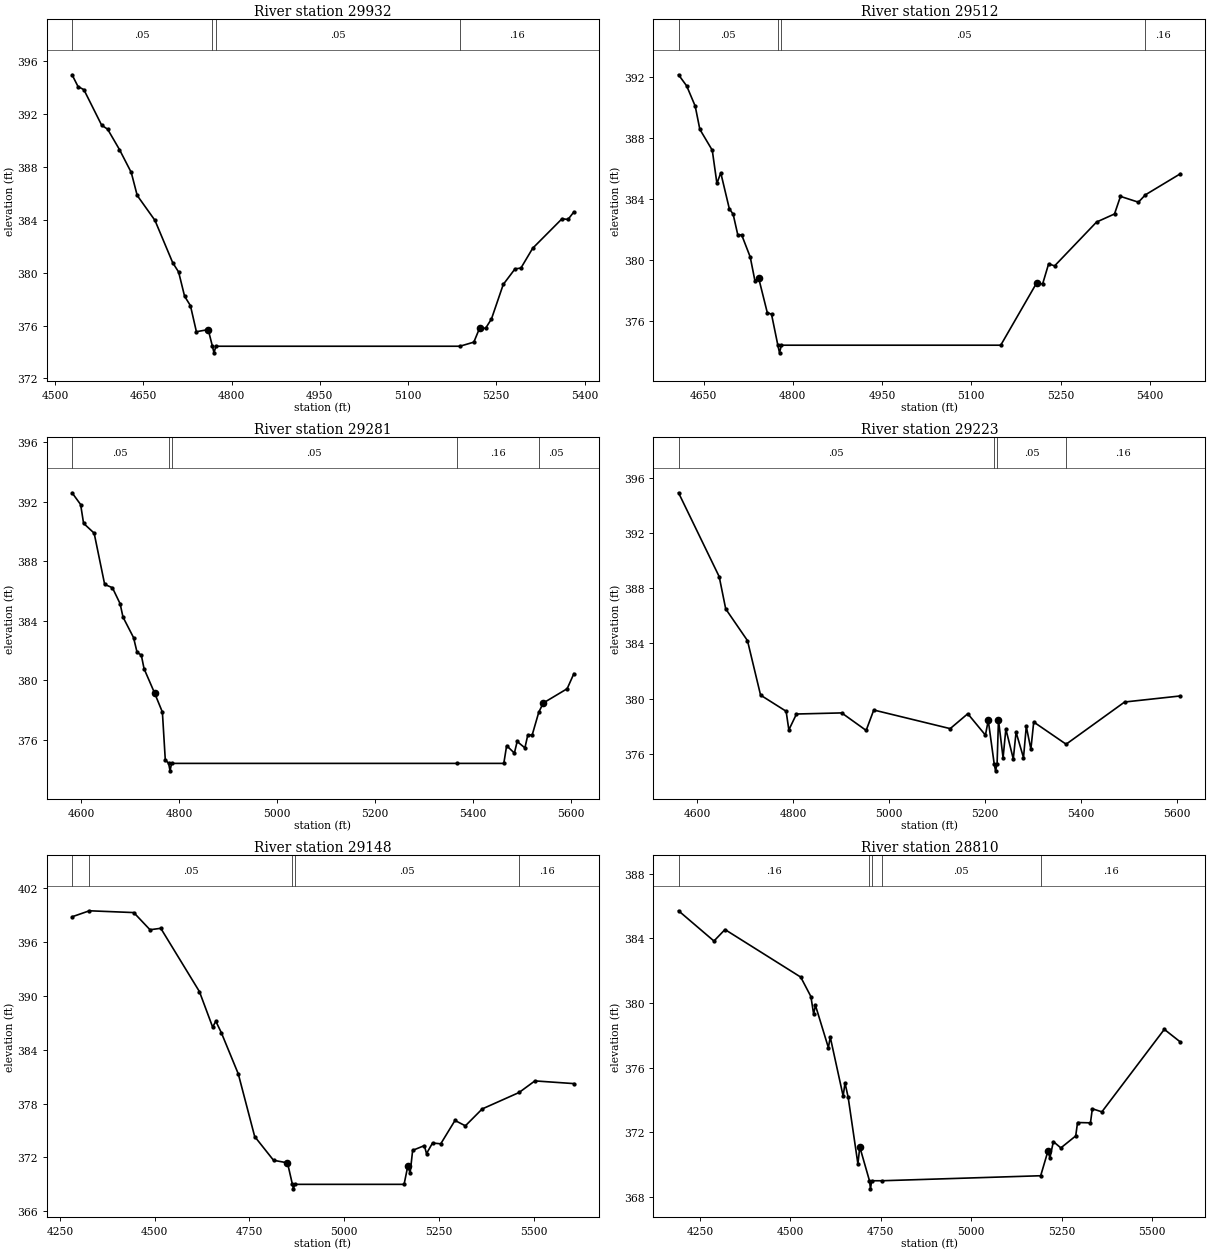
Type RM Length L Ch R = 1 ,29932   ,420,420,420
BEGIN DESCRIPTION:
GUM CREEK 62.0
END DESCRIPTION:
XS GIS Cut Line= 3
      3747499.61     10613410.19      3747949.61     10613360.19
      3748349.64     10613360.19
#Sta/Elev= 30
    4529  394.99  4539.1   394.1  4549.1  393.86  4579.3  391.17  4589.4  390.87
  4609.5  389.33  4629.6  387.59  4639.7  385.85  4669.9  383.96    4700  380.76
  4710.1  380.05  4720.2  378.22  4730.2   377.5  4740.3  375.53  4760.4  375.69
  4767.5  374.43  4770.2  373.93  4773.5  374.43  5188.1  374.43  5211.8  374.74
  5221.8  375.82  5231.8  375.79  5241.8   376.5  5261.8  379.11  5281.8  380.29
  5291.8  380.35  5311.8  381.85  5361.8  384.09  5371.8  384.03  5381.8   384.6
#Mann= 4 ,-1 , 0
    4529     .05       0  4767.5    .033       0  4773.5     .05       0
  5188.1     .16       0
Bank Sta=4760.4,5221.8
XS Rating Curve= 0 ,0
Exp/Cntr=0.3,0.1

Type RM Length L Ch R = 1 ,29512   ,231,231,231
BEGIN DESCRIPTION:
GUM CREEK 61.0
END DESCRIPTION:
XS GIS Cut Line= 3
      3747549.57     10613510.16      3747849.61     10613760.19
      3748299.58     10613710.19
#Sta/Elev= 30
    4608  392.13  4621.7   391.4    4636  390.08  4643.8  388.56  4664.7  387.19
  4672.5  385.02    4679  385.71  4693.3  383.37  4699.8     383  4707.6  381.65
  4714.1  381.65  4728.5   380.2  4736.3  378.66  4742.8   378.8  4757.1  376.57
  4764.3  376.45  4774.9  374.43  4777.7  373.93  4780.9  374.43  5149.5  374.43
  5209.9  378.51  5219.9  378.44    5230  379.76    5240  379.62  5310.5  382.49
  5340.7  383.02  5350.7  384.17  5380.9  383.79  5392.5  384.27  5451.3  385.65
#Mann= 4 ,-1 , 0
    4608     .05       0  4774.9    .033       0  4780.9     .05       0
  5392.5     .16       0
Bank Sta=4742.8,5209.9
XS Rating Curve= 0 ,0
Exp/Cntr=0.3,0.1

Type RM Length L Ch R = 1 ,29281   ,58,58,58
BEGIN DESCRIPTION:
Mapping XS caafbff0
END DESCRIPTION:
XS GIS Cut Line= 2
      3747394.47     10613763.37      3748283.35     10614273.78
#Sta/Elev= 30
  4580.9  392.59  4598.4   391.8  4604.4  390.54    4626  389.88  4647.5  386.44
  4663.3  386.22  4679.1  385.14  4684.9  384.25  4706.5  382.87  4713.7  381.88
  4722.3   381.7    4728  380.78  4749.6  379.14  4765.4  377.87  4771.3  374.67
  4778.2  374.43    4781  373.93  4784.2  374.43  5367.5  374.43  5462.8  374.43
  5468.6  375.62  5484.4  375.12  5490.1   375.9  5505.9  375.47  5511.7  376.32
  5520.9  376.35  5534.1  377.85  5543.3  378.48  5592.2  379.44  5605.9  380.45
#Mann= 5 ,-1 , 0
  4580.9     .05       0  4778.2    .033       0  4784.2     .05       0
  5367.5     .16       0  5534.1     .05       0
Bank Sta=4749.6,5543.3
XS Rating Curve= 0 ,0
Exp/Cntr=0.3,0.1

Type RM Length L Ch R = 1 ,29223   ,75,75,75
BEGIN DESCRIPTION:
GUM CREEK 60.0
END DESCRIPTION:
XS GIS Cut Line= 3
       3747344.2     10613801.28      3747740.89     10614028.18
      3748244.02     10614335.59
#Sta/Elev= 30
  4561.2  394.92    4646  388.84  4659.6   386.5    4705   384.2  4732.3  380.25
  4785.6  379.08  4791.3  377.73  4807.2  378.88  4901.5  378.96  4952.5  377.69
  4968.4  379.17  5127.8  377.82  5164.5   378.9  5201.3  377.35  5207.2  378.42
  5219.6  375.26  5222.4  374.76  5225.6  375.26  5228.5  378.45  5238.1   375.7
  5243.9  377.79  5259.4  375.62  5265.2  377.56  5280.7  375.72  5286.5  377.98
  5296.1  376.33    5302   378.3  5369.6  376.69  5491.6  379.75  5607.8  380.19
#Mann= 4 ,-1 , 0
  4561.2     .05       0  5219.6    .033       0  5225.6     .05       0
  5369.6     .16       0
Bank Sta=5207.2,5228.5
XS Rating Curve= 0 ,0
Exp/Cntr=0.3,0.1

Type RM Length L Ch R = 1 ,29148   ,338,338,338
BEGIN DESCRIPTION:
Mapping XS 8c23f340
END DESCRIPTION:
XS GIS Cut Line= 3
      3747118.14     10613651.73      3747306.92     10613868.73
      3748210.39     10614377.92
#Sta/Elev= 30
  4281.6  398.78  4327.3  399.45  4444.5  399.25  4487.3  397.34  4515.8   397.5
  4617.8  390.46  4652.7  386.51  4661.1  387.16  4675.6  385.89  4720.4   381.3
  4763.7  374.33  4813.4  371.69  4850.3   371.4  4863.3  369.01    4866  368.51
  4869.3  369.01  5158.1  369.01  5168.2   371.1    5174  370.24  5180.7  372.79
  5211.6  373.32  5217.3  372.43  5233.2  373.61  5254.9  373.52  5292.5  376.12
  5319.9  375.52  5364.3   377.4  5461.7  379.23  5503.4  380.52  5606.3  380.22
#Mann= 5 ,-1 , 0
  4281.6     .16       0  4327.3     .05       0  4863.3    .033       0
  4869.3     .05       0  5461.7     .16       0
Bank Sta=4850.3,5168.2
XS Rating Curve= 0 ,0
Exp/Cntr=0.3,0.1

Type RM Length L Ch R = 1 ,28810   ,240,240,240
BEGIN DESCRIPTION:
Mapping XS f9243e22
END DESCRIPTION:
XS GIS Cut Line= 2
      3746684.92     10614142.15      3748029.87     10614485.55
#Sta/Elev= 30
  4190.5   385.7  4288.5  383.83    4319  384.54  4528.5   381.6  4556.6   380.4
  4564.2  379.32  4569.3  379.85    4605  377.24  4610.2  377.89  4645.9  374.24
    4651  375.06  4659.8  374.16  4686.7  370.05  4691.9   371.1  4718.7  369.01
  4721.5  368.51  4724.7  369.01  4753.3  369.01  5192.3  369.32  5212.6  370.86
  5217.8  370.42  5227.4  371.43  5248.1  371.04  5289.2  371.78  5294.3  372.61
    5330  372.59  5335.2  373.46  5361.6  373.27  5534.3  378.37  5578.6  377.59
#Mann= 5 ,-1 , 0
  4190.5     .16       0  4718.7    .033       0  4724.7     .16       0
  4753.3     .05       0  5192.3     .16       0
Bank Sta=4691.9,5212.6
XS Rating Curve= 0 ,0
Exp/Cntr=0.3,0.1

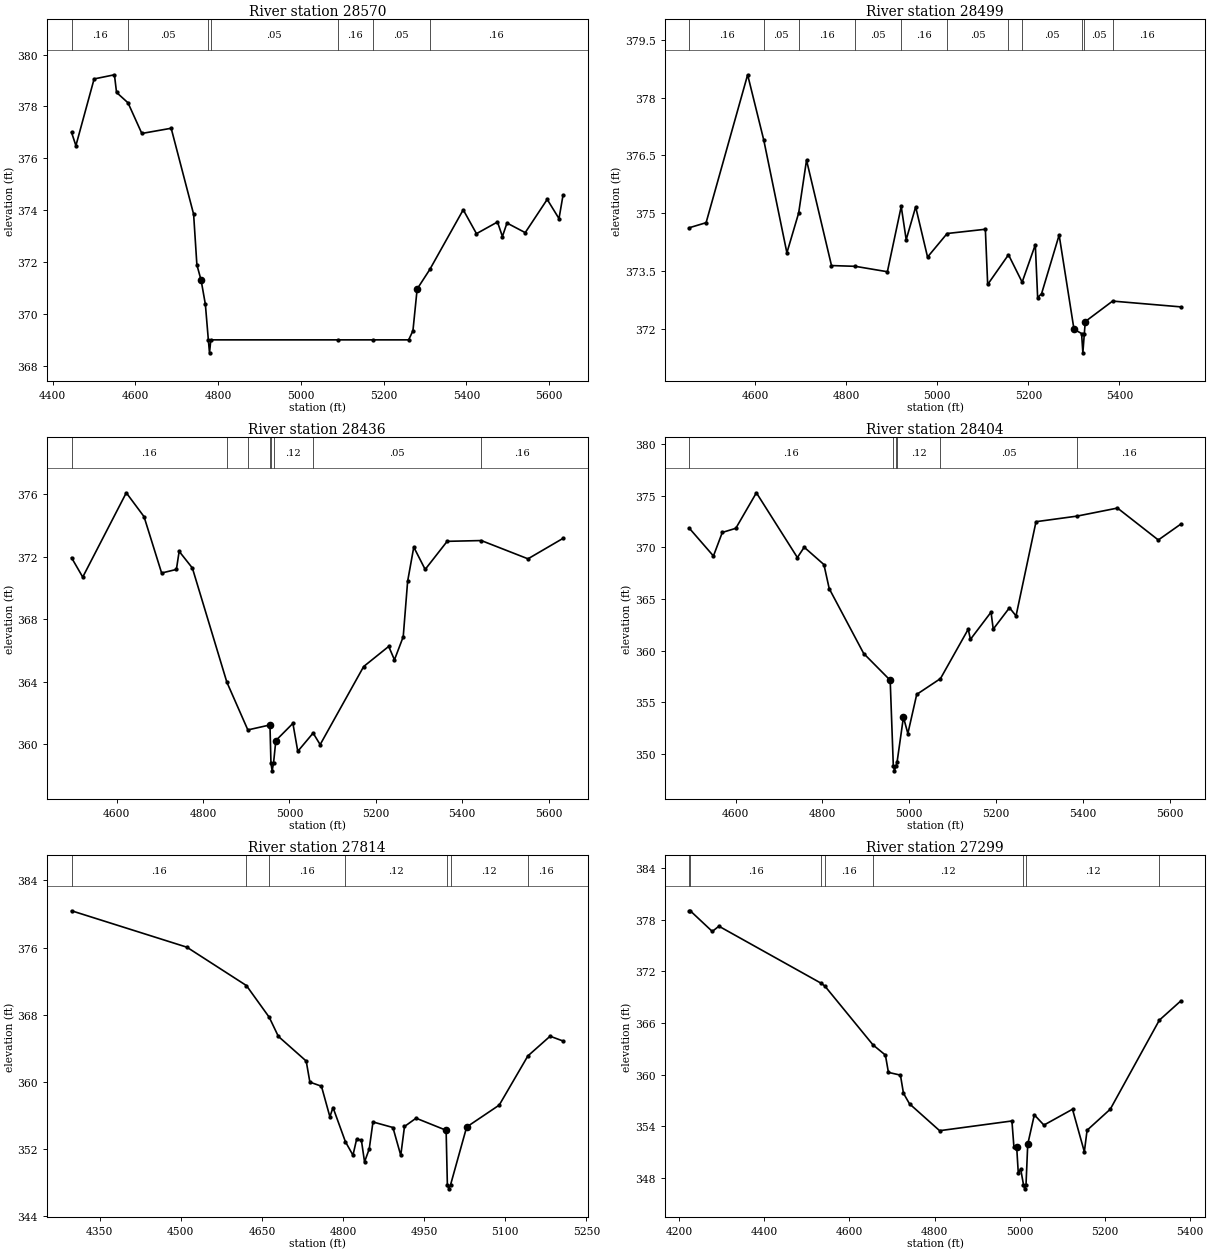
Type RM Length L Ch R = 1 ,28570   ,71,71,71
BEGIN DESCRIPTION:
GUM CREEK 59.0
END DESCRIPTION:
XS GIS Cut Line= 3
      3746793.72     10614423.07      3747793.37     10614640.69
       3747942.5     10614709.72
#Sta/Elev= 30
  4445.8     377  4456.3  376.49  4500.3  379.06  4549.4  379.22  4554.5  378.54
  4582.2  378.14  4615.6  376.96  4686.5  377.16  4740.7  373.85  4748.6   371.9
  4758.9   371.3  4769.1  370.38  4776.3  369.01  4779.1  368.51  4782.3  369.01
  5089.2  369.01  5173.6  369.01  5260.3  369.01  5270.6  369.36  5280.8  370.97
  5311.3  371.72  5392.1  374.02  5424.1   373.1  5474.9  373.55  5486.8  372.99
  5497.8  373.51  5541.9  373.14    5595  374.42  5623.5  373.68  5633.2  374.58
#Mann= 7 ,-1 , 0
  4445.8     .16       0  4582.2     .05       0  4776.3    .033       0
  4782.3     .05       0  5089.2     .16       0  5173.6     .05       0
  5311.3     .16       0
Bank Sta=4758.9,5280.8
XS Rating Curve= 0 ,0
Exp/Cntr=0.3,0.1

Type RM Length L Ch R = 1 ,28499   ,63,63,63
BEGIN DESCRIPTION:
Mapping XS eb83b85d
END DESCRIPTION:
XS GIS Cut Line= 5
      3746765.37     10614477.85      3747185.47     10614573.33
      3747385.12     10614621.94      3747650.75     10614672.29
       3747815.1     10614724.19
#Sta/Elev= 30
  4455.7  374.63  4492.4  374.76  4583.6  378.59    4619   376.9  4669.8  373.98
  4695.6  375.01  4712.9  376.38  4767.7  373.65  4820.1  373.63  4890.4  373.49
  4920.8  375.18  4931.7  374.32  4952.5  375.17  4978.6  373.87  5021.6  374.48
  5105.5  374.59  5110.6  373.16  5156.3  373.93  5186.3  373.22  5215.2  374.19
  5220.3  372.82  5228.9  372.92  5267.5  374.44  5300.1     372  5316.8  371.89
  5319.6  371.39  5322.8  371.89  5324.9   372.2  5384.9  372.73  5534.7  372.58
#Mann= 11 ,-1 , 0
  4455.7     .16       0    4619     .05       0  4695.6     .16       0
  4820.1     .05       0  4920.8     .16       0  5021.6     .05       0
  5156.3     .16       0  5186.3     .05       0  5316.8     .07       0
  5322.8     .05       0  5384.9     .16       0
Bank Sta=5300.1,5324.9
XS Rating Curve= 0 ,0
Exp/Cntr=0.3,0.1

Type RM Length L Ch R = 1 ,28436   ,32,32,32
BEGIN DESCRIPTION:
GUM CREEK 58.0
END DESCRIPTION:
XS GIS Cut Line= 3
      3746764.61      10614561.3       3747723.5     10614738.63
      3747875.34     10614796.67
#Sta/Elev= 30
  4495.7  371.93  4521.6  370.69  4622.4  376.09  4663.5  374.56  4704.2  370.95
  4738.4  371.18  4744.8  372.34  4775.4  371.27  4855.2  363.96  4903.8   360.9
    4955  361.22  4957.3  358.78    4960  358.28  4963.3  358.78  4968.6  360.22
  5008.1  361.32  5019.4  359.53  5054.9   360.7  5071.2  359.96  5171.9  364.96
  5229.9  366.25  5243.2  365.39  5263.5  366.87  5273.7  370.42  5287.9  372.61
  5314.3  371.18  5365.2  372.98  5444.2  373.03  5552.3  371.86  5633.4  373.17
#Mann= 8 ,-1 , 0
  4495.7     .16       0  4855.2     .05       0  4903.8     .16       0
    4955     .12       0  4957.3     .07       0  4963.3     .12       0
  5054.9     .05       0  5444.2     .16       0
Bank Sta=4955,4968.6
XS Rating Curve= 0 ,0
Exp/Cntr=0.3,0.1

Type RM Length L Ch R = 1 ,28404   ,590,590,590
BEGIN DESCRIPTION:
Mapping XS 358a38cf
END DESCRIPTION:
XS GIS Cut Line= 3
      3746745.16     10614586.28      3747675.96     10614761.22
      3747845.43     10614834.41
#Sta/Elev= 30
  4493.8  371.84  4549.2  369.16  4569.6  371.44  4600.7  371.84  4648.1  375.28
  4742.5  369.01  4758.2  370.01  4803.6  368.33  4815.8     366  4895.2  359.72
  4956.2  357.13  4963.4  348.86  4966.1  348.36  4969.4  348.86    4972  349.18
  4986.7  353.56  4996.9  351.97  5017.3  355.76    5072  357.29  5135.9  362.07
    5141  361.09  5188.4  363.72  5193.5  362.08  5230.9  364.15    5246  363.36
    5292  372.48  5386.4  373.02  5479.6   373.8  5573.6  370.71  5625.5  372.25
#Mann= 6 ,-1 , 0
  4493.8     .16       0  4963.4     .07       0  4969.4     .16       0
    4972     .12       0    5072     .05       0  5386.4     .16       0
Bank Sta=4956.2,4986.7
XS Rating Curve= 0 ,0
Exp/Cntr=0.3,0.1

Type RM Length L Ch R = 1 ,27814   ,515,515,515
BEGIN DESCRIPTION:
GUM CREEK 57.0
END DESCRIPTION:
XS GIS Cut Line= 3
      3746237.31     10614718.11      3746795.03     10615052.31
      3747042.45     10615128.27
#Sta/Elev= 30
  4297.8  380.38  4511.1  376.04  4621.2  371.47  4663.4  367.69  4680.3  365.41
  4731.8  362.47  4738.6  359.96    4760  359.47  4775.6  355.83  4781.4  356.93
  4804.3  352.86  4818.3  351.25  4825.1  353.16  4833.9  353.03  4839.7  350.45
  4848.4     352  4855.3  355.21  4892.2  354.55  4906.7  351.23  4913.6  354.67
    4935  355.66  4990.6  354.22  4992.9  347.74  4995.6  347.24  4998.9  347.74
  5028.6  354.61  5088.8  357.22  5141.8  363.08  5182.9  365.43  5206.8  364.86
#Mann= 7 ,-1 , 0
  4297.8     .16       0  4621.2     .12       0  4663.4     .16       0
  4804.3     .12       0  4992.9     .07       0  4998.9     .12       0
  5141.8     .16       0
Bank Sta=4990.6,5028.6
XS Rating Curve= 0 ,0
Exp/Cntr=0.3,0.1

Type RM Length L Ch R = 1 ,27299   ,282,282,282
BEGIN DESCRIPTION:
GUM CREEK 56.0
END DESCRIPTION:
XS GIS Cut Line= 4
      3746139.68     10614937.31      3746465.17     10615126.09
      3746740.77      10615401.7      3747085.22     10615579.34
#Sta/Elev= 30
  4224.2  379.04  4226.2  379.04    4278  376.64  4293.5  377.25  4534.1  370.61
  4542.4  370.29  4655.2  363.47  4684.3  362.29  4691.4  360.28  4719.6  359.96
  4726.7  357.86  4740.9  356.63  4811.6  353.51  4981.3  354.64  4985.9  351.67
  4992.4  351.67  4996.2  348.61  5001.8  349.06  5008.4  347.26  5011.2  346.76
  5014.4  347.26  5018.4  351.93  5033.9  355.35  5056.4  354.16  5123.5     356
  5151.3  351.06  5157.7  353.56  5212.2  356.01  5327.3  366.34  5377.8  368.58
#Mann= 8 ,-1 , 0
  4224.2      .1       0  4226.2     .16       0  4534.1     .12       0
  4542.4     .16       0  4655.2     .12       0  5008.4     .07       0
  5014.4     .12       0  5327.3     .16       0
Bank Sta=4992.4,5018.4
XS Rating Curve= 0 ,0
Exp/Cntr=0.3,0.1