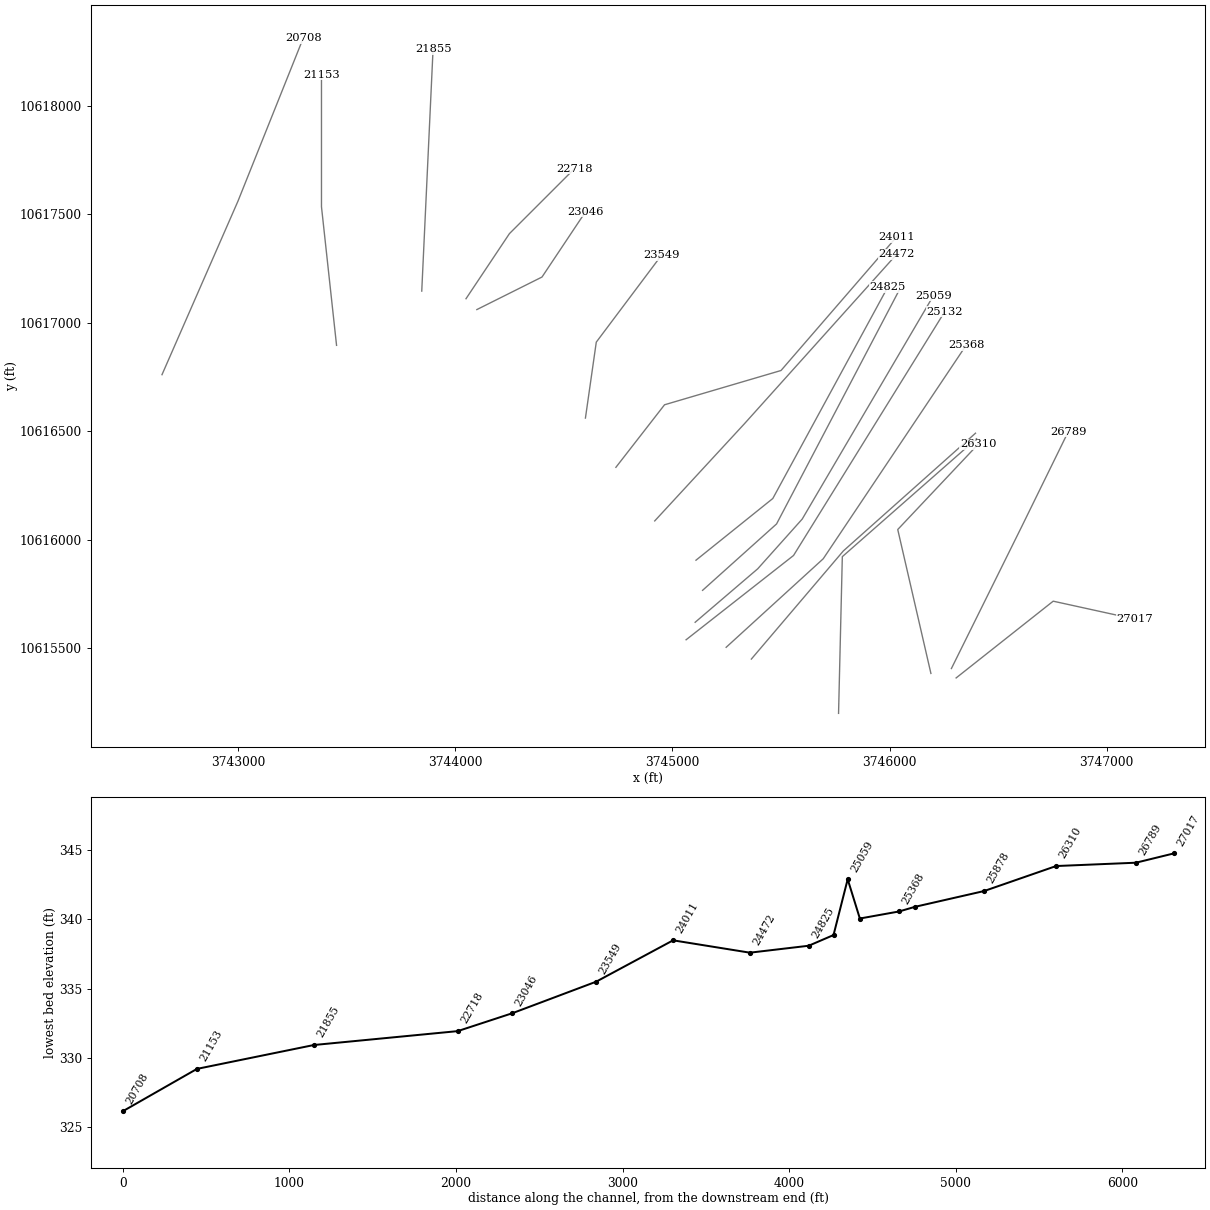
HEC-RAS study GUM CREEK.prj: GUM CREEK Base Level Engineering

--- GUM CREEK.g01 (geometry) --- (continued)

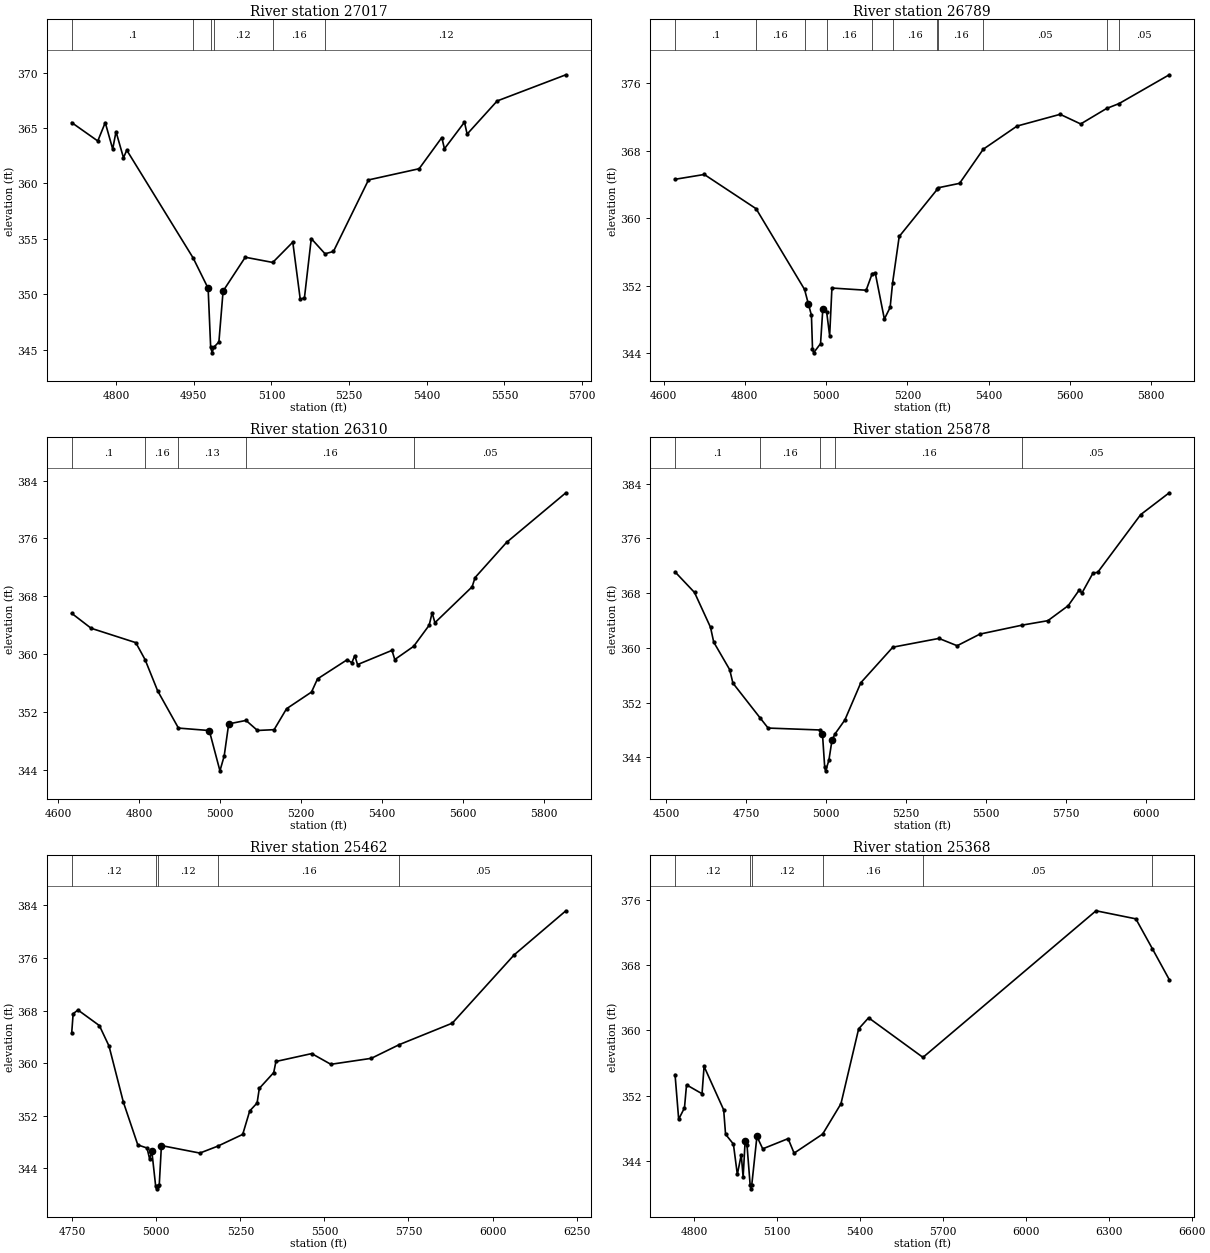
Type RM Length L Ch R = 1 ,27017   ,228,228,228
BEGIN DESCRIPTION:
Mapping XS 7f32df7f
END DESCRIPTION:
XS GIS Cut Line= 3
      3746306.75     10615362.64      3746753.79     10615716.37
      3747129.18     10615633.92
#Sta/Elev= 30
  4714.3  365.49  4764.7  363.83  4779.1  365.49  4793.5   363.1  4799.9  364.67
  4814.3  362.32  4820.7     363  4948.9  353.28  4977.8  350.55  4982.7  345.23
  4985.5  344.73  4988.7  345.23  4998.6  345.71  5006.7   350.3  5049.5  353.35
  5102.6  352.88  5141.3  354.71  5155.7  349.56  5163.8  349.69    5177  355.03
  5203.6  353.66  5219.8  353.87  5287.5  360.32  5385.3  361.33  5429.1  364.14
  5434.2  363.13  5472.9  365.53    5478  364.45    5536  367.44  5668.7   369.8
#Mann= 6 ,-1 , 0
  4714.3      .1       0  4948.9     .12       0  4982.7     .07       0
  4988.7     .12       0  5102.6     .16       0  5203.6     .12       0
Bank Sta=4977.8,5006.7
XS Rating Curve= 0 ,0
Exp/Cntr=0.3,0.1

Type RM Length L Ch R = 1 ,26789   ,479,479,479
BEGIN DESCRIPTION:
GUM CREEK 55.0
END DESCRIPTION:
XS GIS Cut Line= 3
      3746285.03     10615406.02      3746608.39     10616059.25
      3746822.63     10616496.39
#Sta/Elev= 30
  4628.4   364.6  4700.3  365.17  4827.7  361.12    4947  351.56  4956.6   349.8
  4963.9  348.51  4966.5  344.56  4969.2  344.06  4986.3  345.15  4991.9  349.26
  5001.3  348.91  5008.7  346.09  5014.3  351.73  5098.5  351.47  5113.4  353.44
  5120.9  353.51  5143.3  348.06  5157.5  349.44  5163.6  352.36  5179.8  357.83
  5273.7  363.43  5275.1  363.59  5328.3  364.12  5386.6  368.16  5469.7   370.9
  5575.7  372.29  5626.3  371.15  5689.9  372.98  5720.6  373.56  5844.1  376.97
#Mann= 11 ,-1 , 0
  4628.4      .1       0  4827.7     .16       0    4947     .12       0
  5001.3     .16       0  5113.4     .12       0  5163.6     .16       0
  5273.7     .12       0  5275.1     .16       0  5386.6     .05       0
  5689.9     .16       0  5720.6     .05       0
Bank Sta=4956.6,4991.9
XS Rating Curve= 0 ,0
Exp/Cntr=0.3,0.1

Type RM Length L Ch R = 1 ,26310   ,432,432,432
BEGIN DESCRIPTION:
GUM CREEK 54.0
END DESCRIPTION:
XS GIS Cut Line= 3
      3746190.65     10615383.38      3746037.88     10616046.56
      3746407.67     10616438.92
#Sta/Elev= 30
  4633.6  365.63  4681.6  363.56  4791.8  361.57  4814.8  359.21  4845.8  354.89
  4897.1  349.74  4973.2   349.4  4999.5  343.82    5010  345.88  5021.1  350.32
  5063.9   350.8  5092.1  349.41  5133.2  349.52  5163.9  352.42  5225.5  354.73
  5240.3  356.55  5313.4   359.2    5325  358.79  5332.3  359.77  5339.1  358.53
  5424.1   360.5    5431  359.23  5477.6  361.06  5515.9  363.98  5523.2  365.71
  5530.1  364.33  5621.9   369.3  5629.2  370.58  5706.9  375.45  5853.3  382.32
#Mann= 5 ,-1 , 0
  4633.6      .1       0  4814.8     .16       0  4897.1     .13       0
  5063.9     .16       0  5477.6     .05       0
Bank Sta=4973.2,5021.1
XS Rating Curve= 0 ,0
Exp/Cntr=0.3,0.1

Type RM Length L Ch R = 1 ,25878   ,416,416,416
BEGIN DESCRIPTION:
GUM CREEK 53.0
END DESCRIPTION:
XS GIS Cut Line= 3
      3745765.31     10615199.32      3745782.67     10615921.56
      3746400.72     10616464.95
#Sta/Elev= 30
  4527.7  371.09  4588.6  368.08  4638.6  362.99  4648.6  360.83  4698.6   356.8
  4708.6  354.84  4792.9   349.8  4818.7  348.27    4981  347.99  4988.7  347.41
  4995.7  342.52  4998.5  342.02  5008.7  343.55  5018.7  346.56  5028.7  347.47
  5058.7  349.45  5108.7   354.9  5208.8  360.09  5352.9  361.37  5409.8   360.3
    5481     362  5614.2  363.32  5693.5  363.96  5757.1  366.15  5792.2  368.48
  5799.8  367.98  5834.9  370.94  5849.1  371.01  5983.8  379.46  6073.1  382.65
#Mann= 5 ,-1 , 0
  4527.7      .1       0  4792.9     .16       0    4981     .13       0
  5028.7     .16       0  5614.2     .05       0
Bank Sta=4988.7,5018.7
XS Rating Curve= 0 ,0
Exp/Cntr=0.3,0.1

Type RM Length L Ch R = 1 ,25462   ,94,94,94
BEGIN DESCRIPTION:
GUM CREEK 52.0
END DESCRIPTION:
XS GIS Cut Line= 3
      3745363.73      10615449.6      3745787.33     10615947.86
      3746395.97      10616490.5
#Sta/Elev= 30
  4748.6  364.54  4752.9  367.51  4767.2  368.08  4830.9  365.71  4859.5  362.61
  4902.3  354.06  4945.2  347.56  4972.6  347.09  4980.3  345.43  4986.9   346.6
  4998.1  341.38  5000.9  340.88  5004.1  341.38  5008.9  341.42  5015.4  347.46
  5129.7  346.32  5182.9  347.37  5257.1  349.16  5277.9  352.72  5299.9  353.94
  5306.5  356.16  5349.3  358.56  5355.9  360.25  5462.3  361.45  5519.2  359.82
  5639.5  360.73  5722.5  362.81  5880.3  366.08  6064.3  376.47    6218  383.17
#Mann= 5 ,-1 , 0
  4748.6     .12       0  4998.1     .07       0  5004.1     .12       0
  5182.9     .16       0  5722.5     .05       0
Bank Sta=4986.9,5015.4
XS Rating Curve= 0 ,0
Exp/Cntr=0.3,0.1

Type RM Length L Ch R = 1 ,25368   ,236,236,236
BEGIN DESCRIPTION:
Mapping XS 1e91cc61
END DESCRIPTION:
XS GIS Cut Line= 3
      3745247.69     10615503.81      3745694.71     10615911.77
      3746352.26     10616894.84
#Sta/Elev= 30
    4731  354.56  4744.1  349.09  4765.1  350.49  4772.5  353.31  4828.6  352.22
    4836  355.57  4906.9  350.24  4913.7  347.25  4942.1  346.04  4956.3  342.32
  4970.5  344.73  4977.3  341.99  4984.6  346.46  4991.4  345.88  5002.6  341.05
  5005.3  340.55  5008.6  341.05  5027.2  346.98  5048.2  345.46    5140  346.71
  5161.7  344.93    5265  347.27  5331.2  350.99  5395.2  360.18  5431.2  361.54
  5627.9  356.68    6254  374.67  6398.1  373.68  6458.1     370  6518.9  366.23
#Mann= 6 ,-1 , 0
    4731     .12       0  5002.6     .07       0  5008.6     .12       0
    5265     .16       0  5627.9     .05       0  6458.1     .16       0
Bank Sta=4984.6,5027.2
XS Rating Curve= 0 ,0
Exp/Cntr=0.3,0.1

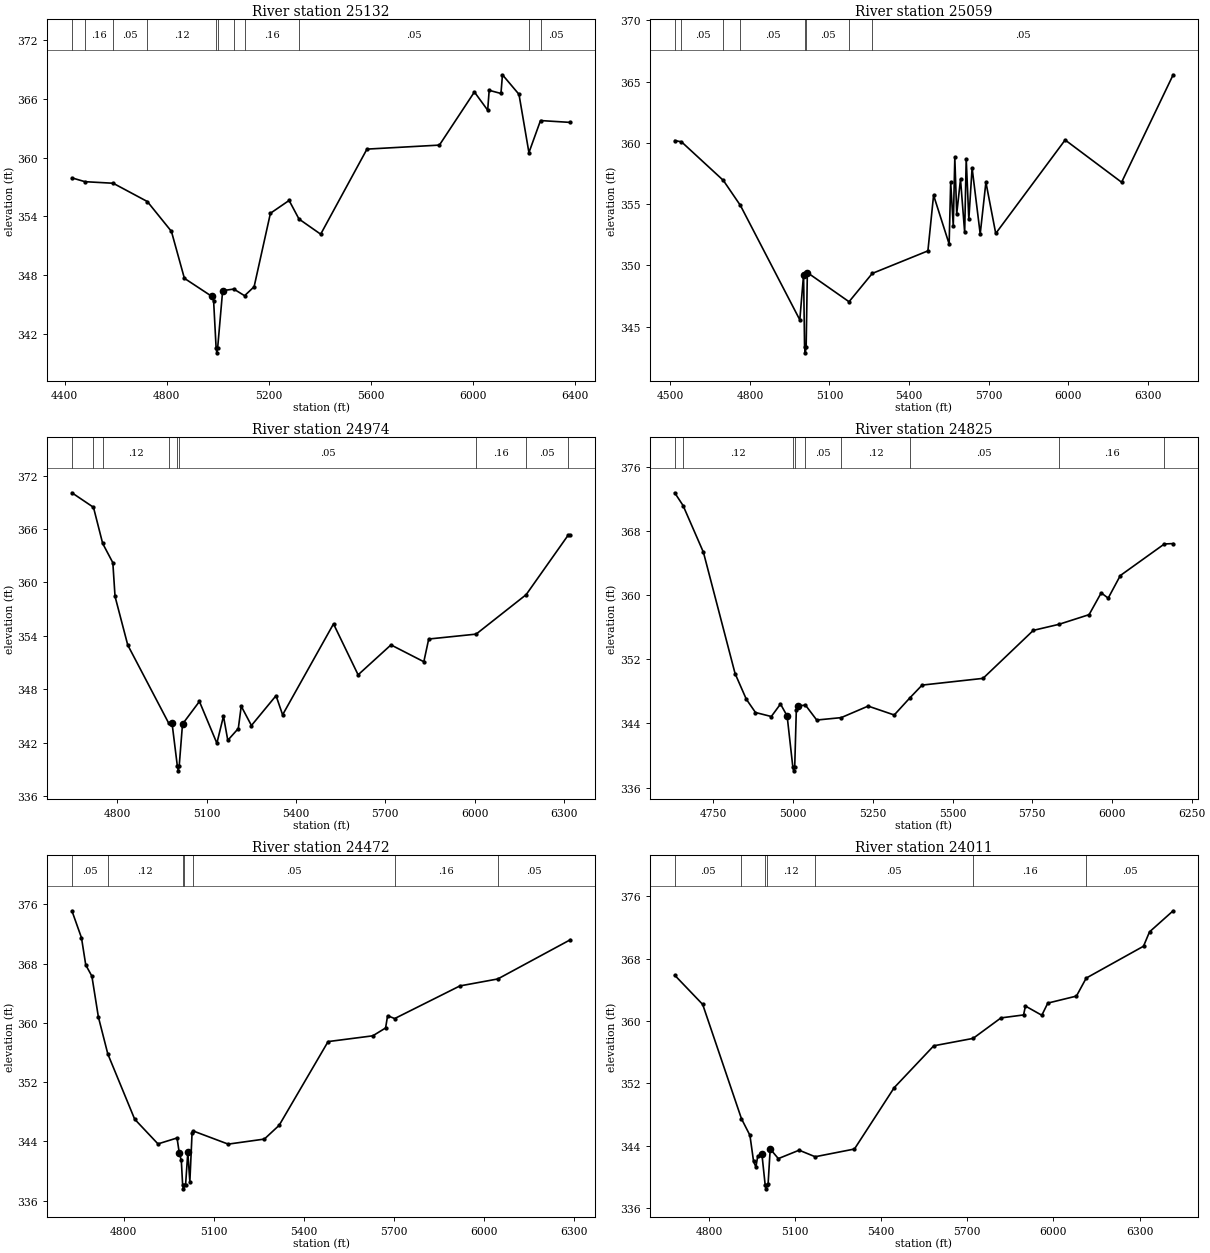
Type RM Length L Ch R = 1 ,25132   ,73,73,73
BEGIN DESCRIPTION:
Mapping XS c8e14d2b
END DESCRIPTION:
XS GIS Cut Line= 3
      3745063.23     10615538.53      3745557.99     10615926.96
      3746254.61      10617051.1
#Sta/Elev= 30
  4428.8  357.93  4479.9  357.54  4590.3  357.38  4724.1  355.51  4818.4  352.46
  4869.2  347.66  4975.6  345.83  4983.6  345.36  4993.4  340.54  4996.2  340.04
  4999.4  340.54    5019   346.4  5062.7  346.56  5104.9  345.88  5142.2   346.8
    5206  354.31  5279.2  355.62  5317.9  353.72  5402.8  352.17    5584  360.87
  5867.6  361.28  6004.6  366.71  6056.6  364.85  6062.5  366.88  6108.6  366.56
  6114.5  368.47  6179.2  366.47  6218.1  360.51  6263.4  363.79  6380.3   363.6
#Mann= 11 ,-1 , 0
  4428.8     .05       0  4479.9     .16       0  4590.3     .05       0
  4724.1     .12       0  4993.4     .07       0  4999.4     .12       0
  5062.7     .05       0  5104.9     .16       0  5317.9     .05       0
  6218.1     .16       0  6263.4     .05       0
Bank Sta=4975.6,5019
XS Rating Curve= 0 ,0
Exp/Cntr=0.3,0.1

Type RM Length L Ch R = 1 ,25059   ,85,85,85
BEGIN DESCRIPTION:
Mapping XS 254b1d8c
END DESCRIPTION:
XS GIS Cut Line= 4
      3745104.91     10615619.12      3745393.13     10615865.67
      3745597.99     10616094.83      3746202.18     10617124.38
#Sta/Elev= 30
  4516.2  360.19  4541.7  360.09  4699.7  356.94    4764   354.9  4988.2  345.56
  5002.4  349.26  5006.1  343.37  5008.9  342.87  5012.1  343.37  5016.6  349.42
  5173.9  347.04  5261.5  349.35  5471.4  351.19  5492.8  355.73  5551.5  351.75
  5557.3  356.78  5567.1  353.22  5572.9  358.81  5580.1  354.21  5594.4  357.04
  5610.1  352.69  5615.9  358.69  5625.8  353.76  5638.1  357.96  5668.7  352.57
  5690.2  356.79  5727.3  352.61  5989.1  360.24  6202.1  356.79  6396.6  365.56
#Mann= 8 ,-1 , 0
  4516.2     .16       0  4541.7     .05       0  4699.7     .08       0
    4764     .05       0  5006.1     .04       0  5012.1     .05       0
  5173.9     .16       0  5261.5     .05       0
Bank Sta=5002.4,5016.6
XS Rating Curve= 0 ,0
Exp/Cntr=0.3,0.1

Type RM Length L Ch R = 1 ,24974   ,149,149,149
BEGIN DESCRIPTION:
GUM CREEK 51.0
END DESCRIPTION:
XS GIS Cut Line= 3
      3745139.14     10615766.35      3745479.86     10616072.36
      3746044.11     10617148.77
#Sta/Elev= 30
  4647.9  370.07  4720.3  368.44  4751.2  364.38  4785.3  362.22  4792.7  358.43
  4835.4  352.97  4972.4  344.23  4984.1  344.19    5002  339.35  5004.8  338.85
    5008  339.35  5019.2   344.1    5076  346.64  5134.6  341.95  5156.7  344.99
  5171.2  342.28  5206.5   343.6  5216.3  346.11  5250.6  343.94  5333.2  347.29
  5355.2  345.14  5526.1  355.35  5608.7  349.63    5719  352.99  5829.3   351.1
  5845.7  353.65  6004.8   354.2  6172.8  358.63  6313.6   365.3  6321.2  365.33
#Mann= 9 ,-1 , 0
  4647.9     .05       0  4720.3     .08       0  4751.2     .12       0
  4972.4     .05       0    5002     .04       0    5008     .05       0
  6004.8     .16       0  6172.8     .05       0  6313.6     .16       0
Bank Sta=4984.1,5019.2
XS Rating Curve= 0 ,0
Exp/Cntr=0.3,0.1

Type RM Length L Ch R = 1 ,24825   ,353,353,353
BEGIN DESCRIPTION:
Mapping XS 7fadc2d1
END DESCRIPTION:
XS GIS Cut Line= 3
      3745108.74     10615905.23       3745462.5     10616189.54
      3745992.01     10617163.92
#Sta/Elev= 30
    4629  372.78  4655.2  371.19  4719.1  365.35  4818.3  350.22  4853.5  347.02
  4882.3  345.36  4931.9  344.86  4960.7  346.42  4981.5  344.93  4999.3  338.58
  5002.1  338.08  5005.3  338.58  5010.3  345.67  5016.7  346.17  5038.8  346.29
  5074.3  344.42    5151  344.72  5235.5  346.16  5317.3  345.05  5366.2  347.18
  5404.7  348.78  5595.7  349.62  5753.4  355.61  5833.4  356.36  5928.2  357.57
  5966.2  360.29  5988.1  359.63  6026.1  362.45  6164.2  366.39  6191.8  366.44
#Mann= 9 ,-1 , 0
    4629     .05       0  4655.2     .12       0  4999.3     .07       0
  5005.3     .12       0  5038.8     .05       0    5151     .12       0
  5366.2     .05       0  5833.4     .16       0  6164.2     .05       0
Bank Sta=4981.5,5016.7
XS Rating Curve= 0 ,0
Exp/Cntr=0.3,0.1

Type RM Length L Ch R = 1 ,24472   ,461,461,461
BEGIN DESCRIPTION:
GUM CREEK 50.0
END DESCRIPTION:
XS GIS Cut Line= 3
      3744918.76     10616086.28      3745331.95      10616534.2
      3746033.21      10617315.3
#Sta/Elev= 30
  4627.6  375.14  4659.5  371.49  4673.7  367.82  4694.1  366.31  4715.7   360.8
  4747.2  355.79  4836.5  346.99  4914.1  343.65  4977.6  344.45    4985  342.41
  4991.8  341.41  4996.2  338.08  4998.9  337.58  5002.2  338.08    5006  338.13
  5013.4   342.5  5020.2  338.55  5027.5  345.07  5030.4  345.41  5147.8  343.62
  5268.1   344.3  5317.4  346.16  5480.3  357.47  5629.1  358.25  5671.7  359.31
  5678.4  360.97  5701.9  360.58  5919.1  364.99  6045.1  365.93  6286.7  371.23
#Mann= 7 ,-1 , 0
  4627.6     .05       0  4747.2     .12       0  4996.2     .07       0
  5002.2     .12       0  5030.4     .05       0  5701.9     .16       0
  6045.1     .05       0
Bank Sta=4985,5013.4
XS Rating Curve= 0 ,0
Exp/Cntr=0.3,0.1

Type RM Length L Ch R = 1 ,24011   ,462,462,462
BEGIN DESCRIPTION:
GUM CREEK 49.0
END DESCRIPTION:
XS GIS Cut Line= 4
      3744739.91     10616333.23      3744963.89     10616621.46
      3745500.35     10616779.44      3746031.58     10617394.01
#Sta/Elev= 30
  4680.4  365.89  4777.9  362.14  4913.1  347.46  4942.5  345.34  4955.2  341.98
  4963.3  341.27  4969.6  342.65  4984.1  342.97  4995.6  338.97  4998.3  338.47
  5001.6  338.97  5005.8  339.09  5013.1  343.59  5041.4  342.35  5113.9  343.43
  5169.8  342.59  5306.6  343.58  5445.2  351.46    5583  356.83  5719.9  357.78
  5817.1  360.41  5895.8  360.79  5902.4  361.93  5959.4  360.75  5980.3  362.31
    6080  363.21  6114.1  365.52  6313.7  369.61  6334.6  371.45    6417  374.16
#Mann= 7 ,-1 , 0
  4680.4     .05       0  4913.1     .12       0  4995.6     .07       0
  5001.6     .12       0  5169.8     .05       0  5719.9     .16       0
  6114.1     .05       0
Bank Sta=4984.1,5013.1
XS Rating Curve= 0 ,0
Exp/Cntr=0.3,0.1

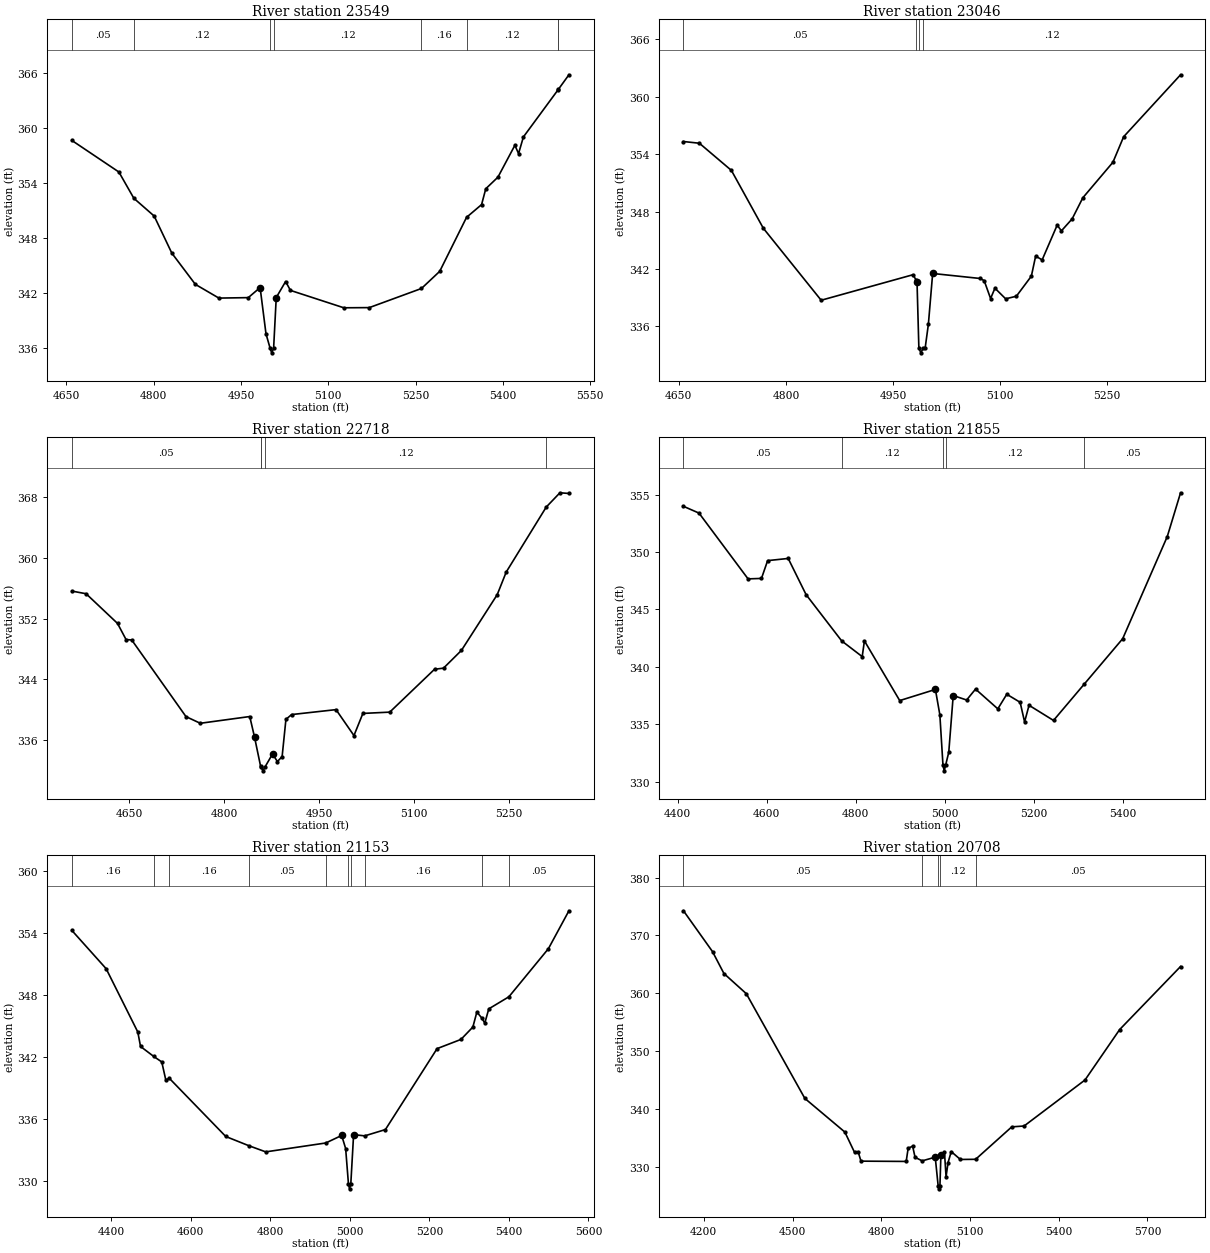
Type RM Length L Ch R = 1 ,23549   ,503,503,503
BEGIN DESCRIPTION:
GUM CREEK 48.0
END DESCRIPTION:
XS GIS Cut Line= 3
      3744599.61     10616560.19      3744649.61     10616910.19
      3744949.64     10617310.22
#Sta/Elev= 30
  4659.6  358.69  4740.4  355.24  4766.1  352.37    4801  350.43  4831.3  346.38
  4871.7  342.97  4912.1  341.47  4962.6  341.52  4982.9  342.62    4993  337.57
  5000.1  335.99  5002.8  335.49  5006.1  335.99  5010.6  341.53  5026.7  343.28
    5035  342.31  5126.7  340.41  5170.4  340.43    5260  342.52  5291.3  344.39
  5337.4  350.29  5363.2  351.68  5370.4  353.41  5391.3  354.68  5420.4  358.16
  5426.7  357.25    5435  359.07  5494.2  364.19  5495.1  364.27  5513.2  365.86
#Mann= 8 ,-1 , 0
  4659.6     .05       0  4766.1     .12       0  5000.1     .07       0
  5006.1     .12       0    5260     .16       0  5337.4     .12       0
  5494.2     .16       0  5495.1     .12       0
Bank Sta=4982.9,5010.6
XS Rating Curve= 0 ,0
Exp/Cntr=0.3,0.1

Type RM Length L Ch R = 1 ,23046   ,328,328,328
BEGIN DESCRIPTION:
GUM CREEK 47.0
END DESCRIPTION:
XS GIS Cut Line= 3
      3744099.62     10617060.19      3744399.61     10617210.19
      3744599.63     10617510.23
#Sta/Elev= 30
  4656.6  355.32  4678.9  355.14  4723.7   352.3  4768.4  346.25  4849.4  338.72
    4978  341.39  4982.4  340.82  4983.6  340.66  4986.2  333.72    4989  333.22
  4992.2  333.72    4995  333.72  4999.5   336.2  5005.5  341.52  5071.6     341
  5077.6  340.78  5086.6   338.9  5092.7  339.98  5107.7  338.87  5122.7  339.14
  5143.7  341.24  5149.7  343.34  5158.8  342.94  5179.8  346.57  5185.8  345.98
  5200.8  347.23  5215.8  349.44  5257.9  353.15  5272.9  355.82  5352.6   362.3
#Mann= 4 ,-1 , 0
  4656.6     .05       0  4982.4     .12       0  4986.2     .07       0
  4992.2     .12       0
Bank Sta=4983.6,5005.5
XS Rating Curve= 0 ,0
Exp/Cntr=0.3,0.1

Type RM Length L Ch R = 1 ,22718   ,863,863,863
BEGIN DESCRIPTION:
GUM CREEK 46.0
END DESCRIPTION:
XS GIS Cut Line= 3
      3744049.63     10617110.23      3744249.61     10617410.19
      3744549.63     10617710.21
#Sta/Elev= 30
  4559.5  355.63    4582  355.28  4631.6  351.37  4645.1  349.24  4654.1  349.18
  4739.7  339.08  4762.3   338.2  4840.4  339.09  4847.9  336.39  4857.5  332.54
  4858.4  332.43  4861.2  331.93  4864.4  332.43  4876.4  334.16    4884  333.15
  4891.5  333.81  4897.5  338.72  4906.5  339.35  4976.6     340  5004.9  336.58
    5019   339.5  5061.4  339.67  5132.1  345.32  5146.3  345.47  5174.6  347.81
  5231.1  355.16  5245.3  358.14  5308.5  366.71  5330.1  368.59  5344.3   368.5
#Mann= 5 ,-1 , 0
  4559.5     .05       0  4857.5     .12       0  4858.4     .07       0
  4864.4     .12       0  5308.5     .05       0
Bank Sta=4847.9,4876.4
XS Rating Curve= 0 ,0
Exp/Cntr=0.3,0.1

Type RM Length L Ch R = 1 ,21855   ,702,702,702
BEGIN DESCRIPTION:
GUM CREEK 45.0
END DESCRIPTION:
XS GIS Cut Line= 2
      3743845.84     10617145.33      3743897.93     10618259.91
#Sta/Elev= 30
  4413.2  353.97  4448.1  353.38  4558.2  347.65  4588.3  347.69  4602.1  349.24
  4648.3  349.43  4688.4  346.28  4768.3  342.25  4814.4  340.88  4819.4  342.25
  4898.6  337.05  4978.7  338.02  4988.7  335.81  4995.7  331.43  4998.5  330.93
  5001.7  331.43  5008.7  332.55  5018.7  337.49  5048.8   337.1  5068.8  338.05
  5118.8  336.33  5138.9   337.6  5168.9   336.9  5178.9  335.19  5188.9  336.64
  5243.8  335.32  5312.7  338.48  5399.1  342.44  5499.2  351.34    5529  355.15
#Mann= 5 ,-1 , 0
  4413.2     .05       0  4768.3     .12       0  4995.7     .07       0
  5001.7     .12       0  5312.7     .05       0
Bank Sta=4978.7,5018.7
XS Rating Curve= 0 ,0
Exp/Cntr=0.3,0.1

Type RM Length L Ch R = 1 ,21153   ,445,445,445
BEGIN DESCRIPTION:
GUM CREEK 44.0
END DESCRIPTION:
XS GIS Cut Line= 3
      3743453.48      10616895.3      3743384.04      10617534.2
      3743384.04     10618141.83
#Sta/Elev= 30
  4300.6  354.24  4386.9  350.53  4466.5   344.4  4473.4     343  4506.7  342.03
  4526.8   341.5  4536.9  339.76  4546.2   339.9  4687.8  334.28  4745.6  333.39
  4788.3  332.79  4939.2  333.65  4979.3  334.38  4989.3  333.11  4996.3  329.71
    4999  329.21  5002.3  329.71  5009.3  334.46  5037.2  334.34  5089.3  334.95
  5219.3  342.79  5279.3  343.68  5309.3  344.88  5319.3  346.33  5331.4  345.77
  5339.3  345.26  5349.3  346.64  5399.9  347.81  5499.3  352.47  5550.9  356.14
#Mann= 10 ,-1 , 0
  4300.6     .16       0  4506.7     .05       0  4546.2     .16       0
  4745.6     .05       0  4939.2     .12       0  4996.3     .07       0
  5002.3     .12       0  5037.2     .16       0  5331.4     .12       0
  5399.9     .05       0
Bank Sta=4979.3,5009.3
XS Rating Curve= 0 ,0
Exp/Cntr=0.3,0.1

Type RM Length L Ch R = 1 ,20708   ,508,508,508
BEGIN DESCRIPTION:
GUM CREEK 43.0
END DESCRIPTION:
XS GIS Cut Line= 3
       3742649.6     10616760.18      3742999.61     10617560.19
      3743299.61     10618310.19
#Sta/Elev= 30
  4131.2  374.26  4229.4   367.2    4268  363.41  4343.7  359.92  4541.7   341.8
    4677  335.98  4709.7  332.47  4721.8  332.59  4731.5  330.95  4884.4   330.9
    4891  333.18  4906.2  333.54  4914.4  331.61  4938.5     331  4982.6  331.64
  4992.5  326.66  4995.2  326.16  4998.5  326.66  5001.7  331.93  5013.8   332.5
  5019.2  328.26    5026  330.71  5036.7   332.6  5067.7  331.24  5119.2  331.27
  5241.4  336.88  5283.1  337.03  5489.1  344.99  5606.2  353.71  5812.2  364.62
#Mann= 5 ,-1 , 0
  4131.2     .05       0  4938.5     .12       0  4992.5     .07       0
  4998.5     .12       0  5119.2     .05       0
Bank Sta=4982.6,5001.7
XS Rating Curve= 0 ,0
Exp/Cntr=0.3,0.1