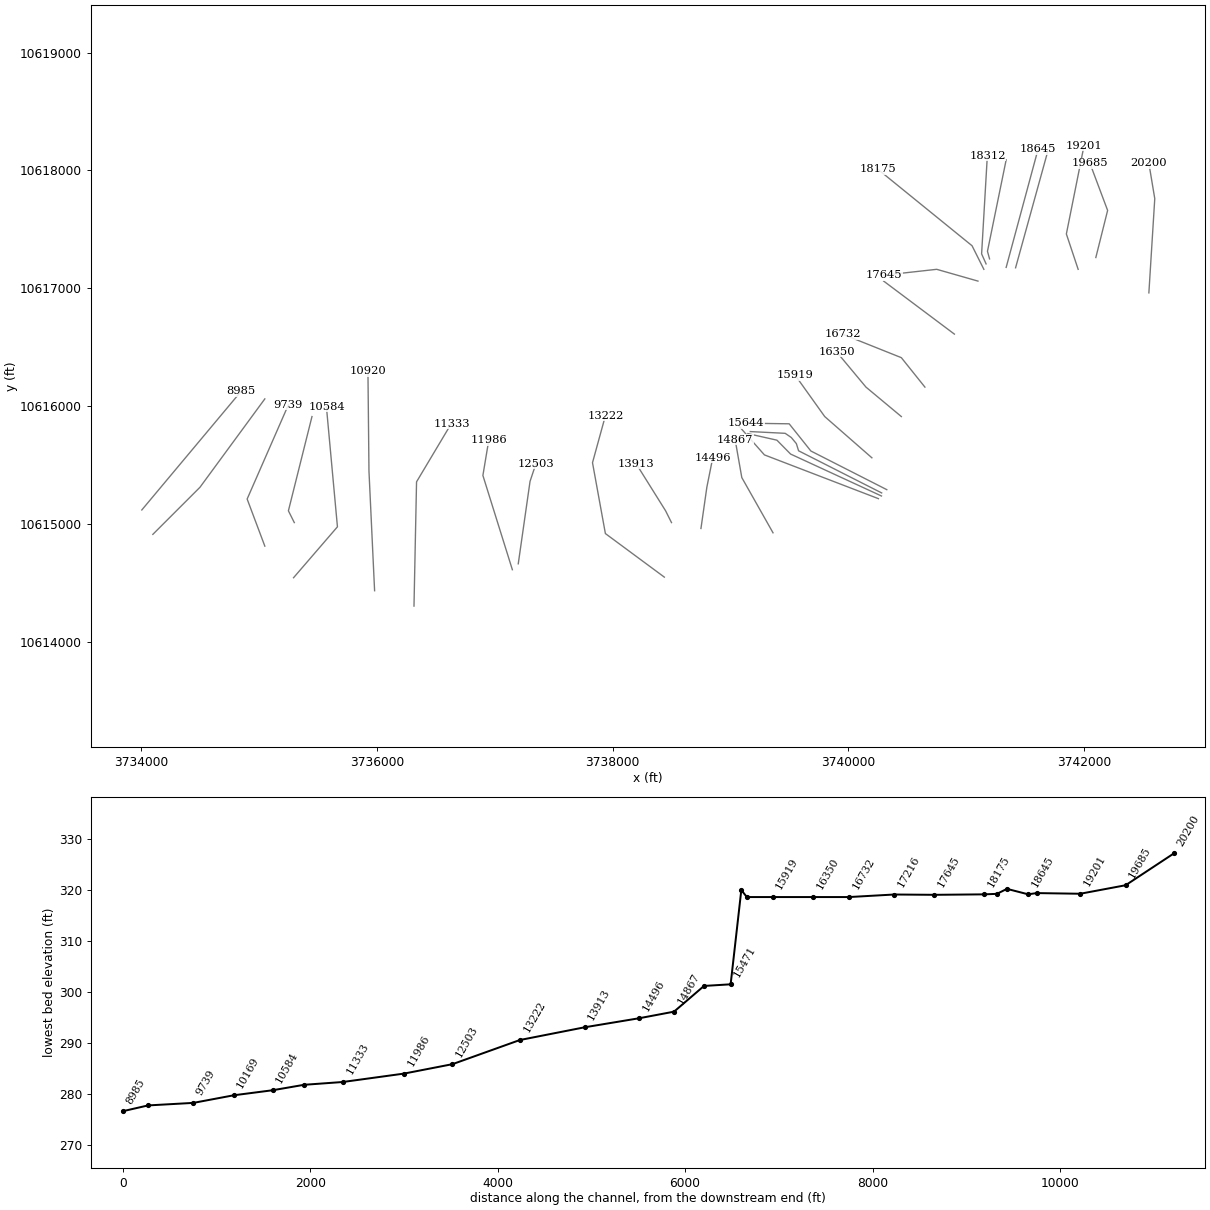
HEC-RAS study GUM CREEK.prj: GUM CREEK Base Level Engineering

--- GUM CREEK.g01 (geometry) --- (continued)

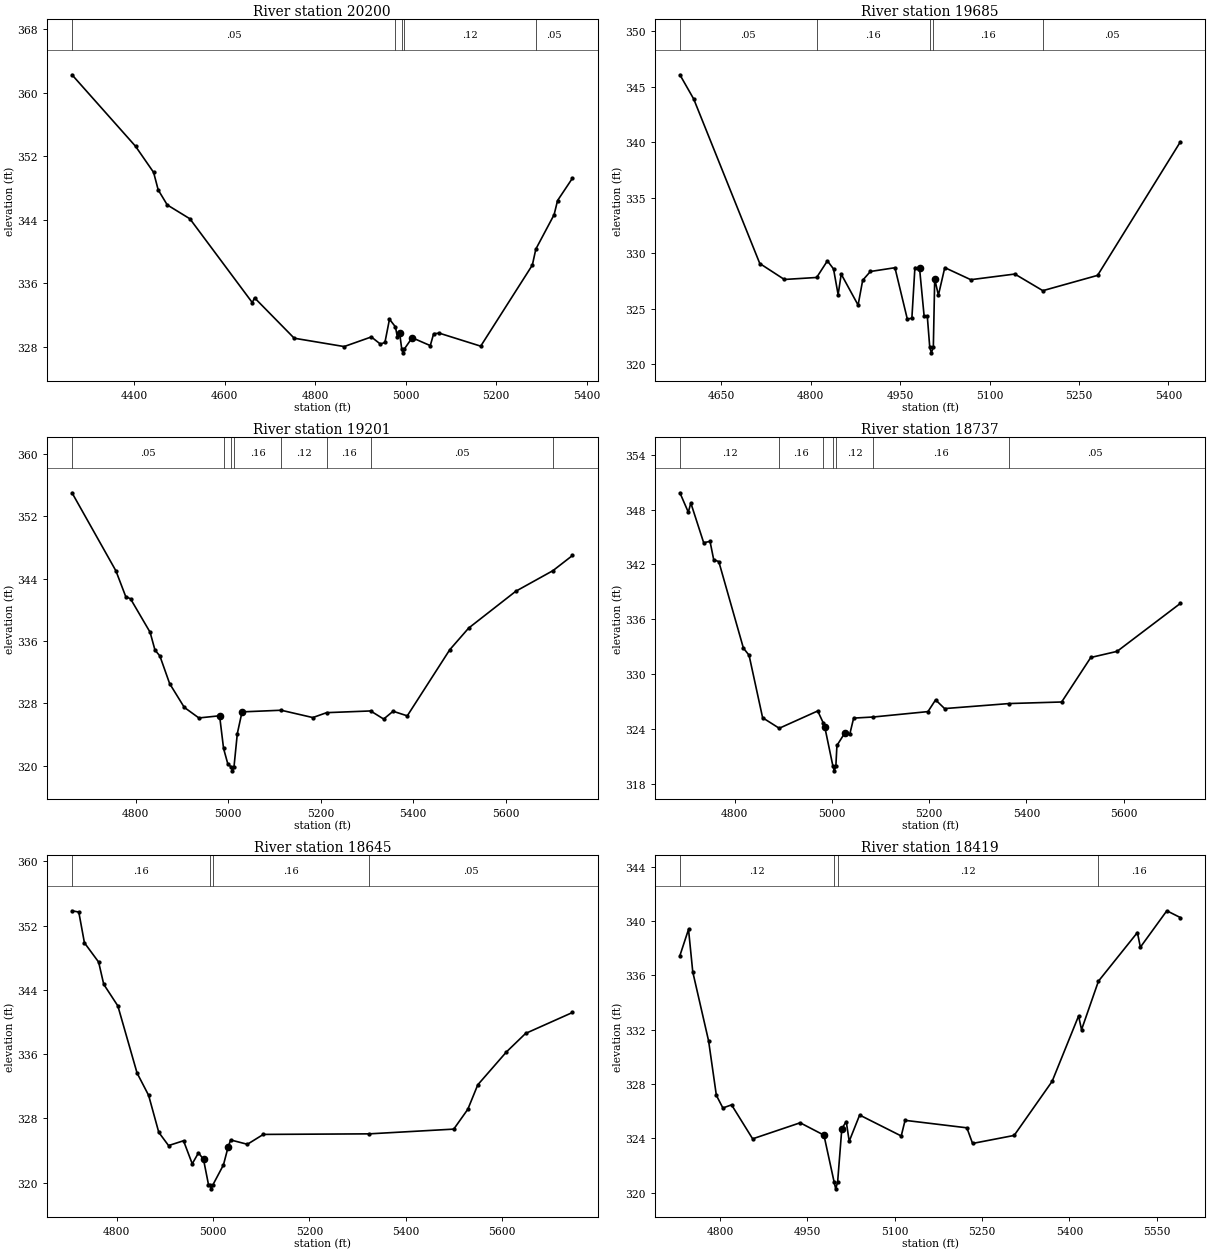
Type RM Length L Ch R = 1 ,20200   ,515,515,515
BEGIN DESCRIPTION:
GUM CREEK 42.0
END DESCRIPTION:
XS GIS Cut Line= 3
      3742549.61      10616960.2      3742599.61     10617760.19
      3742549.61      10618060.2
#Sta/Elev= 30
    4263  362.23  4403.3  353.24  4443.3  349.95  4453.4  347.75  4473.4  345.86
  4523.5  344.11  4661.3  333.57  4666.3  334.17  4753.9  329.09  4864.2  328.04
  4924.3  329.25  4944.3  328.35  4954.3  328.56  4964.4  331.48  4977.6  330.51
  4981.9   329.2  4986.9   329.7  4991.4  327.75  4994.2  327.25  4997.4  327.75
  5014.5  329.15  5054.5  328.16    5062  329.66  5074.7  329.72  5165.9  328.09
    5280  338.29  5287.7   340.3  5328.1  344.63  5335.7  346.41  5368.7  349.23
#Mann= 5 ,-1 , 0
    4263     .05       0  4977.6     .12       0  4991.4     .07       0
  4997.4     .12       0  5287.7     .05       0
Bank Sta=4986.9,5014.5
XS Rating Curve= 0 ,0
Exp/Cntr=0.3,0.1

Type RM Length L Ch R = 1 ,19685   ,484,484,484
BEGIN DESCRIPTION:
GUM CREEK 41.0
END DESCRIPTION:
XS GIS Cut Line= 3
      3742099.62     10617260.21      3742199.61     10617660.19
       3742049.6      10618060.2
#Sta/Elev= 30
  4580.5  346.09  4603.7   343.9  4714.5  329.06  4755.7  327.62  4809.9   327.8
  4827.9   329.3  4838.2  328.57  4845.9  326.25  4851.1   328.1  4879.4  325.31
  4887.1  327.55    4900  328.34  4941.2  328.68  4961.9  324.06  4969.6  324.12
  4974.7   328.7  4982.5  328.62  4990.2  324.29  4995.5  324.29  4999.6   321.5
  5002.3     321  5005.6   321.5  5007.9  327.67  5014.1   326.2  5024.8  328.69
  5068.4   327.6  5142.3  328.11  5189.3  326.61  5281.1  327.99    5420  340.04
#Mann= 5 ,-1 , 0
  4580.5     .05       0  4809.9     .16       0  4999.6     .07       0
  5005.6     .16       0  5189.3     .05       0
Bank Sta=4982.5,5007.9
XS Rating Curve= 0 ,0
Exp/Cntr=0.3,0.1

Type RM Length L Ch R = 1 ,19201   ,464,464,464
BEGIN DESCRIPTION:
GUM CREEK 40.0
END DESCRIPTION:
XS GIS Cut Line= 3
      3741949.62     10617160.16      3741849.61     10617460.19
      3741999.61     10618210.17
#Sta/Elev= 30
  4662.8  355.03  4757.7     345  4778.8  341.71  4789.3  341.41  4831.5  337.12
    4842  334.84  4852.6  334.08  4873.7  330.53  4905.3  327.48  4936.9  326.12
  4981.6   326.4  4990.2   322.2  4999.5  320.19  5006.7  319.83  5009.4  319.33
  5012.7  319.83  5019.9  324.12  5030.1   326.9  5114.6  327.11    5183  326.17
  5212.8   326.8  5307.8  327.02    5336  325.98  5356.4  326.98    5387  326.39
  5478.8  334.88  5519.6  337.66  5621.5  342.39  5701.6  345.03  5743.9  346.98
#Mann= 8 ,-1 , 0
  4662.8     .05       0  4990.2     .16       0  5006.7     .07       0
  5012.7     .16       0  5114.6     .12       0  5212.8     .16       0
  5307.8     .05       0  5701.6     .16       0
Bank Sta=4981.6,5030.1
XS Rating Curve= 0 ,0
Exp/Cntr=0.3,0.1

Type RM Length L Ch R = 1 ,18737   ,92,92,92
BEGIN DESCRIPTION:
Mapping XS f10b7d14
END DESCRIPTION:
XS GIS Cut Line= 2
      3741418.75     10617173.07      3741692.94      10618165.7
#Sta/Elev= 30
  4686.9  349.83  4704.2  347.71  4709.4  348.71  4735.8  344.38  4748.9  344.52
  4756.5  342.51  4766.9  342.32  4817.6  332.86  4829.2  332.09  4857.1  325.26
  4891.3  324.11  4970.5     326  4981.9  324.69  4984.8   324.3  5001.8  319.96
  5004.6  319.46  5007.8  319.96    5010  322.23  5026.3   323.6  5036.6   323.5
  5044.4  325.22  5084.7  325.34  5197.3  325.93    5213  327.21  5231.6  326.26
  5364.6  326.81  5472.4  326.98  5532.3  331.84  5586.5  332.51  5716.7  337.75
#Mann= 7 ,-1 , 0
  4686.9     .12       0  4891.3     .16       0  4981.9     .12       0
  5001.8     .07       0  5007.8     .12       0  5084.7     .16       0
  5364.6     .05       0
Bank Sta=4984.8,5026.3
XS Rating Curve= 0 ,0
Exp/Cntr=0.3,0.1

Type RM Length L Ch R = 1 ,18645   ,226,226,226
BEGIN DESCRIPTION:
GUM CREEK 39.0
END DESCRIPTION:
XS GIS Cut Line= 2
       3741338.9     10617176.57      3741609.74     10618180.06
#Sta/Elev= 30
  4707.1  353.86  4721.2   353.7  4732.9  349.87  4762.4  347.47    4773   344.7
  4802.3  342.01  4842.2  333.65  4866.2  330.87  4887.3  326.26  4907.6  324.61
  4938.7  325.21  4956.8  322.34  4969.8  323.71  4980.2  322.89  4990.5  319.76
  4993.7  319.72  4996.4  319.22  4999.7  319.72  5021.6   322.2  5031.4  324.45
  5036.6  325.31  5071.3  324.77  5104.4     326  5324.3  326.07  5499.9  326.66
  5529.1  329.13  5549.8  332.18  5609.2  336.27  5649.1  338.58  5746.5  341.19
#Mann= 4 ,-1 , 0
  4707.1     .16       0  4993.7     .07       0  4999.7     .16       0
  5324.3     .05       0
Bank Sta=4980.2,5031.4
XS Rating Curve= 0 ,0
Exp/Cntr=0.3,0.1

Type RM Length L Ch R = 1 ,18419   ,107,107,107
BEGIN DESCRIPTION:
Mapping XS 7209ee87
END DESCRIPTION:
XS GIS Cut Line= 3
      3741197.97     10617248.88       3741180.3     10617313.31
       3741338.9     10618089.77
#Sta/Elev= 30
  4731.3  337.45  4746.1  339.38  4753.4  336.25  4780.6  331.17  4793.9  327.17
  4805.1  326.24    4820  326.47  4856.2  323.97  4937.8  325.15  4978.6  324.24
  4996.1  320.79  4998.8  320.29  5002.1  320.79  5009.3  324.72  5016.9  325.24
    5022  323.79  5039.9  325.72  5111.3  324.18  5117.9  325.33    5224  324.78
  5233.8  323.63  5305.2  324.22  5370.4   328.2  5415.8  333.01  5420.9     332
  5449.9  335.57  5516.8  339.15  5521.9  338.07  5567.3  340.75  5590.6  340.25
#Mann= 4 ,-1 , 0
  4731.3     .12       0  4996.1     .07       0  5002.1     .12       0
  5449.9     .16       0
Bank Sta=4978.6,5009.3
XS Rating Curve= 0 ,0
Exp/Cntr=0.3,0.1

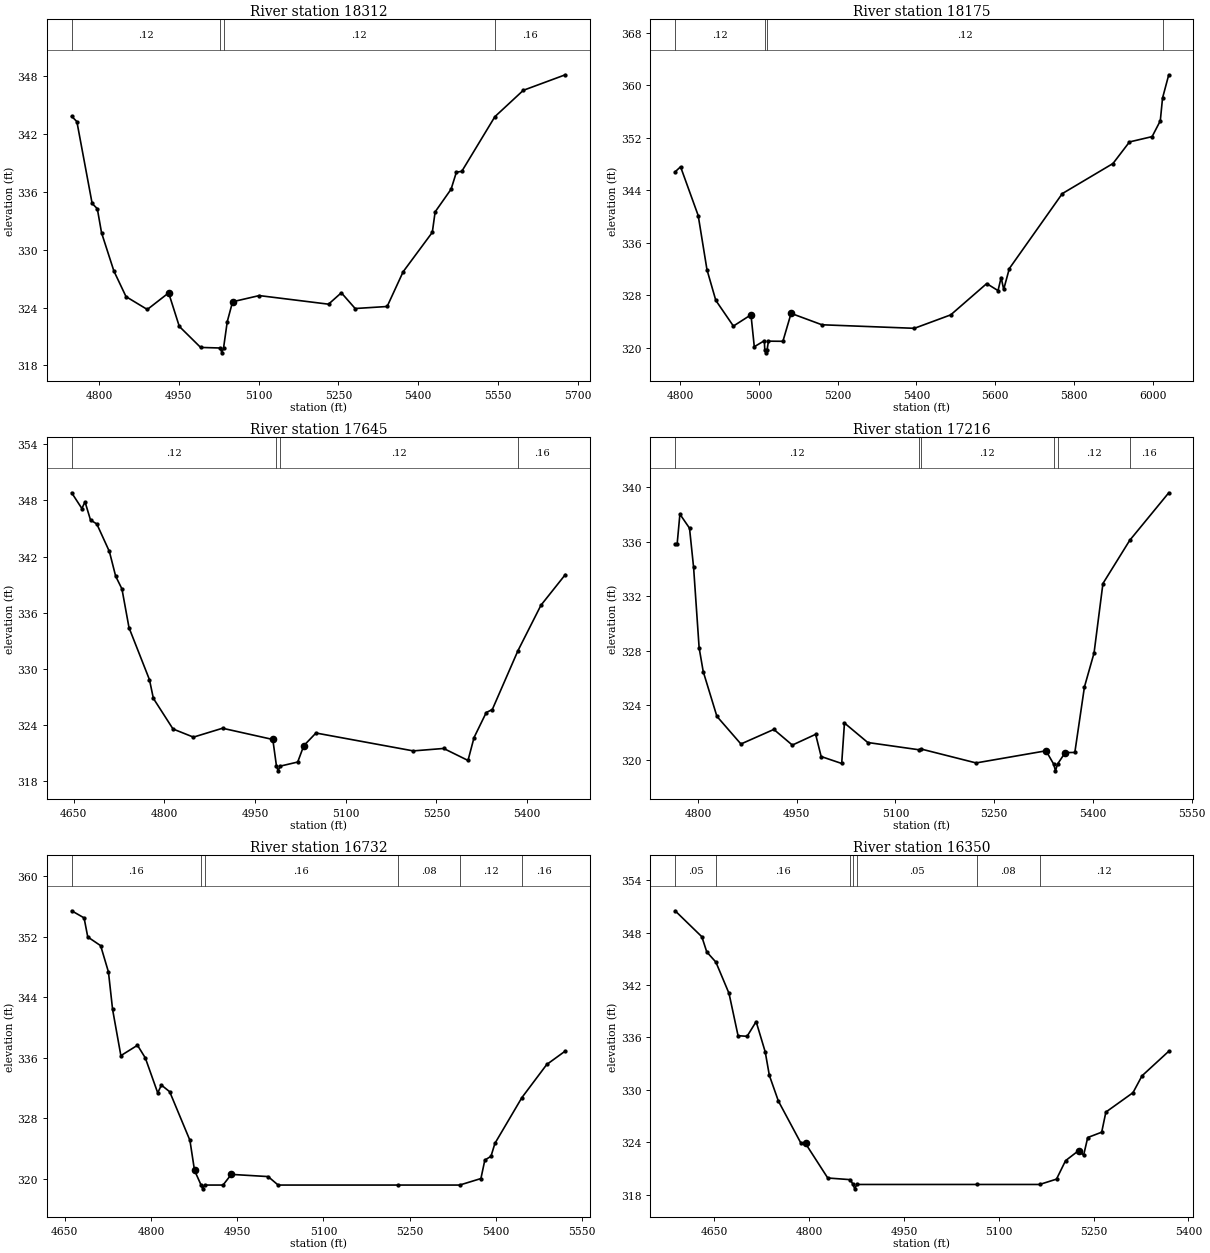
Type RM Length L Ch R = 1 ,18312   ,137,137,137
BEGIN DESCRIPTION:
Mapping XS 6bc3884b
END DESCRIPTION:
XS GIS Cut Line= 3
      3741168.55     10617206.14      3741130.56     10617291.14
      3741179.18     10618124.52
#Sta/Elev= 30
  4748.7  343.81  4758.5  343.26  4787.2  334.78  4796.9  334.24  4804.9  331.74
  4828.1  327.78  4850.9  325.13  4890.9   323.8    4931  325.52    4951  322.05
  4991.1  319.87  5028.2  319.81  5030.9  319.31  5034.2  319.81  5041.2  322.55
  5051.2   324.6  5101.3  325.24  5231.5  324.35  5255.6  325.53  5281.6   323.9
  5341.7  324.11  5371.8  327.71  5426.6  331.79  5431.9  333.91  5461.9  336.26
  5471.9  338.03  5481.9   338.1  5544.2  343.77  5597.6   346.5  5676.6  348.11
#Mann= 4 ,-1 , 0
  4748.7     .12       0  5028.2     .07       0  5034.2     .12       0
  5544.2     .16       0
Bank Sta=4931,5051.2
XS Rating Curve= 0 ,0
Exp/Cntr=0.3,0.1

Type RM Length L Ch R = 1 ,18175   ,530,530,530
BEGIN DESCRIPTION:
GUM CREEK 38.0
END DESCRIPTION:
XS GIS Cut Line= 3
      3741149.59     10617160.22      3741049.61     10617360.19
      3740249.65     10618010.16
#Sta/Elev= 30
  4786.7  346.81  4800.6  347.58  4845.4  340.14  4867.7  331.88  4890.1  327.21
  4934.8  323.29  4979.5  325.01  4987.9  320.14  5013.5  321.06  5014.5  319.71
  5017.2  319.21  5020.5  319.71  5023.9  320.99  5060.6  320.97  5081.4  325.23
  5159.7  323.49  5394.6  322.95    5487     325  5578.4  329.77  5607.2   328.7
  5615.1  330.69  5621.6  328.89  5635.9  332.06  5770.5  343.49  5899.3  348.08
  5941.2  351.37  5998.7  352.18  6019.5  354.59  6025.2  358.06    6041  361.61
#Mann= 4 ,-1 , 0
  4786.7     .12       0  5014.5     .07       0  5020.5     .12       0
  6025.2     .16       0
Bank Sta=4979.5,5081.4
XS Rating Curve= 0 ,0
Exp/Cntr=0.3,0.1

Type RM Length L Ch R = 1 ,17645   ,429,429,429
BEGIN DESCRIPTION:
GUM CREEK 37.0
END DESCRIPTION:
XS GIS Cut Line= 3
      3741099.59     10617060.19      3740749.61     10617160.19
      3740299.57     10617110.18
#Sta/Elev= 30
  4646.6  348.82  4663.5  347.14  4668.7  347.85  4677.8  345.91  4688.2  345.49
    4709  342.55  4719.4  339.91  4729.8  338.55  4741.5  334.41  4775.3  328.86
  4781.8  326.86  4814.3  323.59  4848.1  322.72  4896.2  323.67  4979.4  322.47
  4985.5  319.62  4988.2  319.12  4991.5  319.62  5020.6  320.06  5030.7  321.81
  5050.8  323.16  5211.8  321.25  5262.1  321.51  5302.4  320.23  5312.4  322.68
  5332.6  325.35  5342.6  325.67    5385  331.95  5423.1  336.81  5463.4  340.08
#Mann= 4 ,-1 , 0
  4646.6     .12       0  4985.5     .07       0  4991.5     .12       0
    5385     .16       0
Bank Sta=4979.4,5030.7
XS Rating Curve= 0 ,0
Exp/Cntr=0.3,0.1

Type RM Length L Ch R = 1 ,17216   ,484,484,484
BEGIN DESCRIPTION:
GUM CREEK 36.0
END DESCRIPTION:
XS GIS Cut Line= 3
      3740899.61     10616610.19      3740699.61     10616760.19
      3740299.61     10617060.19
#Sta/Elev= 30
  4765.2  335.83  4768.3  335.83  4772.5  338.02  4787.1  336.99  4793.3  334.11
  4801.7  328.21  4807.9  326.47  4828.7  323.18  4865.2  321.15  4915.2  322.22
  4943.3  321.07  4978.7  321.86  4987.1  320.23  5018.3  319.72  5022.5  322.69
  5057.9  321.26  5135.2  320.73    5139  320.78  5222.5  319.76  5328.7  320.65
  5340.3  319.68  5343.1  319.18  5346.3  319.68  5357.9  320.52  5372.5  320.53
  5387.1  325.34  5401.7  327.83  5415.2  332.93  5455.9   336.1  5515.2  339.59
#Mann= 6 ,-1 , 0
  4765.2     .12       0  5135.2     .08       0    5139     .12       0
  5340.3     .07       0  5346.3     .12       0  5455.9     .16       0
Bank Sta=5328.7,5357.9
XS Rating Curve= 0 ,0
Exp/Cntr=0.3,0.1

Type RM Length L Ch R = 1 ,16732   ,382,382,382
BEGIN DESCRIPTION:
GUM CREEK 35.0
END DESCRIPTION:
XS GIS Cut Line= 3
      3740649.61     10616160.19      3740449.61     10616410.19
      3739949.58      10616610.2
#Sta/Elev= 30
    4662  355.42  4683.6  354.48    4690  351.96  4712.4  350.81    4726  347.33
  4733.2  342.38  4747.6  336.28  4776.5  337.65  4790.1  335.98  4811.7  331.36
  4818.1  332.39  4832.5  331.51  4867.7  325.09  4875.7  321.12  4887.1  319.18
  4889.9  318.68  4893.1  319.18  4925.3  319.18  4939.7  320.59  5003.7   320.3
  5021.2  319.18  5228.8  319.18    5337  319.18  5373.9  320.04  5380.7  322.48
  5391.4  322.98  5398.2  324.68  5445.2  330.74  5488.4  335.11  5520.7  336.89
#Mann= 6 ,-1 , 0
    4662     .16       0  4887.1    .035       0  4893.1     .16       0
  5228.8     .08       0    5337     .12       0  5445.2     .16       0
Bank Sta=4875.7,4939.7
XS Rating Curve= 0 ,0
Exp/Cntr=0.3,0.1

Type RM Length L Ch R = 1 ,16350   ,431,431,431
BEGIN DESCRIPTION:
GUM CREEK 34.0
END DESCRIPTION:
XS GIS Cut Line= 3
      3740449.62     10615910.18      3740149.61     10616160.19
      3739899.63     10616460.16
#Sta/Elev= 30
  4587.9  350.49  4630.2  347.52    4638  345.78  4652.4  344.62  4673.2  341.04
  4687.5   336.2  4701.8  336.13  4716.1  337.81  4730.5  334.34    4737  331.66
  4751.3  328.72  4786.4  323.98  4794.2  323.87  4829.4  319.92  4865.2  319.73
  4869.3  319.18  4872.1  318.68  4875.3  319.18  5064.8  319.18  5164.6  319.18
  5191.3  319.79  5205.6   321.9  5226.4  323.06  5234.2  322.53  5240.7  324.55
  5262.8  325.16  5269.4  327.46  5312.3  329.68  5326.6  331.61  5368.9  334.42
#Mann= 7 ,-1 , 0
  4587.9     .05       0  4652.4     .16       0  4865.2     .05       0
  4869.3    .035       0  4875.3     .05       0  5064.8     .08       0
  5164.6     .12       0
Bank Sta=4794.2,5226.4
XS Rating Curve= 0 ,0
Exp/Cntr=0.3,0.1

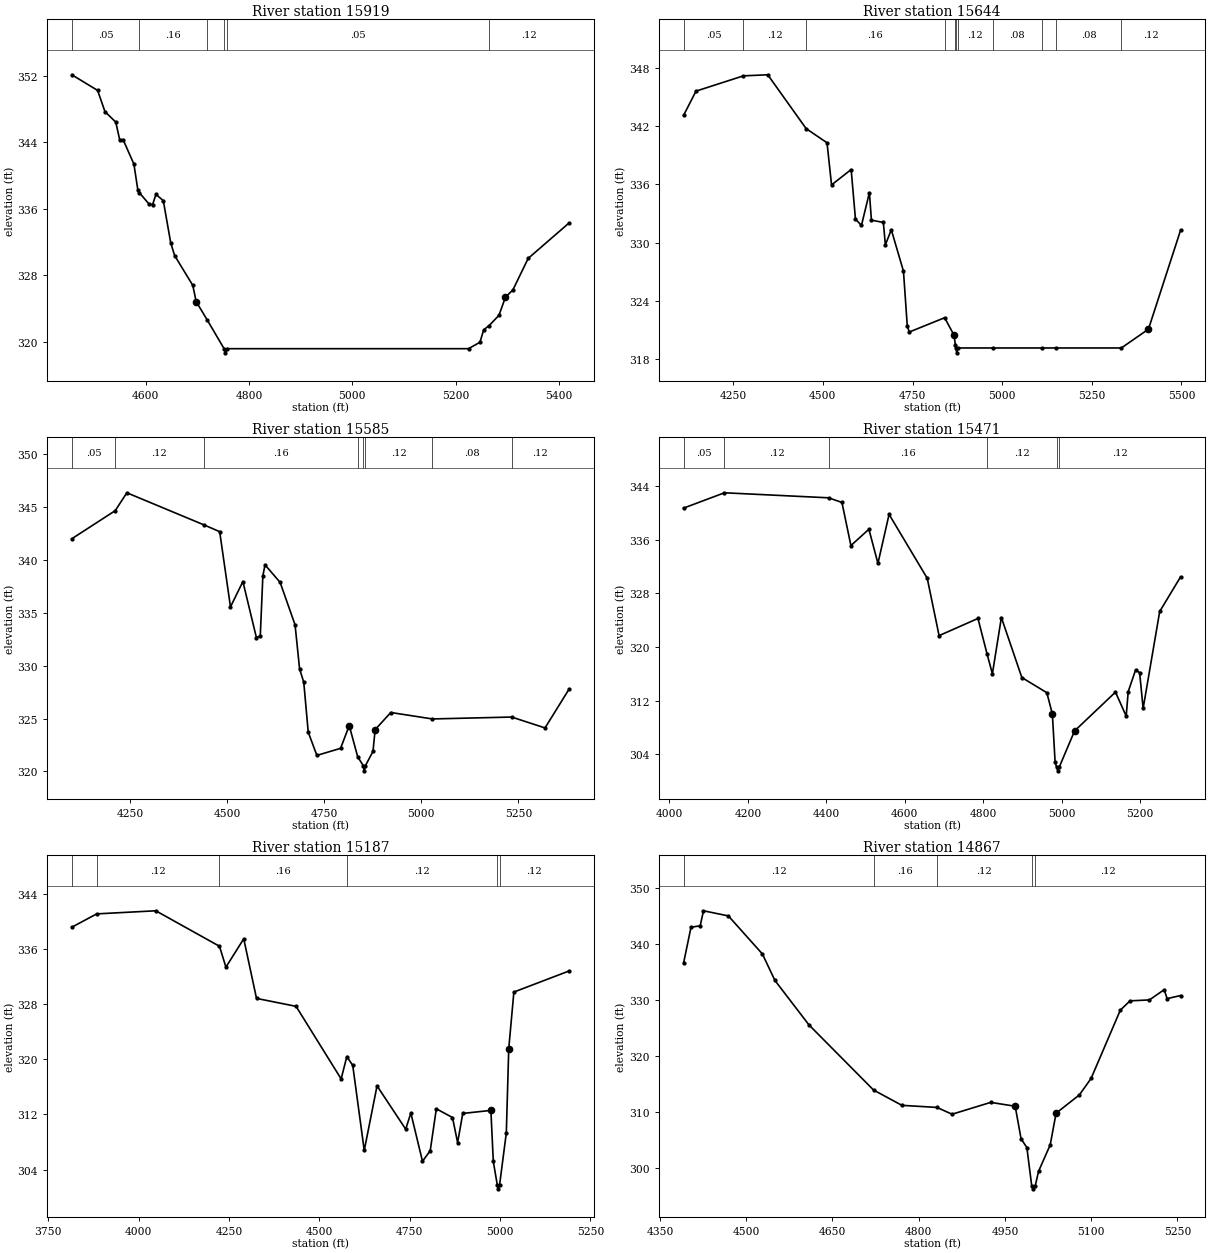
Type RM Length L Ch R = 1 ,15919   ,275,275,275
BEGIN DESCRIPTION:
GUM CREEK 33.0
END DESCRIPTION:
XS GIS Cut Line= 3
      3740199.63     10615560.17      3739799.61     10615910.19
      3739549.58     10616260.22
#Sta/Elev= 30
  4457.4  352.12  4507.3  350.24  4521.5  347.69  4542.4  346.43    4550  344.31
  4556.6  344.32  4577.5  341.38  4585.1  338.28  4588.3  337.92    4606  336.63
  4613.6   336.5  4620.2  337.73  4634.4  336.98  4648.7  331.92  4656.3  330.38
  4691.4   326.8    4698  324.84  4719.3  322.64    4752  319.18  4754.7  318.68
    4758  319.18  5224.9  319.18    5247  319.95  5254.4  321.46  5264.7  321.95
  5283.9   323.2  5296.2  325.35  5310.9  326.26  5340.4  330.04  5419.1  334.28
#Mann= 6 ,-1 , 0
  4457.4     .05       0  4588.3     .16       0  4719.3     .05       0
    4752    .033       0    4758     .05       0  5264.7     .12       0
Bank Sta=4698,5296.2
XS Rating Curve= 0 ,0
Exp/Cntr=0.3,0.1

Type RM Length L Ch R = 1 ,15644   ,59,59,59
BEGIN DESCRIPTION:
Mapping XS a44aaa99
END DESCRIPTION:
XS GIS Cut Line= 4
      3740326.16     10615289.69      3739682.07     10615617.82
      3739498.04     10615848.72        3739130.     10615853.93
#Sta/Elev= 30
  4111.4  343.08  4146.2  345.58  4278.4  347.15  4346.3  347.26  4453.3  341.73
  4511.6  340.27  4524.2  335.94  4578.9  337.52  4590.9  332.43  4607.6  331.77
  4629.8  335.15  4635.4  332.32  4668.7  332.08  4674.3  329.78  4690.9  331.33
  4724.8  327.07  4735.4  321.46    4741  320.82  4839.7  322.29  4865.8  320.49
  4869.6  319.49  4870.8  319.18  4873.5  318.68  4876.8  319.18  4973.3  319.18
  5110.4  319.18  5151.2  319.18  5332.5  319.18    5408  321.11  5497.6  331.28
#Mann= 11 ,-1 , 0
  4111.4     .05       0  4278.4     .12       0  4453.3     .16       0
  4839.7     .08       0  4869.6     .12       0  4870.8     .07       0
  4876.8     .12       0  4973.3     .08       0  5110.4     .05       0
  5151.2     .08       0  5332.5     .12       0
Bank Sta=4865.8,5408
XS Rating Curve= 0 ,0
Exp/Cntr=0.3,0.1

Type RM Length L Ch R = 1 ,15585   ,114,114,114
BEGIN DESCRIPTION:
Mapping XS ea0bc821
END DESCRIPTION:
XS GIS Cut Line= 6
      3740282.75     10615261.92       3739577.9     10615619.55
      3739558.95     10615680.56      3739516.06     10615732.35
      3739464.11     10615767.95      3739168.16     10615782.75
#Sta/Elev= 30
  4099.1  342.02    4211  344.68  4240.9  346.37  4438.5  343.35  4480.2  342.69
    4508  335.57    4540  337.97  4574.8  332.67  4584.8  332.81  4591.5  338.53
  4597.1  339.55    4636  337.89  4674.5  333.87  4686.1  329.71  4696.9  328.44
  4708.4  323.72  4730.7  321.52  4791.8  322.19  4814.1  324.34  4835.8   321.4
    4850  320.56  4852.8  320.06    4856  320.56  4875.3   321.9  4880.9  323.96
  4921.2  325.58  5028.4  324.97  5232.8  325.15  5318.7  324.12  5380.2  327.76
#Mann= 8 ,-1 , 0
  4099.1     .05       0    4211     .12       0  4438.5     .16       0
  4835.8     .12       0    4850     .07       0    4856     .12       0
  5028.4     .08       0  5232.8     .12       0
Bank Sta=4814.1,4880.9
XS Rating Curve= 0 ,0
Exp/Cntr=0.3,0.1

Type RM Length L Ch R = 1 ,15471   ,284,284,284
BEGIN DESCRIPTION:
Mapping XS 1583e23f
END DESCRIPTION:
XS GIS Cut Line= 4
      3740281.06     10615235.86      3739510.19     10615591.78
      3739393.87     10615709.83      3739147.75      10615765.3
#Sta/Elev= 30
  4035.9  340.72  4140.2  343.01  4405.6  342.26  4439.7  341.57  4462.6  335.14
  4508.5  337.57  4531.5  332.48  4559.9  339.79  4657.2  330.26  4687.4  321.71
  4786.5  324.27  4809.7  318.98  4823.3  316.02  4846.2  324.41  4898.4  315.46
  4962.1   313.2  4976.2  310.02  4983.2  302.81  4987.3  302.05  4990.1  301.55
  4993.3  302.05  5032.8   307.5  5137.1  313.29  5164.4  309.71  5169.5  313.36
  5188.3  316.58  5198.6   316.2  5207.6  310.86  5249.8  325.31    5303  330.47
#Mann= 6 ,-1 , 0
  4035.9     .05       0  4140.2     .12       0  4405.6     .16       0
  4809.7     .12       0  4987.3     .07       0  4993.3     .12       0
Bank Sta=4976.2,5032.8
XS Rating Curve= 0 ,0
Exp/Cntr=0.3,0.1

Type RM Length L Ch R = 1 ,15187   ,320,320,320
BEGIN DESCRIPTION:
GUM CREEK 32.0
END DESCRIPTION:
XS GIS Cut Line= 3
      3740254.95     10615213.32      3739287.97     10615584.83
      3739063.45     10615838.71
#Sta/Elev= 30
  3815.4  339.12  3884.1  341.05  4047.6   341.5  4223.8  336.36  4241.6  333.34
  4290.9  337.44  4326.2  328.81  4435.6  327.66  4560.3  317.15    4576  320.38
  4592.4  319.11  4624.2  306.79  4659.6  316.14  4738.9  309.87  4753.1  312.21
  4785.3  305.22  4806.7  306.75  4823.6  312.82  4868.3  311.56  4882.5  307.93
  4896.7  312.15  4974.5  312.59  4981.2  305.19  4992.4  301.73  4995.2  301.23
  4998.4  301.73  5017.2  309.34  5023.9  321.54  5038.1  329.73  5190.2  332.77
#Mann= 6 ,-1 , 0
  3815.4     .05       0  3884.1     .12       0  4223.8     .16       0
    4576     .12       0  4992.4     .07       0  4998.4     .12       0
Bank Sta=4974.5,5023.9
XS Rating Curve= 0 ,0
Exp/Cntr=0.3,0.1

Type RM Length L Ch R = 1 ,14867   ,371,371,371
BEGIN DESCRIPTION:
GUM CREEK 31.0
END DESCRIPTION:
XS GIS Cut Line= 3
      3739360.87     10614923.55      3739096.13     10615392.27
      3739039.71     10615713.44
#Sta/Elev= 30
  4391.1  336.57  4404.1  343.02  4420.1  343.28  4425.8  345.97  4469.1  345.05
  4528.3  338.23    4550   333.5  4609.2  325.54  4721.6  313.87  4770.9  311.13
  4831.8  310.76  4858.1  309.54  4925.3  311.66  4967.9  310.97  4978.1  305.15
  4988.2  303.57  4996.7  296.68  4999.5  296.18  5002.7  296.68  5008.5  299.31
  5028.8  304.05    5039  309.72  5079.6  313.01  5099.9  315.95  5150.7  328.17
  5167.6  329.84  5201.4  330.01    5227  331.84  5232.1  330.24  5255.5  330.79
#Mann= 5 ,-1 , 0
  4391.1     .12       0  4721.6     .16       0  4831.8     .12       0
  4996.7     .07       0  5002.7     .12       0
Bank Sta=4967.9,5039
XS Rating Curve= 0 ,0
Exp/Cntr=0.3,0.1

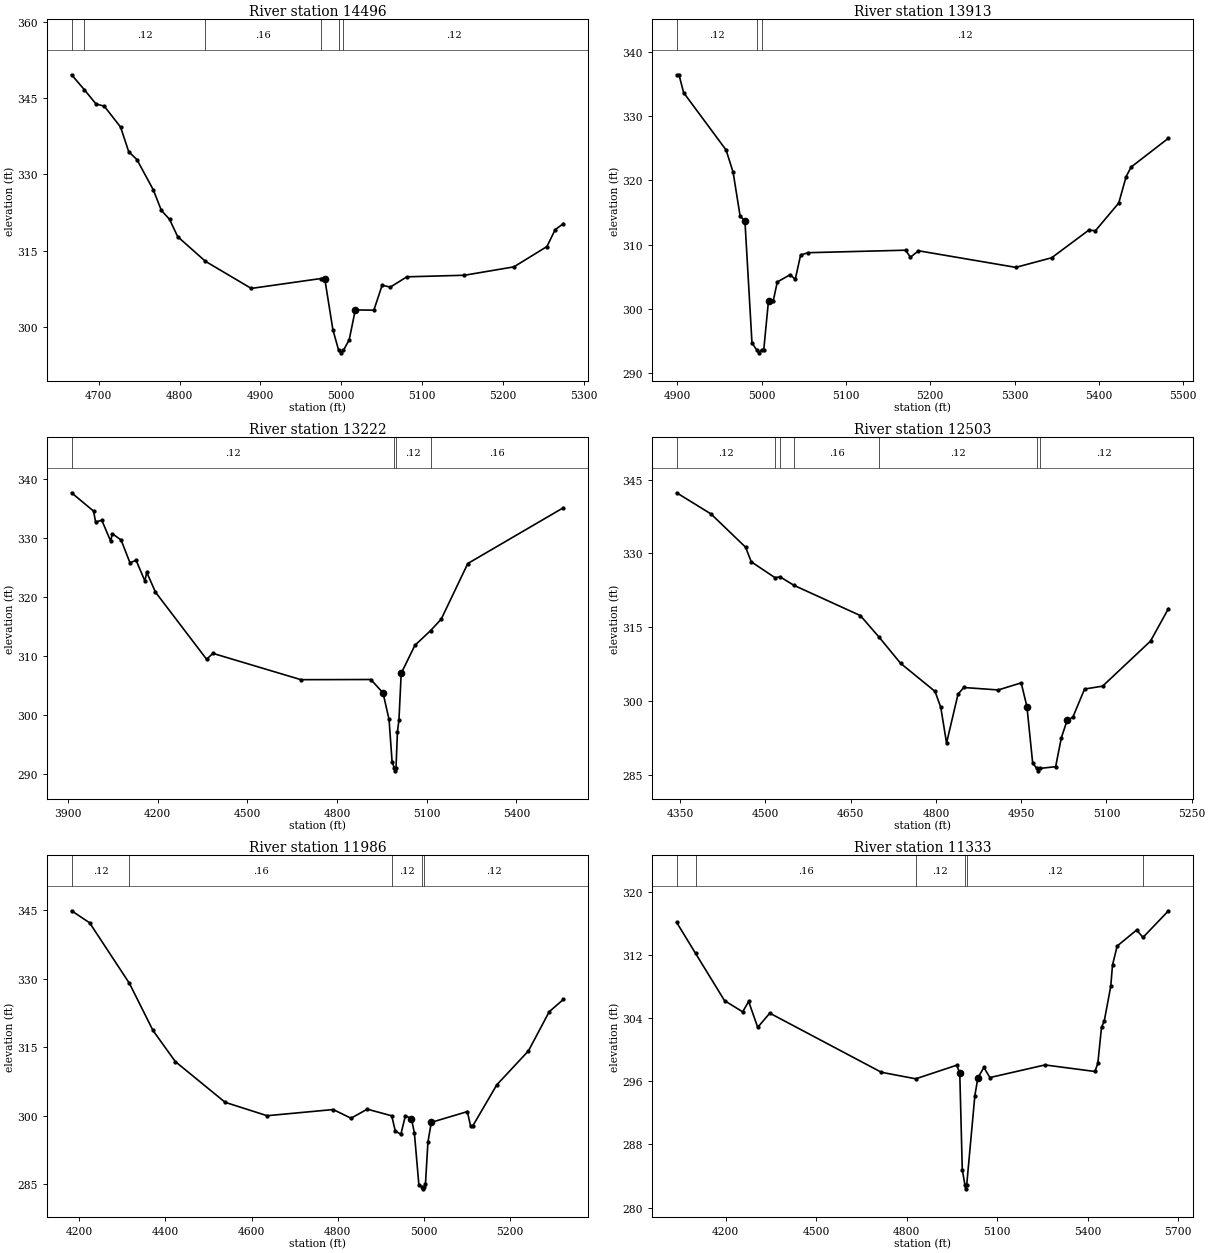
Type RM Length L Ch R = 1 ,14496   ,583,583,583
BEGIN DESCRIPTION:
GUM CREEK 30.0
END DESCRIPTION:
XS GIS Cut Line= 3
      3738749.61     10614960.17      3738799.61     10615310.19
       3738849.6     10615560.16
#Sta/Elev= 30
  4666.3  349.54  4682.1  346.61  4696.6  343.79  4706.7  343.38  4726.9  339.27
    4737  334.42  4747.1  332.88  4767.3  326.96  4777.4  322.88  4787.5  321.13
  4797.6  317.72  4831.8  312.89  4888.6  307.55    4975   309.5  4979.5  309.49
  4989.6  299.44  4996.7  295.39  4999.4  294.89  5002.7  295.39  5009.8  297.46
  5017.3  303.32  5040.3  303.28  5050.5  308.17  5060.7  307.81  5081.1  309.83
  5152.4  310.14  5213.6  311.79  5254.4  315.78  5264.6   319.1  5274.8  320.29
#Mann= 6 ,-1 , 0
  4666.3     .16       0  4682.1     .12       0  4831.8     .16       0
    4975     .12       0  4996.7     .07       0  5002.7     .12       0
Bank Sta=4979.5,5017.3
XS Rating Curve= 0 ,0
Exp/Cntr=0.3,0.1

Type RM Length L Ch R = 1 ,13913   ,691,691,691
BEGIN DESCRIPTION:
GUM CREEK 29.0
END DESCRIPTION:
XS GIS Cut Line= 3
      3738499.59     10615010.22      3738449.61     10615110.19
      3738199.59     10615510.22
#Sta/Elev= 30
  4899.1  336.48  4901.9  336.48  4907.4  333.69  4957.8  324.74  4966.1  321.28
  4974.5  314.38  4980.1  313.75  4988.5  294.65  4993.9  293.61  4996.6  293.11
  4999.9  293.61  5002.5  293.63  5008.1  301.26  5013.8  301.26  5018.5  304.16
  5033.9  305.31  5039.8  304.56  5046.2  308.37  5055.1  308.73  5170.7  309.12
  5176.5  308.02    5186  309.03  5301.5  306.44    5344  307.94  5388.2  312.26
  5395.9  312.15  5423.6  316.48  5432.4  320.61  5438.3  322.09  5482.6  326.59
#Mann= 3 ,-1 , 0
  4899.1     .12       0  4993.9     .07       0  4999.9     .12       0
Bank Sta=4980.1,5008.1
XS Rating Curve= 0 ,0
Exp/Cntr=0.3,0.1

Type RM Length L Ch R = 1 ,13222   ,719,719,719
BEGIN DESCRIPTION:
GUM CREEK 27.0
END DESCRIPTION:
XS GIS Cut Line= 4
      3738438.88     10614547.19      3737938.86     10614916.99
      3737829.49     10615518.55      3737938.62     10615916.11
#Sta/Elev= 30
  3911.5  337.71  3985.2   334.6  3991.8  332.77  4012.7  333.05  4041.9  329.56
  4048.2  330.77  4077.4   329.7  4106.7  325.87  4127.5  326.26  4156.8  322.77
    4163  324.24  4192.2  320.88  4363.4   309.5  4384.2  310.51    4679  306.05
  4912.7  306.08  4953.5  303.82  4973.7  299.32  4983.9  292.15    4991  291.11
  4993.8  290.61    4997  291.11  5001.8  297.23  5006.8  299.21  5014.4  307.13
  5060.2  311.87  5112.4  314.35  5148.3  316.31  5237.2  325.73  5557.1  335.18
#Mann= 4 ,-1 , 0
  3911.5     .12       0    4991     .07       0    4997     .12       0
  5112.4     .16       0
Bank Sta=4953.5,5014.4
XS Rating Curve= 0 ,0
Exp/Cntr=0.3,0.1

Type RM Length L Ch R = 1 ,12503   ,517,517,517
BEGIN DESCRIPTION:
GUM CREEK 26.0
END DESCRIPTION:
XS GIS Cut Line= 3
      3737199.61      10614660.2      3737299.61     10615360.19
      3737349.61     10615510.18
#Sta/Elev= 30
  4343.9  342.32  4404.5  338.01  4465.1  331.28  4475.2  328.31    4517  325.08
  4525.8  325.26  4550.1  323.54  4667.1  317.39  4700.2  312.99  4737.8  307.71
  4798.5  301.99  4808.6  298.74  4818.7  291.51  4838.9  301.43    4849  302.79
  4909.6  302.29    4950  303.73  4960.1  298.91  4970.2  287.47  4977.3  286.37
    4980  285.87  4983.3  286.37  5010.6  286.71  5020.7  292.61  5030.8  296.11
  5040.9  296.76  5061.5  302.48  5093.2  303.06  5177.5  312.21  5209.1  318.82
#Mann= 7 ,-1 , 0
  4343.9     .12       0    4517     .16       0  4525.8     .12       0
  4550.1     .16       0  4700.2     .12       0  4977.3     .07       0
  4983.3     .12       0
Bank Sta=4960.1,5030.8
XS Rating Curve= 0 ,0
Exp/Cntr=0.3,0.1

Type RM Length L Ch R = 1 ,11986   ,653,653,653
BEGIN DESCRIPTION:
GUM CREEK 25.0
END DESCRIPTION:
XS GIS Cut Line= 3
       3737149.6     10614610.23      3736899.61     10615410.19
      3736949.62     10615710.24
#Sta/Elev= 30
    4182  344.86  4223.9  342.23  4316.4  328.97  4371.1  318.67  4422.9  311.87
  4538.7  302.95  4636.1  300.02  4789.6  301.37    4831  299.47  4868.7  301.45
  4925.6     300  4933.7  296.69  4946.8  295.95  4957.3  300.04  4971.4  299.36
  4978.2  296.23  4988.7  284.78  4995.6  284.52  4998.4  284.02  5001.6  284.52
  5003.9  285.06  5009.6  294.23  5017.5  298.57  5101.2  300.92  5108.8  297.71
  5113.9  297.81  5169.6  306.78  5243.1  314.21  5291.3  322.77  5324.3  325.47
#Mann= 5 ,-1 , 0
    4182     .12       0  4316.4     .16       0  4925.6     .12       0
  4995.6     .07       0  5001.6     .12       0
Bank Sta=4971.4,5017.5
XS Rating Curve= 0 ,0
Exp/Cntr=0.3,0.1

Type RM Length L Ch R = 1 ,11333   ,413,413,413
BEGIN DESCRIPTION:
Mapping XS c673b8bc
END DESCRIPTION:
XS GIS Cut Line= 3
      3736315.05     10614301.38      3736336.76     10615356.11
       3736631.9     10615850.92
#Sta/Elev= 30
  4037.1  316.18  4099.8  312.25  4195.9  306.25    4256  304.83    4276  306.14
    4306  302.86    4346  304.66  4716.1  297.16  4830.1  296.33  4966.1  298.06
  4976.1  297.03  4984.4  284.81  4993.1  282.87  4995.9  282.37  4999.1  282.87
  5026.1  294.19  5036.1  296.46  5056.1  297.77  5076.1  296.49  5258.8  298.09
  5424.2  297.26  5433.9  298.29  5446.1  302.85  5455.3  303.68  5476.8  308.07
  5482.6  310.78  5498.2  313.18  5562.6  315.21  5583.7  314.27  5668.2  317.65
#Mann= 6 ,-1 , 0
  4037.1     .12       0  4099.8     .16       0  4830.1     .12       0
  4993.1     .07       0  4999.1     .12       0  5583.7     .05       0
Bank Sta=4976.1,5036.1
XS Rating Curve= 0 ,0
Exp/Cntr=0.3,0.1

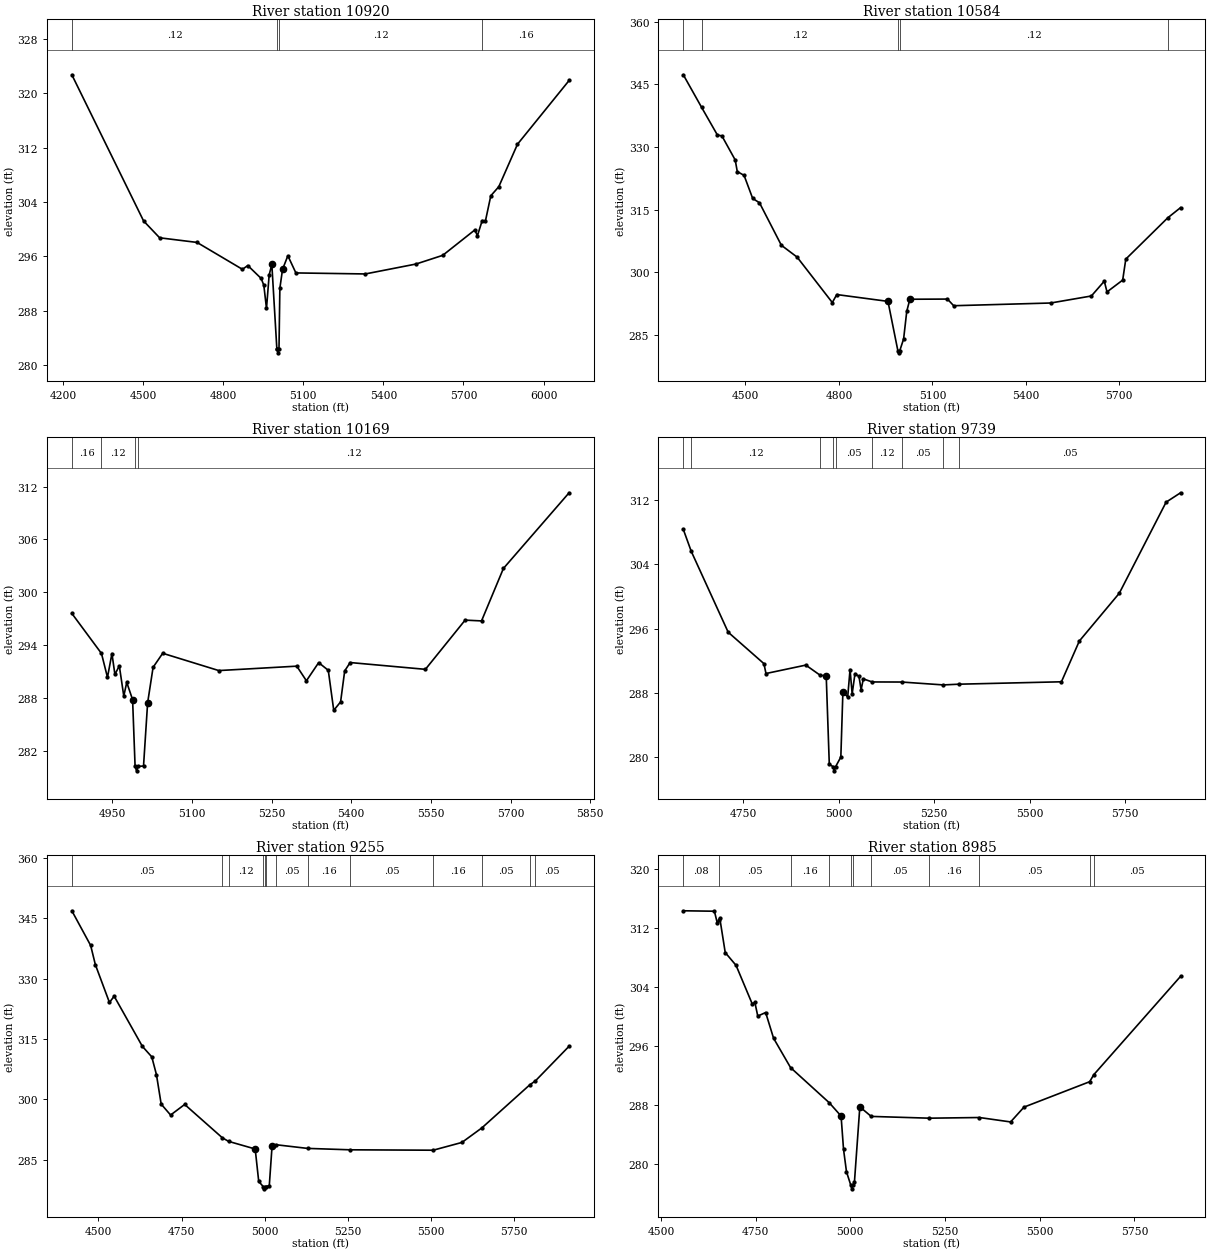
Type RM Length L Ch R = 1 ,10920   ,336,336,336
BEGIN DESCRIPTION:
Mapping XS c7e88aac
END DESCRIPTION:
XS GIS Cut Line= 3
      3735980.85     10614431.67      3735933.11     10615447.26
      3735924.43     10616293.61
#Sta/Elev= 30
  4232.8  322.74  4501.6  301.23  4561.7  298.75  4701.8  298.07    4872  294.11
    4892  294.67  4942.1  292.77  4952.1  291.77  4962.1  288.35  4972.1  293.28
  4982.1  294.84  5000.9  282.43  5002.9  282.32  5005.6  281.82  5008.9  282.32
  5012.2  291.33  5022.2   294.1  5042.2  296.11  5072.2  293.58  5332.4  293.43
  5522.4  294.89  5622.5  296.17  5742.5   299.9  5752.5  299.06  5770.2  301.28
  5782.5  301.24  5802.5  304.93  5832.5  306.27  5902.5  312.52  6095.9   321.9
#Mann= 4 ,-1 , 0
  4232.8     .12       0  5002.9     .07       0  5008.9     .12       0
  5770.2     .16       0
Bank Sta=4982.1,5022.2
XS Rating Curve= 0 ,0
Exp/Cntr=0.3,0.1

Type RM Length L Ch R = 1 ,10584   ,415,415,415
BEGIN DESCRIPTION:
GUM CREEK 22.0
END DESCRIPTION:
XS GIS Cut Line= 3
      3735293.23     10614542.04      3735665.64     10614974.35
       3735571.9     10615995.15
#Sta/Elev= 30
  4300.7  347.26  4359.2   339.5  4410.3  332.83  4424.5  332.65  4467.3  326.88
  4473.9  324.12  4495.8  323.19  4523.3  317.69  4545.2  316.64  4615.4  306.48
  4665.9  303.65  4778.9  292.78  4793.2  294.69  4957.5  293.06  4989.3  281.25
  4992.1  280.75  4995.3  281.25  5007.7  284.07  5017.8  290.69  5027.8  293.57
  5148.3  293.61  5168.4  292.02  5479.7  292.67  5610.2  294.35  5651.7  297.89
  5660.4  295.32  5710.7  298.15  5720.7  303.17  5855.4  313.05  5896.4  315.48
#Mann= 5 ,-1 , 0
  4300.7     .16       0  4359.2     .12       0  4989.3     .07       0
  4995.3     .12       0  5855.4     .16       0
Bank Sta=4957.5,5027.8
XS Rating Curve= 0 ,0
Exp/Cntr=0.3,0.1

Type RM Length L Ch R = 1 ,10169   ,430,430,430
BEGIN DESCRIPTION:
GUM CREEK 21.0
END DESCRIPTION:
XS GIS Cut Line= 3
      3735299.61     10615010.19      3735249.61     10615110.19
       3735449.6     10615910.17
#Sta/Elev= 30
  4873.9  297.61  4929.7  293.07    4941  290.36  4949.4  293.06    4955  290.69
  4963.3  291.67  4971.7  288.24  4977.3  289.79  4988.3  287.83    4993  280.26
  4995.8  279.76    4999  280.26  5008.9  280.31  5016.6  287.47  5026.9   291.5
    5045  293.09  5150.6  291.13  5297.5  291.63  5315.6  289.97  5338.7  292.03
  5356.8  291.16  5367.1  286.62    5380  287.58  5387.7  291.09    5398  292.04
  5539.7  291.27  5614.5  296.85  5645.4  296.76  5686.6  302.71  5810.3  311.29
#Mann= 4 ,-1 , 0
  4873.9     .16       0  4929.7     .12       0    4993     .07       0
    4999     .12       0
Bank Sta=4988.3,5016.6
XS Rating Curve= 0 ,0
Exp/Cntr=0.3,0.1

Type RM Length L Ch R = 1 ,9739    ,484,484,484
BEGIN DESCRIPTION:
GUM CREEK 20.0
END DESCRIPTION:
XS GIS Cut Line= 3
       3735049.6     10614810.22      3734899.61     10615210.19
      3735249.62     10616010.21
#Sta/Elev= 30
    4594  308.37  4614.8  305.63  4711.4  295.55  4804.9  291.63  4810.2   290.4
  4914.4  291.45  4951.2  290.21  4967.8  290.07  4975.8  279.11  4986.1  278.77
  4988.9  278.27  4992.1  278.77    5006  279.99  5011.4  288.15  5023.9  287.46
  5030.1   290.9  5035.6  287.86    5043  290.39  5053.5  290.03    5059  288.37
  5064.8  289.73    5088  289.35  5165.1  289.34    5274  288.98  5314.8  289.07
  5582.9  289.37  5629.7  294.45  5734.2  300.41  5856.6  311.76  5894.4  312.93
#Mann= 9 ,-1 , 0
    4594     .16       0  4614.8     .12       0  4951.2     .05       0
  4986.1     .04       0  4992.1     .05       0    5088     .12       0
  5165.1     .05       0    5274     .12       0  5314.8     .05       0
Bank Sta=4967.8,5011.4
XS Rating Curve= 0 ,0
Exp/Cntr=0.3,0.1

Type RM Length L Ch R = 1 ,9255    ,270,270,270
BEGIN DESCRIPTION:
GUM CREEK 19.0
END DESCRIPTION:
XS GIS Cut Line= 3
      3734099.62      10614910.2      3734499.61     10615310.19
      3735049.59     10616060.17
#Sta/Elev= 30
    4420  346.87  4476.6  338.25  4490.7  333.49  4533.1  324.08  4547.3  325.64
  4632.1  313.18  4660.4  310.57  4674.5  306.15  4688.7  298.83    4717  296.11
  4759.4  298.74  4872.5  290.47  4891.3  289.57  4971.5  287.67  4982.1  279.62
  4996.2  278.27    4999  277.77  5002.2  278.27  5003.8  278.32  5013.9  278.58
  5022.3  288.46  5033.2  288.74    5129  287.82  5257.4  287.47  5506.8  287.37
  5593.3   289.3  5653.4  292.92  5796.8  303.57  5814.5  304.61  5915.7  313.21
#Mann= 13 ,-1 , 0
    4420     .05       0  4872.5     .16       0  4891.3     .12       0
  4996.2     .07       0  5002.2     .12       0  5003.8     .16       0
  5033.2     .05       0    5129     .16       0  5257.4     .05       0
  5506.8     .16       0  5653.4     .05       0  5796.8     .08       0
  5814.5     .05       0
Bank Sta=4971.5,5022.3
XS Rating Curve= 0 ,0
Exp/Cntr=0.3,0.1

Type RM Length L Ch R = 1 ,8985    ,252,252,252
BEGIN DESCRIPTION:
Mapping XS 046f2111
END DESCRIPTION:
XS GIS Cut Line= 2
        3734006.     10615117.37      3734848.01     10616124.31
#Sta/Elev= 30
    4559  314.37  4641.1  314.31  4648.9  312.68  4652.6  313.06  4655.4  313.35
  4669.7   308.7  4698.3  306.96  4741.3  301.69  4747.8  301.96  4755.6  300.08
  4776.4  300.56  4797.3  297.07  4842.1  293.09  4944.4  288.31  4975.5  286.51
    4982  281.97  4989.8  278.95  5001.1  277.13  5003.9  276.63  5007.1  277.13
  5010.7   277.5    5025  287.76    5055  286.46  5208.6  286.22  5340.7  286.31
    5423  285.71  5458.3  287.72  5631.7  291.17  5642.5  292.12  5871.6  305.47
#Mann= 11 ,-1 , 0
    4559     .08       0  4652.6     .05       0  4842.1     .16       0
  4944.4     .12       0  5001.1     .07       0  5007.1     .12       0
    5055     .05       0  5208.6     .16       0  5340.7     .05       0
  5631.7     .16       0  5642.5     .05       0
Bank Sta=4975.5,5025
XS Rating Curve= 0 ,0
Exp/Cntr=0.3,0.1