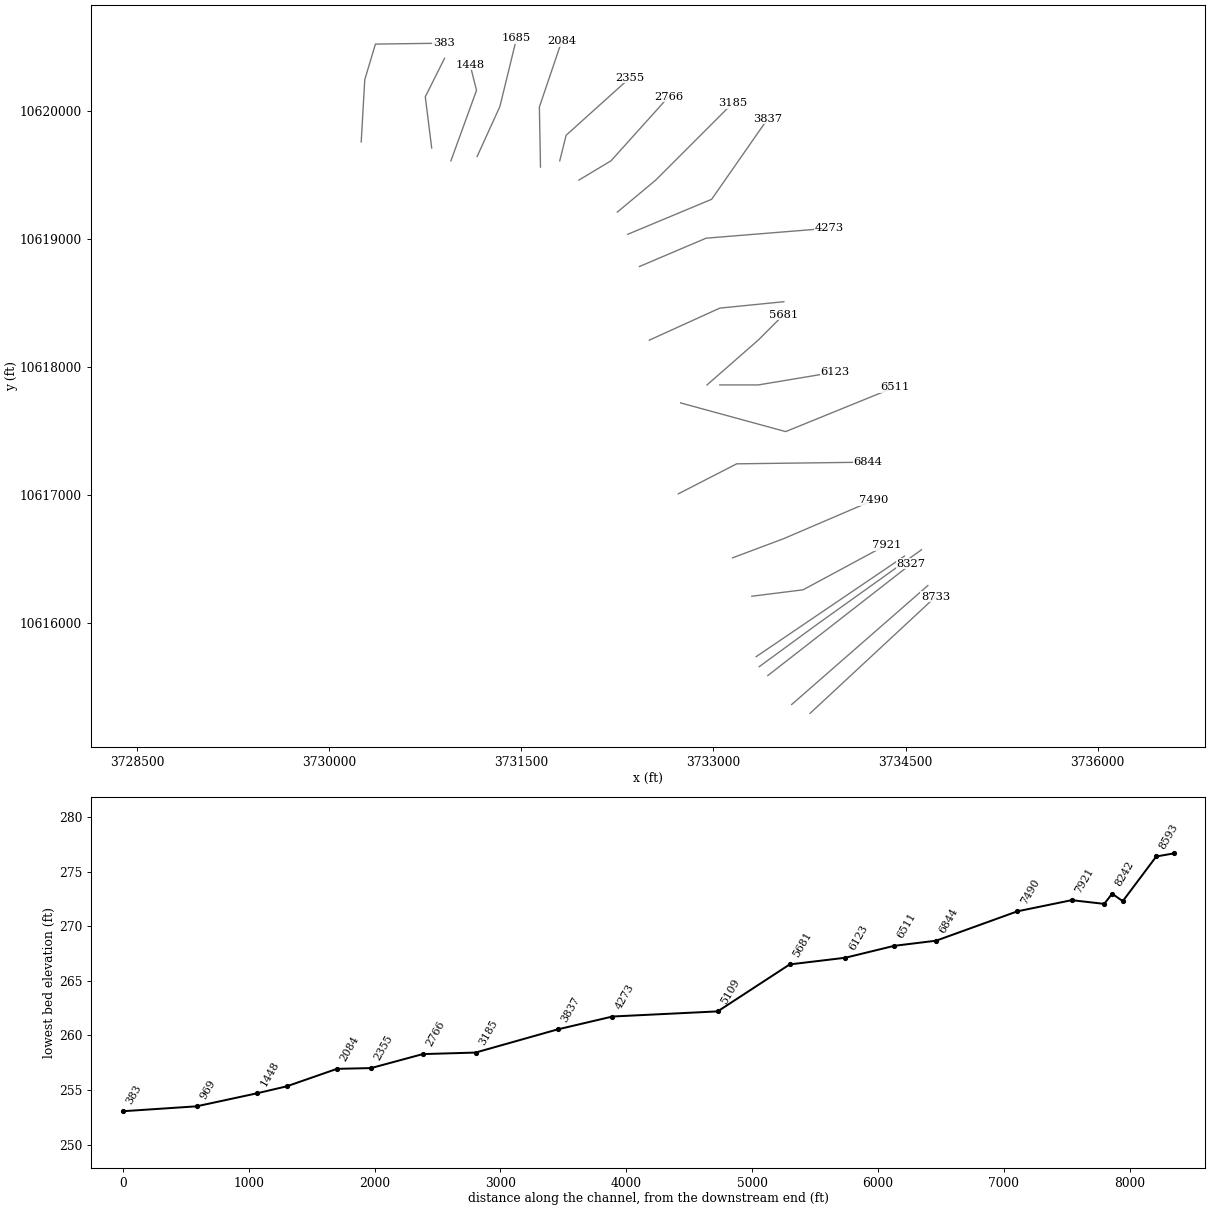
HEC-RAS study GUM CREEK.prj: GUM CREEK Base Level Engineering

--- GUM CREEK.g01 (geometry) --- (continued)

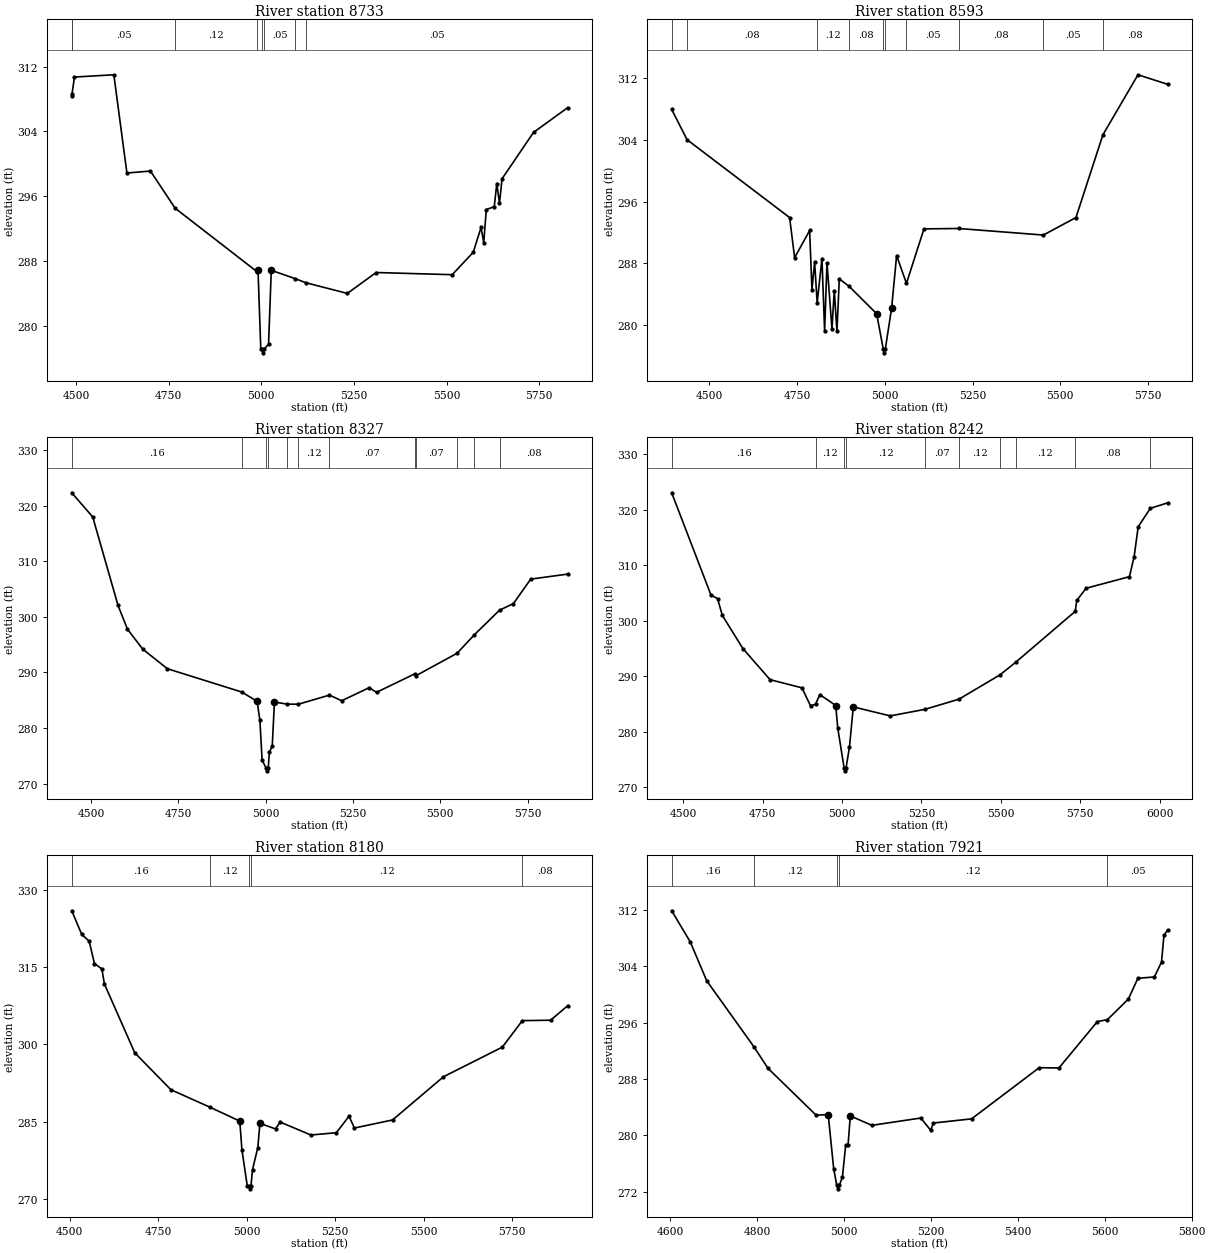
Type RM Length L Ch R = 1 ,8733    ,140,140,140
BEGIN DESCRIPTION:
Mapping XS 0ad87226
END DESCRIPTION:
XS GIS Cut Line= 2
      3733754.26     10615295.33      3734733.99     10616205.69
#Sta/Elev= 30
  4488.9  308.42  4489.4  308.58  4496.2  310.72  4602.4     311  4637.6  298.87
  4701.1  299.11  4767.7  294.52  4989.5  286.65  4991.3  286.83  4998.7  277.16
  5002.5  277.16  5005.2  276.66  5008.5  277.16  5019.7  277.72    5027  286.85
  5090.7  285.84  5119.9  285.32  5232.2     284  5309.9  286.58  5515.1  286.31
  5571.8  289.08  5592.8  292.14  5600.1  290.28    5607  294.36  5628.5  294.71
  5635.3  297.57  5642.6  295.14  5649.5  298.16  5734.5  303.89  5826.3  306.93
#Mann= 8 ,-1 , 0
  4488.9     .08       0  4489.4     .05       0  4767.7     .12       0
  4989.5     .05       0  5002.5     .03       0  5008.5     .05       0
  5090.7     .12       0  5119.9     .05       0
Bank Sta=4991.3,5027
XS Rating Curve= 0 ,0
Exp/Cntr=0.3,0.1

Type RM Length L Ch R = 1 ,8593    ,266,266,266
BEGIN DESCRIPTION:
GUM CREEK 18.0
END DESCRIPTION:
XS GIS Cut Line= 2
      3733611.06     10615364.79      3734674.43     10616293.61
#Sta/Elev= 30
  4393.3  307.95  4437.1  304.03  4729.1  293.93  4743.4  288.72  4786.1  292.25
  4792.7  284.58  4800.3  288.15  4807.6  282.85  4821.2  288.59  4828.8   279.2
  4835.5  288.07  4849.7  279.49  4856.3  284.46  4863.9  279.18  4870.6  285.97
  4898.5  285.01  4976.9  281.46  4995.7  276.88  4998.5  276.38  5001.7  276.88
  5019.6   282.2  5033.8     289  5061.8  285.39  5111.7  292.46  5210.4  292.51
  5451.6  291.66  5544.5  293.93  5621.2  304.66  5721.1  312.45  5805.2  311.22
#Mann= 10 ,-1 , 0
  4393.3     .05       0  4437.1     .08       0  4807.6     .12       0
  4898.5     .08       0  4995.7     .07       0  5001.7     .08       0
  5061.8     .05       0  5210.4     .08       0  5451.6     .05       0
  5621.2     .08       0
Bank Sta=4976.9,5019.6
XS Rating Curve= 0 ,0
Exp/Cntr=0.3,0.1

Type RM Length L Ch R = 1 ,8327    ,85,85,85
BEGIN DESCRIPTION:
GUM CREEK 17.0
END DESCRIPTION:
XS GIS Cut Line= 2
      3733424.45      10615590.5      3734544.23     10616462.89
#Sta/Elev= 30
  4444.9   322.3  4504.9  317.95  4577.3  302.04  4604.4  297.76  4647.9  294.19
  4718.4  290.66  4931.2  286.47  4975.4   284.8  4983.5  281.37  4989.8  274.21
  5001.3  272.79  5004.1  272.29  5007.3  272.79  5010.6  275.62  5018.8  276.75
  5025.1  284.67  5060.8  284.29  5093.6  284.27  5182.6  285.91  5217.8   284.9
  5296.5  287.25  5317.3  286.41  5426.1  289.71  5429.4  289.37  5547.8  293.43
  5597.3  296.75  5669.6  301.19  5709.1  302.36  5758.8  306.77  5864.4  307.67
#Mann= 12 ,-1 , 0
  4444.9     .16       0  4931.2     .12       0  5001.3     .07       0
  5007.3     .12       0  5060.8     .05       0  5093.6     .12       0
  5182.6     .07       0  5426.1     .08       0  5429.4     .07       0
  5547.8     .05       0  5597.3     .12       0  5669.6     .08       0
Bank Sta=4975.4,5025.1
XS Rating Curve= 0 ,0
Exp/Cntr=0.3,0.1

Type RM Length L Ch R = 1 ,8242    ,62,62,62
BEGIN DESCRIPTION:
Mapping XS 66a1bb78
END DESCRIPTION:
XS GIS Cut Line= 3
      3733357.57     10615660.01      3733822.84     10616000.27
      3734624.76     10616573.08
#Sta/Elev= 30
  4463.2  323.02    4587  304.61  4607.8  303.97  4622.5  300.98  4687.4  294.99
  4773.1  289.38  4873.5  287.91  4900.5  284.68  4916.3  284.95  4929.8   286.7
    4980  284.73  4986.2  280.73  5006.4  273.47  5009.1  272.97  5012.4  273.47
  5023.2  277.23  5035.3  284.48  5151.8  282.86  5261.1  284.04  5368.2  285.87
  5497.8  290.26  5546.6   292.5  5734.4  301.68  5739.3  303.65  5768.8  305.84
  5905.2  307.92  5919.9   311.5  5932.7   316.9    5971  320.22  6025.1   321.2
#Mann= 10 ,-1 , 0
  4463.2     .16       0  4916.3     .12       0  5006.4     .07       0
  5012.4     .12       0  5261.1     .07       0  5368.2     .12       0
  5497.8     .07       0  5546.6     .12       0  5734.4     .08       0
    5971      .1       0
Bank Sta=4980,5035.3
XS Rating Curve= 0 ,0
Exp/Cntr=0.3,0.1

Type RM Length L Ch R = 1 ,8180    ,259,259,259
BEGIN DESCRIPTION:
Mapping XS 2b988cb4
END DESCRIPTION:
XS GIS Cut Line= 2
      3733333.32     10615738.08      3734492.15     10616523.65
#Sta/Elev= 30
  4506.1   325.9  4534.2  321.32  4555.2  320.01  4570.1  315.68  4591.1  314.63
  4598.3  311.71    4684  298.39  4785.8  291.25    4897  287.83  4980.5  285.16
  4986.5  279.62  5001.5  272.67    5006  272.54  5008.8  272.04    5012  272.54
  5016.4  275.76  5031.4  280.03  5037.4  284.72  5081.5  283.65  5094.3  284.98
  5181.2  282.47  5253.1  282.91    5289  286.11    5304  283.82  5411.8  285.38
  5555.6  293.75  5721.8  299.49  5778.3  304.62  5858.1   304.7  5906.1  307.49
#Mann= 5 ,-1 , 0
  4506.1     .16       0    4897     .12       0    5006     .07       0
    5012     .12       0  5778.3     .08       0
Bank Sta=4980.5,5037.4
XS Rating Curve= 0 ,0
Exp/Cntr=0.3,0.1

Type RM Length L Ch R = 1 ,7921    ,431,431,431
BEGIN DESCRIPTION:
GUM CREEK 16.0
END DESCRIPTION:
XS GIS Cut Line= 3
       3733299.6     10616210.19      3733699.61     10616260.19
      3734349.64     10616610.21
#Sta/Elev= 30
    4603  311.88  4645.8  307.46  4683.6  301.94  4792.2  292.57  4824.7   289.5
  4935.6  282.84  4963.3  282.94  4975.9  275.25    4983  272.88  4985.7  272.38
    4989  272.88    4996  274.04  5003.6  278.61    5009  278.61  5014.2  282.74
  5063.7   281.4  5176.5  282.44  5199.2   280.7  5205.7  281.73  5293.3  282.32
  5449.1  289.59  5494.5  289.55  5582.9  296.14    5606  296.41  5654.3  299.34
  5676.2  302.29  5714.3  302.48  5730.6   304.6  5736.2   308.4  5744.4   309.1
#Mann= 5 ,-1 , 0
    4603     .16       0  4792.2     .12       0    4983     .07       0
    4989     .12       0    5606     .05       0
Bank Sta=4963.3,5014.2
XS Rating Curve= 0 ,0
Exp/Cntr=0.3,0.1

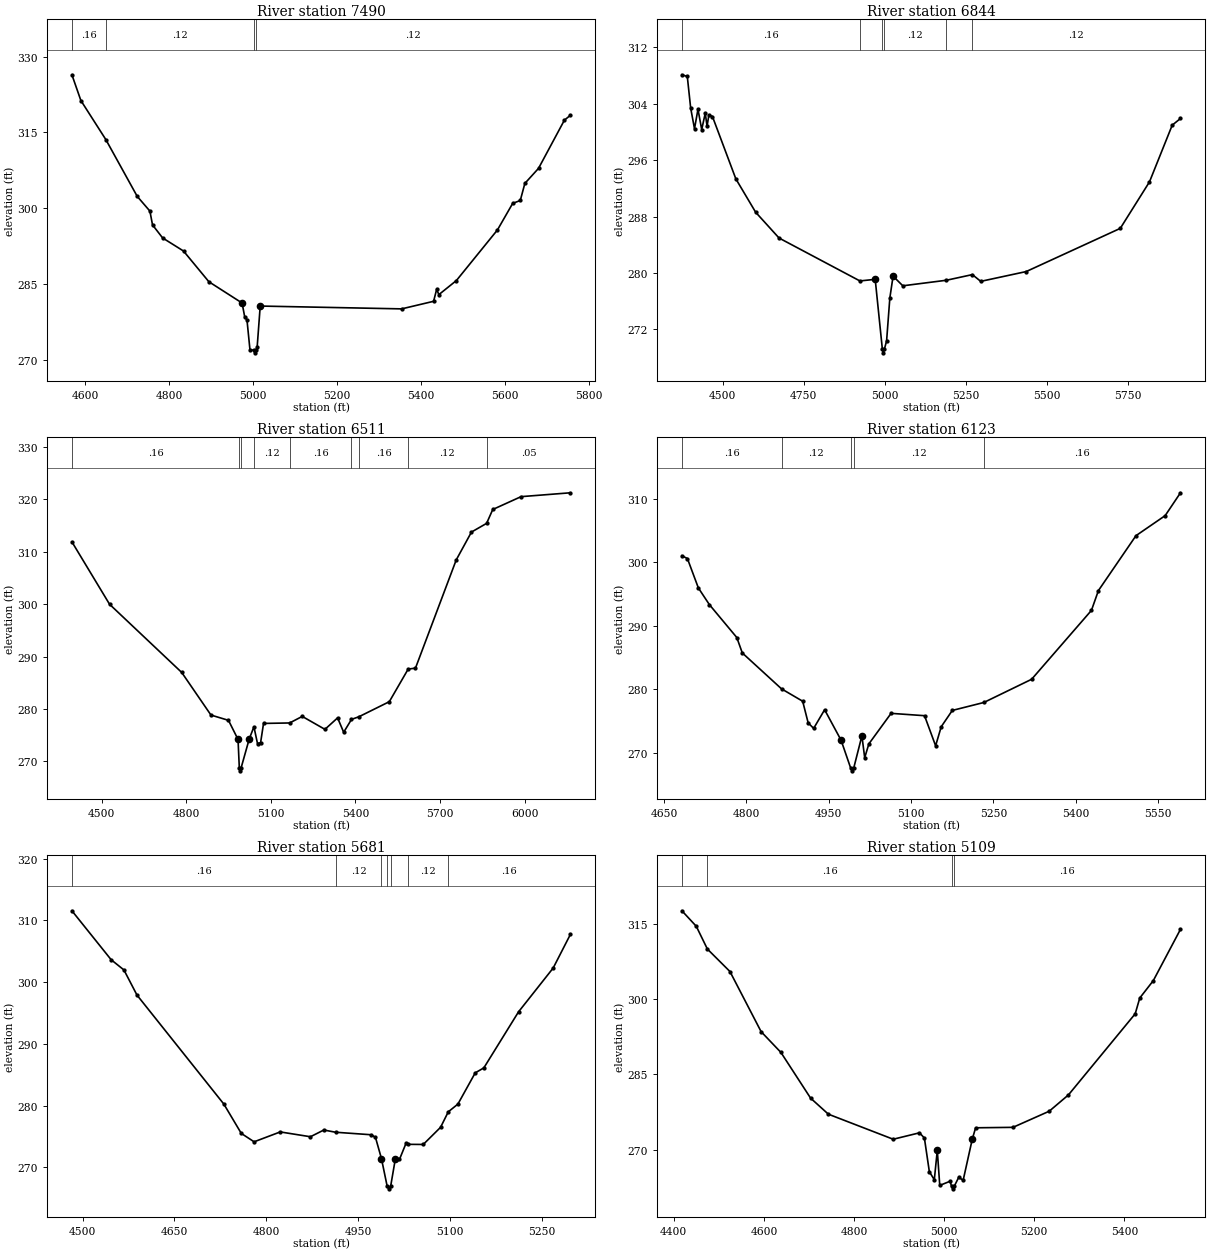
Type RM Length L Ch R = 1 ,7490    ,646,646,646
BEGIN DESCRIPTION:
GUM CREEK 15.0
END DESCRIPTION:
XS GIS Cut Line= 3
      3733149.61     10616510.19      3733549.61     10616660.19
      3734249.64      10616960.2
#Sta/Elev= 30
  4567.7  326.39  4589.1  321.29  4648.5  313.58  4723.4  302.33  4753.7  299.41
  4759.9  296.68    4784   294.1  4833.8  291.51  4894.3  285.43  4973.5  281.22
  4979.8  278.43  4985.1  277.91  4992.2  272.01    5001  271.86  5003.7  271.36
    5007  271.86  5009.4  272.48  5016.7  280.62  5353.9  280.06  5430.1  281.56
  5437.3   283.9  5442.8  282.89  5484.5  285.67  5582.4  295.69  5618.7  300.94
  5636.8  301.51  5647.7  304.89  5680.3  307.87    5742  317.41  5756.5  318.39
#Mann= 4 ,-1 , 0
  4567.7     .16       0  4648.5     .12       0    5001     .07       0
    5007     .12       0
Bank Sta=4973.5,5016.7
XS Rating Curve= 0 ,0
Exp/Cntr=0.3,0.1

Type RM Length L Ch R = 1 ,6844    ,333,333,333
BEGIN DESCRIPTION:
GUM CREEK 14.0
END DESCRIPTION:
XS GIS Cut Line= 3
      3732725.62     10617009.75      3733181.37     10617244.13
       3734205.1     10617257.15
#Sta/Elev= 30
  4374.4  308.12    4391  307.88  4401.4  303.39  4413.2  300.47  4423.9  303.23
  4435.4  300.35  4446.3  302.66  4451.9  300.83  4457.6  302.44  4468.5   302.2
  4540.6  293.35  4601.6  288.62  4673.7  284.96  4922.9  278.87    4970   279.1
  4992.1  269.17  4994.9  268.67  4998.1  269.17  5005.1  270.35  5015.1  276.45
  5025.1  279.55  5055.1  278.18  5189.6  278.97  5269.4  279.77  5295.2  278.81
  5435.2   280.2  5725.2  286.33  5815.2  292.93  5885.2  300.97  5910.7  301.92
#Mann= 6 ,-1 , 0
  4374.4     .16       0  4922.9     .12       0  4992.1     .07       0
  4998.1     .12       0  5189.6     .16       0  5269.4     .12       0
Bank Sta=4970,5025.1
XS Rating Curve= 0 ,0
Exp/Cntr=0.3,0.1

Type RM Length L Ch R = 1 ,6511    ,388,388,388
BEGIN DESCRIPTION:
GUM CREEK 13.0
END DESCRIPTION:
XS GIS Cut Line= 3
      3732743.63     10617719.81      3733563.93     10617495.86
       3734415.1     10617842.05
#Sta/Elev= 30
  4393.8  311.91  4527.4     300  4783.5  286.98  4887.2  278.85  4949.4  277.84
  4983.3  274.19  4987.9   268.7  4990.6   268.2  4993.9   268.7    5023  274.28
  5039.7  276.61  5052.4   273.4  5063.4  273.59  5073.8  277.25  5166.4  277.34
  5211.2  278.59  5291.7  276.12  5336.6  278.31  5358.2  275.56  5385.9  278.02
  5412.4  278.53  5520.1   281.4  5587.1  287.63  5612.9   287.8  5757.6  308.47
  5811.6  313.78  5865.3  315.44  5887.2  318.09  5987.6  320.54    6163  321.28
#Mann= 9 ,-1 , 0
  4393.8     .16       0  4987.9     .07       0  4993.9     .16       0
  5039.7     .12       0  5166.4     .16       0  5385.9     .12       0
  5412.4     .16       0  5587.1     .12       0  5865.3     .05       0
Bank Sta=4983.3,5023
XS Rating Curve= 0 ,0
Exp/Cntr=0.3,0.1

Type RM Length L Ch R = 1 ,6123    ,442,442,442
BEGIN DESCRIPTION:
GUM CREEK 12.0
END DESCRIPTION:
XS GIS Cut Line= 3
      3733049.59     10617860.19      3733349.61     10617860.19
      3733949.61     10617960.19
#Sta/Elev= 30
  4682.6     301  4692.6  300.57  4712.6  295.93  4732.6  293.31  4782.6  288.12
  4792.6  285.69  4864.1  280.03  4902.6  278.08  4912.6  274.67  4922.6   273.8
  4942.6  276.74  4972.6  271.93  4989.8  267.61  4992.5  267.11  4995.8  267.61
  5010.5  272.62  5015.6  269.18  5023.2  271.36  5063.7  276.17  5124.6   275.8
  5144.8  271.06    5155  274.06  5175.2  276.63  5232.6  277.88  5319.7  281.54
  5428.7   292.4  5441.4  295.52  5509.8  304.17    5563  307.33  5590.9  310.93
#Mann= 5 ,-1 , 0
  4682.6     .16       0  4864.1     .12       0  4989.8     .07       0
  4995.8     .12       0  5232.6     .16       0
Bank Sta=4972.6,5010.5
XS Rating Curve= 0 ,0
Exp/Cntr=0.3,0.1

Type RM Length L Ch R = 1 ,5681    ,572,572,572
BEGIN DESCRIPTION:
GUM CREEK 11.0
END DESCRIPTION:
XS GIS Cut Line= 3
       3732949.6     10617860.18      3733349.61     10618210.19
      3733549.64     10618410.22
#Sta/Elev= 30
  4482.5  311.55  4546.6  303.62  4567.5  301.96  4588.8  297.89  4730.7  280.23
  4759.2  275.48  4780.1  274.12  4822.8  275.72  4872.1  274.94    4894  276.03
  4913.2  275.67  4971.8  275.26  4978.4  274.82  4988.1  271.41  4997.3     267
    5000   266.5  5003.3     267  5010.7  271.28  5017.6  271.28  5028.2  273.86
  5031.7  273.71  5056.4  273.69  5084.7  276.47  5097.3  278.98    5113  280.23
  5141.3  285.29  5155.4   286.1    5212  295.17  5268.6  302.27  5296.9  307.75
#Mann= 7 ,-1 , 0
  4482.5     .16       0  4913.2     .12       0  4988.1     .16       0
  4997.3     .07       0  5003.3     .16       0  5031.7     .12       0
  5097.3     .16       0
Bank Sta=4988.1,5010.7
XS Rating Curve= 0 ,0
Exp/Cntr=0.3,0.1

Type RM Length L Ch R = 1 ,5109    ,836,836,836
BEGIN DESCRIPTION:
GUM CREEK 10.0
END DESCRIPTION:
XS GIS Cut Line= 3
      3732499.61     10618210.19      3733049.61     10618460.19
      3733549.56     10618510.18
#Sta/Elev= 30
    4418  317.59  4449.9   314.5  4474.5  309.97  4524.6  305.49  4593.8  293.51
  4637.7  289.38  4703.6  280.27  4743.1  277.07    4887  272.08  4945.3  273.36
  4956.2  272.32  4967.2  265.61  4978.2  264.01  4984.8  269.85  4990.3  262.88
  5013.4  263.72  5016.4   262.7  5019.2   262.2  5022.4   262.7  5032.2  264.46
  5042.3  263.93  5062.4  272.07  5069.9  274.36  5152.8  274.45  5233.2  277.66
  5275.9  280.91  5424.1  297.07  5434.2  300.21  5464.3  303.68  5524.6   313.9
#Mann= 4 ,-1 , 0
    4418     .05       0  4474.5     .16       0  5016.4     .07       0
  5022.4     .16       0
Bank Sta=4984.8,5062.4
XS Rating Curve= 0 ,0
Exp/Cntr=0.3,0.1

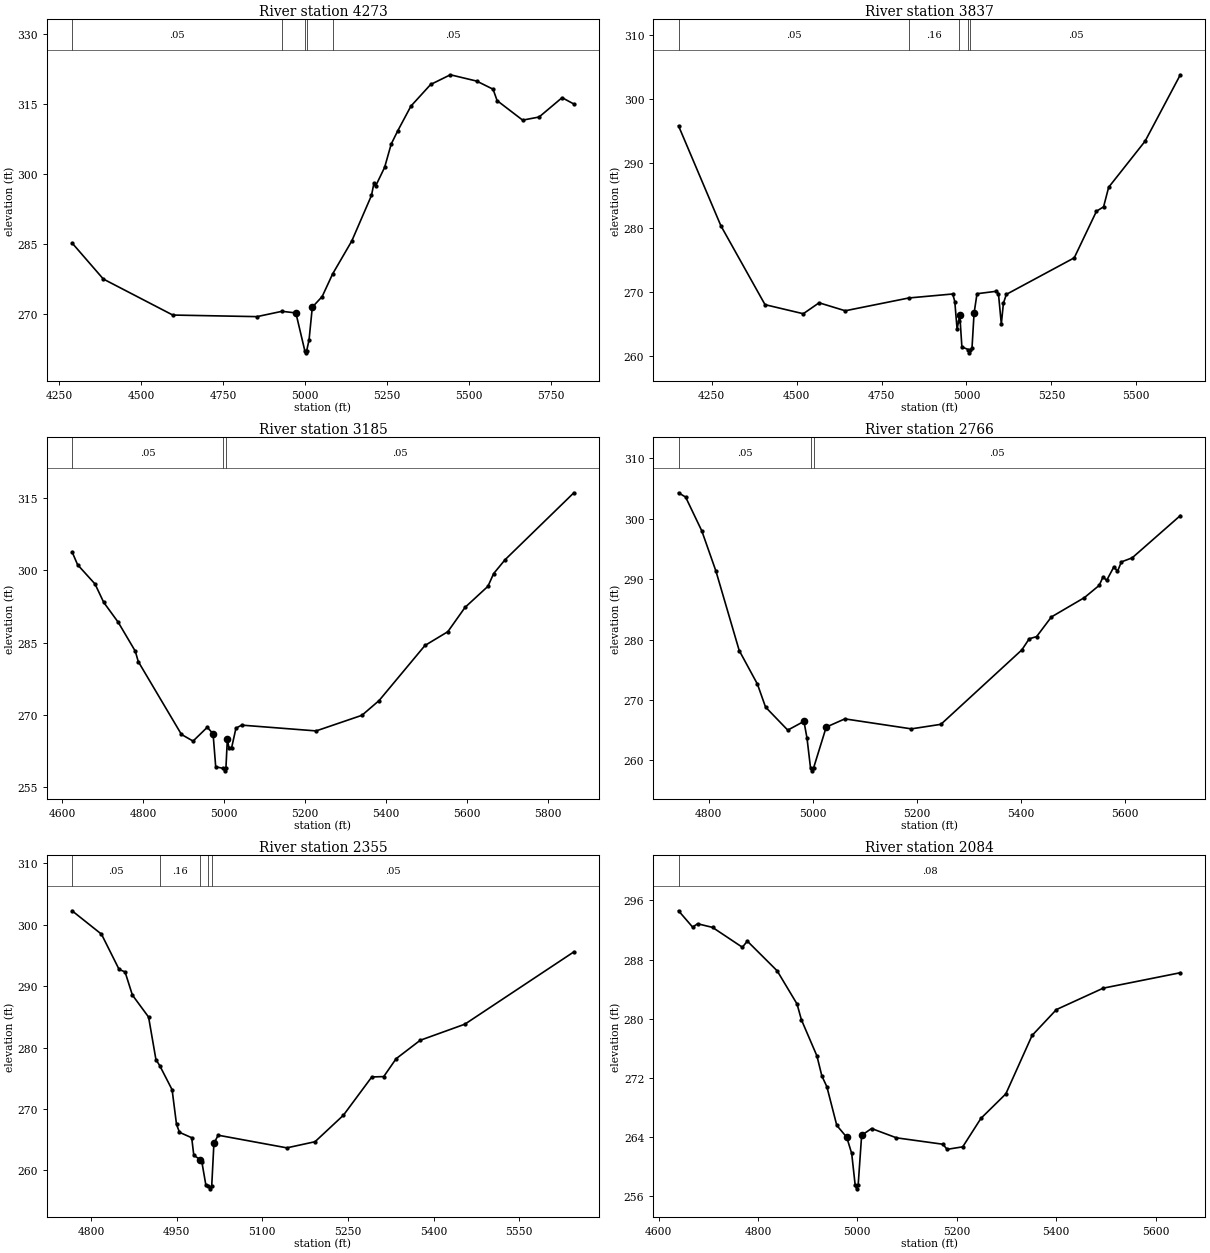
Type RM Length L Ch R = 1 ,4273    ,436,436,436
BEGIN DESCRIPTION:
GUM CREEK 9.0
END DESCRIPTION:
XS GIS Cut Line= 3
      3732421.83     10618784.93      3732942.66     10619006.29
      3733905.38     10619084.35
#Sta/Elev= 30
  4288.4  285.25  4383.8  277.53  4595.8  269.82  4852.9  269.48  4929.2  270.62
  4971.6  270.27  4998.7  262.23  5001.5  261.73  5004.7  262.23  5011.8  264.47
  5021.8  271.51  5051.9  273.78  5083.8  278.62  5142.2  285.66  5202.4  295.42
  5209.7  297.98  5214.7  297.38  5242.5  301.43  5262.6  306.42  5282.7  309.27
  5322.8  314.54    5383  319.17  5443.2  321.25  5523.5   319.9  5573.6  318.16
  5585.9  315.72  5663.9  311.54  5714.1  312.21  5784.3  316.35  5820.2  314.99
#Mann= 5 ,-1 , 0
  4288.4     .05       0  4929.2     .16       0  4998.7     .07       0
  5004.7     .16       0  5083.8     .05       0
Bank Sta=4971.6,5021.8
XS Rating Curve= 0 ,0
Exp/Cntr=0.3,0.1

Type RM Length L Ch R = 1 ,3837    ,652,652,652
BEGIN DESCRIPTION:
GUM CREEK 8.0
END DESCRIPTION:
XS GIS Cut Line= 3
      3732330.72     10619036.69      3732986.06     10619310.11
      3733424.45     10619939.48
#Sta/Elev= 30
  4152.5  295.84  4277.2   280.3  4407.1  268.04  4519.7  266.63  4566.3  268.33
  4643.2  267.09  4830.4  269.08  4959.6   269.7  4965.7  268.53  4972.4  264.26
  4977.3  265.53  4980.5  266.36  4986.6  261.47  5005.9  261.05  5008.7  260.55
  5011.9  261.05  5016.3  261.23  5022.4  266.68  5031.1  269.74  5087.8  270.12
  5094.2  269.75  5102.7  265.02  5108.8  268.26  5117.5  269.64  5317.3  275.32
  5382.8  282.57  5403.7  283.25  5418.6  286.29  5525.9  293.46  5629.6  303.78
#Mann= 5 ,-1 , 0
  4152.5     .05       0  4830.4     .16       0  4977.3     .05       0
  5005.9     .03       0  5011.9     .05       0
Bank Sta=4980.5,5022.4
XS Rating Curve= 0 ,0
Exp/Cntr=0.3,0.1

Type RM Length L Ch R = 1 ,3185    ,419,419,419
BEGIN DESCRIPTION:
GUM CREEK 7.0
END DESCRIPTION:
XS GIS Cut Line= 3
      3732249.58     10619210.17      3732549.61     10619460.19
      3733149.63     10620060.21
#Sta/Elev= 30
  4624.9  303.85  4638.6  301.17  4681.6  297.18    4703  293.38  4738.8  289.25
  4781.1  283.23  4788.3   281.1    4895  265.98  4923.7   264.6  4958.8  267.47
  4973.1  266.11  4979.6  259.27  4998.8  258.93  5001.5  258.43  5004.8  258.93
  5008.3  264.94  5012.2  263.26    5019  263.26  5029.6  267.28  5043.7  267.91
  5227.6  266.71  5340.7  269.95  5383.1  273.01  5496.3  284.43  5552.8  287.29
  5595.3  292.33  5651.8   296.7    5666  299.35  5694.3  302.23    5864   316.1
#Mann= 3 ,-1 , 0
  4624.9     .05       0  4998.8     .03       0  5004.8     .05       0
Bank Sta=4973.1,5008.3
XS Rating Curve= 0 ,0
Exp/Cntr=0.3,0.1

Type RM Length L Ch R = 1 ,2766    ,411,411,411
BEGIN DESCRIPTION:
GUM CREEK 6.0
END DESCRIPTION:
XS GIS Cut Line= 3
      3731949.59     10619460.18      3732199.61     10619610.19
      3732649.64     10620110.22
#Sta/Elev= 30
  4741.9  304.26  4755.5  303.55  4786.6  297.96  4813.8   291.3  4858.5  278.18
  4893.5  272.63  4909.1  268.83  4951.8  265.02  4982.9  266.47  4988.8  263.69
  4995.5  258.79  4998.2  258.29  5001.5  258.79  5025.7  265.52  5061.5  266.88
  5189.3  265.23  5246.1  265.98  5401.6  278.28  5415.8  280.12    5430  280.48
  5458.4  283.73  5521.9  286.93  5550.3  288.95  5557.8  290.38  5564.5  289.76
  5578.7  292.04  5585.4  291.25  5592.9  292.83  5613.8  293.51  5706.2  300.49
#Mann= 3 ,-1 , 0
  4741.9     .05       0  4995.5     .03       0  5001.5     .05       0
Bank Sta=4982.9,5025.7
XS Rating Curve= 0 ,0
Exp/Cntr=0.3,0.1

Type RM Length L Ch R = 1 ,2355    ,271,271,271
BEGIN DESCRIPTION:
GUM CREEK 5.0
END DESCRIPTION:
XS GIS Cut Line= 3
      3731799.61     10619610.21      3731849.61     10619810.19
       3732349.6     10620260.18
#Sta/Elev= 30
  4766.9  302.27  4818.4  298.46  4849.3  292.72  4859.7  292.32  4872.5  288.56
  4900.9  284.97  4913.8  278.04  4920.4  277.07  4942.1  273.14  4949.8  267.51
    4955  266.21  4976.4  265.33  4980.1  262.46  4991.4  261.77  4994.3  261.34
  5001.1  257.69  5005.5  257.51  5008.3  257.01  5011.5  257.51  5015.3  264.39
  5022.7  265.74  5143.1  263.68  5192.4  264.68  5242.1  268.99  5291.8  275.22
  5312.7  275.28  5334.4  278.19  5376.6  281.19  5454.8  283.81  5645.7  295.58
#Mann= 5 ,-1 , 0
  4766.9     .05       0  4920.4     .16       0  4991.4     .05       0
  5005.5     .03       0  5011.5     .05       0
Bank Sta=4991.4,5015.3
XS Rating Curve= 0 ,0
Exp/Cntr=0.3,0.1

Type RM Length L Ch R = 1 ,2084    ,399,399,399
BEGIN DESCRIPTION:
GUM CREEK 4.0
END DESCRIPTION:
XS GIS Cut Line= 3
      3731649.26     10619561.84      3731640.57     10620030.59
      3731814.18     10620542.74
#Sta/Elev= 30
  4640.2   294.6  4668.5  292.39  4678.6  292.84  4708.6  292.35  4768.6  289.66
  4778.6  290.49  4838.6  286.47  4878.6  281.98  4887.4  279.84  4918.6  274.95
  4928.6  272.22  4938.6  270.78  4958.6  265.53  4978.6  263.93  4988.6  261.73
  4995.6  257.44  4998.4  256.94  5001.6  257.44  5008.6  264.19  5028.6  265.11
  5078.6  263.85    5172  262.98  5180.6  262.29    5212  262.63  5248.7  266.49
  5298.7   269.8  5351.5  277.71  5400.5  281.22  5494.7  284.12  5649.8  286.21
#Mann= 1 ,-1 , 0
  4640.2     .08       0
Bank Sta=4978.6,5008.6
XS Rating Curve= 0 ,0
Exp/Cntr=0.3,0.1

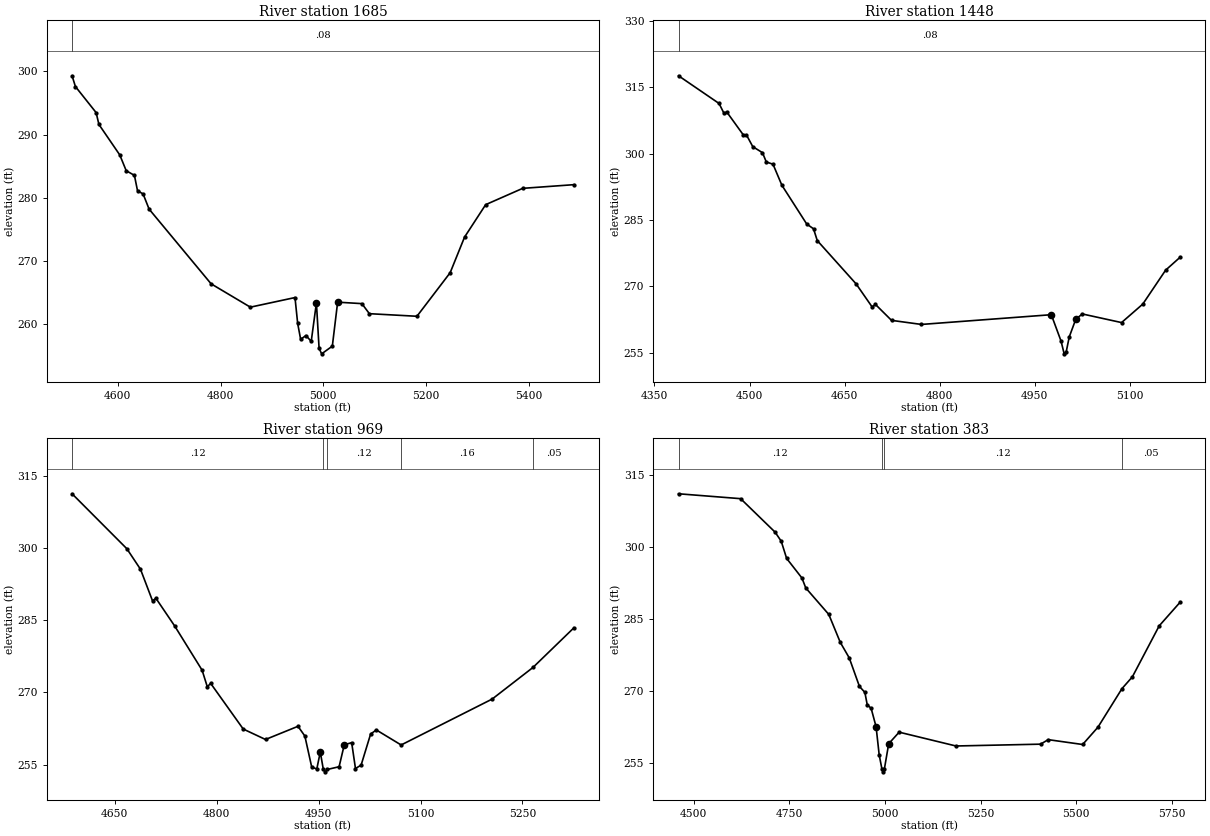
Type RM Length L Ch R = 1 ,1685    ,237,237,237
BEGIN DESCRIPTION:
Mapping XS 30c84b82
END DESCRIPTION:
XS GIS Cut Line= 3
      3731154.45     10619644.29      3731332.42     10620034.93
      3731462.18     10620566.97
#Sta/Elev= 30
    4511  299.31  4517.5  297.61  4557.8  293.49  4563.3  291.61  4603.9  286.79
  4616.4   284.3  4632.4  283.56  4638.4  281.14  4649.3  280.62    4661  278.22
  4781.7  266.41  4858.1  262.72    4945  264.24  4950.2  260.15    4956  257.63
  4966.3  258.24  4976.6  257.31  4986.7   263.4  4991.9  256.21  4996.9  255.34
  5017.7  256.56    5028  263.51  5075.2  263.28  5089.8  261.69  5182.4  261.28
  5247.1  268.17  5275.1   273.8  5316.2  278.93  5388.3  281.51  5487.9  282.09
#Mann= 1 ,-1 , 0
    4511     .08       0
Bank Sta=4986.7,5028
XS Rating Curve= 0 ,0
Exp/Cntr=0.3,0.1

Type RM Length L Ch R = 1 ,1448    ,479,479,479
BEGIN DESCRIPTION:
GUM CREEK 3.0
END DESCRIPTION:
XS GIS Cut Line= 3
       3730949.6     10619610.15      3731149.61     10620160.19
      3731099.62     10620360.16
#Sta/Elev= 30
    4388  317.58  4451.9  311.32  4459.2  309.23  4464.5  309.31  4489.8  304.28
  4495.1  304.21  4505.1  301.55  4520.4  300.19  4526.4  298.09    4537  297.58
    4551  292.82  4590.2  284.05  4600.9  282.98  4606.8  280.31    4668  270.53
  4693.3  265.31  4698.6  265.87  4723.9  262.27  4771.1  261.35  4975.9  263.55
  4991.3  257.58  4996.2   254.7  4999.5   255.2  5004.2  258.52  5014.5  262.52
  5024.8  263.72  5086.7  261.77  5120.2  265.95  5156.2  273.62  5179.4  276.59
#Mann= 1 ,-1 , 0
    4388     .08       0
Bank Sta=4975.9,5014.5
XS Rating Curve= 0 ,0
Exp/Cntr=0.3,0.1

Type RM Length L Ch R = 1 ,969     ,586,586,586
BEGIN DESCRIPTION:
GUM CREEK 2.0
END DESCRIPTION:
XS GIS Cut Line= 3
       3730799.6     10619710.23      3730749.61     10620110.19
      3730899.62      10620410.2
#Sta/Elev= 30
  4587.1  311.27  4667.7  299.86  4687.8  295.59  4705.5  289.03  4710.5  289.56
  4738.2  283.79  4778.5  274.62  4786.1  271.19  4791.1  271.88    4839   262.4
  4871.8  260.23  4919.6  262.97  4929.7  260.95  4939.8  254.49  4947.3  254.11
  4952.4  257.63  4956.9  254.01  4959.7  253.51  4962.9  254.01  4980.1  254.57
  4987.7  259.13  4998.6  259.57  5004.2   254.2  5012.5  254.91  5026.5  261.37
  5034.9  262.21  5071.4  259.09  5205.4  268.63  5265.4  275.19  5325.6  283.42
#Mann= 5 ,-1 , 0
  4587.1     .12       0  4956.9     .07       0  4962.9     .12       0
  5071.4     .16       0  5265.4     .05       0
Bank Sta=4952.4,4987.7
XS Rating Curve= 0 ,0
Exp/Cntr=0.3,0.1

Type RM Length L Ch R = 1 ,383     ,0,0,0
BEGIN DESCRIPTION:
GUM CREEK 1.0
END DESCRIPTION:
XS GIS Cut Line= 4
      3730249.24     10619758.17      3730277.02     10620244.33
      3730360.35     10620522.11      3730894.85     10620529.05
#Sta/Elev= 30
  4460.3  311.03  4622.6  310.01  4712.7  303.03  4728.7  301.14  4742.8  297.56
  4782.8  293.47  4792.9  291.39    4853  285.88    4883  280.06  4906.5  276.81
  4933.1  270.87  4947.3  269.63  4953.4  267.08  4963.8  266.27  4976.6  262.47
  4984.7  256.62  4992.1  253.56  4994.9  253.06  4998.1  253.56  5009.6  258.92
  5036.9  261.33  5185.4  258.45  5406.5  258.83  5426.5  259.77  5516.5  258.76
  5556.5  262.37  5619.3  270.41  5646.5  272.87  5716.6   283.5  5771.8  288.47
#Mann= 4 ,-1 , 0
  4460.3     .12       0  4992.1     .07       0  4998.1     .12       0
  5619.3     .05       0
Bank Sta=4976.6,5009.6
XS Rating Curve= 0 ,0
Exp/Cntr=0.3,0.1

Chan Stop Cuts=-1
Use User Specified Reach Order=0
Composite Channel Slope=5