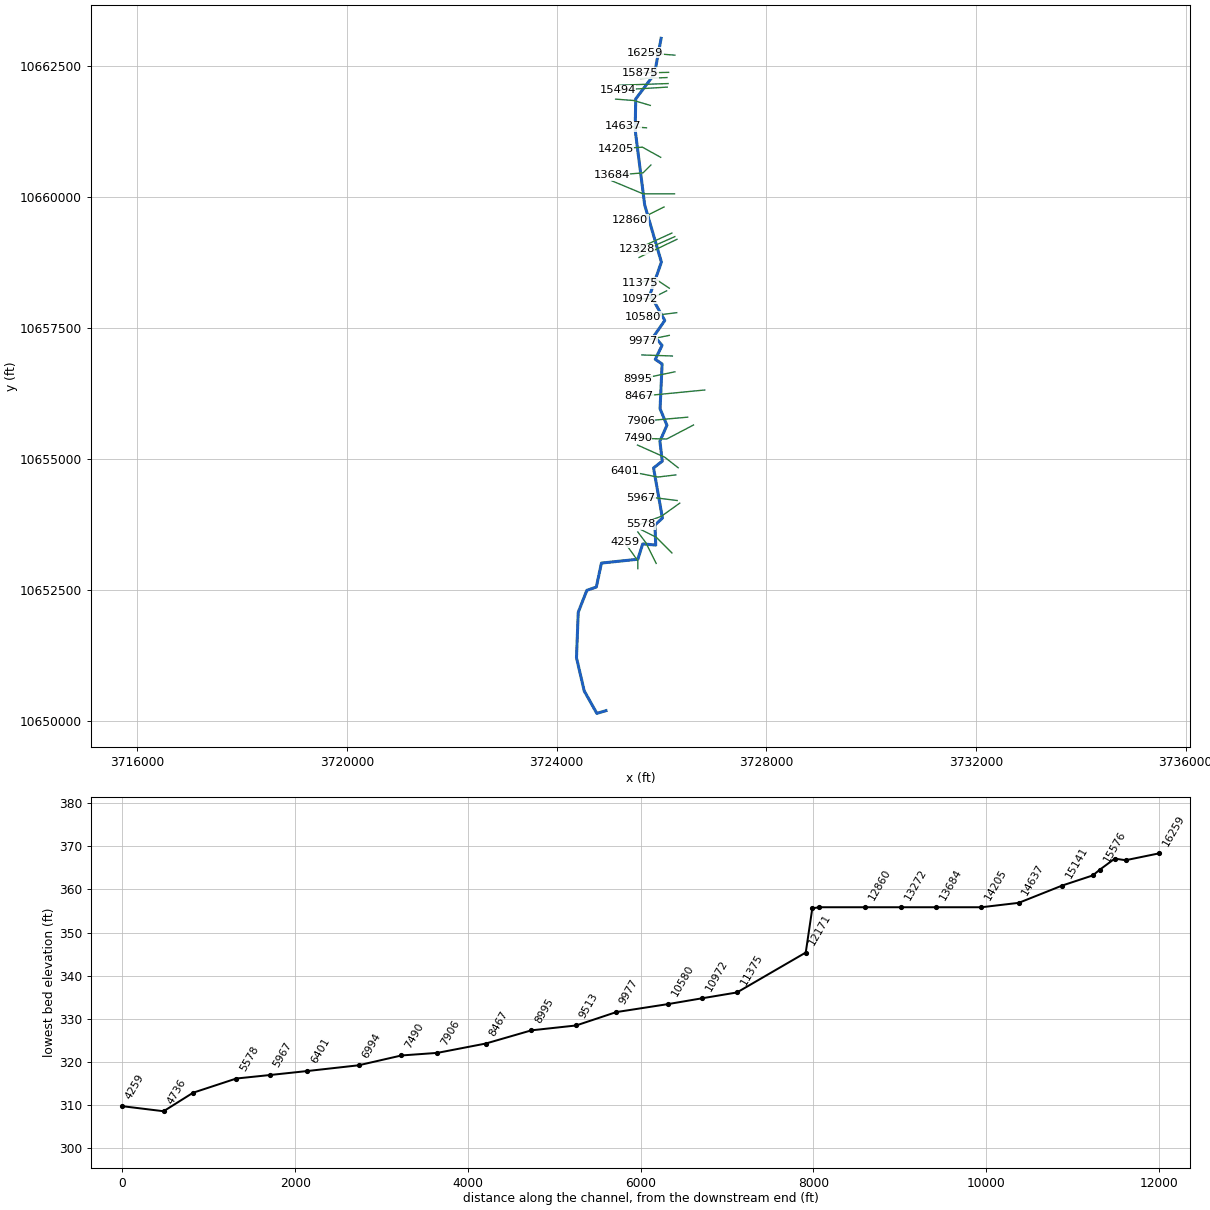
--- HARRISON LAKE.prj (project) ---

Proj Title=HARRISON LAKE Base Level Engineering
Current Plan=p01
Default Exp/Contr=0.3,0.1
English Units
Geom File=g01
Flow File=f01
Plan File=p01
Y Axis Title=Elevation
X Axis Title(PF)=Main Channel Distance
X Axis Title(XS)=Station
BEGIN DESCRIPTION:
HARRISON LAKE
END DESCRIPTION:
DSS Export Rating Curves= 0
DSS Export Rating Curve Sorted= 0
DSS Export Volume Flow Curves= 0
DXF OffsetX= 0
DXF OffsetY= 0
DXF ScaleX= 1
DXF ScaleY= 10

--- HARRISON LAKE.p01 (plan) ---

Plan Title=Multiple Run
Short Identifier=Multiple
Geom File=g01
Flow File=f01
Subcritical Flow
K Sum by GR= 0
Std Step Tol= 0.01
Critical Tol= 0.01
Num of Std Step Trials= 20
Max Error Tol= 0.3
Flow Tol Ratio= 0.001
Split Flow NTrial= 30
Split Flow Tol= 0.02
Split Flow Ratio= 0.02
Log Output Level= 0
Friction Slope Method= 1
Unsteady Friction Slope Method= 2
Unsteady Bridges Friction Slope Method= 1
Parabolic Critical Depth
Global Vel Dist=  1 , 1 , 1
Global Log Level= 0
CheckData=True
Encroach Param= -1, 0, 0, 0
BEGIN DESCRIPTION:
Multiple Run
END DESCRIPTION:

--- HARRISON LAKE.f01 (steady flow) ---

Flow Title=Multiple
Program Version=4.10
Number of Profiles= 7
Profile Names=10-year,25-year,50-year,1pct_min,100-year,1pct_plu,500-year
River Rch & RM=HARRISON LAKE,Reach-1         ,16259
     240     306     358     309     418     565     570
River Rch & RM=HARRISON LAKE,Reach-1         ,14205
     513     685     826     732     990    1339    1426
River Rch & RM=HARRISON LAKE,Reach-1         ,13684
     513     685     826     732     990    1339    1426
River Rch & RM=HARRISON LAKE,Reach-1         ,8467
     714     969    1180    1054    1426    1928    2090
Boundary for River Rch & Prof#=HARRISON LAKE,Reach-1         , 1
Up Type= 0
Dn Type= 3
Dn Slope=0.005
Boundary for River Rch & Prof#=HARRISON LAKE,Reach-1         , 2
Up Type= 0
Dn Type= 3
Dn Slope=0.005
Boundary for River Rch & Prof#=HARRISON LAKE,Reach-1         , 3
Up Type= 0
Dn Type= 3
Dn Slope=0.005
Boundary for River Rch & Prof#=HARRISON LAKE,Reach-1         , 4
Up Type= 0
Dn Type= 3
Dn Slope=0.005
Boundary for River Rch & Prof#=HARRISON LAKE,Reach-1         , 5
Up Type= 0
Dn Type= 3
Dn Slope=0.005
Boundary for River Rch & Prof#=HARRISON LAKE,Reach-1         , 6
Up Type= 0
Dn Type= 3
Dn Slope=0.005
Boundary for River Rch & Prof#=HARRISON LAKE,Reach-1         , 7
Up Type= 0
Dn Type= 3
Dn Slope=0.005
DSS Import GetInterval= 0
DSS Import GetPeak= 0
DSS Import FillOption= 0

--- HARRISON LAKE.g01 (geometry) ---

Geom Title=Existing Conditions
Program Version=4.10

River Reach=HARRISON LAKE   ,Reach-1
Reach XY= 30
      3725993.59     10663026.01      3725867.75       10662346.
       3725509.5       10661870.       3725499.5       10661276.
      3725680.75       10659847.       3725999.5       10658758.
      3725783.75       10658145.      3726063.75       10657644.
        3725859.       10657350.        3726012.       10657169.
       3725882.5       10656903.        3726013.       10656815.
        3725974.       10655961.      3726104.75       10655646.
        3725971.       10655340.      3726015.75       10654961.
      3725849.75       10654831.        3726019.       10653875.
        3725876.       10653744.      3725891.25       10653360.
       3725643.5       10653383.      3725549.75       10653090.
      3724855.75       10653017.      3724758.25       10652560.
      3724577.25       10652497.      3724413.25       10652079.
      3724379.75       10651210.       3724527.5       10650578.
        3724768.       10650150.      3724942.75       10650202.

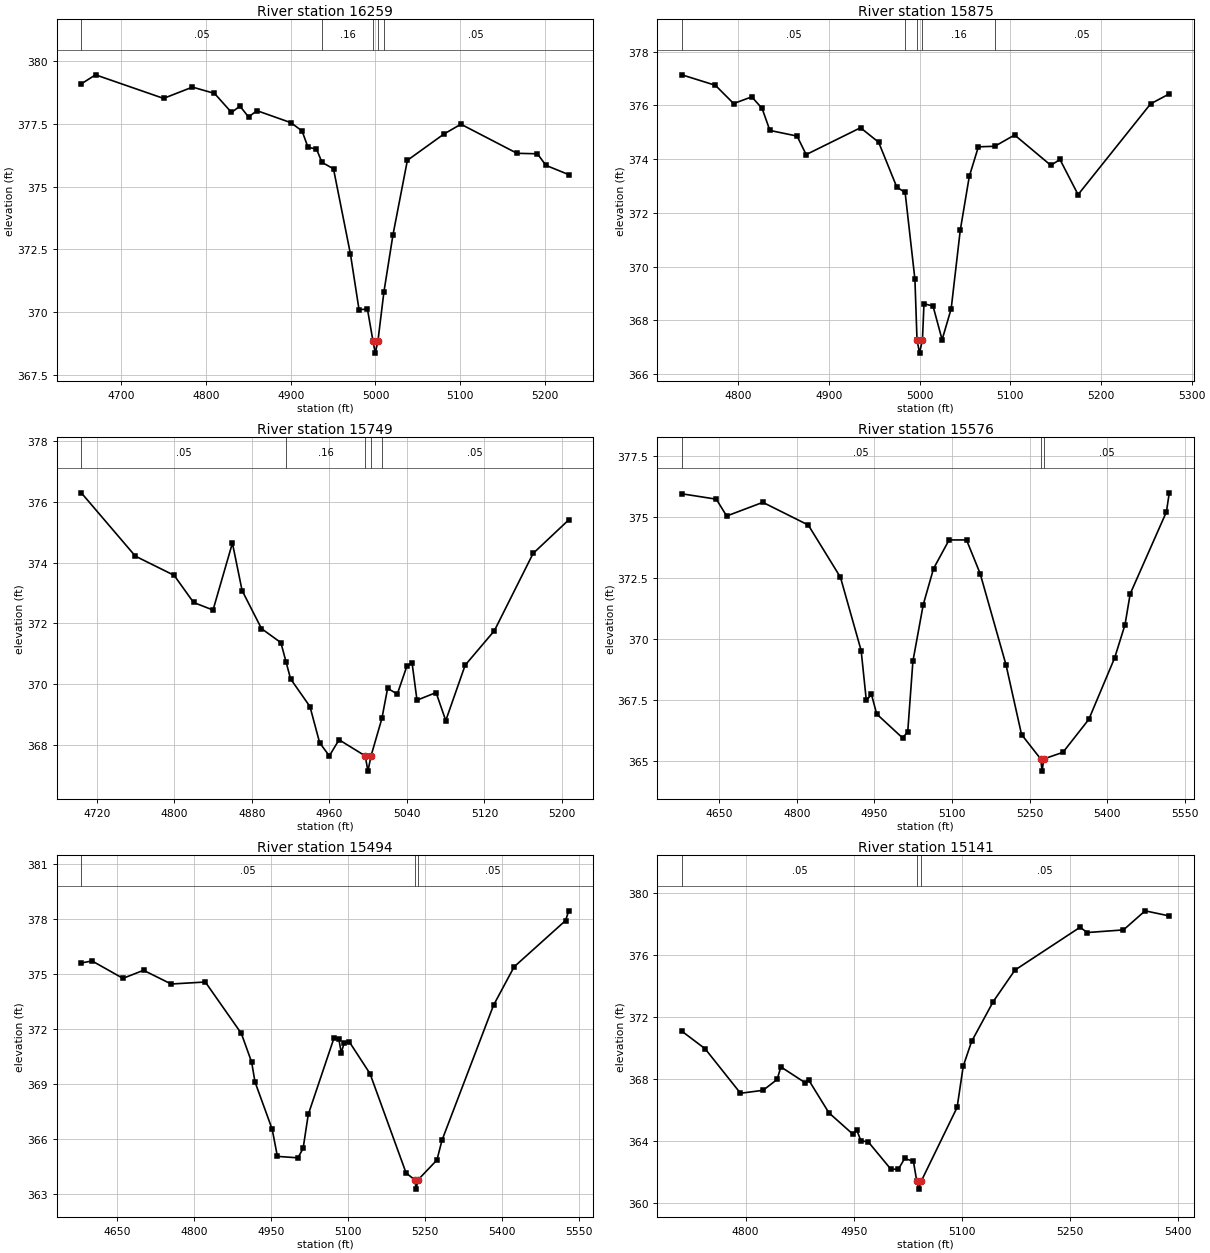
Type RM Length L Ch R = 1 ,16259   ,384,384,384
BEGIN DESCRIPTION:
HARRISON LAKE 35.0
END DESCRIPTION:
XS GIS Cut Line= 2
      3726256.38     10662705.05      3725682.83     10662749.86
#Sta/Elev= 30
  4652.8   379.1  4669.6  379.46  4749.9  378.52    4784  378.97    4810  378.72
  4830.1  377.96  4840.1  378.21  4850.2  377.78  4860.2  378.03  4900.3  377.55
  4913.4  377.22  4920.4  376.57  4930.4   376.5  4936.9  375.97  4950.5  375.71
  4970.5  372.31  4980.6   370.1  4990.6  370.11    4997  368.86  4999.8  368.36
    5003  368.86    5010   370.8  5020.7  373.08  5037.7  376.05  5080.9   377.1
  5100.9  377.49  5167.1  376.33  5191.2  376.31  5201.2  375.85  5228.1  375.48
#Mann= 5 ,-1 , 0
  4652.8     .05       0  4936.9     .16       0    4997     .07       0
    5003     .16       0    5010     .05       0
Bank Sta=4997,5003
XS Rating Curve= 0 ,0
Exp/Cntr=0.3,0.1

Type RM Length L Ch R = 1 ,15875   ,126,126,126
BEGIN DESCRIPTION:
Mapping XS 5d429113
END DESCRIPTION:
XS GIS Cut Line= 2
      3726136.65     10662376.92      3725599.06     10662365.95
#Sta/Elev= 30
  4737.6  377.14  4774.6  376.75  4794.7  376.07  4814.7  376.32  4826.1  375.89
  4834.7  375.07  4864.7  374.86  4874.7  374.17  4934.7  375.17  4954.7  374.63
  4974.7  372.96  4983.9  372.76  4994.7  369.53    4997  367.28  4999.8  366.78
    5003  367.28  5004.7  368.62  5014.7  368.53  5024.7  367.28  5034.7  368.43
  5044.7  371.35  5054.7  373.36  5064.7  374.46  5082.8  374.48  5104.7   374.9
  5144.7  373.77  5154.7  373.99  5174.7  372.68  5254.7  376.06  5275.3  376.43
#Mann= 5 ,-1 , 0
  4737.6     .05       0  4983.9     .16       0    4997     .07       0
    5003     .16       0  5082.8     .05       0
Bank Sta=4997,5003
XS Rating Curve= 0 ,0
Exp/Cntr=0.3,0.1

Type RM Length L Ch R = 1 ,15749   ,173,173,173
BEGIN DESCRIPTION:
HARRISON LAKE 34.0
END DESCRIPTION:
XS GIS Cut Line= 2
      3726105.37     10662277.96      3725602.92     10662259.16
#Sta/Elev= 30
  4704.1  376.29  4759.9  374.21  4799.9  373.58  4819.9  372.69    4840  372.44
    4860  374.64    4870  373.08    4890  371.83    4910  371.37  4915.3  370.74
    4920  370.18    4940  369.27    4950  368.08    4960  367.65    4970  368.18
    4997  367.65  4999.8  367.15    5003  367.65  5014.2  368.88  5020.1  369.87
  5030.1  369.68  5040.1  370.61  5045.4  370.69  5050.4  369.48  5070.1  369.73
  5080.1  368.81  5100.1  370.63  5130.2  371.76  5170.2   374.3  5206.9   375.4
#Mann= 5 ,-1 , 0
  4704.1     .05       0  4915.3     .16       0    4997     .07       0
    5003     .16       0  5014.2     .05       0
Bank Sta=4997,5003
XS Rating Curve= 0 ,0
Exp/Cntr=0.3,0.1

Type RM Length L Ch R = 1 ,15576   ,82,82,82
BEGIN DESCRIPTION:
HARRISON LAKE 33.0
END DESCRIPTION:
XS GIS Cut Line= 2
      3726126.16     10662163.38      3725184.07     10662132.15
#Sta/Elev= 30
  4577.7  375.95  4644.3  375.73  4664.3  375.04  4734.3   375.6  4822.2  374.67
  4884.4  372.53  4924.4  369.53  4934.4  367.49  4944.4  367.73  4954.5  366.93
  5004.5  365.95  5014.5   366.2  5024.5  369.09  5044.5  371.41  5064.5  372.89
  5094.5  374.06  5128.2  374.06  5154.6  372.68  5204.6  368.94  5234.6  366.09
  5271.6  365.09  5274.4  364.59  5277.6  365.09  5314.7  365.36  5364.7  366.71
  5414.7  369.23  5434.7  370.59  5444.7  371.85  5514.8  375.21  5520.3  375.99
#Mann= 3 ,-1 , 0
  4577.7     .05       0  5271.6     .03       0  5277.6     .05       0
Bank Sta=5271.6,5277.6
XS Rating Curve= 0 ,0
Exp/Cntr=0.3,0.1

Type RM Length L Ch R = 1 ,15494   ,353,353,353
BEGIN DESCRIPTION:
Mapping XS 744c4796
END DESCRIPTION:
XS GIS Cut Line= 2
      3726110.57     10662095.67       3725163.6     10662038.44
#Sta/Elev= 30
  4580.8  375.61  4601.8  375.72  4661.9  374.77    4702  375.21  4755.8  374.46
  4822.2  374.57  4892.3  371.76  4912.4  370.19  4918.9  369.11  4952.4  366.52
  4962.5  365.04  5002.5  364.96  5012.6  365.48  5022.6  367.33  5072.7  371.51
  5081.9  371.47  5086.9  370.71  5092.7  371.26  5102.7  371.29  5142.8  369.56
  5212.9  364.14    5230  363.75  5232.7  363.25    5236  363.75    5273  364.84
    5283  365.93  5383.2   373.3  5423.3   375.4  5523.5  377.93  5529.5  378.46
#Mann= 3 ,-1 , 0
  4580.8     .05       0    5230     .03       0    5236     .05       0
Bank Sta=5230,5236
XS Rating Curve= 0 ,0
Exp/Cntr=0.3,0.1

Type RM Length L Ch R = 1 ,15141   ,504,504,504
BEGIN DESCRIPTION:
HARRISON LAKE 32.0
END DESCRIPTION:
XS GIS Cut Line= 3
      3725787.62     10661746.73      3725469.95     10661840.46
      3725126.24      10661866.5
#Sta/Elev= 30
  4711.6  371.09  4743.8  369.96  4792.9  367.09  4824.2  367.28  4843.7  367.98
  4848.9  368.79  4882.2  367.78  4887.4  367.95  4915.5  365.83  4948.8  364.45
    4954  364.74  4959.8  364.03  4970.2  363.95  5001.5  362.19  5011.9   362.2
  5020.6  362.89  5032.7   362.7  5037.4  361.41  5040.1  360.91  5043.4  361.41
  5093.3  366.18  5101.8  368.84  5113.4  370.43  5143.4     373  5173.5  375.03
  5263.8  377.79  5273.8  377.45    5324  377.62    5354  378.85  5387.5  378.52
#Mann= 3 ,-1 , 0
  4711.6     .05       0  5037.4     .03       0  5043.4     .05       0
Bank Sta=5037.4,5043.4
XS Rating Curve= 0 ,0
Exp/Cntr=0.3,0.1

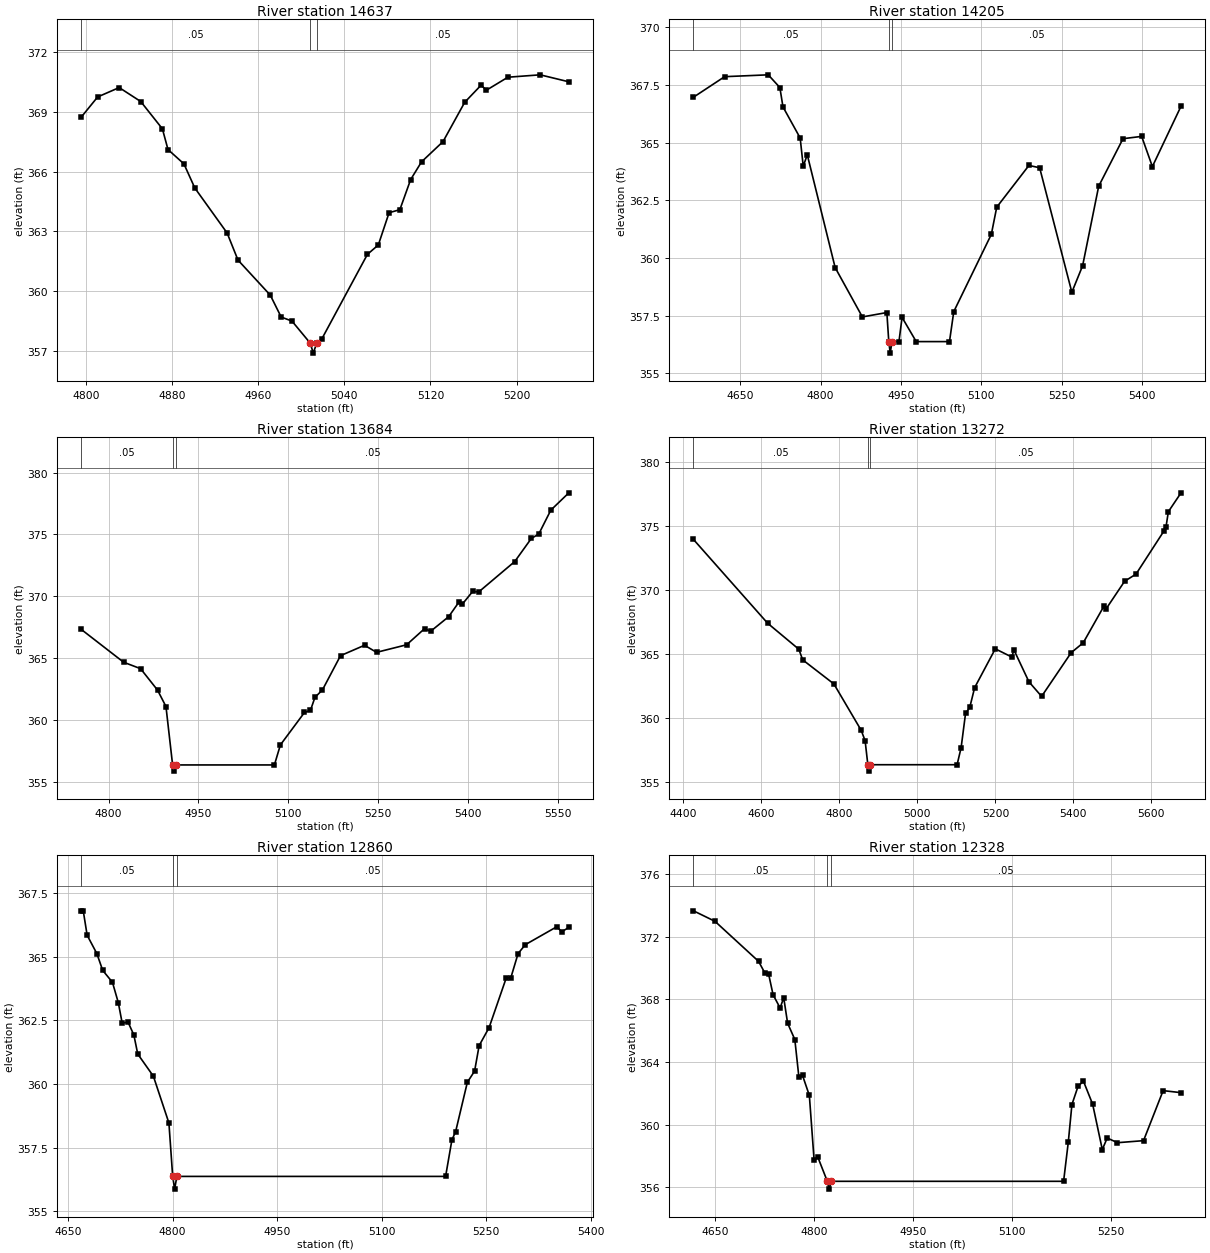
Type RM Length L Ch R = 1 ,14637   ,432,432,432
BEGIN DESCRIPTION:
HARRISON LAKE 31.0
END DESCRIPTION:
XS GIS Cut Line= 2
      3725714.73     10661319.63       3725263.1     10661350.78
#Sta/Elev= 30
  4795.8  368.74    4811  369.75    4831  370.22    4851  369.52  4871.1  368.15
  4876.3  367.11  4891.1  366.39  4901.2  365.18  4931.2  362.92  4941.3  361.56
  4971.3   359.8  4981.4   358.7  4991.4   358.5  5008.4  357.39  5011.2  356.89
  5014.4  357.39  5019.2  357.61  5061.5  361.85  5071.6  362.32  5081.6  363.94
  5091.6  364.09  5101.6   365.6  5111.7  366.49  5131.7  367.51  5151.8  369.48
    5167  370.34    5172  370.09  5191.9  370.74  5221.9  370.86  5248.5  370.51
#Mann= 3 ,-1 , 0
  4795.8     .05       0  5008.4     .03       0  5014.4     .05       0
Bank Sta=5008.4,5014.4
XS Rating Curve= 0 ,0
Exp/Cntr=0.3,0.1

Type RM Length L Ch R = 1 ,14205   ,521,521,521
BEGIN DESCRIPTION:
HARRISON LAKE 30.0
END DESCRIPTION:
XS GIS Cut Line= 3
      3725985.57     10660757.13      3725636.62     10660949.84
       3725126.2     10660918.59
#Sta/Elev= 30
  4562.8  366.97  4620.9  367.86  4702.3  367.94    4724  367.39  4729.8  366.55
  4761.9   365.2  4767.6  363.98  4775.2  364.47  4827.2  359.58    4878  357.44
  4923.7  357.63  4927.3  356.37    4930  355.87  4933.3  356.37  4946.3  356.37
  4952.1  357.42  4978.5  356.37  5040.6  356.37  5048.6  357.67  5118.7  361.02
  5128.8   362.2  5188.9  364.01  5208.9  363.91    5269  358.51  5289.1  359.66
  5319.1  363.11  5364.5  365.17  5399.3  365.27  5419.3  363.96  5472.8  366.58
#Mann= 3 ,-1 , 0
  4562.8     .05       0  4927.3     .03       0  4933.3     .05       0
Bank Sta=4927.3,4933.3
XS Rating Curve= 0 ,0
Exp/Cntr=0.3,0.1

Type RM Length L Ch R = 1 ,13684   ,412,412,412
BEGIN DESCRIPTION:
HARRISON LAKE 29.0
END DESCRIPTION:
XS GIS Cut Line= 3
      3725799.59     10660610.17      3725649.61     10660460.19
       3725049.6     10660410.19
#Sta/Elev= 30
  4754.5  367.32  4825.2  364.67  4853.5  364.15  4881.8  362.42  4895.9  361.09
    4907  356.37  4909.8  355.87    4913  356.37    5077  356.37    5087  357.99
  5127.2  360.61  5137.2  360.78  5144.7  361.83  5157.3  362.44  5187.4   365.2
  5227.5  366.04  5247.6  365.47  5297.8  366.08  5327.9  367.39  5337.9  367.17
    5368  368.35  5385.6  369.56  5390.6  369.35  5408.1  370.39  5418.2  370.35
  5478.4  372.81    5506  374.67  5518.5  375.03  5538.6  376.96  5568.7  378.36
#Mann= 3 ,-1 , 0
  4754.5     .05       0    4907     .03       0    4913     .05       0
Bank Sta=4907,4913
XS Rating Curve= 0 ,0
Exp/Cntr=0.3,0.1

Type RM Length L Ch R = 1 ,13272   ,412,412,412
BEGIN DESCRIPTION:
HARRISON LAKE 28.0
END DESCRIPTION:
XS GIS Cut Line= 3
      3726249.57     10660060.19      3725649.61     10660060.19
      3725049.57      10660310.2
#Sta/Elev= 30
  4425.9  373.94  4615.9  367.41  4695.9  365.38  4705.9  364.55  4785.9  362.67
  4855.9  359.05  4865.9  358.24  4872.9  356.37  4875.6  355.87  4878.9  356.37
  5101.7  356.37    5112  357.69  5123.4  360.37  5134.2  360.84  5146.7  362.38
  5199.7  365.41    5242  364.77  5247.4  365.33  5285.9  362.84  5318.4   361.7
  5394.2  365.11  5425.1  365.88  5478.2  368.74  5483.6  368.52  5531.2  370.68
  5560.5  371.24    5632   374.6  5637.4  374.93  5643.4  376.11  5675.9  377.58
#Mann= 3 ,-1 , 0
  4425.9     .05       0  4872.9     .03       0  4878.9     .05       0
Bank Sta=4872.9,4878.9
XS Rating Curve= 0 ,0
Exp/Cntr=0.3,0.1

Type RM Length L Ch R = 1 ,12860   ,532,532,532
BEGIN DESCRIPTION:
HARRISON LAKE 27.0
END DESCRIPTION:
XS GIS Cut Line= 3
      3726049.58     10659810.17      3725749.61     10659660.19
      3725399.59     10659560.18
#Sta/Elev= 30
  4668.9  366.81  4671.7  366.81  4677.3  365.85  4691.2  365.13  4699.6  364.47
  4713.6     364    4722   363.2  4727.6  362.39  4735.9  362.44  4744.3  361.93
  4749.9  361.18  4772.3  360.31  4794.6  358.47    4800  356.37  4802.8  355.87
    4806  356.37  5191.5  356.37  5200.6  357.81  5205.8  358.12  5222.7  360.07
  5233.1  360.51  5239.6  361.51  5253.9  362.22  5278.6  364.18  5285.1  364.18
  5295.5  365.13  5305.9  365.48  5351.4  366.19  5357.9  365.98  5368.3  366.16
#Mann= 3 ,-1 , 0
  4668.9     .05       0    4800    .033       0    4806     .05       0
Bank Sta=4800,4806
XS Rating Curve= 0 ,0
Exp/Cntr=0.3,0.1

Type RM Length L Ch R = 1 ,12328   ,81,81,81
BEGIN DESCRIPTION:
HARRISON LAKE 26.0
END DESCRIPTION:
XS GIS Cut Line= 2
      3726199.15     10659311.83      3725527.93     10659004.84
#Sta/Elev= 30
  4617.4  373.67  4649.9     373  4715.9  370.44  4725.5  369.69    4731  369.65
  4737.9   368.3  4748.5  367.46    4754  368.11  4759.9  366.48  4770.8  365.44
    4777  363.02  4782.5  363.14  4792.8  361.86    4800  357.72  4805.5  357.93
    4820  356.37  4822.8  355.87    4826  356.37  5177.7  356.37  5184.8  358.87
  5190.3  361.28  5199.7  362.46  5207.8  362.77  5221.7   361.3  5236.3   358.4
  5243.7  359.14  5259.3  358.84  5298.7  358.97  5328.4  362.17  5355.5  362.04
#Mann= 3 ,-1 , 0
  4617.4     .05       0    4820    .033       0    4826     .05       0
Bank Sta=4820,4826
XS Rating Curve= 0 ,0
Exp/Cntr=0.3,0.1

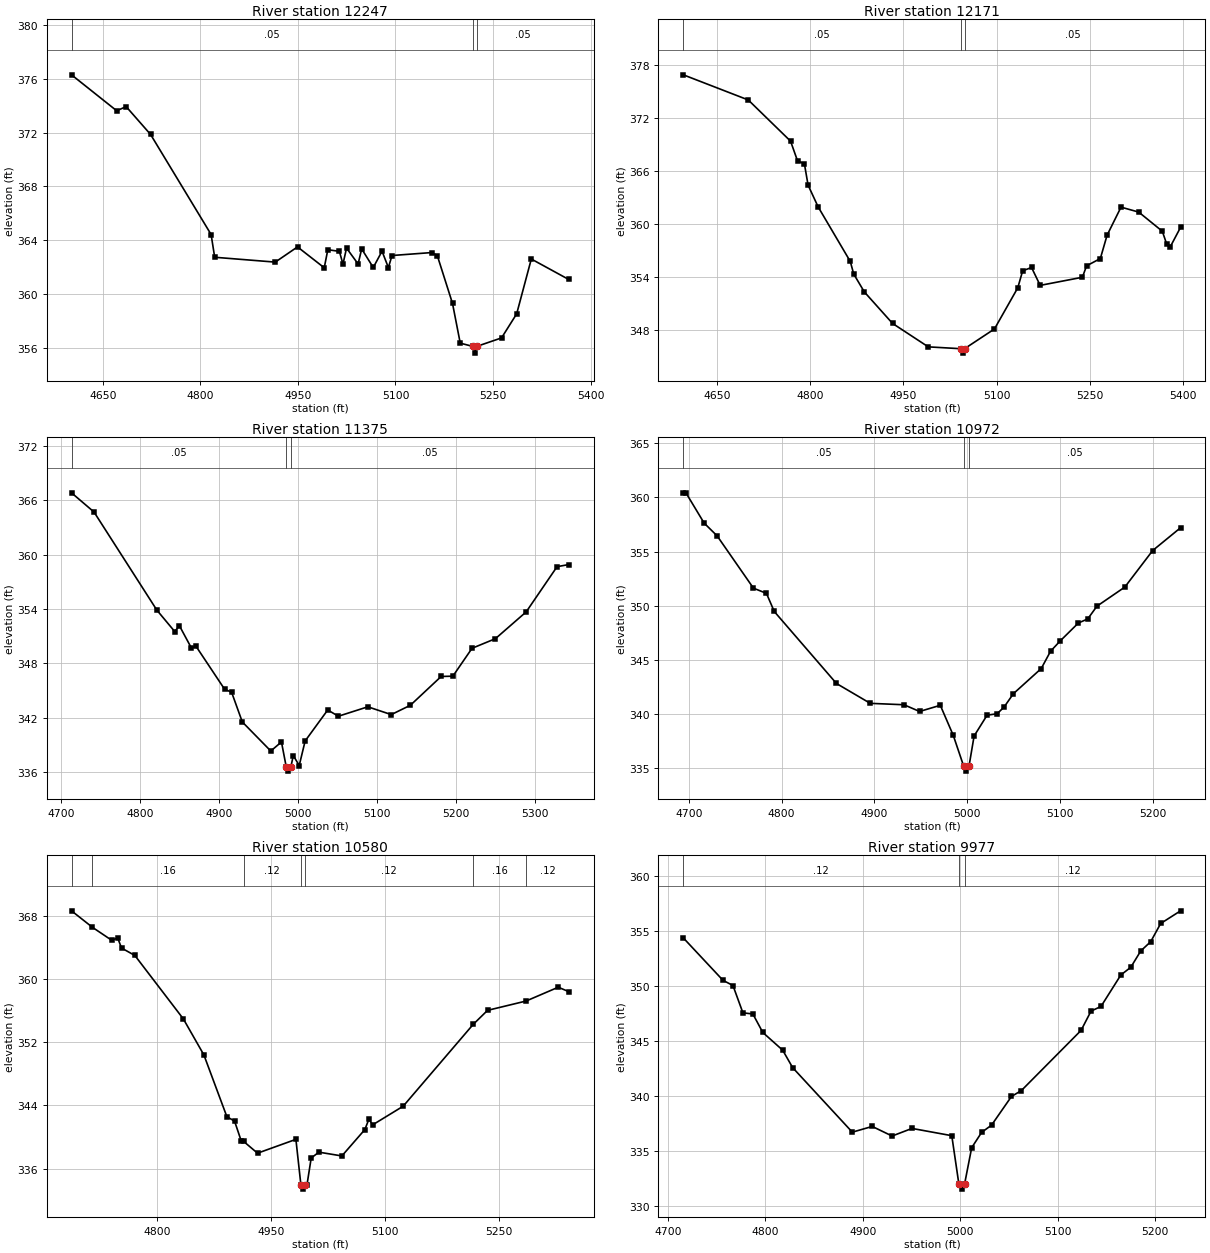
Type RM Length L Ch R = 1 ,12247   ,76,76,76
BEGIN DESCRIPTION:
Mapping XS 97a11ff0
END DESCRIPTION:
XS GIS Cut Line= 2
       3726256.4      10659244.1      3725556.98     10658934.69
#Sta/Elev= 30
  4601.7  376.29  4671.2  373.62  4685.7  373.93  4723.3  371.86  4816.4  364.43
  4821.9  362.74  4915.1  362.38  4949.3  363.51  4990.4  361.96  4995.9   363.3
  5013.7  363.18  5019.2  362.23  5024.7  363.42  5042.5  362.24    5048  363.36
  5065.8  361.98  5079.3  363.19  5089.1  361.97  5094.6  362.87  5155.9  363.09
  5164.4  362.85  5187.7  359.31  5199.6  356.36    5219  356.12  5221.7  355.62
    5225  356.12  5263.1  356.75  5286.4  358.54  5308.9  362.61  5366.5  361.09
#Mann= 3 ,-1 , 0
  4601.7     .05       0    5219     .03       0    5225     .05       0
Bank Sta=5219,5225
XS Rating Curve= 0 ,0
Exp/Cntr=0.3,0.1

Type RM Length L Ch R = 1 ,12171   ,796,796,796
BEGIN DESCRIPTION:
HARRISON LAKE 25.0
END DESCRIPTION:
XS GIS Cut Line= 2
      3726295.48     10659192.03       3725573.1     10658846.43
#Sta/Elev= 30
  4595.5  376.91  4700.1  374.06  4768.2  369.39  4779.4  367.16  4790.5  366.82
  4796.4  364.41  4812.6  361.94  4864.4  355.75  4869.9  354.33    4887   352.3
  4932.4  348.73    4990  346.07  5042.4  345.86  5045.2  345.36  5048.4  345.86
  5096.6   348.1  5134.1  352.76    5142  354.69  5156.3  355.07  5170.2  353.04
  5238.2  353.96    5245  355.26  5267.1  356.08    5278  358.73  5300.4  361.91
  5328.9  361.35  5366.9  359.18  5374.2  357.68  5379.8  357.42  5396.3  359.62
#Mann= 3 ,-1 , 0
  4595.5     .05       0  5042.4     .03       0  5048.4     .05       0
Bank Sta=5042.4,5048.4
XS Rating Curve= 0 ,0
Exp/Cntr=0.3,0.1

Type RM Length L Ch R = 1 ,11375   ,403,403,403
BEGIN DESCRIPTION:
HARRISON LAKE 24.0
END DESCRIPTION:
XS GIS Cut Line= 3
      3726149.59      10658260.2      3725849.61     10658460.19
       3725599.6     10658360.18
#Sta/Elev= 30
  4713.5  366.82    4742   364.7  4821.6  353.87  4844.2  351.51  4850.2  352.14
  4865.2  349.71  4871.2  349.88  4907.3  345.15  4916.3   344.8  4929.8  341.53
  4965.9  338.32  4979.4  339.32  4985.4   336.6  4988.1   336.1  4991.4   336.6
  4994.4  337.82  5001.9  336.72  5009.4  339.43    5038  342.85  5051.5  342.16
  5088.8   343.2  5118.5  342.34  5142.7  343.37  5181.7  346.55  5196.5  346.58
  5220.8  349.66  5250.4  350.72  5289.4  353.68  5328.5  358.67  5343.3   358.9
#Mann= 3 ,-1 , 0
  4713.5     .05       0  4985.4     .03       0  4991.4     .05       0
Bank Sta=4985.4,4991.4
XS Rating Curve= 0 ,0
Exp/Cntr=0.3,0.1

Type RM Length L Ch R = 1 ,10972   ,392,392,392
BEGIN DESCRIPTION:
HARRISON LAKE 23.0
END DESCRIPTION:
XS GIS Cut Line= 3
      3726099.64      10658210.2      3725799.61     10658060.19
      3725599.65     10658060.19
#Sta/Elev= 30
  4694.2  360.41    4697  360.41  4716.6  357.62  4730.6  356.44  4769.7  351.62
  4783.7  351.14  4792.1  349.47  4859.1  342.83  4895.5     341  4931.8  340.87
  4948.6  340.25  4970.9  340.82  4984.9  338.04  4995.9  335.25  4998.6  334.75
  5001.9  335.25  5007.3  337.99  5021.3  339.91  5032.1  340.04  5039.6  340.66
  5049.6  341.89  5079.6  344.21  5089.6   345.8  5099.6  346.72  5119.6  348.41
  5129.6  348.78  5139.6  349.96  5169.6  351.72  5199.6  355.09  5229.6  357.19
#Mann= 3 ,-1 , 0
  4694.2     .05       0  4995.9     .03       0  5001.9     .05       0
Bank Sta=4995.9,5001.9
XS Rating Curve= 0 ,0
Exp/Cntr=0.3,0.1

Type RM Length L Ch R = 1 ,10580   ,603,603,603
BEGIN DESCRIPTION:
HARRISON LAKE 22.0
END DESCRIPTION:
XS GIS Cut Line= 2
      3726292.16     10657792.91      3725643.75     10657713.16
#Sta/Elev= 30
  4687.9  368.64  4715.4  366.55  4740.9   364.9  4748.5  365.22  4753.6  363.93
  4771.1  362.99  4834.8  354.96  4861.8   350.4    4892  342.58  4902.1  342.02
    4911  339.47  4913.9  339.46  4932.3  337.96  4982.7  339.71  4989.3  333.91
  4992.1  333.41  4995.3  333.91  4997.3  333.97  5002.8  337.35  5012.9  338.09
  5043.1  337.61  5073.3  340.95  5078.6  342.26  5083.6  341.55  5123.7  343.91
  5215.7  354.27  5234.5  356.04  5285.1  357.22  5327.4  358.97  5341.2  358.41
#Mann= 7 ,-1 , 0
  4687.9     .05       0  4715.4     .16       0  4913.9     .12       0
  4989.3     .07       0  4995.3     .12       0  5215.7     .16       0
  5285.1     .12       0
Bank Sta=4989.3,4995.3
XS Rating Curve= 0 ,0
Exp/Cntr=0.3,0.1

Type RM Length L Ch R = 1 ,9977    ,464,464,464
BEGIN DESCRIPTION:
HARRISON LAKE 21.0
END DESCRIPTION:
XS GIS Cut Line= 3
      3726149.56     10657360.18      3725899.61     10657310.19
      3725649.57     10657260.18
#Sta/Elev= 30
    4716  354.34  4756.7  350.49  4766.9  350.02  4777.1  347.54  4787.3  347.44
  4797.5  345.76  4817.9  344.15  4828.1  342.57  4889.3  336.71  4909.7  337.23
  4930.1  336.36  4950.5  337.05  4991.3  336.39  4998.5  332.04  5001.3  331.54
  5004.5  332.04  5011.7   335.3  5021.9  336.69  5032.1  337.35  5052.5  339.95
  5062.7  340.49  5123.9  345.95  5134.1   347.7  5144.3  348.12  5164.7  350.98
  5174.9  351.68  5185.1  353.16  5195.3     354  5205.5  355.65  5225.9   356.8
#Mann= 3 ,-1 , 0
    4716     .12       0  4998.5     .07       0  5004.5     .12       0
Bank Sta=4998.5,5004.5
XS Rating Curve= 0 ,0
Exp/Cntr=0.3,0.1

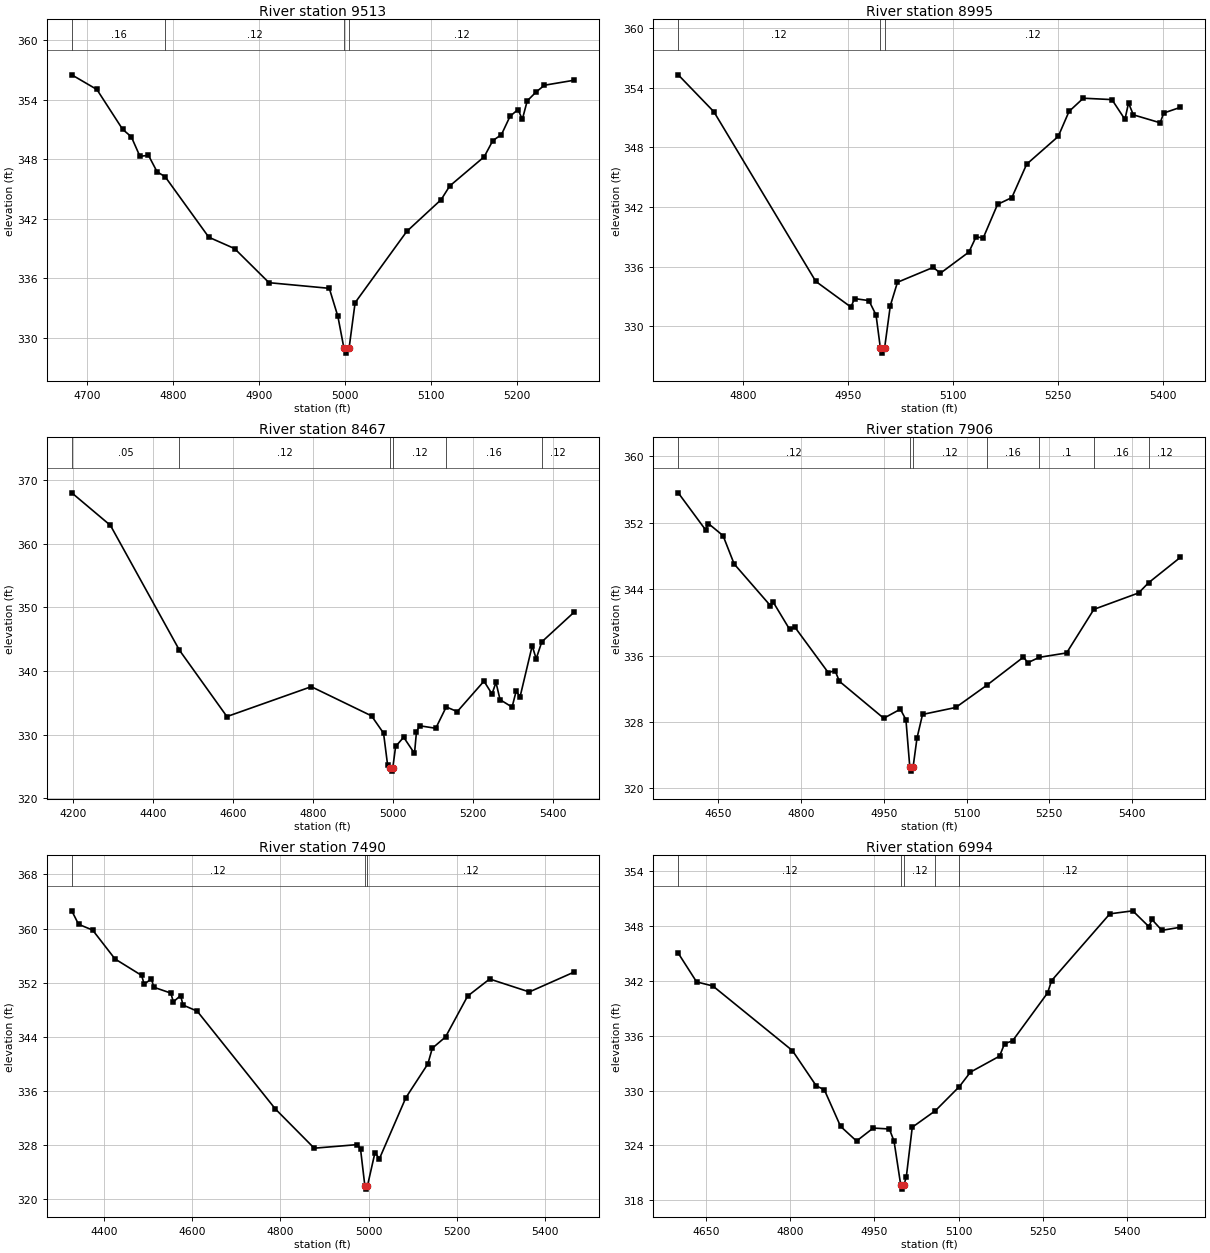
Type RM Length L Ch R = 1 ,9513    ,518,518,518
BEGIN DESCRIPTION:
HARRISON LAKE 20.0
END DESCRIPTION:
XS GIS Cut Line= 2
      3726208.78     10656966.52      3725625.45     10656987.35
#Sta/Elev= 30
  4682.3  356.53  4711.5  355.05  4741.5  351.02  4751.5  350.28  4761.5  348.31
  4771.5   348.4  4781.5  346.74  4790.9  346.24  4841.6  340.14  4871.6  338.99
  4911.6  335.55  4981.7  334.98  4991.7  332.14  4998.7  328.94  5001.4  328.44
  5004.7  328.94  5011.7  333.53  5071.7  340.72  5111.7  343.93  5121.7  345.31
  5161.8  348.26  5171.8  349.89  5181.8  350.49  5191.8  352.34  5201.1  353.03
  5206.1  352.03  5211.8   353.9  5221.8  354.77  5231.8  355.48    5266  355.98
#Mann= 4 ,-1 , 0
  4682.3     .16       0  4790.9     .12       0  4998.7     .07       0
  5004.7     .12       0
Bank Sta=4998.7,5004.7
XS Rating Curve= 0 ,0
Exp/Cntr=0.3,0.1

Type RM Length L Ch R = 1 ,8995    ,528,528,528
BEGIN DESCRIPTION:
HARRISON LAKE 19.0
END DESCRIPTION:
XS GIS Cut Line= 2
      3726256.33     10656665.12      3725553.89     10656519.86
#Sta/Elev= 30
  4707.6  355.28  4758.5  351.57  4904.1  334.52  4954.3  331.94  4959.5  332.79
    4980  332.59  4990.2  331.14  4996.4  327.81  4999.2  327.31  5002.4  327.81
  5010.6  332.08  5020.8  334.43  5071.9  335.93  5082.1  335.34  5122.9  337.47
  5133.1     339  5143.3  338.88  5163.8  342.26  5184.2  342.94  5205.4   346.3
  5250.5  349.09  5265.9   351.6  5286.3  352.93  5327.2  352.79  5345.8   350.8
  5350.9  352.45  5357.8  351.26  5396.1  350.46  5401.2  351.44  5424.9  352.01
#Mann= 3 ,-1 , 0
  4707.6     .12       0  4996.4     .07       0  5002.4     .12       0
Bank Sta=4996.4,5002.4
XS Rating Curve= 0 ,0
Exp/Cntr=0.3,0.1

Type RM Length L Ch R = 1 ,8467    ,561,561,561
BEGIN DESCRIPTION:
HARRISON LAKE 18.0
END DESCRIPTION:
XS GIS Cut Line= 2
      3726825.88     10656318.33      3725575.88      10656196.8
#Sta/Elev= 30
  4195.9  368.02  4292.6   362.9  4465.2  343.27    4584  332.83    4795  337.53
  4945.7  332.94  4975.8  330.22  4985.9  325.22  4992.9  324.75  4995.7  324.25
  4998.9  324.75    5006  328.13  5026.1  329.58  5053.2  327.03  5058.2  330.48
  5066.3  331.38  5106.4  330.99  5132.6  334.35  5160.1  333.61    5227   338.4
  5247.1  336.38    5257  338.21  5267.2  335.49  5297.3  334.32  5307.4  336.81
  5317.4  335.97  5347.6  343.96  5357.6  341.92  5371.6  344.58  5451.8  349.21
#Mann= 6 ,-1 , 0
  4195.9     .05       0  4465.2     .12       0  4992.9     .07       0
  4998.9     .12       0  5132.6     .16       0  5371.6     .12       0
Bank Sta=4992.9,4998.9
XS Rating Curve= 0 ,0
Exp/Cntr=0.3,0.1

Type RM Length L Ch R = 1 ,7906    ,416,416,416
BEGIN DESCRIPTION:
HARRISON LAKE 17.0
END DESCRIPTION:
XS GIS Cut Line= 2
      3726500.49     10655799.85       3725594.4     10655720.01
#Sta/Elev= 30
  4577.7  355.61  4627.3  351.14  4632.3  351.91  4658.9  350.45    4679  347.04
  4744.5  342.03  4749.5  342.47  4779.4  339.17  4789.4  339.39  4849.6  333.94
  4861.7   334.2  4869.7   332.9    4950  328.45  4980.1  329.54  4990.2  328.28
  4997.2  322.58    5000  322.08  5003.2  322.58  5010.3  326.08  5020.3  328.91
  5080.5  329.75    5137  332.44  5203.2  335.82    5211  335.14  5231.7  335.79
  5281.3  336.32  5330.7  341.57  5411.8  343.55  5429.7  344.77  5487.3  347.83
#Mann= 7 ,-1 , 0
  4577.7     .12       0  4997.2     .07       0  5003.2     .12       0
    5137     .16       0  5231.7      .1       0  5330.7     .16       0
  5429.7     .12       0
Bank Sta=4997.2,5003.2
XS Rating Curve= 0 ,0
Exp/Cntr=0.3,0.1

Type RM Length L Ch R = 1 ,7490    ,496,496,496
BEGIN DESCRIPTION:
HARRISON LAKE 16.0
END DESCRIPTION:
XS GIS Cut Line= 3
      3726611.59     10655650.55      3726101.16     10655383.18
      3725538.64     10655397.07
#Sta/Elev= 30
  4326.8  362.62  4342.2  360.63  4374.2  359.77  4424.8  355.51  4485.3  353.07
    4491  351.77  4507.4  352.56    4513  351.32  4551.5  350.46  4557.2  349.16
  4573.6  350.09  4579.2  348.69  4611.3  347.79  4788.6  333.33  4876.8  327.53
  4974.6  328.06  4981.9  327.36  4991.6  321.98  4994.3  321.48  4997.6  321.98
  5014.6  326.89  5024.6  325.96  5084.6  334.99  5134.6     340  5144.6  342.31
  5174.6  343.97  5224.7  350.01  5274.7  352.54  5364.7  350.63  5465.7  353.55
#Mann= 3 ,-1 , 0
  4326.8     .12       0  4991.6     .07       0  4997.6     .12       0
Bank Sta=4991.6,4997.6
XS Rating Curve= 0 ,0
Exp/Cntr=0.3,0.1

Type RM Length L Ch R = 1 ,6994    ,593,593,593
BEGIN DESCRIPTION:
HARRISON LAKE 15.0
END DESCRIPTION:
XS GIS Cut Line= 3
      3726319.89     10654834.59      3726062.96     10655035.96
      3725543.38     10655268.05
#Sta/Elev= 30
    4600  345.05  4632.8   341.9  4661.7  341.46  4803.6  334.38  4846.1  330.52
  4860.6  330.08  4889.5  326.08    4918  324.47  4947.8  325.89  4976.5  325.79
  4984.9  324.46  4996.7   319.7  4999.4   319.2  5002.7   319.7  5006.8  320.54
  5017.4  325.98  5058.6  327.79  5101.5  330.44  5121.2  332.02  5173.1  333.77
    5182  335.13  5196.3  335.45  5258.7  340.69    5266  342.05  5369.8  349.36
  5410.7  349.69  5439.4  347.96  5444.9  348.74  5462.6  347.55  5495.5  347.89
#Mann= 5 ,-1 , 0
    4600     .12       0  4996.7     .07       0  5002.7     .12       0
  5058.6     .16       0  5101.5     .12       0
Bank Sta=4996.7,5002.7
XS Rating Curve= 0 ,0
Exp/Cntr=0.3,0.1

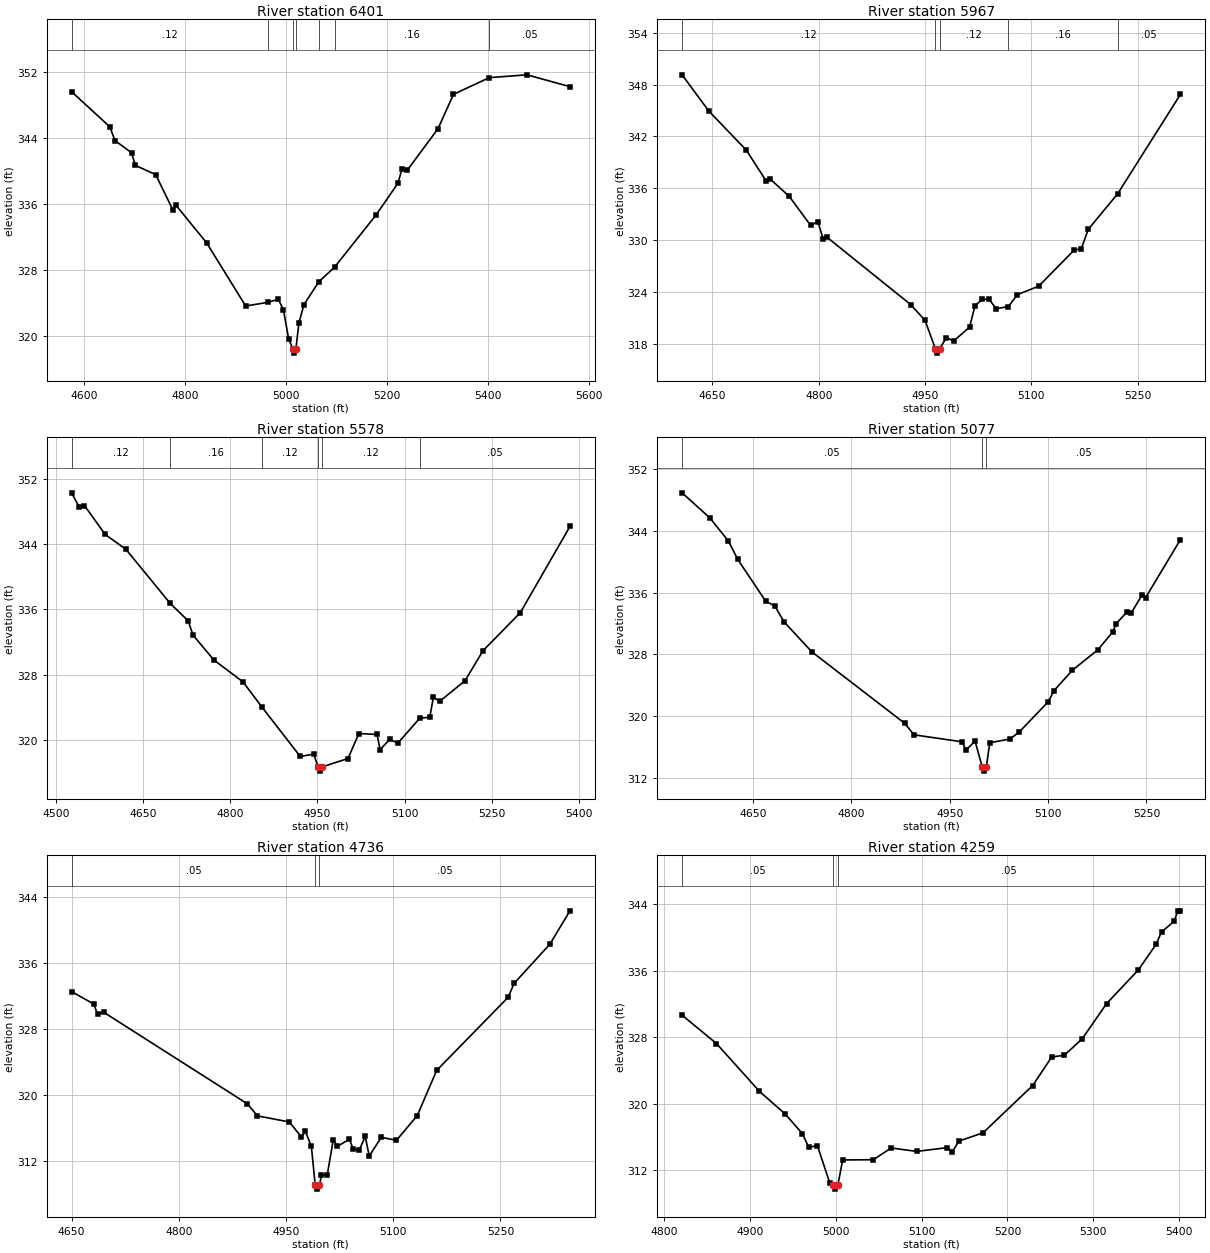
Type RM Length L Ch R = 1 ,6401    ,434,434,434
BEGIN DESCRIPTION:
HARRISON LAKE 14.0
END DESCRIPTION:
XS GIS Cut Line= 3
      3726274.76     10654699.16      3725931.02     10654657.49
      3725303.57     10654782.29
#Sta/Elev= 30
  4575.9  349.64  4651.6  345.37  4661.7   343.7  4694.5  342.22    4702  340.69
  4742.3  339.56  4776.3  335.27  4782.6  335.82    4843  331.28  4920.3   323.6
  4963.5  324.03  4984.8   324.4    4995  323.16  5005.2  319.63  5013.7  318.37
  5016.4  317.87  5019.7  318.37  5025.6  321.57  5035.7  323.77  5065.1  326.55
  5096.1  328.31  5178.5  334.68  5221.2  338.49  5229.5  340.21  5239.7  340.08
  5300.8  345.14  5331.4  349.32  5402.4  351.35  5476.8  351.69  5561.9  350.25
#Mann= 7 ,-1 , 0
  4575.9     .12       0  4963.5     .16       0  5013.7     .07       0
  5019.7     .16       0  5065.1     .12       0  5096.1     .16       0
  5402.4     .05       0
Bank Sta=5013.7,5019.7
XS Rating Curve= 0 ,0
Exp/Cntr=0.3,0.1

Type RM Length L Ch R = 1 ,5967    ,389,389,389
BEGIN DESCRIPTION:
HARRISON LAKE 13.0
END DESCRIPTION:
XS GIS Cut Line= 3
      3726299.62     10654210.19      3725899.61     10654260.19
      3725599.64     10654260.19
#Sta/Elev= 30
  4607.3  349.12  4645.1  344.92    4698   340.4  4725.7  336.87  4730.8  337.13
  4758.5  335.06  4788.7   331.7  4798.8  332.16  4806.3  330.14  4811.4  330.36
  4929.8  322.55    4950  320.73  4964.6  317.44  4967.3  316.94  4970.6  317.44
  4980.2  318.74  4990.3  318.34  5012.9  319.94  5020.4  322.39  5030.4  323.16
  5040.4  323.16  5050.4  322.07  5067.6  322.33  5080.4  323.71  5110.4  324.68
  5160.4  328.86  5170.4     329  5180.4  331.27  5221.8  335.37  5310.4  346.87
#Mann= 5 ,-1 , 0
  4607.3     .12       0  4964.6     .07       0  4970.6     .12       0
  5067.6     .16       0  5221.8     .05       0
Bank Sta=4964.6,4970.6
XS Rating Curve= 0 ,0
Exp/Cntr=0.3,0.1

Type RM Length L Ch R = 1 ,5578    ,501,501,501
BEGIN DESCRIPTION:
HARRISON LAKE 12.0
END DESCRIPTION:
XS GIS Cut Line= 3
      3726349.63      10654160.2      3725999.61     10653910.19
      3725599.65      10653760.2
#Sta/Elev= 30
  4527.3  350.34  4540.8  348.54  4549.4  348.78  4585.1  345.22  4620.7   343.4
  4696.8  336.76  4727.6  334.62  4736.2  332.85  4771.9   329.8  4822.3  327.09
  4854.9  323.99  4920.6  317.93  4943.9  318.22  4951.4  316.63  4954.1  316.13
  4957.4  316.63  5002.8  317.68  5021.5  320.75  5052.7  320.64    5058  318.77
  5074.9  320.06  5088.3  319.55  5126.1  322.63  5143.4  322.76  5149.7  325.23
  5160.4   324.7    5204  327.24  5235.1  330.94  5299.2  335.61  5384.6  346.21
#Mann= 6 ,-1 , 0
  4527.3     .12       0  4696.8     .16       0  4854.9     .12       0
  4951.4     .07       0  4957.4     .12       0  5126.1     .05       0
Bank Sta=4951.4,4957.4
XS Rating Curve= 0 ,0
Exp/Cntr=0.3,0.1

Type RM Length L Ch R = 1 ,5077    ,341,341,341
BEGIN DESCRIPTION:
HARRISON LAKE 11.0
END DESCRIPTION:
XS GIS Cut Line= 3
       3726199.6     10653210.19      3725899.61     10653510.19
      3725599.58      10653660.2
#Sta/Elev= 30
  4542.2  348.94  4584.6  345.68  4612.9  342.67    4627   340.3  4669.5   334.9
  4683.6  334.24  4697.8  332.18  4740.2  328.29  4881.6  319.03  4895.7  317.54
  4969.3  316.63  4974.8  315.56  4988.8  316.72  4999.8  313.33  5002.5  312.83
  5005.8  313.33  5011.2  316.52  5041.9  316.99  5055.9  317.89  5100.6  321.86
    5109  323.27    5137  325.91  5176.1  328.59  5198.4  330.87    5204  331.98
  5220.8  333.53  5226.4   333.3  5243.2  335.66  5248.8  335.35  5301.9  342.88
#Mann= 3 ,-1 , 0
  4542.2     .05       0  4999.8     .03       0  5005.8     .05       0
Bank Sta=4999.8,5005.8
XS Rating Curve= 0 ,0
Exp/Cntr=0.3,0.1

Type RM Length L Ch R = 1 ,4736    ,477,477,477
BEGIN DESCRIPTION:
HARRISON LAKE 10.0
END DESCRIPTION:
XS GIS Cut Line= 3
       3725899.6     10653010.22      3725699.61     10653410.19
       3725549.6      10653610.2
#Sta/Elev= 30
    4650  332.48  4680.7  330.99  4686.3  329.76  4694.7  329.99  4895.9  318.88
  4909.9  317.42  4954.6  316.68  4971.4  314.87    4977  315.55  4985.4  313.74
  4990.8  309.04  4993.5  308.54  4996.8  309.04  4999.4   310.2  5007.7  310.29
  5016.1  314.53  5021.7  313.71  5038.5  314.59  5044.1  313.39  5052.5  313.28
  5060.8  314.93  5066.4  312.54  5083.2  314.82  5104.5  314.46  5133.6  317.46
  5160.7  322.93  5260.7  331.79  5269.1  333.49  5319.1  338.23  5347.2  342.27
#Mann= 3 ,-1 , 0
    4650     .05       0  4990.8     .03       0  4996.8     .05       0
Bank Sta=4990.8,4996.8
XS Rating Curve= 0 ,0
Exp/Cntr=0.3,0.1

Type RM Length L Ch R = 1 ,4259    ,476,476,476
BEGIN DESCRIPTION:
HARRISON LAKE 9.0
END DESCRIPTION:
XS GIS Cut Line= 3
      3725549.61      10652910.2      3725549.61     10653060.19
      3725299.61     10653410.18
#Sta/Elev= 30
  4821.3  330.64  4861.3  327.23  4911.3  321.48  4941.3  318.75  4961.3  316.39
  4968.8  314.72  4978.7  314.96  4993.4  310.39  4996.6  310.21  4999.3  309.71
  5002.6  310.21  5008.2  313.22  5043.8  313.25  5064.7  314.66  5094.2  314.25
  5129.8   314.7    5136  314.22  5143.3  315.48  5171.6  316.49  5229.4  322.18
  5251.5  325.61  5266.2  325.82  5287.1  327.81  5315.4  332.04  5352.2  336.07
  5373.1  339.18  5379.3  340.66    5394  341.93  5398.3   343.2  5401.4   343.2
#Mann= 3 ,-1 , 0
  4821.3     .05       0  4996.6     .03       0  5002.6     .05       0
Bank Sta=4996.6,5002.6
XS Rating Curve= 0 ,0
Exp/Cntr=0.3,0.1