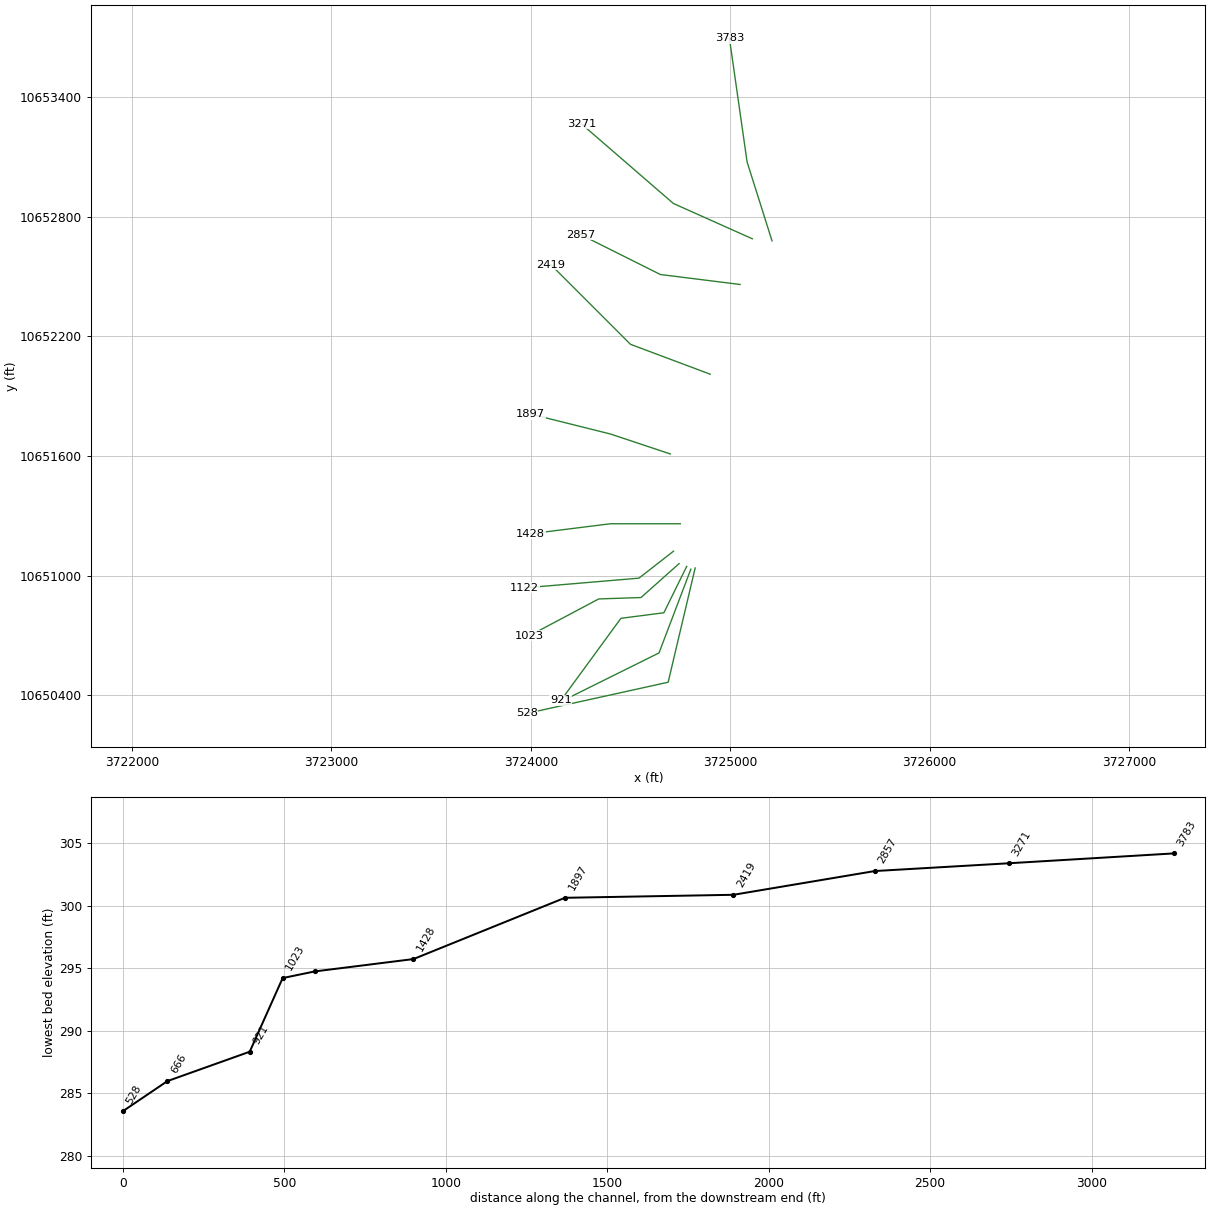
HEC-RAS study HARRISON LAKE.prj: HARRISON LAKE Base Level Engineering

--- HARRISON LAKE.g01 (geometry) --- (continued)

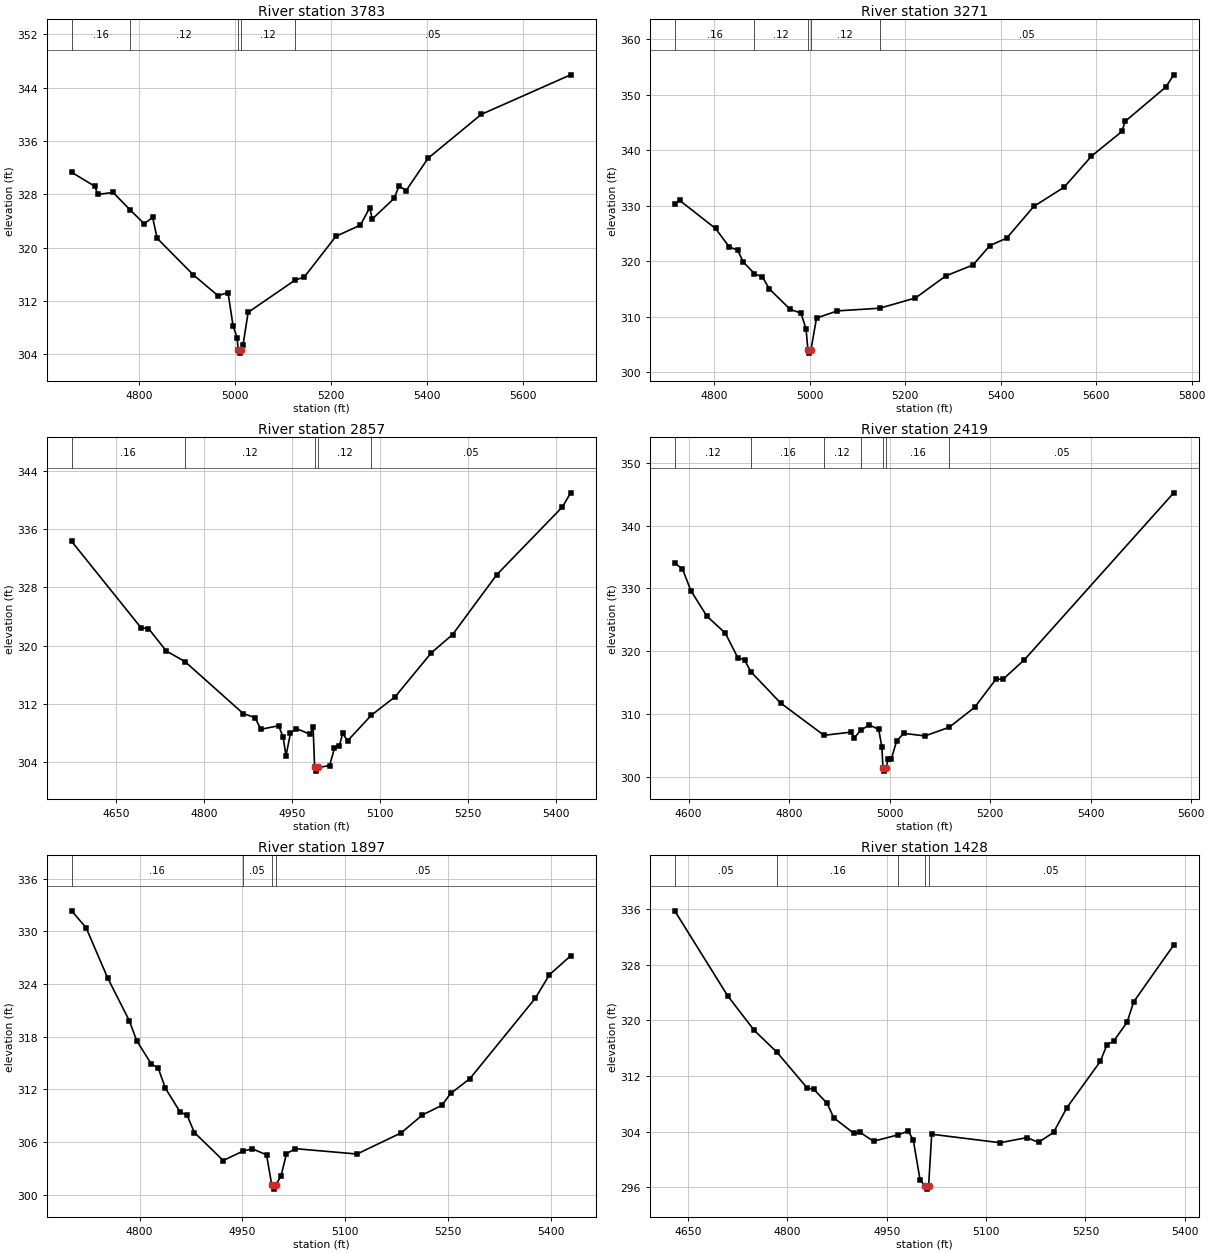
Type RM Length L Ch R = 1 ,3783    ,512,512,512
BEGIN DESCRIPTION:
HARRISON LAKE 8.0
END DESCRIPTION:
XS GIS Cut Line= 3
      3725209.55     10652678.98      3725084.54     10653074.84
        3724996.     10653694.62
#Sta/Elev= 30
  4658.5  331.32  4707.5  329.19  4712.8     328  4745.1  328.29  4780.4  325.69
  4809.8   323.6  4827.6  324.55  4836.9  321.42    4912  315.96  4963.9  312.81
  4984.9  313.26  4995.3   308.3  5003.8   306.5    5006  304.69  5008.8  304.19
    5012  304.69  5016.3  305.48  5026.8  310.31  5123.7  315.09  5144.3  315.64
  5209.9  321.71  5260.9  323.39  5280.6  326.01  5285.7   324.3  5331.6  327.42
  5341.7  329.28  5356.4  328.57  5402.3  333.43  5513.4  340.01  5699.7  345.94
#Mann= 5 ,-1 , 0
  4658.5     .16       0  4780.4     .12       0    5006     .07       0
    5012     .12       0  5123.7     .05       0
Bank Sta=5006,5012
XS Rating Curve= 0 ,0
Exp/Cntr=0.3,0.1

Type RM Length L Ch R = 1 ,3271    ,414,414,414
BEGIN DESCRIPTION:
HARRISON LAKE 7.0
END DESCRIPTION:
XS GIS Cut Line= 3
      3725110.62     10652689.41      3724714.75     10652866.51
      3724252.59     10653266.35
#Sta/Elev= 30
  4717.7  330.32  4728.1  330.94  4803.1  325.88  4831.8  322.56  4849.5  321.97
  4861.2  319.83  4884.7  317.74  4901.4  317.12    4916  314.96  4959.8  311.27
    4982  310.62  4992.7  307.71  4996.7   303.9  4999.4   303.4  5002.7   303.9
  5014.6  309.72  5058.4  311.02  5146.8   311.5  5221.7  313.34  5285.4  317.33
  5342.4  319.31  5377.5   322.8  5412.6  324.13  5469.6  329.86  5533.2  333.34
  5590.3  338.93  5653.9  343.37  5660.7  345.19    5746   351.4  5762.5  353.59
#Mann= 5 ,-1 , 0
  4717.7     .16       0  4884.7     .12       0  4996.7     .07       0
  5002.7     .12       0  5146.8     .05       0
Bank Sta=4996.7,5002.7
XS Rating Curve= 0 ,0
Exp/Cntr=0.3,0.1

Type RM Length L Ch R = 1 ,2857    ,438,438,438
BEGIN DESCRIPTION:
HARRISON LAKE 6.0
END DESCRIPTION:
XS GIS Cut Line= 3
      3725049.63     10652460.19      3724649.61     10652510.19
      3724249.65     10652710.17
#Sta/Elev= 30
  4574.3  334.32  4692.7  322.45  4705.3  322.35  4735.6  319.27  4767.4  317.82
  4866.6  310.69  4886.7  310.13  4896.8  308.52    4927  309.01  4934.6  307.49
  4939.6  304.89  4947.2  307.99  4957.3  308.63  4980.2  307.85  4985.8  308.83
  4988.4  303.28  4991.2  302.78  4994.4  303.28  5013.8  303.54  5022.2  305.92
  5030.5  306.25  5036.1  307.97  5044.5  306.94  5084.7  310.43  5125.6  312.99
  5187.1  319.01  5223.4  321.52  5298.9  329.76  5410.7  339.05  5424.6  340.98
#Mann= 5 ,-1 , 0
  4574.3     .16       0  4767.4     .12       0  4988.4     .07       0
  4994.4     .12       0  5084.7     .05       0
Bank Sta=4988.4,4994.4
XS Rating Curve= 0 ,0
Exp/Cntr=0.3,0.1

Type RM Length L Ch R = 1 ,2419    ,522,522,522
BEGIN DESCRIPTION:
HARRISON LAKE 5.0
END DESCRIPTION:
XS GIS Cut Line= 3
      3724899.63     10652010.18      3724499.61     10652160.19
      3724099.61     10652560.19
#Sta/Elev= 30
  4572.4  333.98  4587.5  333.17  4604.5  329.64  4636.5  325.56    4673  322.88
  4697.9  318.96  4711.3  318.61  4723.7  316.73  4783.3  311.72  4869.4  306.59
    4924   307.1  4929.3  306.13  4942.3  307.39  4959.6  308.23  4978.3  307.53
  4984.5  304.73  4986.8  301.38  4989.6  300.88  4992.8  301.38  4996.9  302.78
  5003.2  302.78  5013.8  305.66  5027.9   306.9  5070.3  306.49  5118.6  307.87
  5169.3  311.06  5211.7  315.55  5225.9  315.54  5268.3  318.64  5565.3  345.23
#Mann= 7 ,-1 , 0
  4572.4     .12       0  4723.7     .16       0  4869.4     .12       0
  4942.3     .16       0  4986.8     .07       0  4992.8     .16       0
  5118.6     .05       0
Bank Sta=4986.8,4992.8
XS Rating Curve= 0 ,0
Exp/Cntr=0.3,0.1

Type RM Length L Ch R = 1 ,1897    ,469,469,469
BEGIN DESCRIPTION:
HARRISON LAKE 4.0
END DESCRIPTION:
XS GIS Cut Line= 3
       3724699.6     10651610.19      3724399.61     10651710.19
      3723999.64     10651810.18
#Sta/Elev= 30
  4700.7  332.35  4721.8  330.43  4753.4  324.69    4785  319.82  4795.6  317.57
  4816.6  314.95  4827.2  314.41  4837.7  312.12  4858.8  309.46  4869.3  309.05
  4879.9  307.09    4922   303.9  4950.3  304.95  4964.2  305.24  4985.3  304.55
  4992.8  301.14  4995.6  300.64  4998.8  301.14  5006.4  302.13  5014.3  304.67
  5027.2  305.25  5117.4  304.64  5181.8  307.05  5212.8  309.09  5241.1  310.18
    5254  311.54  5282.3  313.24  5377.7   322.4  5398.3  325.07  5429.2  327.22
#Mann= 4 ,-1 , 0
  4700.7     .16       0  4950.3     .05       0  4992.8     .03       0
  4998.8     .05       0
Bank Sta=4992.8,4998.8
XS Rating Curve= 0 ,0
Exp/Cntr=0.3,0.1

Type RM Length L Ch R = 1 ,1428    ,306,306,306
BEGIN DESCRIPTION:
HARRISON LAKE 3.0
END DESCRIPTION:
XS GIS Cut Line= 3
      3724749.61     10651260.19      3724399.61     10651260.19
      3723999.63     10651210.19
#Sta/Elev= 30
  4630.2  335.74  4710.2  323.51  4750.2  318.56  4784.5  315.41  4830.2  310.27
  4840.2  310.09  4860.2  308.07  4870.2  305.99  4900.2  303.79  4910.2  303.88
  4930.2  302.62  4967.6  303.55  4982.7  304.09  4990.3  302.76  5000.4   297.1
  5007.4  296.24  5010.2  295.74  5013.4  296.24    5018  303.63  5121.3  302.41
  5161.6  303.14  5179.2  302.47  5201.9  303.89  5222.1  307.46  5272.5   314.1
  5282.5  316.49  5292.6  317.01  5312.8  319.72  5322.9  322.67  5383.3  330.83
#Mann= 5 ,-1 , 0
  4630.2     .05       0  4784.5     .16       0  4967.6     .05       0
  5007.4     .03       0  5013.4     .05       0
Bank Sta=5007.4,5013.4
XS Rating Curve= 0 ,0
Exp/Cntr=0.3,0.1

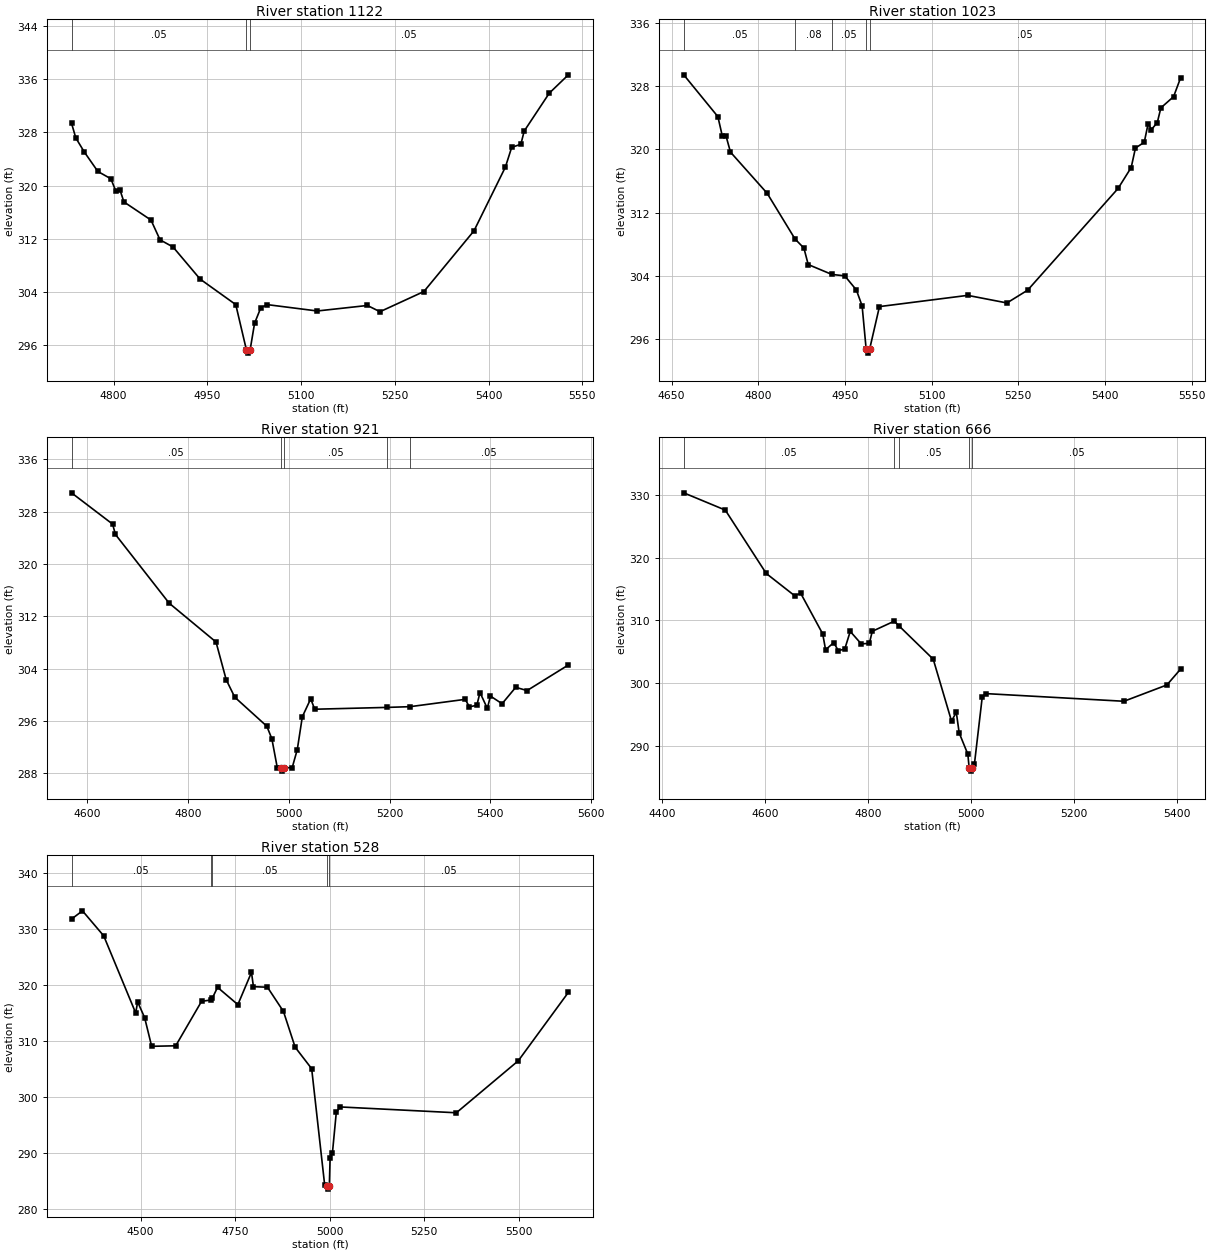
Type RM Length L Ch R = 1 ,1122    ,99,99,99
BEGIN DESCRIPTION:
Mapping XS 24c11969
END DESCRIPTION:
XS GIS Cut Line= 3
      3724715.76     10651122.78      3724542.13     10650987.35
      3723969.19     10650938.74
#Sta/Elev= 30
  4732.5  329.39  4739.4  327.17    4753  325.05  4774.7  322.12  4795.5  321.02
  4803.6  319.12    4810  319.36  4816.4  317.53  4859.7   314.8  4874.2  311.82
    4895  310.74  4938.4   305.9  4995.4  302.06  5012.4  295.25  5015.2  294.75
  5018.4  295.25  5025.5  299.25  5035.5  301.59  5045.6  302.06  5125.8   301.1
  5206.1  301.93  5226.2  300.99  5296.5  304.03  5376.7  313.18  5426.9  322.77
    5437  325.75  5451.7  326.22    5457   328.2  5497.2  333.92  5527.7  336.68
#Mann= 3 ,-1 , 0
  4732.5     .05       0  5012.4     .03       0  5018.4     .05       0
Bank Sta=5012.4,5018.4
XS Rating Curve= 0 ,0
Exp/Cntr=0.3,0.1

Type RM Length L Ch R = 1 ,1023    ,102,102,102
BEGIN DESCRIPTION:
HARRISON LAKE 2.0
END DESCRIPTION:
XS GIS Cut Line= 4
      3724743.54     10651060.29      3724552.55     10650890.13
      3724340.74     10650883.18      3723994.04     10650699.43
#Sta/Elev= 30
  4670.9  329.44    4730  324.15  4737.6  321.72  4744.3  321.65  4751.8  319.66
  4815.3  314.45  4863.6  308.66  4878.9  307.52  4886.4  305.43  4927.3  304.18
  4949.6     304  4969.7  302.22  4979.7   300.2  4986.7  294.72  4989.4  294.22
  4992.7  294.72  5009.7  300.11  5162.5  301.53  5230.4  300.57  5266.3  302.19
  5422.8  315.06  5445.5  317.71  5452.9  320.18  5468.1   320.9  5474.9  323.28
  5480.5  322.51  5490.7   323.4  5496.9  325.26  5518.9  326.68    5531  329.05
#Mann= 5 ,-1 , 0
  4670.9     .05       0  4863.6     .08       0  4927.3     .05       0
  4986.7     .04       0  4992.7     .05       0
Bank Sta=4986.7,4992.7
XS Rating Curve= 0 ,0
Exp/Cntr=0.3,0.1

Type RM Length L Ch R = 1 ,921     ,255,255,255
BEGIN DESCRIPTION:
Mapping XS 1a41164c
END DESCRIPTION:
XS GIS Cut Line= 4
      3724781.69     10651046.34      3724667.13     10650813.74
      3724451.85     10650785.96      3724150.65     10650373.97
#Sta/Elev= 30
  4568.4  330.86    4650  326.08  4655.6   324.5  4762.3     314  4855.4  308.06
  4875.6   302.3  4892.6  299.63  4956.3  295.19  4966.3  293.27  4977.1  288.84
  4983.5  288.83  4986.3  288.33  4989.5  288.83  5006.7  288.87  5016.8  291.63
  5026.8  296.64  5043.4  299.38  5051.4  297.79  5195.7  298.07  5240.7  298.18
  5350.2   299.3  5358.7  298.15  5373.4   298.4  5379.6  300.34  5394.2  297.92
  5400.4   299.8  5423.5  298.63  5450.6  301.14  5473.1  300.64  5555.1  304.55
#Mann= 5 ,-1 , 0
  4568.4     .05       0  4983.5     .03       0  4989.5     .05       0
  5195.7     .08       0  5240.7     .05       0
Bank Sta=4983.5,4989.5
XS Rating Curve= 0 ,0
Exp/Cntr=0.3,0.1

Type RM Length L Ch R = 1 ,666     ,138,138,138
BEGIN DESCRIPTION:
Mapping XS 84aa13cd
END DESCRIPTION:
XS GIS Cut Line= 3
      3724802.56     10651032.52      3724642.83     10650612.35
      3724181.06      10650383.2
#Sta/Elev= 30
  4441.4  330.32  4522.1  327.57  4601.7  317.47  4656.6  313.94  4668.6  314.31
  4711.3  307.85  4716.9  305.32  4732.7  306.45  4741.6  305.19  4754.1  305.42
  4764.8  308.24  4786.2  306.25  4801.9  306.34  4807.6  308.26  4850.3  309.87
  4859.4  309.13    4926  303.81  4961.5  293.96  4970.8  295.35  4976.4  292.07
  4993.2  288.68  4995.8  286.48  4998.5  285.98  5001.8  286.48  5006.1  287.18
  5021.2   297.8  5028.5  298.33  5296.4  297.11  5379.8  299.71  5406.4  302.23
#Mann= 5 ,-1 , 0
  4441.4     .05       0  4850.3     .08       0  4859.4     .05       0
  4995.8     .03       0  5001.8     .05       0
Bank Sta=4995.8,5001.8
XS Rating Curve= 0 ,0
Exp/Cntr=0.3,0.1

Type RM Length L Ch R = 1 ,528     ,0,0,0
BEGIN DESCRIPTION:
HARRISON LAKE 1.0
END DESCRIPTION:
XS GIS Cut Line= 3
      3724824.13     10651038.41       3724688.7     10650465.46
      3723980.36     10650309.21
#Sta/Elev= 30
  4317.4  331.71  4346.4  333.18  4402.6  328.72  4487.2  314.96  4492.3  316.95
  4510.8  314.14  4529.4  309.03    4593  309.12  4661.4  317.05  4685.6  317.28
  4689.5  317.57  4703.7  319.54  4757.4  316.46  4793.4  322.21  4798.6  319.66
  4835.7  319.56    4878  315.24  4908.9  308.87  4952.6  305.04  4987.1  284.24
  4993.3  284.07    4996  283.57  4999.3  284.07  5001.4   289.2  5007.6  290.09
  5017.8  297.29  5028.1  298.22  5335.3  297.18  5499.1  306.45  5631.5  318.64
#Mann= 5 ,-1 , 0
  4317.4     .05       0  4685.6     .08       0  4689.5     .05       0
  4993.3     .03       0  4999.3     .05       0
Bank Sta=4993.3,4999.3
XS Rating Curve= 0 ,0
Exp/Cntr=0.3,0.1

Chan Stop Cuts=-1
Use User Specified Reach Order=0
Composite Channel Slope=5