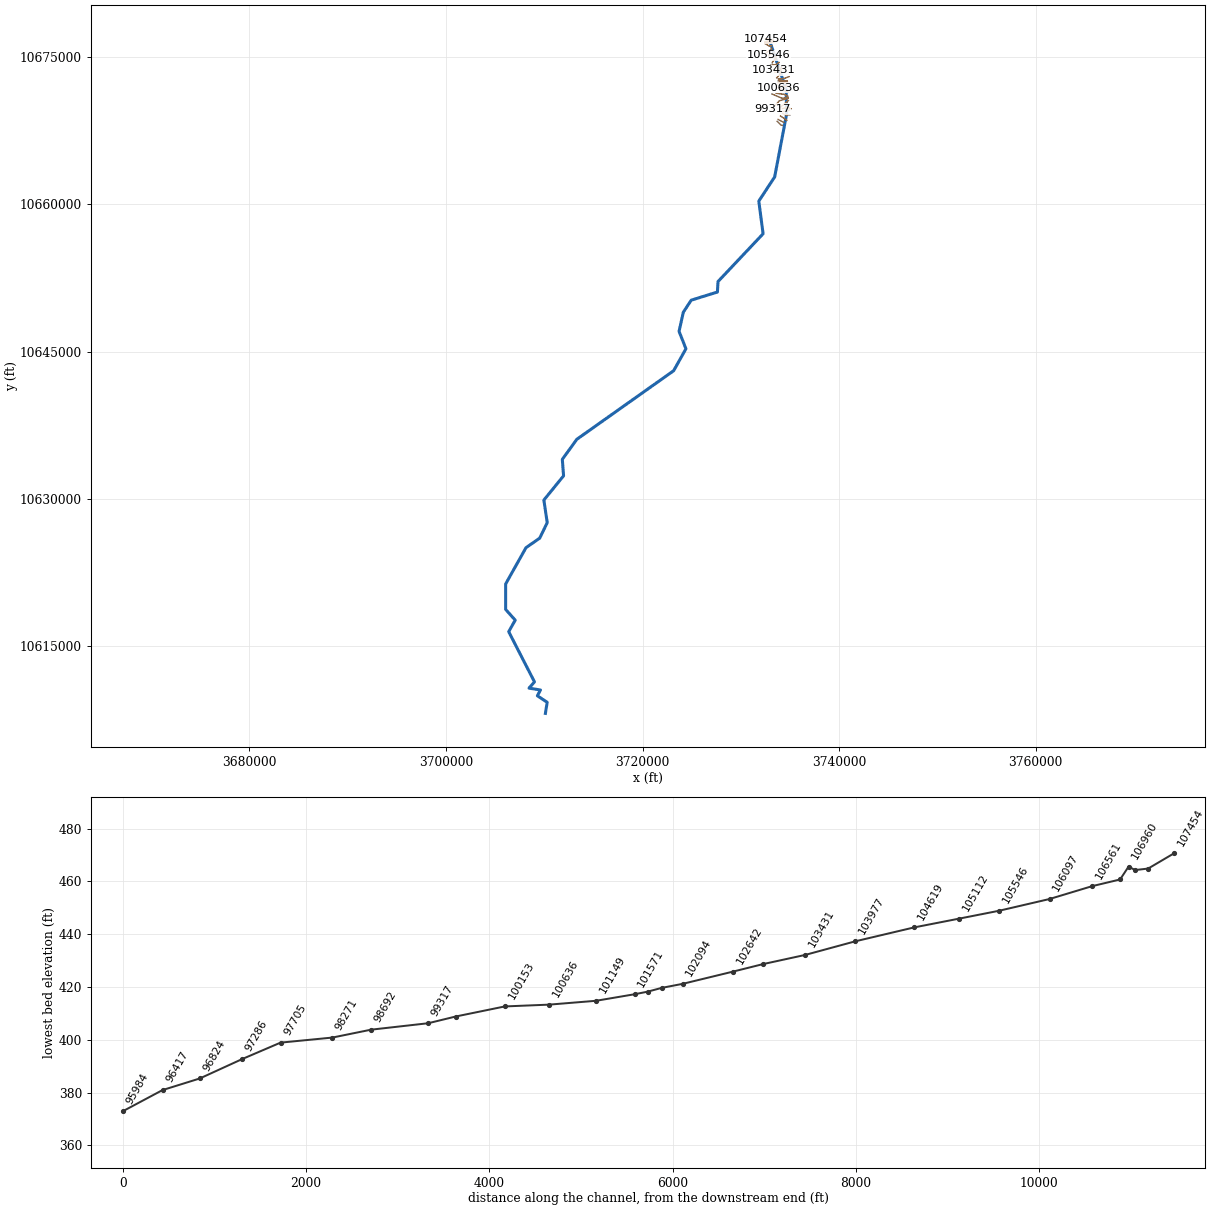
--- KEECHIE CREEK.prj (project) ---

Proj Title=KEECHIE CREEK Base Level Engineering
Current Plan=p01
Default Exp/Contr=0.3,0.1
English Units
Geom File=g01
Flow File=f01
Plan File=p01
Y Axis Title=Elevation
X Axis Title(PF)=Main Channel Distance
X Axis Title(XS)=Station
BEGIN DESCRIPTION:
KEECHIE CREEK
END DESCRIPTION:
DSS Export Rating Curves= 0
DSS Export Rating Curve Sorted= 0
DSS Export Volume Flow Curves= 0
DXF OffsetX= 0
DXF OffsetY= 0
DXF ScaleX= 1
DXF ScaleY= 10

--- KEECHIE CREEK.p01 (plan) ---

Plan Title=Multiple Run
Short Identifier=Multiple
Geom File=g01
Flow File=f01
Subcritical Flow
K Sum by GR= 0
Std Step Tol= 0.01
Critical Tol= 0.01
Num of Std Step Trials= 20
Max Error Tol= 0.3
Flow Tol Ratio= 0.001
Split Flow NTrial= 30
Split Flow Tol= 0.02
Split Flow Ratio= 0.02
Log Output Level= 0
Friction Slope Method= 1
Unsteady Friction Slope Method= 2
Unsteady Bridges Friction Slope Method= 1
Parabolic Critical Depth
Global Vel Dist=  1 , 1 , 1
Global Log Level= 0
CheckData=True
Encroach Param= -1, 0, 0, 0
BEGIN DESCRIPTION:
Multiple Run
END DESCRIPTION:

--- KEECHIE CREEK.f01 (steady flow) ---

Flow Title=Multiple
Program Version=4.10
Number of Profiles= 7
Profile Names=10-year,25-year,50-year,1pct_min,100-year,1pct_plu,500-year
River Rch & RM=KEECHIE CREEK,Reach-1         ,107454
     755    1052    1306    1193    1614    2183    2472
River Rch & RM=KEECHIE CREEK,Reach-1         ,106960
     852    1192    1482    1356    1833    2479    2815
River Rch & RM=KEECHIE CREEK,Reach-1         ,102094
    1465    2104    2663    2473    3345    4524    5301
River Rch & RM=KEECHIE CREEK,Reach-1         ,98271
    1615    2325    2947    2739    3705    5010    5882
River Rch & RM=KEECHIE CREEK,Reach-1         ,97705
    1615    2325    2947    2739    3705    5010    5882
River Rch & RM=KEECHIE CREEK,Reach-1         ,93738
    1738    2506    3180    2958    4000    5410    6358
River Rch & RM=KEECHIE CREEK,Reach-1         ,89365
    1968    2847    3620    3373    4561    6168    7274
River Rch & RM=KEECHIE CREEK,Reach-1         ,84427
    2045    2958    3760    3501    4735    6403    7544
River Rch & RM=KEECHIE CREEK,Reach-1         ,79759
    2256    3268    4157    3872    5236    7082    8347
River Rch & RM=KEECHIE CREEK,Reach-1         ,71833
    5204    7765   10083    9567   12938   17497   21394
River Rch & RM=KEECHIE CREEK,Reach-1         ,68013
    5313    7893   10219    9664   13069   17675   21468
River Rch & RM=KEECHIE CREEK,Reach-1         ,56563
    5619    8331   10769   10166   13748   18593   22499
River Rch & RM=KEECHIE CREEK,Reach-1         ,51523
    5619    8331   10769   10166   13748   18593   22499
River Rch & RM=KEECHIE CREEK,Reach-1         ,45519
    5601    8295   10715   10107   13668   18485   22332
River Rch & RM=KEECHIE CREEK,Reach-1         ,42212
    5835    8643   11166   10531   14242   19260   23265
River Rch & RM=KEECHIE CREEK,Reach-1         ,39610
    5821    8612   11116   10474   14165   19157   23097
River Rch & RM=KEECHIE CREEK,Reach-1         ,36064
    5815    8589   11075   10423   14096   19064   22931
River Rch & RM=KEECHIE CREEK,Reach-1         ,29606
    5711    8409   10817   10156   13735   18575   22236
River Rch & RM=KEECHIE CREEK,Reach-1         ,20796
    5758    8476   10903   10236   13843   18721   22406
River Rch & RM=KEECHIE CREEK,Reach-1         ,16332
    5742    8446   10858   10188   13778   18633   22274
River Rch & RM=KEECHIE CREEK,Reach-1         ,12828
    6271    9232   11875   11145   15072   20384   24378
River Rch & RM=KEECHIE CREEK,Reach-1         ,10625
    6271    9232   11875   11145   15072   20384   24378
River Rch & RM=KEECHIE CREEK,Reach-1         ,4674
   10859   16172   20980   19844   26837   36294   44047
Boundary for River Rch & Prof#=KEECHIE CREEK,Reach-1         , 1
Up Type= 0
Dn Type= 3
Dn Slope=0.005
Boundary for River Rch & Prof#=KEECHIE CREEK,Reach-1         , 2
Up Type= 0
Dn Type= 3
Dn Slope=0.005
Boundary for River Rch & Prof#=KEECHIE CREEK,Reach-1         , 3
Up Type= 0
Dn Type= 3
Dn Slope=0.005
Boundary for River Rch & Prof#=KEECHIE CREEK,Reach-1         , 4
Up Type= 0
Dn Type= 3
Dn Slope=0.005
Boundary for River Rch & Prof#=KEECHIE CREEK,Reach-1         , 5
Up Type= 0
Dn Type= 3
Dn Slope=0.005
Boundary for River Rch & Prof#=KEECHIE CREEK,Reach-1         , 6
Up Type= 0
Dn Type= 3
Dn Slope=0.005
Boundary for River Rch & Prof#=KEECHIE CREEK,Reach-1         , 7
Up Type= 0
Dn Type= 3
Dn Slope=0.005
DSS Import GetInterval= 0
DSS Import GetPeak= 0
DSS Import FillOption= 0

--- KEECHIE CREEK.g01 (geometry) ---

Geom Title=Existing Conditions
Program Version=4.10

River Reach=KEECHIE CREEK   ,Reach-1
Reach XY= 30
      3732851.84      10676900.2      3734619.07     10671705.98
      3734656.75       10669174.      3733445.25       10662793.
      3731831.25       10660335.      3732267.75       10657006.
       3727680.5       10652140.      3727622.25       10651075.
      3724956.75       10650245.      3724152.75       10649019.
        3723719.       10647067.      3724417.75       10645296.
      3723165.75       10643058.       3713317.5       10636077.
       3711841.5       10634035.      3711967.75       10632356.
        3709963.       10629889.        3710306.       10627585.
       3709539.5       10626010.      3708145.75       10625041.
      3706074.25       10621343.      3706073.25       10618752.
      3707048.75       10617660.        3706385.       10616487.
      3709008.75       10611373.      3708451.25       10610736.
      3709618.75       10610547.        3709300.       10609960.
        3710300.       10609295.        3710120.       10608166.

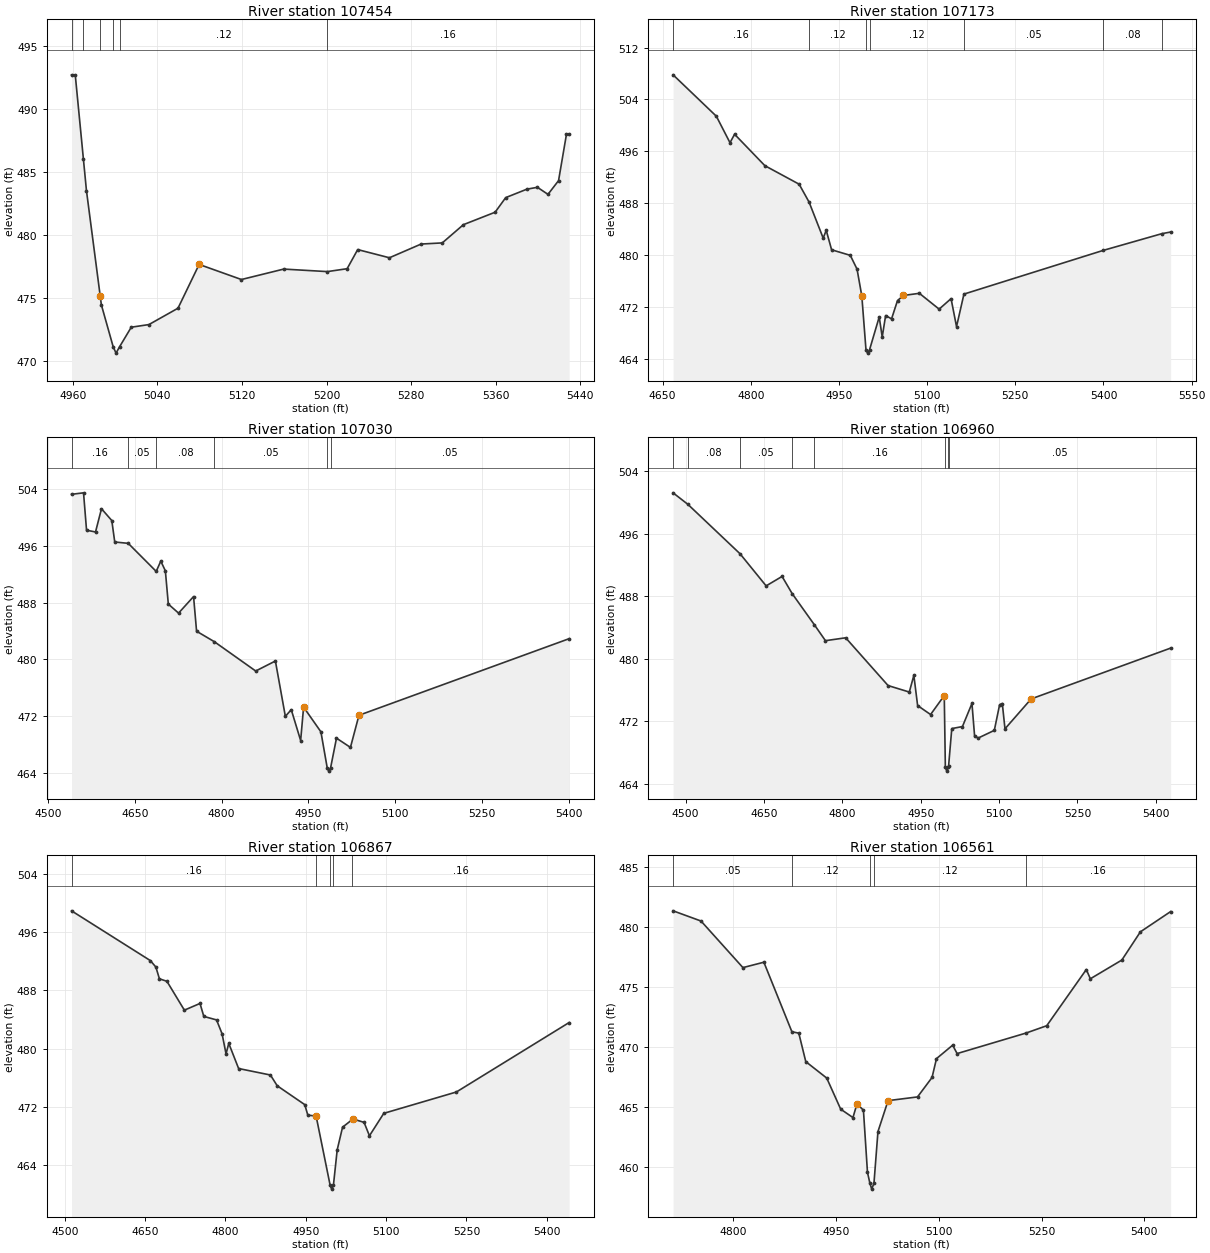
Type RM Length L Ch R = 1 ,107454  ,281,281,281
BEGIN DESCRIPTION:
KEECHIE CREEK 178.0
END DESCRIPTION:
XS GIS Cut Line= 3
      3732949.58     10676910.16      3732899.61     10676860.19
      3732499.58     10676860.19
#Sta/Elev= 30
  4958.8  492.71  4962.3  492.71    4970  486.03  4972.9  483.51  4985.9  475.14
    4987  474.43  4998.2  471.09  5000.9  470.59  5004.2  471.09  5015.3  472.65
    5032  472.86  5059.5  474.16  5079.5  477.64  5119.5  476.44  5159.5  477.27
  5200.8  477.07  5219.5   477.3  5229.5  478.82  5259.5  478.17  5289.5  479.26
  5309.5  479.35  5329.5   480.8  5359.5  481.79  5369.5  482.95  5389.5  483.62
  5399.5  483.77  5409.5  483.21  5419.5   484.3    5427  487.99  5429.5  487.99
#Mann= 6 ,-1 , 0
  4958.8     .12       0    4970     .16       0  4985.9     .12       0
  4998.2     .07       0  5004.2     .12       0  5200.8     .16       0
Bank Sta=4985.9,5079.5
XS Rating Curve= 0 ,0
Exp/Cntr=0.3,0.1

Type RM Length L Ch R = 1 ,107173  ,143,143,143
BEGIN DESCRIPTION:
Mapping XS 8d572631
END DESCRIPTION:
XS GIS Cut Line= 4
      3733280.93     10676748.42      3732980.58     10676672.03
      3732754.89     10676637.31      3732452.83     10676576.89
#Sta/Elev= 30
    4668   507.8  4741.6  501.41  4764.8  497.32  4772.6  498.63  4824.1  493.78
  4882.4  490.92  4899.3  488.16  4923.3   482.6  4928.5   483.8  4937.6   480.8
  4969.4  479.94  4980.9  477.81    4989  473.67  4996.1  465.35  4998.9  464.85
  5002.1  465.35  5018.6  470.43  5023.7  467.34  5029.5  470.65  5039.6  470.14
  5049.7  472.96  5059.8  473.75  5086.9  474.08  5120.5  471.64  5140.8  473.26
  5150.1  468.94  5162.7  473.96  5399.4   480.7  5499.5  483.29  5514.3  483.54
#Mann= 7 ,-1 , 0
    4668     .16       0  4899.3     .12       0  4996.1     .07       0
  5002.1     .12       0  5162.7     .05       0  5399.4     .08       0
  5499.5     .05       0
Bank Sta=4989,5059.8
XS Rating Curve= 0 ,0
Exp/Cntr=0.3,0.1

Type RM Length L Ch R = 1 ,107030  ,70,70,70
BEGIN DESCRIPTION:
Mapping XS 58bcc6cd
END DESCRIPTION:
XS GIS Cut Line= 3
      3733300.08     10676680.72      3732852.11     10676581.75
      3732458.06     10676510.58
#Sta/Elev= 30
  4540.9  503.24  4561.6  503.45  4566.8  498.19  4582.3  497.94  4592.6  501.21
  4610.4  499.55  4615.5  496.53  4638.8  496.34  4687.1  492.39    4695  493.84
  4702.9  492.47    4708  487.79  4725.7  486.52  4751.6  488.85  4756.8  483.97
  4787.6  482.49  4858.9  478.37  4892.9  479.78  4910.1  471.99  4920.3  472.93
  4936.5  468.59  4941.6  473.29  4971.5  469.81  4982.3  464.78    4985  464.28
  4988.3  464.78  4998.4  468.92  5022.5  467.62  5037.2  472.14  5400.1  482.92
#Mann= 6 ,-1 , 0
  4540.9     .16       0  4638.8     .05       0  4687.1     .08       0
  4787.6     .05       0  4982.3     .04       0  4988.3     .05       0
Bank Sta=4941.6,5037.2
XS Rating Curve= 0 ,0
Exp/Cntr=0.3,0.1

Type RM Length L Ch R = 1 ,106960  ,93,93,93
BEGIN DESCRIPTION:
Mapping XS e8d49280
END DESCRIPTION:
XS GIS Cut Line= 4
      3733385.11     10676604.32      3732923.29     10676524.46
      3732725.38       10676488.      3732445.83     10676448.07
#Sta/Elev= 30
  4476.2  501.26  4504.6  499.78  4604.4  493.45  4654.3  489.34  4684.8  490.55
  4704.1  488.35  4746.6  484.36  4767.8  482.32  4806.5  482.69  4887.7  476.57
  4928.3  475.74    4937  477.88  4944.2  474.01    4969  472.86  4995.2  475.29
  4997.3  466.11    5000  465.61  5003.3  466.11  5003.5  466.27  5009.6  471.06
    5030  471.32  5048.2  474.28  5053.3  470.07  5060.5  469.86    5091  470.83
  5101.1  474.11  5106.3  474.27  5111.4  471.03  5161.5  474.86  5428.5  481.37
#Mann= 8 ,-1 , 0
  4476.2     .05       0  4504.6     .08       0  4604.4     .05       0
  4704.1     .08       0  4746.6     .16       0  4997.3     .07       0
  5003.3     .16       0  5003.5     .05       0
Bank Sta=4995.2,5161.5
XS Rating Curve= 0 ,0
Exp/Cntr=0.3,0.1

Type RM Length L Ch R = 1 ,106867  ,306,306,306
BEGIN DESCRIPTION:
Mapping XS 922c5463
END DESCRIPTION:
XS GIS Cut Line= 4
      3733362.53     10676534.88      3732933.71     10676428.97
      3732718.43     10676408.14      3732447.58     10676394.25
#Sta/Elev= 30
  4512.6  498.91  4659.8  492.08  4670.1  491.19  4676.7  489.58  4690.7  489.24
  4723.3  485.28  4752.5   486.2  4759.6  484.42  4783.4  483.94  4793.7  482.04
  4801.1  479.28  4806.2  480.72  4824.6  477.27    4884  476.38  4896.7   474.9
  4948.2  472.31  4953.8  470.87  4969.3  470.75  4995.6  461.22  4998.4  460.72
  5001.6  461.22  5008.7  466.11  5018.7  469.22  5037.1  470.28  5038.8  470.33
  5058.9  469.88  5068.9  468.04  5095.7  471.12  5231.3  474.05  5441.8  483.58
#Mann= 5 ,-1 , 0
  4512.6     .16       0  4969.3     .12       0  4995.6     .07       0
  5001.6     .12       0  5037.1     .16       0
Bank Sta=4969.3,5038.8
XS Rating Curve= 0 ,0
Exp/Cntr=0.3,0.1

Type RM Length L Ch R = 1 ,106561  ,464,464,464
BEGIN DESCRIPTION:
KEECHIE CREEK 176.0
END DESCRIPTION:
XS GIS Cut Line= 3
      3733149.66      10676160.2      3732899.61     10676110.19
      3732499.61     10676360.19
#Sta/Elev= 30
  4711.8  481.36  4752.6  480.51  4813.8  476.63  4844.4  477.08  4885.3  471.29
  4895.4  471.17  4905.6   468.8  4936.2  467.43  4956.6  464.84  4974.5  464.14
  4980.4  465.29  4989.8  464.75  4995.7  459.58  4999.2  458.68  5001.9  458.18
  5005.2  458.68    5011  462.97  5025.8  465.55  5068.8  465.86    5090  467.48
  5096.5  469.05  5120.1  470.17  5126.6  469.47  5227.3  471.18  5257.5  471.79
  5315.3  476.47  5321.2   475.7  5367.2  477.26  5394.3  479.61  5438.5   481.3
#Mann= 5 ,-1 , 0
  4711.8     .05       0  4885.3     .12       0  4999.2     .07       0
  5005.2     .12       0  5227.3     .16       0
Bank Sta=4980.4,5025.8
XS Rating Curve= 0 ,0
Exp/Cntr=0.3,0.1

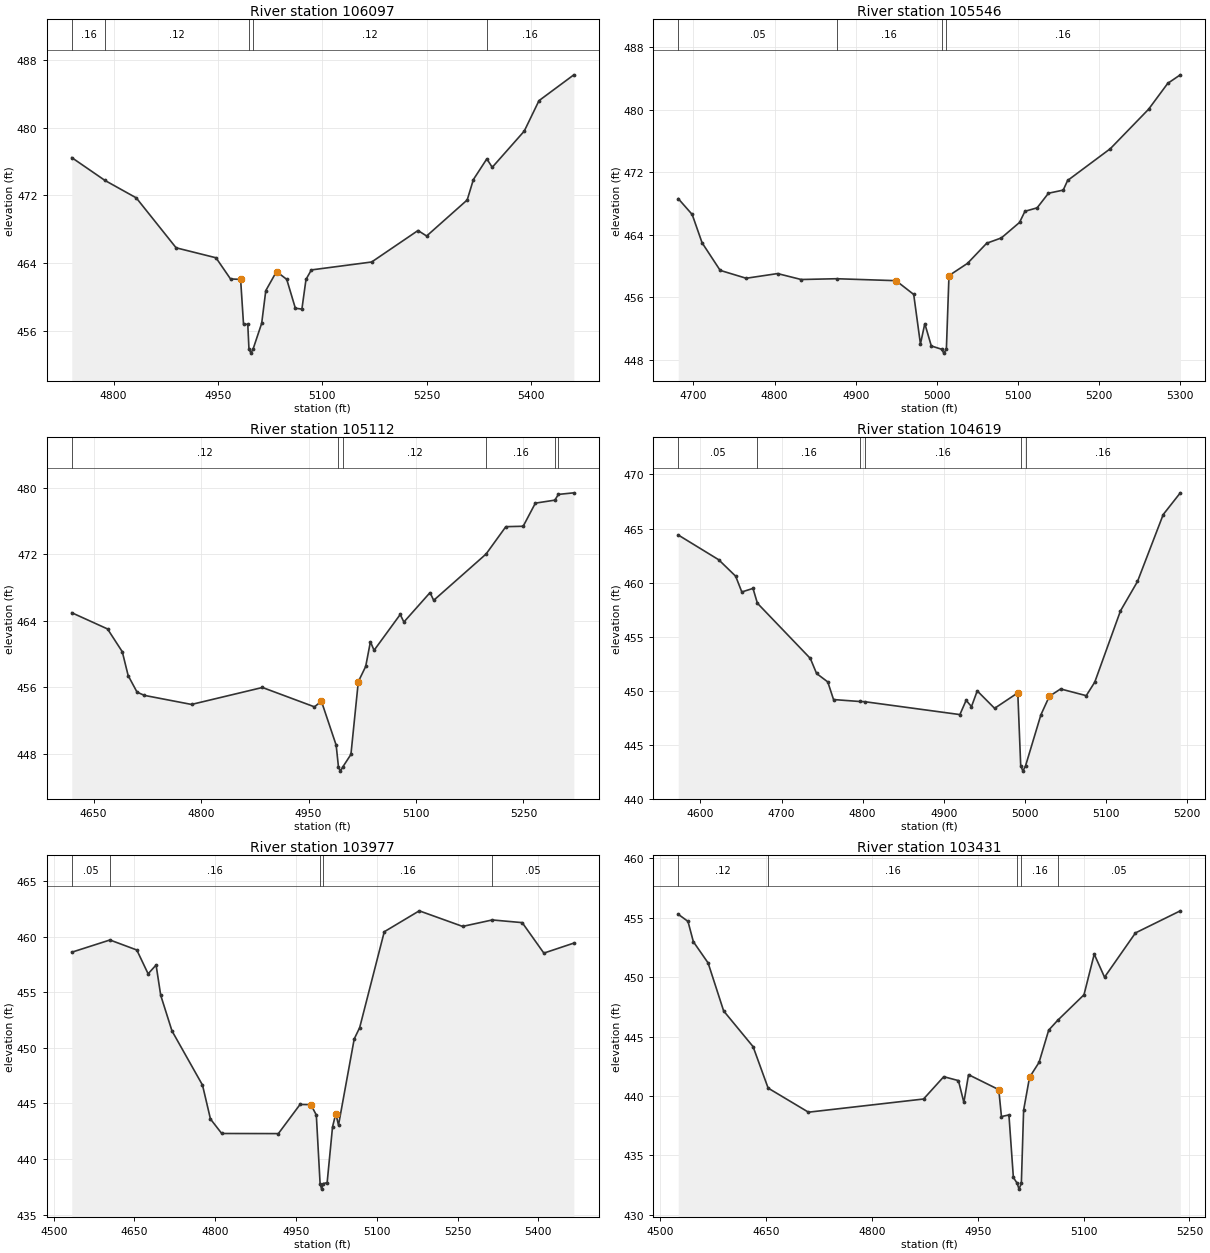
Type RM Length L Ch R = 1 ,106097  ,551,551,551
BEGIN DESCRIPTION:
KEECHIE CREEK 175.0
END DESCRIPTION:
XS GIS Cut Line= 3
      3733149.63     10675910.22      3732999.61     10675710.19
      3732599.64     10675460.21
#Sta/Elev= 30
    4740  476.49  4787.8  473.78  4832.7  471.72    4890   465.8  4947.3  464.62
  4968.2  462.11  4982.7  462.06  4986.9  456.73    4993  456.73  4994.7  453.82
  4997.5  453.32  5000.7  453.82    5013  456.86  5018.9  460.73  5034.3  462.99
    5049  462.06  5061.4  458.64  5070.8  458.54  5076.7  462.06  5084.4  463.18
  5171.1  464.12  5237.7  467.85  5250.1   467.2  5308.4  471.47  5317.3  473.89
  5336.6  476.34  5344.4  475.34  5390.4  479.63  5411.6  483.24  5461.7   486.3
#Mann= 5 ,-1 , 0
    4740     .16       0  4787.8     .12       0  4994.7     .07       0
  5000.7     .12       0  5336.6     .16       0
Bank Sta=4982.7,5034.3
XS Rating Curve= 0 ,0
Exp/Cntr=0.3,0.1

Type RM Length L Ch R = 1 ,105546  ,434,434,434
BEGIN DESCRIPTION:
KEECHIE CREEK 174.0
END DESCRIPTION:
XS GIS Cut Line= 2
      3733386.68     10675433.56      3732817.18     10675190.48
#Sta/Elev= 30
  4681.2  468.64  4698.4  466.61  4710.6  462.99  4732.9  459.46    4765  458.45
  4803.7  459.05  4832.8  458.29  4876.5  458.39  4949.8  458.14  4971.6  456.38
  4979.9  450.04  4985.3  452.64  4993.3  449.79  5005.9  449.37  5008.7  448.87
  5011.9  449.37  5015.1  458.79    5038  460.36  5061.6  462.93  5079.7  463.61
  5102.1  465.59  5108.8  467.02  5123.8  467.46  5137.8  469.33    5156  469.73
  5161.4  470.96  5214.1  475.03  5261.3  480.08  5284.9  483.39  5300.4  484.48
#Mann= 4 ,-1 , 0
  4681.2     .05       0  4876.5     .16       0  5005.9     .07       0
  5011.9     .16       0
Bank Sta=4949.8,5015.1
XS Rating Curve= 0 ,0
Exp/Cntr=0.3,0.1

Type RM Length L Ch R = 1 ,105112  ,493,493,493
BEGIN DESCRIPTION:
KEECHIE CREEK 173.0
END DESCRIPTION:
XS GIS Cut Line= 2
      3733588.05     10675044.66      3732907.46     10674877.98
#Sta/Elev= 30
  4619.6  464.95  4669.5     463  4690.1  460.26  4698.3  457.39  4710.7   455.4
  4720.9  455.01  4786.7  453.92  4885.7  455.96  4958.3  453.63    4968  454.31
  4988.6  449.02  4991.8   446.4  4994.5   445.9  4997.8   446.4  5009.2  447.91
  5019.5  456.66  5029.8  458.49  5036.4  461.46  5041.5  460.43    5078  464.74
  5083.1  463.83  5119.6  467.37  5124.7  466.44  5197.8  472.01  5225.4   475.3
  5249.6  475.35  5266.6  478.13  5293.8  478.49  5298.7  479.18  5320.3  479.37
#Mann= 6 ,-1 , 0
  4619.6     .12       0  4991.8     .07       0  4997.8     .12       0
  5197.8     .16       0  5293.8     .12       0  5298.7     .05       0
Bank Sta=4968,5019.5
XS Rating Curve= 0 ,0
Exp/Cntr=0.3,0.1

Type RM Length L Ch R = 1 ,104619  ,642,642,642
BEGIN DESCRIPTION:
KEECHIE CREEK 172.0
END DESCRIPTION:
XS GIS Cut Line= 3
      3733599.58     10674860.16      3733249.61     10674560.19
      3733199.59     10674410.14
#Sta/Elev= 30
  4572.6   464.4  4622.5  462.11  4643.4  460.59    4651  459.13  4664.8  459.46
  4670.2  458.09  4735.5  452.98  4743.2  451.59    4757  450.81  4764.1  449.18
  4796.4     449  4802.7  448.98  4919.9  447.79  4927.6  449.11  4934.2  448.53
  4941.3  449.98  4962.7  448.37  4991.3   449.8  4994.9  443.06  4997.6  442.56
  5000.9  443.06  5019.8  447.77  5030.2  449.48  5044.1  450.16  5075.7  449.54
  5086.2  450.79  5117.9  457.38  5138.9   460.1  5170.6  466.29  5191.7   468.3
#Mann= 6 ,-1 , 0
  4572.6     .05       0  4670.2     .16       0  4796.4     .12       0
  4802.7     .16       0  4994.9     .07       0  5000.9     .16       0
Bank Sta=4991.3,5030.2
XS Rating Curve= 0 ,0
Exp/Cntr=0.3,0.1

Type RM Length L Ch R = 1 ,103977  ,546,546,546
BEGIN DESCRIPTION:
KEECHIE CREEK 171.0
END DESCRIPTION:
XS GIS Cut Line= 3
      3733895.04     10674453.63      3733589.47     10674238.34
      3733034.27     10674175.88
#Sta/Elev= 30
  4533.5  458.59  4604.4  459.69  4654.3  458.79  4675.3  456.65  4690.1  457.44
  4698.7  454.72  4719.6  451.52  4776.3  446.65  4791.1   443.6    4812   442.3
  4917.2  442.29  4957.5  444.91  4977.6  444.89  4987.7  443.96  4994.7   437.8
  4997.5   437.3  5000.7   437.8  5007.8  437.88  5017.8  442.89  5023.9  444.09
  5028.9  443.05  5058.1   450.8  5068.2  451.81  5113.9  460.43  5178.9  462.31
  5259.4  460.91  5314.5  461.49  5370.1  461.25  5410.3  458.51    5466  459.41
#Mann= 5 ,-1 , 0
  4533.5     .05       0  4604.4     .16       0  4994.7     .07       0
  5000.7     .16       0  5314.5     .05       0
Bank Sta=4977.6,5023.9
XS Rating Curve= 0 ,0
Exp/Cntr=0.3,0.1

Type RM Length L Ch R = 1 ,103431  ,463,463,463
BEGIN DESCRIPTION:
KEECHIE CREEK 170.0
END DESCRIPTION:
XS GIS Cut Line= 3
      3733849.64     10674110.22      3733499.61     10673810.19
      3733299.63      10673660.2
#Sta/Elev= 30
    4526   455.3  4539.8   454.7  4547.4  452.99  4568.3   451.2  4590.3  447.16
    4632  444.15  4653.3  440.66  4710.4  438.63  4873.4  439.74    4902  441.62
  4922.8  441.29  4930.5  439.45  4937.1  441.79  4979.9  440.53  4983.7  438.26
  4994.3   438.4  5000.6  433.13  5005.9  432.65  5008.6  432.15  5011.9  432.65
  5015.1   438.8  5023.5  441.57    5037  442.83  5050.6  445.54  5063.2  446.36
  5100.6  448.52  5115.1  451.94  5129.7     450  5173.5  453.73    5237  455.59
#Mann= 5 ,-1 , 0
    4526     .12       0  4653.3     .16       0  5005.9     .07       0
  5011.9     .16       0  5063.2     .05       0
Bank Sta=4979.9,5023.5
XS Rating Curve= 0 ,0
Exp/Cntr=0.3,0.1

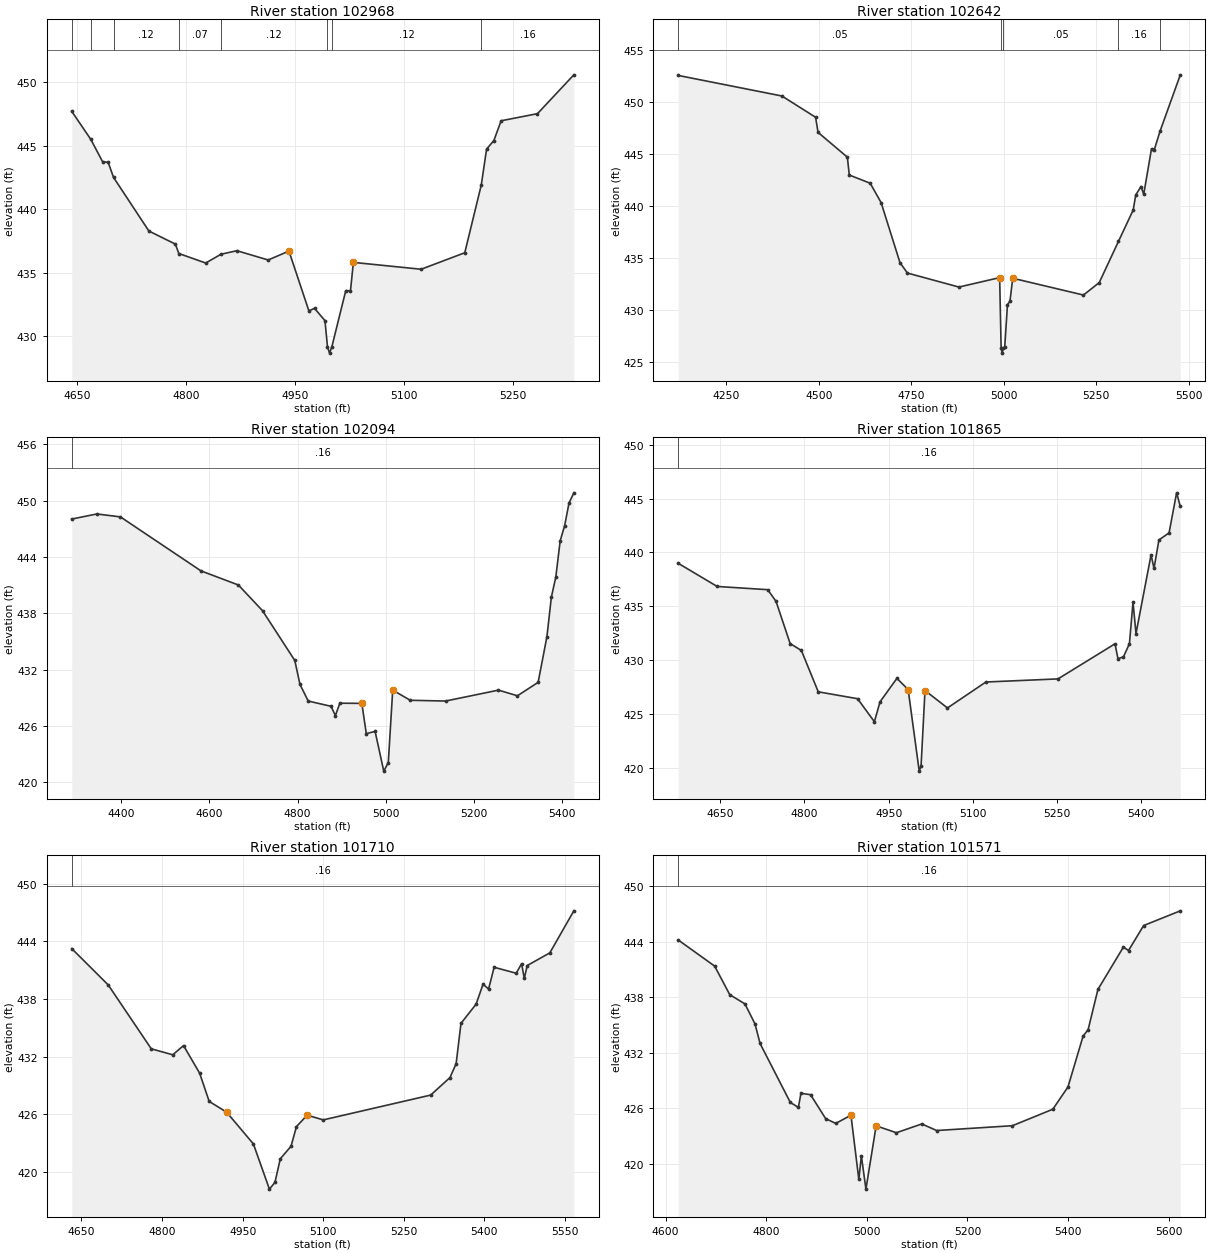
Type RM Length L Ch R = 1 ,102968  ,326,326,326
BEGIN DESCRIPTION:
KEECHIE CREEK 169.0
END DESCRIPTION:
XS GIS Cut Line= 3
      3733999.61     10673760.18      3733749.61     10673460.19
      3733449.62     10673460.19
#Sta/Elev= 30
    4643   447.7  4669.2  445.49  4685.3  443.74  4693.1  443.68  4700.4   442.5
  4749.1  438.27  4785.5  437.24  4790.2   436.5  4827.2  435.75  4848.2  436.44
  4870.1  436.72  4913.1  435.99  4941.7  436.69  4969.1  431.98  4976.9  432.18
  4991.2  431.21  4994.7  429.15  4997.5  428.65  5000.7  429.15  5019.8  433.57
  5026.3  433.56  5030.3   435.8  5123.5  435.26  5183.5  436.56  5206.2   441.9
  5213.5  444.73  5223.5   445.4  5233.5  446.96  5283.5  447.52  5333.5  450.58
#Mann= 8 ,-1 , 0
    4643     .05       0  4669.2     .07       0  4700.4     .12       0
  4790.2     .07       0  4848.2     .12       0  4994.7     .07       0
  5000.7     .12       0  5206.2     .16       0
Bank Sta=4941.7,5030.3
XS Rating Curve= 0 ,0
Exp/Cntr=0.3,0.1

Type RM Length L Ch R = 1 ,102642  ,548,548,548
BEGIN DESCRIPTION:
KEECHIE CREEK 168.0
END DESCRIPTION:
XS GIS Cut Line= 3
      3734145.03     10674085.59      3734061.69     10673328.62
      3733658.93     10672891.13
#Sta/Elev= 30
  4120.6  452.59  4400.6  450.61  4491.6  448.56  4498.3   447.1  4577.5  444.71
  4582.6  442.99  4639.1   442.2  4668.5  440.34  4719.6  434.54  4739.7  433.54
  4878.8  432.19  4988.8   433.1  4992.8  426.32  4995.5  425.82  4998.8  426.32
  5002.5  426.39  5009.9  430.49  5016.7  430.83  5024.1  433.04  5215.2  431.42
  5257.8  432.62  5309.7  436.59  5349.6  439.62  5356.4  441.07  5370.6  441.88
    5378  441.14    5399  445.52  5406.3   445.4  5421.8  447.19  5476.8  452.65
#Mann= 5 ,-1 , 0
  4120.6     .05       0  4992.8     .03       0  4998.8     .05       0
  5309.7     .16       0  5421.8     .05       0
Bank Sta=4988.8,5024.1
XS Rating Curve= 0 ,0
Exp/Cntr=0.3,0.1

Type RM Length L Ch R = 1 ,102094  ,229,229,229
BEGIN DESCRIPTION:
Mapping XS 56b78181
END DESCRIPTION:
XS GIS Cut Line= 3
      3734922.83      10673018.3       3734417.6     10672825.58
      3733818.61     10672799.53
#Sta/Elev= 30
  4287.3  448.03  4344.3  448.57  4397.8  448.26  4580.8  442.51  4665.7  441.01
  4720.6  438.27  4793.8  432.98  4805.5  430.44  4824.3  428.66  4876.1   428.1
  4886.1  427.11  4896.1  428.43  4946.1  428.41  4956.2  425.19  4976.2  425.43
  4995.9   421.2  5006.2  422.11  5016.2  429.82  5056.2  428.74  5136.3  428.66
  5256.4  429.82  5299.5  429.22  5346.5  430.65  5366.5  435.52  5376.5   439.7
  5386.6  441.85  5396.6  445.72  5406.6   447.3  5416.6  449.73  5427.6  450.82
#Mann= 1 ,-1 , 0
  4287.3     .16       0
Bank Sta=4946.1,5016.2
XS Rating Curve= 0 ,0
Exp/Cntr=0.3,0.1

Type RM Length L Ch R = 1 ,101865  ,155,155,155
BEGIN DESCRIPTION:
KEECHIE CREEK 167.0
END DESCRIPTION:
XS GIS Cut Line= 3
      3734728.84     10672590.77      3734216.64     10672603.79
      3733853.31     10672720.57
#Sta/Elev= 30
  4575.3  438.98  4644.6  436.83  4734.6  436.53  4749.4  435.45  4774.6  431.52
  4794.6  430.88  4824.6  427.04  4894.6   426.4  4924.6  424.26  4934.6  426.11
  4964.7  428.29  4984.7  427.25  5004.4  419.67  5007.7  420.17  5014.7  427.16
  5054.7  425.54  5123.1  427.95  5251.5  428.24    5353   431.5  5358.3  430.12
  5368.1  430.29  5378.7  431.51  5385.1  435.37  5390.4  432.45  5417.2  439.76
  5422.5  438.51  5431.2  441.15  5449.3  441.81  5462.7  445.53  5469.3  444.26
#Mann= 1 ,-1 , 0
  4575.3     .16       0
Bank Sta=4984.7,5014.7
XS Rating Curve= 0 ,0
Exp/Cntr=0.3,0.1

Type RM Length L Ch R = 1 ,101710  ,139,139,139
BEGIN DESCRIPTION:
KEECHIE CREEK 166.0
END DESCRIPTION:
XS GIS Cut Line= 3
      3734737.49      10672464.9      3734247.02     10672484.43
      3733815.16     10672586.43
#Sta/Elev= 30
  4631.9  443.23  4699.8  439.45  4779.9  432.81  4819.9  432.19  4839.9  433.15
    4870  430.27  4887.7  427.34    4920  426.23    4970  422.92  4999.8  418.22
  5010.1  418.92  5020.1  421.38  5040.1  422.68  5050.1  424.72  5070.1  425.91
  5100.1  425.42    5300     428  5335.9  429.82  5347.4  431.27  5356.4  435.46
  5384.6  437.46  5397.5  439.53  5407.8  439.03  5418.1  441.29  5459.2  440.67
  5469.2  441.66  5474.3  440.13  5479.7  441.47  5521.8  442.79  5566.5  447.16
#Mann= 1 ,-1 , 0
  4631.9     .16       0
Bank Sta=4920,5070.1
XS Rating Curve= 0 ,0
Exp/Cntr=0.3,0.1

Type RM Length L Ch R = 1 ,101571  ,422,422,422
BEGIN DESCRIPTION:
Mapping XS 6ded6f54
END DESCRIPTION:
XS GIS Cut Line= 2
      3734771.76     10672315.16      3733776.95      10672398.5
#Sta/Elev= 30
    4625  444.18  4697.4  441.36  4727.5  438.27  4757.6  437.28  4777.7  435.11
  4787.7     433  4847.9  426.63  4863.9   426.1    4869  427.62  4888.1  427.47
  4918.2  424.88  4938.2  424.37  4968.4  425.25  4984.1  418.32  4989.1  420.87
  4998.2  417.27  5018.5  424.11  5058.7  423.36  5109.2  424.31  5138.9   423.6
  5289.5  424.12  5369.8   425.9  5399.9   428.3    5430   433.8    5440  434.49
  5459.5  438.84  5510.2  443.42  5520.3  443.04  5550.4  445.74  5623.3  447.33
#Mann= 1 ,-1 , 0
    4625     .16       0
Bank Sta=4968.4,5018.5
XS Rating Curve= 0 ,0
Exp/Cntr=0.3,0.1

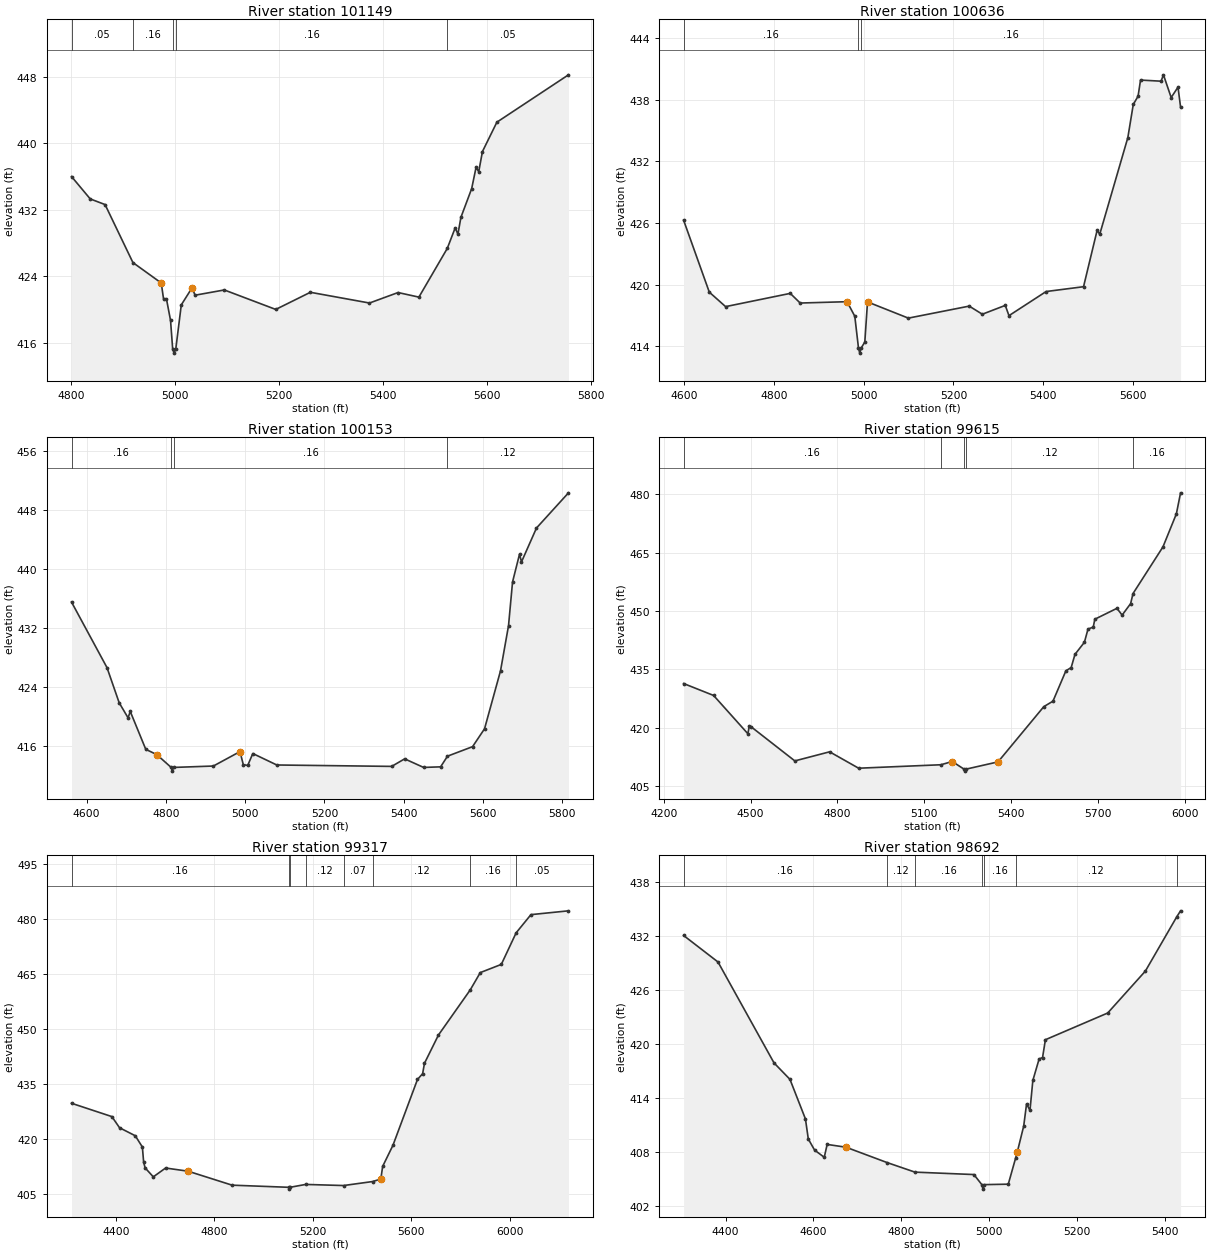
Type RM Length L Ch R = 1 ,101149  ,513,513,513
BEGIN DESCRIPTION:
KEECHIE CREEK 165.0
END DESCRIPTION:
XS GIS Cut Line= 3
      3734699.59     10672060.18      3734549.61     10671960.19
      3733799.57      10672160.2
#Sta/Elev= 30
  4800.5     436  4836.5  433.31  4865.1  432.63  4918.7  425.66  4973.2  423.21
  4977.7  421.27  4983.3  421.27  4991.1  418.71  4995.2  415.28    4998  414.78
  5001.2  415.28  5011.8  420.58  5032.5  422.63  5038.3  421.74  5094.6  422.37
  5193.6  420.03  5260.2  422.09    5374   420.8    5429  422.06  5469.1  421.51
  5523.7  427.36    5539  429.84  5544.2  429.07    5550   431.1  5570.7  434.55
  5579.1  437.09  5584.3  436.59  5591.4     439  5619.2  442.53    5757  448.22
#Mann= 5 ,-1 , 0
  4800.5     .05       0  4918.7     .16       0  4995.2     .07       0
  5001.2     .16       0  5523.7     .05       0
Bank Sta=4973.2,5032.5
XS Rating Curve= 0 ,0
Exp/Cntr=0.3,0.1

Type RM Length L Ch R = 1 ,100636  ,483,483,483
BEGIN DESCRIPTION:
KEECHIE CREEK 164.0
END DESCRIPTION:
XS GIS Cut Line= 2
      3734824.12     10671419.67      3733824.42     10671893.48
#Sta/Elev= 30
  4599.3  426.27  4656.5  419.26  4692.8  417.85  4836.7  419.14  4858.8   418.2
  4963.2  418.33  4980.4  416.91  4988.6  413.82  4991.4  413.32  4994.6  413.82
  5002.7   414.4  5008.7  418.31  5099.6  416.73  5235.1   417.9  5264.3  417.11
  5315.4  417.97  5323.6  416.97  5406.3  419.32  5489.6  419.79    5520  425.31
  5525.6  424.89  5588.2  434.31  5600.3  437.54    5611  438.35  5616.5  439.92
  5662.2  439.81  5667.5  440.43  5684.7  438.22  5699.9  439.23  5705.6  437.29
#Mann= 4 ,-1 , 0
  4599.3     .16       0  4988.6     .07       0  4994.6     .16       0
  5662.2     .05       0
Bank Sta=4963.2,5008.7
XS Rating Curve= 0 ,0
Exp/Cntr=0.3,0.1

Type RM Length L Ch R = 1 ,100153  ,538,538,538
BEGIN DESCRIPTION:
KEECHIE CREEK 163.0
END DESCRIPTION:
XS GIS Cut Line= 3
      3734799.63     10671010.18      3734399.61     10671210.19
      3733599.57     10671310.19
#Sta/Elev= 30
  4562.1  435.51  4651.6  426.64  4682.3  421.89  4704.7  419.85  4710.3  420.71
  4749.4  415.59  4777.3  414.87  4813.5  413.14  4816.2  412.64  4819.5  413.14
  4919.9  413.33    4987  415.28  4995.4  413.52  5006.5  413.41  5019.4  415.02
  5079.9  413.47  5369.6  413.28  5402.4   414.3  5450.2  413.14  5493.1  413.22
  5510.4  414.66  5573.7  415.95  5603.9  418.37  5644.2  426.21  5664.4  432.32
  5674.5  438.22  5692.1  441.98  5697.1  440.94  5734.9  445.52  5815.6  450.28
#Mann= 4 ,-1 , 0
  4562.1     .16       0  4813.5     .07       0  4819.5     .16       0
  5510.4     .12       0
Bank Sta=4777.3,4987
XS Rating Curve= 0 ,0
Exp/Cntr=0.3,0.1

Type RM Length L Ch R = 1 ,99615   ,298,298,298
BEGIN DESCRIPTION:
KEECHIE CREEK 162.0
END DESCRIPTION:
XS GIS Cut Line= 3
      3734803.02     10670862.04      3734178.01     10670815.16
      3733173.66     10671241.88
#Sta/Elev= 30
  4268.1  431.35  4371.8  428.28  4490.2  418.44  4495.3  420.41  4502.2  420.18
  4652.6  411.44  4772.9  413.78  4873.2  409.56  5157.4  410.45  5196.9  411.28
  5237.8  409.31  5240.6  408.81  5243.8  409.31  5355.1  411.19  5513.3   425.4
    5545  426.81  5589.7  434.63  5607.9  435.45  5621.1  438.86  5653.7  441.97
    5666  445.34  5684.3  445.89  5689.7   447.9  5766.1   450.7  5784.1  448.96
  5813.4  451.91  5821.8  454.51  5925.3  466.52  5971.6  475.01  5986.1  480.42
#Mann= 5 ,-1 , 0
  4268.1     .16       0  5157.4     .12       0  5237.8     .07       0
  5243.8     .12       0  5821.8     .16       0
Bank Sta=5196.9,5355.1
XS Rating Curve= 0 ,0
Exp/Cntr=0.3,0.1

Type RM Length L Ch R = 1 ,99317   ,625,625,625
BEGIN DESCRIPTION:
KEECHIE CREEK 161.0
END DESCRIPTION:
XS GIS Cut Line= 3
      3734787.35     10670794.32       3733917.6     10670549.54
      3733178.04     10669716.23
#Sta/Elev= 30
  4220.4  429.71  4384.3  426.07  4415.4  423.03  4479.3  420.84  4508.1  417.77
  4513.3  413.61  4519.3  412.07  4552.5  409.63  4602.4  412.04  4693.9  411.17
  4872.5  407.36  5101.7  406.78  5104.4  406.28  5107.7  406.78  5171.2  407.56
    5325  407.26  5442.9  408.35  5476.2  409.03  5483.7  412.49  5525.5  418.25
    5625   436.2  5645.9  437.78  5653.5  440.63  5710.3  448.34  5839.2  460.64
  5880.1  465.37  5965.4   467.6  6025.6  476.22  6085.7  481.18  6238.1  482.22
#Mann= 8 ,-1 , 0
  4220.4     .16       0  5101.7     .07       0  5107.7     .16       0
  5171.2     .12       0    5325     .07       0  5442.9     .12       0
  5839.2     .16       0  6025.6     .05       0
Bank Sta=4693.9,5476.2
XS Rating Curve= 0 ,0
Exp/Cntr=0.3,0.1

Type RM Length L Ch R = 1 ,98692   ,421,421,421
BEGIN DESCRIPTION:
KEECHIE CREEK 160.0
END DESCRIPTION:
XS GIS Cut Line= 2
      3734844.65     10670575.55      3733980.07     10669846.39
#Sta/Elev= 30
  4304.5  432.03  4382.8  429.08  4510.3  417.86  4546.6  416.03  4581.8  411.63
  4588.3   409.4  4602.6  408.17  4624.6  407.37  4631.2   408.8  4674.1  408.49
  4767.2  406.79    4831  405.72  4965.2  405.45  4983.2  404.33  4985.9  403.83
  4989.2  404.33  5043.4  404.38  5060.4  407.33  5064.2  408.01  5078.5  410.84
    5085   413.3  5092.8  412.59  5099.3  415.91  5113.6   418.3  5121.4  418.46
  5127.9  420.44  5269.7  423.41  5355.4  428.07    5427  434.12  5435.5  434.77
#Mann= 7 ,-1 , 0
  4304.5     .16       0  4767.2     .12       0    4831     .16       0
  4983.2     .07       0  4989.2     .16       0  5060.4     .12       0
    5427     .16       0
Bank Sta=4674.1,5064.2
XS Rating Curve= 0 ,0
Exp/Cntr=0.3,0.1

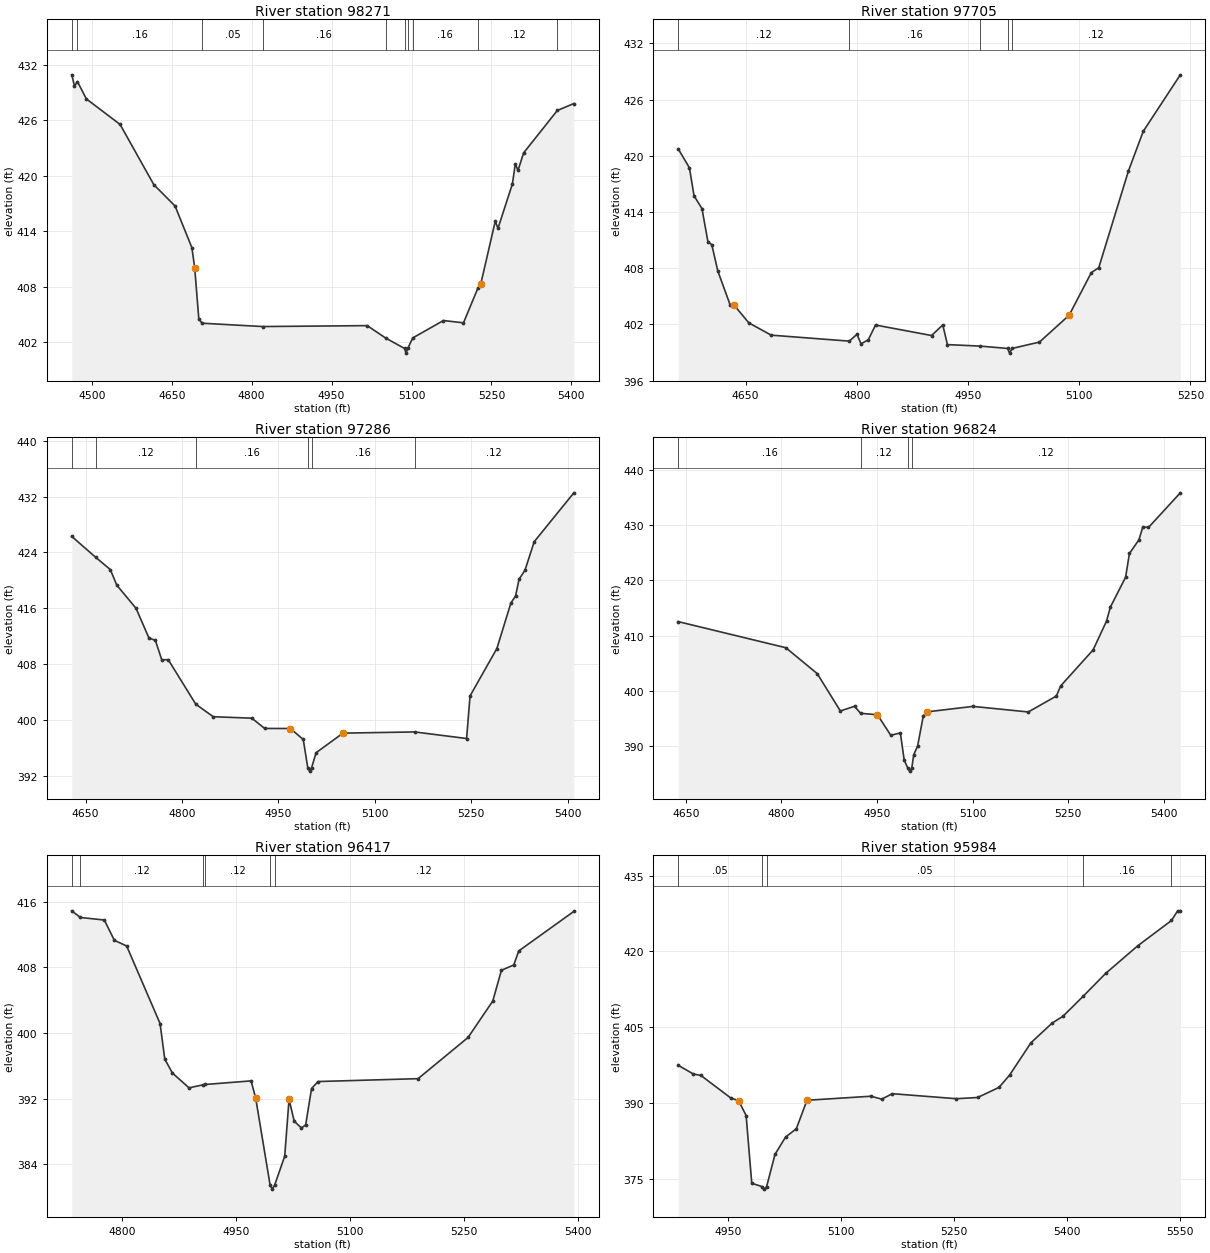
Type RM Length L Ch R = 1 ,98271   ,566,566,566
BEGIN DESCRIPTION:
KEECHIE CREEK 159.0
END DESCRIPTION:
XS GIS Cut Line= 3
      3735115.53     10669742.24      3734683.22     10669888.08
      3734219.67     10669742.24
#Sta/Elev= 30
  4462.4   430.9  4467.5  429.69  4473.1  430.16  4489.8   428.3  4553.1  425.54
  4616.4  419.04  4656.3  416.73  4687.8  412.24  4693.1  410.07  4700.8  404.55
  4706.9  404.08  4820.7  403.72  5016.8  403.82  5051.2  402.49  5086.9  401.35
  5089.7  400.85  5092.9  401.35  5102.3  402.49  5159.9  404.37  5197.5  404.12
  5224.4  407.85  5229.9  408.31  5257.1  415.09  5262.3  414.33  5289.3  419.12
  5294.7  421.26  5299.9  420.59  5310.3  422.47  5373.6  427.05  5404.6   427.8
#Mann= 10 ,-1 , 0
  4462.4     .12       0  4473.1     .16       0  4706.9     .05       0
  4820.7     .16       0  5051.2     .12       0  5086.9     .07       0
  5092.9     .12       0  5102.3     .16       0  5224.4     .12       0
  5373.6     .16       0
Bank Sta=4693.1,5229.9
XS Rating Curve= 0 ,0
Exp/Cntr=0.3,0.1

Type RM Length L Ch R = 1 ,97705   ,419,419,419
BEGIN DESCRIPTION:
KEECHIE CREEK 158.0
END DESCRIPTION:
XS GIS Cut Line= 3
      3734949.57     10669610.17      3734549.61     10669460.19
      3734299.57     10669460.19
#Sta/Elev= 30
  4559.1  420.73  4574.2  418.71  4580.4  415.73  4591.1  414.36  4599.1  410.84
  4604.4   410.5  4612.5  407.69  4629.4  404.02  4634.7  404.03  4654.3  402.16
  4684.5  400.85  4789.8  400.21  4800.2  400.94  4805.6  399.93  4815.4  400.35
  4825.2  401.93  4900.8  400.81  4915.9  401.94  4922.2  399.84  4966.5  399.68
  5003.3  399.43    5006  398.93  5009.3  399.43  5046.3  400.11  5086.3  402.97
  5116.3  407.53  5126.3  408.05  5166.3  418.37  5186.3  422.61  5236.3  428.64
#Mann= 5 ,-1 , 0
  4559.1     .12       0  4789.8     .16       0  4966.5     .12       0
  5003.3     .07       0  5009.3     .12       0
Bank Sta=4634.7,5086.3
XS Rating Curve= 0 ,0
Exp/Cntr=0.3,0.1

Type RM Length L Ch R = 1 ,97286   ,462,462,462
BEGIN DESCRIPTION:
KEECHIE CREEK 157.0
END DESCRIPTION:
XS GIS Cut Line= 3
      3734999.64     10669110.19      3734599.61     10669110.19
      3734249.62     10669260.18
#Sta/Elev= 30
  4628.6   426.3  4665.9   423.3  4688.6  421.55  4698.6  419.32  4728.6     416
  4748.6  411.76  4758.6  411.42  4768.6  408.63  4778.6  408.66  4821.4  402.29
  4848.6  400.49  4908.6  400.28  4928.6  398.81  4968.6   398.8  4988.6  397.23
  4995.6   393.2  4998.4   392.7  5001.6   393.2  5008.6  395.34  5050.4  398.14
  5161.8  398.31  5242.6  397.37    5248  403.47  5289.7  410.25  5311.5  416.77
  5318.8  417.78  5324.2  420.18  5333.3  421.44  5347.8  425.55  5409.4  432.54
#Mann= 6 ,-1 , 0
  4628.6     .16       0  4665.9     .12       0  4821.4     .16       0
  4995.6     .07       0  5001.6     .16       0  5161.8     .12       0
Bank Sta=4968.6,5050.4
XS Rating Curve= 0 ,0
Exp/Cntr=0.3,0.1

Type RM Length L Ch R = 1 ,96824   ,407,407,407
BEGIN DESCRIPTION:
KEECHIE CREEK 156.0
END DESCRIPTION:
XS GIS Cut Line= 2
      3734689.85     10668557.48      3734038.81     10669000.19
#Sta/Elev= 30
  4638.3  412.52    4807  407.78  4856.3  403.07  4892.5  396.29  4914.7  397.14
  4924.3  395.86  4950.6  395.61  4971.6  391.87  4986.6  392.31  4992.6  387.39
  4998.4  385.86  5001.1  385.36  5004.4  385.86  5007.6  388.35  5013.6  389.88
  5022.5  395.36  5028.5  396.13  5100.4  397.12  5187.2  396.11  5231.2     399
    5238  400.84  5288.9  407.39  5309.9  412.62  5315.9  415.15  5339.8  420.59
  5345.8   424.9  5360.7  427.38  5366.8  429.72  5375.7  429.63  5425.6  435.92
#Mann= 4 ,-1 , 0
  4638.3     .16       0  4924.3     .12       0  4998.4     .07       0
  5004.4     .12       0
Bank Sta=4950.6,5028.5
XS Rating Curve= 0 ,0
Exp/Cntr=0.3,0.1

Type RM Length L Ch R = 1 ,96417   ,433,433,433
BEGIN DESCRIPTION:
KEECHIE CREEK 155.0
END DESCRIPTION:
XS GIS Cut Line= 2
      3734377.31     10668340.49      3733795.75     10668652.98
#Sta/Elev= 30
  4734.2  414.87  4745.4  414.06    4777  413.75  4790.2  411.28  4806.4  410.58
  4850.3  401.14  4856.5   396.8  4866.5  395.11  4888.4   393.3  4906.8  393.67
  4909.6  393.71    4970  394.15  4976.1  392.02    4995  381.46  4997.8  380.96
    5001  381.46  5014.2  384.97  5019.9   391.9  5026.7  389.24  5036.2  388.41
  5041.8   388.8  5049.5  393.22  5058.1  394.07  5189.6  394.42  5255.3  399.44
  5287.8  403.88  5299.2  407.63  5315.4  408.27  5321.9  409.98  5394.4   414.8
#Mann= 6 ,-1 , 0
  4734.2     .05       0  4745.4     .12       0  4906.8     .16       0
  4909.6     .12       0    4995     .07       0    5001     .12       0
Bank Sta=4976.1,5019.9
XS Rating Curve= 0 ,0
Exp/Cntr=0.3,0.1

Type RM Length L Ch R = 1 ,95984   ,315,315,315
BEGIN DESCRIPTION:
KEECHIE CREEK 154.0
END DESCRIPTION:
XS GIS Cut Line= 3
      3734199.62     10668060.19      3734099.61     10668060.19
      3733699.61     10668460.19
#Sta/Elev= 30
  4884.3  397.46  4904.3  395.74  4914.3  395.46  4954.3  390.95  4964.3  390.48
  4974.3  387.52  4981.8  374.11  4995.5  373.45  4998.2  372.95  5001.5  373.45
  5012.6  379.83  5026.7  383.28  5040.9   384.9    5055  390.54  5139.9  391.34
    5154  390.76  5168.2  391.84    5253  390.85  5281.3  391.09  5309.6  393.09
  5323.7  395.53    5352  401.93  5380.3  405.85  5394.4  407.16    5421   411.1
    5451  415.65  5493.4   421.1  5538.3  426.13  5546.5  428.04    5550  428.04
#Mann= 5 ,-1 , 0
  4884.3     .05       0  4995.5     .03       0  5001.5     .05       0
    5421     .16       0  5538.3     .12       0
Bank Sta=4964.3,5055
XS Rating Curve= 0 ,0
Exp/Cntr=0.3,0.1