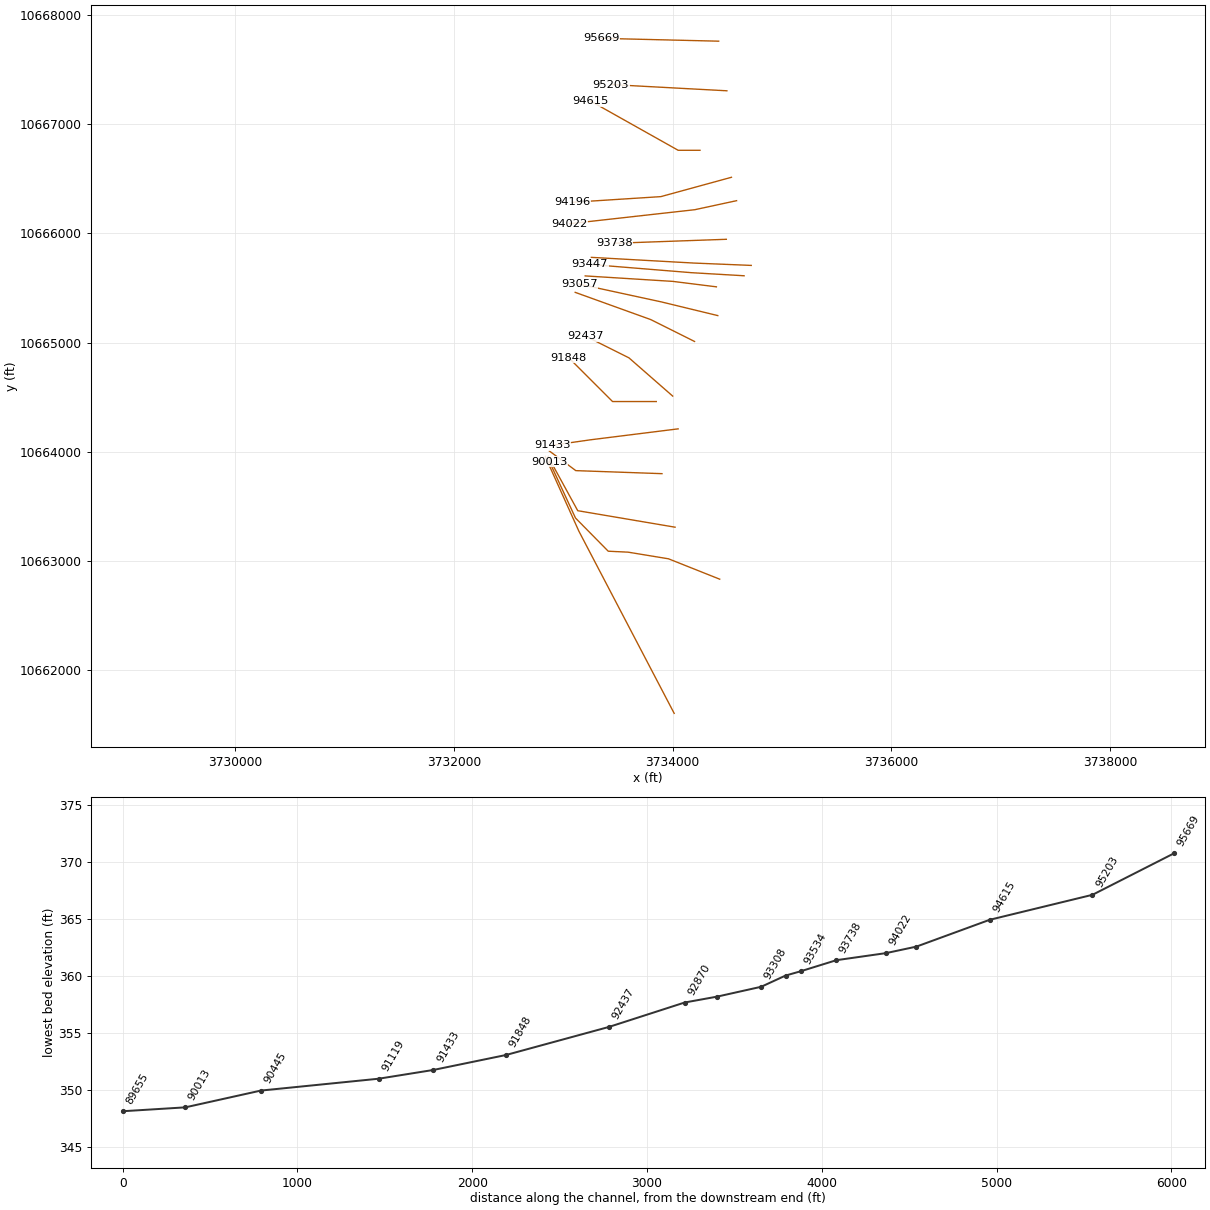
HEC-RAS study KEECHIE CREEK.prj: KEECHIE CREEK Base Level Engineering

--- KEECHIE CREEK.g01 (geometry) --- (continued)

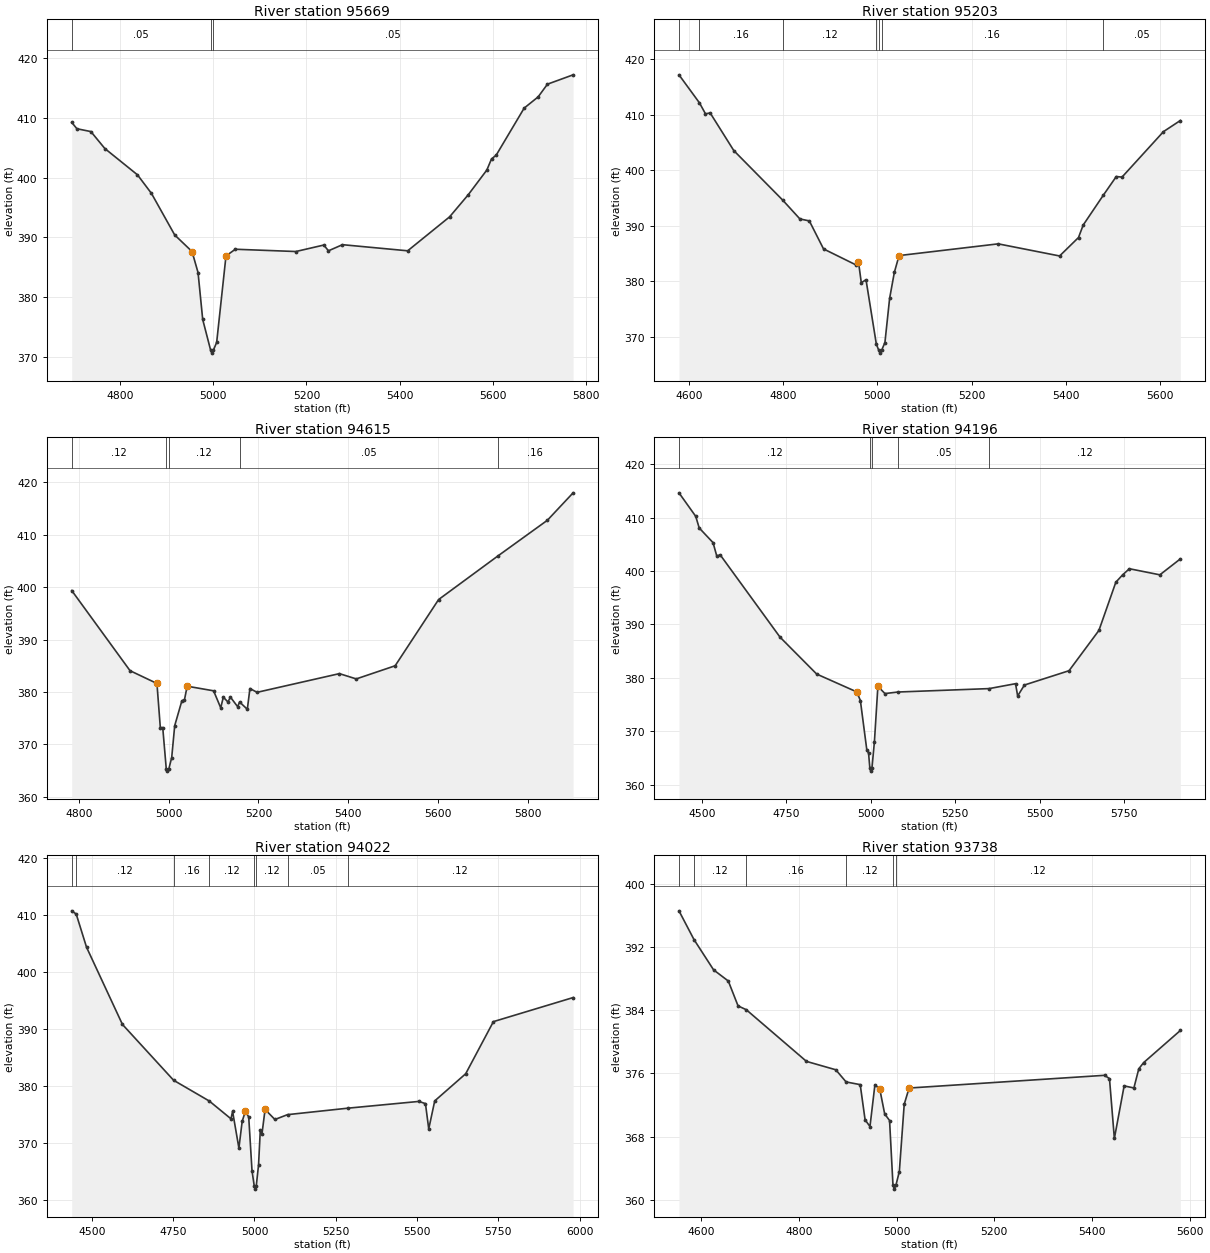
Type RM Length L Ch R = 1 ,95669   ,466,466,466
BEGIN DESCRIPTION:
KEECHIE CREEK 153.0
END DESCRIPTION:
XS GIS Cut Line= 2
      3734420.69     10667758.89       3733344.5     10667784.92
#Sta/Elev= 30
    4696  409.19  4707.1  408.13  4737.1  407.66  4767.1  404.83  4837.1  400.45
  4867.1  397.36  4917.1  390.42  4954.3  387.66  4967.2  384.15  4977.2  376.33
  4994.2  371.22  4996.9  370.72  5000.2  371.22  5007.2  372.52  5027.2  386.92
  5047.2  388.04  5177.2  387.66  5237.2  388.74  5247.2  387.78  5277.3   388.8
  5417.3  387.78  5507.3  393.44  5547.3  397.12  5587.3  401.25  5597.3   403.1
  5607.3  403.72  5667.4  411.57  5697.4  413.44  5717.4  415.56  5772.5  417.12
#Mann= 3 ,-1 , 0
    4696     .05       0  4994.2     .03       0  5000.2     .05       0
Bank Sta=4954.3,5027.2
XS Rating Curve= 0 ,0
Exp/Cntr=0.3,0.1

Type RM Length L Ch R = 1 ,95203   ,588,588,588
BEGIN DESCRIPTION:
KEECHIE CREEK 152.0
END DESCRIPTION:
XS GIS Cut Line= 2
      3734495.74     10667304.74      3733433.88       10667362.
#Sta/Elev= 30
  4579.2  417.16  4622.7  412.11  4635.4  410.15  4645.4   410.3  4695.5  403.53
  4799.1  394.63  4835.7  391.23  4855.7  390.88  4885.8  385.84  4954.9  382.95
  4959.9  383.53  4965.9  379.75  4975.9   380.3  4997.7  368.77  5002.9  367.59
  5005.7  367.09  5008.9  367.59    5016  368.98    5026  376.95    5036  381.61
    5046  384.64  5256.3  386.75  5386.5  384.57  5426.6  387.89  5436.6  390.14
  5478.8  395.45  5506.7  398.86  5518.9  398.76  5606.8  406.94  5642.6  408.94
#Mann= 7 ,-1 , 0
  4579.2     .12       0  4622.7     .16       0  4799.1     .12       0
  4997.7     .16       0  5002.9     .07       0  5008.9     .16       0
  5478.8     .05       0
Bank Sta=4959.9,5046
XS Rating Curve= 0 ,0
Exp/Cntr=0.3,0.1

Type RM Length L Ch R = 1 ,94615   ,419,419,419
BEGIN DESCRIPTION:
KEECHIE CREEK 151.0
END DESCRIPTION:
XS GIS Cut Line= 3
      3734249.59     10666760.19      3734049.61     10666760.19
      3733249.58     10667210.21
#Sta/Elev= 30
  4783.8  399.37  4913.8  384.07  4973.8  381.63  4981.3  373.22  4986.7  373.22
  4994.5   365.4  4997.2   364.9  5000.5   365.4  5006.7  367.49  5013.4  373.58
  5029.4  378.33  5035.1   378.5  5041.2  381.11  5100.1  380.23    5116  376.98
  5121.8  379.02    5132   378.1  5137.7  379.02  5153.7   377.2  5158.1   378.1
  5175.3   376.7  5181.1  380.67    5197  379.94  5380.6  383.51  5418.2   382.5
  5504.9  385.01  5601.8  397.65  5733.2  405.92  5844.3  412.78  5901.7  418.02
#Mann= 5 ,-1 , 0
  4783.8     .12       0  4994.5     .07       0  5000.5     .12       0
  5158.1     .05       0  5733.2     .16       0
Bank Sta=4973.8,5041.2
XS Rating Curve= 0 ,0
Exp/Cntr=0.3,0.1

Type RM Length L Ch R = 1 ,94196   ,174,174,174
BEGIN DESCRIPTION:
KEECHIE CREEK 150.0
END DESCRIPTION:
XS GIS Cut Line= 3
       3734537.4     10666513.08      3733891.55     10666335.99
       3733079.1     10666283.91
#Sta/Elev= 30
  4432.3  414.65  4481.9  410.25  4492.2  408.07  4533.1  405.33  4544.1  402.84
  4554.4  403.03  4731.4  387.63  4839.9  380.72  4958.9  377.37  4969.2  375.75
  4988.2  366.53  4993.4  365.92  4997.3  363.05  5000.1  362.55  5003.3  363.05
  5010.7  368.03    5021  378.43  5041.8  377.07  5080.4  377.36  5350.2     378
  5428.4  378.92  5434.6  376.62  5454.7  378.67  5586.7  381.35  5675.1  388.89
  5725.2  397.92  5745.2  399.29  5765.3  400.44  5855.5   399.3  5916.1  402.28
#Mann= 5 ,-1 , 0
  4432.3     .12       0  4997.3     .07       0  5003.3     .12       0
  5080.4     .05       0  5350.2     .12       0
Bank Sta=4958.9,5021
XS Rating Curve= 0 ,0
Exp/Cntr=0.3,0.1

Type RM Length L Ch R = 1 ,94022   ,284,284,284
BEGIN DESCRIPTION:
Mapping XS e880af31
END DESCRIPTION:
XS GIS Cut Line= 3
      3734584.07     10666298.73       3734202.1     10666216.26
      3733058.42     10666088.22
#Sta/Elev= 30
  4438.1  410.78  4451.9  410.21  4483.6   404.4    4594  390.86  4751.3  381.07
    4861  377.43  4927.7  374.31  4932.7  375.61  4952.1  369.17  4962.2  373.88
  4972.3  375.67  4982.3  374.61  4992.4  365.21  4999.4  362.48  5002.2  361.98
  5005.4  362.48  5012.5  366.23  5017.9  372.32  5022.9  371.62  5032.6  375.95
  5062.8  374.19  5101.6  375.04  5286.4  376.17  5505.6  377.36  5525.7  376.97
  5535.8  372.54  5554.2  377.45  5649.4  382.21  5734.6  391.35  5979.7  395.57
#Mann= 8 ,-1 , 0
  4438.1     .05       0  4451.9     .12       0  4751.3     .16       0
    4861     .12       0  4999.4     .07       0  5005.4     .12       0
  5101.6     .05       0  5286.4     .12       0
Bank Sta=4972.3,5032.6
XS Rating Curve= 0 ,0
Exp/Cntr=0.3,0.1

Type RM Length L Ch R = 1 ,93738   ,204,204,204
BEGIN DESCRIPTION:
KEECHIE CREEK 149.0
END DESCRIPTION:
XS GIS Cut Line= 2
      3734490.51     10665945.37      3733464.56     10665908.91
#Sta/Elev= 30
  4554.2  396.57  4584.9  392.94  4625.1   389.1  4655.2  387.69  4675.2  384.54
    4692  384.06  4815.3  377.52  4875.3  376.46  4896.4  374.92  4925.3  374.58
  4935.3  370.13  4945.3  369.28  4955.4  374.56  4965.4     374  4975.4  370.88
  4985.4  370.04  4992.4  361.86  4995.1  361.36  4998.4  361.86  5005.4  363.56
  5015.4  372.09  5025.4  374.15  5425.7  375.76  5435.7  375.34  5445.7  367.77
  5465.7  374.42  5485.7  374.16  5495.7  376.58  5505.7  377.37  5580.8  381.43
#Mann= 6 ,-1 , 0
  4554.2     .16       0  4584.9     .12       0    4692     .16       0
  4896.4     .12       0  4992.4     .07       0  4998.4     .12       0
Bank Sta=4965.4,5025.4
XS Rating Curve= 0 ,0
Exp/Cntr=0.3,0.1

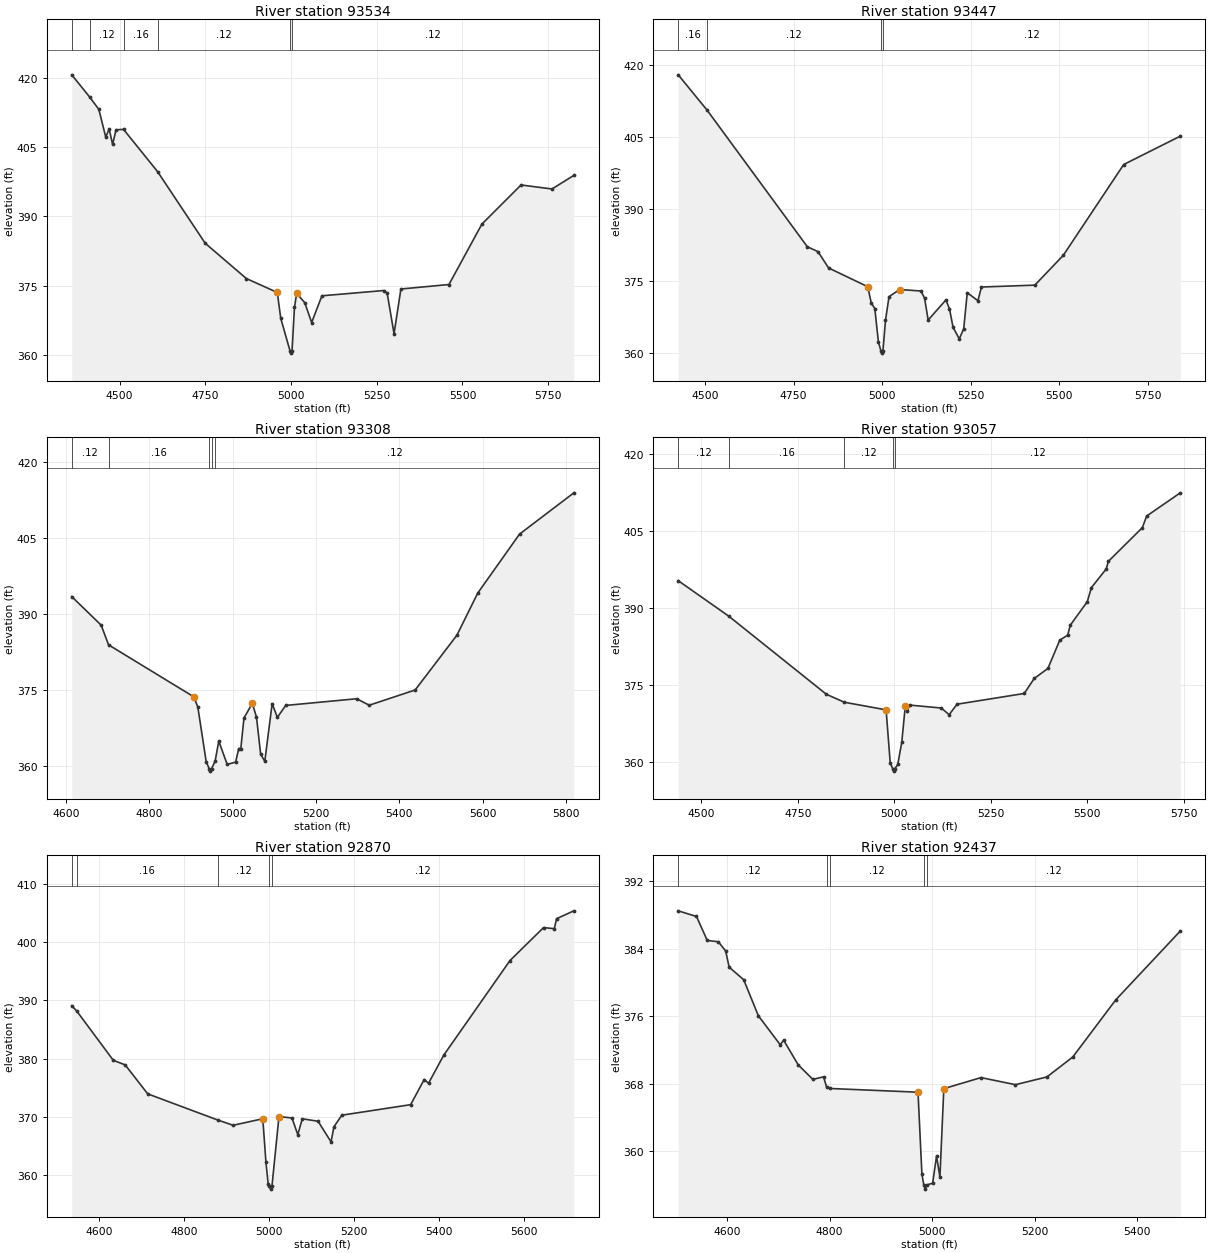
Type RM Length L Ch R = 1 ,93534   ,87,87,87
BEGIN DESCRIPTION:
Mapping XS a4eb7b8e
END DESCRIPTION:
XS GIS Cut Line= 3
      3734718.59     10665706.28      3734191.25     10665727.98
      3733255.89     10665780.06
#Sta/Elev= 30
  4360.3  420.63  4412.1  415.86  4439.3  413.15  4459.4  407.14  4469.4  408.92
  4479.4  405.57  4489.4  408.73  4511.3  408.82  4610.5  399.69  4749.6  384.17
  4869.7  376.53  4959.8  373.52  4969.9  367.93  4996.9  360.89  4999.7  360.39
  5002.9  360.89  5009.9  370.29  5016.4  373.33    5040   371.3    5060  367.01
    5090   372.8  5270.3  373.94  5280.3  373.39  5300.4  364.59  5320.4  374.27
  5460.6  375.24  5556.6  388.31  5670.9  396.79  5761.1  395.92  5824.9  398.86
#Mann= 6 ,-1 , 0
  4360.3     .05       0  4412.1     .12       0  4511.3     .16       0
  4610.5     .12       0  4996.9     .07       0  5002.9     .12       0
Bank Sta=4959.8,5016.4
XS Rating Curve= 0 ,0
Exp/Cntr=0.3,0.1

Type RM Length L Ch R = 1 ,93447   ,139,139,139
BEGIN DESCRIPTION:
Mapping XS 95b3221d
END DESCRIPTION:
XS GIS Cut Line= 3
      3734653.21     10665611.53      3734171.44     10665639.74
      3733240.43      10665715.7
#Sta/Elev= 30
  4424.6  417.89  4506.5   410.5  4788.8  382.14  4818.9  381.12  4848.9  377.72
  4959.2  373.83  4969.2  370.48  4979.3  369.27  4989.3  362.41  4996.3  360.51
  4999.1  360.01  5002.3  360.51  5009.4  366.81  5019.4  371.76  5049.5  373.24
  5109.7  372.93  5119.7  371.42  5129.8   366.9  5179.9  371.07    5190  369.22
    5200   365.4  5217.6  362.98  5230.1  365.06  5240.1  372.58  5270.2  370.91
  5280.3  373.76  5430.8  374.15    5511  380.34  5681.6  399.24  5841.3  405.14
#Mann= 4 ,-1 , 0
  4424.6     .16       0  4506.5     .12       0  4996.3     .07       0
  5002.3     .12       0
Bank Sta=4959.2,5049.5
XS Rating Curve= 0 ,0
Exp/Cntr=0.3,0.1

Type RM Length L Ch R = 1 ,93308   ,251,251,251
BEGIN DESCRIPTION:
KEECHIE CREEK 148.0
END DESCRIPTION:
XS GIS Cut Line= 3
      3734399.63     10665510.19      3733999.61     10665560.19
       3733199.6     10665610.19
#Sta/Elev= 30
  4613.9  393.43  4684.5   387.8  4702.1  383.93  4906.2   373.7  4916.3   371.7
  4936.4  360.91  4943.5  359.53  4946.2  359.03  4949.5  359.53  4957.9     361
  4966.6  364.96  4986.8  360.36    5007   360.8  5014.5  363.47  5019.5  363.47
  5027.1   369.5  5047.1  372.39  5057.1  369.68  5067.1  362.36  5077.1  360.98
  5094.7  372.33  5107.2  369.63  5127.2  371.98  5297.6   373.3  5327.6  372.02
  5437.9  375.03    5538  385.82  5588.1  394.14  5688.3  405.75  5818.6  413.89
#Mann= 5 ,-1 , 0
  4613.9     .12       0  4702.1     .16       0  4943.5     .07       0
  4949.5     .16       0  4957.9     .12       0
Bank Sta=4906.2,5047.1
XS Rating Curve= 0 ,0
Exp/Cntr=0.3,0.1

Type RM Length L Ch R = 1 ,93057   ,187,187,187
BEGIN DESCRIPTION:
Mapping XS b0591971
END DESCRIPTION:
XS GIS Cut Line= 3
       3734412.3     10665246.95      3733893.66     10665372.81
      3733144.55     10665535.19
#Sta/Elev= 30
  4440.6  395.25    4571  388.37  4824.1  373.14  4870.4  371.59  4978.9   370.1
  4989.6  359.74  4995.9  358.67  4998.7  358.17  5001.9  358.67  5009.1  359.47
  5019.4  363.75  5028.6  370.84  5033.7  369.86  5039.8  371.03  5121.7  370.46
  5142.2  369.16  5162.6   371.2  5336.6  373.29  5362.6  376.22    5398  378.17
  5428.7  383.67  5449.1  384.65  5455.9  386.59    5500  391.18  5510.5   393.9
  5549.1  397.55  5554.3     399  5642.4  405.57  5653.8  407.85  5740.8  412.36
#Mann= 5 ,-1 , 0
  4440.6     .12       0    4571     .16       0  4870.4     .12       0
  4995.9     .07       0  5001.9     .12       0
Bank Sta=4978.9,5028.6
XS Rating Curve= 0 ,0
Exp/Cntr=0.3,0.1

Type RM Length L Ch R = 1 ,92870   ,433,433,433
BEGIN DESCRIPTION:
KEECHIE CREEK 147.0
END DESCRIPTION:
XS GIS Cut Line= 3
      3734199.58      10665010.2      3733799.61     10665210.19
       3733108.1     10665459.61
#Sta/Elev= 30
  4536.1  389.08    4548  388.14  4633.9  379.72  4661.8  378.94    4715  373.97
  4880.2  369.48  4916.2  368.59  4985.9  369.71  4993.3   362.3  4998.6   358.5
  5001.5  358.15  5004.3  357.65  5007.5  358.15    5024  370.08  5054.7  369.84
  5068.3  366.99    5079   369.7    5116  369.28  5146.7  365.74  5153.4  368.33
  5172.1  370.32  5334.1  372.12    5366  376.43  5376.2  375.79  5412.2  380.62
    5568  396.81  5647.1  402.46  5672.4  402.27  5677.7  403.98  5718.4  405.33
#Mann= 5 ,-1 , 0
  4536.1     .12       0    4548     .16       0  4880.2     .12       0
  5001.5     .07       0  5007.5     .12       0
Bank Sta=4985.9,5024
XS Rating Curve= 0 ,0
Exp/Cntr=0.3,0.1

Type RM Length L Ch R = 1 ,92437   ,589,589,589
BEGIN DESCRIPTION:
KEECHIE CREEK 146.0
END DESCRIPTION:
XS GIS Cut Line= 3
       3733999.6      10664510.2      3733599.61     10664860.19
      3733199.62     10665060.19
#Sta/Elev= 30
  4504.9  388.47  4540.5   387.8  4561.4  384.97  4583.2   384.8  4597.4  383.71
  4604.1   381.8  4632.5  380.31    4661  376.05  4703.7  372.61  4710.4  373.15
  4738.8  370.22  4767.3  368.51  4788.2  368.81  4794.1  367.59  4800.5  367.43
  4972.3  366.99  4979.9  357.27  4983.6  356.01  4986.3  355.51  4989.6  356.01
  5000.8  356.21  5008.4  359.42    5015  356.94  5022.6  367.41  5095.1  368.72
  5162.2  367.88  5223.7   368.8    5274  371.16  5357.8  377.93  5483.6  386.08
#Mann= 5 ,-1 , 0
  4504.9     .12       0  4794.1     .16       0  4800.5     .12       0
  4983.6     .07       0  4989.6     .12       0
Bank Sta=4972.3,5022.6
XS Rating Curve= 0 ,0
Exp/Cntr=0.3,0.1

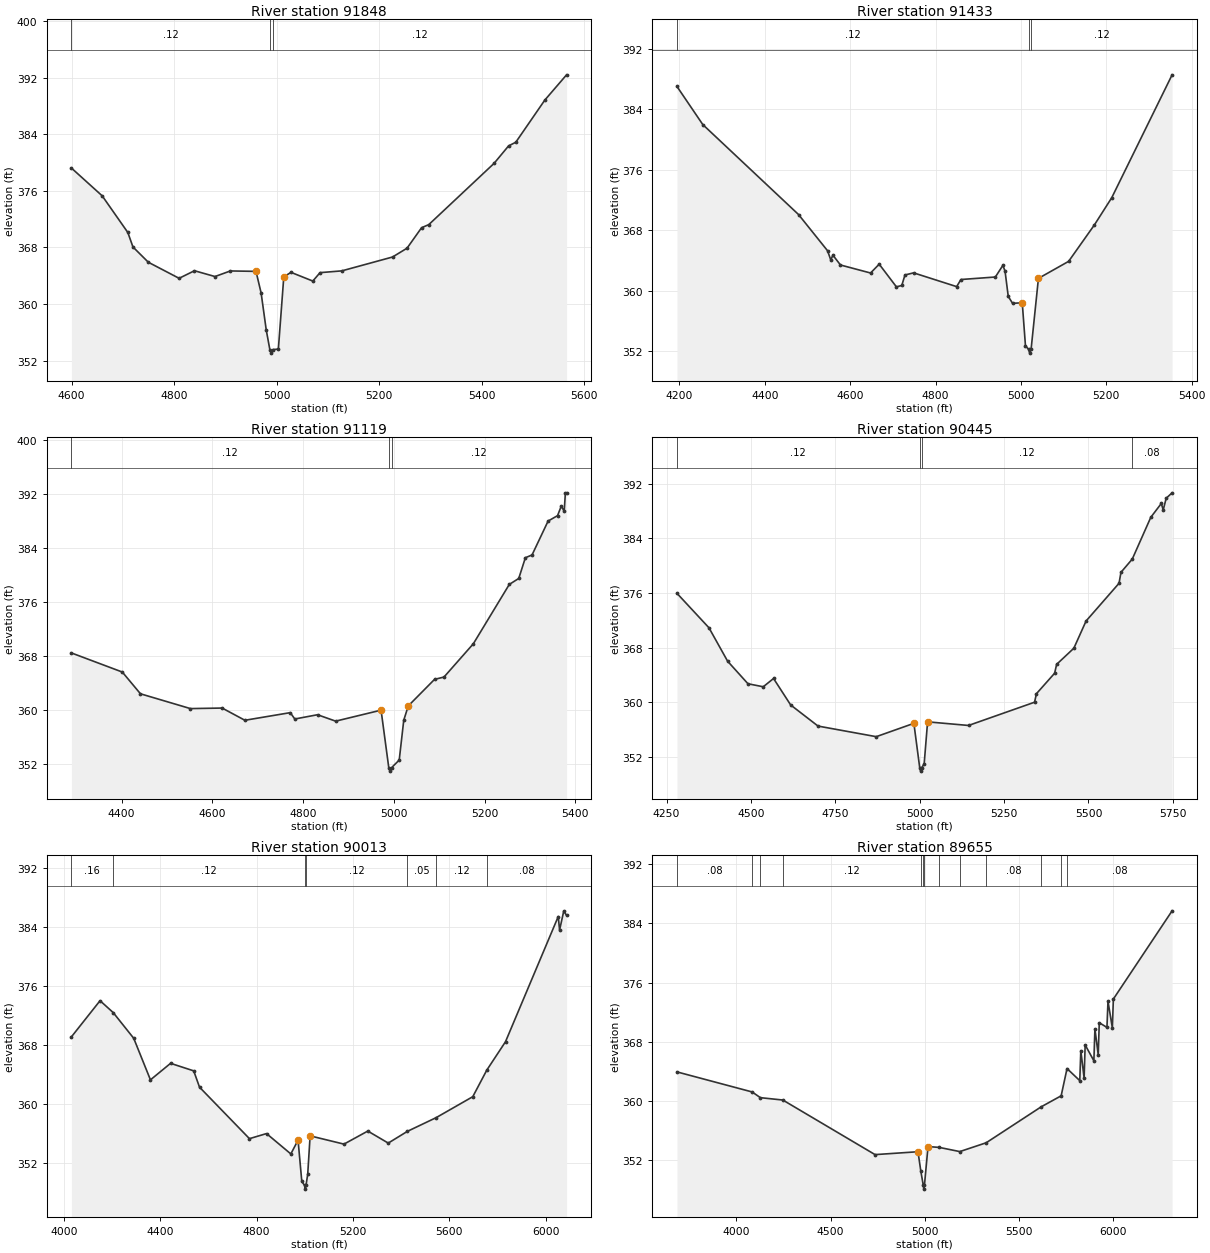
Type RM Length L Ch R = 1 ,91848   ,415,415,415
BEGIN DESCRIPTION:
KEECHIE CREEK 145.0
END DESCRIPTION:
XS GIS Cut Line= 3
      3733849.65     10664460.19      3733449.61     10664460.19
      3733049.63     10664860.17
#Sta/Elev= 30
  4599.8  379.22  4659.8  375.29  4709.8  370.11  4719.8  368.06  4749.8   365.9
  4809.8  363.63  4839.8   364.7  4879.8  363.88  4909.8  364.67  4959.8  364.61
  4969.8  361.55  4979.8  356.31  4986.8  353.55  4989.6  353.05  4992.8  353.55
  5003.4  353.62    5014  363.84  5028.1  364.47  5070.6  363.24  5084.7  364.43
  5127.1  364.68  5226.1  366.64  5254.4  367.89  5282.7  370.78  5296.8  371.22
  5424.1  379.88  5452.4  382.35  5466.5  382.87  5523.1  388.83  5565.5   392.4
#Mann= 3 ,-1 , 0
  4599.8     .12       0  4986.8     .07       0  4992.8     .12       0
Bank Sta=4959.8,5014
XS Rating Curve= 0 ,0
Exp/Cntr=0.3,0.1

Type RM Length L Ch R = 1 ,91433   ,314,314,314
BEGIN DESCRIPTION:
KEECHIE CREEK 144.0
END DESCRIPTION:
XS GIS Cut Line= 3
      3734049.63     10664210.19      3733249.61     10664110.19
      3732899.61     10664060.19
#Sta/Elev= 30
  4194.4  387.02  4254.9  381.98  4479.1  370.08  4547.1  365.29  4554.7  364.07
  4559.7   364.7  4577.4   363.4  4647.9  362.34  4668.1  363.51  4708.4  360.51
    4721  360.69  4728.5  362.08  4748.7  362.36  4849.5  360.54  4859.6  361.48
  4940.2  361.81  4957.8  363.35  4962.9  362.59  4970.4  359.25  4980.5  358.33
  5003.2   358.4  5010.7  352.73  5017.9  352.24  5020.6  351.74  5023.9  352.24
  5041.1  361.63  5111.8  363.88  5172.4  368.72  5212.8   372.3  5354.2  388.56
#Mann= 3 ,-1 , 0
  4194.4     .12       0  5017.9     .07       0  5023.9     .12       0
Bank Sta=5003.2,5041.1
XS Rating Curve= 0 ,0
Exp/Cntr=0.3,0.1

Type RM Length L Ch R = 1 ,91119   ,674,674,674
BEGIN DESCRIPTION:
KEECHIE CREEK 143.0
END DESCRIPTION:
XS GIS Cut Line= 3
      3733901.75       10663800.      3733113.57     10663827.78
      3732870.48     10664008.36
#Sta/Elev= 30
  4289.3  368.47  4401.5  365.64  4441.5  362.42  4551.6  360.23  4621.6  360.31
  4671.7   358.5  4771.7  359.63  4781.7  358.69  4831.8  359.32  4871.8  358.37
  4971.9     360  4988.9  351.47  4991.6  350.97  4994.9  351.47  5011.9  352.61
  5021.9  358.51  5031.9  360.63  5089.8  364.56  5110.6   364.9  5175.3  369.83
  5254.6  378.62  5275.4   379.5    5290  382.57  5304.7  382.98  5340.1     388
  5360.9   388.8  5369.3  390.24  5375.6  389.43  5378.2  392.18  5380.8  392.18
#Mann= 3 ,-1 , 0
  4289.3     .12       0  4988.9     .07       0  4994.9     .12       0
Bank Sta=4971.9,5031.9
XS Rating Curve= 0 ,0
Exp/Cntr=0.3,0.1

Type RM Length L Ch R = 1 ,90445   ,432,432,432
BEGIN DESCRIPTION:
KEECHIE CREEK 142.0
END DESCRIPTION:
XS GIS Cut Line= 3
      3734021.75     10663309.95      3733131.14     10663460.99
      3732860.45     10663955.53
#Sta/Elev= 30
  4280.7  375.94  4375.5   370.9  4430.8  366.01  4491.1  362.71  4536.4  362.27
  4566.9  363.48  4617.6  359.61  4698.7  356.52  4871.2  354.97  4982.7  356.92
    5000  350.43  5002.8  349.93    5006  350.43  5013.2     351  5023.3  357.14
  5144.6  356.61  5340.2  360.01  5345.9  361.26  5399.7  364.25  5405.7  365.55
  5456.7  367.91  5492.9  371.89  5590.6  377.41  5596.3  379.01  5629.8  380.95
  5684.7  387.06  5715.8  389.08  5721.5  388.14  5730.3  389.85  5747.8  390.64
#Mann= 4 ,-1 , 0
  4280.7     .12       0    5000     .07       0    5006     .12       0
  5629.8     .08       0
Bank Sta=4982.7,5023.3
XS Rating Curve= 0 ,0
Exp/Cntr=0.3,0.1

Type RM Length L Ch R = 1 ,90013   ,358,358,358
BEGIN DESCRIPTION:
Mapping XS 0fe92e2d
END DESCRIPTION:
XS GIS Cut Line= 6
       3734430.1     10662834.05      3733961.37     10663020.67
      3733592.44     10663081.43      3733410.15     10663090.11
      3733110.67     10663393.93      3732871.96     10663910.42
#Sta/Elev= 30
  4030.6   369.1  4149.5     374  4204.4  372.38  4289.4   368.9  4358.8  363.27
  4442.4  365.51  4538.5  364.49  4562.6  362.28    4770   355.3  4840.9  355.99
  4941.9  353.23  4971.9   355.1  4987.4  349.51  4998.9  348.96  5001.7  348.46
  5004.9  348.96    5012  350.47    5022  355.68  5162.6  354.56  5261.6  356.33
  5346.5   354.7    5426  356.29  5545.5  358.15  5697.6  360.99  5755.8  364.59
  5833.5  368.44  6052.6  385.41  6058.1  383.57  6075.6  386.18  6087.1  385.55
#Mann= 7 ,-1 , 0
  4030.6     .16       0  4204.4     .12       0  4998.9     .07       0
  5004.9     .12       0    5426     .05       0  5545.5     .12       0
  5755.8     .08       0
Bank Sta=4971.9,5022
XS Rating Curve= 0 ,0
Exp/Cntr=0.3,0.1

Type RM Length L Ch R = 1 ,89655   ,158,158,158
BEGIN DESCRIPTION:
KEECHIE CREEK 141.0
END DESCRIPTION:
XS GIS Cut Line= 3
      3734013.45     10661605.74      3733141.55     10663273.49
      3732834.56     10663955.13
#Sta/Elev= 30
  3684.6  363.95    4084  361.24  4127.7  360.47  4246.9  360.15  4736.6  352.78
  4964.7  353.17  4979.4  350.59  4992.8  348.62  4995.6  348.12  4998.8  348.62
  5017.9  353.87  5078.3  353.75  5186.7  353.19  5326.8  354.38  5619.2  359.24
  5724.9  360.72  5756.1   364.4  5823.8  362.77  5829.3  366.82  5846.9  363.12
  5852.4  367.59  5898.7  365.45  5904.2  369.76  5921.8  366.28  5927.3  370.59
  5968.1  369.96  5973.6  373.49  5996.8   369.9  6002.2  373.79  6314.1   385.7
#Mann= 13 ,-1 , 0
  3684.6     .08       0    4084     .05       0  4127.7     .08       0
  4246.9     .12       0  4979.4     .08       0  4992.8     .07       0
  4998.8     .08       0  5078.3     .05       0  5186.7     .12       0
  5326.8     .08       0  5619.2     .05       0  5724.9     .12       0
  5756.1     .08       0
Bank Sta=4964.7,5017.9
XS Rating Curve= 0 ,0
Exp/Cntr=0.3,0.1