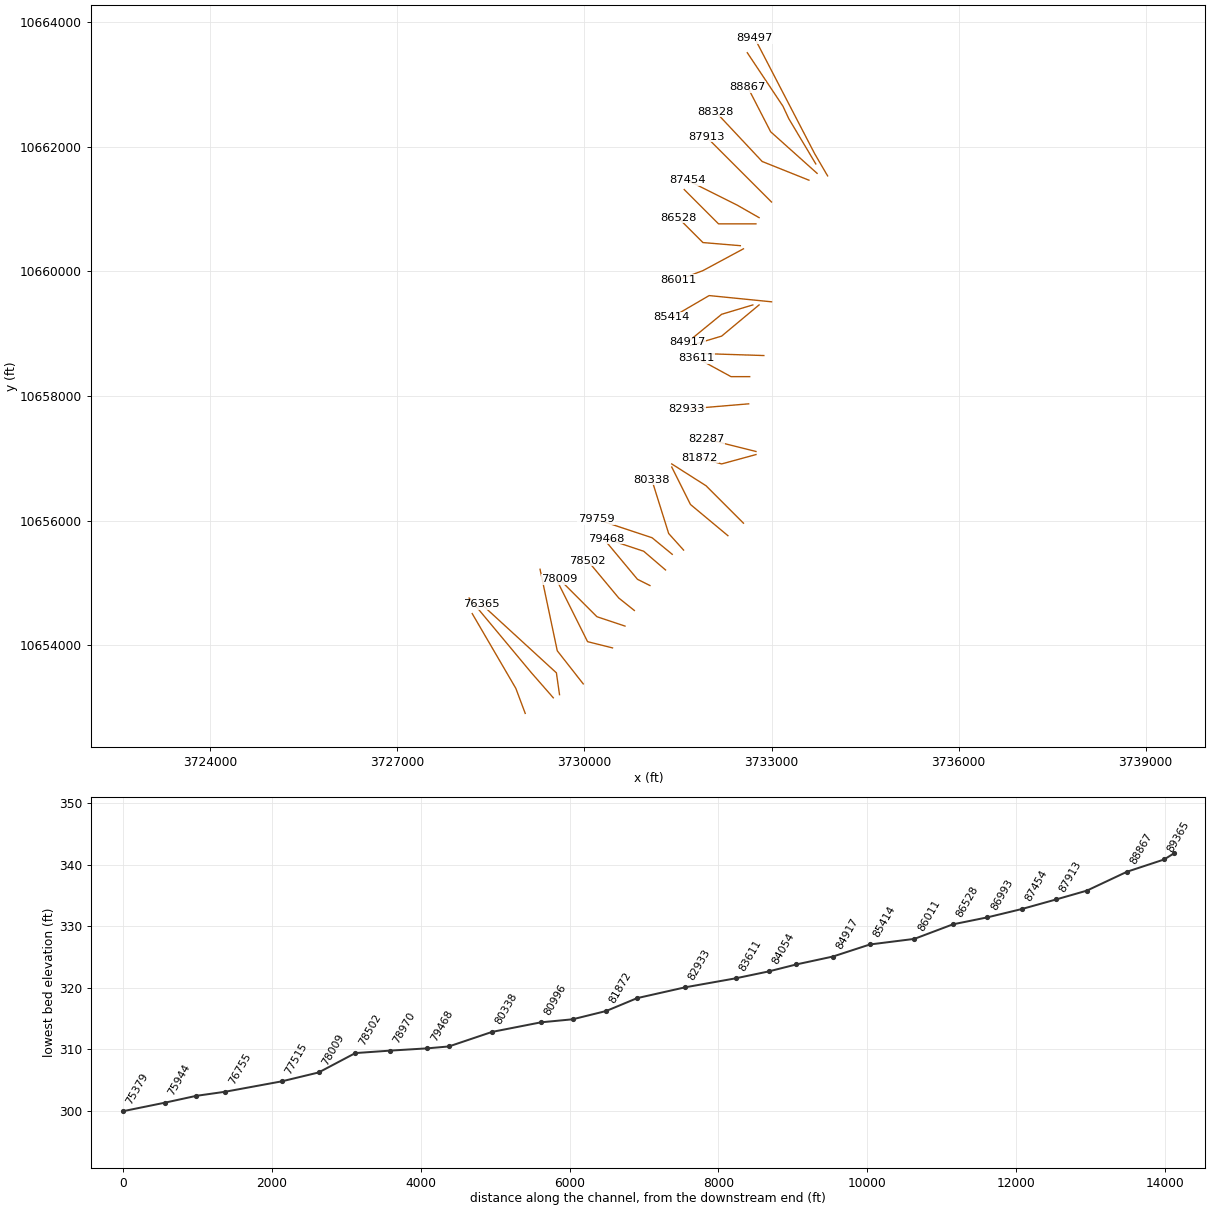
HEC-RAS study KEECHIE CREEK.prj: KEECHIE CREEK Base Level Engineering

--- KEECHIE CREEK.g01 (geometry) --- (continued)

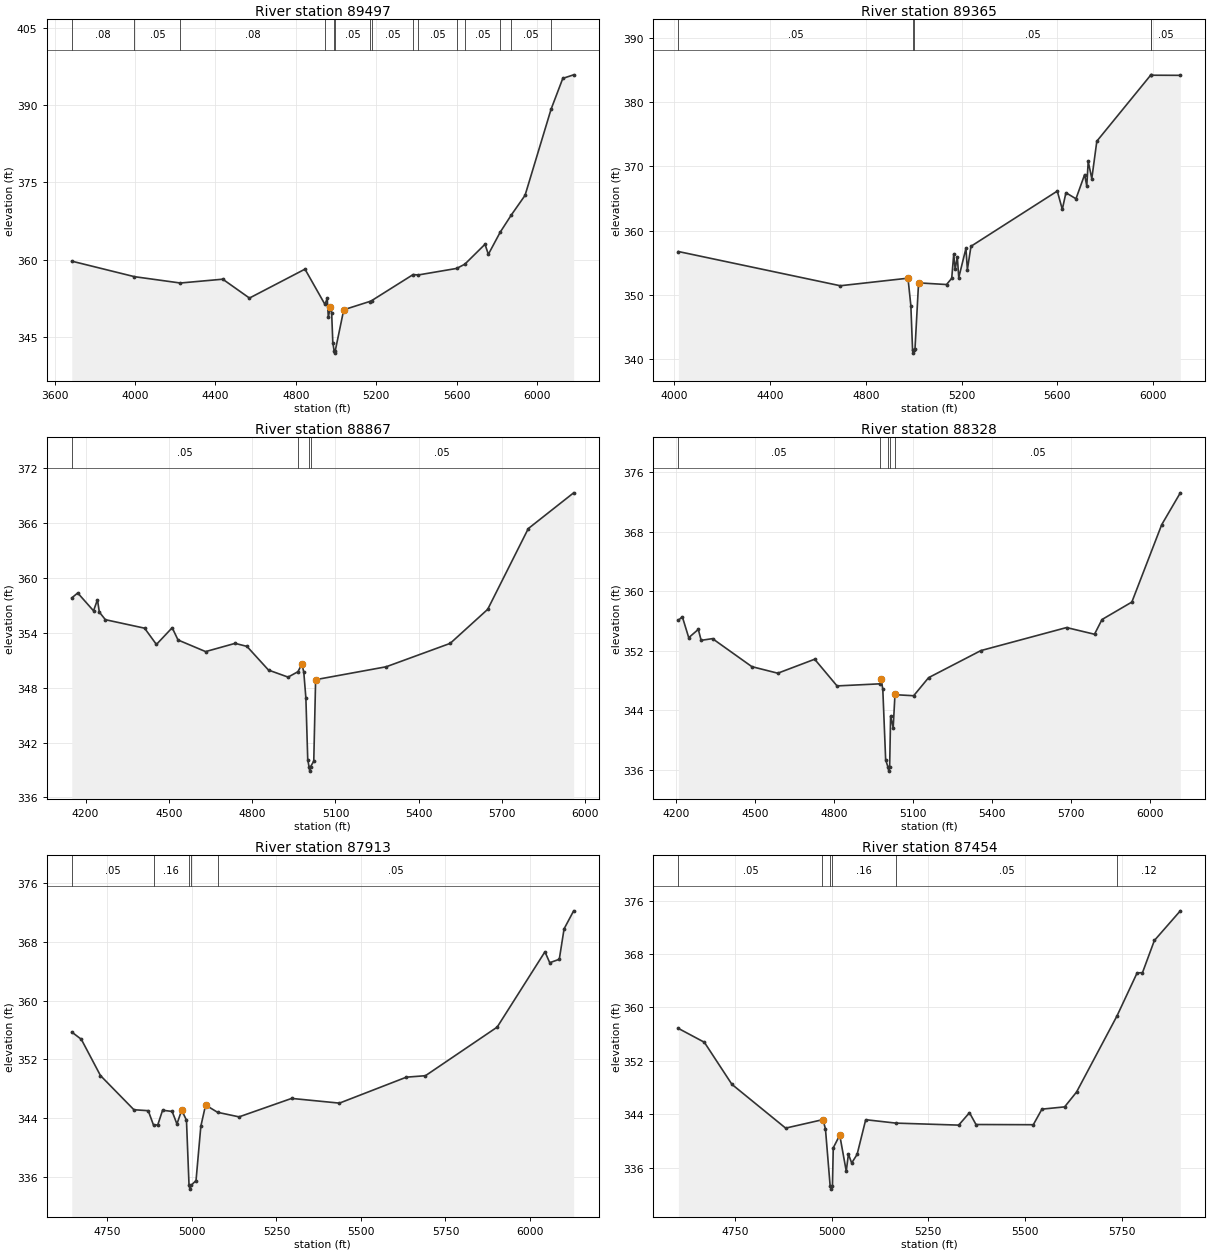
Type RM Length L Ch R = 1 ,89497   ,132,132,132
BEGIN DESCRIPTION:
KEECHIE CREEK 140.0
END DESCRIPTION:
XS GIS Cut Line= 3
      3733898.83     10661529.05      3733690.52     10661886.64
      3732730.82     10663735.22
#Sta/Elev= 30
  3685.1  359.69  3996.9  356.68  4225.2  355.45  4436.3  356.19    4569  352.53
  4845.3  358.14  4944.6   351.3  4955.9  352.47  4961.5  348.77  4970.5   350.8
    4978  349.69  4983.7   343.9  4990.1  342.35  4992.8  341.85  4996.1  342.35
  5038.1  350.26  5166.7  351.86  5176.5  352.02  5383.3  357.09  5408.5  357.01
  5599.9  358.28  5640.4   359.1  5740.9  362.97  5757.4  361.01  5816.6  365.32
  5872.3  368.68    5940  372.45  6069.5  389.16  6127.8  395.14  6181.8  395.83
#Mann= 15 ,-1 , 0
  3685.1     .08       0  3996.9     .05       0  4225.2     .08       0
  4944.6     .05       0  4990.1     .04       0  4996.1     .05       0
  5166.7     .08       0  5176.5     .05       0  5383.3     .08       0
  5408.5     .05       0  5599.9     .16       0  5640.4     .05       0
  5816.6     .16       0  5872.3     .05       0  6069.5     .08       0
Bank Sta=4970.5,5038.1
XS Rating Curve= 0 ,0
Exp/Cntr=0.3,0.1

Type RM Length L Ch R = 1 ,89365   ,498,498,498
BEGIN DESCRIPTION:
Mapping XS 98349a60
END DESCRIPTION:
XS GIS Cut Line= 4
      3733709.27      10661721.4      3733276.97     10662445.37
      3733181.39     10662648.89      3732610.67     10663504.68
#Sta/Elev= 30
  4017.2  356.72  4693.3  351.38  4976.2  352.56  4988.2  348.27  4995.3  341.36
  4998.1  340.86  5001.3  341.36  5005.5  341.55  5020.4  351.83  5137.2  351.57
  5158.9  352.54  5167.3   356.3  5173.3  353.97  5182.3  355.87  5188.3  352.64
  5218.3  357.22  5224.3   353.9  5239.4  357.54  5599.9  366.16  5620.9  363.31
    5636   365.9    5678  364.96  5714.1  368.73  5723.1  366.97  5729.1  370.78
  5744.1  368.11  5765.1  373.95  5991.2  384.31  5993.1  384.25  6113.9  384.23
#Mann= 5 ,-1 , 0
  4017.2     .05       0  4995.3     .03       0  5001.3     .05       0
  5991.2     .08       0  5993.1     .05       0
Bank Sta=4976.2,5020.4
XS Rating Curve= 0 ,0
Exp/Cntr=0.3,0.1

Type RM Length L Ch R = 1 ,88867   ,539,539,539
BEGIN DESCRIPTION:
KEECHIE CREEK 139.0
END DESCRIPTION:
XS GIS Cut Line= 3
      3733730.13     10661570.34       3732985.3     10662237.04
      3732615.66      10662955.5
#Sta/Elev= 30
  4150.2  357.81  4171.7  358.35  4228.6   356.4  4242.8  357.61  4249.5  356.26
  4271.2  355.43  4412.5   354.5  4455.1  352.72  4511.9  354.55  4532.9  353.21
  4632.3  351.94  4738.5  352.84  4781.1  352.51  4858.8  349.92  4929.3  349.15
  4964.8  349.74  4979.2  350.58  4985.9  349.68  4993.4  346.87  5000.1  340.14
  5004.6  339.37  5007.4  338.87  5010.6  339.37  5021.8  339.96  5028.5  348.87
  5282.6  350.28  5513.2  352.84  5648.2  356.56  5794.4  365.39  5957.8   369.3
#Mann= 4 ,-1 , 0
  4150.2     .05       0  4964.8     .16       0  5004.6     .07       0
  5010.6     .05       0
Bank Sta=4979.2,5028.5
XS Rating Curve= 0 ,0
Exp/Cntr=0.3,0.1

Type RM Length L Ch R = 1 ,88328   ,415,415,415
BEGIN DESCRIPTION:
KEECHIE CREEK 138.0
END DESCRIPTION:
XS GIS Cut Line= 3
      3733599.63     10661460.18      3732849.61     10661760.19
       3732099.6      10662560.2
#Sta/Elev= 30
  4209.9   356.1  4224.7  356.56    4249  353.75  4285.3  354.86  4296.1  353.39
  4339.2  353.62  4488.6  349.85  4586.9  348.97  4726.9  350.85  4811.7  347.26
  4973.7  347.54  4978.7  348.22  4985.4   346.8  4996.2  337.33  5005.3   336.3
    5008   335.8  5011.3   336.3    5015   343.2  5024.8  341.64  5031.6  346.13
  5032.5  346.08  5102.5  345.94  5159.1  348.37  5357.4  352.01  5682.7  355.11
  5788.7  354.21  5817.1  356.19  5930.4  358.54  6043.7  368.95  6114.3  373.23
#Mann= 5 ,-1 , 0
  4209.9     .05       0  4973.7     .16       0  5005.3     .07       0
  5011.3     .16       0  5032.5     .05       0
Bank Sta=4978.7,5031.6
XS Rating Curve= 0 ,0
Exp/Cntr=0.3,0.1

Type RM Length L Ch R = 1 ,87913   ,459,459,459
BEGIN DESCRIPTION:
KEECHIE CREEK 137.0
END DESCRIPTION:
XS GIS Cut Line= 3
      3732999.63     10661110.17      3732749.61     10661360.19
      3731949.58     10662160.22
#Sta/Elev= 30
  4644.3  355.73  4672.6  354.74  4729.2  349.81  4828.2  345.16  4870.6  345.03
  4886.4  343.04  4898.9  343.11    4913  345.09  4941.3  344.93  4955.5  343.22
  4969.6  345.11  4983.7  343.73  4991.3  334.86  4994.1  334.36  4997.3  334.86
    5012  335.53  5026.2  342.91  5040.3   345.8  5075.7  344.81  5139.3  344.19
  5294.9   346.7  5436.3  346.06  5634.3  349.59  5690.8  349.79    5903   356.4
  6044.4  366.65  6058.5  365.16  6086.8  365.63    6101  369.77  6129.3  372.22
#Mann= 5 ,-1 , 0
  4644.3     .05       0  4886.4     .16       0  4991.3     .07       0
  4997.3     .16       0  5075.7     .05       0
Bank Sta=4969.6,5040.3
XS Rating Curve= 0 ,0
Exp/Cntr=0.3,0.1

Type RM Length L Ch R = 1 ,87454   ,461,461,461
BEGIN DESCRIPTION:
KEECHIE CREEK 136.0
END DESCRIPTION:
XS GIS Cut Line= 3
      3732799.65     10660860.17      3732449.61     10661060.19
      3731649.59      10661460.2
#Sta/Elev= 30
  4603.9  356.86  4670.9  354.79  4742.2  348.49  4881.1  341.94  4975.7  343.19
  4977.5   343.2    4984  341.83  4996.1  333.31  4998.9  332.81  5002.1  333.31
  5004.2  338.99    5021  340.89  5037.8  335.49  5043.4  338.06  5051.8  336.72
  5065.8     338  5088.1   343.2  5166.1  342.69  5328.5  342.39  5356.4  344.25
  5373.2  342.48  5521.4  342.45  5543.7  344.78  5602.4  345.12  5633.2  347.34
  5737.6  358.71  5789.7  365.16  5803.7  365.21  5834.4  370.02  5901.5  374.46
#Mann= 6 ,-1 , 0
  4603.9     .05       0  4975.7     .16       0  4996.1     .07       0
  5002.1     .16       0  5166.1     .05       0  5737.6     .12       0
Bank Sta=4977.5,5021
XS Rating Curve= 0 ,0
Exp/Cntr=0.3,0.1

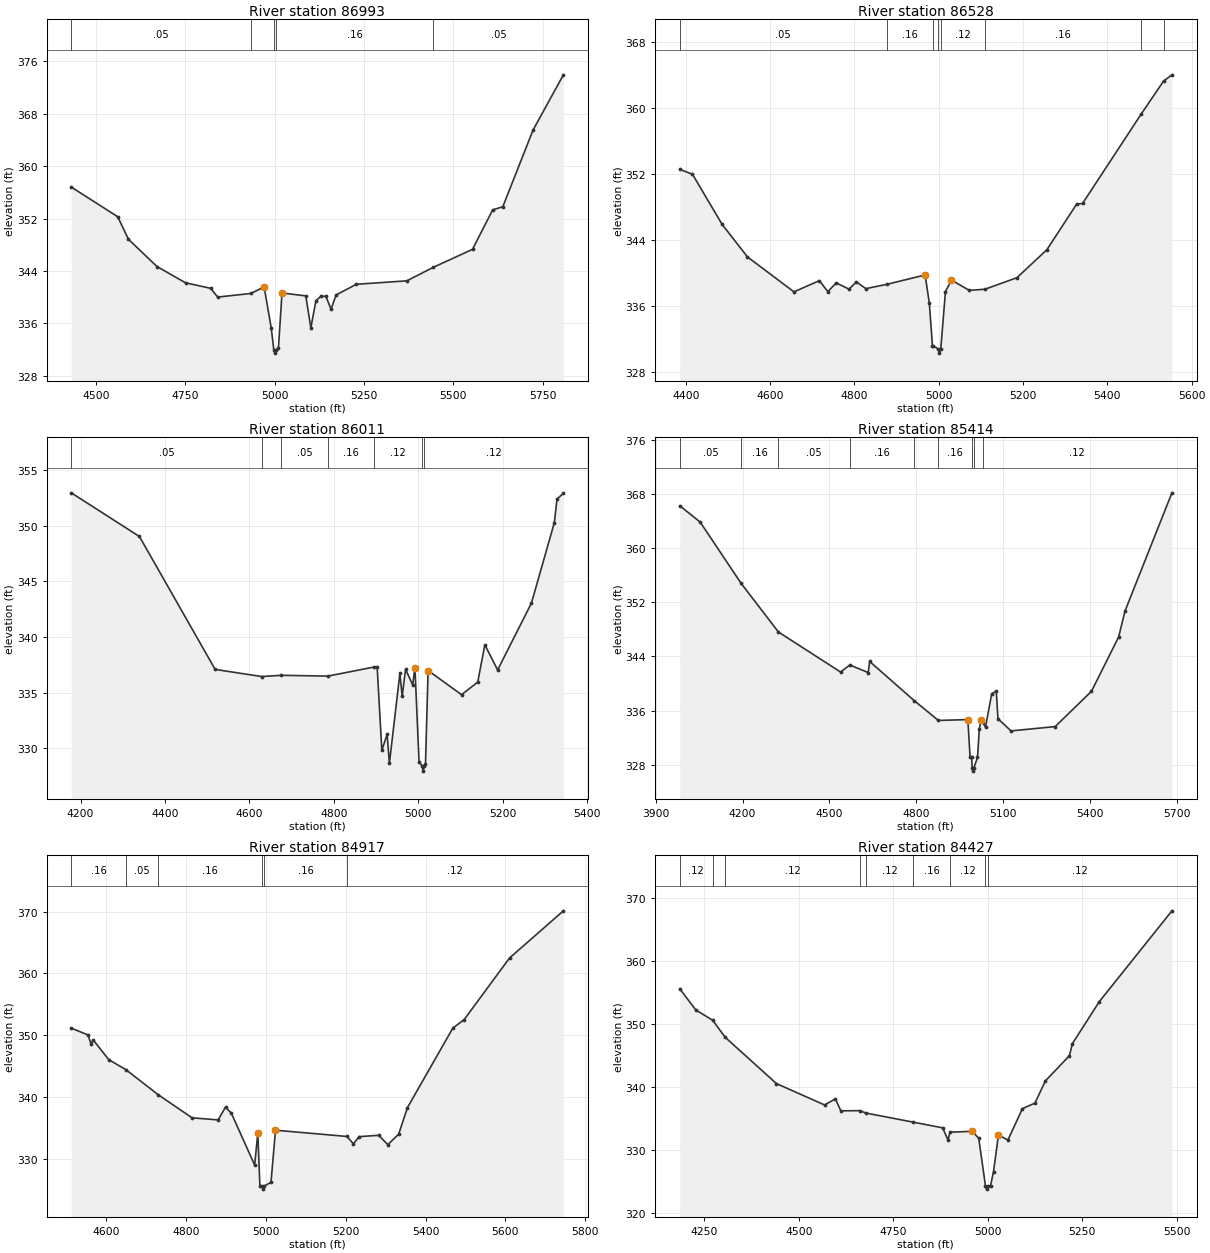
Type RM Length L Ch R = 1 ,86993   ,465,465,465
BEGIN DESCRIPTION:
KEECHIE CREEK 135.0
END DESCRIPTION:
XS GIS Cut Line= 3
      3732749.61     10660760.19      3732149.61     10660760.19
      3731599.62     10661310.18
#Sta/Elev= 30
  4430.4  356.82  4560.4  352.29  4590.4  348.85  4670.4  344.68  4750.4   342.2
  4820.4  341.36  4840.4  340.02  4932.8  340.57  4970.4  341.56  4990.4  335.24
  4997.4  331.96  5000.1  331.46  5003.4  331.96  5010.4  332.25  5020.4  340.65
    5087   340.2  5101.1  335.32  5115.3  339.44  5129.4  340.16  5143.5  340.12
  5157.7  338.16  5171.8  340.34  5228.4  341.97  5369.8   342.5  5443.8  344.56
  5553.7  347.31  5610.2  353.34  5638.5  353.81  5723.4  365.55  5808.2  373.96
#Mann= 5 ,-1 , 0
  4430.4     .05       0  4932.8     .16       0  4997.4     .07       0
  5003.4     .16       0  5443.8     .05       0
Bank Sta=4970.4,5020.4
XS Rating Curve= 0 ,0
Exp/Cntr=0.3,0.1

Type RM Length L Ch R = 1 ,86528   ,517,517,517
BEGIN DESCRIPTION:
KEECHIE CREEK 134.0
END DESCRIPTION:
XS GIS Cut Line= 3
      3732499.59     10660410.19      3731899.61     10660460.19
      3731499.64     10660860.16
#Sta/Elev= 30
  4385.5   352.6  4415.6  352.01  4485.8  345.94    4546  341.99  4656.4  337.75
  4716.6  339.11  4736.7  337.78  4756.8  338.84  4786.9  338.08  4804.4  338.96
    4827  338.14  4876.5  338.66  4967.5   339.8  4977.5  336.41    4985  331.21
  4986.6  331.21  4998.7  330.82  5001.4  330.32  5004.7  330.82  5015.8  337.78
    5030  339.18  5072.4  337.93  5109.6  338.07  5185.5  339.47  5256.3  342.85
    5327  348.38  5341.1  348.47  5480.2  359.31  5533.5  363.32  5553.2  364.07
#Mann= 8 ,-1 , 0
  4385.5     .05       0  4876.5     .16       0  4986.6     .12       0
  4998.7     .07       0  5004.7     .12       0  5109.6     .16       0
  5480.2     .12       0  5533.5     .16       0
Bank Sta=4967.5,5030
XS Rating Curve= 0 ,0
Exp/Cntr=0.3,0.1

Type RM Length L Ch R = 1 ,86011   ,597,597,597
BEGIN DESCRIPTION:
KEECHIE CREEK 133.0
END DESCRIPTION:
XS GIS Cut Line= 3
      3732549.57     10660360.17      3731899.61     10660010.19
      3731499.61     10659860.19
#Sta/Elev= 30
  4178.1  352.94  4339.5  349.02  4518.8  337.09  4628.7  336.45  4675.8  336.56
  4785.9  336.49    4896  337.31  4902.5   337.3  4913.5  329.83  4926.1  331.26
  4931.4  328.65  4956.3  336.73  4961.7  334.68  4969.7   337.1  4986.6   335.7
  4991.9  337.26  5001.7  328.77  5008.5  328.46  5011.3  327.96  5014.5  328.46
  5016.9  328.59  5023.1  336.99  5102.3  334.82  5140.6  335.95  5157.5   339.3
  5187.7  337.04  5267.8  343.04  5322.1  350.27  5328.4  352.39  5343.5  352.89
#Mann= 7 ,-1 , 0
  4178.1     .05       0  4628.7     .16       0  4675.8     .05       0
  4785.9     .16       0    4896     .12       0  5008.5     .07       0
  5014.5     .12       0
Bank Sta=4991.9,5023.1
XS Rating Curve= 0 ,0
Exp/Cntr=0.3,0.1

Type RM Length L Ch R = 1 ,85414   ,497,497,497
BEGIN DESCRIPTION:
KEECHIE CREEK 132.0
END DESCRIPTION:
XS GIS Cut Line= 3
      3732999.56     10659510.19      3731999.61     10659610.19
      3731399.58     10659260.17
#Sta/Elev= 30
  3983.4  366.25  4053.7  363.84  4194.8  354.81    4324   347.6  4538.6  341.69
  4570.7  342.73  4634.1  341.61  4639.1  343.25  4793.4  337.45  4876.3  334.54
  4978.3  334.66  4985.8  329.17  4991.2  329.17  4993.2  327.55  4995.9  327.05
  4999.2  327.55  5011.5  329.07  5017.7   333.2  5023.5  334.65  5029.1  334.24
  5039.2  333.57  5060.7   338.5  5076.4  338.84  5082.2  334.79  5127.3  332.99
  5279.8  333.63  5405.1  338.84    5499  346.87  5520.9   350.7    5683  368.16
#Mann= 9 ,-1 , 0
  3983.4     .05       0  4194.8     .16       0    4324     .05       0
  4570.7     .16       0  4793.4     .05       0  4876.3     .16       0
  4993.2     .07       0  4999.2     .16       0  5029.1     .12       0
Bank Sta=4978.3,5023.5
XS Rating Curve= 0 ,0
Exp/Cntr=0.3,0.1

Type RM Length L Ch R = 1 ,84917   ,490,490,490
BEGIN DESCRIPTION:
KEECHIE CREEK 131.0
END DESCRIPTION:
XS GIS Cut Line= 3
      3732699.57     10659460.18      3732199.61     10659310.19
      3731649.62     10658860.19
#Sta/Elev= 30
  4512.6  351.13  4554.3  350.04  4562.2  348.57  4567.4  349.23  4606.5  346.03
  4649.1  344.43  4730.8  340.34  4815.3  336.62  4880.6  336.29  4898.9  338.37
  4913.6  337.36  4971.9  328.99  4979.8  334.13    4985   325.6  4989.8  325.59
  4992.6  325.09  4995.8  325.59  5012.8  326.19  5024.1  334.62  5203.3  333.61
  5219.1  332.42  5233.4  333.58  5282.9   333.8  5305.2  332.28  5332.5  333.97
  5354.7  338.29  5468.1  351.12  5496.8  352.53  5610.3  362.48  5745.2  370.11
#Mann= 6 ,-1 , 0
  4512.6     .16       0  4649.1     .05       0  4730.8     .16       0
  4989.8     .07       0  4995.8     .16       0  5203.3     .12       0
Bank Sta=4979.8,5024.1
XS Rating Curve= 0 ,0
Exp/Cntr=0.3,0.1

Type RM Length L Ch R = 1 ,84427   ,373,373,373
BEGIN DESCRIPTION:
KEECHIE CREEK 130.0
END DESCRIPTION:
XS GIS Cut Line= 3
      3732799.64     10659460.22      3732199.61     10658960.19
      3731699.59     10658810.18
#Sta/Elev= 30
  4184.8  355.54  4227.1  352.19  4271.9  350.56  4304.6  347.88  4440.6  340.53
  4568.2  337.14  4596.8  338.11  4611.2  336.21  4661.9  336.24  4677.6  335.86
  4802.6  334.42  4880.6  333.52  4894.9  331.61  4900.3  332.83  4958.7  332.96
  4976.3  331.87  4994.2  324.31  4996.9  323.81  5000.2  324.31  5007.6  324.35
  5015.5  326.59  5028.5  332.36  5053.7  331.59    5092  336.56  5125.1  337.43
  5152.9  340.96  5216.4  344.94  5224.3  346.85  5295.6  353.51  5487.9  367.89
#Mann= 9 ,-1 , 0
  4184.8     .12       0  4271.9     .16       0  4304.6     .12       0
  4661.9     .16       0  4677.6     .12       0  4802.6     .16       0
  4900.3     .12       0  4994.2     .07       0  5000.2     .12       0
Bank Sta=4958.7,5028.5
XS Rating Curve= 0 ,0
Exp/Cntr=0.3,0.1

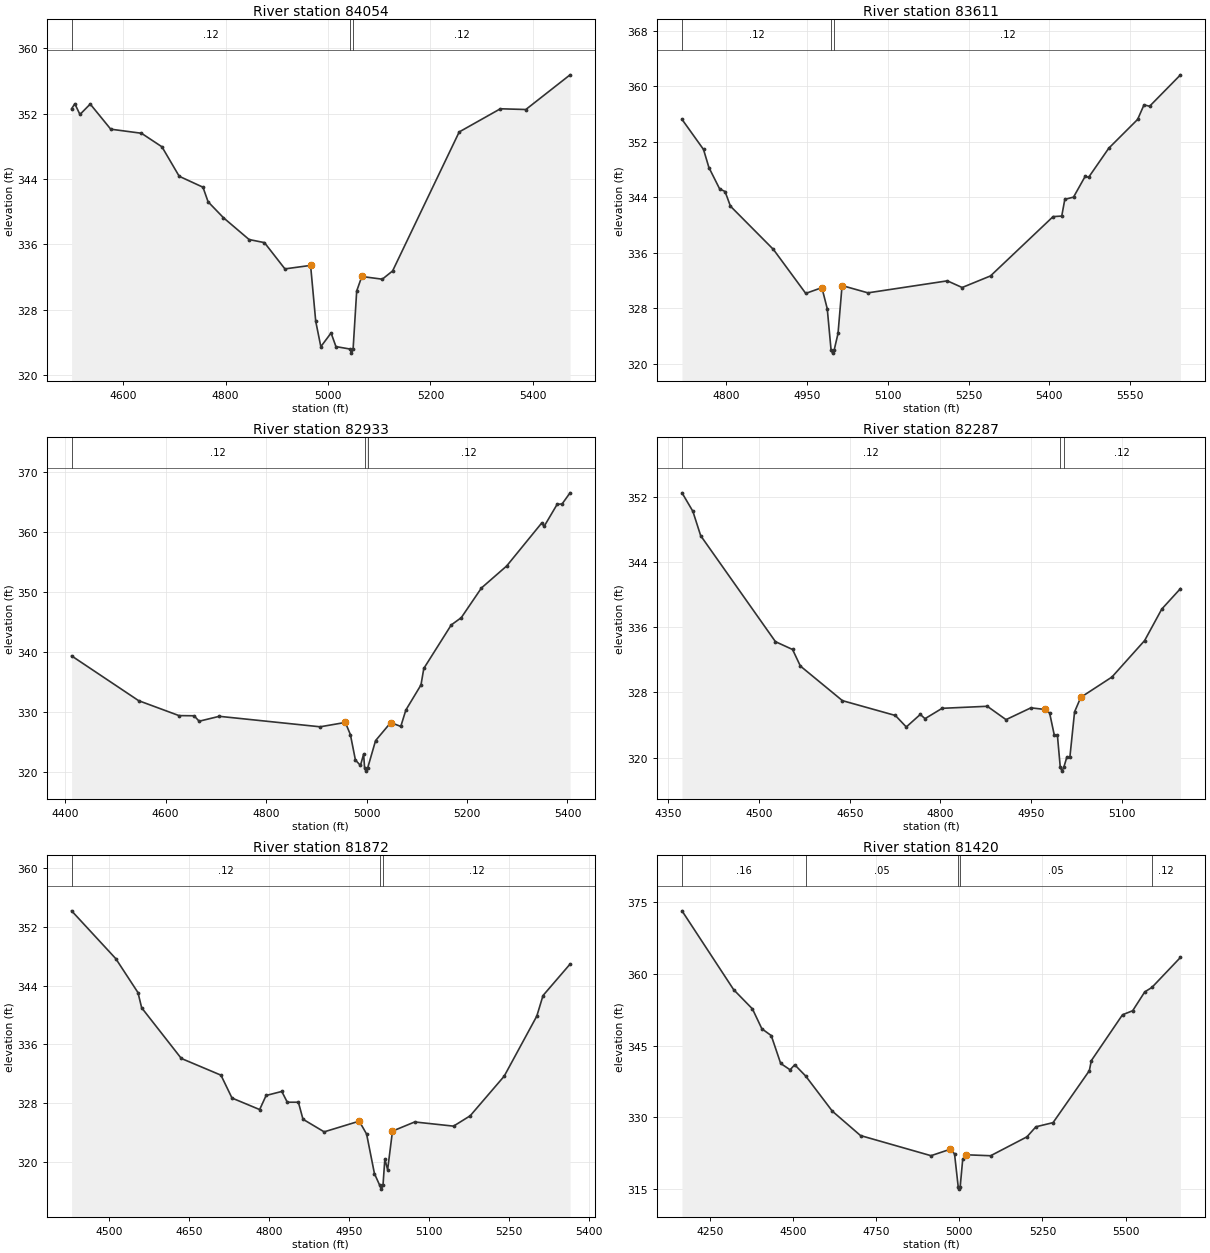
Type RM Length L Ch R = 1 ,84054   ,443,443,443
BEGIN DESCRIPTION:
KEECHIE CREEK 129.0
END DESCRIPTION:
XS GIS Cut Line= 2
      3732875.94     10658648.49      3731903.24      10658679.7
#Sta/Elev= 30
  4499.5  352.61  4505.8  353.23  4515.8  351.91  4535.9  353.19  4575.9  350.11
  4635.9  349.61  4675.9  347.95  4709.6  344.34    4756     343    4766  341.21
    4796  339.26    4846  336.59    4876  336.21    4916  332.99  4966.1  333.42
  4976.1  326.58  4986.1  323.46  5006.1  325.14  5015.6  323.47  5043.1  323.17
  5045.9  322.67  5049.1  323.17  5056.1  330.28  5066.1  332.06  5106.1  331.73
  5126.2  332.74  5256.2  349.77  5336.6  352.61  5386.3  352.52  5472.7  356.77
#Mann= 3 ,-1 , 0
  4499.5     .12       0  5043.1     .07       0  5049.1     .12       0
Bank Sta=4966.1,5066.1
XS Rating Curve= 0 ,0
Exp/Cntr=0.3,0.1

Type RM Length L Ch R = 1 ,83611   ,678,678,678
BEGIN DESCRIPTION:
KEECHIE CREEK 128.0
END DESCRIPTION:
XS GIS Cut Line= 3
      3732649.65     10658310.19      3732349.61     10658310.19
      3731799.64     10658610.17
#Sta/Elev= 30
  4717.3  355.25  4757.3  350.91  4767.3  348.31  4787.3  345.22  4797.3  344.85
  4807.3  342.74  4887.3  336.49  4947.3  330.16  4977.3  330.99  4987.3  327.94
  4994.3  322.05  4997.1  321.55  5000.3  322.05  5007.3  324.39  5014.8  331.29
  5062.9  330.24  5210.5  331.97    5238  331.01  5290.7  332.68    5407  341.23
  5423.1  341.31  5428.8  343.72    5445  344.04  5466.8  347.06    5473  346.89
  5510.5  351.09  5564.1  355.24    5576  357.34  5586.4  357.14  5643.8  361.67
#Mann= 3 ,-1 , 0
  4717.3     .12       0  4994.3     .07       0  5000.3     .12       0
Bank Sta=4977.3,5014.8
XS Rating Curve= 0 ,0
Exp/Cntr=0.3,0.1

Type RM Length L Ch R = 1 ,82933   ,646,646,646
BEGIN DESCRIPTION:
KEECHIE CREEK 127.0
END DESCRIPTION:
XS GIS Cut Line= 2
      3732632.62     10657874.07      3731643.82     10657790.81
#Sta/Elev= 30
  4412.9  339.33  4546.4  331.85  4626.7  329.36  4656.8  329.33  4666.8  328.42
  4706.9  329.24  4907.7  327.49  4957.8  328.22  4967.9  326.18  4977.9  321.94
  4987.9  321.04  4994.2  322.92  4996.2  320.59    4999  320.09  5002.2  320.59
    5018  325.18  5048.2   328.2  5068.2  327.55  5078.3  330.29  5108.4  334.48
    5114  337.23  5168.6  344.49  5188.6  345.71  5228.8  350.67    5279  354.34
  5348.6   361.5  5353.6  360.96  5379.3  364.61  5389.4  364.71  5405.2  366.55
#Mann= 3 ,-1 , 0
  4412.9     .12       0  4996.2     .07       0  5002.2     .12       0
Bank Sta=4957.8,5048.2
XS Rating Curve= 0 ,0
Exp/Cntr=0.3,0.1

Type RM Length L Ch R = 1 ,82287   ,415,415,415
BEGIN DESCRIPTION:
KEECHIE CREEK 126.0
END DESCRIPTION:
XS GIS Cut Line= 3
      3732749.57      10657110.2      3732149.61     10657260.19
       3731949.6     10657310.19
#Sta/Elev= 30
  4372.4  352.49  4390.4  350.22  4403.3  347.23    4527  334.22  4555.3  333.26
  4568.2  331.23  4637.8  326.98  4725.4  325.16  4743.4  323.75  4766.6  325.29
  4774.4  324.77  4802.7  326.04  4877.4  326.29  4908.4  324.65  4949.6   326.1
  4972.8   325.9  4980.5  325.47  4988.3  322.73  4993.4  322.73  4998.1  318.83
  5000.9  318.33  5004.1  318.83  5008.9  320.02    5014  320.02  5021.8  325.61
  5032.1  327.39  5083.6  329.88  5137.7  334.36  5166.1  338.23    5197  340.74
#Mann= 3 ,-1 , 0
  4372.4     .12       0  4998.1     .07       0  5004.1     .12       0
Bank Sta=4972.8,5032.1
XS Rating Curve= 0 ,0
Exp/Cntr=0.3,0.1

Type RM Length L Ch R = 1 ,81872   ,452,452,452
BEGIN DESCRIPTION:
KEECHIE CREEK 125.0
END DESCRIPTION:
XS GIS Cut Line= 3
       3732749.6     10657060.19      3732199.61     10656910.19
       3731849.6     10657010.19
#Sta/Elev= 30
  4430.2  354.19  4513.1  347.66  4554.6  343.04  4561.5  340.97  4635.8  334.06
  4710.1  331.78  4730.8  328.66  4782.6  327.09  4794.7  329.01  4824.1  329.56
  4834.4  328.09  4855.2  328.09  4863.8  325.77  4903.5  324.05  4969.2  325.51
    4983  323.75  4997.7  318.36  5007.7  316.74  5010.4  316.24  5013.7  316.74
  5017.2  320.35  5022.4  318.88  5031.5  324.15  5073.1   325.4  5145.9  324.83
  5177.1  326.24  5240.8  331.64  5301.9  339.83  5313.6  342.64  5364.3  346.93
#Mann= 3 ,-1 , 0
  4430.2     .12       0  5007.7     .07       0  5013.7     .12       0
Bank Sta=4969.2,5031.5
XS Rating Curve= 0 ,0
Exp/Cntr=0.3,0.1

Type RM Length L Ch R = 1 ,81420   ,424,424,424
BEGIN DESCRIPTION:
KEECHIE CREEK 124.0
END DESCRIPTION:
XS GIS Cut Line= 3
      3732549.62     10655960.18      3731949.61     10656560.19
      3731399.57     10656910.21
#Sta/Elev= 30
  4164.9  373.24  4320.5   356.7    4377  352.67  4405.3  348.51  4433.6  347.08
  4461.9  341.25  4490.2  339.91  4504.3  340.96  4537.2   338.6  4617.5  331.23
  4702.3  326.12  4914.4   321.9    4971  323.22  4985.2  322.32  4996.3  315.39
    4999  314.89  5002.3  315.39  5009.9  321.18  5021.1  322.09  5093.9  321.89
  5203.1  325.85  5230.2  327.96  5281.8  328.83    5391  339.72    5397  341.83
  5490.9  351.45  5521.4  352.29  5557.8  356.24  5579.5  357.19  5665.4  363.48
#Mann= 5 ,-1 , 0
  4164.9     .16       0  4537.2     .05       0  4996.3     .03       0
  5002.3     .05       0  5579.5     .12       0
Bank Sta=4971,5021.1
XS Rating Curve= 0 ,0
Exp/Cntr=0.3,0.1

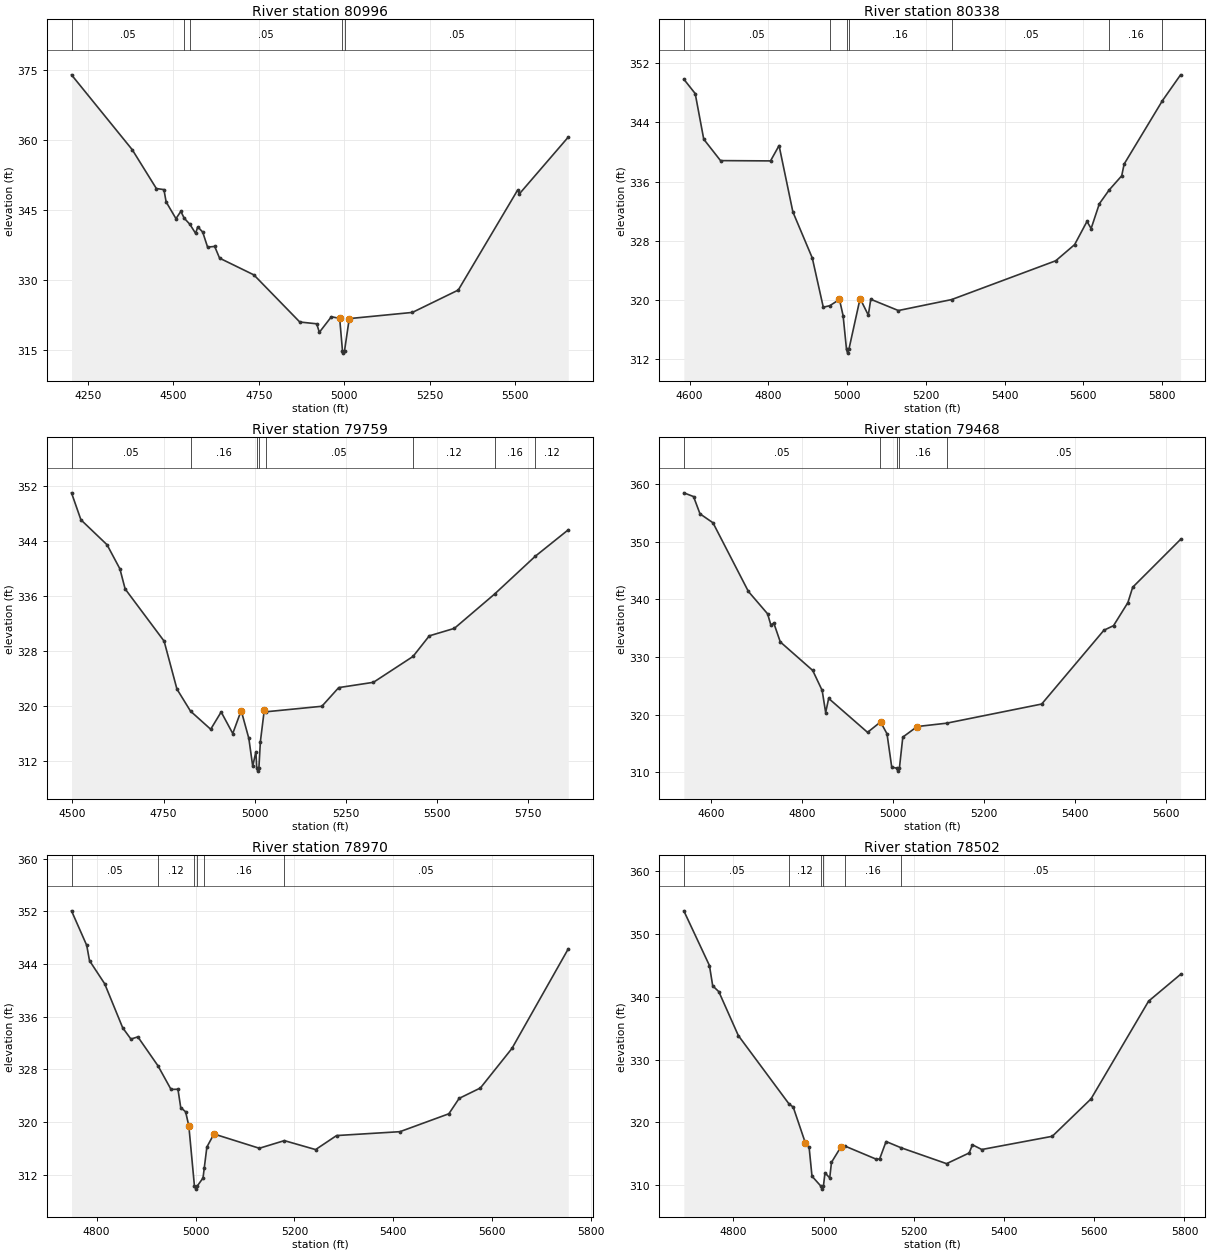
Type RM Length L Ch R = 1 ,80996   ,658,658,658
BEGIN DESCRIPTION:
KEECHIE CREEK 123.0
END DESCRIPTION:
XS GIS Cut Line= 3
      3732299.63     10655760.17      3731699.61     10656260.19
       3731399.6     10656860.21
#Sta/Elev= 30
  4202.8  373.88  4380.5  357.86  4450.8  349.58  4472.9  349.35  4479.4  346.72
  4508.1  343.14  4522.4   344.7  4532.1  343.25  4548.8  341.93  4565.4     340
  4571.9  341.39  4586.2  340.28  4600.5  337.07  4621.3   337.2  4635.6   334.7
  4735.9  331.12    4870  321.05  4919.4  320.67  4927.2  318.85  4962.4  322.18
  4986.6  321.82  4994.8   314.9  4997.6   314.4  5000.8   314.9  5014.6  321.78
  5199.1   323.1  5333.2  327.88  5506.5  349.22  5512.1  348.46  5654.7  360.57
#Mann= 5 ,-1 , 0
  4202.8     .05       0  4532.1     .16       0  4548.8     .05       0
  4994.8     .03       0  5000.8     .05       0
Bank Sta=4986.6,5014.6
XS Rating Curve= 0 ,0
Exp/Cntr=0.3,0.1

Type RM Length L Ch R = 1 ,80338   ,579,579,579
BEGIN DESCRIPTION:
KEECHIE CREEK 122.0
END DESCRIPTION:
XS GIS Cut Line= 3
      3731589.45     10655528.72      3731349.89     10655794.33
      3731079.65     10656657.01
#Sta/Elev= 30
  4585.3  349.82  4614.2  347.88  4635.9  341.72  4678.5  338.83  4805.5  338.79
  4827.2  340.86  4862.3   331.9  4911.6  325.68  4939.5  319.04  4955.9  319.24
  4980.6  320.08  4989.9  317.89  4998.5  313.34  5001.3  312.84  5004.5  313.34
    5033  320.21  5053.9  317.97  5060.1  320.11  5130.2  318.59  5265.5  320.07
    5530  325.31  5577.9  327.49  5609.3  330.62  5619.8  329.66  5640.7  333.01
  5665.7  334.87  5697.5  336.78  5703.6  338.36    5801  346.93    5847  350.41
#Mann= 7 ,-1 , 0
  4585.3     .05       0  4955.9     .16       0  4998.5     .07       0
  5004.5     .16       0  5265.5     .05       0  5665.7     .16       0
    5801     .05       0
Bank Sta=4980.6,5033
XS Rating Curve= 0 ,0
Exp/Cntr=0.3,0.1

Type RM Length L Ch R = 1 ,79759   ,291,291,291
BEGIN DESCRIPTION:
KEECHIE CREEK 121.0
END DESCRIPTION:
XS GIS Cut Line= 3
      3731407.17       10655461.      3731084.26     10655726.62
      3730188.39     10656023.51
#Sta/Elev= 30
  4497.7  351.03  4523.5   347.1  4595.2  343.46  4630.4  339.95  4644.7  337.03
  4751.6  329.42  4786.8  322.43    4824  319.22  4879.3  316.58    4908   319.1
  4939.8  315.96  4962.9  319.31  4983.9  315.24  4994.5   311.2  5003.2   313.3
  5005.5  310.98  5008.2  310.48  5011.5  310.98  5015.5  314.76  5026.1  319.33
  5029.7  319.12  5184.1  319.93  5230.3  322.65  5325.4  323.42    5434  327.19
  5478.6  330.19  5547.3  331.28  5657.4  336.27  5769.2  341.79  5859.6  345.64
#Mann= 8 ,-1 , 0
  4497.7     .05       0    4824     .16       0  5005.5     .07       0
  5011.5     .16       0  5029.7     .05       0    5434     .12       0
  5657.4     .16       0  5769.2     .12       0
Bank Sta=4962.9,5026.1
XS Rating Curve= 0 ,0
Exp/Cntr=0.3,0.1

Type RM Length L Ch R = 1 ,79468   ,498,498,498
BEGIN DESCRIPTION:
KEECHIE CREEK 120.0
END DESCRIPTION:
XS GIS Cut Line= 3
      3731299.58     10655210.21      3730949.61     10655510.19
      3730349.61     10655710.19
#Sta/Elev= 30
  4539.2  358.54  4560.6  357.89  4574.8  354.89  4603.4  353.33  4681.3   341.4
  4723.6  337.51  4730.7  335.58  4737.3  335.89  4751.5  332.63  4822.9  327.67
  4843.7  324.19  4851.4  320.35    4858  322.81  4943.6  316.91  4970.7  318.62
  4972.2  318.72  4986.4  316.66  4996.8  310.89  5007.7  310.67  5010.4  310.17
  5013.7  310.67  5021.2  316.08  5052.8  317.92  5117.5   318.5  5326.9  321.83
  5463.9  334.66    5485  335.45  5516.6  339.46  5527.2  342.13  5632.6  350.45
#Mann= 5 ,-1 , 0
  4539.2     .05       0  4970.7     .16       0  5007.7     .07       0
  5013.7     .16       0  5117.5     .05       0
Bank Sta=4972.2,5052.8
XS Rating Curve= 0 ,0
Exp/Cntr=0.3,0.1

Type RM Length L Ch R = 1 ,78970   ,468,468,468
BEGIN DESCRIPTION:
KEECHIE CREEK 119.0
END DESCRIPTION:
XS GIS Cut Line= 3
      3731049.64     10654960.17      3730849.61     10655060.19
      3730349.59     10655660.21
#Sta/Elev= 30
  4749.2  352.09    4780  346.84  4785.6  344.52  4816.3  341.01  4852.7  334.32
  4869.4   332.6  4883.4  332.94  4924.1  328.54  4950.5  324.95  4964.5  324.98
  4970.1   322.2    4980  321.55  4986.5  319.41  4997.8   310.3  5000.6   309.8
  5003.8   310.3  5015.2  311.49  5017.6  312.94    5023   316.2  5037.3  318.18
  5129.1  316.01  5179.7  317.17  5242.9  315.81  5285.3  317.94  5413.5  318.53
  5512.4  321.25  5533.2  323.59  5576.2  325.17    5640  331.18  5753.9  346.31
#Mann= 6 ,-1 , 0
  4749.2     .05       0  4924.1     .12       0  4997.8     .07       0
  5003.8     .12       0  5017.6     .16       0  5179.7     .05       0
Bank Sta=4986.5,5037.3
XS Rating Curve= 0 ,0
Exp/Cntr=0.3,0.1

Type RM Length L Ch R = 1 ,78502   ,493,493,493
BEGIN DESCRIPTION:
KEECHIE CREEK 118.0
END DESCRIPTION:
XS GIS Cut Line= 3
      3730799.58     10654560.21      3730549.61     10654760.19
      3730049.64     10655360.16
#Sta/Elev= 30
  4690.3  353.65  4747.1  344.95  4754.3  341.73  4767.9  340.79  4811.1  333.82
  4923.1  322.98  4932.8  322.44    4960  316.68    4968  316.06  4974.4  311.46
  4993.8   309.9  4996.6   309.4  4999.8   309.9  5003.2     312  5013.7  311.18
  5017.6  313.66  5038.4   316.1  5047.7  316.24  5116.5  314.17  5124.3  314.19
  5138.6  316.97  5171.4  315.99  5272.7  313.45  5322.8  315.15    5330  316.45
  5350.8   315.7    5507   317.8  5592.9  323.75  5720.5  339.29  5791.4  343.55
#Mann= 6 ,-1 , 0
  4690.3     .05       0  4923.1     .12       0  4993.8     .07       0
  4999.8     .12       0  5047.7     .16       0  5171.4     .05       0
Bank Sta=4960,5038.4
XS Rating Curve= 0 ,0
Exp/Cntr=0.3,0.1

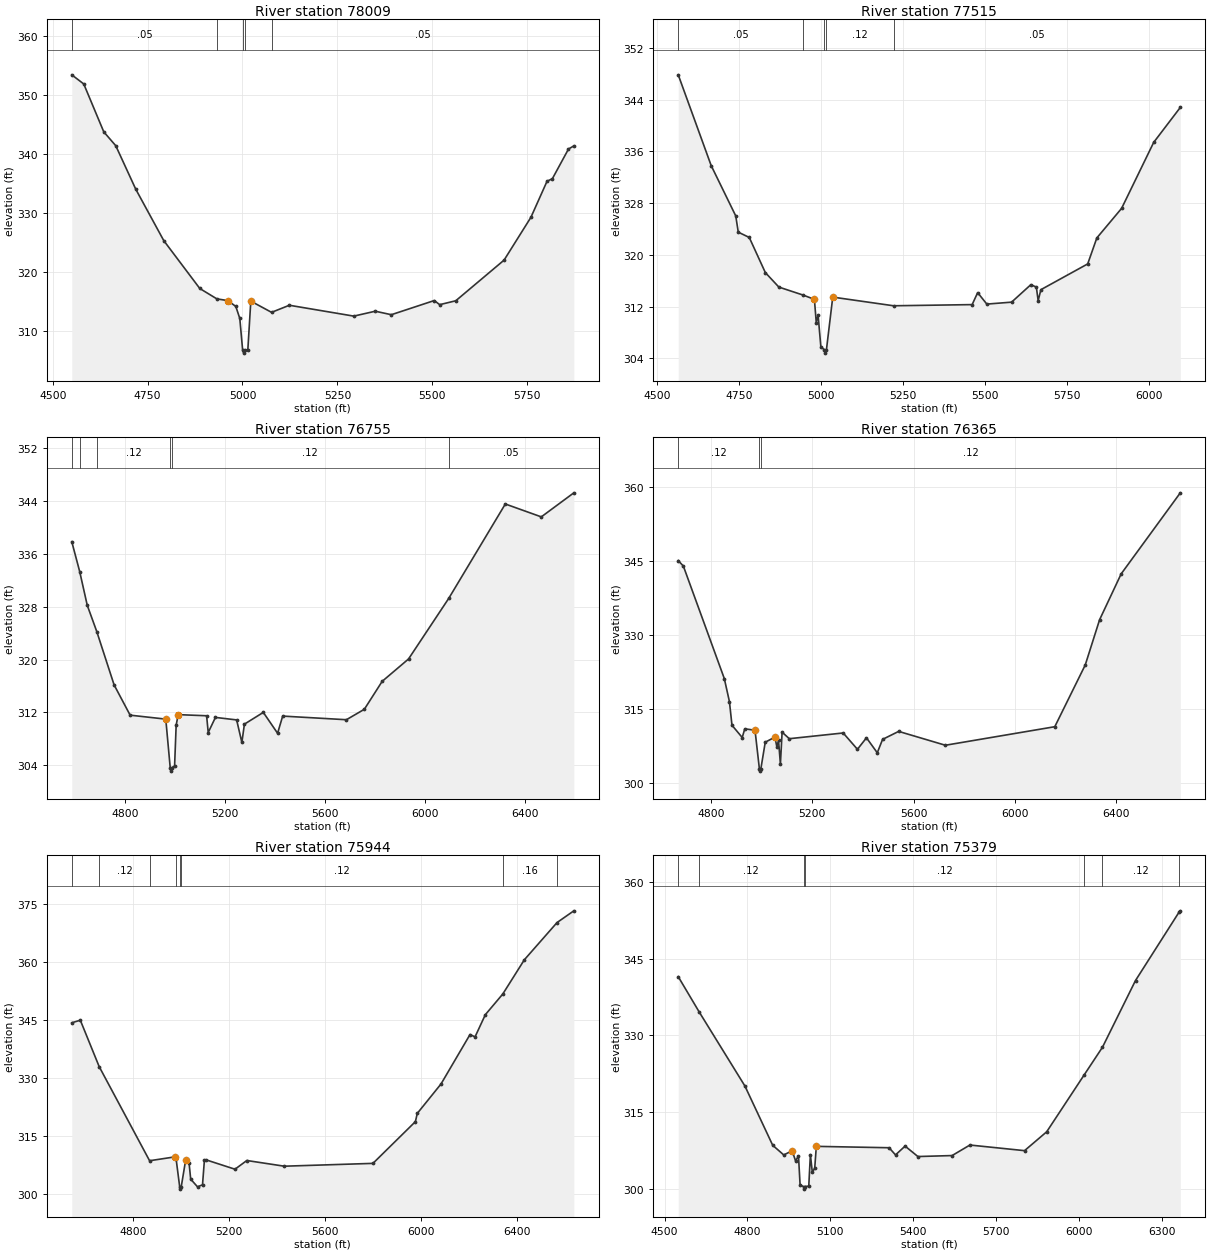
Type RM Length L Ch R = 1 ,78009   ,494,494,494
BEGIN DESCRIPTION:
KEECHIE CREEK 117.0
END DESCRIPTION:
XS GIS Cut Line= 3
      3730649.58      10654310.2      3730199.61     10654460.19
      3729599.64     10655060.16
#Sta/Elev= 30
  4550.2   353.4  4581.8  351.85  4634.5  343.74  4666.1  341.39  4718.8  334.02
  4792.6  325.31  4887.5   317.2  4932.5  315.44  4961.3  315.15  4982.4  314.16
  4992.9  312.12  5000.4  306.75  5003.2  306.25  5006.4  306.75    5014  306.75
  5021.9  315.06  5076.6  313.16  5123.5  314.36  5293.2  312.52  5349.8  313.35
  5392.2  312.76  5505.3  315.16  5519.5  314.46  5561.9  315.12  5689.2  322.01
  5759.9  329.26  5802.3  335.36  5816.5  335.81  5858.9  340.83    5873  341.36
#Mann= 5 ,-1 , 0
  4550.2     .05       0  4932.5     .12       0  5000.4     .07       0
  5006.4     .12       0  5076.6     .05       0
Bank Sta=4961.3,5021.9
XS Rating Curve= 0 ,0
Exp/Cntr=0.3,0.1

Type RM Length L Ch R = 1 ,77515   ,760,760,760
BEGIN DESCRIPTION:
KEECHIE CREEK 116.0
END DESCRIPTION:
XS GIS Cut Line= 3
      3730449.65     10653960.18      3730049.61     10654060.19
       3729549.6      10655060.2
#Sta/Elev= 30
  4565.5  347.83    4666  333.79  4740.8  326.02  4748.5  323.51    4782  322.69
    4831  317.26  4872.2  315.02  4945.8  313.79  4980.6  313.12  4986.2  309.54
  4991.8  310.69  5000.2  305.81  5011.2  305.31  5013.9  304.81  5017.2  305.31
  5036.5  313.47  5221.8  312.13  5461.4  312.31  5478.2  314.16  5506.1  312.39
  5581.6  312.69  5640.3  315.39  5657.1  315.02  5662.6  312.92    5671  314.62
  5813.6   318.6  5841.5  322.62    5917  327.19  6014.8  337.39  6095.9  342.79
#Mann= 5 ,-1 , 0
  4565.5     .05       0  4945.8     .12       0  5011.2     .07       0
  5017.2     .12       0  5221.8     .05       0
Bank Sta=4980.6,5036.5
XS Rating Curve= 0 ,0
Exp/Cntr=0.3,0.1

Type RM Length L Ch R = 1 ,76755   ,390,390,390
BEGIN DESCRIPTION:
KEECHIE CREEK 115.0
END DESCRIPTION:
XS GIS Cut Line= 3
      3729980.13     10653382.83      3729563.43     10653914.12
      3729287.39     10655221.39
#Sta/Elev= 30
  4586.2  337.85  4617.9  333.33  4648.2  328.22  4686.4  324.24  4755.8  316.17
    4820  311.59  4962.8  310.99  4980.6  303.62  4983.4  303.12  4986.6  303.62
  4998.1   303.9  5004.4  310.07  5012.5  311.67  5126.4   311.5  5132.8  308.96
  5161.7  311.25  5246.7  310.87  5267.6  307.46  5277.8  310.23  5353.5  312.01
  5410.7  308.85  5431.1  311.45  5686.4   310.9  5758.2  312.48  5829.7  316.71
  5935.2  320.09  6096.4  329.27    6323  343.55  6467.1   341.6  6597.5  345.24
#Mann= 6 ,-1 , 0
  4586.2     .12       0  4617.9     .16       0  4686.4     .12       0
  4980.6     .07       0  4986.6     .12       0  6096.4     .05       0
Bank Sta=4962.8,5012.5
XS Rating Curve= 0 ,0
Exp/Cntr=0.3,0.1

Type RM Length L Ch R = 1 ,76365   ,421,421,421
BEGIN DESCRIPTION:
KEECHIE CREEK 114.0
END DESCRIPTION:
XS GIS Cut Line= 3
      3729599.61     10653210.22      3729549.61     10653560.19
      3728349.61     10654660.18
#Sta/Elev= 30
  4670.7  345.16  4690.9  344.05  4852.5  321.23  4872.7  316.56  4882.8  311.76
  4923.2  309.27  4933.3  311.03  4973.7  310.75  4990.9  302.95  4993.7  302.45
  4996.9  302.95  5014.1  308.32  5052.3  309.35  5059.7  307.43  5066.5  308.67
  5073.9  303.88  5080.6  310.35    5109  309.03  5321.7  310.19  5377.9  306.88
  5413.6  309.21  5456.2  306.17  5477.1  308.89  5540.6  310.51    5725   307.7
  6156.7  311.46  6276.9  323.98  6333.6  333.17  6418.7  342.47  6652.1  358.91
#Mann= 3 ,-1 , 0
  4670.7     .12       0  4990.9     .07       0  4996.9     .12       0
Bank Sta=4973.7,5052.3
XS Rating Curve= 0 ,0
Exp/Cntr=0.3,0.1

Type RM Length L Ch R = 1 ,75944   ,565,565,565
BEGIN DESCRIPTION:
KEECHIE CREEK 113.0
END DESCRIPTION:
XS GIS Cut Line= 3
      3729499.61     10653160.18      3729149.61     10653560.19
      3728149.59     10654760.21
#Sta/Elev= 30
  4543.4  344.29    4579  344.96  4657.7  332.97  4867.9  308.67  4975.7  309.69
  4978.4  309.19  4993.6  301.84  4996.4  301.34  4999.6  301.84  5018.4  308.89
  5032.7  307.97  5039.3  303.92  5067.8  301.93  5088.6  302.46  5096.4  308.77
  5102.9  308.91    5224  306.48  5273.4  308.73  5429.6  307.26  5799.3  307.99
  5976.3  318.77  5984.2   320.9  6083.1  328.49  6204.1  341.26    6225  340.65
  6267.9  346.38  6340.8  351.73  6430.6  360.56  6566.9  370.17    6637   373.2
#Mann= 8 ,-1 , 0
  4543.4     .16       0  4657.7     .12       0  4867.9     .16       0
  4978.4     .12       0  4993.6     .07       0  4999.6     .12       0
  6340.8     .16       0  6566.9     .12       0
Bank Sta=4975.7,5018.4
XS Rating Curve= 0 ,0
Exp/Cntr=0.3,0.1

Type RM Length L Ch R = 1 ,75379   ,551,551,551
BEGIN DESCRIPTION:
KEECHIE CREEK 112.0
END DESCRIPTION:
XS GIS Cut Line= 3
      3729049.61     10652910.17      3728899.61     10653310.19
      3728199.59     10654510.22
#Sta/Elev= 30
  4549.7  341.48  4625.3   334.6  4790.9  320.11  4891.5  308.52  4931.5  306.63
  4961.8  307.45  4974.2  305.47  4984.8  306.45  4990.6  300.73  5003.3  300.45
    5006  299.95  5009.3  300.45    5022  300.55  5027.8   306.7  5034.8  303.24
  5043.5  304.04  5049.3  308.31  5312.6  308.04  5335.8  306.64  5370.5  308.36
  5416.8  306.32  5540.5  306.51    5605  308.57  5802.6  307.47  5882.8  311.16
    6019  322.33  6084.6  327.69  6204.1  340.73  6362.8  354.19  6366.2  354.35
#Mann= 7 ,-1 , 0
  4549.7     .16       0  4625.3     .12       0  5003.3     .07       0
  5009.3     .12       0    6019     .16       0  6084.6     .12       0
  6362.8     .16       0
Bank Sta=4961.8,5049.3
XS Rating Curve= 0 ,0
Exp/Cntr=0.3,0.1