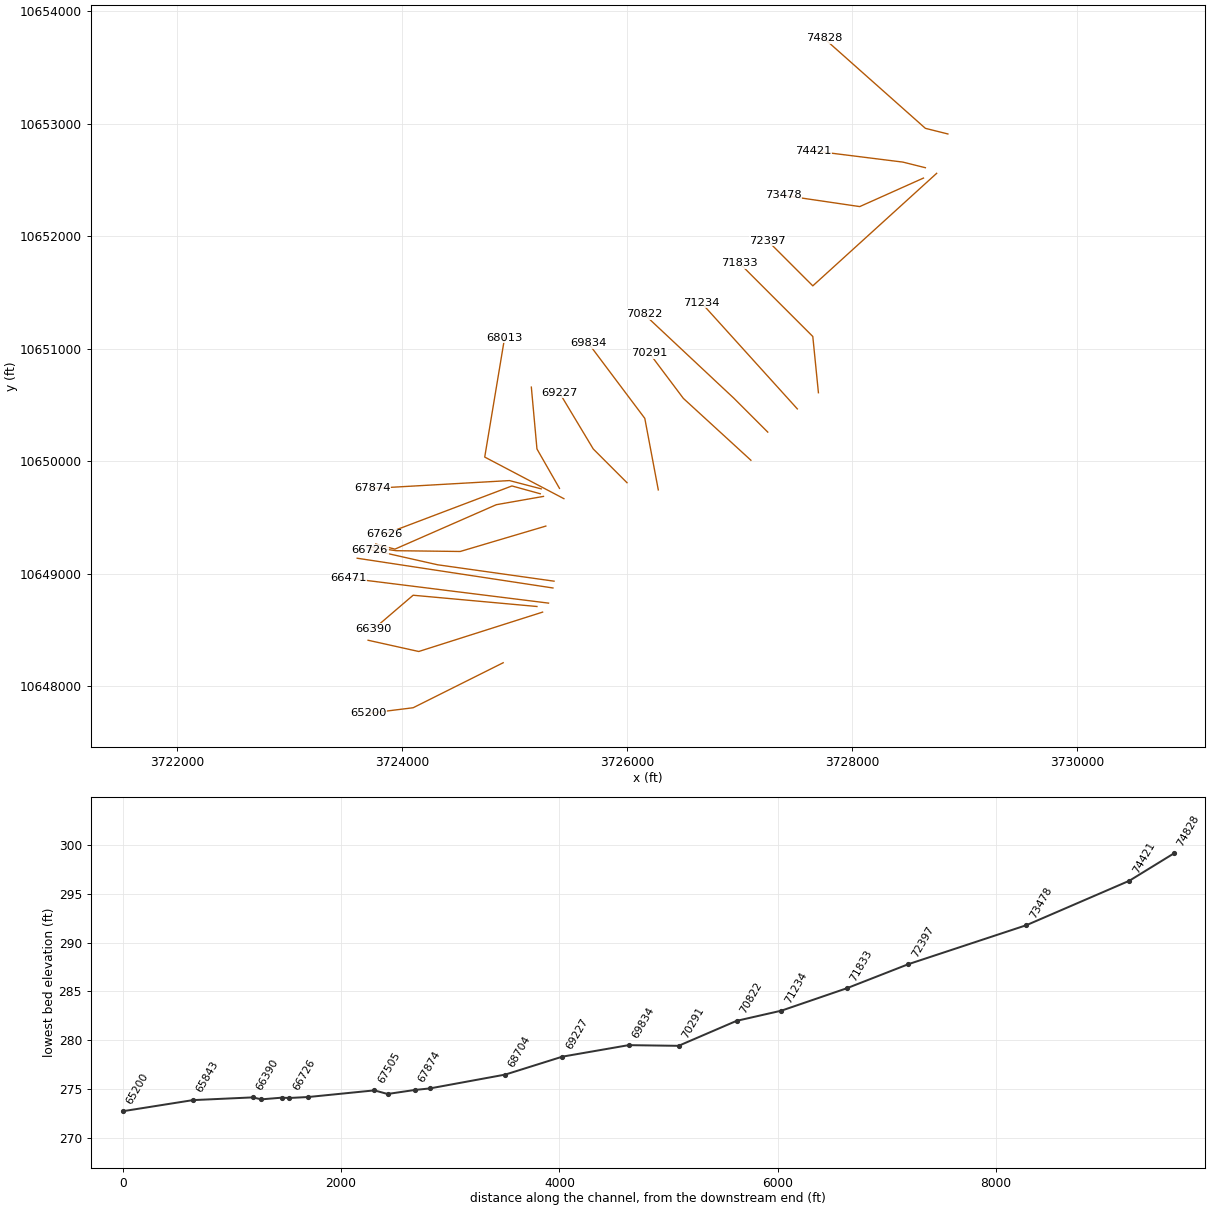
HEC-RAS study KEECHIE CREEK.prj: KEECHIE CREEK Base Level Engineering

--- KEECHIE CREEK.g01 (geometry) --- (continued)

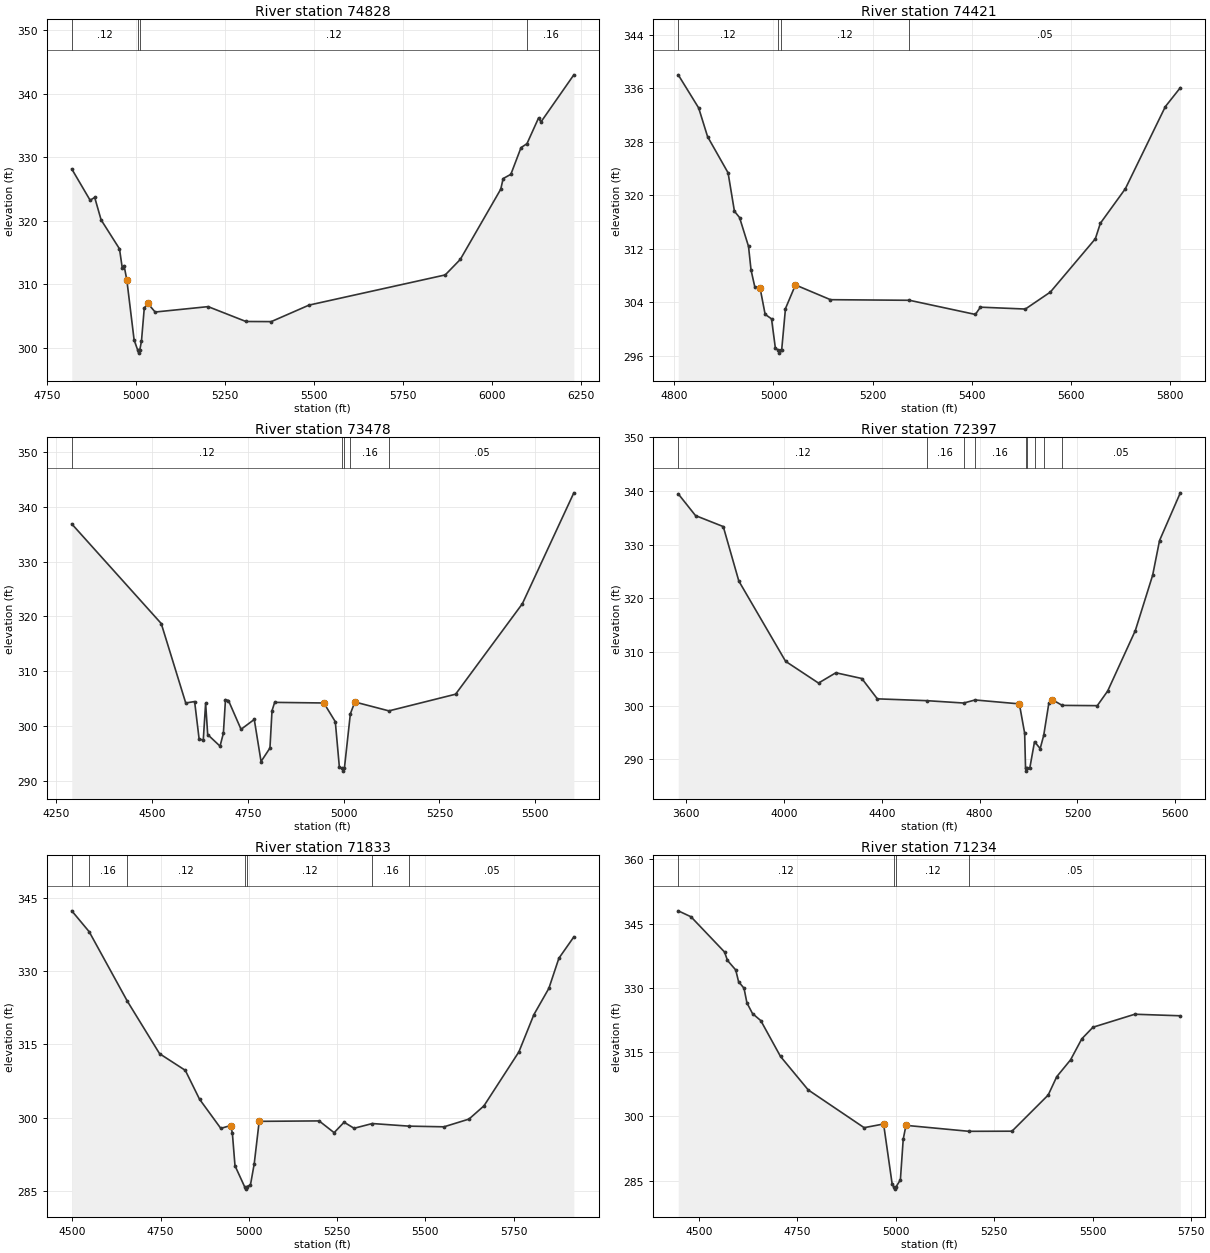
Type RM Length L Ch R = 1 ,74828   ,407,407,407
BEGIN DESCRIPTION:
KEECHIE CREEK 111.0
END DESCRIPTION:
XS GIS Cut Line= 3
      3728849.59     10652910.19      3728649.61     10652960.19
       3727749.6     10653760.19
#Sta/Elev= 30
  4819.5  328.15    4871  323.23  4883.9  323.67  4901.9  320.14  4953.5  315.58
  4961.2  312.62  4966.4  312.94  4974.1   310.7  4994.7   301.2  5004.6  299.66
  5007.3  299.16  5010.6  299.66  5015.3  301.06  5023.1  306.22  5032.7  307.02
  5053.6  305.63  5202.5  306.48  5308.7  304.14  5379.8  304.12    5486  306.72
  5868.5  311.47  5910.8  313.91  6024.5  324.97  6031.2  326.64  6052.9  327.31
  6081.4  331.51  6098.1  332.13  6130.7  336.18  6137.4  335.55  6229.8  342.97
#Mann= 4 ,-1 , 0
  4819.5     .12       0  5004.6     .07       0  5010.6     .12       0
  6098.1     .16       0
Bank Sta=4974.1,5032.7
XS Rating Curve= 0 ,0
Exp/Cntr=0.3,0.1

Type RM Length L Ch R = 1 ,74421   ,943,943,943
BEGIN DESCRIPTION:
KEECHIE CREEK 110.0
END DESCRIPTION:
XS GIS Cut Line= 3
      3728649.56      10652610.2      3728449.61     10652660.19
      3727649.64     10652760.18
#Sta/Elev= 30
    4808  338.02  4849.2  333.06  4867.2  328.76  4908.5  323.35  4921.3   317.6
  4931.6  316.66  4949.7  312.34  4954.8   308.8  4962.6   306.2  4972.9  306.15
  4983.2  302.17  4996.1  301.49  5003.8  297.14  5008.5  296.86  5011.3  296.36
  5014.5  296.86  5016.6  296.86  5024.2  303.03  5044.3  306.57  5114.9  304.36
  5274.2  304.27  5407.1  302.15  5417.2  303.24  5507.9  302.96  5558.3   305.5
    5649  313.48  5659.1   315.8  5709.5  320.97  5790.1  333.26  5820.3  336.09
#Mann= 4 ,-1 , 0
    4808     .12       0  5008.5     .07       0  5014.5     .12       0
  5274.2     .05       0
Bank Sta=4972.9,5044.3
XS Rating Curve= 0 ,0
Exp/Cntr=0.3,0.1

Type RM Length L Ch R = 1 ,73478   ,1081,1081,1081
BEGIN DESCRIPTION:
Mapping XS b58803b3
END DESCRIPTION:
XS GIS Cut Line= 3
      3728632.67     10652518.17       3728066.7      10652264.7
      3727384.39     10652365.14
#Sta/Elev= 30
  4290.7  336.85  4524.1   318.7    4588  304.22  4611.2  304.48  4622.8  297.73
  4633.7   297.4  4639.9  304.17  4645.3  298.46  4677.5  296.35  4686.2   298.7
  4691.7  304.84  4699.5  304.67  4732.3  299.42  4766.8  301.22  4784.5  293.55
  4807.7  296.01  4813.1  302.81    4820  304.33  4948.3  304.22  4978.2  300.81
  4988.8  292.53  4995.9   292.3  4998.6   291.8  5001.9   292.3  5017.5  302.26
  5029.2   304.4  5118.1  302.78    5292  305.82  5466.2  322.31  5600.5  342.52
#Mann= 5 ,-1 , 0
  4290.7     .12       0  4995.9     .07       0  5001.9     .12       0
  5017.5     .16       0  5118.1     .05       0
Bank Sta=4948.3,5029.2
XS Rating Curve= 0 ,0
Exp/Cntr=0.3,0.1

Type RM Length L Ch R = 1 ,72397   ,564,564,564
BEGIN DESCRIPTION:
KEECHIE CREEK 109.0
END DESCRIPTION:
XS GIS Cut Line= 3
      3728749.61     10652560.19      3727649.61     10651560.19
       3727249.6     10651960.19
#Sta/Elev= 30
  3568.3  339.47  3638.9  335.42  3752.4  333.37    3816  323.22  4007.2  308.26
  4141.7  304.21  4212.6  306.13  4318.7  305.06  4382.2  301.27  4584.3  300.93
  4735.3  300.49  4781.6  301.06  4962.7  300.33  4984.3  294.88    4988   288.3
  4990.8   287.8    4994   288.3  5005.2  288.33  5024.7  293.29  5047.8     292
  5062.3  294.48  5083.2  300.46  5097.3  301.11  5137.9  300.05  5281.2     300
  5323.6  302.72  5436.7  313.99  5507.5   324.3  5535.7  330.77  5620.6  339.66
#Mann= 9 ,-1 , 0
  3568.3     .12       0  4584.3     .16       0  4735.3     .12       0
  4781.6     .16       0    4988     .07       0    4994     .16       0
  5024.7     .12       0  5062.3     .16       0  5137.9     .05       0
Bank Sta=4962.7,5097.3
XS Rating Curve= 0 ,0
Exp/Cntr=0.3,0.1

Type RM Length L Ch R = 1 ,71833   ,599,599,599
BEGIN DESCRIPTION:
KEECHIE CREEK 108.0
END DESCRIPTION:
XS GIS Cut Line= 3
       3727699.6     10650610.24      3727649.61     10651110.19
       3726999.6      10651760.2
#Sta/Elev= 30
  4498.7  342.36    4548  338.08    4656  323.85  4747.4  313.08  4820.2  309.67
  4860.4  303.77  4920.7  297.78  4948.4  298.36  4953.4  296.85  4960.9  290.12
  4988.1  285.83  4990.8  285.33  4994.1  285.83  5004.7   286.2  5015.3   290.5
  5029.4  299.22  5199.1  299.31  5241.6   296.9  5269.8  299.04  5298.1   297.8
  5349.7  298.77    5453  298.24  5552.7   298.1  5623.4  299.68  5665.8  302.39
  5764.8  313.46  5807.2  321.08  5849.7  326.48    5878  332.64  5920.4  337.02
#Mann= 7 ,-1 , 0
  4498.7     .12       0    4548     .16       0    4656     .12       0
  4988.1     .07       0  4994.1     .12       0  5349.7     .16       0
    5453     .05       0
Bank Sta=4948.4,5029.4
XS Rating Curve= 0 ,0
Exp/Cntr=0.3,0.1

Type RM Length L Ch R = 1 ,71234   ,412,412,412
BEGIN DESCRIPTION:
KEECHIE CREEK 107.0
END DESCRIPTION:
XS GIS Cut Line= 2
      3727512.16      10650466.6      3726658.03     10651411.87
#Sta/Elev= 30
    4448  347.97  4480.4  346.58  4565.5  338.36    4573  336.39  4593.9  334.17
  4601.1  331.44  4614.9  329.91  4622.3  326.49  4636.5  323.99  4657.5  322.35
  4707.5  313.99  4777.8  306.18  4919.7  297.37  4969.1  298.23  4990.7   284.3
  4994.5  283.53  4997.2  283.03  5000.5  283.53  5011.7   285.2  5018.9  294.69
  5025.9  297.91  5185.7  296.52  5294.9  296.55  5386.8  304.99  5408.4  309.26
  5443.6  313.21    5472   318.1  5500.4  320.81  5606.5  323.84    5722  323.48
#Mann= 4 ,-1 , 0
    4448     .12       0  4994.5     .07       0  5000.5     .12       0
  5185.7     .05       0
Bank Sta=4969.1,5025.9
XS Rating Curve= 0 ,0
Exp/Cntr=0.3,0.1

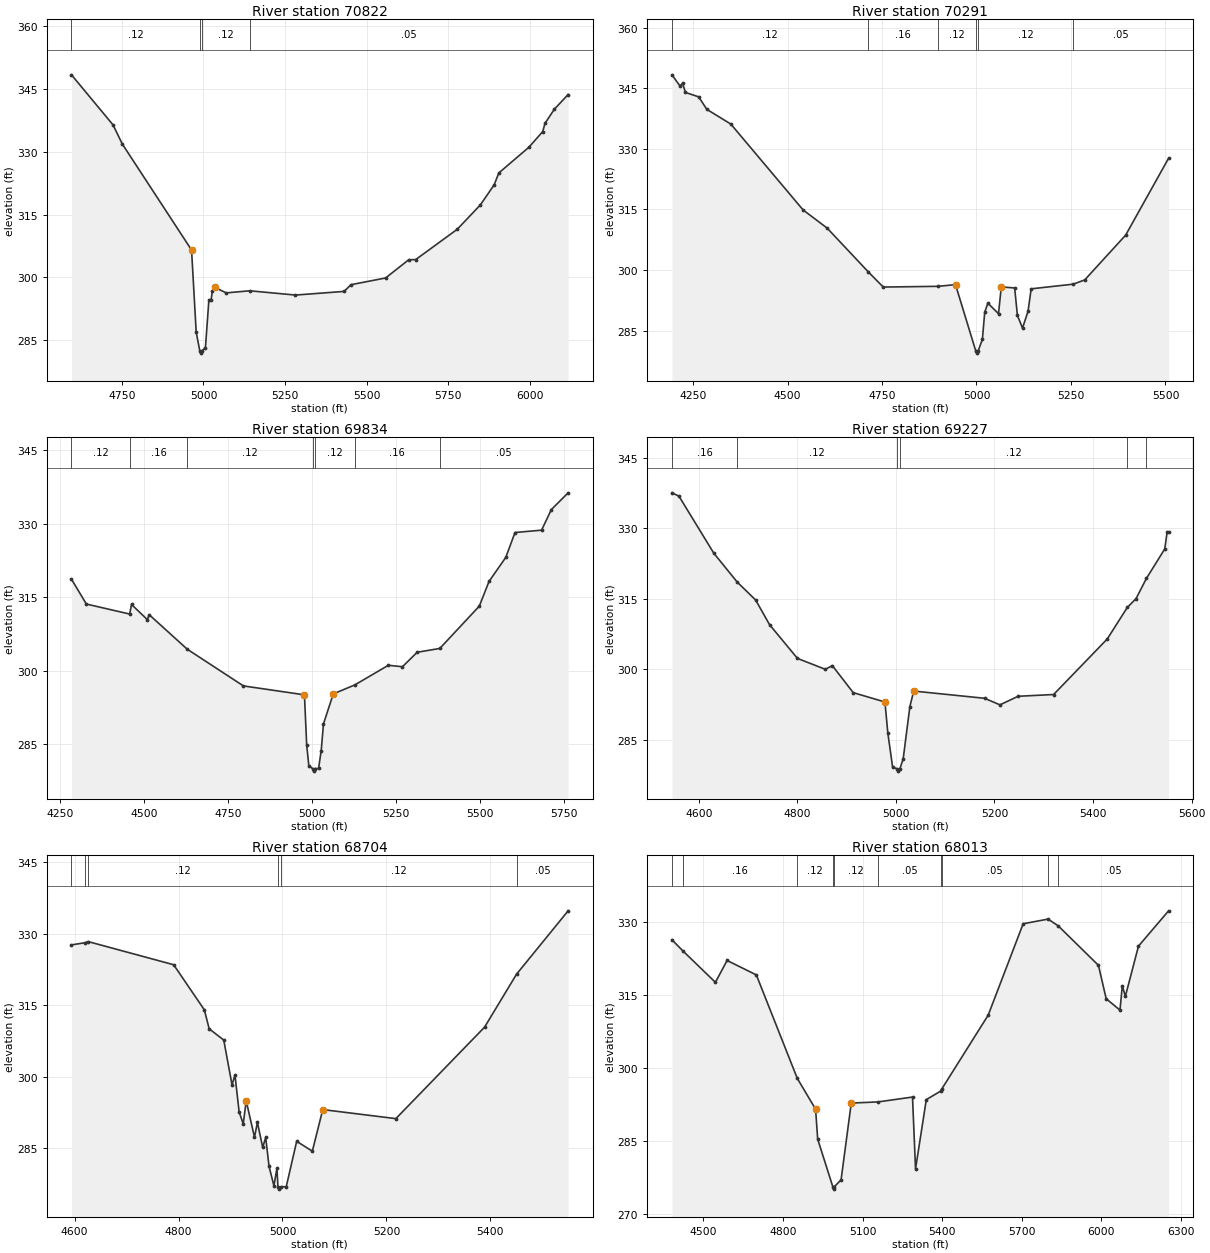
Type RM Length L Ch R = 1 ,70822   ,531,531,531
BEGIN DESCRIPTION:
KEECHIE CREEK 106.0
END DESCRIPTION:
XS GIS Cut Line= 3
      3727249.64     10650260.16      3726949.61     10650560.19
       3726149.6      10651310.2
#Sta/Elev= 30
  4595.8  348.27  4723.1  336.33  4751.4  331.79  4963.5  306.54  4977.7  286.97
  4988.8  282.48  4991.6  281.98  4994.8  282.48    5006   283.3  5016.6   294.7
  5023.5   294.7  5027.2  296.77    5034  297.66  5069.7  296.33  5141.8  296.83
  5281.7  295.81  5430.6  296.68  5451.7  298.28  5557.7  299.88  5628.5  304.22
    5650  304.27    5777  311.47  5847.8  317.27  5890.3  322.09  5904.5   324.9
  5996.3     331  6038.8  334.74  6046.1  336.74  6074.4  340.07  6116.7  343.57
#Mann= 4 ,-1 , 0
  4595.8     .12       0  4988.8     .07       0  4994.8     .12       0
  5141.8     .05       0
Bank Sta=4963.5,5034
XS Rating Curve= 0 ,0
Exp/Cntr=0.3,0.1

Type RM Length L Ch R = 1 ,70291   ,457,457,457
BEGIN DESCRIPTION:
KEECHIE CREEK 105.0
END DESCRIPTION:
XS GIS Cut Line= 3
      3727099.63     10650010.17      3726499.61     10650560.19
      3726199.59     10650960.21
#Sta/Elev= 30
  4194.3  348.33  4215.6  345.56  4222.4  346.25  4229.8  343.97  4264.9  342.88
  4286.5  339.78    4350  336.14  4541.2  314.88  4604.7  310.39  4713.5  299.56
  4753.3  295.78  4898.4  295.96  4944.5  296.38  4998.2  279.92  5000.9  279.42
  5004.2  279.92  5015.6  282.81  5021.8  289.55  5030.1  291.79  5058.3  289.19
  5065.6  295.81    5101  295.56  5108.3  288.74  5121.8  285.62  5136.4  289.78
  5144.7  295.34  5256.1   296.5  5286.4  297.55  5394.7  308.64  5508.3  327.68
#Mann= 6 ,-1 , 0
  4194.3     .12       0  4713.5     .16       0  4898.4     .12       0
  4998.2     .07       0  5004.2     .12       0  5256.1     .05       0
Bank Sta=4944.5,5065.6
XS Rating Curve= 0 ,0
Exp/Cntr=0.3,0.1

Type RM Length L Ch R = 1 ,69834   ,607,607,607
BEGIN DESCRIPTION:
KEECHIE CREEK 104.0
END DESCRIPTION:
XS GIS Cut Line= 3
      3726277.25      10649746.7      3726157.45     10650382.13
      3725657.43     10651048.83
#Sta/Elev= 30
  4283.6  318.65  4327.9  313.59  4456.9  311.55  4462.5   313.5  4509.8   310.4
  4514.9  311.43  4628.8  304.36    4796  296.88  4977.8  295.06  4984.5  284.81
  4990.8  280.63  5002.3  279.99  5005.1  279.49  5008.3  279.99  5019.9  280.03
  5027.8   283.7  5034.5  289.12  5063.7  295.25  5128.1  297.09  5227.8  301.09
  5269.9   300.8  5313.7  303.75  5381.2  304.53  5499.1  313.18  5527.8   318.2
  5577.8  323.11  5605.3  328.19  5684.5  328.67  5713.7  332.88  5763.6  336.29
#Mann= 7 ,-1 , 0
  4283.6     .12       0  4456.9     .16       0  4628.8     .12       0
  5002.3     .07       0  5008.3     .12       0  5128.1     .16       0
  5381.2     .05       0
Bank Sta=4977.8,5063.7
XS Rating Curve= 0 ,0
Exp/Cntr=0.3,0.1

Type RM Length L Ch R = 1 ,69227   ,523,523,523
BEGIN DESCRIPTION:
KEECHIE CREEK 103.0
END DESCRIPTION:
XS GIS Cut Line= 3
      3725999.61     10649810.18      3725699.61     10650110.19
      3725399.59     10650610.22
#Sta/Elev= 30
  4545.8  337.57  4559.9  336.87  4630.7  324.71  4678.3  318.55  4715.5  314.75
  4743.8  309.49  4800.4  302.31  4856.9  299.99  4871.1  300.78  4913.5  295.02
  4977.8  293.03  4983.7  286.41  4993.4  279.15  5002.1  278.81  5004.8  278.31
  5008.1  278.81  5014.8  280.91  5028.4  292.05  5036.2  295.36    5180  293.82
  5211.1  292.42    5248  294.25  5319.9  294.62  5428.8  306.45  5469.6  313.19
  5487.1  315.02  5508.2  319.34  5545.4  325.62  5550.3  329.27  5553.2  329.27
#Mann= 6 ,-1 , 0
  4545.8     .16       0  4678.3     .12       0  5002.1     .07       0
  5008.1     .12       0  5469.6     .16       0  5508.2     .05       0
Bank Sta=4977.8,5036.2
XS Rating Curve= 0 ,0
Exp/Cntr=0.3,0.1

Type RM Length L Ch R = 1 ,68704   ,691,691,691
BEGIN DESCRIPTION:
KEECHIE CREEK 102.0
END DESCRIPTION:
XS GIS Cut Line= 3
      3725399.59     10649760.21      3725199.61     10650110.19
       3725149.6     10650660.24
#Sta/Elev= 30
  4594.1  327.71  4620.7  328.18    4626  328.41  4790.6  323.55  4849.6   314.1
    4859   310.1    4887  307.75  4902.9  298.36  4908.6  300.39  4916.6  292.65
  4924.5  290.17  4930.2     295  4946.1  287.36  4951.8  290.45  4961.9  285.22
  4967.7  287.31  4974.1  281.26  4983.5  277.17  4989.3  280.81  4991.3  276.97
  4994.1  276.47  4997.3  276.97  5007.2  276.97  5027.3   286.5  5057.4  284.43
  5077.5  293.16  5218.1  291.26  5388.8  310.46  5450.3  321.57  5549.5  334.86
#Mann= 6 ,-1 , 0
  4594.1     .05       0  4620.7     .16       0    4626     .12       0
  4991.3     .07       0  4997.3     .12       0  5450.3     .05       0
Bank Sta=4930.2,5077.5
XS Rating Curve= 0 ,0
Exp/Cntr=0.3,0.1

Type RM Length L Ch R = 1 ,68013   ,139,139,139
BEGIN DESCRIPTION:
KEECHIE CREEK 101.0
END DESCRIPTION:
XS GIS Cut Line= 3
      3725438.72     10649668.58      3724735.58     10650038.38
      3724912.66     10651100.87
#Sta/Elev= 30
  4381.4  326.28  4422.5     324  4545.1  317.54  4589.2  322.03  4699.4  319.06
  4853.8  297.79  4922.7  291.48  4930.5  285.33  4987.5  275.55  4990.3  275.05
  4993.5  275.55  5018.7  276.96  5057.1  292.73  5158.4  292.97  5287.9  293.97
  5299.3   279.2  5339.9  293.44  5393.6  295.18  5399.3  295.72  5573.1  310.79
  5704.9  329.57  5798.6  330.53  5836.9  329.15  5988.7  321.03  6017.8  314.17
  6069.8  311.83  6078.6  316.83  6090.1  314.66  6139.5  324.98    6253  332.23
#Mann= 10 ,-1 , 0
  4381.4     .05       0  4422.5     .16       0  4853.8     .12       0
  4987.5     .07       0  4993.5     .12       0  5158.4     .05       0
  5393.6     .16       0  5399.3     .05       0  5798.6     .08       0
  5836.9     .05       0
Bank Sta=4922.7,5057.1
XS Rating Curve= 0 ,0
Exp/Cntr=0.3,0.1

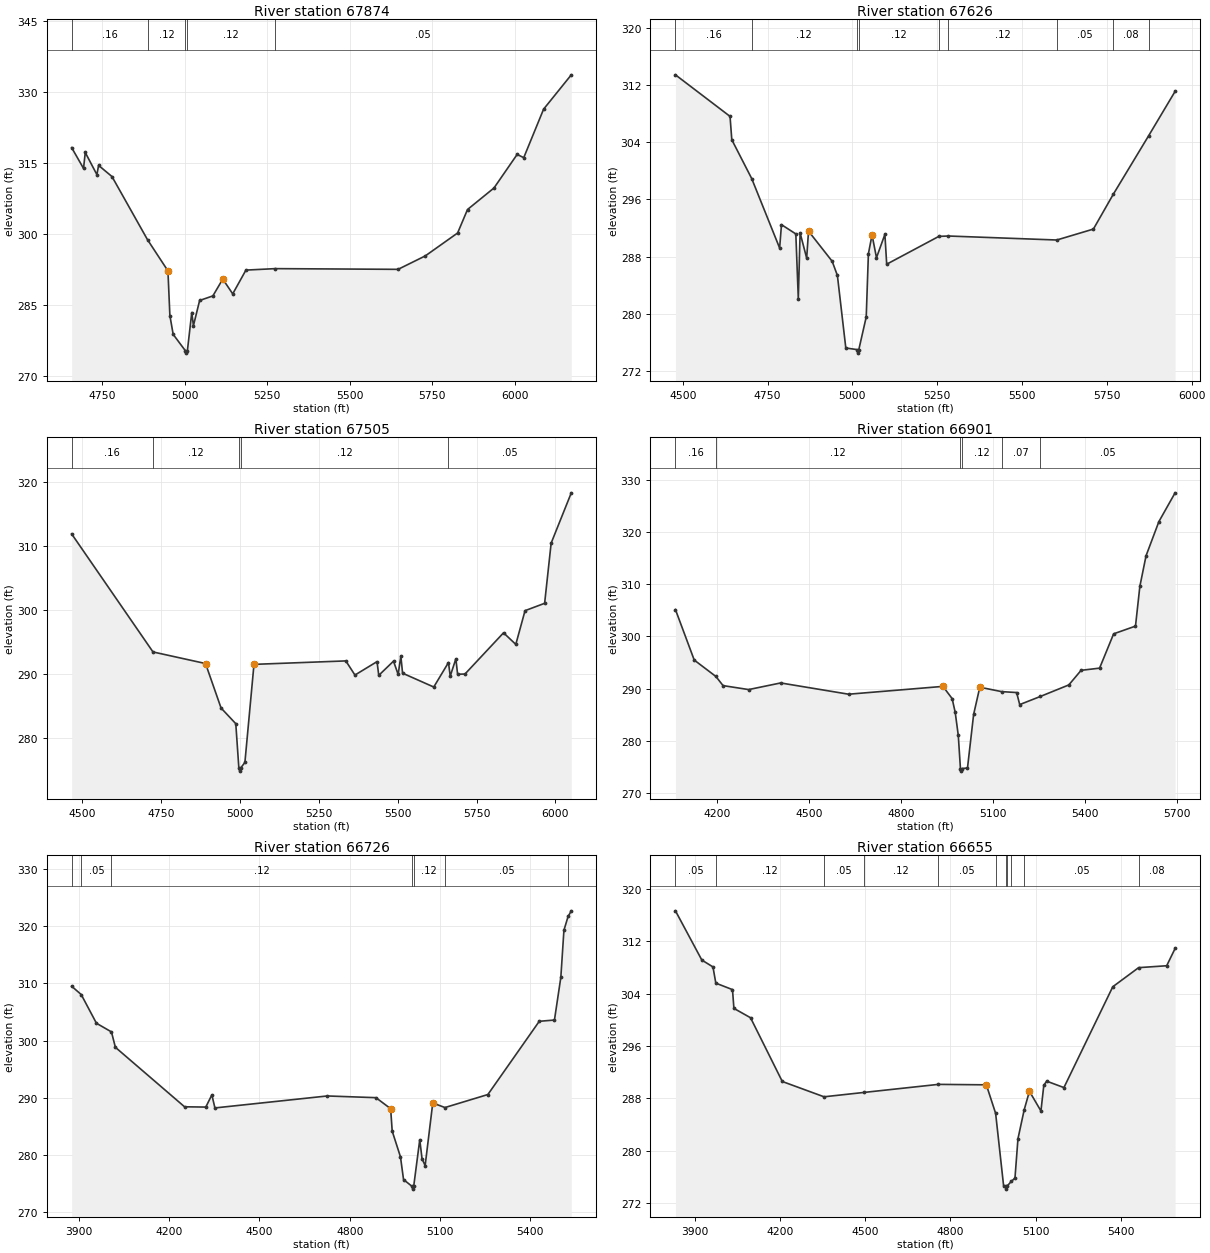
Type RM Length L Ch R = 1 ,67874   ,248,248,248
BEGIN DESCRIPTION:
Mapping XS fce41fd6
END DESCRIPTION:
XS GIS Cut Line= 3
      3725237.58     10649755.58      3724955.47     10649829.37
      3723735.84     10649759.92
#Sta/Elev= 30
  4657.7  318.21  4693.7  313.82  4698.9  317.18  4734.2  312.51  4739.3  314.46
  4779.8  312.11  4887.5  298.79  4949.3  292.23  4955.2  282.81  4965.2  278.84
  5002.2  275.39    5005  274.89  5008.2  275.39  5021.5  283.45  5026.5  280.68
  5045.3  285.99  5085.4  286.95  5115.4   290.5  5145.5  287.38  5185.5  292.39
    5274   292.7  5646.3  292.55  5728.9  295.39  5826.6  300.21  5856.6  305.16
  5936.8   309.7  6006.9  316.77  6026.9  316.09    6087  326.31  6170.9  333.55
#Mann= 5 ,-1 , 0
  4657.7     .16       0  4887.5     .12       0  5002.2     .07       0
  5008.2     .12       0    5274     .05       0
Bank Sta=4949.3,5115.4
XS Rating Curve= 0 ,0
Exp/Cntr=0.3,0.1

Type RM Length L Ch R = 1 ,67626   ,121,121,121
BEGIN DESCRIPTION:
KEECHIE CREEK 100.0
END DESCRIPTION:
XS GIS Cut Line= 3
      3725228.95     10649712.17      3724977.17     10649781.62
       3723844.5     10649351.99
#Sta/Elev= 30
  4478.6  313.45  4639.5  307.63  4644.7  304.36  4703.3  298.93  4785.7  289.19
  4791.1  292.47  4833.4  291.17  4840.7  282.11    4846  291.31  4865.4  287.78
  4870.8  291.56  4940.4  287.35  4955.9  285.36  4980.7   275.2  5013.1  274.98
  5015.9  274.48  5019.1  274.98  5040.9  279.55  5047.3  288.39    5058  291.04
  5071.1  287.84  5095.9  291.11  5101.2  286.93    5255  290.83  5283.2  290.88
  5602.5  290.32  5710.4  291.85  5768.7   296.7    5873   304.9  5951.2  311.13
#Mann= 9 ,-1 , 0
  4478.6     .16       0  4703.3     .12       0  5013.1     .07       0
  5019.1     .12       0    5255     .05       0  5283.2     .12       0
  5602.5     .05       0  5768.7     .08       0    5873     .05       0
Bank Sta=4870.8,5058
XS Rating Curve= 0 ,0
Exp/Cntr=0.3,0.1

Type RM Length L Ch R = 1 ,67505   ,604,604,604
BEGIN DESCRIPTION:
Mapping XS 33e11955
END DESCRIPTION:
XS GIS Cut Line= 4
       3725257.4     10649688.74      3724838.57     10649614.96
      3723937.96     10649219.99      3723767.84     10649265.13
#Sta/Elev= 30
  4465.6  311.91  4723.6  293.47  4890.2  291.66  4939.5  284.71  4986.2  282.26
  4995.9  275.35  4998.7  274.85  5001.9  275.35  5015.1  276.21  5043.9  291.53
  5335.2  292.07  5364.1  289.86  5434.2  291.96  5439.6  289.81  5486.4  292.03
  5501.2  289.95  5509.7  292.83  5515.2  290.15  5614.1  287.99  5660.8  291.82
  5666.3  289.69  5684.2   292.4  5689.7  289.99  5713.1  290.02  5835.4  296.46
  5874.3  294.65  5903.6  299.92  5965.7  301.07  5986.4  310.47  6050.3  318.33
#Mann= 5 ,-1 , 0
  4465.6     .16       0  4723.6     .12       0  4995.9     .07       0
  5001.9     .12       0  5660.8     .05       0
Bank Sta=4890.2,5043.9
XS Rating Curve= 0 ,0
Exp/Cntr=0.3,0.1

Type RM Length L Ch R = 1 ,66901   ,175,175,175
BEGIN DESCRIPTION:
Mapping XS 78fd94ce
END DESCRIPTION:
XS GIS Cut Line= 4
      3725278.26     10649424.86      3724517.83     10649199.16
      3723948.38      10649206.1      3723685.98     10649243.07
#Sta/Elev= 30
  4065.2  305.15  4126.4  295.47    4197  292.32  4220.3  290.57  4303.7  289.81
    4408  291.08  4629.3  288.92  4936.6  290.42  4966.6  288.08  4976.6  285.43
  4986.6  281.02  4993.6  274.67  4996.4  274.17  4999.6  274.67  5016.6  274.77
  5036.6  285.05  5056.7  290.26  5127.6  289.42  5176.7  289.24  5186.7  286.93
    5254  288.49  5346.7   290.7  5386.7   293.5  5446.9  293.92  5492.7   300.5
  5563.9  301.98  5578.1   309.6  5598.3  315.47  5640.1  322.02  5692.9  327.54
#Mann= 6 ,-1 , 0
  4065.2     .16       0    4197     .12       0  4993.6     .07       0
  4999.6     .12       0  5127.6     .07       0    5254     .05       0
Bank Sta=4936.6,5056.7
XS Rating Curve= 0 ,0
Exp/Cntr=0.3,0.1

Type RM Length L Ch R = 1 ,66726   ,71,71,71
BEGIN DESCRIPTION:
Mapping XS 4b65845c
END DESCRIPTION:
XS GIS Cut Line= 3
      3725351.19     10648935.26      3724316.44      10649081.1
       3723715.7     10649216.53
#Sta/Elev= 30
  3875.7  309.48  3907.5  308.03  3958.1  303.02    4008  301.51  4021.1  298.82
    4251  288.44  4321.6  288.39  4341.8  290.52  4351.9  288.24  4725.6  290.33
  4887.2  290.03    4936  288.11  4941.2  284.19  4968.7   279.7  4978.9  275.74
  5006.7  274.57  5009.4  274.07  5012.7  274.57  5032.8   282.7  5040.4  279.36
  5050.7  278.18    5076   289.1  5116.6  288.31  5259.2  290.58    5430  303.36
  5480.5  303.58  5501.7  311.02    5512  319.25  5525.8  321.65  5536.5  322.64
#Mann= 7 ,-1 , 0
  3875.7     .12       0  3907.5     .05       0    4008     .12       0
  5006.7     .07       0  5012.7     .12       0  5116.6     .05       0
  5525.8     .08       0
Bank Sta=4936,5076
XS Rating Curve= 0 ,0
Exp/Cntr=0.3,0.1

Type RM Length L Ch R = 1 ,66655   ,184,184,184
BEGIN DESCRIPTION:
KEECHIE CREEK 99.0
END DESCRIPTION:
XS GIS Cut Line= 2
      3725341.48     10648874.75      3723602.78     10649139.24
#Sta/Elev= 30
  3832.2  316.66  3925.1  309.13  3964.3  308.08  3974.3   305.6    4033  304.61
    4038  301.74  4096.5  300.31  4208.3  290.56  4355.2  288.22  4494.3  288.88
  4757.8  290.12  4926.5  290.05  4959.2  285.69  4987.2  274.64  4994.3   274.6
  4997.1   274.1  5000.3   274.6  5014.4  275.28  5027.3  275.79  5037.8   281.8
  5059.8  286.24  5078.2  289.06  5118.7  286.05  5128.8  289.98  5138.9  290.61
  5199.6  289.63  5371.6  305.05  5462.5  307.97  5561.3  308.26  5590.9   310.9
#Mann= 11 ,-1 , 0
  3832.2     .05       0  3974.3     .12       0  4355.2     .05       0
  4494.3     .12       0  4757.8     .05       0  4959.2     .08       0
  4994.3     .07       0  5000.3     .08       0  5014.4     .12       0
  5059.8     .05       0  5462.5     .08       0
Bank Sta=4926.5,5078.2
XS Rating Curve= 0 ,0
Exp/Cntr=0.3,0.1

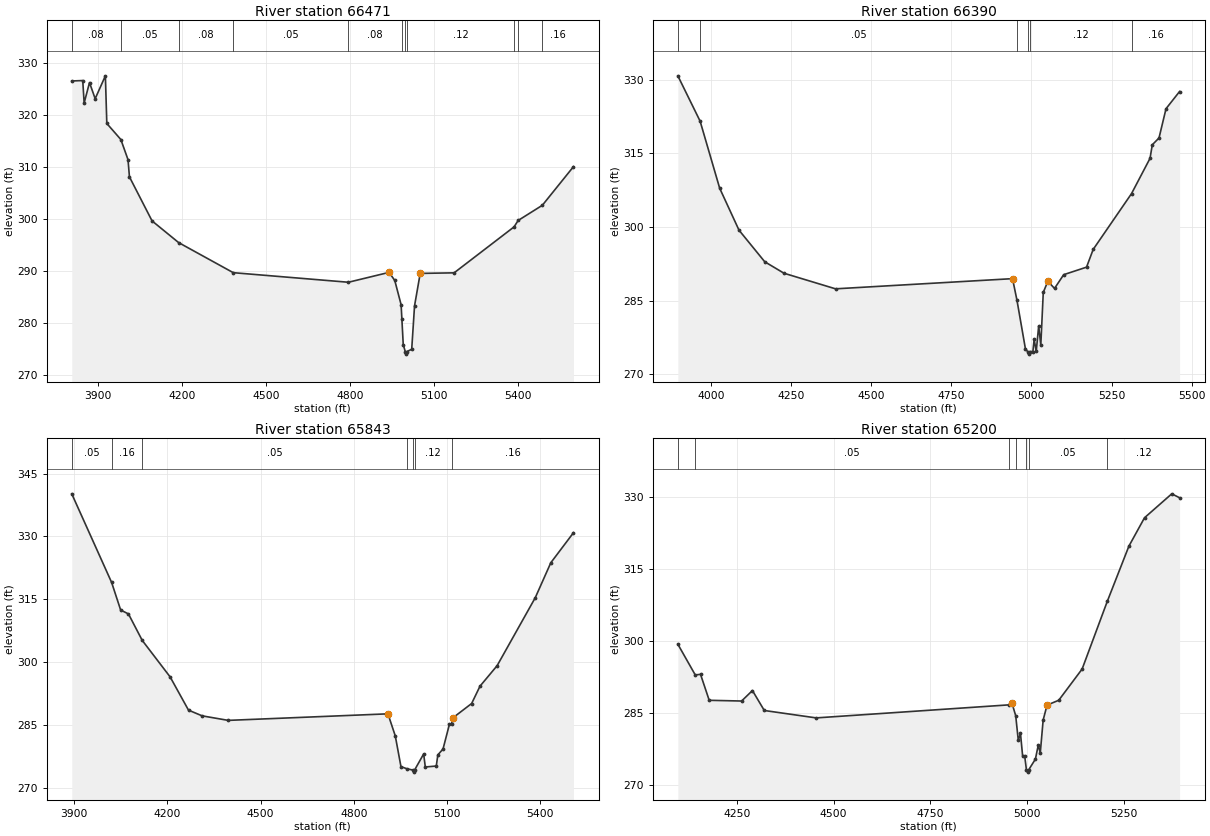
Type RM Length L Ch R = 1 ,66471   ,81,81,81
BEGIN DESCRIPTION:
Mapping XS 1e8b6303
END DESCRIPTION:
XS GIS Cut Line= 2
      3725302.42      10648740.2      3723527.27     10648961.56
#Sta/Elev= 30
  3807.9  326.45  3847.1  326.53  3852.1  322.21  3871.2  326.14  3891.4  323.04
  3927.8  327.44  3932.9  318.28    3983  315.19  4008.5  311.32  4013.6  308.01
  4094.3  299.54  4189.1  295.37  4383.8  289.59  4794.3  287.75  4939.4  289.65
  4959.6  288.09  4982.2  283.43  4984.9  280.71  4989.8  275.76  4996.9  274.43
  4999.6  273.93  5002.9  274.43    5020  274.86  5030.1  283.22  5050.3  289.45
  5171.2  289.56    5385   298.4  5399.5  299.63  5485.8  302.55  5596.8  309.98
#Mann= 11 ,-1 , 0
  3807.9     .08       0    3983     .05       0  4189.1     .08       0
  4383.8     .05       0  4794.3     .08       0  4984.9     .12       0
  4996.9     .07       0  5002.9     .12       0    5385     .16       0
  5399.5     .08       0  5485.8     .16       0
Bank Sta=4939.4,5050.3
XS Rating Curve= 0 ,0
Exp/Cntr=0.3,0.1

Type RM Length L Ch R = 1 ,66390   ,547,547,547
BEGIN DESCRIPTION:
KEECHIE CREEK 98.0
END DESCRIPTION:
XS GIS Cut Line= 3
       3725199.6     10648710.19      3724099.61     10648810.19
      3723749.61     10648510.19
#Sta/Elev= 30
  3896.9  330.77  3966.4  321.54  4027.4   307.9  4087.7  299.36    4168  292.93
  4228.2  290.59  4388.9  287.42  4941.2  289.49  4955.1  285.07  4981.3  275.25
  4988.4  274.63  4991.1  274.13  4994.4  274.63  5004.7  274.64  5008.6  277.15
  5015.1  274.68  5022.8  279.86  5029.4  275.97  5037.1  286.69  5051.4  288.96
  5072.2   287.5  5100.8   290.3  5172.1  291.83  5192.9  295.45  5312.5   306.8
  5370.2  313.98  5377.3  316.74  5398.2  318.12  5420.1  324.08  5462.4  327.58
#Mann= 6 ,-1 , 0
  3896.9     .08       0  3966.4     .05       0  4955.1     .12       0
  4988.4     .07       0  4994.4     .12       0  5312.5     .16       0
Bank Sta=4941.2,5051.4
XS Rating Curve= 0 ,0
Exp/Cntr=0.3,0.1

Type RM Length L Ch R = 1 ,65843   ,643,643,643
BEGIN DESCRIPTION:
KEECHIE CREEK 97.0
END DESCRIPTION:
XS GIS Cut Line= 3
      3725249.64      10648660.2      3724149.61     10648310.19
      3723699.56      10648410.2
#Sta/Elev= 30
  3892.2  340.16  4020.6  319.04  4049.6  312.48  4074.8  311.54  4119.1  305.24
  4208.9  296.54  4268.1  288.62    4312  287.26  4395.9  286.18  4910.2  287.74
  4933.8  282.49  4952.1  275.17  4971.2  274.65    4990  274.35  4992.7  273.85
    4996  274.35  5025.2  278.18  5030.5  275.08  5065.8   275.3  5070.9  277.96
  5087.6  279.37    5108  285.21    5115  285.41  5119.6   286.8  5179.7   290.2
  5206.6  294.33  5261.7  299.21  5384.6  315.42  5434.6  323.74  5507.6   330.9
#Mann= 7 ,-1 , 0
  3892.2     .05       0  4020.6     .16       0  4119.1     .05       0
  4971.2     .12       0    4990     .07       0    4996     .12       0
    5115     .16       0
Bank Sta=4910.2,5119.6
XS Rating Curve= 0 ,0
Exp/Cntr=0.3,0.1

Type RM Length L Ch R = 1 ,65200   ,1102,1102,1102
BEGIN DESCRIPTION:
KEECHIE CREEK 96.0
END DESCRIPTION:
XS GIS Cut Line= 3
      3724899.63      10648210.2      3724099.61     10647810.19
      3723699.57     10647760.18
#Sta/Elev= 30
    4097  299.32    4142  292.93  4155.7  293.05  4178.1  287.65  4261.9   287.5
  4289.9  289.68  4320.6  285.53  4454.8  283.99    4953   286.7  4960.7  287.18
  4970.8  284.44  4977.5  279.29  4983.1  280.77  4988.7  276.06    4994  276.06
  4998.5  273.21  5001.3  272.71  5004.5  273.21  5021.7  275.41  5029.2  278.35
  5034.3  276.68  5041.8  283.56  5051.9  286.65  5082.1  287.66  5142.6  294.16
  5207.9  308.29  5263.6  319.73  5303.9  325.62  5374.4   330.6  5394.6  329.78
#Mann= 7 ,-1 , 0
    4097     .16       0    4142     .05       0    4953     .12       0
  4970.8     .05       0  4998.5     .03       0  5004.5     .05       0
  5207.9     .12       0
Bank Sta=4960.7,5051.9
XS Rating Curve= 0 ,0
Exp/Cntr=0.3,0.1