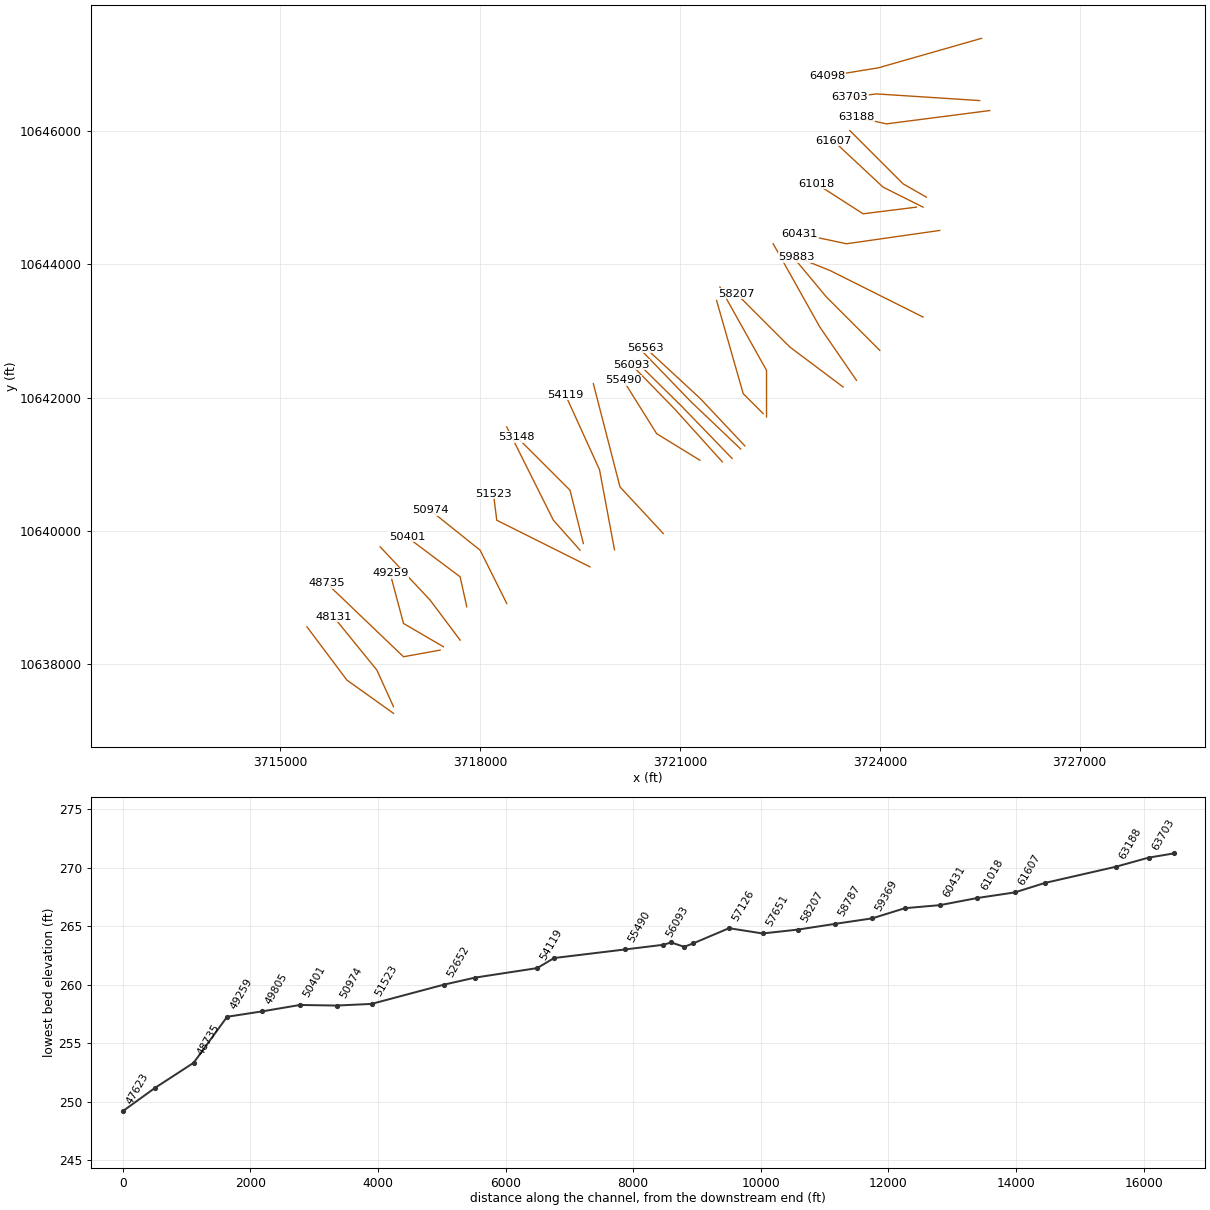
HEC-RAS study KEECHIE CREEK.prj: KEECHIE CREEK Base Level Engineering

--- KEECHIE CREEK.g01 (geometry) --- (continued)

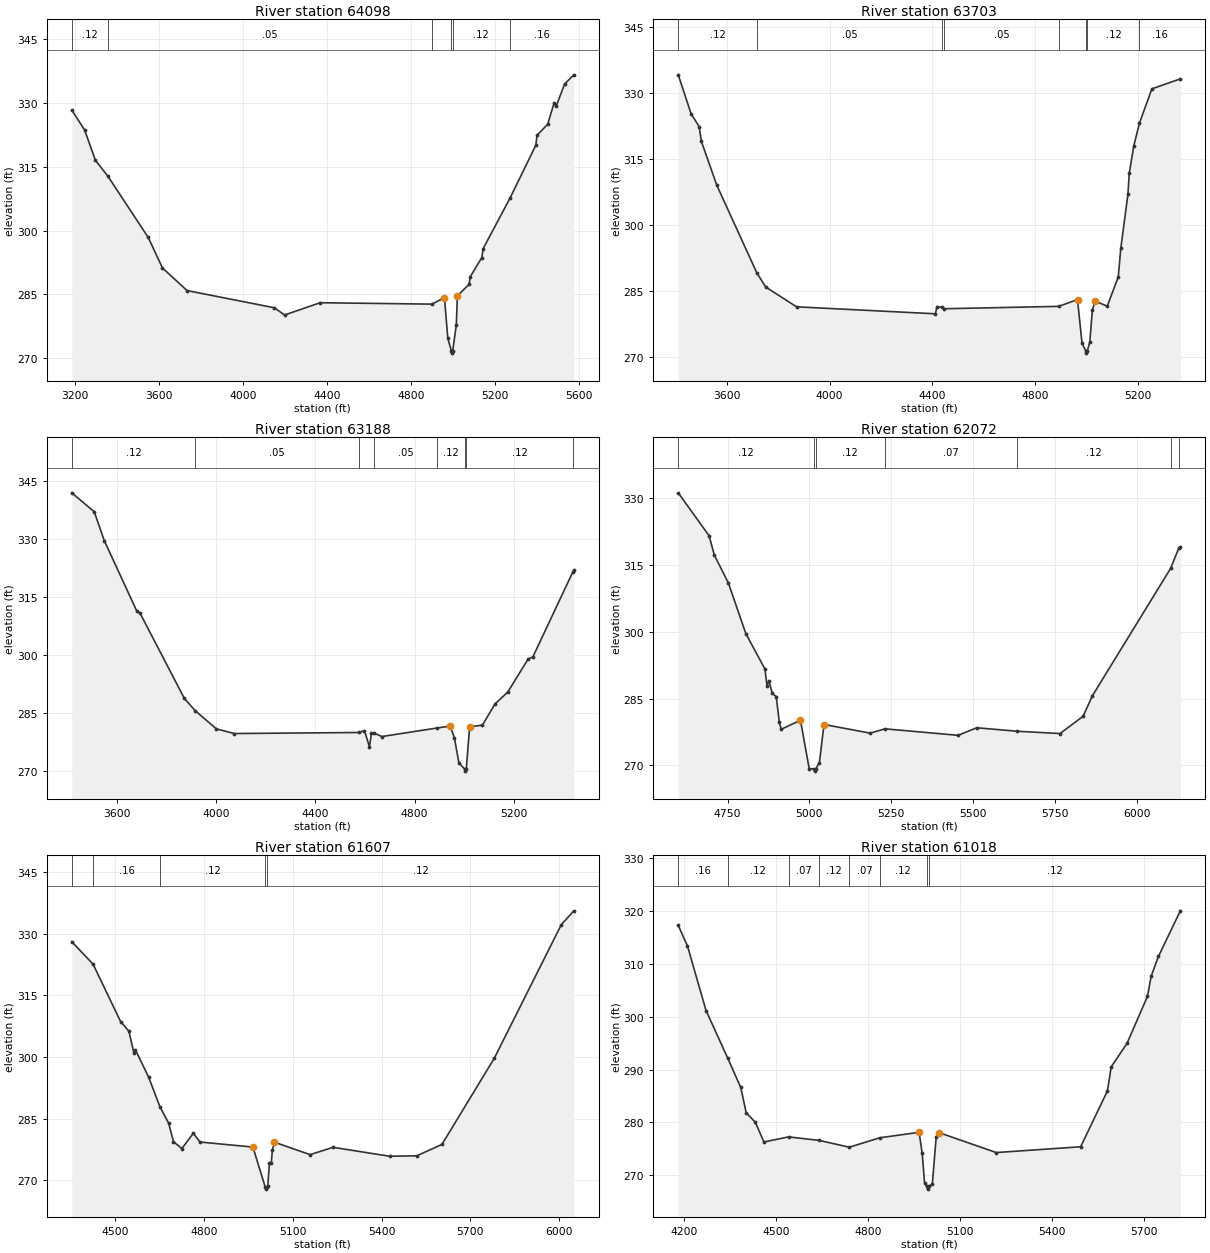
Type RM Length L Ch R = 1 ,64098   ,395,395,395
BEGIN DESCRIPTION:
KEECHIE CREEK 95.0
END DESCRIPTION:
XS GIS Cut Line= 3
      3725528.38     10647394.47      3723978.91     10646951.76
      3723206.37      10646825.9
#Sta/Elev= 30
  3183.6  328.28  3244.7  323.61  3296.7  316.45  3356.6  312.69  3548.3  298.37
  3615.9  291.22  3733.5   285.9  4149.5  281.87  4198.3  280.17  4367.9  283.05
    4901  282.72  4960.9  284.25  4976.7  274.73    4994  271.72  4996.8  271.22
    5000  271.72  5017.3  277.82  5022.4  284.66  5078.1  287.38  5083.9  289.15
  5138.9  293.65  5145.4  295.76  5273.5  307.61  5396.4  320.01  5402.3  322.35
  5452.9  324.93  5483.3  329.87  5493.5  329.15    5534  334.41  5577.8  336.54
#Mann= 6 ,-1 , 0
  3183.6     .12       0  3356.6     .05       0    4901     .12       0
    4994     .07       0    5000     .12       0  5273.5     .16       0
Bank Sta=4960.9,5022.4
XS Rating Curve= 0 ,0
Exp/Cntr=0.3,0.1

Type RM Length L Ch R = 1 ,63703   ,515,515,515
BEGIN DESCRIPTION:
KEECHIE CREEK 94.0
END DESCRIPTION:
XS GIS Cut Line= 3
      3725499.59     10646460.19      3723949.61     10646560.19
      3723549.63     10646510.19
#Sta/Elev= 30
  3410.1  334.06  3460.2  325.22  3491.5   322.3  3500.3  318.94  3560.4  308.98
  3716.1  289.11  3750.8  285.88    3871  281.38  4412.2  279.79  4418.4  281.44
  4438.1  281.24  4446.6  280.94  4892.5  281.48  4965.8  283.02  4983.5  273.07
  4998.1  271.36  5000.8  270.86  5004.1  271.36  5013.7  273.39  5023.8   280.6
  5033.8  282.69  5081.7  281.52  5124.5  288.12  5134.6  294.71  5162.3  306.91
  5167.4  311.66    5185  317.88  5207.2   323.1  5255.6  330.88  5366.4  333.14
#Mann= 8 ,-1 , 0
  3410.1     .12       0  3716.1     .05       0  4438.1     .12       0
  4446.6     .05       0  4892.5     .12       0  4998.1     .07       0
  5004.1     .12       0  5207.2     .16       0
Bank Sta=4965.8,5033.8
XS Rating Curve= 0 ,0
Exp/Cntr=0.3,0.1

Type RM Length L Ch R = 1 ,63188   ,1116,1116,1116
BEGIN DESCRIPTION:
KEECHIE CREEK 93.0
END DESCRIPTION:
XS GIS Cut Line= 3
      3725649.57     10646310.18      3724099.61     10646110.19
       3723649.6     10646210.19
#Sta/Elev= 30
  3418.3  341.98    3509  337.08  3549.3  329.64  3680.4  311.42  3693.6  310.88
    3872  288.87  3915.6  285.71  4001.2     281  4073.6  279.79  4574.1  280.06
    4598  280.53  4618.1   276.4  4626.3  279.83  4636.8   279.9  4668.5  279.02
  4889.8  281.21  4943.9  281.72  4960.9  278.61  4978.6  272.23  5002.4  270.58
  5005.2  270.08  5008.4  270.58  5022.1  281.54  5073.3  281.95  5124.5  287.45
  5175.7  290.51  5257.7  299.03  5276.9  299.58  5437.3  321.44  5442.1  321.99
#Mann= 8 ,-1 , 0
  3418.3     .12       0  3915.6     .05       0  4574.1     .12       0
  4636.8     .05       0  4889.8     .12       0  5002.4     .07       0
  5008.4     .12       0  5437.3     .16       0
Bank Sta=4943.9,5022.1
XS Rating Curve= 0 ,0
Exp/Cntr=0.3,0.1

Type RM Length L Ch R = 1 ,62072   ,465,465,465
BEGIN DESCRIPTION:
KEECHIE CREEK 92.0
END DESCRIPTION:
XS GIS Cut Line= 3
      3724699.61     10645010.19      3724349.61     10645210.19
       3723549.6      10646010.2
#Sta/Elev= 30
  4599.2  331.19  4693.5  321.55  4709.3  317.25  4752.5  310.93  4805.8  299.58
  4864.1  291.63  4870.6   287.9  4876.3  289.03  4886.4  286.19  4898.7  285.41
    4908  279.77  4913.8  278.08  4972.8  280.13  4999.4  269.26  5013.5  269.19
  5016.2  268.69  5019.5  269.19  5030.6  270.59  5044.7  279.16  5186.2  277.22
  5231.1  278.19  5454.9  276.73  5511.4  278.43  5633.9  277.65    5766  277.13
  5836.7  281.02    5865  285.61  6104.4  314.26    6129  318.79  6133.7  318.97
#Mann= 7 ,-1 , 0
  4599.2     .12       0  5013.5     .07       0  5019.5     .12       0
  5231.1     .07       0  5633.9     .12       0  6104.4     .16       0
    6129     .12       0
Bank Sta=4972.8,5044.7
XS Rating Curve= 0 ,0
Exp/Cntr=0.3,0.1

Type RM Length L Ch R = 1 ,61607   ,589,589,589
BEGIN DESCRIPTION:
KEECHIE CREEK 91.0
END DESCRIPTION:
XS GIS Cut Line= 3
      3724649.65     10644860.17      3724049.61     10645160.19
      3723299.59     10645860.21
#Sta/Elev= 30
  4353.1  328.09  4425.1  322.61  4518.1  308.66    4546  306.33  4562.8  301.11
  4568.4  301.74  4613.1   295.1  4650.7  287.97  4680.2  283.98  4696.9  279.45
  4724.9  277.74    4764  281.49  4786.4  279.35  4965.3  278.12    5007  268.39
  5009.7  267.89    5013  268.39  5015.6  268.77  5021.2  274.21  5027.4  274.21
    5031  277.36  5037.9  279.31  5158.6  276.28  5236.2  278.06  5427.2  275.89
  5519.1  275.99  5604.1  278.77  5780.9  299.71  6007.6  332.24  6049.9  335.59
#Mann= 5 ,-1 , 0
  4353.1     .12       0  4425.1     .16       0  4650.7     .12       0
    5007     .07       0    5013     .12       0
Bank Sta=4965.3,5037.9
XS Rating Curve= 0 ,0
Exp/Cntr=0.3,0.1

Type RM Length L Ch R = 1 ,61018   ,587,587,587
BEGIN DESCRIPTION:
KEECHIE CREEK 90.0
END DESCRIPTION:
XS GIS Cut Line= 3
      3724549.57     10644860.18      3723749.61     10644760.19
      3723049.65     10645210.16
#Sta/Elev= 30
  4181.8  317.25    4212  313.33  4272.5  301.15  4343.2  292.16  4385.8  286.61
  4403.5  281.84  4433.7  280.02  4461.4  276.31  4541.7  277.28  4640.9  276.62
  4740.1  275.33  4839.4  277.11  4967.8  278.14  4977.9  274.15  4985.5  268.62
  4992.6  267.91  4995.3  267.41  4998.6  267.91  5010.8  268.31  5023.6  277.27
  5031.9   278.1  5219.5  274.32  5494.9  275.41  5582.4  285.98  5594.6  290.51
  5646.1  294.93  5712.8   303.8    5725  307.63  5748.8  311.37  5820.1  319.98
#Mann= 8 ,-1 , 0
  4181.8     .16       0  4343.2     .12       0  4541.7     .07       0
  4640.9     .12       0  4740.1     .07       0  4839.4     .12       0
  4992.6     .07       0  4998.6     .12       0
Bank Sta=4967.8,5031.9
XS Rating Curve= 0 ,0
Exp/Cntr=0.3,0.1

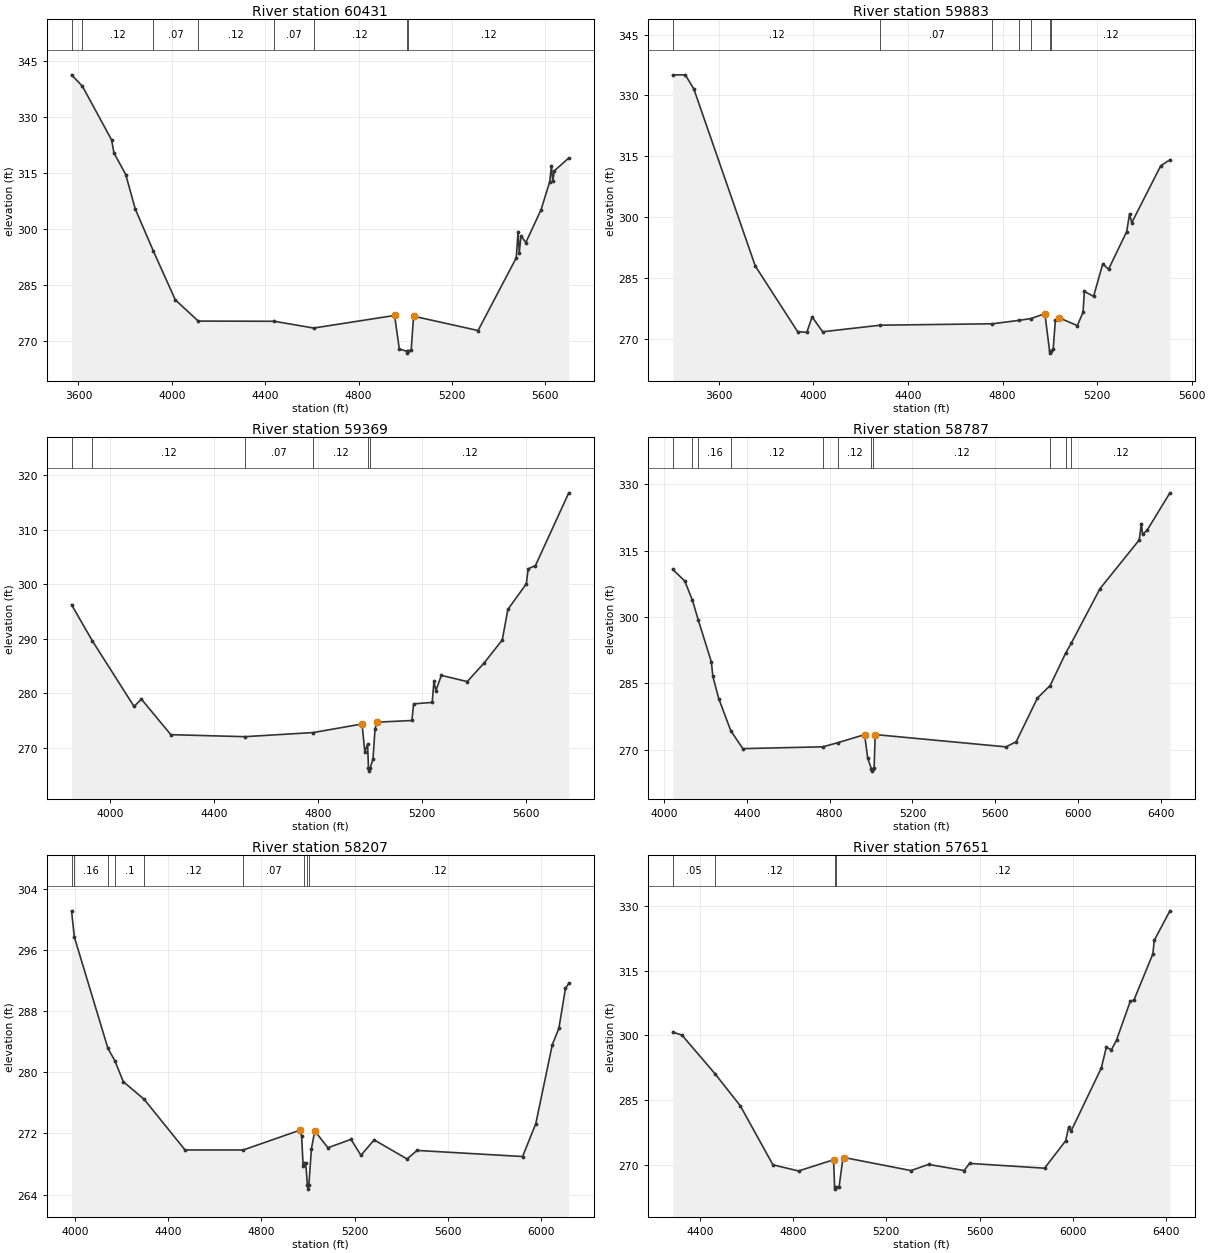
Type RM Length L Ch R = 1 ,60431   ,548,548,548
BEGIN DESCRIPTION:
KEECHIE CREEK 89.0
END DESCRIPTION:
XS GIS Cut Line= 3
       3724899.6     10644510.19      3723499.61     10644310.19
       3722799.6     10644460.19
#Sta/Elev= 30
  3570.2  341.26  3616.7  338.22  3741.9  323.84    3752  320.36  3802.5  314.57
  3842.9  305.42  3921.3  294.04  4014.7  281.06  4113.1  275.38    4439  275.32
  4607.5  273.51  4954.1  276.88  4974.3  267.92  5006.1   267.3  5008.9   266.8
  5012.1   267.3  5025.3  267.73  5035.5  276.68  5311.7  272.85  5475.3   292.3
    5483  299.27  5488.1  293.67  5495.8  298.18  5516.2  296.38  5581.8  305.21
  5618.5  312.64  5626.1  316.95  5631.3  312.81  5638.9   315.6  5700.3  319.02
#Mann= 8 ,-1 , 0
  3570.2     .05       0  3616.7     .12       0  3921.3     .07       0
  4113.1     .12       0    4439     .07       0  4607.5     .12       0
  5006.1     .07       0  5012.1     .12       0
Bank Sta=4954.1,5035.5
XS Rating Curve= 0 ,0
Exp/Cntr=0.3,0.1

Type RM Length L Ch R = 1 ,59883   ,514,514,514
BEGIN DESCRIPTION:
KEECHIE CREEK 88.0
END DESCRIPTION:
XS GIS Cut Line= 3
      3724649.61     10643210.19      3723249.61     10643910.19
      3722749.58      10644110.2
#Sta/Elev= 30
  3404.3  335.06  3457.4  335.07  3493.7   331.6  3753.7     288  3932.6  271.86
  3971.7  271.64  3994.1  275.47  4038.8   271.8  4282.5  273.42  4757.2  273.77
    4870  274.61  4920.3  275.06    4979  276.26  4998.9  267.04  5001.6  266.54
  5004.9  267.04    5014  267.47  5023.4  274.62  5038.2  275.26  5116.3  273.32
  5140.5   276.6  5145.9  281.76    5185  280.52    5224  288.55  5248.2  287.18
    5325  296.45  5337.1  300.79  5346.5  298.65    5469  312.66  5508.1  314.16
#Mann= 7 ,-1 , 0
  3404.3     .12       0  4282.5     .07       0  4757.2     .12       0
    4870     .07       0  4920.3     .12       0  4998.9     .07       0
  5004.9     .12       0
Bank Sta=4979,5038.2
XS Rating Curve= 0 ,0
Exp/Cntr=0.3,0.1

Type RM Length L Ch R = 1 ,59369   ,582,582,582
BEGIN DESCRIPTION:
KEECHIE CREEK 87.0
END DESCRIPTION:
XS GIS Cut Line= 3
      3723999.63     10642710.16      3723199.61     10643510.19
      3722699.63     10644110.17
#Sta/Elev= 30
  3852.3  296.21  3931.9  289.61  4092.8  277.53    4121  278.88  4234.2  272.36
  4517.9  271.99  4782.2  272.75  4969.6  274.32  4980.2  269.24  4990.9  270.59
  4994.4  266.17  4997.1  265.67  5000.4  266.17  5011.7  267.91  5019.5  273.32
    5026  274.65  5161.4  274.96  5167.9  278.01  5239.5  278.28    5246  282.14
  5253.8  280.45  5274.6  283.24  5374.2   282.1  5438.7  285.49  5508.9  289.74
  5530.4  295.33  5601.4  300.04  5608.5  302.78  5636.5  303.39  5764.7  316.73
#Mann= 6 ,-1 , 0
  3852.3     .16       0  3931.9     .12       0  4517.9     .07       0
  4782.2     .12       0  4994.4     .07       0  5000.4     .12       0
Bank Sta=4969.6,5026
XS Rating Curve= 0 ,0
Exp/Cntr=0.3,0.1

Type RM Length L Ch R = 1 ,58787   ,580,580,580
BEGIN DESCRIPTION:
KEECHIE CREEK 86.0
END DESCRIPTION:
XS GIS Cut Line= 3
      3723649.63     10642260.16      3723099.61     10643060.19
      3722399.62     10644310.17
#Sta/Elev= 30
  4041.4  310.77  4099.6  308.16  4137.1  303.76  4164.5  299.42  4228.2  289.89
  4235.6  286.59    4264  281.59  4322.1  274.34  4380.4  270.28  4766.8  270.69
  4841.2  271.64    4969  273.45  4983.9  268.18  5001.8   265.7  5004.6   265.2
  5007.8   265.7  5015.1  265.95  5020.2  273.46  5652.7  270.68  5701.8  271.85
  5804.5  281.72  5866.1  284.54  5940.7  291.84    5968   294.1    6107  306.43
  6296.5  317.42  6306.8  321.13  6312.5  318.67  6334.2  319.59  6444.9  328.06
#Mann= 11 ,-1 , 0
  4041.4     .16       0  4137.1     .12       0  4164.5     .16       0
  4322.1     .12       0  4766.8     .07       0  4841.2     .12       0
  5001.8     .07       0  5007.8     .12       0  5866.1     .16       0
  5940.7      .1       0    5968     .12       0
Bank Sta=4969,5020.2
XS Rating Curve= 0 ,0
Exp/Cntr=0.3,0.1

Type RM Length L Ch R = 1 ,58207   ,556,556,556
BEGIN DESCRIPTION:
KEECHIE CREEK 85.0
END DESCRIPTION:
XS GIS Cut Line= 3
      3723449.63     10642160.17      3722649.61     10642760.19
      3721849.61     10643560.19
#Sta/Elev= 30
  3986.1  301.16  3998.3  297.72    4142  283.16  4171.6  281.54    4208  278.79
  4297.5  276.47  4472.6  269.84  4722.2  269.84  4964.2  272.42  4972.6  271.63
  4978.8   267.7  4982.4  268.11  4989.7  268.18  4997.3  265.21    5000  264.71
  5003.3  265.21  5014.4     270  5028.6  272.34  5085.1  270.13  5184.1  271.23
  5226.5  269.14  5283.1  271.16  5424.5  268.66    5467  269.78  5919.5  268.98
  5976.1  273.28  6046.8  283.62  6075.1  285.78  6103.4  291.02  6117.5  291.65
#Mann= 9 ,-1 , 0
  3986.1     .12       0  3998.3     .16       0    4142     .05       0
  4171.6      .1       0  4297.5     .12       0  4722.2     .07       0
  4982.4     .12       0  4997.3     .07       0  5003.3     .12       0
Bank Sta=4964.2,5028.6
XS Rating Curve= 0 ,0
Exp/Cntr=0.3,0.1

Type RM Length L Ch R = 1 ,57651   ,525,525,525
BEGIN DESCRIPTION:
KEECHIE CREEK 84.0
END DESCRIPTION:
XS GIS Cut Line= 3
      3722299.61     10641710.17      3722299.61     10642410.19
       3721599.6     10643660.21
#Sta/Elev= 30
  4283.7  300.75  4323.7  300.05  4464.3  291.16  4573.7  283.68  4713.7     270
  4823.7  268.59  4973.7  271.18  4978.2  264.88    4981  264.38  4984.2  264.88
  4997.4  264.88  5013.4  271.42  5019.1   271.7  5305.7  268.68    5381   270.1
  5533.9  268.69  5556.8  270.34  5878.7  269.23  5969.4   275.6  5981.5  278.68
  5991.7  277.75  6121.9  292.42  6143.6  297.23  6165.3  296.65  6187.2  298.89
  6246.3  307.89  6262.3  308.22  6343.3  318.88    6349     322  6416.4  328.84
#Mann= 4 ,-1 , 0
  4283.7     .05       0  4464.3     .12       0  4978.2     .07       0
  4984.2     .12       0
Bank Sta=4973.7,5019.1
XS Rating Curve= 0 ,0
Exp/Cntr=0.3,0.1

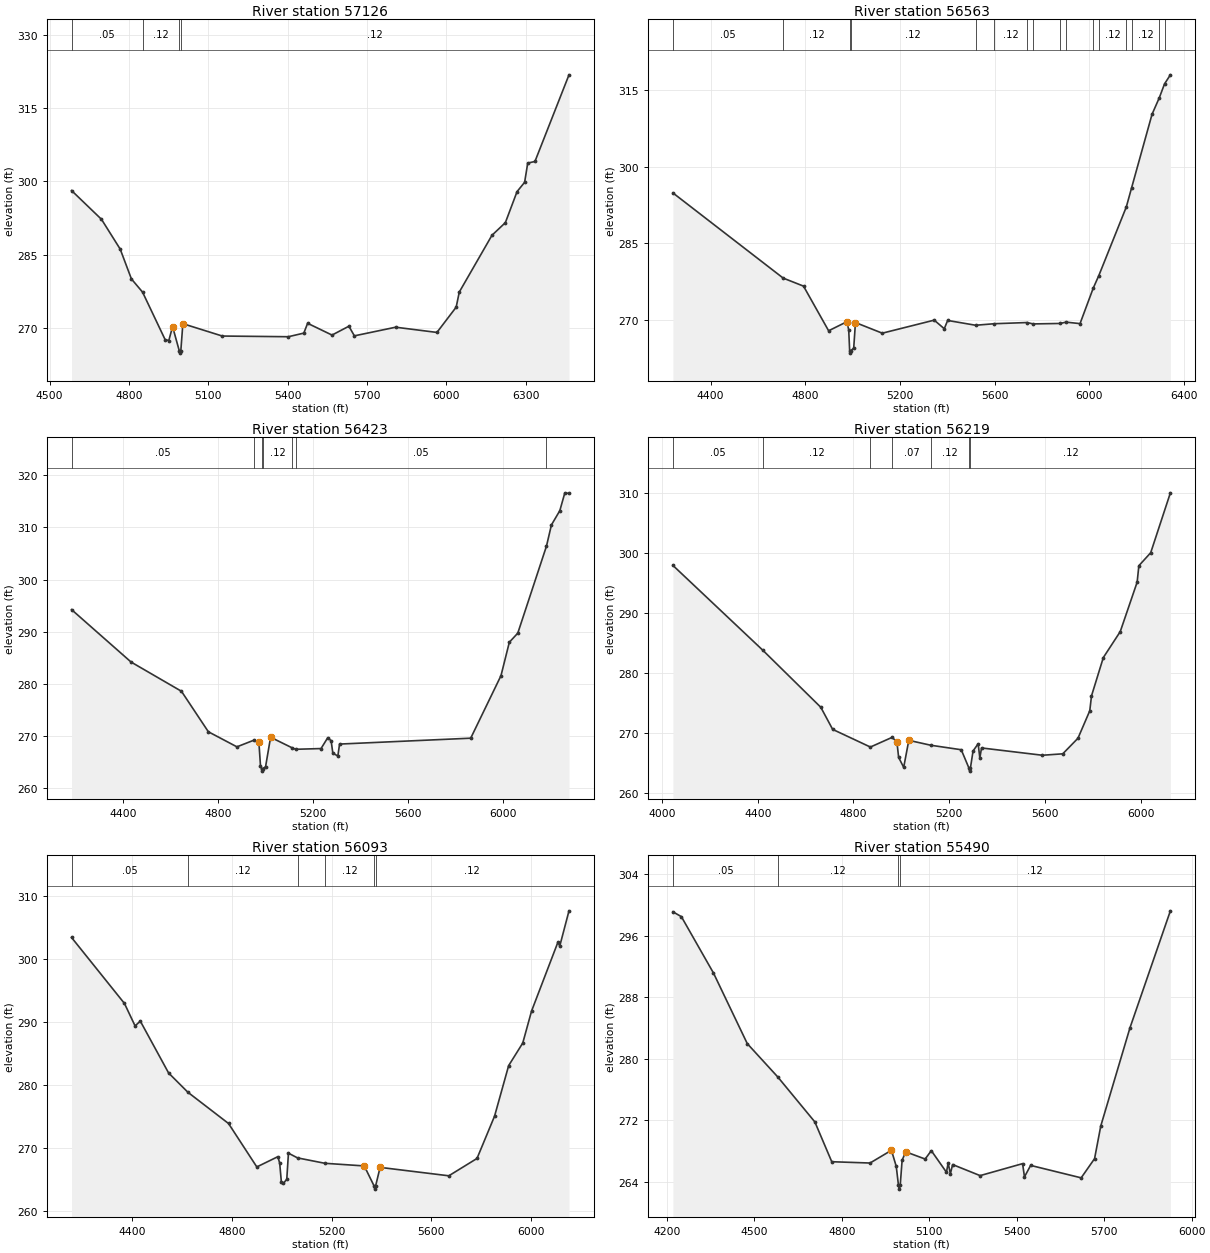
Type RM Length L Ch R = 1 ,57126   ,563,563,563
BEGIN DESCRIPTION:
KEECHIE CREEK 83.0
END DESCRIPTION:
XS GIS Cut Line= 3
      3722249.63     10641760.17      3721949.61     10642060.19
      3721549.61     10643460.18
#Sta/Elev= 30
  4583.3  298.14  4696.5  292.24  4767.2  286.14  4809.6  280.03  4851.7  277.33
  4936.9  267.61    4951  267.41  4965.2  270.27  4990.4  265.33  4993.2  264.83
  4996.4  265.33  5004.1  270.86  5153.2  268.33  5402.8  268.19  5461.3  268.93
  5475.6  270.94  5567.9  268.53  5631.6  270.34  5652.4  268.37  5808.4  270.14
  5964.4  269.07  6037.2  274.25  6048.9  277.34  6172.4  288.97  6223.1  291.56
  6267.3  297.92  6295.9  299.83  6307.6  303.76  6334.9  304.09  6463.6  321.84
#Mann= 4 ,-1 , 0
  4583.3     .05       0  4851.7     .12       0  4990.4     .07       0
  4996.4     .12       0
Bank Sta=4965.2,5004.1
XS Rating Curve= 0 ,0
Exp/Cntr=0.3,0.1

Type RM Length L Ch R = 1 ,56563   ,140,140,140
BEGIN DESCRIPTION:
Mapping XS 48e77314
END DESCRIPTION:
XS GIS Cut Line= 3
      3721974.51      10641275.8      3721302.64     10641989.34
      3720479.74     10642749.73
#Sta/Elev= 30
  4241.2  294.85  4706.7   278.2  4792.6  276.63  4898.6   267.9  4976.2  269.68
  4983.5  268.03  4987.4  264.03  4990.2  263.53  4993.4  264.03  5004.6  264.54
  5011.9  269.51  5125.2  267.43  5344.5  269.98    5387   268.3  5401.2  269.92
  5519.2  268.98  5598.5  269.28  5736.5  269.51  5762.2  269.24  5876.2  269.33
  5900.9  269.59  5960.2   269.3  6015.9  276.23  6039.6   278.7  6155.6  292.11
  6178.3  295.91  6264.2  310.22  6295.3   313.5    6317  316.17  6341.7  317.94
#Mann= 16 ,-1 , 0
  4241.2     .05       0  4706.7     .12       0  4987.4     .07       0
  4993.4     .12       0  5519.2     .05       0  5598.5     .12       0
  5736.5     .05       0  5762.2     .12       0  5876.2     .05       0
  5900.9     .12       0  6015.9     .05       0  6039.6     .12       0
  6155.6     .05       0  6178.3     .12       0  6295.3     .16       0
    6317     .12       0
Bank Sta=4976.2,5011.9
XS Rating Curve= 0 ,0
Exp/Cntr=0.3,0.1

Type RM Length L Ch R = 1 ,56423   ,204,204,204
BEGIN DESCRIPTION:
KEECHIE CREEK 82.0
END DESCRIPTION:
XS GIS Cut Line= 3
        3721912.     10641228.93      3721162.01     10641942.46
      3720427.66     10642702.86
#Sta/Elev= 30
  4183.9  294.23  4434.2  284.17  4646.2  278.56  4759.4  270.79  4879.5   267.9
  4949.4  269.15  4971.7  268.91  4978.6  264.28  4982.9  263.74  4985.6  263.24
  4988.9  263.74    5000  264.09  5021.1  269.74  5112.6  267.69  5126.5  267.43
  5233.3  267.57  5261.6  269.66  5275.7  269.07  5282.9  266.69    5304  266.14
  5311.2  268.43  5862.8  269.56  5990.1  281.55  6025.3  287.97  6060.8  289.71
  6181.5  306.41  6202.3  310.47  6237.6  313.21  6258.7  316.63  6276.2  316.51
#Mann= 7 ,-1 , 0
  4183.9     .05       0  4949.4     .12       0  4982.9     .07       0
  4988.9     .12       0  5112.6     .08       0  5126.5     .05       0
  6181.5     .16       0
Bank Sta=4971.7,5021.1
XS Rating Curve= 0 ,0
Exp/Cntr=0.3,0.1

Type RM Length L Ch R = 1 ,56219   ,126,126,126
BEGIN DESCRIPTION:
KEECHIE CREEK 81.0
END DESCRIPTION:
XS GIS Cut Line= 3
      3721781.81     10641088.29      3721021.39     10641874.75
       3720319.4     10642566.34
#Sta/Elev= 30
  4045.2  297.95  4421.5  283.77  4663.3  274.27  4712.9  270.58  4870.6  267.63
  4961.5  269.25  4981.5  268.48  4988.7   265.9  5009.8  264.24  5031.2  268.75
  5123.3  267.93  5250.4  267.18  5282.7  264.11  5285.4  263.61  5288.7  264.11
  5299.8  266.98  5321.1  268.18  5328.1   265.8  5335.2  267.48  5589.8  266.26
  5674.7   266.5  5738.3   269.1  5787.7  273.69  5794.8  276.16  5844.3  282.57
    5915   286.9  5985.7  295.16  5992.8   297.9  6042.3  300.07  6124.6  310.07
#Mann= 7 ,-1 , 0
  4045.2     .05       0  4421.5     .12       0  4870.6     .08       0
  4961.5     .07       0  5123.3     .12       0  5282.7     .07       0
  5288.7     .12       0
Bank Sta=4981.5,5031.2
XS Rating Curve= 0 ,0
Exp/Cntr=0.3,0.1

Type RM Length L Ch R = 1 ,56093   ,603,603,603
BEGIN DESCRIPTION:
Mapping XS 7eb6a70d
END DESCRIPTION:
XS GIS Cut Line= 3
      3721635.99     10641036.18      3720917.22     10641833.09
      3720271.41     10642494.52
#Sta/Elev= 30
  4155.3  303.44  4367.9  292.94  4410.5  289.37  4431.4  290.14    4545  281.89
  4622.8  278.81  4785.7  273.85  4899.3  266.94  4983.7  268.57  4991.2  267.54
  4997.9  264.52  5005.4  264.31  5019.6  264.97  5026.3  269.13  5062.7  268.38
  5172.5  267.52  5330.8   267.1  5370.3  263.91    5373  263.41  5376.3  263.91
  5394.4  266.87  5670.3  265.53  5783.5  268.29    5854  275.02  5910.6  283.06
  5967.2  286.65  6002.6  291.74  6108.6  302.71  6115.8  302.08  6152.9  307.68
#Mann= 6 ,-1 , 0
  4155.3     .05       0  4622.8     .12       0  5062.7     .07       0
  5172.5     .12       0  5370.3     .07       0  5376.3     .12       0
Bank Sta=5330.8,5394.4
XS Rating Curve= 0 ,0
Exp/Cntr=0.3,0.1

Type RM Length L Ch R = 1 ,55490   ,1106,1106,1106
BEGIN DESCRIPTION:
KEECHIE CREEK 80.0
END DESCRIPTION:
XS GIS Cut Line= 3
      3721299.65     10641060.16      3720649.61     10641460.19
      3720149.59     10642260.22
#Sta/Elev= 30
  4220.3  299.13  4249.3   298.5  4359.4  291.16  4475.4  281.96  4579.8  277.63
  4707.3  271.76  4765.2  266.58  4896.6  266.41    4970  268.07  4986.5  265.97
  4994.1  263.51  4996.9  263.01  5000.1  263.51  5006.6  266.77  5018.9  267.87
  5085.6  266.93  5106.8  268.02  5158.7  265.21  5164.6  266.41  5172.2  265.01
  5179.9  266.21  5274.2  264.77  5419.9  266.33  5426.4  264.61  5447.6   266.1
  5620.9  264.48  5666.9  266.98  5688.2  271.24  5788.4  284.03    5927  299.26
#Mann= 4 ,-1 , 0
  4220.3     .05       0  4579.8     .12       0  4994.1     .07       0
  5000.1     .12       0
Bank Sta=4970,5018.9
XS Rating Curve= 0 ,0
Exp/Cntr=0.3,0.1

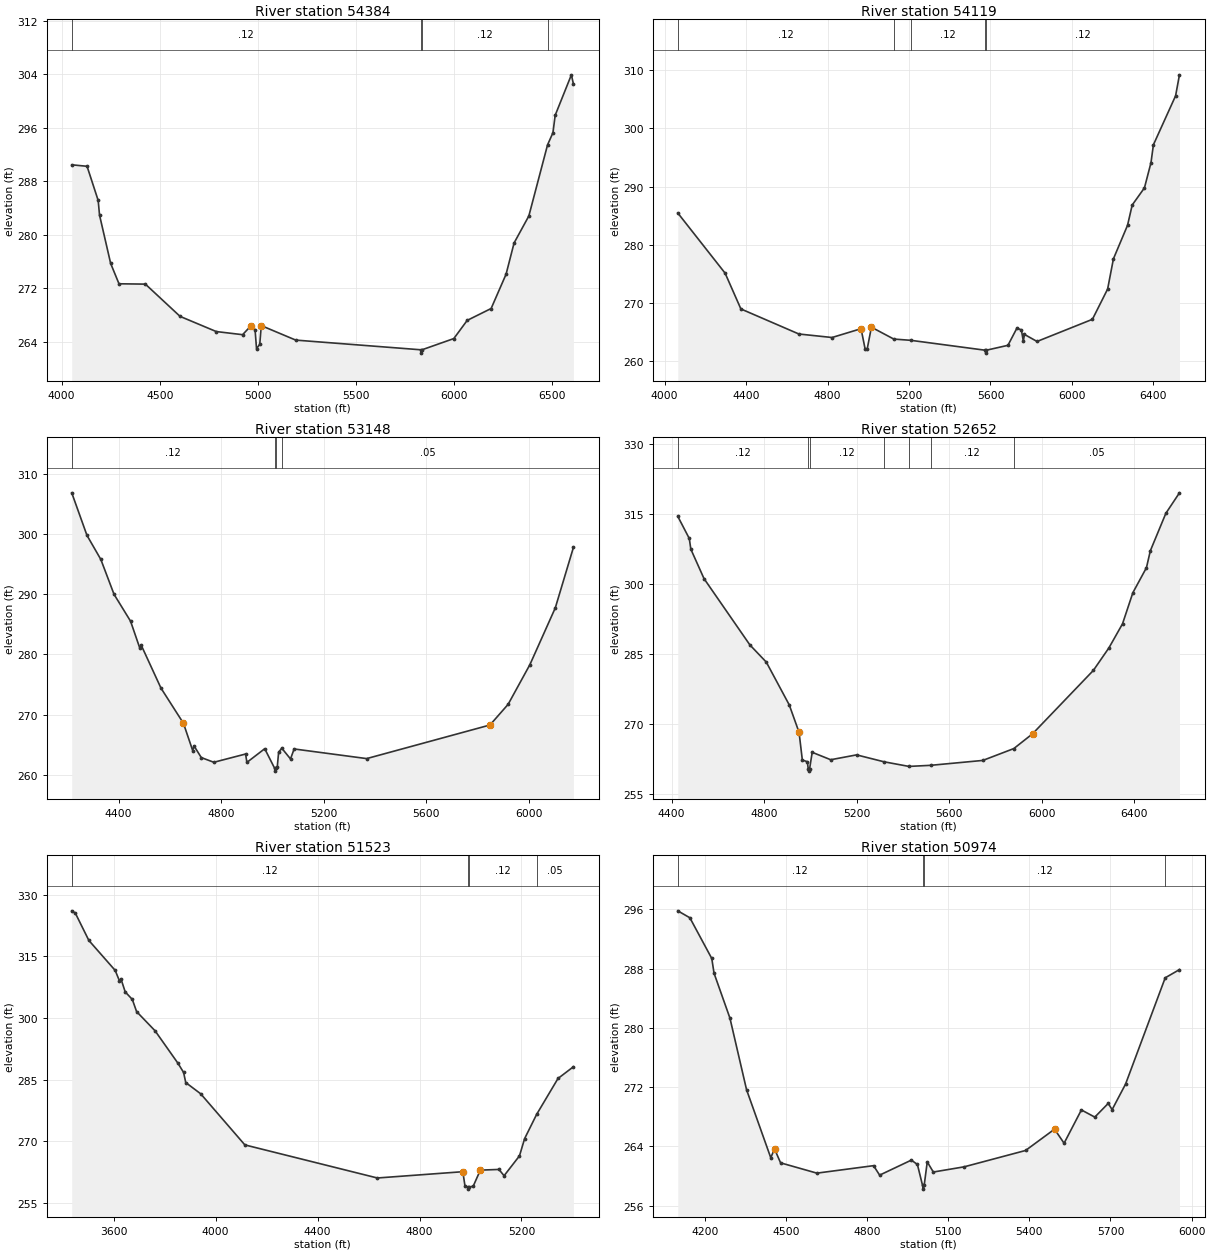
Type RM Length L Ch R = 1 ,54384   ,265,265,265
BEGIN DESCRIPTION:
KEECHIE CREEK 79.0
END DESCRIPTION:
XS GIS Cut Line= 3
      3720749.64     10639960.16      3720099.61     10640660.19
       3719699.6     10642210.21
#Sta/Elev= 30
  4051.9  290.47  4129.9  290.25  4186.6  285.13  4193.4  282.95  4250.1  275.71
  4292.6  272.66    4427  272.61  4603.8  267.78  4788.1  265.51  4922.4  265.04
  4964.9  266.37  4985.9   265.8  4993.3  262.96  5009.8  263.59  5017.5   266.4
  5193.1  264.23  5830.4  262.78  5833.2  262.28  5836.4  262.78  5998.6  264.46
  6066.7  267.18  6188.7  268.96  6264.9   274.1  6305.6  278.77  6380.8  282.81
  6476.1  293.45  6503.7  295.28    6515  297.88  6597.6  303.94    6608  302.57
#Mann= 4 ,-1 , 0
  4051.9     .12       0  5830.4     .07       0  5836.4     .12       0
  6476.1     .16       0
Bank Sta=4964.9,5017.5
XS Rating Curve= 0 ,0
Exp/Cntr=0.3,0.1

Type RM Length L Ch R = 1 ,54119   ,971,971,971
BEGIN DESCRIPTION:
KEECHIE CREEK 78.0
END DESCRIPTION:
XS GIS Cut Line= 3
      3720017.17     10639715.69       3719792.2     10640918.61
      3719278.63     10642046.62
#Sta/Elev= 30
  4064.6  285.46  4297.1  275.13  4374.4     269  4659.2   264.7    4822   264.1
  4964.4  265.61  4984.8  262.07    4995   262.2  5015.3  265.87  5125.3  263.83
  5208.1  263.62  5573.7  261.92  5576.5  261.42  5579.7  261.92  5685.7  262.76
  5729.6   265.7  5751.6  265.41  5761.2  263.47  5766.7  264.63  5828.5  263.42
  6100.4  267.22  6175.1  272.41  6203.6   277.6  6272.8  283.34  6295.8  286.83
  6355.9  289.77    6388  294.09  6399.9  297.16  6508.8  305.56  6527.8  309.16
#Mann= 5 ,-1 , 0
  4064.6     .12       0  5125.3     .05       0  5208.1     .12       0
  5573.7     .07       0  5579.7     .12       0
Bank Sta=4964.4,5015.3
XS Rating Curve= 0 ,0
Exp/Cntr=0.3,0.1

Type RM Length L Ch R = 1 ,53148   ,496,496,496
BEGIN DESCRIPTION:
KEECHIE CREEK 77.0
END DESCRIPTION:
XS GIS Cut Line= 3
       3719549.6     10639810.21      3719349.61     10640610.19
      3718549.59     10641410.21
#Sta/Elev= 30
  4217.7  306.81    4277  299.75  4331.1  295.75  4382.6  289.96    4447   285.5
  4483.1  281.02  4488.3  281.54  4565.6  274.39  4653.2  268.55  4689.3  264.02
  4694.4   264.8  4722.8  262.86  4771.7  262.08  4895.4  263.45  4900.6  262.06
  4970.1  264.33  5008.4  261.11  5011.1  260.61  5014.4  261.11  5019.1  261.35
  5024.3  263.75  5036.6  264.42  5070.6  262.63  5084.7  264.29  5367.6  262.69
  5848.4  268.27  5919.1   271.7    6004  278.29    6103  287.71  6173.7  297.75
#Mann= 4 ,-1 , 0
  4217.7     .12       0  5008.4     .07       0  5014.4     .12       0
  5036.6     .05       0
Bank Sta=4653.2,5848.4
XS Rating Curve= 0 ,0
Exp/Cntr=0.3,0.1

Type RM Length L Ch R = 1 ,52652   ,1129,1129,1129
BEGIN DESCRIPTION:
KEECHIE CREEK 76.0
END DESCRIPTION:
XS GIS Cut Line= 3
      3719499.59     10639710.21      3719099.61     10640160.19
      3718399.61     10641560.19
#Sta/Elev= 30
  4427.1  314.56  4476.8  309.82  4483.5  307.53  4540.4  301.23  4738.6  287.03
  4809.6  283.34  4908.7  274.18    4951  268.31  4965.2  262.38  4986.9  262.01
  4990.6   260.5  4993.4     260  4996.6   260.5  5007.8  264.03  5087.8  262.44
  5199.6  263.48    5318     262  5425.6  261.01    5519  261.24  5744.7  262.29
  5878.8  264.83  5959.9     268  6222.6  281.58  6289.7   286.4  6348.4  291.55
  6393.1  298.21  6451.8  303.57  6468.6  307.19  6535.7  315.22  6594.4   319.6
#Mann= 7 ,-1 , 0
  4427.1     .12       0  4990.6     .07       0  4996.6     .12       0
    5318     .07       0  5425.6     .05       0    5519     .12       0
  5878.8     .05       0
Bank Sta=4951,5959.9
XS Rating Curve= 0 ,0
Exp/Cntr=0.3,0.1

Type RM Length L Ch R = 1 ,51523   ,549,549,549
BEGIN DESCRIPTION:
KEECHIE CREEK 75.0
END DESCRIPTION:
XS GIS Cut Line= 3
      3719649.63     10639460.18      3718249.61     10640160.19
      3718199.61      10640560.2
#Sta/Elev= 30
  3435.5  326.06  3449.5  325.51  3502.6  318.86    3606  311.56  3622.8     309
  3628.4  309.55  3645.2  306.34  3673.1  304.51  3689.9  301.55  3762.5  296.87
    3852     289  3874.4  286.74  3882.7  284.29  3941.4  281.55  4114.7  269.12
  4634.6  261.07    4970   262.6  4978.4  259.13  4989.4  258.86  4992.1  258.36
  4995.4  258.86  5010.8  259.09  5038.6  262.98  5111.6  263.15  5131.8  261.62
  5192.2  266.45  5212.4  270.65  5259.7  276.56  5343.4  285.28  5403.9  288.13
#Mann= 4 ,-1 , 0
  3435.5     .12       0  4989.4     .07       0  4995.4     .12       0
  5259.7     .05       0
Bank Sta=4970,5038.6
XS Rating Curve= 0 ,0
Exp/Cntr=0.3,0.1

Type RM Length L Ch R = 1 ,50974   ,573,573,573
BEGIN DESCRIPTION:
KEECHIE CREEK 74.0
END DESCRIPTION:
XS GIS Cut Line= 3
      3718399.59     10638910.22      3717999.61     10639710.19
      3717249.58     10640310.21
#Sta/Elev= 30
  4100.1  295.82  4144.8  294.88  4225.8  289.38  4234.2  287.39  4292.9  281.33
  4354.4  271.65  4443.9  262.46  4457.8  263.65  4480.2  261.77  4614.4  260.38
    4824  261.39  4846.4  260.11  4963.7  262.14  4986.1  261.55  5005.1  258.72
  5007.8  258.22  5011.1  258.72  5022.5   261.9  5044.9  260.53  5158.6  261.23
  5385.9  263.44  5493.1  266.32  5528.4  264.42  5592.4  268.92    5642  267.95
  5691.6   269.8    5706  268.96  5755.7  272.41  5902.3  286.77    5955  287.88
#Mann= 4 ,-1 , 0
  4100.1     .12       0  5005.1     .07       0  5011.1     .12       0
  5902.3     .16       0
Bank Sta=4457.8,5493.1
XS Rating Curve= 0 ,0
Exp/Cntr=0.3,0.1

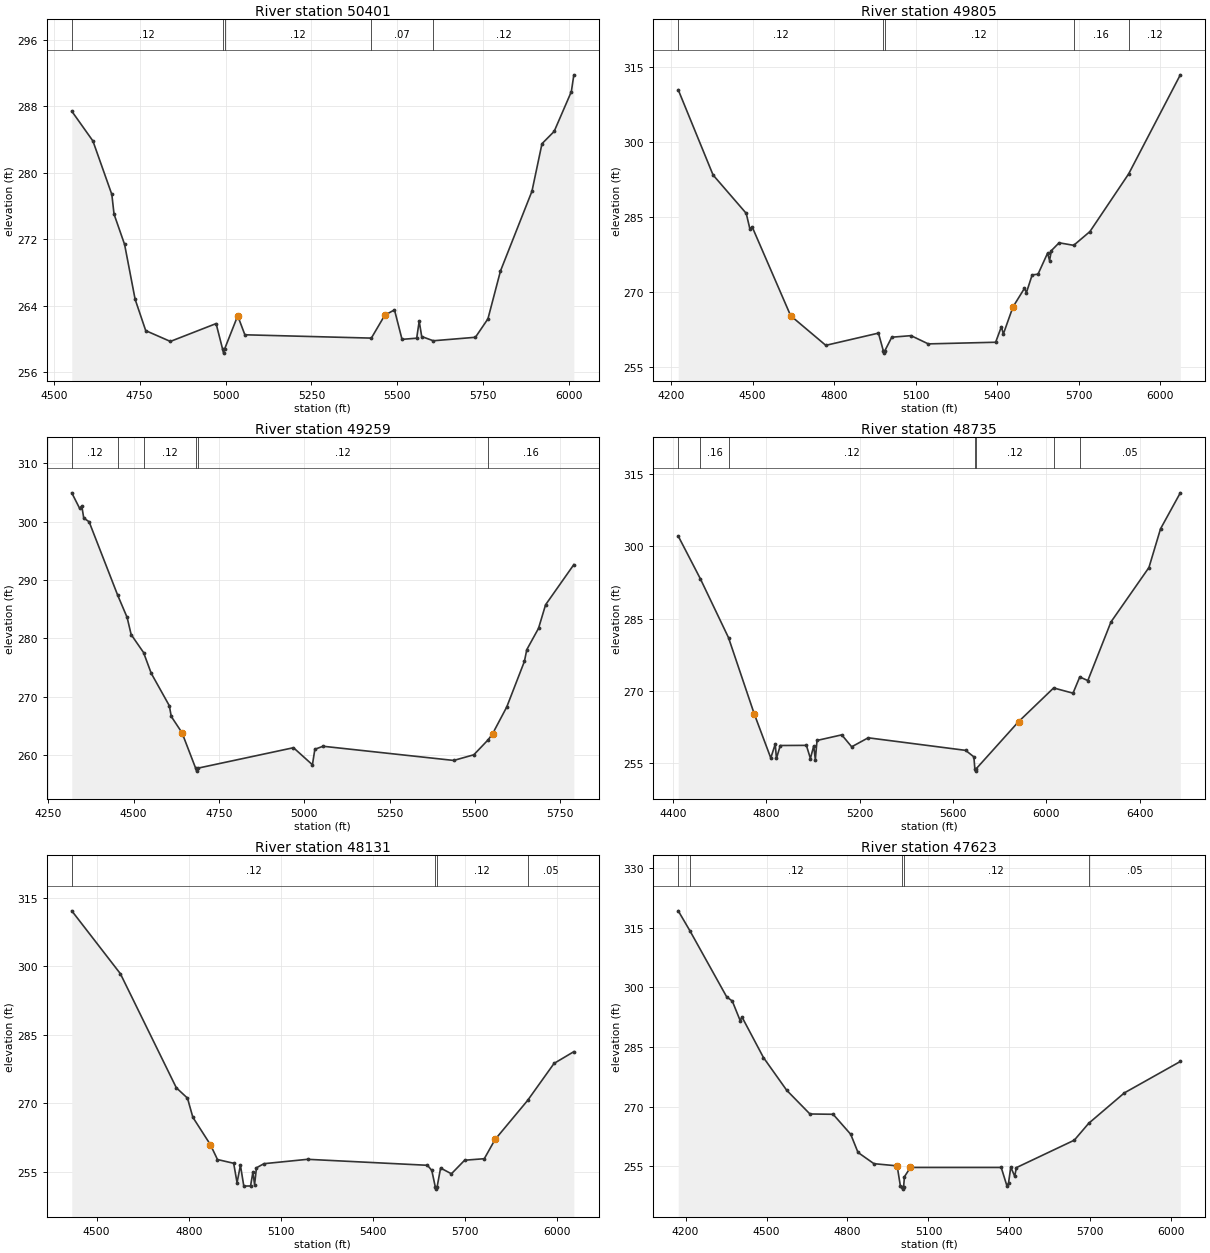
Type RM Length L Ch R = 1 ,50401   ,596,596,596
BEGIN DESCRIPTION:
KEECHIE CREEK 73.0
END DESCRIPTION:
XS GIS Cut Line= 3
      3717799.62     10638860.14      3717699.61     10639310.19
      3716899.63     10639910.18
#Sta/Elev= 30
  4552.5  287.43    4614  283.84  4669.1  277.39  4675.5  275.02  4706.2  271.37
  4736.9  264.75  4767.7  260.98  4839.4  259.68  4972.5  261.83  4991.3  258.77
  4994.1  258.27  4997.3  258.77  5035.4  262.77  5056.2  260.48  5424.2  260.08
  5463.5  262.85  5491.6  263.48  5513.5  259.93  5556.2  260.07  5563.5  262.13
  5570.8  260.27  5604.5  259.76  5727.1  260.18  5763.5   262.4    5800  268.17
  5891.6  277.78  5920.8  283.51  5956.2  284.99  6006.2  289.78  6013.5  291.81
#Mann= 5 ,-1 , 0
  4552.5     .12       0  4991.3     .07       0  4997.3     .12       0
  5424.2     .07       0  5604.5     .12       0
Bank Sta=5035.4,5463.5
XS Rating Curve= 0 ,0
Exp/Cntr=0.3,0.1

Type RM Length L Ch R = 1 ,49805   ,546,546,546
BEGIN DESCRIPTION:
KEECHIE CREEK 72.0
END DESCRIPTION:
XS GIS Cut Line= 3
       3717699.6     10638360.21      3717249.61     10638960.19
      3716499.59     10639760.21
#Sta/Elev= 30
  4226.6  310.46  4354.7   293.4  4476.6  285.72  4490.1  282.61  4498.5  283.01
  4640.1  265.21  4769.3  259.28    4963  261.73  4980.7  258.22  4983.4  257.72
  4986.7  258.22    5012  260.91  5082.8  261.22  5146.3  259.57    5394   259.9
  5415.2  263.02  5422.3  261.54  5457.5  266.95    5500   270.7  5507.3  269.86
  5528.3  273.39  5549.8  273.53    5585  277.74  5592.3  276.27  5599.1  278.26
  5627.4  279.82    5681  279.31  5740.8  282.07  5883.2  293.62  6073.2  313.46
#Mann= 5 ,-1 , 0
  4226.6     .12       0  4980.7     .07       0  4986.7     .12       0
    5681     .16       0  5883.2     .12       0
Bank Sta=4640.1,5457.5
XS Rating Curve= 0 ,0
Exp/Cntr=0.3,0.1

Type RM Length L Ch R = 1 ,49259   ,524,524,524
BEGIN DESCRIPTION:
KEECHIE CREEK 71.0
END DESCRIPTION:
XS GIS Cut Line= 3
      3717449.59      10638260.2      3716849.61     10638610.19
      3716649.61     10639360.18
#Sta/Elev= 30
  4318.7  304.92  4341.8  302.25    4348  302.66  4353.8  300.61  4369.5  299.96
  4453.4  287.36  4480.8  283.59  4492.7  280.64    4529  277.57  4551.5  274.01
  4604.4  268.47  4610.2  266.62  4641.6  263.84  4681.6  257.76  4684.3  257.26
  4687.6  257.76  4968.2  261.27  5023.7  258.35  5030.8     261  5054.7  261.52
  5437.6  259.09  5496.5  260.06  5538.5  262.63  5551.5  263.67  5592.9  268.24
  5644.6  276.04  5651.7  278.07    5686  281.71  5706.7  285.75  5789.5  292.63
#Mann= 6 ,-1 , 0
  4318.7     .12       0  4453.4     .16       0    4529     .12       0
  4681.6     .07       0  4687.6     .12       0  5538.5     .16       0
Bank Sta=4641.6,5551.5
XS Rating Curve= 0 ,0
Exp/Cntr=0.3,0.1

Type RM Length L Ch R = 1 ,48735   ,604,604,604
BEGIN DESCRIPTION:
KEECHIE CREEK 70.0
END DESCRIPTION:
XS GIS Cut Line= 3
      3717399.63     10638210.19      3716849.61     10638110.19
      3715699.62     10639210.18
#Sta/Elev= 30
  4423.3  302.13  4518.2  293.25  4638.6  281.04  4748.6  265.25  4819.7  256.05
  4838.8  258.95  4843.9  255.96  4860.4  258.65  4972.2  258.68  4989.4  255.95
  5003.6  258.57  5010.5  255.72  5017.7   259.7  5123.7  260.86  5166.2  258.38
  5236.9  260.25  5654.3  257.64  5689.5  256.29  5693.7  253.83  5696.5  253.33
  5699.7  253.83  5880.7  263.59  6031.2   270.6  6114.1  269.51    6143  272.88
  6177.6  272.13  6276.7   284.3  6439.3   295.6    6489  303.64  6573.7  311.11
#Mann= 7 ,-1 , 0
  4423.3     .12       0  4518.2     .16       0  4638.6     .12       0
  5693.7     .07       0  5699.7     .12       0  6031.2     .16       0
    6143     .05       0
Bank Sta=4748.6,5880.7
XS Rating Curve= 0 ,0
Exp/Cntr=0.3,0.1

Type RM Length L Ch R = 1 ,48131   ,508,508,508
BEGIN DESCRIPTION:
KEECHIE CREEK 69.0
END DESCRIPTION:
XS GIS Cut Line= 3
       3716699.6     10637360.21      3716449.61     10637910.19
      3715799.61     10638710.19
#Sta/Elev= 30
  4419.2  312.13  4577.4  298.37  4759.7  273.38  4795.9  271.12  4813.5  266.92
  4870.6  260.93  4893.7  257.67  4946.4  256.85  4957.4   252.6  4968.4  256.41
  4979.4  251.86  5001.4  251.88    5009  254.91  5014.5  252.18  5020.6  255.86
  5044.9  256.76  5187.1  257.72  5577.4  256.41  5591.5  255.29  5602.9  251.69
  5605.6  251.19  5608.9  251.69  5620.2  255.81  5655.4  254.55  5698.5  257.52
  5762.5  257.85  5797.6  262.06  5903.4   270.6  5989.7  278.72  6054.1  281.29
#Mann= 4 ,-1 , 0
  4419.2     .12       0  5602.9     .07       0  5608.9     .12       0
  5903.4     .05       0
Bank Sta=4870.6,5797.6
XS Rating Curve= 0 ,0
Exp/Cntr=0.3,0.1

Type RM Length L Ch R = 1 ,47623   ,522,522,522
BEGIN DESCRIPTION:
KEECHIE CREEK 68.0
END DESCRIPTION:
XS GIS Cut Line= 3
      3716699.63     10637260.18      3715999.61     10637760.19
      3715399.58     10638560.23
#Sta/Elev= 30
  4172.9  319.29  4216.2  314.26  4352.3  297.63  4373.2  296.56  4402.7  291.59
  4408.9  292.57  4488.7  282.33  4574.8  274.09  4660.8  268.12  4746.8  268.04
    4812     263    4839  258.43    4898   255.6    4984  255.05  4996.3  249.86
  5001.9  249.69  5004.6  249.19  5007.9  249.69    5011  252.31  5033.2  254.65
  5369.6  254.65  5390.4  250.09  5396.7   250.7    5405  254.75  5419.6  252.43
  5425.9  254.61  5640.4  261.52  5693.8  265.77  5825.9  273.43  6033.2  281.34
#Mann= 5 ,-1 , 0
  4172.9     .05       0  4216.2     .12       0  5001.9     .07       0
  5007.9     .12       0  5693.8     .05       0
Bank Sta=4984,5033.2
XS Rating Curve= 0 ,0
Exp/Cntr=0.3,0.1