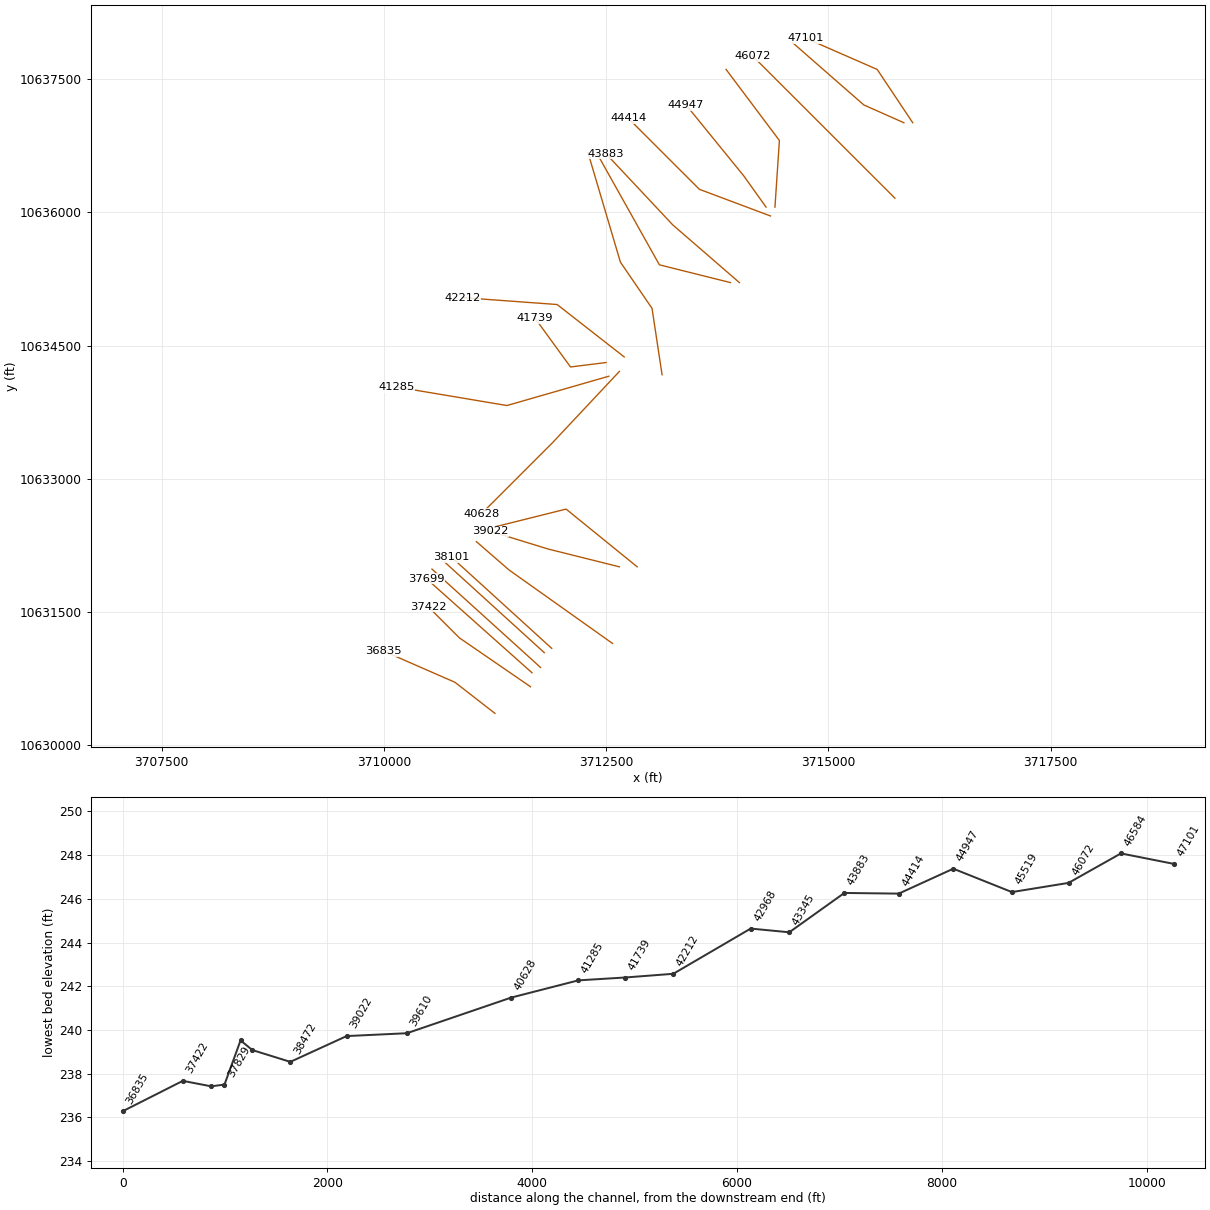
HEC-RAS study KEECHIE CREEK.prj: KEECHIE CREEK Base Level Engineering

--- KEECHIE CREEK.g01 (geometry) --- (continued)

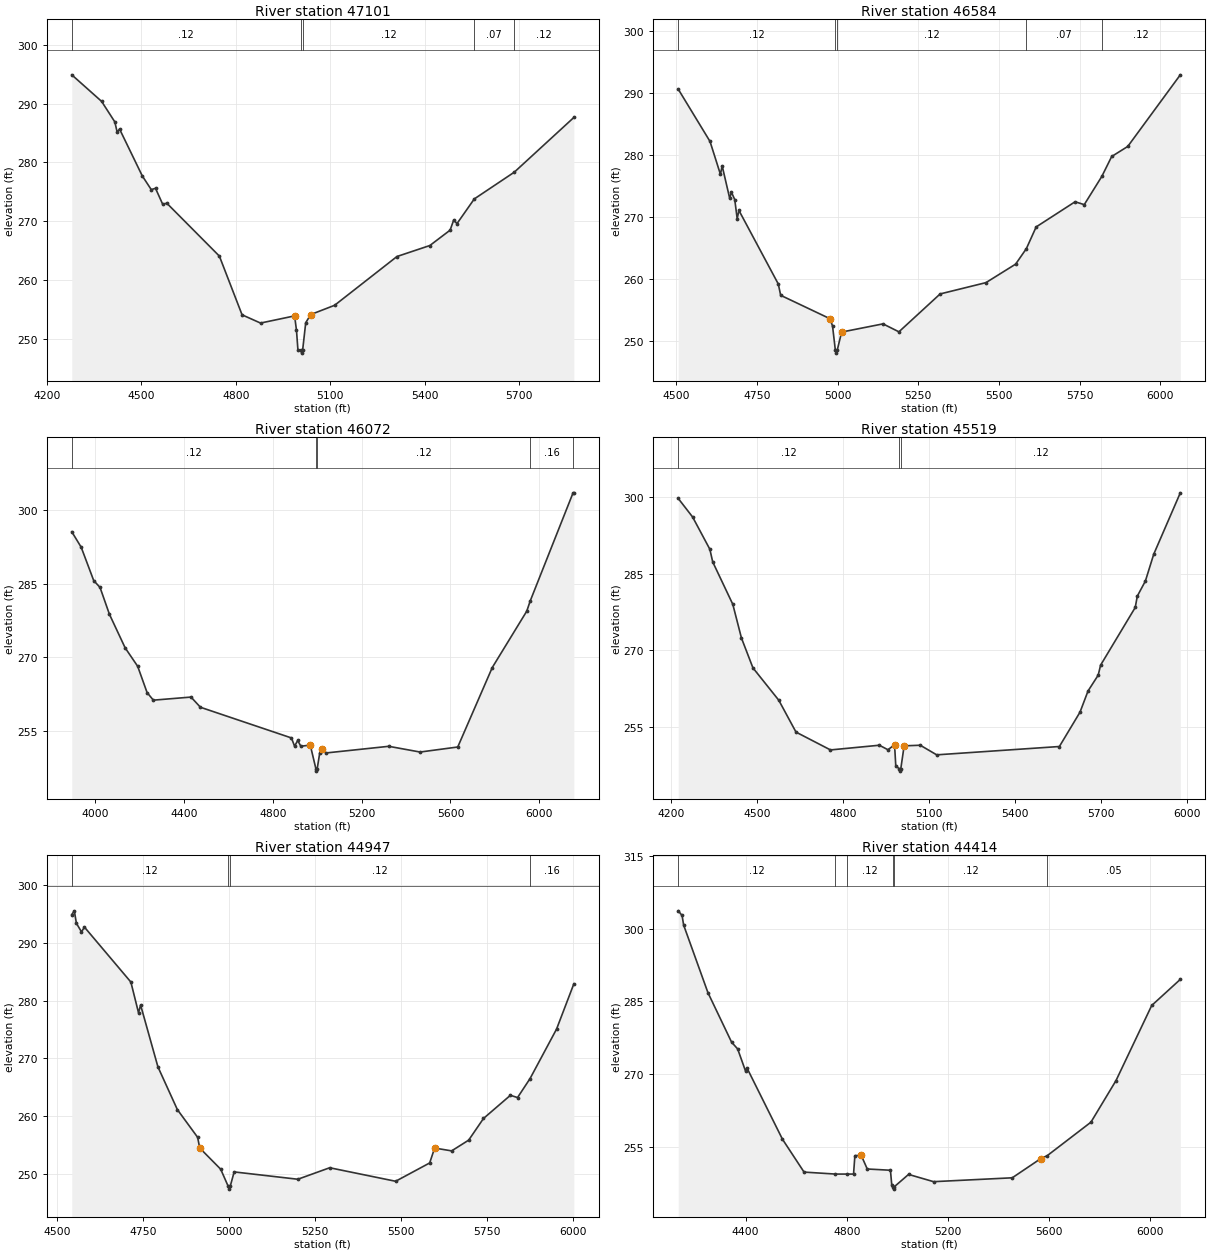
Type RM Length L Ch R = 1 ,47101   ,517,517,517
BEGIN DESCRIPTION:
KEECHIE CREEK 67.0
END DESCRIPTION:
XS GIS Cut Line= 3
      3715949.61     10637010.18      3715549.61     10637610.19
      3714749.64     10637960.18
#Sta/Elev= 30
  4279.3   294.9    4374  290.39    4416   286.9  4423.5  285.15    4431  285.69
  4503.2  277.72  4531.7  275.39  4545.2  275.61  4567.8  272.93  4581.3  273.07
    4748  264.09  4820.1  254.11  4878.7  252.71  4986.9  253.93  4992.9  251.47
  4997.4  248.18  5006.4   248.1  5009.1   247.6  5012.4   248.1  5022.2  252.77
  5038.2  254.16  5113.9  255.73  5311.9  264.02  5416.4  265.89  5480.7   268.5
    5492  270.21  5502.5  269.61  5557.5  273.81  5684.4  278.35  5873.6  287.65
#Mann= 5 ,-1 , 0
  4279.3     .12       0  5006.4     .07       0  5012.4     .12       0
  5557.5     .07       0  5684.4     .12       0
Bank Sta=4986.9,5038.2
XS Rating Curve= 0 ,0
Exp/Cntr=0.3,0.1

Type RM Length L Ch R = 1 ,46584   ,512,512,512
BEGIN DESCRIPTION:
KEECHIE CREEK 66.0
END DESCRIPTION:
XS GIS Cut Line= 3
      3715849.64     10637010.18      3715399.61     10637210.19
       3714599.6      10637910.2
#Sta/Elev= 30
  4506.4  290.58  4604.9  282.16  4637.1  276.87  4642.5  278.23  4665.8  273.01
  4671.3  273.98  4681.5   272.8    4689  269.74  4694.5  271.05  4816.3  259.22
  4823.8  257.39    4977  253.61  4984.5  252.43  4993.1  248.58  4995.9  248.08
  4999.1  248.58  5012.6  251.47  5140.8  252.79  5190.1  251.51  5317.8  257.61
  5459.7  259.43  5551.7  262.41    5585  264.91  5615.3   268.4  5735.9  272.45
  5764.3  271.99  5818.7  276.53  5849.3  279.74  5899.1  281.36  6061.9  292.89
#Mann= 5 ,-1 , 0
  4506.4     .12       0  4993.1     .07       0  4999.1     .12       0
    5585     .07       0  5818.7     .12       0
Bank Sta=4977,5012.6
XS Rating Curve= 0 ,0
Exp/Cntr=0.3,0.1

Type RM Length L Ch R = 1 ,46072   ,553,553,553
BEGIN DESCRIPTION:
KEECHIE CREEK 65.0
END DESCRIPTION:
XS GIS Cut Line= 3
      3715749.61     10636160.18      3714949.61     10636960.19
      3714149.64     10637760.15
#Sta/Elev= 30
  3893.2  295.64  3935.6  292.48  3992.2  285.65  4020.5  284.27  4062.9  278.78
  4133.6  271.93  4190.2  268.15  4232.6  262.78  4260.9  261.23  4430.6  261.86
    4473  259.78  4883.2  253.51  4897.3  251.83  4911.4  252.99  4925.6  251.81
    4968  252.06  4993.3  247.23    4996  246.73  4999.3  247.23  5010.4  250.36
    5021  251.29  5038.7  250.44  5321.6   251.8    5463  250.63  5632.7  251.66
  5788.3   267.9  5943.8  279.42  5959.2  281.49  6152.4  303.59  6155.9  303.59
#Mann= 5 ,-1 , 0
  3893.2     .12       0  4993.3     .07       0  4999.3     .12       0
  5959.2     .16       0  6152.4     .12       0
Bank Sta=4968,5021
XS Rating Curve= 0 ,0
Exp/Cntr=0.3,0.1

Type RM Length L Ch R = 1 ,45519   ,572,572,572
BEGIN DESCRIPTION:
KEECHIE CREEK 64.0
END DESCRIPTION:
XS GIS Cut Line= 3
      3714399.61     10636060.17      3714449.61     10636810.19
       3713849.6      10637610.2
#Sta/Elev= 30
  4224.8   299.7  4274.9  296.07  4335.1  289.75  4345.1  287.27  4415.2  278.97
  4445.3  272.38  4485.4  266.53  4575.6  260.19  4635.7  253.95    4756  250.46
  4926.4  251.38  4956.4   250.5  4979.6  251.47  4983.8  247.31  4995.4  246.81
  4998.1  246.31  5001.4  246.81  5012.9  251.26  5069.2  251.38  5126.5   249.5
  5554.6  251.13  5626.5  257.85  5654.6  262.01    5690   265.1  5698.4  267.06
  5819.2  278.35  5826.5  280.58  5854.6  283.52  5883.8  288.79  5976.5   300.8
#Mann= 3 ,-1 , 0
  4224.8     .12       0  4995.4     .07       0  5001.4     .12       0
Bank Sta=4979.6,5012.9
XS Rating Curve= 0 ,0
Exp/Cntr=0.3,0.1

Type RM Length L Ch R = 1 ,44947   ,533,533,533
BEGIN DESCRIPTION:
KEECHIE CREEK 63.0
END DESCRIPTION:
XS GIS Cut Line= 3
       3714299.6      10636060.2      3714049.61     10636410.19
       3713399.6      10637210.2
#Sta/Elev= 30
    4542   294.9  4549.4  295.55  4555.5  293.39  4570.3  291.91  4578.9  292.73
    4714  283.22  4736.2  277.91  4742.3  279.24  4792.7  268.54  4849.2  261.15
  4908.2  256.35  4914.3   254.5  4975.3  250.83  4997.1  247.88  4999.9  247.38
  5003.1  247.88  5014.5  250.36  5199.8  249.09  5292.5  251.08  5484.3  248.74
  5583.4  251.91  5597.8  254.49  5647.3     254  5696.9  255.86    5740  259.61
  5818.3  263.62  5839.1  263.23  5875.5  266.52  5952.6  275.08  6002.9  282.91
#Mann= 4 ,-1 , 0
    4542     .12       0  4997.1     .07       0  5003.1     .12       0
  5875.5     .16       0
Bank Sta=4914.3,5597.8
XS Rating Curve= 0 ,0
Exp/Cntr=0.3,0.1

Type RM Length L Ch R = 1 ,44414   ,531,531,531
BEGIN DESCRIPTION:
KEECHIE CREEK 62.0
END DESCRIPTION:
XS GIS Cut Line= 3
      3714349.65     10635960.17      3713549.61     10636260.19
      3712749.62     10637060.18
#Sta/Elev= 30
  4133.7  303.73  4148.9  302.77  4155.1  300.78  4251.2  286.82  4344.7   276.6
  4368.7   275.2  4399.9  270.63  4405.2  271.31  4545.8  256.56  4631.3  249.76
  4755.7  249.35  4801.2  249.35  4827.1  249.35  4832.4  253.15  4857.3  253.23
  4881.3   250.4    4973  250.14  4978.4  246.99  4982.5  246.74  4985.2  246.24
  4988.5  246.74  5044.7  249.28  5143.7  247.78  5454.8  248.58    5568  252.56
  5593.1  253.15    5766  260.07    5865  268.65  6006.4  284.18  6119.5  289.57
#Mann= 6 ,-1 , 0
  4133.7     .12       0  4755.7     .07       0  4801.2     .12       0
  4982.5     .07       0  4988.5     .12       0  5593.1     .05       0
Bank Sta=4857.3,5568
XS Rating Curve= 0 ,0
Exp/Cntr=0.3,0.1

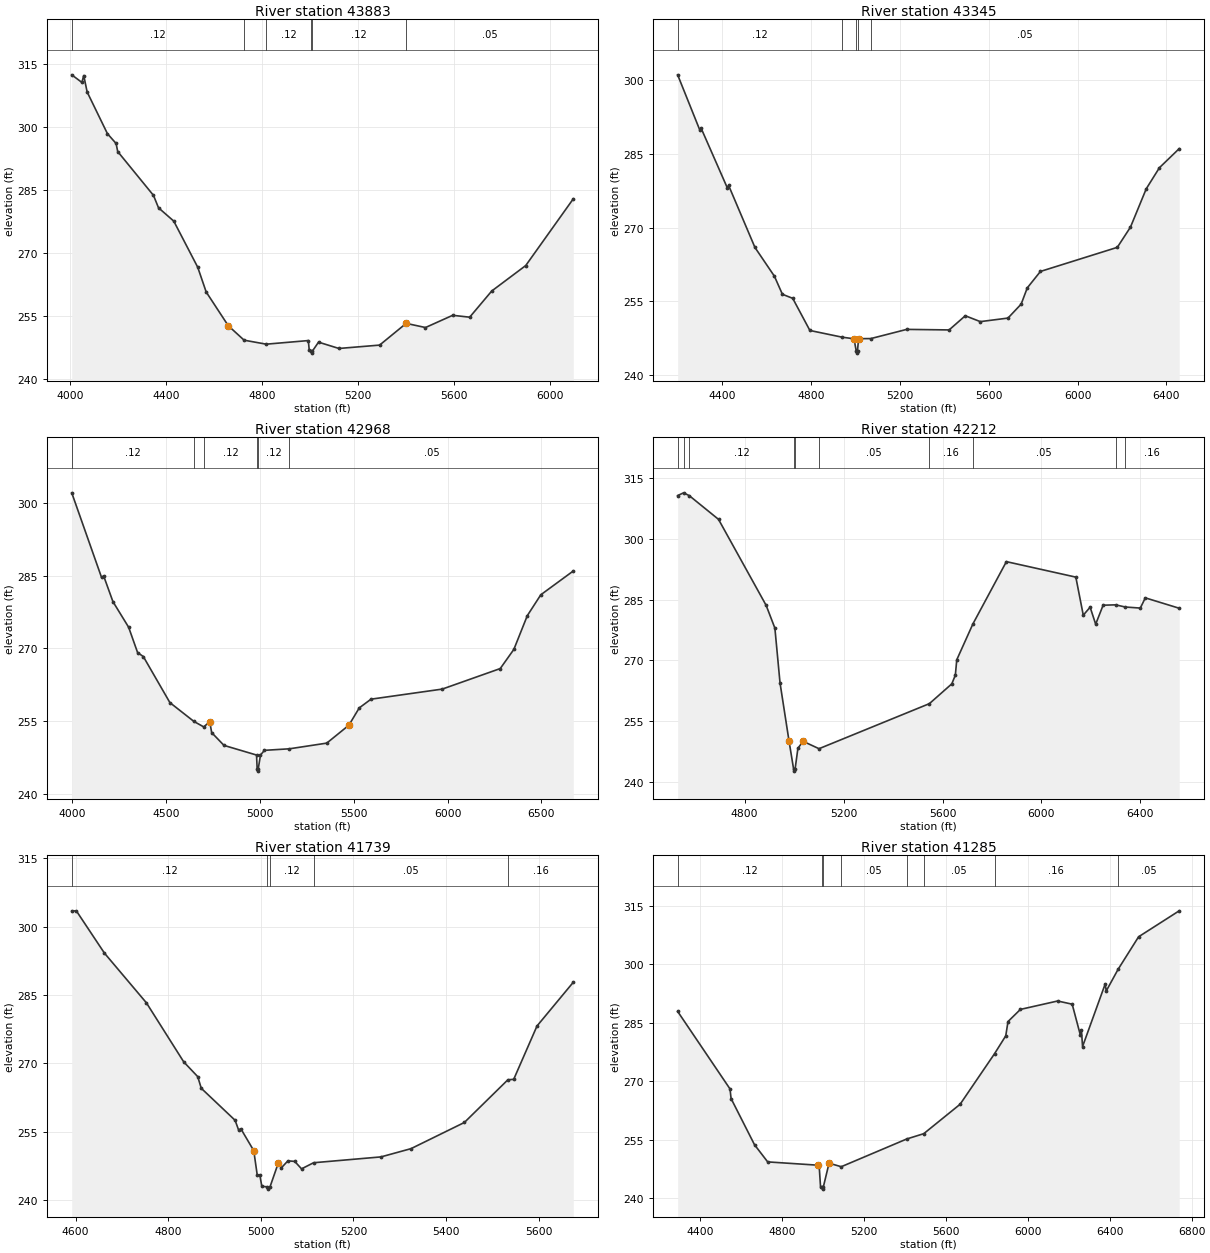
Type RM Length L Ch R = 1 ,43883   ,538,538,538
BEGIN DESCRIPTION:
KEECHIE CREEK 61.0
END DESCRIPTION:
XS GIS Cut Line= 3
      3713999.64     10635210.16      3713249.61     10635860.19
      3712499.61     10636660.19
#Sta/Elev= 30
  4007.8  312.49  4050.1  310.68  4057.7  312.32    4072   308.4  4156.5  298.48
  4192.6  296.15  4199.2  294.24  4348.3   283.8  4369.2  280.85  4432.8  277.68
  4532.6   266.7  4567.7  260.83  4659.8  252.79  4725.7  249.35  4817.9   248.4
  4993.2  249.26    4997  247.01  5004.4  246.77  5007.1  246.27  5010.4  246.77
  5035.7  248.88  5120.7  247.38  5290.2  248.18  5400.8  253.35  5481.2  252.36
  5594.5  255.27  5665.3  254.82  5757.2  261.05  5898.8  267.11  6096.9  282.99
#Mann= 6 ,-1 , 0
  4007.8     .12       0  4725.7     .05       0  4817.9     .12       0
  5004.4     .07       0  5010.4     .12       0  5400.8     .05       0
Bank Sta=4659.8,5400.8
XS Rating Curve= 0 ,0
Exp/Cntr=0.3,0.1

Type RM Length L Ch R = 1 ,43345   ,377,377,377
BEGIN DESCRIPTION:
KEECHIE CREEK 60.0
END DESCRIPTION:
XS GIS Cut Line= 3
      3713899.58      10635210.2      3713099.61     10635410.19
      3712399.63     10636660.15
#Sta/Elev= 30
  4200.1  301.09  4300.6  289.77  4305.7  290.24  4424.3  278.03  4429.4   278.6
    4548  265.97  4635.6  260.12  4671.6  256.44    4718  255.62  4795.3  249.08
  4940.8  247.71  4993.8  247.39  5003.6  244.97  5006.4  244.47  5009.6  244.97
  5014.4  247.41  5069.6  247.43    5231   249.3  5421.9  249.19  5494.6  252.07
  5562.3  250.88  5686.8   251.6  5746.1  254.44  5773.6  257.74  5832.9  261.09
  6178.8  265.99  6238.1  270.11    6309   277.9  6368.3  282.19  6457.3  286.07
#Mann= 5 ,-1 , 0
  4200.1     .12       0  4940.8     .07       0  5003.6     .07       0
  5009.6     .07       0  5069.6     .05       0
Bank Sta=4993.8,5014.4
XS Rating Curve= 0 ,0
Exp/Cntr=0.3,0.1

Type RM Length L Ch R = 1 ,42968   ,756,756,756
BEGIN DESCRIPTION:
KEECHIE CREEK 59.0
END DESCRIPTION:
XS GIS Cut Line= 4
      3713129.55      10634173.3       3713016.7     10634919.86
       3712660.8     10635440.69      3712296.21     10636673.35
#Sta/Elev= 30
  3998.3  302.08    4157  284.62  4168.7  284.88  4217.7  279.62  4301.3  274.34
  4349.1   269.1  4379.5  268.29  4521.1  258.78  4648.9   254.9  4701.2  253.77
  4733.4  254.83  4743.6  252.59  4809.2  249.95  4982.6  247.96  4985.7  245.14
  4988.4  244.64  4991.7  245.14  5003.6  247.96  5024.6  248.93  5157.9  249.25
  5356.5  250.42  5474.4  254.12  5529.6  257.69  5592.2  259.49  5971.5  261.57
  6280.5  265.81  6353.1  269.77  6424.8  276.74  6496.6  281.04  6669.6  285.95
#Mann= 6 ,-1 , 0
  3998.3     .12       0  4648.9     .16       0  4701.2     .12       0
  4985.7     .07       0  4991.7     .12       0  5157.9     .05       0
Bank Sta=4733.4,5474.4
XS Rating Curve= 0 ,0
Exp/Cntr=0.3,0.1

Type RM Length L Ch R = 1 ,42212   ,473,473,473
BEGIN DESCRIPTION:
KEECHIE CREEK 58.0
END DESCRIPTION:
XS GIS Cut Line= 3
      3712704.19     10634372.99      3711948.99     10634963.26
      3710882.95     10635041.26
#Sta/Elev= 30
  4529.3  310.76  4553.4  311.44  4576.4  310.74  4694.5  304.88  4887.1  283.59
  4922.4  277.96  4943.2   264.4  4979.3  250.13  4998.1  243.07  5000.8  242.57
  5004.1  243.07  5015.5  248.22  5036.4  249.95  5100.8  248.12    5547  259.27
  5637.6  264.17  5651.9  266.33  5657.6  270.12  5722.8  278.99  5858.2  294.41
  6138.9  290.58    6169  281.16  6196.7  283.14  6219.1  278.93  6249.2  283.63
  6299.7  283.72  6339.1  283.18  6399.6  282.92  6419.7  285.45  6556.7  282.88
#Mann= 10 ,-1 , 0
  4529.3     .12       0  4553.4     .16       0  4576.4     .12       0
  4998.1     .07       0  5004.1     .12       0  5100.8     .05       0
    5547     .16       0  5722.8     .05       0  6299.7     .12       0
  6339.1     .16       0
Bank Sta=4979.3,5036.4
XS Rating Curve= 0 ,0
Exp/Cntr=0.3,0.1

Type RM Length L Ch R = 1 ,41739   ,454,454,454
BEGIN DESCRIPTION:
KEECHIE CREEK 57.0
END DESCRIPTION:
XS GIS Cut Line= 3
      3712499.64     10634310.19      3712099.61     10634260.19
      3711699.62     10634810.18
#Sta/Elev= 30
  4591.5  303.46  4601.6  303.43  4662.1  294.18  4752.8  283.27  4833.4  270.31
  4863.6  267.08  4871.2  264.53  4944.3   257.5  4951.8  255.39  4956.8  255.63
  4984.6  250.84  4992.1   245.5  4997.7   245.5    5002  243.02  5013.7   242.9
  5016.4   242.4  5019.7   242.9  5037.5   248.1  5044.1  247.06  5058.4  248.61
  5073.1  248.48  5087.8  246.85  5113.8  248.19  5259.3  249.47  5324.2  251.28
  5439.4  257.02  5533.4  266.39    5546  266.49  5596.3  278.19  5674.7  287.79
#Mann= 5 ,-1 , 0
  4591.5     .12       0  5013.7     .07       0  5019.7     .12       0
  5113.8     .05       0  5533.4     .16       0
Bank Sta=4984.6,5037.5
XS Rating Curve= 0 ,0
Exp/Cntr=0.3,0.1

Type RM Length L Ch R = 1 ,41285   ,657,657,657
BEGIN DESCRIPTION:
KEECHIE CREEK 56.0
END DESCRIPTION:
XS GIS Cut Line= 3
      3712530.54     10634155.96      3711384.76     10633826.11
      3710144.03     10634034.34
#Sta/Elev= 30
  4288.8  287.88  4544.7  267.98  4549.9  265.52  4664.4  253.66  4728.7  249.26
  4974.9  248.41  4980.1  248.37    4987  242.83  4994.4  242.77  4997.1  242.27
  5000.4  242.77  5028.6  248.93  5088.1  248.02  5408.2  255.14  5491.2   256.5
  5668.9  264.05  5837.3  277.04  5891.9  281.61  5902.8  285.27  5963.4  288.39
  6145.4  290.55  6216.4  289.73  6256.4   281.8  6261.5  283.16  6267.1  278.86
  6377.7  294.92  6382.8  293.12  6440.6  298.67  6540.9  307.03  6739.2  313.69
#Mann= 8 ,-1 , 0
  4288.8     .12       0  4994.4     .07       0  5000.4     .12       0
  5088.1     .05       0  5408.2     .16       0  5491.2     .05       0
  5837.3     .16       0  6440.6     .05       0
Bank Sta=4974.9,5028.6
XS Rating Curve= 0 ,0
Exp/Cntr=0.3,0.1

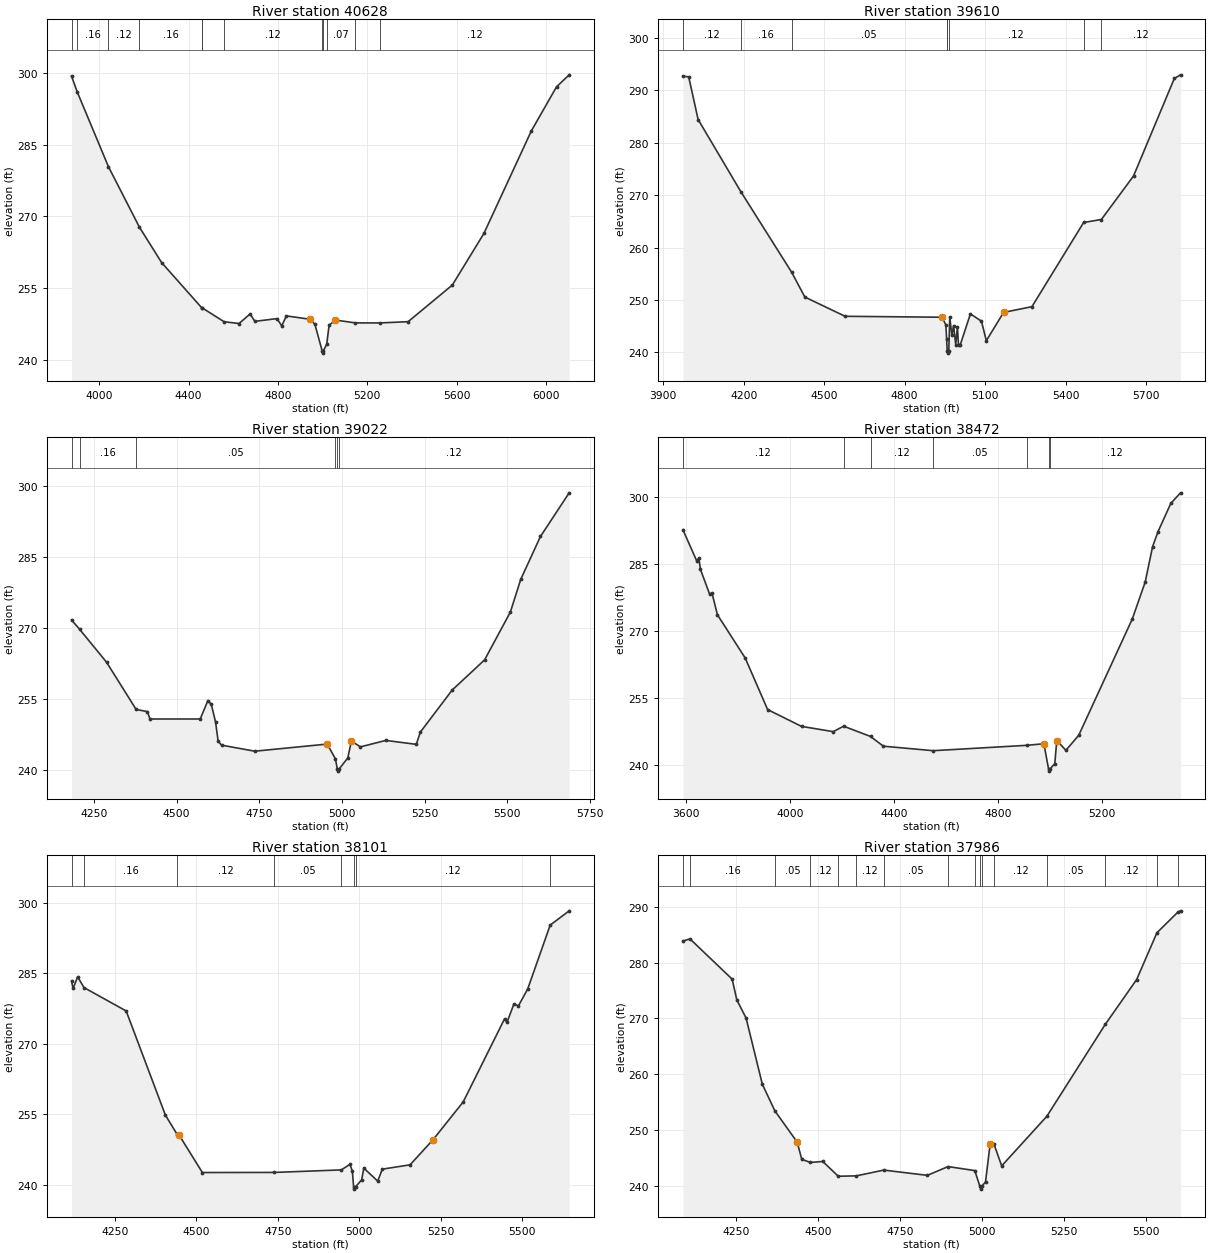
Type RM Length L Ch R = 1 ,40628   ,1018,1018,1018
BEGIN DESCRIPTION:
KEECHIE CREEK 55.0
END DESCRIPTION:
XS GIS Cut Line= 3
      3712649.58     10634210.15      3711899.61     10633410.19
      3711099.62      10632610.2
#Sta/Elev= 30
  3875.6  299.28  3900.7  296.02  4040.8  280.38  4179.6  267.75  4278.8  260.38
  4457.5  250.99  4459.2  250.96  4558.5  248.03  4625.6  247.66  4674.9  249.65
  4696.4  248.11  4795.1  248.68  4816.6  247.18  4837.6  249.25    4944  248.54
  4965.1  247.49  4997.4  241.98  5000.2  241.48  5003.4  241.98    5018  243.34
  5028.7   247.3    5057  248.38  5146.7  247.79  5255.8  247.78  5382.3  248.04
  5580.3  255.68  5721.7  266.45  5933.8  287.82  6046.9  297.05  6103.5  299.55
#Mann= 12 ,-1 , 0
  3875.6     .12       0  3900.7     .16       0  4040.8     .12       0
  4179.6     .16       0  4457.5     .12       0  4459.2     .16       0
  4558.5     .12       0  4997.4     .07       0  5003.4     .12       0
    5018     .07       0  5146.7     .05       0  5255.8     .12       0
Bank Sta=4944,5057
XS Rating Curve= 0 ,0
Exp/Cntr=0.3,0.1

Type RM Length L Ch R = 1 ,39610   ,588,588,588
BEGIN DESCRIPTION:
KEECHIE CREEK 54.0
END DESCRIPTION:
XS GIS Cut Line= 3
      3712849.62     10632010.18      3712049.61     10632660.19
      3711249.62     10632460.19
#Sta/Elev= 30
  3973.1  292.68  3994.7  292.58  4029.9  284.43  4188.9  270.68  4378.3  255.31
  4427.8  250.55  4577.9  246.88  4939.5   246.7  4953.6  245.22  4956.3  242.54
  4958.5  240.35  4961.3  239.85  4964.5  240.35    4968  246.77  4975.9  243.23
  4982.3   245.1  4990.3  241.48  4996.7   244.9  5000.7  241.32  5006.5  241.32
  5045.1  247.34  5086.3  245.94  5104.4  242.22  5168.8  247.62  5274.5  248.72
  5467.2  264.78  5533.3  265.35  5653.3  273.66  5805.3  292.26  5828.5  292.96
#Mann= 8 ,-1 , 0
  3973.1     .12       0  4188.9     .16       0  4378.3     .05       0
  4956.3     .12       0  4958.5     .07       0  4964.5     .12       0
  5467.2     .05       0  5533.3     .12       0
Bank Sta=4939.5,5168.8
XS Rating Curve= 0 ,0
Exp/Cntr=0.3,0.1

Type RM Length L Ch R = 1 ,39022   ,550,550,550
BEGIN DESCRIPTION:
KEECHIE CREEK 53.0
END DESCRIPTION:
XS GIS Cut Line= 3
      3712649.64     10632010.18      3711849.61     10632210.19
      3711199.63     10632410.18
#Sta/Elev= 30
  4182.1  271.67  4206.2  269.72  4287.8  262.75  4377.4  252.76  4411.5  252.29
  4419.2  250.74  4571.2  250.74  4594.4  254.64  4604.7  253.83  4617.6  250.09
  4625.4  246.04  4635.7  245.21  4736.2  243.93  4955.2  245.44  4979.9  242.32
  4985.7  240.22  4988.5  239.72  4991.7  240.22  5017.2  242.48  5028.3  246.06
  5055.8  244.85  5132.3  246.21  5224.5  245.38  5236.9  247.98  5333.1  256.86
  5431.1  263.24    5509  273.35  5540.3  280.24  5599.9  289.31  5686.8  298.54
#Mann= 6 ,-1 , 0
  4182.1     .12       0  4206.2     .16       0  4377.4     .05       0
  4979.9     .12       0  4985.7     .07       0  4991.7     .12       0
Bank Sta=4955.2,5028.3
XS Rating Curve= 0 ,0
Exp/Cntr=0.3,0.1

Type RM Length L Ch R = 1 ,38472   ,371,371,371
BEGIN DESCRIPTION:
KEECHIE CREEK 52.0
END DESCRIPTION:
XS GIS Cut Line= 3
      3712572.04     10631147.67      3711408.87     10631974.04
       3711040.8      10632293.5
#Sta/Elev= 30
  3588.3  292.75  3641.1   285.8  3649.8  286.38  3655.9  283.83  3691.6  278.21
  3700.2  278.54  3721.1  273.65  3828.1  263.93  3914.2  252.36  4044.6  248.59
  4166.4  247.41  4206.5  248.63  4310.2  246.32  4359.5  244.14  4550.8  243.13
  4910.4  244.33  4976.9  244.69  4994.8  239.04  4997.6  238.54  5000.8  239.04
  5018.8  240.22  5026.5   245.4  5061.6  243.22  5110.9  246.59    5317  272.72
  5366.4  280.97  5394.9  288.93  5415.8  292.31  5465.1  298.67  5502.5  301.04
#Mann= 7 ,-1 , 0
  3588.3     .12       0  4206.5     .05       0  4310.2     .12       0
  4550.8     .05       0  4910.4     .12       0  4994.8     .07       0
  5000.8     .12       0
Bank Sta=4976.9,5026.5
XS Rating Curve= 0 ,0
Exp/Cntr=0.3,0.1

Type RM Length L Ch R = 1 ,38101   ,115,115,115
BEGIN DESCRIPTION:
Mapping XS d688e083
END DESCRIPTION:
XS GIS Cut Line= 2
      3711888.07     10631092.07      3710759.57     10632119.87
#Sta/Elev= 30
    4117   283.3  4121.7  281.75  4135.8  284.23  4155.1  281.94  4284.5  276.97
  4404.8  254.83  4440.6  250.75  4447.3  250.53  4518.3  242.61  4738.8  242.63
  4944.6  243.17    4971  244.35  4978.4  242.87  4982.2  239.58  4984.9  239.08
  4988.2  239.58  5006.8  241.05  5013.5  243.55  5056.1  240.78  5070.3  243.33
  5155.4  244.25  5225.7  249.58  5318.3  257.62  5445.3  275.31  5452.7  274.55
  5473.7  278.43  5487.9  278.07  5516.2  281.64  5585.1  295.22  5643.4  298.26
#Mann= 8 ,-1 , 0
    4117      .1       0  4155.1     .16       0  4440.6     .12       0
  4738.8     .05       0  4944.6     .12       0  4982.2     .07       0
  4988.2     .12       0  5585.1     .05       0
Bank Sta=4447.3,5225.7
XS Rating Curve= 0 ,0
Exp/Cntr=0.3,0.1

Type RM Length L Ch R = 1 ,37986   ,157,157,157
BEGIN DESCRIPTION:
KEECHIE CREEK 51.0
END DESCRIPTION:
XS GIS Cut Line= 2
      3711804.69     10631043.49      3710683.87     10632063.69
#Sta/Elev= 30
  4088.9  283.83  4110.6  284.21  4238.9  277.03  4253.1  273.33  4281.4  270.06
  4330.8  258.26  4369.1  253.49  4436.8  247.93    4451  244.83  4477.3  244.29
    4515  244.46    4562  241.82    4617  241.89  4700.7  242.92  4833.5  241.98
  4896.5  243.55    4978  242.83  4993.3  240.02  4996.1  239.52  4999.3  240.02
  5010.5  240.81  5024.7  247.61  5036.3  247.56  5059.8  243.67  5197.6  252.55
  5375.4  268.96  5470.7  276.94  5532.6  285.31  5595.3  288.94  5604.5  289.23
#Mann= 16 ,-1 , 0
  4088.9     .05       0  4110.6     .16       0  4369.1     .05       0
  4477.3     .12       0    4562     .08       0    4617     .12       0
  4700.7     .05       0  4896.5     .12       0    4978     .08       0
  4993.3     .07       0  4999.3     .08       0  5036.3     .12       0
  5197.6     .05       0  5375.4     .12       0  5532.6     .08       0
  5595.3     .05       0
Bank Sta=4436.8,5024.7
XS Rating Curve= 0 ,0
Exp/Cntr=0.3,0.1

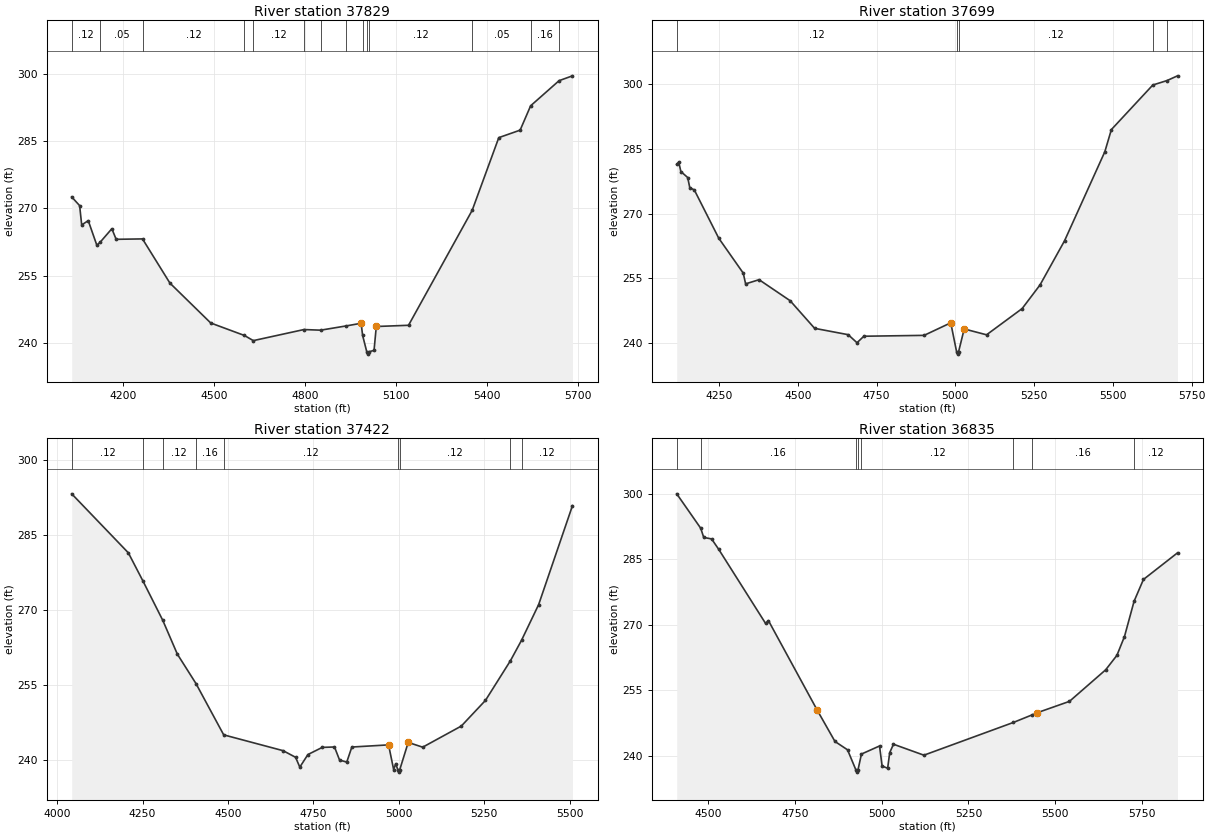
Type RM Length L Ch R = 1 ,37829   ,130,130,130
BEGIN DESCRIPTION:
Mapping XS f7b31e06
END DESCRIPTION:
XS GIS Cut Line= 2
      3711763.03     10630876.82      3710540.78     10631984.49
#Sta/Elev= 30
    4032  272.55  4058.1  270.61  4064.9  266.31  4086.5  267.26  4114.9  261.76
  4126.6  262.52  4164.2  265.46  4178.4   263.1  4265.2  263.19  4355.5  253.34
    4490  244.44  4600.9  241.66  4630.2  240.51    4797  242.98  4851.9  242.84
  4937.1   243.8  4985.3  244.38  4990.3  241.66    5004     238  5006.7   237.5
    5010     238  5027.9  238.34  5035.3  243.66  5141.5  243.93  5351.2  269.57
  5438.8  285.77  5509.1  287.44  5543.7  292.87  5637.4  298.47  5681.5  299.55
#Mann= 14 ,-1 , 0
    4032     .12       0  4126.6     .05       0  4265.2     .12       0
  4600.9     .08       0  4630.2     .12       0    4797     .05       0
  4851.9     .12       0  4937.1     .08       0  4990.3     .12       0
    5004     .07       0    5010     .12       0  5351.2     .05       0
  5543.7     .16       0  5637.4     .05       0
Bank Sta=4985.3,5035.3
XS Rating Curve= 0 ,0
Exp/Cntr=0.3,0.1

Type RM Length L Ch R = 1 ,37699   ,277,277,277
BEGIN DESCRIPTION:
Mapping XS ae3d074a
END DESCRIPTION:
XS GIS Cut Line= 2
       3711665.8      10630817.8      3710479.22     10631876.01
#Sta/Elev= 30
  4115.2   281.4  4121.6  281.97  4128.3  279.76    4150  278.37  4156.7  275.99
  4170.9  275.51  4248.6   264.3  4326.4   256.2  4333.9  253.71  4376.6  254.68
  4475.2  249.81    4553   243.4  4659.5  241.93  4687.6  240.06  4709.3  241.57
  4900.6  241.77  4985.2  244.68  5003.9  237.92  5006.7  237.42  5009.9  237.92
  5027.9  243.26  5098.9   241.9  5211.8  247.98  5268.6  253.46  5346.4  263.69
  5474.3  284.33  5495.2  289.49  5626.7  299.82  5672.2  300.86  5705.1  301.95
#Mann= 5 ,-1 , 0
  4115.2     .12       0  5003.9     .07       0  5009.9     .12       0
  5626.7     .16       0  5672.2     .05       0
Bank Sta=4985.2,5027.9
XS Rating Curve= 0 ,0
Exp/Cntr=0.3,0.1

Type RM Length L Ch R = 1 ,37422   ,587,587,587
BEGIN DESCRIPTION:
KEECHIE CREEK 50.0
END DESCRIPTION:
XS GIS Cut Line= 3
      3711649.61     10630660.19      3710849.61     10631210.19
      3710499.61     10631560.19
#Sta/Elev= 30
  4042.7  293.23  4208.5  281.45  4251.8  275.75  4309.3  267.97  4351.9  261.23
  4406.4  255.36  4487.6  245.11  4661.6  241.95    4698  240.63  4710.4  238.67
  4734.1  241.18  4776.1  242.61  4811.9  242.69  4826.8  240.08  4847.8  239.67
  4862.7  242.68  4970.2  243.11  4985.1  238.17  4991.2  239.37    4997  238.17
  4999.8  237.67    5003  238.17  5027.7   243.6  5070.1  242.65  5183.2  246.87
  5253.9     252  5326.8   259.9  5359.3  263.98  5409.5  271.12  5508.5  290.87
#Mann= 9 ,-1 , 0
  4042.7     .12       0  4251.8     .16       0  4309.3     .12       0
  4406.4     .16       0  4487.6     .12       0    4997     .07       0
    5003     .12       0  5326.8     .16       0  5359.3     .12       0
Bank Sta=4970.2,5027.7
XS Rating Curve= 0 ,0
Exp/Cntr=0.3,0.1

Type RM Length L Ch R = 1 ,36835   ,771,771,771
BEGIN DESCRIPTION:
KEECHIE CREEK 49.0
END DESCRIPTION:
XS GIS Cut Line= 3
      3711249.63     10630360.17      3710799.61     10630710.19
      3709999.63     10631060.18
#Sta/Elev= 30
  4409.2  300.03  4478.3  292.15    4487  290.04  4509.7   289.7  4530.5  287.28
  4665.3  270.34  4673.5  270.99  4814.6   250.4  4865.3   243.3  4901.5  241.39
  4925.6  236.78  4928.4  236.28  4931.6  236.78  4941.6  240.42  4993.7  242.27
  5001.1  237.68  5017.1  237.17    5023  240.73  5033.9  242.67  5121.6  240.16
  5379.8  247.67  5432.1  249.35  5448.7   249.9  5541.1  252.49  5645.5  259.72
  5677.9  263.03  5699.7  267.34  5727.4  275.43  5754.3  280.41  5852.5  286.51
#Mann= 8 ,-1 , 0
  4409.2     .05       0  4478.3     .16       0  4925.6     .07       0
  4931.6     .16       0  4941.6     .12       0  5379.8     .05       0
  5432.1     .16       0  5727.4     .12       0
Bank Sta=4814.6,5448.7
XS Rating Curve= 0 ,0
Exp/Cntr=0.3,0.1