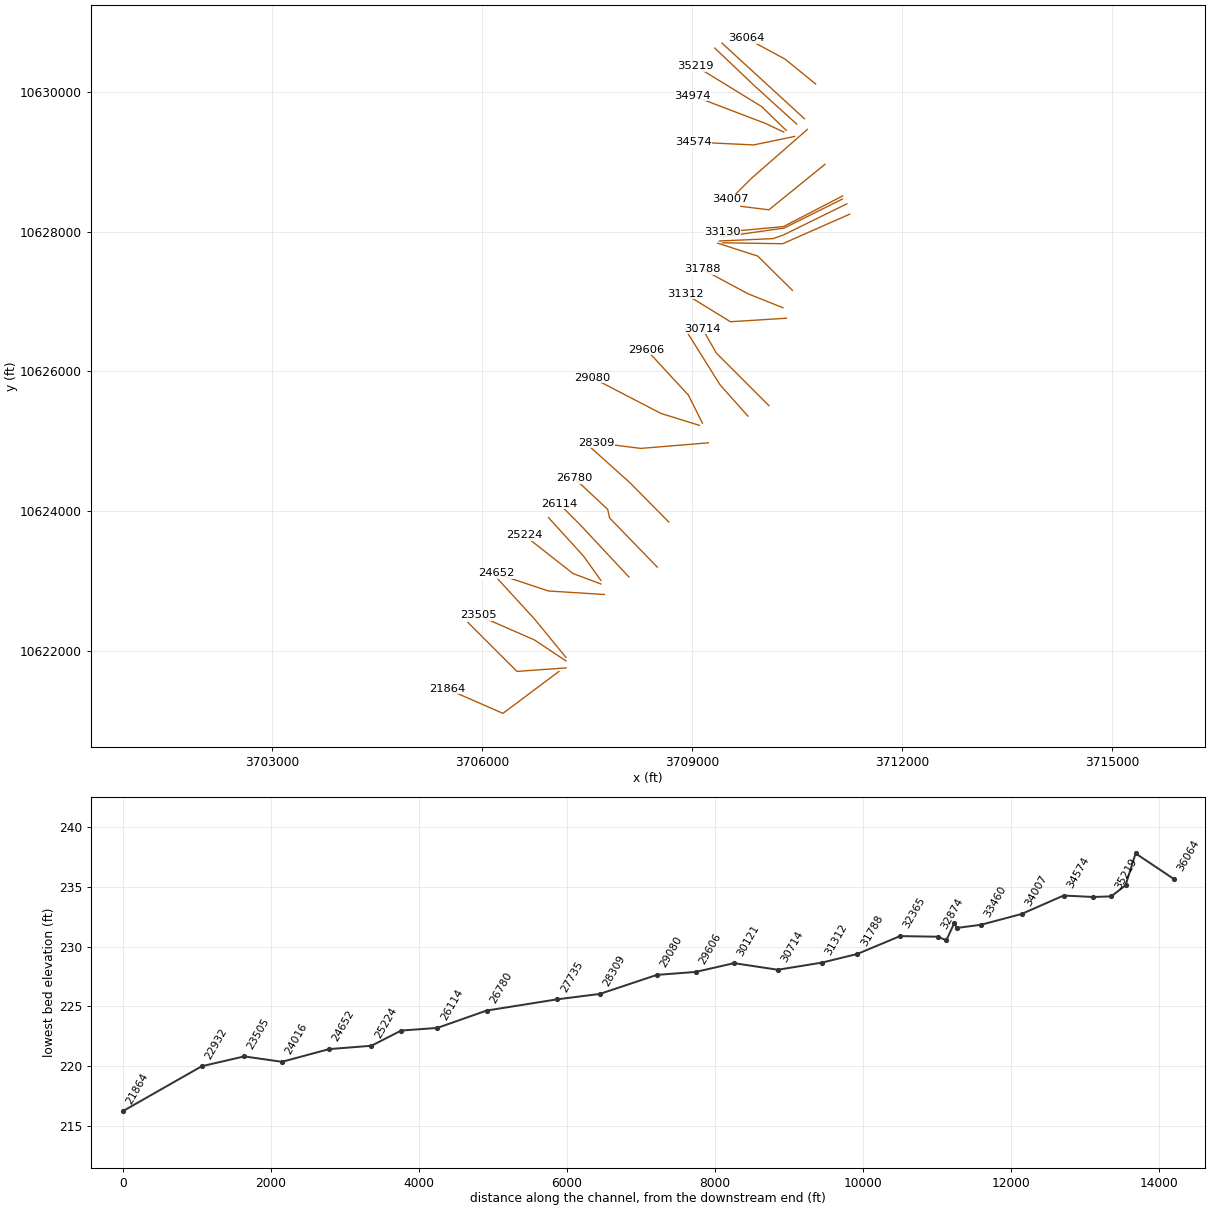
HEC-RAS study KEECHIE CREEK.prj: KEECHIE CREEK Base Level Engineering

--- KEECHIE CREEK.g01 (geometry) --- (continued)

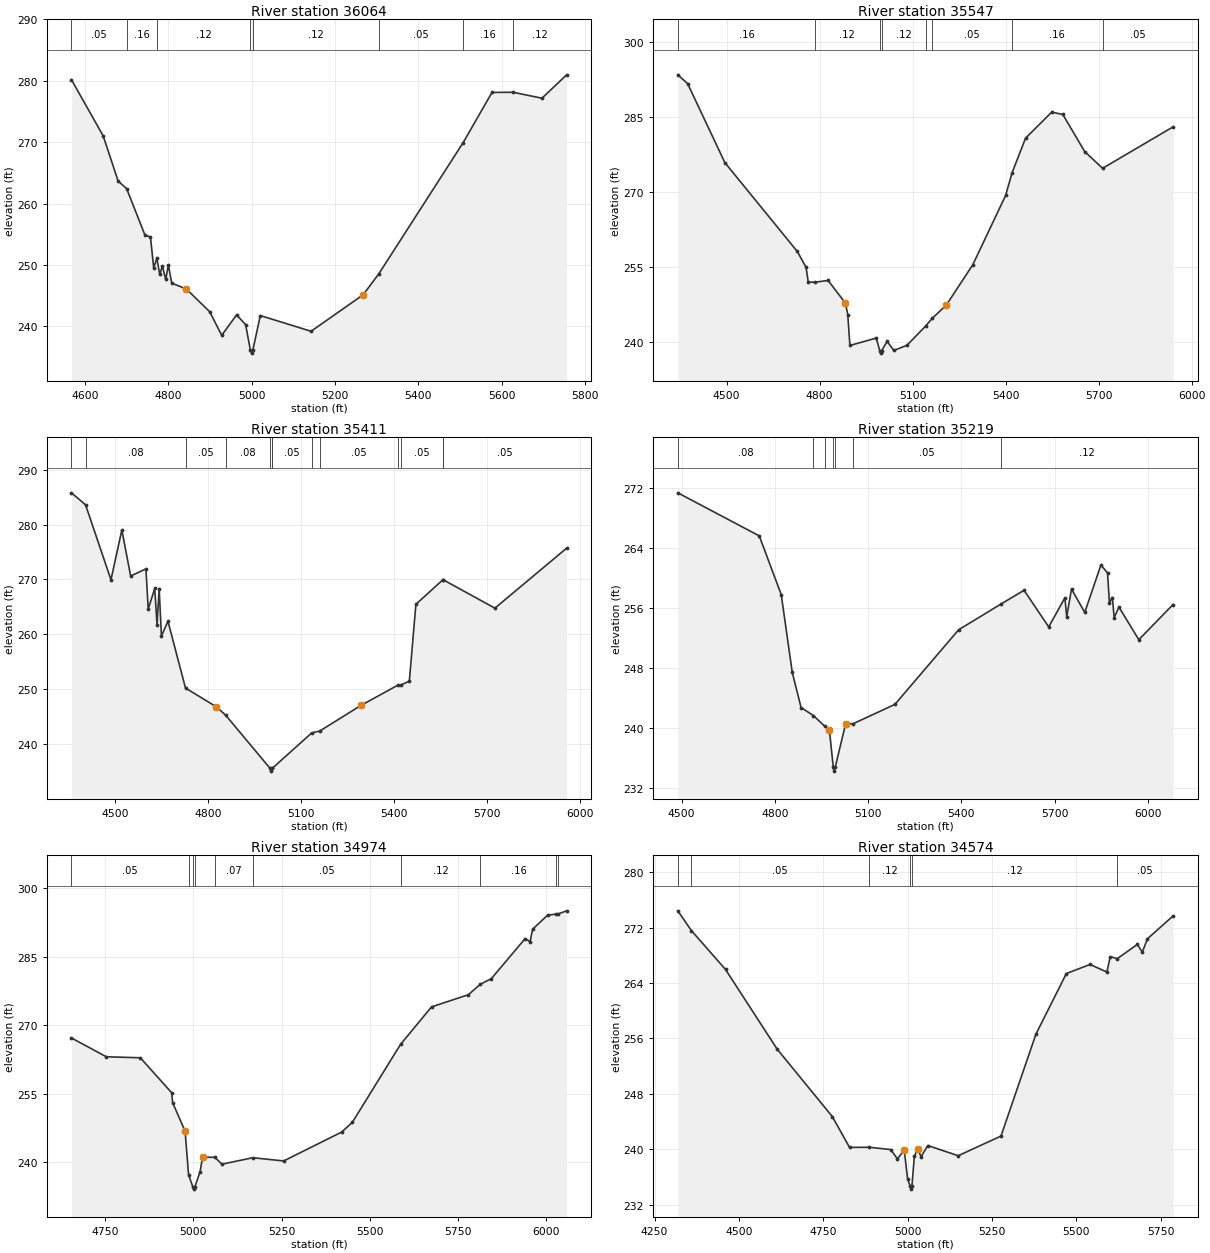
Type RM Length L Ch R = 1 ,36064   ,517,517,517
BEGIN DESCRIPTION:
KEECHIE CREEK 48.0
END DESCRIPTION:
XS GIS Cut Line= 3
      3710766.47     10630109.49      3710332.48     10630463.62
       3709780.4     10630762.23
#Sta/Elev= 30
  4567.9  280.18    4644  271.03    4680  263.66  4700.3  262.44  4744.5  254.82
  4757.4  254.59  4765.3   249.5  4772.7   251.1  4779.7  248.47  4786.1   249.8
    4794  247.65  4800.5  249.97  4808.4  247.04  4843.6  246.09  4899.6  242.38
  4928.3  238.54    4964  241.86  4985.7  240.29  4997.1  236.14  4999.9  235.64
  5003.1  236.14  5020.9  241.76  5142.7   239.2  5267.7  245.15  5305.5  248.59
  5507.6  269.94  5576.6   278.1  5627.2  278.13  5696.5  277.16  5755.7  280.97
#Mann= 8 ,-1 , 0
  4567.9     .05       0  4700.3     .16       0  4772.7     .12       0
  4997.1     .07       0  5003.1     .12       0  5305.5     .05       0
  5507.6     .16       0  5627.2     .12       0
Bank Sta=4843.6,5267.7
XS Rating Curve= 0 ,0
Exp/Cntr=0.3,0.1

Type RM Length L Ch R = 1 ,35547   ,136,136,136
BEGIN DESCRIPTION:
Mapping XS 8ed04840
END DESCRIPTION:
XS GIS Cut Line= 2
      3710606.77     10629612.95      3709429.67     10630692.82
#Sta/Elev= 30
  4342.6  293.49  4374.1  291.74  4494.3  275.92    4728  258.13  4756.4  254.93
  4763.2  252.01  4784.9  251.97  4827.3  252.33  4883.4  247.77  4890.8   245.5
  4897.6  239.31  4982.7  240.79  4993.9  238.28  4996.6  237.78  4999.9  238.28
  5017.8  240.12  5039.4  238.31  5081.9  239.36  5142.2  243.22  5163.1  244.74
    5209  247.43  5294.1  255.48  5400.1  269.36  5420.6  273.86  5464.2   280.8
  5548.7  286.03  5584.5  285.55  5655.1  278.12  5712.8  274.78    5940  283.07
#Mann= 8 ,-1 , 0
  4342.6     .16       0  4784.9     .12       0  4993.9     .07       0
  4999.9     .12       0  5142.2     .16       0  5163.1     .05       0
  5420.6     .16       0  5712.8     .05       0
Bank Sta=4883.4,5209
XS Rating Curve= 0 ,0
Exp/Cntr=0.3,0.1

Type RM Length L Ch R = 1 ,35411   ,192,192,192
BEGIN DESCRIPTION:
KEECHIE CREEK 47.0
END DESCRIPTION:
XS GIS Cut Line= 3
      3710495.69     10629536.53      3709888.03     10630088.62
      3709325.54     10630623.34
#Sta/Elev= 30
  4360.3  285.77  4405.9  283.59  4487.8  269.94  4522.9  279.02  4551.3  270.63
  4600.6  271.93    4608  264.63    4629  268.36  4636.4  261.74  4643.2  268.34
  4650.6  259.71  4671.6  262.39  4728.2  250.24  4827.7  246.82  4857.9  245.29
    5001  235.62  5003.8  235.12    5007  235.62  5007.9  235.62    5135  242.07
  5161.2  242.42  5294.4  247.09    5412  250.73  5422.1  250.78  5450.1   251.5
  5471.2  265.48  5558.9  269.98  5559.1  269.95    5726  264.78  5957.4   275.7
#Mann= 13 ,-1 , 0
  4360.3     .16       0  4405.9     .08       0  4728.2     .05       0
  4857.9     .08       0    5001     .07       0    5007     .08       0
  5007.9     .05       0    5135     .08       0  5161.2     .05       0
    5412     .08       0  5422.1     .05       0  5558.9     .16       0
  5559.1     .05       0
Bank Sta=4827.7,5294.4
XS Rating Curve= 0 ,0
Exp/Cntr=0.3,0.1

Type RM Length L Ch R = 1 ,35219   ,245,245,245
BEGIN DESCRIPTION:
KEECHIE CREEK 46.0
END DESCRIPTION:
XS GIS Cut Line= 3
      3710346.38     10629446.25      3709995.67     10629786.54
      3709053.88     10630364.78
#Sta/Elev= 30
  4487.7  271.29  4749.8  265.55  4820.5  257.72    4856  247.35  4884.3  242.67
  4924.2  241.59  4960.6  240.17  4975.4  239.69  4988.1  234.69  4990.9  234.19
  4994.1  234.69  5027.8   240.5  5051.9  240.51  5186.4  243.09  5391.3  253.03
  5527.5  256.46    5602   258.3  5681.3  253.42  5733.4  257.29  5739.3  254.78
  5754.7  258.46  5797.3  255.35  5849.4  261.67  5870.7  260.61  5876.6  256.65
  5886.2  257.33    5892  254.66  5907.5  256.05  5971.3  251.71  6081.5   256.4
#Mann= 7 ,-1 , 0
  4487.7     .08       0  4924.2     .12       0  4960.6      .1       0
  4988.1     .07       0  4994.1      .1       0  5051.9     .05       0
  5527.5     .12       0
Bank Sta=4975.4,5027.8
XS Rating Curve= 0 ,0
Exp/Cntr=0.3,0.1

Type RM Length L Ch R = 1 ,34974   ,400,400,400
BEGIN DESCRIPTION:
Mapping XS a26ecba7
END DESCRIPTION:
XS GIS Cut Line= 3
      3710311.64     10629421.96       3710054.7     10629543.49
      3709009.52     10629942.81
#Sta/Elev= 30
  4654.8   267.2  4753.5  263.09  4850.1  262.86    4939   255.2  4941.5  253.05
  4976.9   246.8  4986.7  237.31  4998.6  234.64  5001.4  234.14  5004.6  234.64
  5019.4  237.98  5026.3  241.13  5061.3   241.1  5081.1  239.59  5168.8  241.01
  5256.1   240.3  5420.5  246.62  5450.6  248.73  5587.3   265.8    5675  273.99
  5779.3  276.65  5813.7  278.95  5844.7  280.18    5940  288.91  5954.3  288.28
  5961.5  290.98  6003.7  294.04  6028.7   294.3  6033.2   294.3  6057.9     295
#Mann= 10 ,-1 , 0
  4654.8     .05       0  4986.7     .12       0  4998.6     .07       0
  5004.6     .12       0  5061.3     .07       0  5168.8     .05       0
  5587.3     .12       0  5813.7     .16       0  6028.7     .05       0
  6033.2     .16       0
Bank Sta=4976.9,5026.3
XS Rating Curve= 0 ,0
Exp/Cntr=0.3,0.1

Type RM Length L Ch R = 1 ,34574   ,567,567,567
BEGIN DESCRIPTION:
KEECHIE CREEK 45.0
END DESCRIPTION:
XS GIS Cut Line= 3
      3710467.93     10629359.47      3709881.09     10629237.93
      3709013.78     10629279.56
#Sta/Elev= 30
  4319.1  274.42  4359.3  271.57  4460.4  265.96  4613.5  254.46  4776.9  244.73
    4828  240.28  4886.1   240.3  4949.9  239.97  4969.9  238.62    4990  239.94
    5000  235.73    5007  234.76  5009.7  234.26    5013  234.76    5020  239.01
    5030  240.03    5040  238.95    5060  240.55  5150.1  239.08  5276.8  241.92
  5380.4  256.63  5470.5  265.37  5540.6  266.68  5590.6  265.59  5600.7  267.81
  5621.6  267.52  5680.7  269.57  5695.6  268.46  5710.8  270.38  5786.7  273.68
#Mann= 6 ,-1 , 0
  4319.1     .08       0  4359.3     .05       0  4886.1     .12       0
    5007     .07       0    5013     .12       0  5621.6     .05       0
Bank Sta=4990,5030
XS Rating Curve= 0 ,0
Exp/Cntr=0.3,0.1

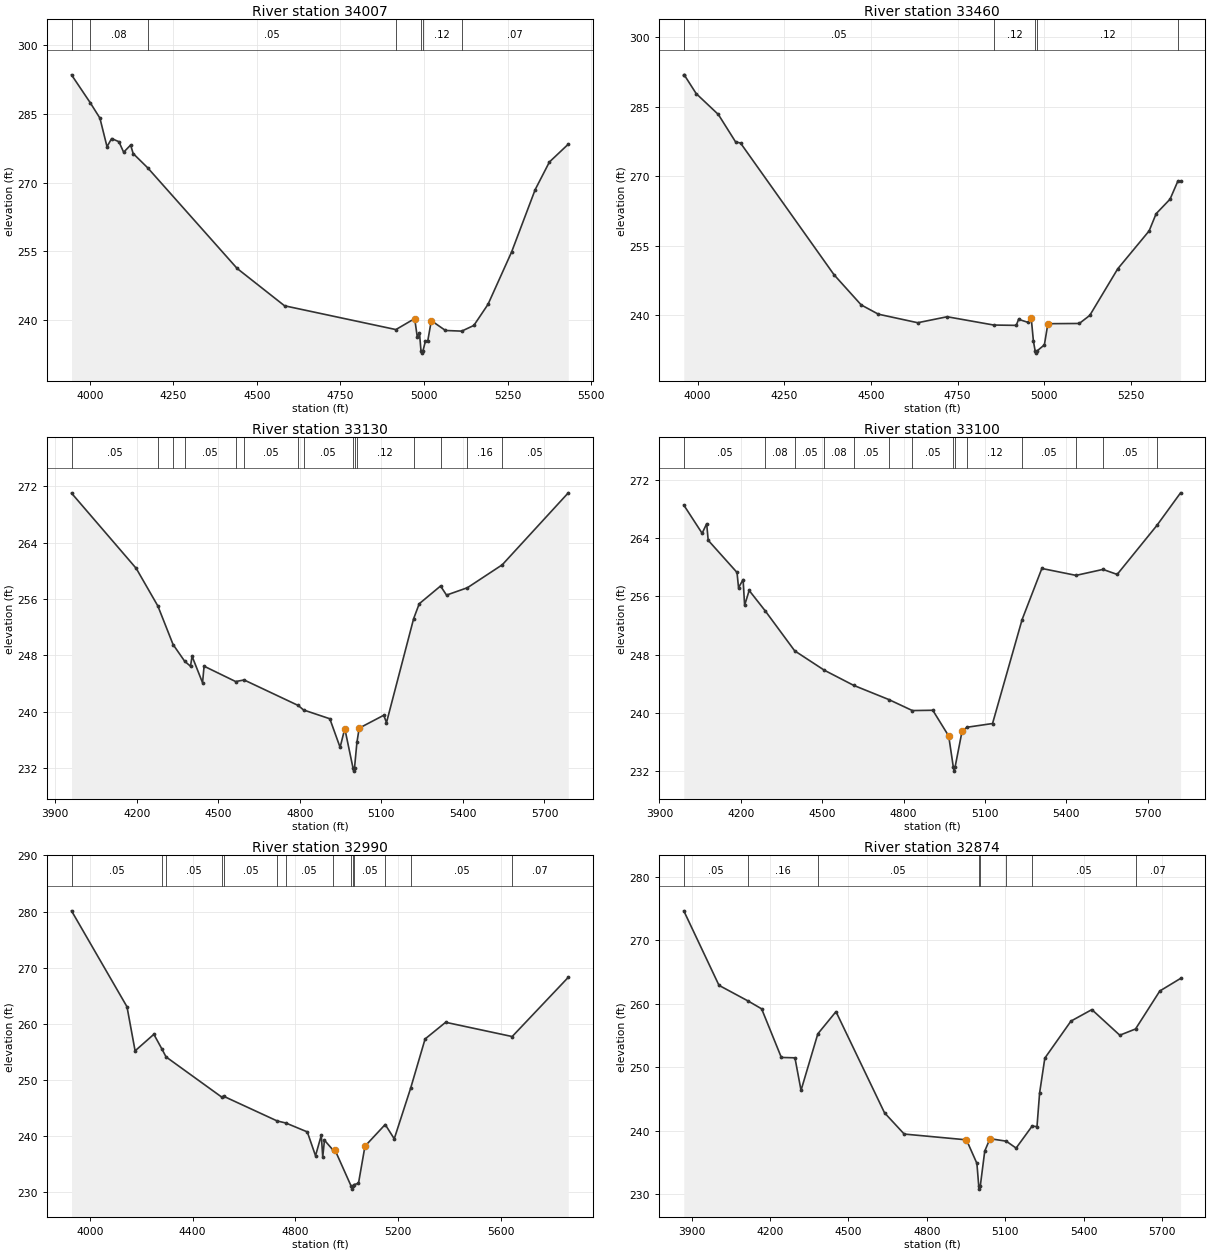
Type RM Length L Ch R = 1 ,34007   ,547,547,547
BEGIN DESCRIPTION:
KEECHIE CREEK 44.0
END DESCRIPTION:
XS GIS Cut Line= 3
      3710649.62      10629460.2      3709849.61     10628760.19
       3709549.6     10628460.18
#Sta/Elev= 30
  3944.7  293.56  4001.5  287.38  4029.7   284.1    4051  277.85  4064.8  279.63
  4086.6  278.94  4100.8  276.64  4121.7  278.21  4129.3  276.35  4172.7  273.24
  4440.6  251.23  4582.5  243.07  4915.9  237.87  4972.1  240.27  4979.7  236.33
  4986.4  237.18    4991  233.22  4993.7  232.72    4997  233.22  5004.4  235.41
  5011.3  235.41  5021.9  239.82  5064.3  237.67  5112.9  237.53  5149.2  238.77
  5191.6  243.38  5262.3  254.84    5333  268.49  5375.4   274.5    5432   278.4
#Mann= 7 ,-1 , 0
  3944.7     .16       0  4001.5     .08       0  4172.7     .05       0
  4915.9     .12       0    4991     .07       0    4997     .12       0
  5112.9     .07       0
Bank Sta=4972.1,5021.9
XS Rating Curve= 0 ,0
Exp/Cntr=0.3,0.1

Type RM Length L Ch R = 1 ,33460   ,330,330,330
BEGIN DESCRIPTION:
KEECHIE CREEK 43.0
END DESCRIPTION:
XS GIS Cut Line= 3
      3710899.59     10628960.17      3710099.61     10628310.19
      3709699.58     10628360.19
#Sta/Elev= 30
  3959.9  291.87  3961.1  291.87  3995.8  287.81  4059.7  283.31  4109.3  277.41
  4123.7  277.15  4393.7  248.72    4472  242.22  4521.6  240.22  4635.1  238.38
  4720.1  239.67  4854.6  237.88  4919.5  237.81  4926.2  239.11  4954.7  238.43
  4962.7   239.4  4969.1  234.38    4974  232.32  4976.8  231.82    4980  232.32
  5000.7   233.6  5010.8  238.17  5101.5  238.22  5131.7  239.96  5212.4  250.01
  5303.1   258.2  5323.2   261.9  5363.5  265.05  5385.8  268.91  5393.8  268.92
#Mann= 6 ,-1 , 0
  3959.9     .08       0  3961.1     .05       0  4854.6     .12       0
    4974     .07       0    4980     .12       0  5385.8     .07       0
Bank Sta=4962.7,5010.8
XS Rating Curve= 0 ,0
Exp/Cntr=0.3,0.1

Type RM Length L Ch R = 1 ,33130   ,30,30,30
BEGIN DESCRIPTION:
KEECHIE CREEK 42.0
END DESCRIPTION:
XS GIS Cut Line= 3
      3711151.06     10628507.98      3710307.28     10628070.47
      3709433.45     10627989.85
#Sta/Elev= 30
  3959.7  271.05  4197.9  260.35  4277.6     255  4333.4  249.54  4376.5  247.14
  4397.6  246.46  4403.3  247.87  4441.9  244.11  4447.5  246.46  4563.6  244.28
    4595   244.5  4793.8  240.88  4813.5  240.24  4910.2  238.99    4948  234.93
  4965.3   237.6  4995.2  232.05    4998  231.55  5001.2  232.05  5009.9  235.63
  5018.3  237.66  5108.7  239.49  5118.7  238.44  5218.6  253.21  5239.2  255.33
  5317.6  257.85  5339.6  256.56  5416.6  257.61  5544.8  260.87  5787.7  271.09
#Mann= 15 ,-1 , 0
  3959.7     .05       0  4277.6     .16       0  4333.4     .08       0
  4376.5     .05       0  4563.6     .08       0    4595     .05       0
  4793.8     .08       0  4813.5     .05       0  4995.2     .03       0
  5001.2     .05       0  5009.9     .12       0  5218.6     .16       0
  5317.6      .1       0  5416.6     .16       0  5544.8     .05       0
Bank Sta=4965.3,5018.3
XS Rating Curve= 0 ,0
Exp/Cntr=0.3,0.1

Type RM Length L Ch R = 1 ,33100   ,110,110,110
BEGIN DESCRIPTION:
Mapping XS d13b8e6f
END DESCRIPTION:
XS GIS Cut Line= 3
      3711148.41     10628463.69       3710317.7     10628049.63
      3709423.21     10627922.22
#Sta/Elev= 30
  3989.8  268.55  4057.4  264.67  4074.2  265.99  4079.8  263.71  4186.1  259.29
  4191.7  257.19  4208.5  258.32  4214.1  254.78  4230.9  256.82  4290.4     254
  4398.8  248.52  4507.6  245.87  4615.7  243.79  4745.9  241.83  4832.6  240.32
  4907.9  240.36  4966.6  236.82  4983.8   232.5  4986.5     232  4989.8   232.5
  5016.2  237.55  5034.7  238.03  5128.2  238.54  5237.2  252.82    5310  259.84
    5436  258.89  5535.4  259.71  5587.7  259.02  5734.1  265.75  5821.5  270.23
#Mann= 14 ,-1 , 0
  3989.8     .05       0  4290.4     .08       0  4398.8     .05       0
  4507.6     .08       0  4615.7     .05       0  4745.9     .08       0
  4832.6     .05       0  4983.8     .03       0  4989.8     .05       0
  5034.7     .12       0  5237.2     .05       0    5436      .1       0
  5535.4     .05       0  5734.1     .12       0
Bank Sta=4966.6,5016.2
XS Rating Curve= 0 ,0
Exp/Cntr=0.3,0.1

Type RM Length L Ch R = 1 ,32990   ,116,116,116
BEGIN DESCRIPTION:
Mapping XS 8d887b96
END DESCRIPTION:
XS GIS Cut Line= 4
       3711213.5     10628395.97      3710312.49     10627953.28
      3710161.45     10627898.59      3709392.62     10627864.83
#Sta/Elev= 30
  3928.8  280.13  4144.8  263.03  4176.4  255.17  4249.4  258.12  4280.4  255.53
  4296.9  254.09  4513.2  246.94  4521.8  247.06  4729.6  242.67  4763.1  242.31
  4846.8  240.72  4878.8  236.47  4901.3  240.13  4906.9  236.25  4913.6  239.24
  4945.4  237.57  4954.1  237.55  5017.8  231.02  5020.6  230.52  5023.8  231.02
  5028.7  231.33    5046  231.54  5071.3  238.17  5150.1  242.04  5185.3  239.49
  5248.9  248.48  5305.4  257.29  5385.4  260.26  5644.4  257.72  5862.9  268.28
#Mann= 14 ,-1 , 0
  3928.8     .05       0  4280.4     .16       0  4296.9     .05       0
  4513.2     .08       0  4521.8     .05       0  4729.6     .08       0
  4763.1     .05       0  4945.4     .08       0  5017.8     .07       0
  5023.8     .08       0  5028.7     .05       0  5150.1     .08       0
  5248.9     .05       0  5644.4     .07       0
Bank Sta=4954.1,5071.3
XS Rating Curve= 0 ,0
Exp/Cntr=0.3,0.1

Type RM Length L Ch R = 1 ,32874   ,509,509,509
BEGIN DESCRIPTION:
Mapping XS c01a2590
END DESCRIPTION:
XS GIS Cut Line= 3
      3711252.62     10628247.56      3710296.87     10627825.68
       3709440.1      10627838.7
#Sta/Elev= 30
  3869.9  274.63  4004.7   262.9  4116.8  260.42  4167.9   259.2  4243.3  251.55
  4295.4  251.49  4318.7  246.37    4383  255.27  4452.5  258.76  4638.2  242.84
  4713.6  239.49  4951.9  238.58  4991.9  234.87  4998.9  231.32  5001.6  230.82
  5004.9  231.32  5021.9  236.81  5041.9  238.76  5104.2  238.37  5141.9  237.28
  5203.2  240.74  5221.9  240.66  5231.9  245.96  5251.9  251.44  5351.9  257.27
  5431.9  259.08  5538.8  255.05  5599.1  256.03    5692  262.01  5771.5  263.99
#Mann= 8 ,-1 , 0
  3869.9     .05       0  4116.8     .16       0    4383     .05       0
  4998.9     .03       0  5004.9     .05       0  5104.2     .08       0
  5203.2     .05       0  5599.1     .07       0
Bank Sta=4951.9,5041.9
XS Rating Curve= 0 ,0
Exp/Cntr=0.3,0.1

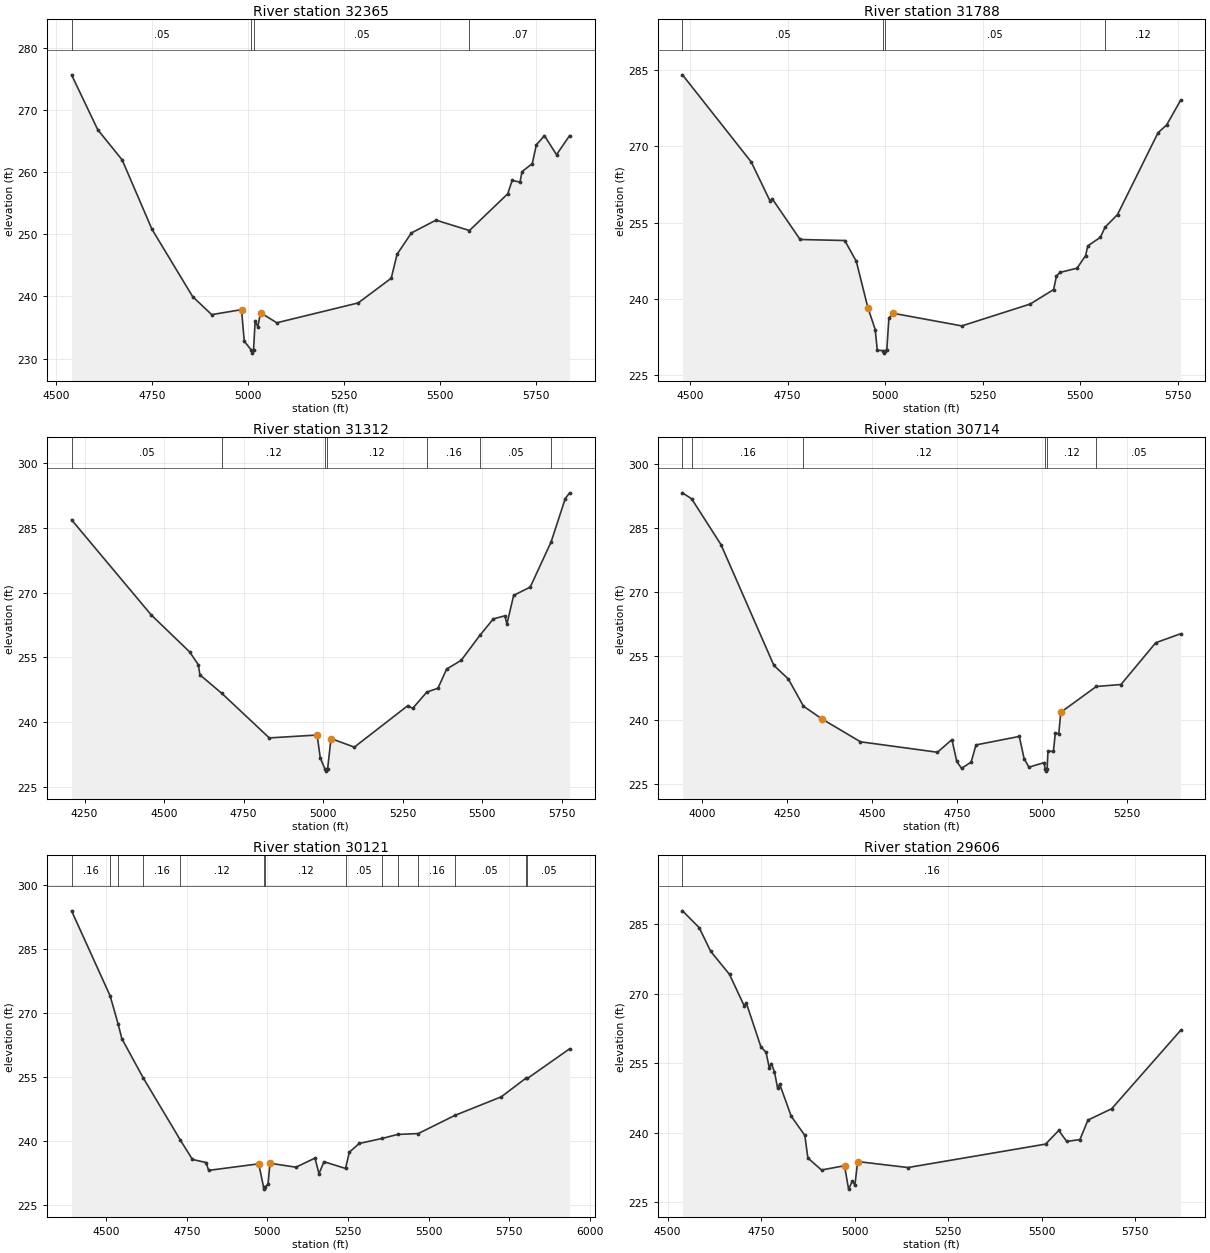
Type RM Length L Ch R = 1 ,32365   ,577,577,577
BEGIN DESCRIPTION:
KEECHIE CREEK 41.0
END DESCRIPTION:
XS GIS Cut Line= 3
       3710434.9     10627158.99       3709940.1     10627648.59
      3709367.18     10627833.49
#Sta/Elev= 30
  4539.5  275.61  4607.7  266.79  4671.4  261.93  4749.1  250.78  4855.2  239.95
  4904.7  237.06  4982.5  237.86  4989.6  232.79  5007.8  231.37  5010.6  230.87
  5013.8  231.37  5017.9  235.96    5025  235.14    5032  237.37  5074.4  235.75
  5286.5  238.94  5372.7  242.91  5387.9  246.76  5425.2  250.19  5489.3  252.25
  5576.5  250.58  5676.3  256.48  5687.9  258.63  5708.3  258.36  5713.6  260.05
  5740.3  261.34    5751  264.36    5772  265.83  5803.5  262.77  5837.6  265.84
#Mann= 4 ,-1 , 0
  4539.5     .05       0  5007.8     .03       0  5013.8     .05       0
  5576.5     .07       0
Bank Sta=4982.5,5032
XS Rating Curve= 0 ,0
Exp/Cntr=0.3,0.1

Type RM Length L Ch R = 1 ,31788   ,476,476,476
BEGIN DESCRIPTION:
KEECHIE CREEK 40.0
END DESCRIPTION:
XS GIS Cut Line= 3
      3710299.58      10626910.2      3709799.61     10627110.19
      3709149.63     10627460.18
#Sta/Elev= 30
  4480.5  283.97  4656.8  266.87  4705.3  259.17  4710.7  259.64    4782  251.67
  4896.5  251.47  4926.1  247.39  4955.7  238.31  4974.6  234.01  4979.9  229.93
  4994.4  229.88  4997.2  229.38  5000.4  229.88  5004.2   229.9  5009.6  236.23
    5019  237.22  5196.6  234.72  5371.9  239.01  5431.9  241.85  5439.2   244.5
  5448.1  245.21  5491.9  246.04  5513.8  248.49  5519.5  250.41    5552  252.12
  5563.7  254.08  5595.8  256.57  5699.6  272.62  5721.5  274.12  5757.2  278.95
#Mann= 4 ,-1 , 0
  4480.5     .05       0  4994.4     .03       0  5000.4     .05       0
  5563.7     .12       0
Bank Sta=4955.7,5019
XS Rating Curve= 0 ,0
Exp/Cntr=0.3,0.1

Type RM Length L Ch R = 1 ,31312   ,598,598,598
BEGIN DESCRIPTION:
KEECHIE CREEK 39.0
END DESCRIPTION:
XS GIS Cut Line= 3
      3710349.59     10626760.19      3709549.61     10626710.19
      3708899.57     10627110.21
#Sta/Elev= 30
  4209.3  286.85  4459.8  264.81    4580  256.29  4607.6   253.3  4612.6  250.95
  4681.9  246.64  4830.5  236.35  4980.8  237.02  4990.8   231.7  5005.3  229.16
  5008.1  228.66  5011.3  229.16  5013.8  229.16  5024.4   236.2  5097.8  234.22
  5265.9  243.83  5280.9  243.17  5325.4  246.96  5360.5  247.86  5387.7  252.29
  5433.5  254.32  5492.5  260.13  5534.4  263.91  5571.1  264.63    5577  262.68
  5598.3  269.35  5650.4  271.28  5715.9  281.72  5760.5  291.77  5774.1   293.1
#Mann= 7 ,-1 , 0
  4209.3     .05       0  4681.9     .12       0  5005.3     .07       0
  5011.3     .12       0  5325.4     .16       0  5492.5     .05       0
  5715.9     .12       0
Bank Sta=4980.8,5024.4
XS Rating Curve= 0 ,0
Exp/Cntr=0.3,0.1

Type RM Length L Ch R = 1 ,30714   ,593,593,593
BEGIN DESCRIPTION:
KEECHIE CREEK 38.0
END DESCRIPTION:
XS GIS Cut Line= 3
       3710099.6      10625510.2      3709349.61     10626260.19
      3709149.59     10626610.23
#Sta/Elev= 30
  3942.5  293.35  3969.5  291.94  4055.6  281.21  4211.2  252.86  4253.6  249.68
  4298.1   243.3  4352.6  240.29  4465.7  234.94    4692  232.49  4734.4  235.46
  4748.6  230.35  4762.7  228.71    4791  230.19  4805.2  234.21  4932.4   236.2
  4946.6     231  4960.7  228.99    5006  230.07  5008.1  228.56  5010.8  228.06
  5014.1  228.56  5016.8  232.72  5032.7  232.69  5038.4  237.03  5048.5  236.82
  5054.3  241.85  5158.8  247.92  5231.3  248.38  5333.6  258.19  5406.3  260.28
#Mann= 6 ,-1 , 0
  3942.5     .12       0  3969.5     .16       0  4298.1     .12       0
  5008.1     .07       0  5014.1     .12       0  5158.8     .05       0
Bank Sta=4352.6,5054.3
XS Rating Curve= 0 ,0
Exp/Cntr=0.3,0.1

Type RM Length L Ch R = 1 ,30121   ,515,515,515
BEGIN DESCRIPTION:
KEECHIE CREEK 37.0
END DESCRIPTION:
XS GIS Cut Line= 3
      3709799.62     10625360.17      3709399.61     10625810.19
      3708899.61     10626610.19
#Sta/Elev= 30
  4392.3  293.96  4511.9     274  4536.4   267.5  4548.3  263.95    4614  254.82
  4729.7  240.15  4767.4  235.58    4810  234.85  4817.5  233.01  4973.1  234.55
  4988.1  229.11  4990.8  228.61  4994.1  229.11  5002.1  229.86    5008  234.68
  5088.7  233.76  5147.7   235.9  5160.1  232.22  5175.4  235.05  5242.4  233.47
  5254.4   237.3  5285.1  239.33  5355.3   240.5  5403.8  241.45  5468.2  241.66
  5581.1   245.9  5726.1   250.3  5801.6  254.63  5806.9   254.6  5937.8  261.56
#Mann= 14 ,-1 , 0
  4392.3     .16       0  4511.9     .12       0  4536.4      .1       0
    4614     .16       0  4729.7     .12       0  4988.1     .07       0
  4994.1     .12       0  5242.4     .05       0  5355.3     .16       0
  5403.8     .05       0  5468.2     .16       0  5581.1     .05       0
  5801.6     .16       0  5806.9     .05       0
Bank Sta=4973.1,5008
XS Rating Curve= 0 ,0
Exp/Cntr=0.3,0.1

Type RM Length L Ch R = 1 ,29606   ,526,526,526
BEGIN DESCRIPTION:
KEECHIE CREEK 36.0
END DESCRIPTION:
XS GIS Cut Line= 3
      3709149.62     10625260.16      3708949.61     10625660.19
      3708349.63     10626310.17
#Sta/Elev= 30
  4539.7  287.92  4584.4  284.29  4615.2  279.17  4665.5   274.2  4704.6  267.44
  4710.2  268.09  4749.4  258.58  4763.3  257.38  4771.7  254.07  4777.3  254.98
  4785.7   253.2  4794.1  249.65  4799.7  250.51  4830.4  243.62  4866.8  239.48
  4875.1  234.59  4911.5  232.01    4973  232.93  4983.9  227.88    4994  229.62
  5000.8  228.79  5008.2  233.83  5142.6  232.54  5510.6  237.59  5545.8  240.54
  5567.3  238.17  5602.5  238.57    5624  242.78  5687.5  245.23  5871.5  262.11
#Mann= 1 ,-1 , 0
  4539.7     .16       0
Bank Sta=4973,5008.2
XS Rating Curve= 0 ,0
Exp/Cntr=0.3,0.1

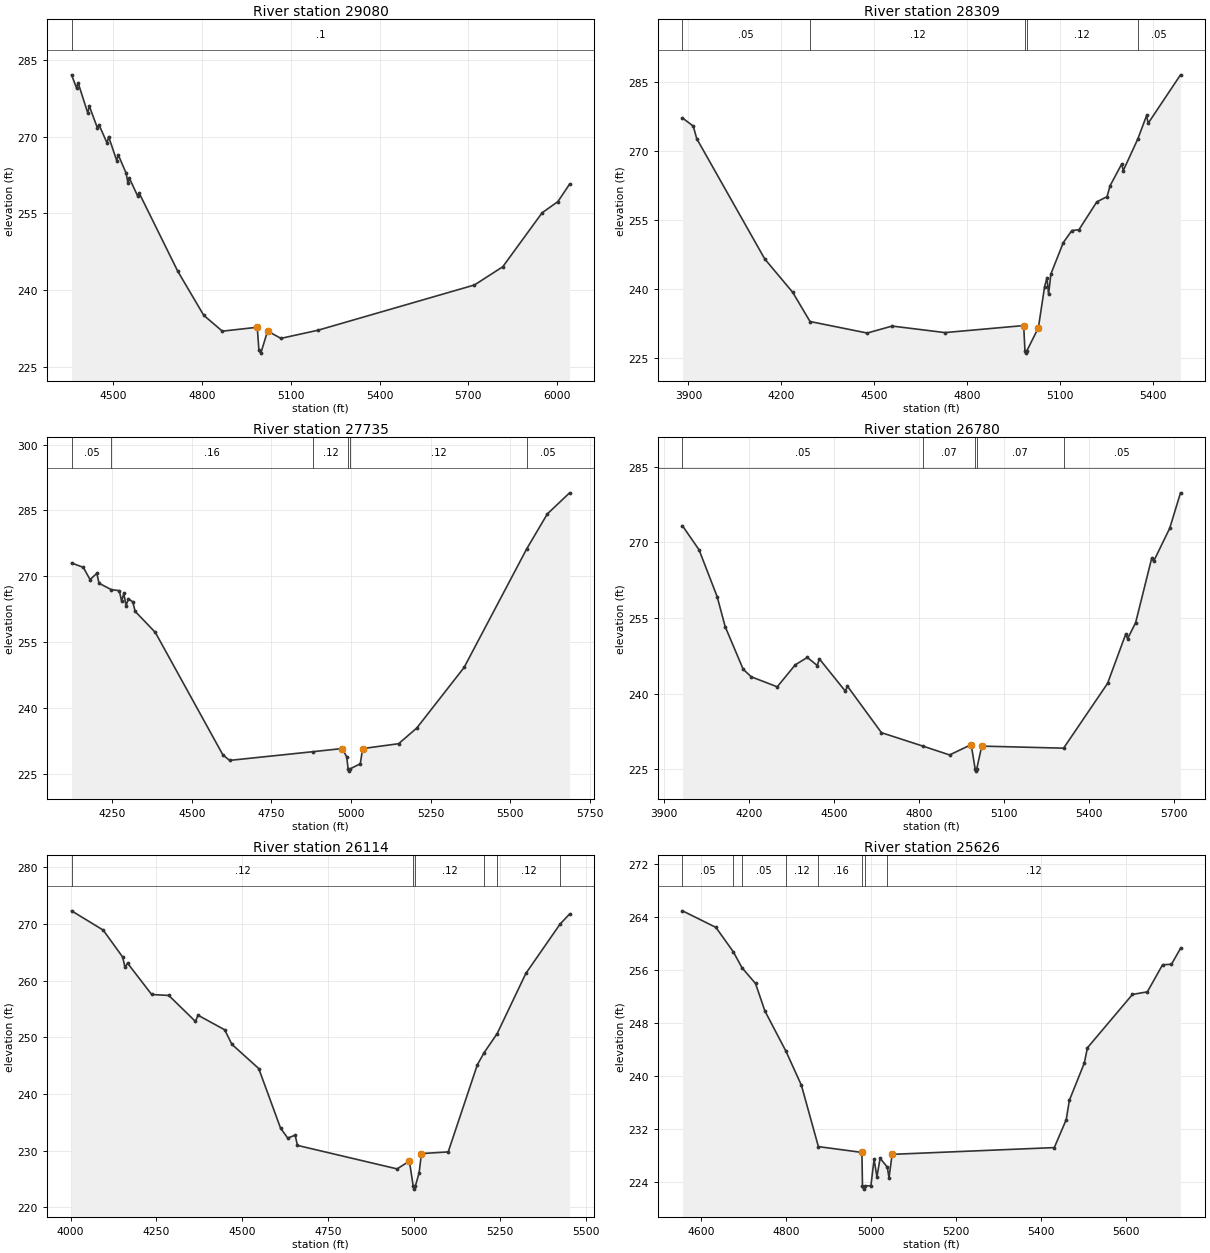
Type RM Length L Ch R = 1 ,29080   ,771,771,771
BEGIN DESCRIPTION:
KEECHIE CREEK 35.0
END DESCRIPTION:
XS GIS Cut Line= 3
      3709105.85     10625228.67      3708557.23     10625398.81
      3707574.58     10625909.23
#Sta/Elev= 30
    4360  282.14  4376.9  279.56  4382.1  280.57  4414.7  274.67  4419.9  276.02
  4447.3  271.74  4452.5  272.39  4479.9  268.76  4485.1  270.04  4512.5  265.34
  4517.7  266.46  4544.5  262.85  4550.3  260.92  4555.5  261.86  4582.9  258.44
  4588.1     259  4718.4  243.69  4806.3  235.04  4869.1  231.93    4987   232.7
  4992.7  228.17  4999.1  227.63  5021.9  231.96  5066.9  230.52  5191.7  232.11
  5720.5  240.98  5816.1  244.55  5948.8  255.11  6002.2  257.31  6041.7  260.73
#Mann= 1 ,-1 , 0
    4360      .1       0
Bank Sta=4987,5021.9
XS Rating Curve= 0 ,0
Exp/Cntr=0.3,0.1

Type RM Length L Ch R = 1 ,28309   ,574,574,574
BEGIN DESCRIPTION:
KEECHIE CREEK 34.0
END DESCRIPTION:
XS GIS Cut Line= 3
      3709234.28     10624978.67      3708269.04     10624898.81
      3707634.07     10624978.61
#Sta/Elev= 30
  3880.8  277.21  3915.6  275.44  3926.8  272.71  4146.4  246.54  4236.7  239.28
  4292.7  232.92  4477.5  230.41  4557.8  231.93  4728.4  230.51  4982.8  232.04
  4986.9  226.54  4989.6  226.04  4992.9  226.54  5030.2  231.55  5050.3  240.49
  5058.1  242.46  5063.2   238.8  5070.5  243.24  5110.8  250.11  5138.5  252.72
  5161.2  252.89  5218.9  258.95  5251.9  260.09    5262  262.49  5299.4  267.21
  5304.4  265.76  5351.5  272.66  5379.8  277.75  5384.8  276.05  5489.3   286.6
#Mann= 5 ,-1 , 0
  3880.8     .05       0  4292.7     .12       0  4986.9     .07       0
  4992.9     .12       0  5351.5     .05       0
Bank Sta=4982.8,5030.2
XS Rating Curve= 0 ,0
Exp/Cntr=0.3,0.1

Type RM Length L Ch R = 1 ,27735   ,955,955,955
BEGIN DESCRIPTION:
KEECHIE CREEK 33.0
END DESCRIPTION:
XS GIS Cut Line= 3
      3708668.31     10623846.76      3708112.79     10624409.23
       3707537.2     10624925.86
#Sta/Elev= 30
  4122.6  273.02  4159.4  272.04  4180.7  269.24  4201.9  270.67    4209   268.4
  4247.4  266.96  4272.6  266.72  4279.7  264.34  4286.7  266.08  4293.8  263.24
  4300.9  264.91    4315  264.14  4322.1  262.02  4385.7   257.2  4597.9  229.28
  4619.1  228.04  4881.9  230.03  4972.4  230.74  4986.7  228.84  4991.1  226.09
  4993.9  225.59  4997.1  226.09  5029.3  227.28  5036.7  230.73  5149.6  231.84
  5206.4  235.39  5355.2  249.21  5552.4  276.31  5616.8  284.22  5686.6  289.02
#Mann= 6 ,-1 , 0
  4122.6     .05       0  4247.4     .16       0  4881.9     .12       0
  4991.1     .07       0  4997.1     .12       0  5552.4     .05       0
Bank Sta=4972.4,5036.7
XS Rating Curve= 0 ,0
Exp/Cntr=0.3,0.1

Type RM Length L Ch R = 1 ,26780   ,666,666,666
BEGIN DESCRIPTION:
KEECHIE CREEK 32.0
END DESCRIPTION:
XS GIS Cut Line= 4
      3708504.02     10623201.84       3707822.6     10623904.97
      3707796.55      10624026.5      3707319.12     10624473.55
#Sta/Elev= 30
  3964.5  273.27    4023   268.5  4086.8  259.23  4115.1  253.29  4178.6  244.85
  4206.9  243.35  4298.8  241.36  4362.5  245.72    4405  247.18  4440.2  245.58
  4447.4   246.9  4539.3  240.49  4546.5  241.49  4666.6  232.27  4812.2  229.62
  4907.1  227.86  4983.3   229.9  4997.1  225.15  4999.9  224.65  5003.1  225.15
  5020.6  229.61  5309.4   229.2  5464.5  242.03  5528.4  251.76  5535.3  250.89
  5563.6  254.07  5620.3  266.84  5627.1  266.23  5683.8  272.77    5722   279.8
#Mann= 5 ,-1 , 0
  3964.5     .05       0  4812.2     .07       0  4997.1     .07       0
  5003.1     .07       0  5309.4     .05       0
Bank Sta=4983.3,5020.6
XS Rating Curve= 0 ,0
Exp/Cntr=0.3,0.1

Type RM Length L Ch R = 1 ,26114   ,488,488,488
BEGIN DESCRIPTION:
KEECHIE CREEK 31.0
END DESCRIPTION:
XS GIS Cut Line= 3
      3708099.63     10623060.16      3707399.61     10623810.19
      3707099.62     10624110.18
#Sta/Elev= 30
  4002.9  272.33    4095  268.93  4151.7  264.17  4158.5  262.34  4165.9  263.09
  4236.2  257.56    4286  257.39  4363.7   252.8    4371  253.91  4448.7  251.33
  4469.7  248.77  4547.9  244.49  4611.4  233.98  4632.4  232.21  4653.9  232.73
  4660.7  230.92  4950.9  226.77  4986.6  228.15  4997.8   223.7  5000.5   223.2
  5003.8   223.7  5014.9  226.07  5021.8  229.48  5099.6  229.77  5184.4  245.14
  5204.3   247.3  5242.2  250.66  5325.8  261.29  5425.4  269.99  5453.1  271.77
#Mann= 6 ,-1 , 0
  4002.9     .12       0  4997.8     .07       0  5003.8     .12       0
  5204.3     .07       0  5242.2     .12       0  5425.4     .16       0
Bank Sta=4986.6,5021.8
XS Rating Curve= 0 ,0
Exp/Cntr=0.3,0.1

Type RM Length L Ch R = 1 ,25626   ,402,402,402
BEGIN DESCRIPTION:
KEECHIE CREEK 30.0
END DESCRIPTION:
XS GIS Cut Line= 3
      3707699.64     10623010.15      3707449.61     10623360.19
      3706949.59     10623910.21
#Sta/Elev= 30
  4555.9  264.99  4634.6  262.49  4675.5  258.82  4696.1   256.4    4728  254.02
  4750.1  249.87  4799.6  243.81  4836.1  238.66  4876.1   229.4  4978.7  228.52
    4980  223.48  4982.7  222.98    4986  223.48  4999.9  223.49  5007.3  227.48
  5014.1  224.84  5021.5  227.64  5038.5  226.31  5042.5  224.69  5049.9  228.23
    5432  229.25  5460.1  233.47  5467.5  236.39  5502.7  242.01  5510.1  244.32
  5616.2  252.37  5651.3  252.76  5687.1  256.85  5708.1  256.92  5729.4  259.33
#Mann= 8 ,-1 , 0
  4555.9     .05       0  4675.5     .12       0  4696.1     .05       0
  4799.6     .12       0  4876.1     .16       0    4980     .07       0
    4986     .16       0  5038.5     .12       0
Bank Sta=4978.7,5049.9
XS Rating Curve= 0 ,0
Exp/Cntr=0.3,0.1

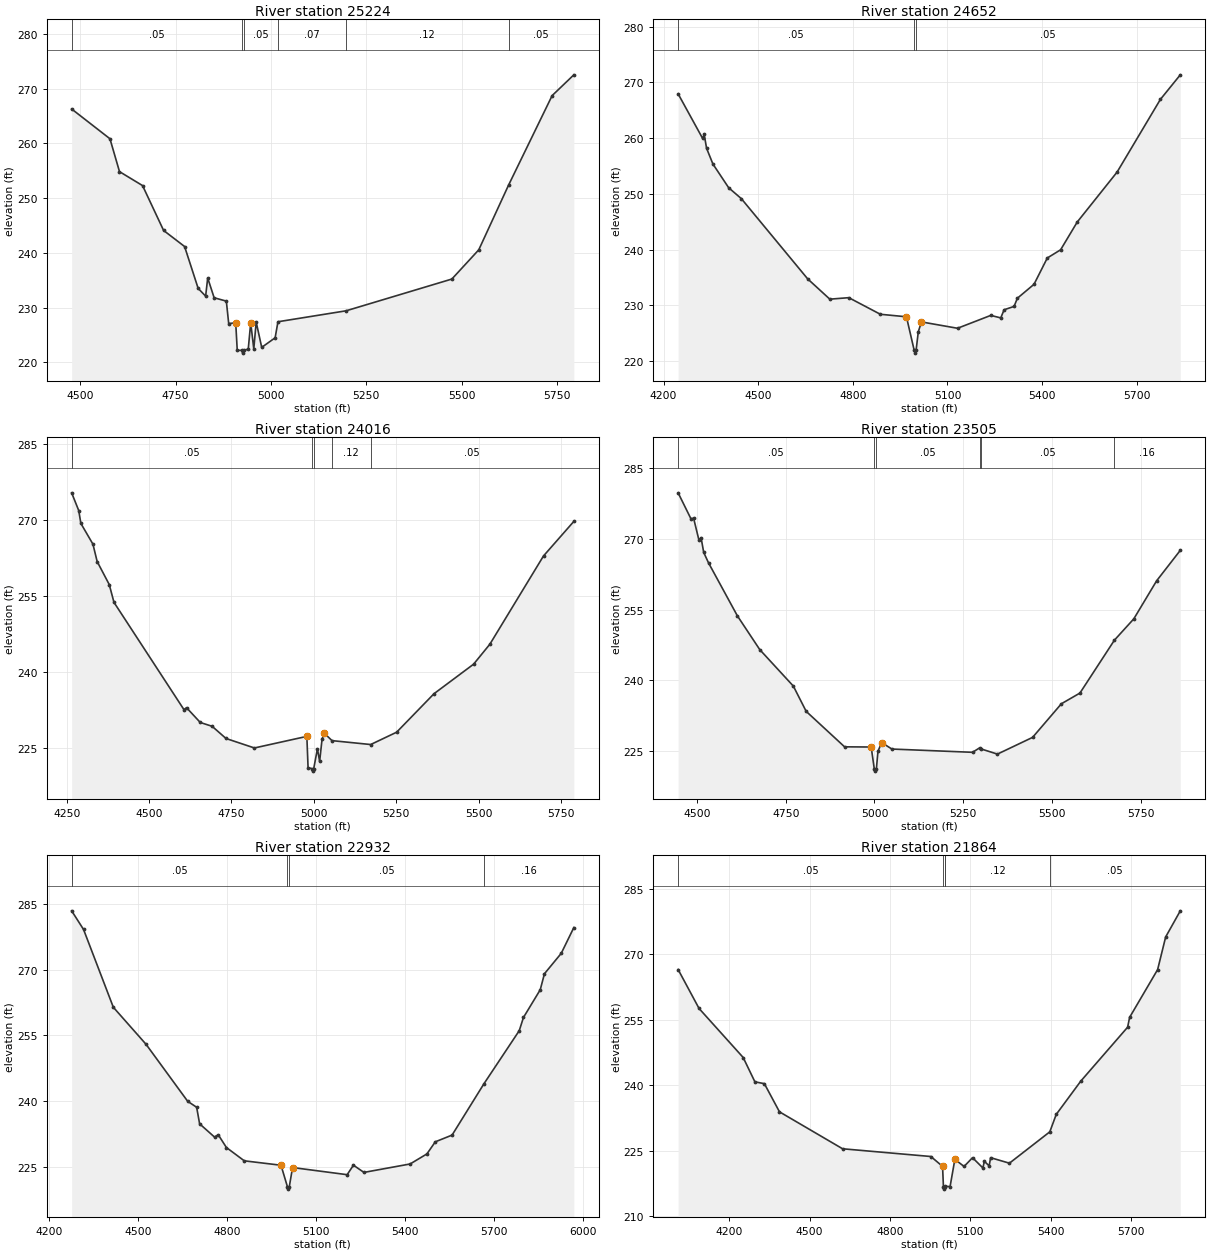
Type RM Length L Ch R = 1 ,25224   ,572,572,572
BEGIN DESCRIPTION:
KEECHIE CREEK 29.0
END DESCRIPTION:
XS GIS Cut Line= 3
      3707699.58      10622960.2      3707299.61     10623110.19
      3706599.61     10623660.19
#Sta/Elev= 30
  4477.2   266.3  4577.7  260.86  4602.7  254.86  4663.2  252.31  4718.4  244.12
  4773.5  241.18  4809.1  233.53  4828.7  232.12  4834.1  235.44    4851  231.82
    4883  231.21  4889.2  227.11  4907.6  227.25  4911.6  222.22  4923.1  222.21
  4925.8  221.71  4929.1  222.21  4940.5  222.46  4946.9  227.25    4955  222.49
  4961.3  227.38  4975.8  222.76    5011  224.51  5018.4  227.44  5197.1  229.44
  5474.6  235.24  5545.2  240.58  5623.2  252.37  5737.7  268.75  5794.6  272.54
#Mann= 6 ,-1 , 0
  4477.2     .05       0  4923.1     .03       0  4929.1     .05       0
  5018.4     .07       0  5197.1     .12       0  5623.2     .05       0
Bank Sta=4907.6,4946.9
XS Rating Curve= 0 ,0
Exp/Cntr=0.3,0.1

Type RM Length L Ch R = 1 ,24652   ,636,636,636
BEGIN DESCRIPTION:
KEECHIE CREEK 28.0
END DESCRIPTION:
XS GIS Cut Line= 3
      3707749.64     10622810.19      3706949.61     10622860.19
      3706199.58      10623110.2
#Sta/Elev= 30
  4246.1  267.95  4323.8  259.95  4328.8  260.66  4336.3  258.19  4356.4  255.36
  4406.4   251.1  4446.5  249.15  4656.9  234.75  4727.1  231.11  4787.2  231.38
  4887.4   228.4    4970  227.95  4994.6  221.93  4997.3  221.43  5000.6  221.93
  5007.6  225.26  5017.6  227.03    5132  225.89  5237.4   228.2  5269.1  227.75
  5279.6  229.21  5311.2  229.81  5321.8  231.28  5374.5  233.78  5416.6   238.5
  5458.8  239.97  5511.5  244.95    5638  253.92    5775  266.94  5838.3  271.36
#Mann= 3 ,-1 , 0
  4246.1     .05       0  4994.6     .03       0  5000.6     .05       0
Bank Sta=4970,5017.6
XS Rating Curve= 0 ,0
Exp/Cntr=0.3,0.1

Type RM Length L Ch R = 1 ,24016   ,511,511,511
BEGIN DESCRIPTION:
KEECHIE CREEK 27.0
END DESCRIPTION:
XS GIS Cut Line= 3
      3707199.59     10621910.21      3706749.61     10622460.19
      3706199.64     10623060.15
#Sta/Elev= 30
  4264.8   275.3  4286.3   271.8  4292.8  269.26  4329.4  265.17  4342.3  261.73
  4378.9   257.2  4393.3  253.68  4605.7  232.51  4613.6  232.89  4655.3  229.97
  4691.2  229.22  4733.5  226.81  4819.6  224.94  4978.8  227.23  4982.5  221.07
  4993.7  220.87  4996.4  220.37  4999.7  220.87  5010.9  224.79  5017.6  222.28
    5025   226.7  5031.8  227.86  5055.1  226.39  5172.6  225.62  5251.3  228.05
  5364.8  235.65    5485  241.48  5534.4  245.42  5697.2  262.84  5789.3  269.66
#Mann= 5 ,-1 , 0
  4264.8     .05       0  4993.7     .03       0  4999.7     .05       0
  5055.1     .12       0  5172.6     .05       0
Bank Sta=4978.8,5031.8
XS Rating Curve= 0 ,0
Exp/Cntr=0.3,0.1

Type RM Length L Ch R = 1 ,23505   ,573,573,573
BEGIN DESCRIPTION:
KEECHIE CREEK 26.0
END DESCRIPTION:
XS GIS Cut Line= 3
      3707199.61     10621860.19      3706749.61     10622160.19
      3705949.65     10622510.17
#Sta/Elev= 30
  4447.1  279.68  4483.2  274.19  4490.7  274.32  4505.7  269.68  4511.7   270.2
  4519.2  267.07  4532.7  264.87  4613.9  253.67    4677  246.52  4771.6   238.8
  4807.7  233.46  4915.8  225.96  4990.7  225.92  4999.4  221.32  5002.1  220.82
  5005.4  221.32  5009.8  225.02  5020.3  226.85  5049.1  225.49    5276   224.8
  5295.9  225.73  5300.3  225.51  5346.2  224.42  5445.2  227.96  5526.3  235.07
  5578.5  237.33  5675.6  248.52  5730.2  253.03  5794.5  261.08  5861.1  267.52
#Mann= 6 ,-1 , 0
  4447.1     .05       0  4999.4     .03       0  5005.4     .05       0
  5295.9     .12       0  5300.3     .05       0  5675.6     .16       0
Bank Sta=4990.7,5020.3
XS Rating Curve= 0 ,0
Exp/Cntr=0.3,0.1

Type RM Length L Ch R = 1 ,22932   ,1068,1068,1068
BEGIN DESCRIPTION:
KEECHIE CREEK 25.0
END DESCRIPTION:
XS GIS Cut Line= 3
      3707199.64     10621760.19      3706499.61     10621710.19
      3705799.58     10622410.21
#Sta/Elev= 30
  4277.1   283.4  4317.2  279.15  4417.5  261.43  4527.8  252.99  4668.1     240
  4698.2  238.65  4708.2  234.88  4758.4  231.86  4770.9  232.39  4798.5  229.48
  4858.6  226.45  4982.4  225.44  5004.2   220.5  5006.9     220  5010.2   220.5
  5021.3  224.92  5205.2  223.29  5226.4  225.45  5261.8  223.81  5417.3  225.73
  5473.9  228.02  5502.2  230.78  5558.7  232.31  5666.2  244.02    5785   256.1
  5799.2  259.11  5855.7  265.42  5869.9  269.07  5926.4  273.71  5968.9  279.59
#Mann= 4 ,-1 , 0
  4277.1     .05       0  5004.2     .03       0  5010.2     .05       0
  5666.2     .16       0
Bank Sta=4982.4,5021.3
XS Rating Curve= 0 ,0
Exp/Cntr=0.3,0.1

Type RM Length L Ch R = 1 ,21864   ,541,541,541
BEGIN DESCRIPTION:
KEECHIE CREEK 24.0
END DESCRIPTION:
XS GIS Cut Line= 3
      3707099.59     10621710.17      3706299.61     10621110.19
      3705499.59     10621460.19
#Sta/Elev= 30
  4009.8  266.53  4087.9  257.61  4252.5  246.38  4296.2  240.81  4331.6  240.39
  4387.9  233.94  4623.3  225.48  4952.5  223.71  4996.2  221.45  4999.5  216.74
  5002.2  216.24  5005.5  216.74  5005.9   216.9  5024.2  216.81  5042.1  223.06
  5076.4  221.43    5108  223.44  5146.6  221.09  5152.1  222.62    5170  221.56
  5175.4  223.44  5245.6  222.18  5396.2  229.36  5420.3  233.36  5511.9  240.98
  5686.5  253.32  5693.9  255.57  5798.4  266.51  5828.4  273.99    5883  279.97
#Mann= 5 ,-1 , 0
  4009.8     .05       0  4999.5     .03       0  5005.5     .05       0
  5005.9     .12       0  5396.2     .05       0
Bank Sta=4996.2,5042.1
XS Rating Curve= 0 ,0
Exp/Cntr=0.3,0.1