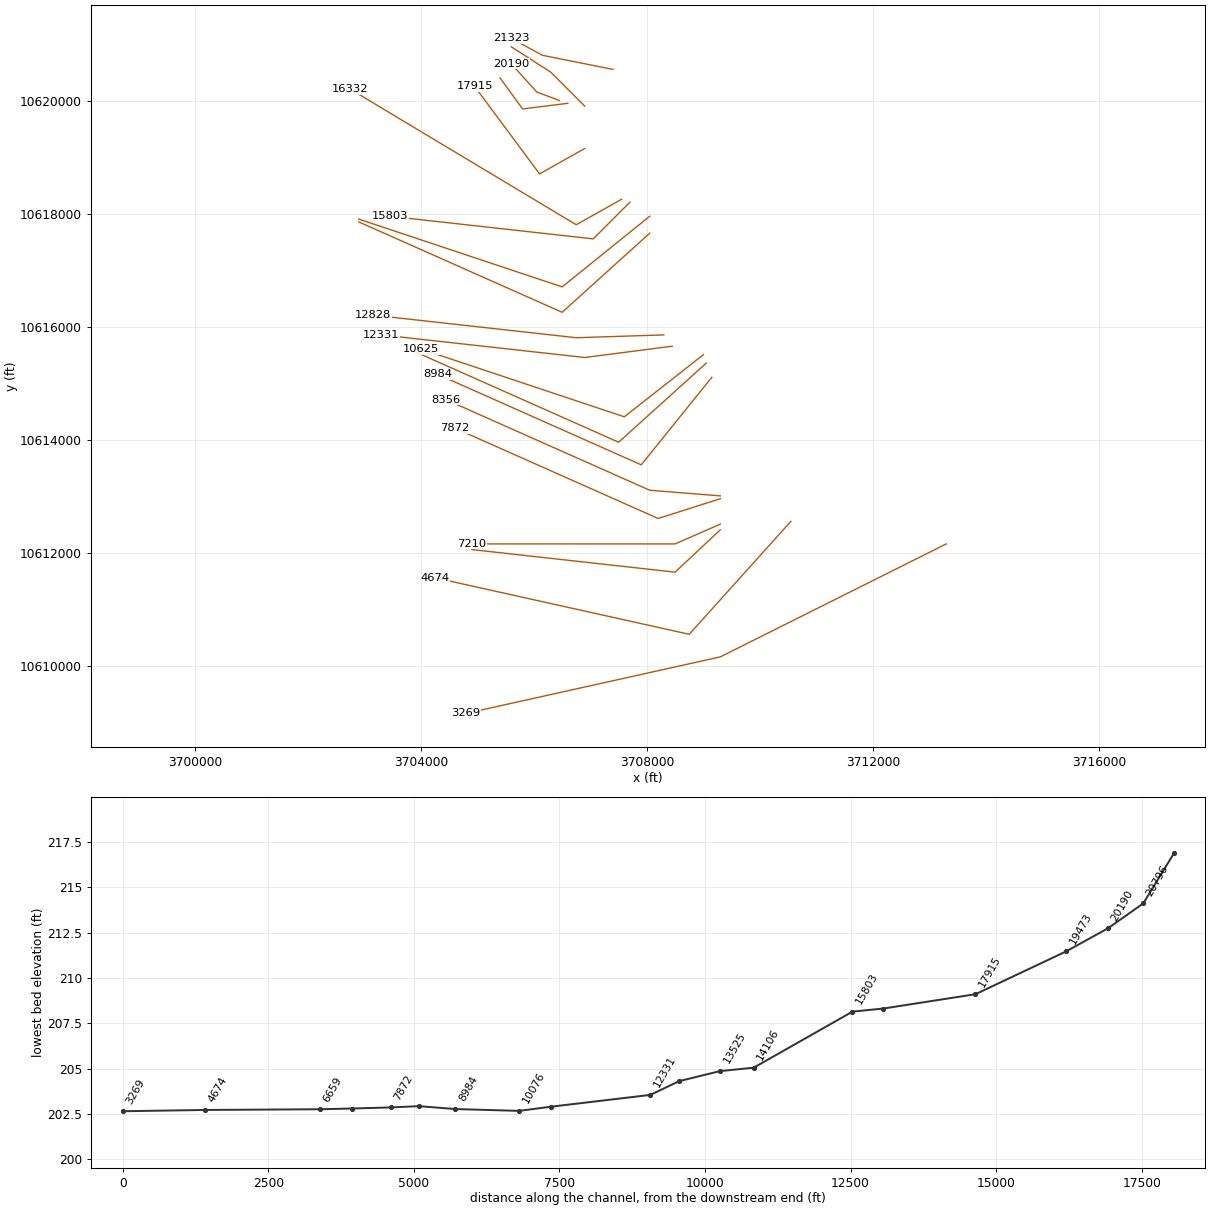
HEC-RAS study KEECHIE CREEK.prj: KEECHIE CREEK Base Level Engineering

--- KEECHIE CREEK.g01 (geometry) --- (continued)

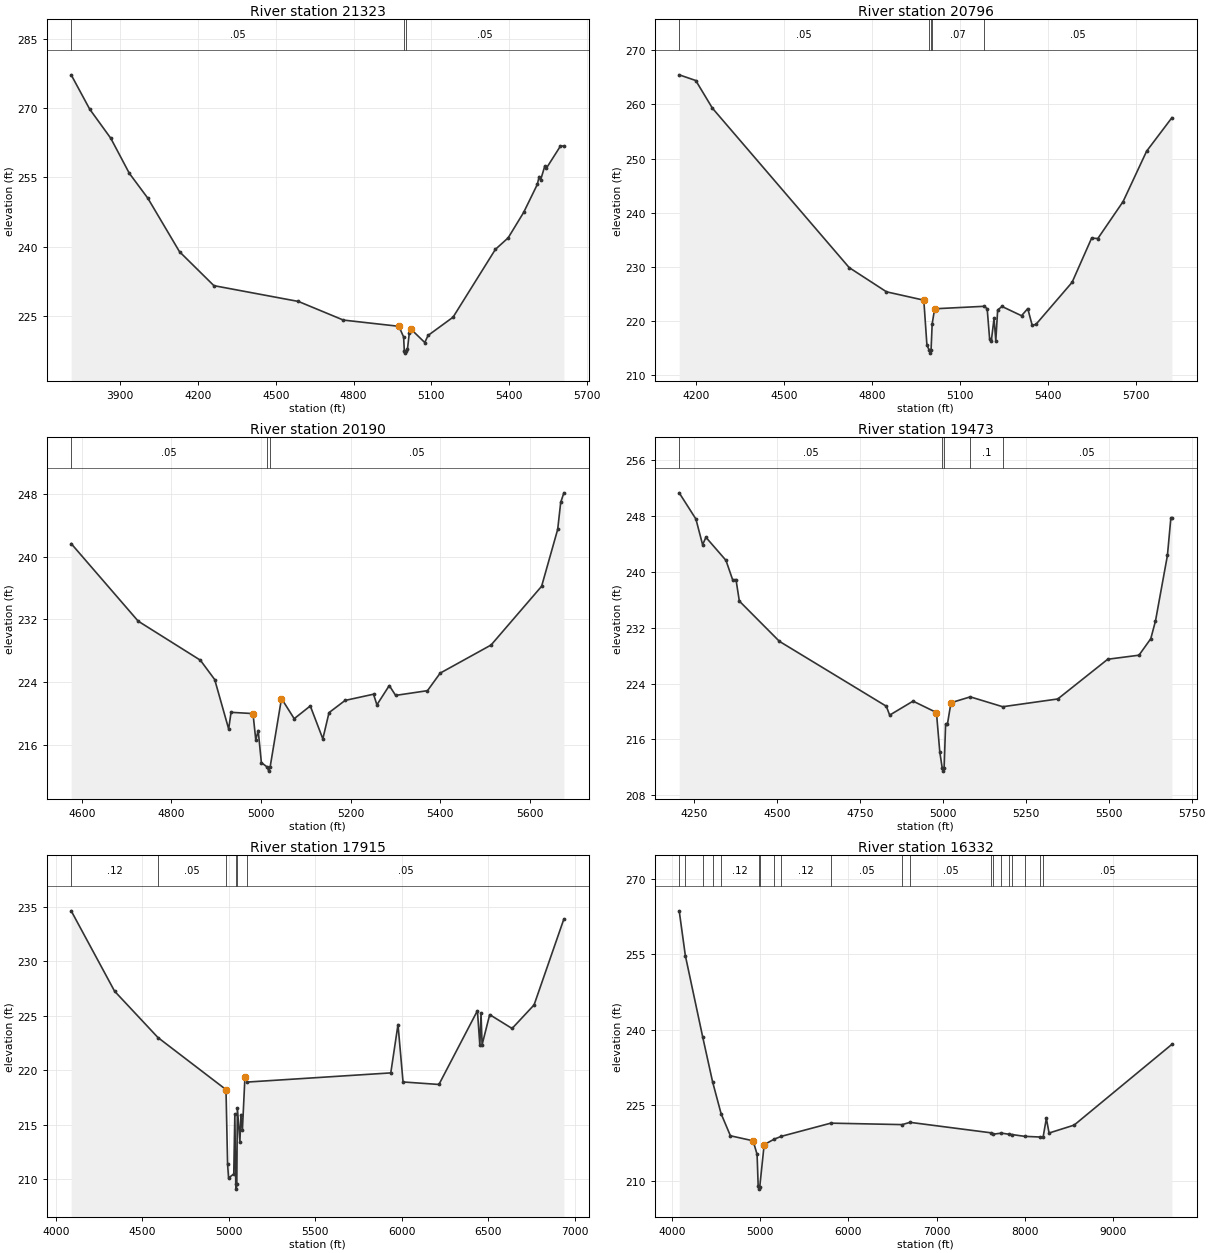
Type RM Length L Ch R = 1 ,21323   ,527,527,527
BEGIN DESCRIPTION:
KEECHIE CREEK 23.0
END DESCRIPTION:
XS GIS Cut Line= 3
      3707399.58     10620560.19      3706149.61     10620810.19
      3705599.63     10621110.18
#Sta/Elev= 30
  3710.5  277.25  3781.9  269.81  3863.4  263.48  3934.8  255.89  4006.2  250.49
  4128.6  238.87  4261.2  231.51  4587.5  228.08  4760.9  224.04    4975  222.69
  4993.3  220.37    4996  217.37  4998.7  216.87    5002  217.37    5008  217.67
  5015.1  221.15  5020.8  222.12  5074.9  219.17  5087.7  220.71  5184.1  224.67
  5347.4  239.38  5396.7  241.88  5456.5   247.4  5509.2  253.47  5516.3  255.18
    5522  254.44  5538.2  257.48  5543.9  256.96    5598  261.75  5611.7  261.84
#Mann= 3 ,-1 , 0
  3710.5     .05       0    4996     .03       0    5002     .05       0
Bank Sta=4975,5020.8
XS Rating Curve= 0 ,0
Exp/Cntr=0.3,0.1

Type RM Length L Ch R = 1 ,20796   ,606,606,606
BEGIN DESCRIPTION:
KEECHIE CREEK 22.0
END DESCRIPTION:
XS GIS Cut Line= 3
      3706899.59     10619910.21      3706299.61     10620510.19
      3705599.58     10620960.21
#Sta/Elev= 30
  4143.3  265.45  4199.8   264.4  4256.4  259.31  4723.1  229.89  4850.4  225.42
  4977.7  223.88  4988.3  215.61  4996.4  214.61  4999.1  214.11  5002.4  214.61
  5006.2  219.48  5014.6  222.29  5184.2  222.75  5193.9  222.29  5202.2  216.73
  5208.1  216.41  5217.3  220.53  5223.3  216.41  5229.6  222.07  5244.4  222.72
  5311.1  221.01  5332.3  222.33  5347.5  219.22  5360.3  219.42  5483.5  227.17
  5550.2  235.33  5571.3  235.25  5657.5  242.07  5737.8  251.37    5824  257.54
#Mann= 5 ,-1 , 0
  4143.3     .05       0  4996.4     .03       0  5002.4     .05       0
  5006.2     .07       0  5184.2     .05       0
Bank Sta=4977.7,5014.6
XS Rating Curve= 0 ,0
Exp/Cntr=0.3,0.1

Type RM Length L Ch R = 1 ,20190   ,717,717,717
BEGIN DESCRIPTION:
KEECHIE CREEK 21.0
END DESCRIPTION:
XS GIS Cut Line= 3
      3706449.65     10620010.17      3706049.61     10620160.19
      3705599.63     10620660.17
#Sta/Elev= 30
  4576.2  241.64  4725.8  231.79  4864.6  226.83  4896.6  224.37  4927.8  218.09
  4933.1  220.21  4982.1  220.05  4988.3  216.71  4993.7   217.9  5000.8  213.82
  5014.3  213.24    5017  212.74  5020.3  213.24  5045.7  221.96  5074.1   219.4
    5110  221.02    5138  216.84  5151.8  220.17  5187.7  221.72  5251.2  222.51
  5258.7  221.16  5286.3  223.61  5300.5  222.36  5371.6  222.96    5400  225.19
  5513.6  228.76  5626.4  236.22  5662.3  243.45    5669  246.87  5676.1  248.09
#Mann= 3 ,-1 , 0
  4576.2     .05       0  5014.3     .03       0  5020.3     .05       0
Bank Sta=4982.1,5045.7
XS Rating Curve= 0 ,0
Exp/Cntr=0.3,0.1

Type RM Length L Ch R = 1 ,19473   ,1558,1558,1558
BEGIN DESCRIPTION:
KEECHIE CREEK 20.0
END DESCRIPTION:
XS GIS Cut Line= 3
      3706599.62     10619960.19      3705799.61     10619860.19
      3705399.61     10620410.18
#Sta/Elev= 30
  4204.1  251.27  4254.5  247.52  4274.7  243.85  4284.7  244.91  4345.2  241.61
  4365.4  238.82  4375.4  238.87  4385.5  235.79  4506.4  230.03  4828.9  220.75
    4839  219.48  4909.6  221.48  4980.1  219.85  4990.2  214.23  4997.3  211.97
    5000  211.47  5003.3  211.97  5007.8  218.24  5013.4  218.24  5023.9  221.25
  5082.2  222.09    5180  220.68  5346.1  221.79  5496.8  227.47  5591.1  228.05
  5626.7  230.41  5640.9  232.95  5676.9  242.32  5687.3   247.7  5690.4   247.7
#Mann= 5 ,-1 , 0
  4204.1     .05       0  4997.3     .03       0  5003.3     .05       0
  5082.2      .1       0    5180     .05       0
Bank Sta=4980.1,5023.9
XS Rating Curve= 0 ,0
Exp/Cntr=0.3,0.1

Type RM Length L Ch R = 1 ,17915   ,1583,1583,1583
BEGIN DESCRIPTION:
KEECHIE CREEK 19.0
END DESCRIPTION:
XS GIS Cut Line= 3
      3706899.57     10619160.16      3706099.61     10618710.19
      3704949.58     10620260.23
#Sta/Elev= 30
  4089.1  234.61  4339.9  227.25  4590.6     223    4984  218.23  4984.3  218.01
  4993.2  211.37    4999  210.13  5028.9   210.5  5035.1  215.97  5040.5  209.61
  5043.2  209.11  5046.5  209.61  5049.7  216.56  5064.3  213.44  5070.5  215.94
  5078.9  214.55  5093.5  219.37  5106.8  218.92  5936.5  219.76  5978.2  224.19
  6007.4  218.93  6214.8   218.7  6437.3  225.46  6451.3  222.28  6458.1  225.21
  6464.3  222.34  6508.2   225.1  6637.6  223.83  6764.8  225.99    6937  233.86
#Mann= 6 ,-1 , 0
  4089.1     .12       0  4590.6     .05       0  4984.3     .07       0
  5040.5     .07       0  5046.5     .07       0  5106.8     .05       0
Bank Sta=4984,5093.5
XS Rating Curve= 0 ,0
Exp/Cntr=0.3,0.1

Type RM Length L Ch R = 1 ,16332   ,529,529,529
BEGIN DESCRIPTION:
KEECHIE CREEK 18.0
END DESCRIPTION:
XS GIS Cut Line= 3
      3707549.59     10618260.18      3706749.61     10617810.19
      3702749.62     10620210.18
#Sta/Elev= 30
  4083.3  263.62  4152.8  254.73  4350.7  238.46  4461.8  229.63  4557.8  223.32
  4663.6  218.92  4920.8  217.92  4965.8  215.22  4978.2  208.91  4990.2  208.82
  4992.9  208.32  4996.2  208.82  5045.9  217.16    5160  218.25  5240.5  218.81
  5801.3  221.43  6609.5  221.14  6698.7  221.59  7616.4  219.51  7638.2  219.23
  7734.5  219.45  7817.2  219.23  7852.6  219.17  7996.3  218.81  8175.4  218.67
  8206.9  218.68  8243.2  222.37  8274.3  219.47    8558  221.04  9665.9  237.09
#Mann= 20 ,-1 , 0
  4083.3     .12       0  4152.8     .16       0  4350.7      .1       0
  4461.8     .16       0  4557.8     .12       0  4990.2     .07       0
  4996.2     .12       0    5160     .07       0  5240.5     .12       0
  5801.3     .05       0  6609.5     .07       0  6698.7     .05       0
  7616.4     .07       0  7638.2     .05       0  7734.5     .12       0
  7817.2     .05       0  7852.6      .1       0  7996.3     .05       0
  8175.4      .1       0  8206.9     .05       0
Bank Sta=4920.8,5045.9
XS Rating Curve= 0 ,0
Exp/Cntr=0.3,0.1

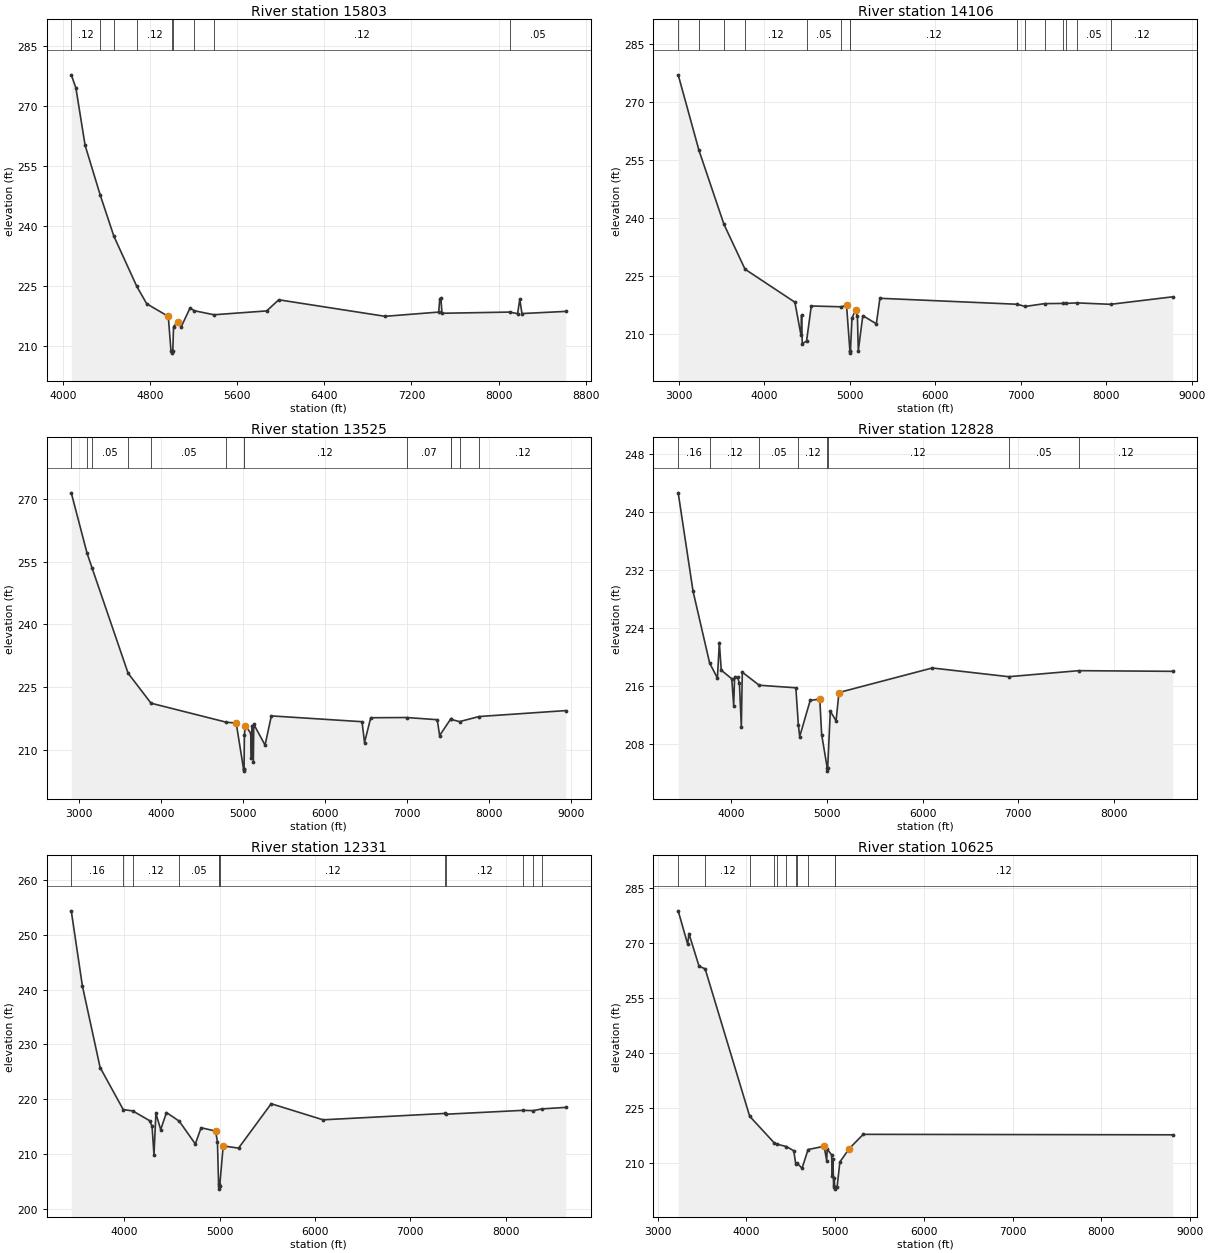
Type RM Length L Ch R = 1 ,15803   ,1697,1697,1697
BEGIN DESCRIPTION:
KEECHIE CREEK 17.0
END DESCRIPTION:
XS GIS Cut Line= 3
      3707699.58     10618210.16      3707049.61     10617560.19
      3703449.56     10617960.19
#Sta/Elev= 30
  4076.3   277.7  4118.7  274.45  4203.5  260.07  4343.1  247.58  4467.5  237.38
  4677.3  224.87  4769.2  220.48  4967.2  217.33    4992  208.68  5002.6  208.65
  5005.3  208.15  5008.6  208.65  5015.6  214.79  5055.9  216.02  5086.1  214.74
  5166.5   219.4  5207.9  218.74  5386.1  217.74  5870.9   218.7  5981.5  221.48
  6957.5  217.35  7450.5  218.41  7460.6  221.78  7470.6  221.83  7480.7  218.11
  8102.2  218.41  8174.9  218.01  8195.1   221.6  8215.2  218.04  8617.7  218.58
#Mann= 9 ,-1 , 0
  4076.3     .12       0  4343.1     .16       0  4467.5      .1       0
  4677.3     .12       0  5002.6     .07       0  5008.6     .12       0
  5207.9     .07       0  5386.1     .12       0  8102.2     .05       0
Bank Sta=4967.2,5055.9
XS Rating Curve= 0 ,0
Exp/Cntr=0.3,0.1

Type RM Length L Ch R = 1 ,14106   ,581,581,581
BEGIN DESCRIPTION:
KEECHIE CREEK 16.0
END DESCRIPTION:
XS GIS Cut Line= 3
       3708049.6     10617960.18      3706499.61     10616710.19
      3702899.65     10617910.17
#Sta/Elev= 30
    2992  277.01  3234.8   257.5  3527.4  238.36  3773.9  226.76  4357.1  218.23
    4429  209.66  4435.4  214.89  4443.4  207.53  4493.6  208.14    4549  217.25
  4899.5  217.04  4961.6  217.46  5001.3  205.56    5004  205.06  5007.3  205.56
  5025.4  214.16  5067.5  216.22  5088.6  214.61  5099.2  205.69  5151.9  214.76
    5310  212.64  5352.1  219.24  6961.5  217.69  7050.3  217.12  7278.8  217.86
  7490.9  217.91  7529.9  217.92  7657.3  218.05  8050.6  217.68  8777.9  219.62
#Mann= 15 ,-1 , 0
    2992     .12       0  3234.8     .16       0  3527.4     .05       0
  3773.9     .12       0  4493.6     .05       0  4899.5     .12       0
  5001.3     .07       0  5007.3     .12       0  6961.5     .07       0
  7050.3     .12       0  7278.8     .07       0  7490.9     .12       0
  7529.9     .07       0  7657.3     .05       0  8050.6     .12       0
Bank Sta=4961.6,5067.5
XS Rating Curve= 0 ,0
Exp/Cntr=0.3,0.1

Type RM Length L Ch R = 1 ,13525   ,697,697,697
BEGIN DESCRIPTION:
KEECHIE CREEK 15.0
END DESCRIPTION:
XS GIS Cut Line= 3
      3708049.64     10617660.22      3706499.61     10616260.19
      3702899.65     10617860.17
#Sta/Elev= 30
  2907.4  271.48  3100.2     257  3159.4  253.59  3599.9  228.32  3879.4  221.13
  4799.5  216.57    4918  216.38  5007.5  205.37  5010.2  204.87  5013.5  205.37
    5018  213.45  5028.2  215.76  5094.6  213.97  5103.5  207.98    5109  215.79
  5126.7  207.02  5132.2  216.08  5269.7   211.1  5346.3  218.09  6451.5   216.7
  6482.3  211.72  6557.6  217.65  6995.4   217.7  7368.7  217.18  7397.4  213.39
  7530.3  217.28  7535.7  217.26  7640.8  216.72  7878.1  217.94  8935.6  219.36
#Mann= 13 ,-1 , 0
  2907.4     .05       0  3100.2     .16       0  3159.4     .05       0
  3599.9     .12       0  3879.4     .05       0  4799.5     .12       0
  5007.5     .07       0  5013.5     .12       0  6995.4     .07       0
  7530.3     .05       0  7535.7     .12       0  7640.8     .05       0
  7878.1     .12       0
Bank Sta=4918,5028.2
XS Rating Curve= 0 ,0
Exp/Cntr=0.3,0.1

Type RM Length L Ch R = 1 ,12828   ,497,497,497
BEGIN DESCRIPTION:
KEECHIE CREEK 14.0
END DESCRIPTION:
XS GIS Cut Line= 3
      3708299.64     10615860.19      3706749.61     10615810.19
       3703149.6     10616210.19
#Sta/Elev= 30
  3442.9  242.69    3598  229.14  3771.8  219.22  3853.1  217.15  3873.2  222.05
  3893.2  218.24  4003.2  217.05  4023.2  213.35  4033.2  217.34  4063.3  217.29
  4083.3  216.43  4103.3  210.45  4113.3  217.96  4290.7  216.16  4673.6  215.81
  4699.6  210.73  4713.6  209.08  4823.6  214.07  4923.7  214.25  4943.7  209.36
  5000.8  204.82  5003.5  204.32  5006.8  204.82    5034  212.58  5094.4  211.26
  5124.5  215.16  6100.5  218.54  6900.4  217.34  7631.6  218.17  8615.9  218.08
#Mann= 8 ,-1 , 0
  3442.9     .16       0  3771.8     .12       0  4290.7     .05       0
  4699.6     .12       0  5000.8     .07       0  5006.8     .12       0
  6900.4     .05       0  7631.6     .12       0
Bank Sta=4923.7,5124.5
XS Rating Curve= 0 ,0
Exp/Cntr=0.3,0.1

Type RM Length L Ch R = 1 ,12331   ,1706,1706,1706
BEGIN DESCRIPTION:
KEECHIE CREEK 13.0
END DESCRIPTION:
XS GIS Cut Line= 3
      3708449.61     10615660.19      3706899.61     10615460.19
      3703299.62     10615860.19
#Sta/Elev= 30
    3445  254.43  3561.6   240.7  3747.5  225.79  3989.9   218.1  4089.1  217.86
  4266.1  216.08    4292  215.09  4312.1  209.81  4332.3   217.4  4382.7  214.44
  4443.2  217.56  4577.8  215.97  4745.7  211.81  4806.2  214.78  4957.4  214.18
  4977.6  212.26  4989.6  204.43  4994.8  204.06  4997.5  203.56  5000.8  204.06
    5038  211.45    5199  211.06  5541.1  219.17  6084.4  216.23  7368.5   217.4
  7371.9  217.25  8180.8  217.96  8287.9  217.91  8380.7  218.23    8630   218.5
#Mann= 12 ,-1 , 0
    3445     .16       0  3989.9     .05       0  4089.1     .12       0
  4577.8     .05       0  4989.6     .12       0  4994.8     .07       0
  5000.8     .12       0  7368.5     .05       0  7371.9     .12       0
  8180.8     .07       0  8287.9     .05       0  8380.7     .07       0
Bank Sta=4957.4,5038
XS Rating Curve= 0 ,0
Exp/Cntr=0.3,0.1

Type RM Length L Ch R = 1 ,10625   ,549,549,549
BEGIN DESCRIPTION:
KEECHIE CREEK 12.0
END DESCRIPTION:
XS GIS Cut Line= 3
      3708999.62      10615510.2      3707599.61     10614410.19
      3703999.61     10615610.19
#Sta/Elev= 30
  3230.6  278.79  3337.3  269.68  3351.7  272.59  3465.6  263.69  3534.2  262.98
  4036.2  222.79  4314.1   215.5  4349.4  215.13  4450.6  214.52  4533.9  213.36
  4555.2  209.85  4572.6  209.96  4626.9   208.6  4694.7   213.7  4875.5   214.6
  4904.4   210.7  4910.8   213.8  4960.5  212.25  4968.6  206.41  4974.9  211.13
    4983  203.59  4989.4  206.05  4994.5  203.41  4997.2  202.91  5000.5  203.41
  5021.6  203.42  5053.2  210.32  5158.6  213.95  5316.8  217.85  8805.8  217.72
#Mann= 11 ,-1 , 0
  3230.6     .16       0  3534.2     .12       0  4036.2     .05       0
  4314.1     .07       0  4349.4     .05       0  4450.6     .07       0
  4555.2     .05       0  4572.6     .07       0  4694.7     .12       0
  4994.5     .07       0  5000.5     .12       0
Bank Sta=4875.5,5158.6
XS Rating Curve= 0 ,0
Exp/Cntr=0.3,0.1

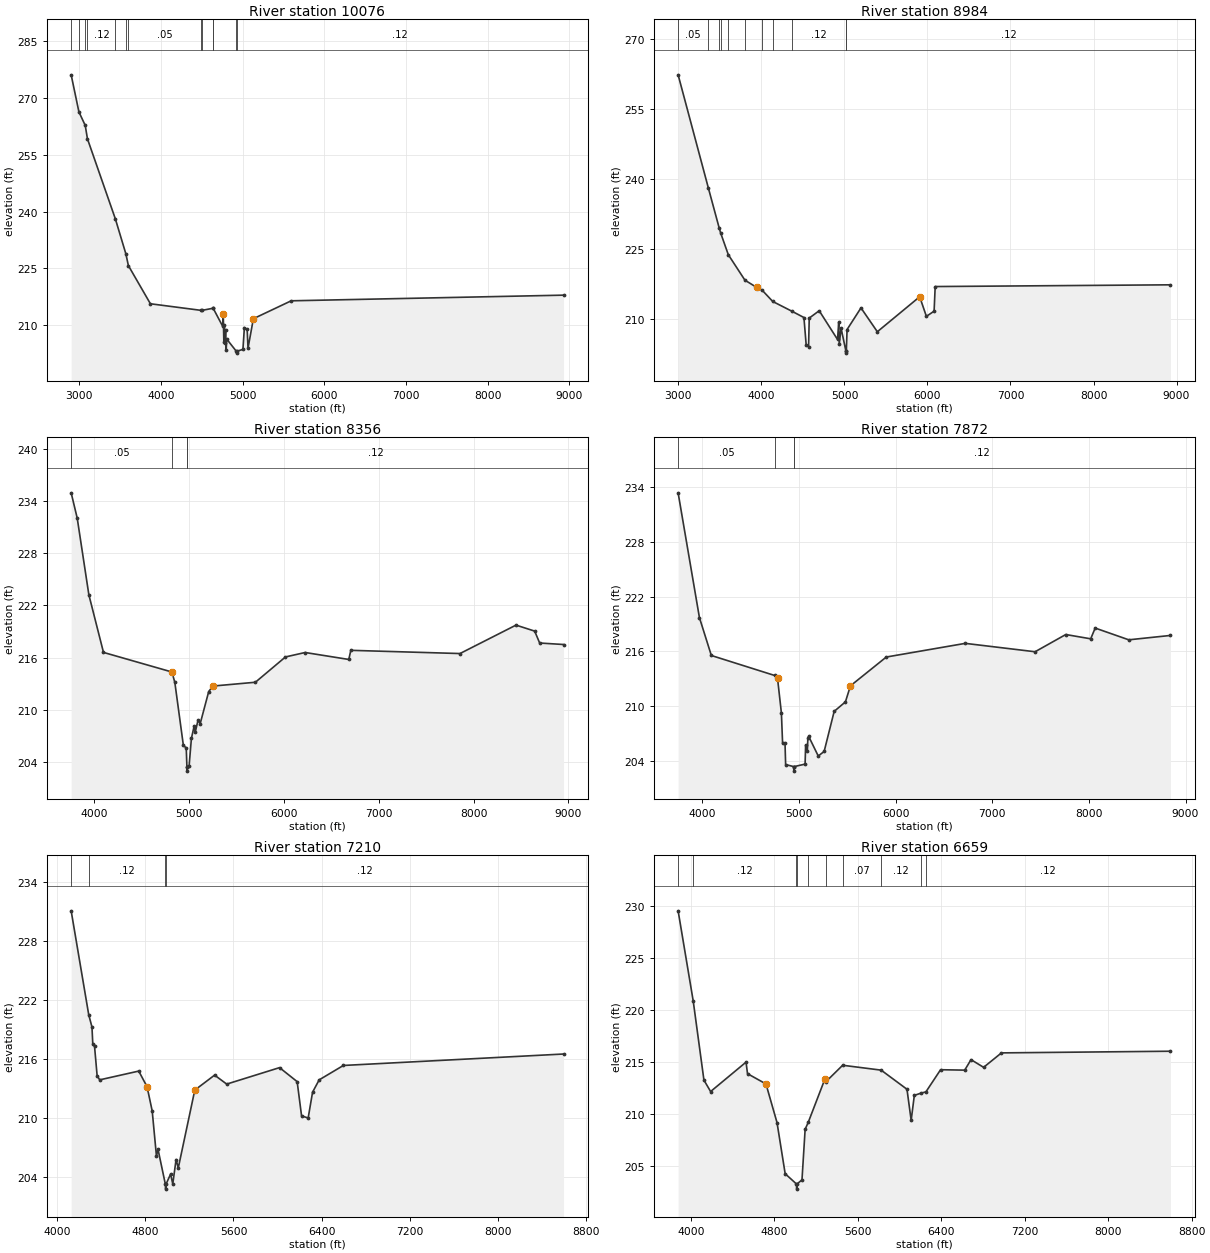
Type RM Length L Ch R = 1 ,10076   ,1092,1092,1092
BEGIN DESCRIPTION:
KEECHIE CREEK 11.0
END DESCRIPTION:
XS GIS Cut Line= 3
      3709049.63     10615360.21      3707499.61     10613960.19
      3703899.64     10615560.18
#Sta/Elev= 30
  2900.6  276.03  2995.5  266.26    3073  262.69  3099.9  259.17  3441.9  238.05
  3570.8  228.82  3601.1  225.75  3870.8  215.69  4484.5  213.97  4502.7  213.95
  4631.5  214.48  4637.9  214.56  4755.8  209.75  4762.5   213.1    4770  205.72
  4776.7  210.16  4784.2  205.39  4790.9  208.78  4798.3  203.48  4805.1  206.38
  4922.4  203.18  4925.1  202.68  4928.4  203.18  5003.6  203.66  5021.4  209.42
  5055.6  208.94  5065.9  203.97  5131.5  211.75  5594.6  216.47  8928.8  217.96
#Mann= 13 ,-1 , 0
  2900.6     .16       0  2995.5     .05       0    3073     .16       0
  3099.9     .12       0  3441.9     .05       0  3570.8     .12       0
  3601.1     .05       0  4484.5     .07       0  4502.7     .12       0
  4631.5     .07       0  4637.9     .12       0  4922.4     .07       0
  4928.4     .12       0
Bank Sta=4762.5,5131.5
XS Rating Curve= 0 ,0
Exp/Cntr=0.3,0.1

Type RM Length L Ch R = 1 ,8984    ,628,628,628
BEGIN DESCRIPTION:
KEECHIE CREEK 10.0
END DESCRIPTION:
XS GIS Cut Line= 3
      3709149.61     10615110.19      3707899.61     10613560.19
      3704299.59      10615160.2
#Sta/Elev= 30
  2996.4  262.26    3360  238.12  3490.1  229.59    3509  228.45  3600.8  223.82
  3801.2  218.37  3942.4  216.83  4010.2   216.2  4136.2  213.82  4369.6  211.71
  4511.8  210.39    4539  204.52  4567.8  204.16  4575.8  210.27  4695.8  211.84
  4916.5   205.7  4930.9  209.33  4937.3  204.78  4959.6  208.09  5016.8  203.28
  5019.5  202.78  5022.8  203.28  5031.4  207.82    5199  212.45    5396  207.35
  5906.2  214.83  5986.9  210.64  6079.9  211.75  6092.9  217.01  8927.2  217.38
#Mann= 11 ,-1 , 0
  2996.4     .05       0    3360     .16       0  3490.1     .12       0
    3509     .05       0  3600.8     .12       0  3801.2     .05       0
  4010.2     .12       0  4136.2     .07       0  4369.6     .12       0
  5016.8     .07       0  5022.8     .12       0
Bank Sta=3942.4,5906.2
XS Rating Curve= 0 ,0
Exp/Cntr=0.3,0.1

Type RM Length L Ch R = 1 ,8356    ,484,484,484
BEGIN DESCRIPTION:
KEECHIE CREEK 9.0
END DESCRIPTION:
XS GIS Cut Line= 3
      3709299.57     10613010.19      3708049.61     10613110.19
      3704449.61     10614710.19
#Sta/Elev= 30
  3755.8  234.94  3819.7  232.03  3942.6  223.21  4096.8  216.59  4814.6  214.35
  4817.9  214.36  4849.2  213.15  4939.5  205.89  4969.6  205.61  4976.7  203.44
  4979.4  202.94  4982.7  203.44  4999.7   203.5  5024.1   206.7  5053.5  208.14
  5064.5  207.41  5093.9  208.79  5117.1  208.41  5206.7  212.09  5250.5  212.72
  5699.2  213.16  6016.5  216.07  6223.8  216.58  6684.1  215.78  6705.9  216.83
    7857  216.46    8448  219.73  8644.9  219.04  8697.6  217.67  8949.3   217.5
#Mann= 4 ,-1 , 0
  3755.8     .05       0  4814.6     .12       0  4976.7     .07       0
  4982.7     .12       0
Bank Sta=4817.9,5250.5
XS Rating Curve= 0 ,0
Exp/Cntr=0.3,0.1

Type RM Length L Ch R = 1 ,7872    ,662,662,662
BEGIN DESCRIPTION:
KEECHIE CREEK 8.0
END DESCRIPTION:
XS GIS Cut Line= 3
      3709299.59     10612960.18      3708199.61     10612610.19
      3704599.57      10614210.2
#Sta/Elev= 30
  3750.7  233.41  3971.1  219.72  4094.4  215.56  4748.4  213.37  4779.1  213.06
  4819.2  209.25  4831.6  205.92  4856.7  205.91    4863  203.59  4945.8  203.37
  4948.5  202.87  4951.8  203.37  5064.4  203.64  5069.8  205.73  5087.6  205.07
  5093.1  206.54    5102  206.67  5200.5  204.53  5261.4  205.03  5365.3  209.43
  5481.6  210.47  5533.6  212.23  5904.3  215.39  6721.6  216.89  7443.8  215.97
  7761.2  217.86    8019  217.39  8065.5  218.57    8413  217.28  8844.6  217.76
#Mann= 4 ,-1 , 0
  3750.7     .05       0  4748.4     .12       0  4945.8     .07       0
  4951.8     .12       0
Bank Sta=4779.1,5533.6
XS Rating Curve= 0 ,0
Exp/Cntr=0.3,0.1

Type RM Length L Ch R = 1 ,7210    ,551,551,551
BEGIN DESCRIPTION:
KEECHIE CREEK 7.0
END DESCRIPTION:
XS GIS Cut Line= 3
      3709299.61     10612510.19      3708499.61     10612160.19
      3704899.63     10612160.19
#Sta/Elev= 30
  4125.5  231.03    4285   220.5  4314.6  219.24    4322  217.53    4338  217.28
  4361.4  214.31  4384.7  213.89  4739.5  214.78  4815.1  213.19  4861.9  210.73
  4900.5  206.14  4914.1  206.87  4981.3  203.31    4984  202.81  4987.3  203.31
  5028.7  204.33  5048.7  203.34  5078.7  205.81  5098.7  204.96  5248.7  212.85
  5428.7  214.37  5538.7  213.46  6018.7  215.13  6178.7  213.71  6218.7  210.24
  6278.7  210.02  6318.7  212.64  6378.7  213.89  6598.7  215.35  8598.7  216.51
#Mann= 4 ,-1 , 0
  4125.5     .05       0    4285     .12       0  4981.3     .07       0
  4987.3     .12       0
Bank Sta=4815.1,5248.7
XS Rating Curve= 0 ,0
Exp/Cntr=0.3,0.1

Type RM Length L Ch R = 1 ,6659    ,1985,1985,1985
BEGIN DESCRIPTION:
KEECHIE CREEK 6.0
END DESCRIPTION:
XS GIS Cut Line= 3
      3709299.61     10612410.19      3708499.61     10611660.19
      3704899.65     10612060.18
#Sta/Elev= 30
  3878.4  229.55    4023  220.88  4125.8  213.26  4189.8  212.16  4529.3  214.99
  4543.4  213.88  4720.3  212.89  4826.3  209.17  4904.4  204.25  5012.2  203.27
    5015  202.77  5018.2  203.27  5065.5  203.66  5095.7  208.53  5125.6   209.2
  5286.9  213.41  5296.2  213.12  5455.3  214.69  5824.3  214.22  6071.7  212.38
  6111.9  209.39  6142.1  211.79  6203.9     212  6253.3  212.13  6393.7  214.26
  6625.1  214.22  6685.4  215.23  6806.2  214.49  6977.2  215.88  8597.1  216.04
#Mann= 10 ,-1 , 0
  3878.4     .05       0    4023     .12       0  5012.2     .07       0
  5018.2     .12       0  5125.6     .07       0  5296.2     .12       0
  5455.3     .07       0  5824.3     .12       0  6203.9     .07       0
  6253.3     .12       0
Bank Sta=4720.3,5286.9
XS Rating Curve= 0 ,0
Exp/Cntr=0.3,0.1

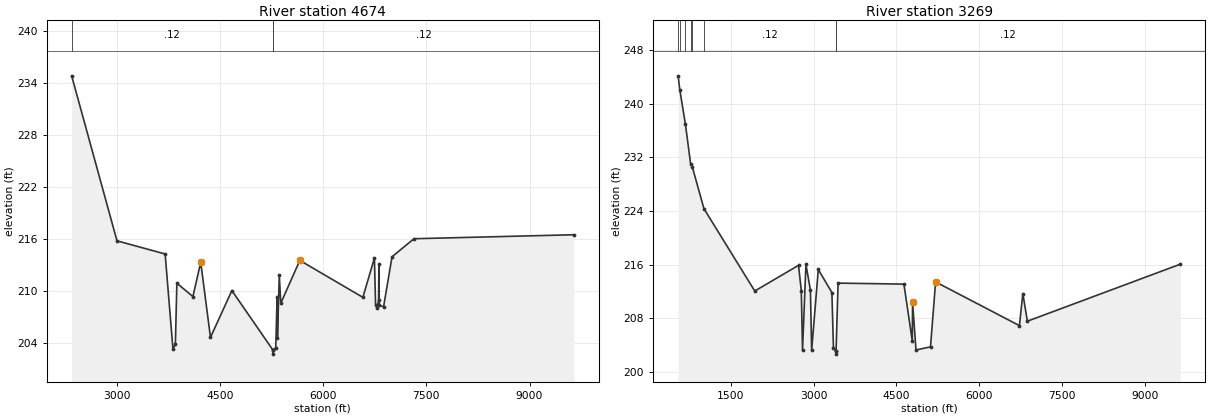
Type RM Length L Ch R = 1 ,4674    ,1405,1405,1405
BEGIN DESCRIPTION:
KEECHIE CREEK 5.0
END DESCRIPTION:
XS GIS Cut Line= 3
      3710549.62      10612560.2      3708749.61     10610560.19
      3704249.62     10611560.19
#Sta/Elev= 30
  2343.7  234.83  3002.6   215.8  3702.9  214.28  3816.5   203.3  3851.6  203.89
  3873.3  210.91  4106.5  209.37  4220.1  213.33  4361.8  204.66  4673.1  210.06
  5267.1  203.23  5269.8  202.73  5273.1  203.23    5311  203.45  5330.2  209.32
  5335.4  204.61  5362.2  211.83    5384   208.6  5660.6  213.54  6577.4  209.28
  6745.2  213.81  6761.8  208.44  6786.2  208.06  6805.4  208.94  6810.5  213.07
  6816.9  208.37  6878.3  208.19  7001.3  213.96  7320.1  216.04  9644.2   216.5
#Mann= 3 ,-1 , 0
  2343.7     .12       0  5267.1     .07       0  5273.1     .12       0
Bank Sta=4220.1,5660.6
XS Rating Curve= 0 ,0
Exp/Cntr=0.3,0.1

Type RM Length L Ch R = 1 ,3269    ,712,712,712
BEGIN DESCRIPTION:
KEECHIE CREEK 4.0
END DESCRIPTION:
XS GIS Cut Line= 3
      3713299.59     10612160.18      3709299.61     10610160.19
      3704799.59     10609160.19
#Sta/Elev= 30
   550.7  244.16   581.3  242.07     682  236.99   777.5  230.99   807.4  230.57
  1017.5  224.35    1937  212.07    2728   215.9  2778.4  212.13  2800.7  203.23
  2862.2  216.05  2943.3  212.21  2965.6  203.23  3085.8  215.28  3331.8  211.84
  3359.7  203.56  3401.5  203.16  3404.2  202.66  3407.5  203.16  3443.6  213.25
  4634.3   213.1  4785.2  204.66  4790.8  210.41  4852.3  203.28    5115  203.74
  5207.2  213.43  6723.3  206.91  6784.8  211.69  6866.7  207.57  9632.6  216.07
#Mann= 8 ,-1 , 0
   550.7     .12       0   581.3     .16       0     682     .12       0
   777.5     .16       0   807.4     .05       0  1017.5     .12       0
  3401.5     .07       0  3407.5     .12       0
Bank Sta=4790.8,5207.2
XS Rating Curve= 0 ,0
Exp/Cntr=0.3,0.1