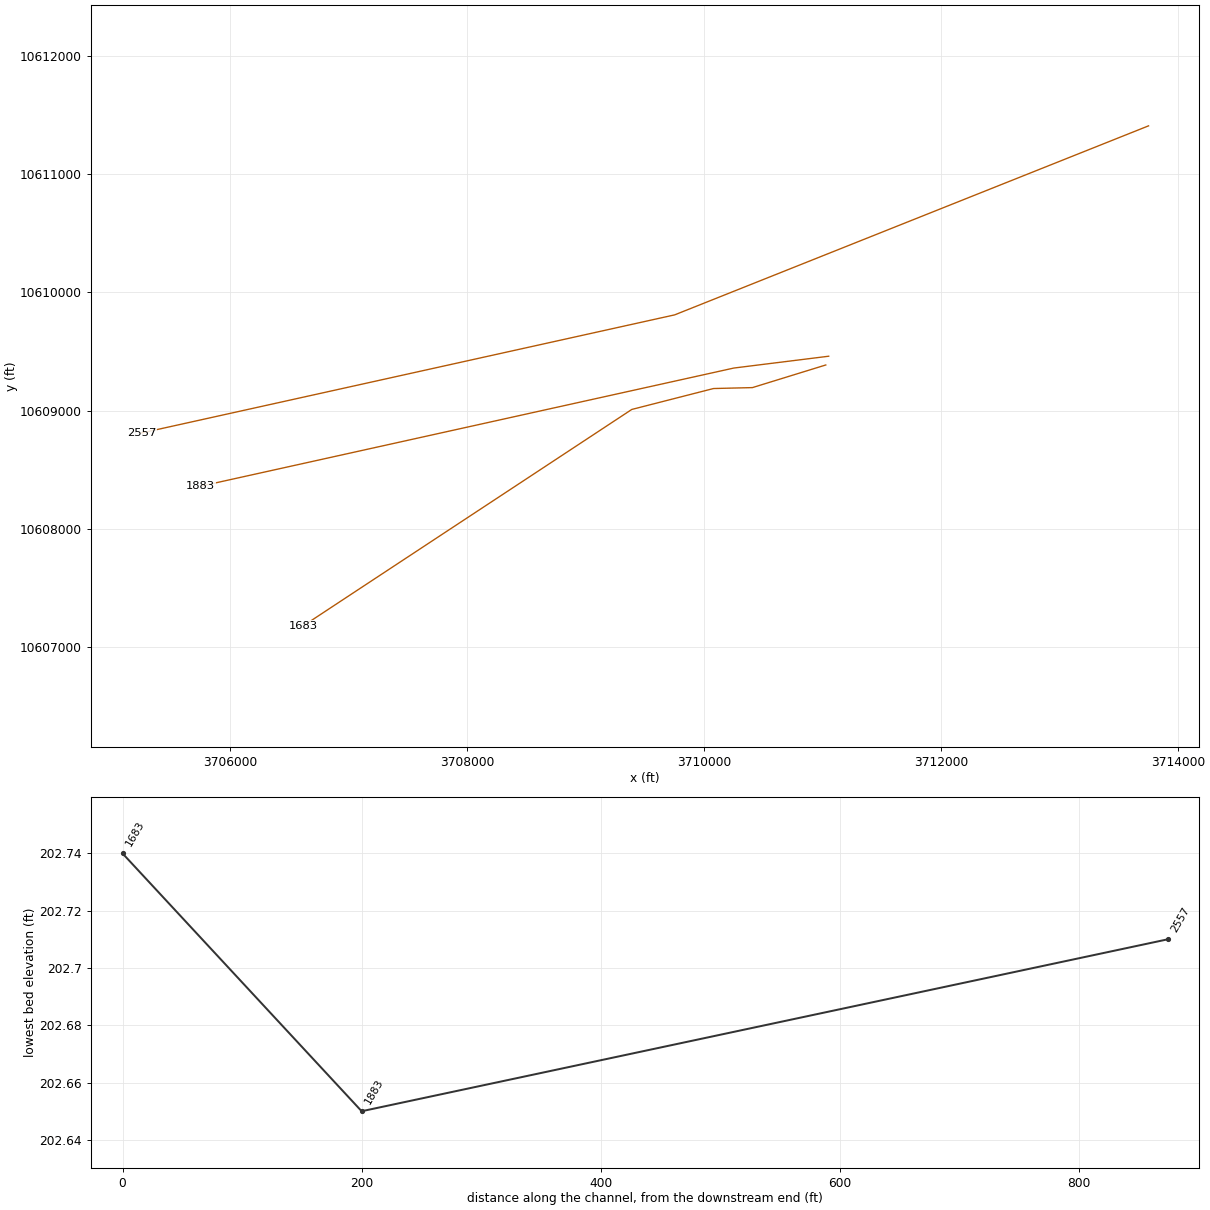
HEC-RAS study KEECHIE CREEK.prj: KEECHIE CREEK Base Level Engineering

--- KEECHIE CREEK.g01 (geometry) --- (continued)

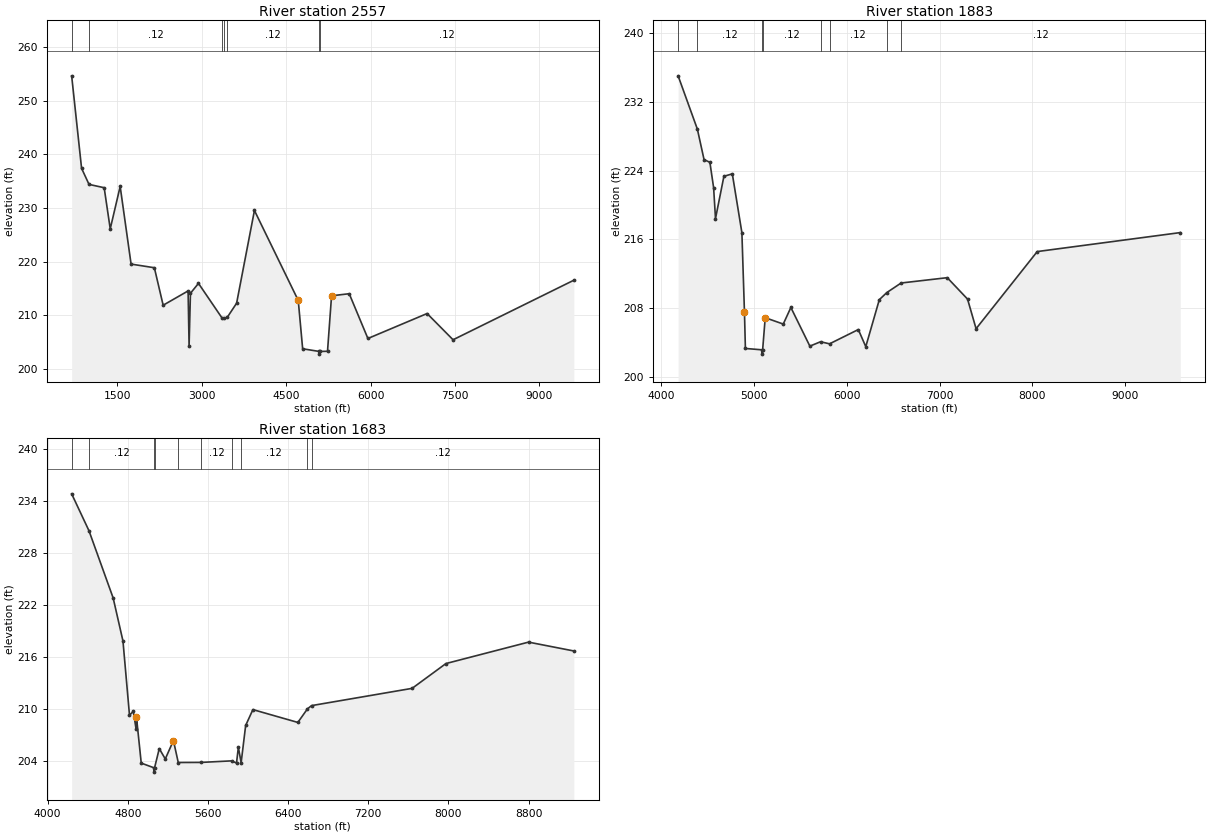
Type RM Length L Ch R = 1 ,2557    ,674,674,674
BEGIN DESCRIPTION:
KEECHIE CREEK 3.0
END DESCRIPTION:
XS GIS Cut Line= 3
      3713749.56     10611410.17      3709749.61     10609810.19
      3705249.56     10608810.18
#Sta/Elev= 30
   692.5  254.67   868.8   237.4    1001   234.4    1270  233.78  1377.7   226.1
  1554.1  234.02  1747.9  219.52  2161.3  218.84  2317.4  211.84  2760.4  214.51
  2777.9  204.25  2802.1  214.07  2944.8  215.92  3363.3  209.45    3398  209.43
  3455.3  209.57    3622  212.22  3938.4  229.53  4716.5  212.73  4794.6  203.71
  5089.8  203.21  5092.5  202.71  5095.8  203.21  5236.2  203.24  5307.9   213.6
  5621.6  213.99  5953.3  205.63  7004.6  210.29  7465.5  205.39  9610.4  216.51
#Mann= 7 ,-1 , 0
   692.5     .16       0    1001     .12       0  3363.3     .05       0
    3398     .07       0  3455.3     .12       0  5089.8     .07       0
  5095.8     .12       0
Bank Sta=4716.5,5307.9
XS Rating Curve= 0 ,0
Exp/Cntr=0.3,0.1

Type RM Length L Ch R = 1 ,1883    ,200,200,200
BEGIN DESCRIPTION:
KEECHIE CREEK 2.0
END DESCRIPTION:
XS GIS Cut Line= 3
      3711049.58     10609460.18      3710249.61     10609360.19
      3705749.58     10608360.18
#Sta/Elev= 30
  4179.3  235.05    4387  228.84  4458.9   225.3  4521.9  224.98  4562.2  222.03
  4582.4  218.43  4673.1  223.35  4763.8  223.64  4867.1  216.79  4894.8  207.53
  4904.9  203.31  5084.9  203.15  5087.7  202.65  5090.9  203.15  5118.7  206.89
  5313.3  206.15  5395.3  208.08  5600.1  203.58  5715.1  204.09  5812.5  203.85
  6122.6  205.51  6203.2  203.52  6349.2  208.99  6430.5  209.82  6584.3  210.93
  7081.7  211.55  7300.6  209.06  7392.8  205.61  8052.3  214.59  9595.3   216.8
#Mann= 8 ,-1 , 0
  4179.3     .05       0    4387     .12       0  5084.9     .07       0
  5090.9     .12       0  5715.1     .07       0  5812.5     .12       0
  6430.5     .07       0  6584.3     .12       0
Bank Sta=4894.8,5118.7
XS Rating Curve= 0 ,0
Exp/Cntr=0.3,0.1

Type RM Length L Ch R = 1 ,1683    ,0,0,0
BEGIN DESCRIPTION:
KEECHIE CREEK 1.0
END DESCRIPTION:
XS GIS Cut Line= 5
       3711025.2     10609386.12      3710405.95     10609194.59
      3710077.83     10609186.77      3709387.72     10609009.69
      3706614.36     10607177.85
#Sta/Elev= 30
  4239.8  234.83  4412.8  230.57  4654.1  222.82    4752  217.86  4817.2   209.3
  4855.1  209.75  4882.4  207.76    4887  209.05  4934.4  203.78  5061.4  203.24
  5064.1  202.74  5067.4  203.24  5114.4  205.45  5174.4  204.26  5255.7  206.38
  5303.8  203.85  5532.3  203.86  5837.4  204.04  5885.4  203.78  5903.7  205.61
  5931.6  203.83  5976.7  208.12    6049  209.95  6497.5  208.47  6593.8  210.04
  6634.5  210.41  7638.3   212.4  7975.8  215.26  8800.2  217.73  9252.4  216.71
#Mann= 10 ,-1 , 0
  4239.8     .05       0  4412.8     .12       0  5061.4     .07       0
  5067.4     .12       0  5303.8     .07       0  5532.3     .12       0
  5837.4     .07       0  5931.6     .12       0  6593.8     .07       0
  6634.5     .12       0
Bank Sta=4887,5255.7
XS Rating Curve= 0 ,0
Exp/Cntr=0.3,0.1

Chan Stop Cuts=-1
Use User Specified Reach Order=0
Composite Channel Slope=5