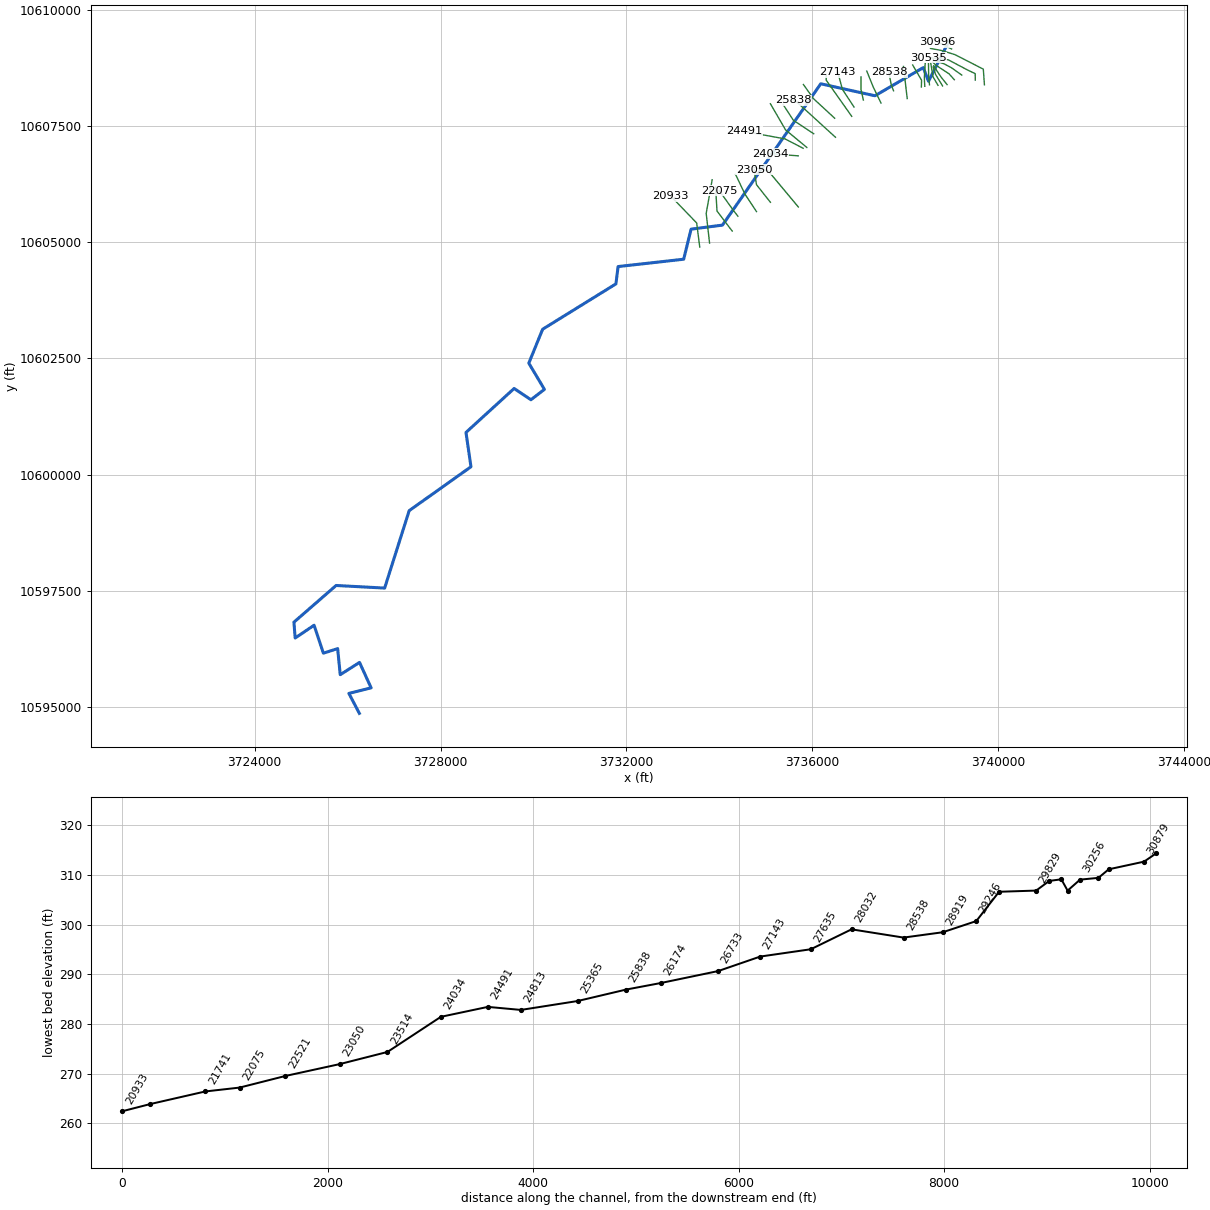
--- MACK CREEK.prj (project) ---

Proj Title=MACK CREEK Base Level Engineering
Current Plan=p01
Default Exp/Contr=0.3,0.1
English Units
Geom File=g01
Flow File=f01
Plan File=p01
Y Axis Title=Elevation
X Axis Title(PF)=Main Channel Distance
X Axis Title(XS)=Station
BEGIN DESCRIPTION:
MACK CREEK
END DESCRIPTION:
DSS Export Rating Curves= 0
DSS Export Rating Curve Sorted= 0
DSS Export Volume Flow Curves= 0
DXF OffsetX= 0
DXF OffsetY= 0
DXF ScaleX= 1
DXF ScaleY= 10

--- MACK CREEK.p01 (plan) ---

Plan Title=Multiple Run
Short Identifier=Multiple
Geom File=g01
Flow File=f01
Subcritical Flow
K Sum by GR= 0
Std Step Tol= 0.01
Critical Tol= 0.01
Num of Std Step Trials= 20
Max Error Tol= 0.3
Flow Tol Ratio= 0.001
Split Flow NTrial= 30
Split Flow Tol= 0.02
Split Flow Ratio= 0.02
Log Output Level= 0
Friction Slope Method= 1
Unsteady Friction Slope Method= 2
Unsteady Bridges Friction Slope Method= 1
Parabolic Critical Depth
Global Vel Dist=  1 , 1 , 1
Global Log Level= 0
CheckData=True
Encroach Param= -1, 0, 0, 0
BEGIN DESCRIPTION:
Multiple Run
END DESCRIPTION:

--- MACK CREEK.f01 (steady flow) ---

Flow Title=Multiple
Program Version=4.10
Number of Profiles= 7
Profile Names=10-year,25-year,50-year,1pct_min,100-year,1pct_plu,500-year
River Rch & RM=MACK CREEK,Reach-1         ,30996
     877    1215    1499    1359    1838    2486    2774
River Rch & RM=MACK CREEK,Reach-1         ,28919
    1088    1520    1887    1719    2324    3144    3542
River Rch & RM=MACK CREEK,Reach-1         ,23050
    1270    1787    2228    2038    2756    3728    4235
River Rch & RM=MACK CREEK,Reach-1         ,20933
    1931    2754    3465    3192    4317    5839    6732
River Rch & RM=MACK CREEK,Reach-1         ,20420
    1931    2754    3465    3192    4317    5839    6732
River Rch & RM=MACK CREEK,Reach-1         ,5742
    2029    2900    3655    3371    4559    6166    7128
Boundary for River Rch & Prof#=MACK CREEK,Reach-1         , 1
Up Type= 0
Dn Type= 3
Dn Slope=0.007
Boundary for River Rch & Prof#=MACK CREEK,Reach-1         , 2
Up Type= 0
Dn Type= 3
Dn Slope=0.007
Boundary for River Rch & Prof#=MACK CREEK,Reach-1         , 3
Up Type= 0
Dn Type= 3
Dn Slope=0.007
Boundary for River Rch & Prof#=MACK CREEK,Reach-1         , 4
Up Type= 0
Dn Type= 3
Dn Slope=0.007
Boundary for River Rch & Prof#=MACK CREEK,Reach-1         , 5
Up Type= 0
Dn Type= 3
Dn Slope=0.007
Boundary for River Rch & Prof#=MACK CREEK,Reach-1         , 6
Up Type= 0
Dn Type= 3
Dn Slope=0.007
Boundary for River Rch & Prof#=MACK CREEK,Reach-1         , 7
Up Type= 0
Dn Type= 3
Dn Slope=0.007
DSS Import GetInterval= 0
DSS Import GetPeak= 0
DSS Import FillOption= 0

--- MACK CREEK.g01 (geometry) ---

Geom Title=Existing Conditions
Program Version=4.10

River Reach=MACK CREEK      ,Reach-1
Reach XY= 30
      3738972.36     10609389.15        3738502.       10608464.
        3738389.       10608759.        3737349.     10608153.17
        3736183.     10608411.17      3734067.34       10605369.
        3733392.       10605282.       3733232.5       10604635.
        3731821.       10604477.        3731774.       10604104.
        3730197.       10603128.      3729899.25       10602398.
      3730235.25       10601834.        3729945.       10601610.
      3729583.25       10601853.      3728547.25       10600907.
      3728654.25       10600168.       3727324.5       10599223.
       3726796.5       10597557.        3725752.       10597613.
        3724844.       10596823.      3724870.25       10596482.
      3725277.75       10596757.        3725478.       10596156.
      3725784.75       10596254.      3725840.75       10595693.
      3726255.75       10595957.      3726505.25       10595410.
        3726027.       10595290.      3726252.17     10594860.28

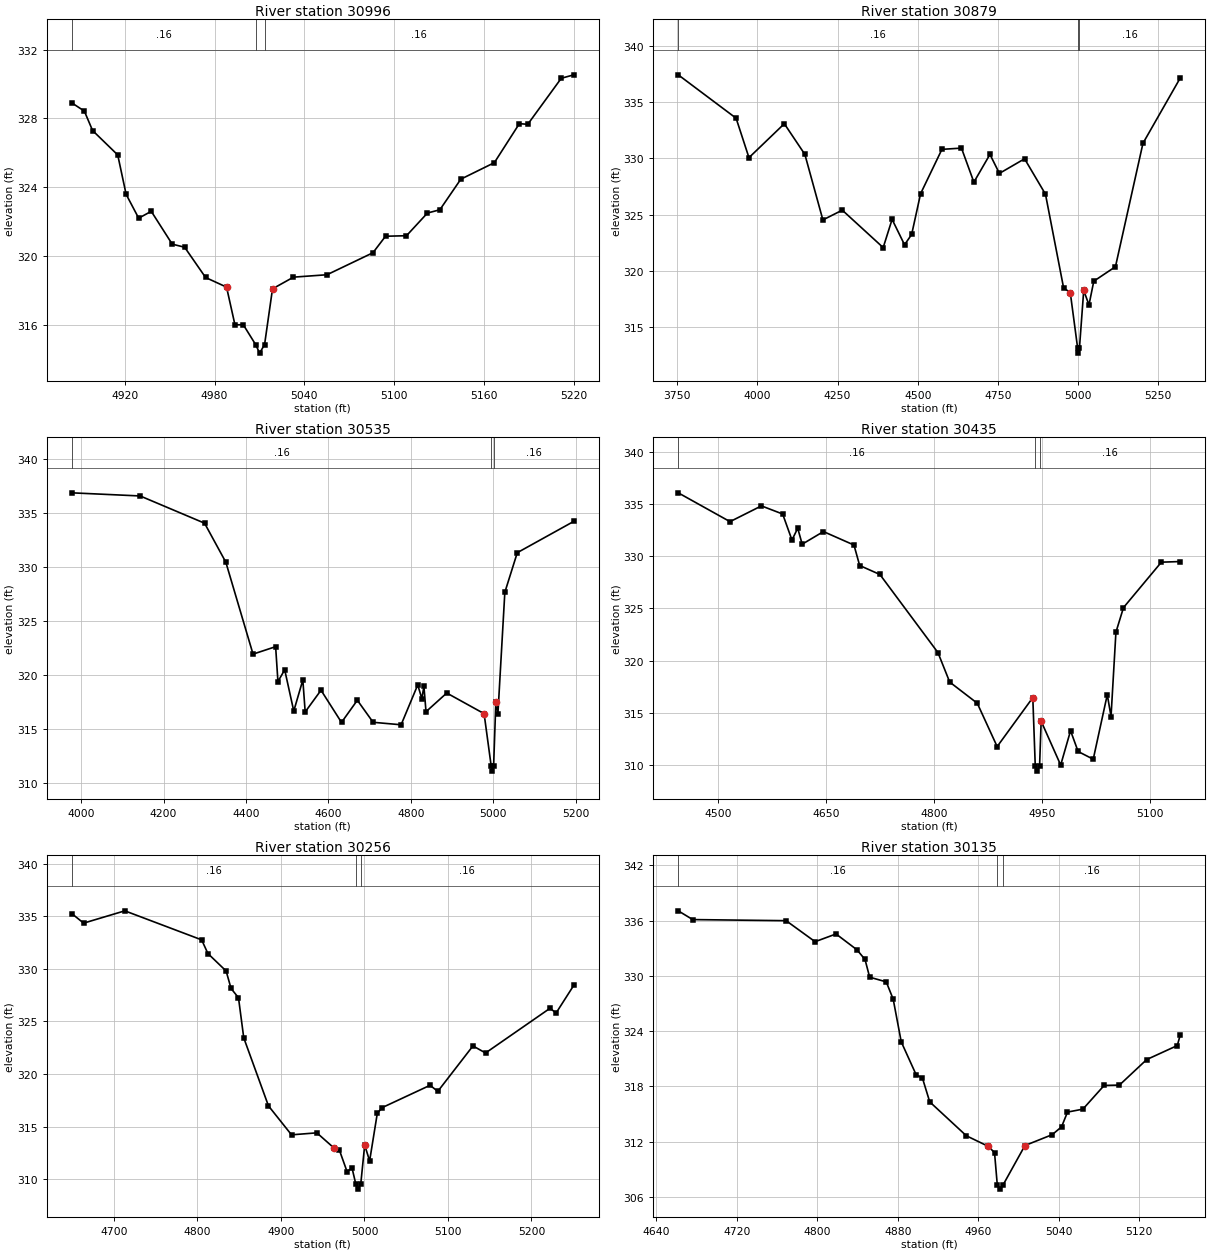
Type RM Length L Ch R = 1 ,30996   ,117,117,117
BEGIN DESCRIPTION:
MACK CREEK 62.0
END DESCRIPTION:
XS GIS Cut Line= 3
      3738999.59      10609160.2      3738899.61     10609210.19
       3738699.6      10609310.2
#Sta/Elev= 30
  4884.6   328.9    4893  328.42  4898.5  327.29  4915.3  325.87  4920.9  323.58
  4929.3  322.19  4937.7  322.59  4951.7  320.68    4960   320.5    4974  318.74
    4988  318.18  4993.6  315.99  4999.2  315.99  5007.4  314.84  5010.1  314.34
  5013.4  314.84  5018.7  318.08  5032.7  318.76  5055.1   318.9  5085.8  320.18
  5094.2  321.14  5108.2  321.17  5122.2  322.49  5130.5  322.68  5144.5  324.46
  5166.9  325.42  5183.6  327.69  5189.2  327.65  5211.6  330.33    5220  330.53
#Mann= 3 ,-1 , 0
  4884.6     .16       0  5007.4     .07       0  5013.4     .16       0
Bank Sta=4988,5018.7
XS Rating Curve= 0 ,0
Exp/Cntr=0.3,0.1

Type RM Length L Ch R = 1 ,30879   ,344,344,344
BEGIN DESCRIPTION:
Mapping XS 0a057f5d
END DESCRIPTION:
XS GIS Cut Line= 5
3739705.5684443210608390.1453157      3739681.48     10608726.05
       3739072.8     10609037.95      3738781.13     10609128.23
      3738545.01     10609171.63
#Sta/Elev= 30
  3752.9  337.44  3933.4  333.58  3973.5  330.07  4083.8  333.09  4147.9  330.36
  4204.1  324.53  4264.6   325.4  4392.2  322.07    4420  324.58  4458.8  322.32
    4481  323.24  4508.8  326.86  4575.4  330.81  4636.4  330.92  4675.1  327.89
  4725.2  330.36  4754.7  328.67  4833.2  329.97  4898.4  326.82  4954.9  318.49
  4975.8  318.06  4998.5  313.18  5001.3  312.68  5004.5  313.18  5017.7  318.26
  5034.1  316.97  5049.1  319.08  5116.7  320.37  5202.5  331.35    5319  337.17
#Mann= 3 ,-1 , 0
  3752.9     .16       0  4998.5     .07       0  5004.5     .16       0
Bank Sta=4975.8,5017.7
XS Rating Curve= 0 ,0
Exp/Cntr=0.3,0.1

Type RM Length L Ch R = 1 ,30535   ,100,100,100
BEGIN DESCRIPTION:
MACK CREEK 61.0
END DESCRIPTION:
XS GIS Cut Line= 5
      3739509.24      10608490.4      3739507.65     10608628.61
      3739331.95     10608713.39      3738927.37     10608926.96
      3738493.31      10608976.1
#Sta/Elev= 30
  3977.4   336.9  4143.3  336.61  4299.5  334.09  4351.1  330.48  4417.1  321.97
  4471.9  322.66  4477.5  319.43  4493.9  320.52  4515.9   316.7  4537.9  319.58
  4543.6  316.62    4582  318.63  4631.7  315.65  4670.1   317.7  4708.4  315.66
  4776.3  315.43  4816.6  319.12  4826.6  317.85  4831.6  318.99  4836.7  316.64
    4887  318.37  4977.6  316.46  4994.7  311.64  4997.5  311.14  5000.7  311.64
  5006.1  317.57  5011.1  316.45  5027.9  327.69  5058.1  331.36  5195.3  334.26
#Mann= 3 ,-1 , 0
  3977.4     .16       0  4994.7     .07       0  5000.7     .16       0
Bank Sta=4977.6,5006.1
XS Rating Curve= 0 ,0
Exp/Cntr=0.3,0.1

Type RM Length L Ch R = 1 ,30435   ,179,179,179
BEGIN DESCRIPTION:
Mapping XS 3e3df57b
END DESCRIPTION:
XS GIS Cut Line= 4
3739218.1083952510608597.6506703      3738998.78     10608754.39
      3738834.95     10608841.77      3738604.33     10608914.59
#Sta/Elev= 30
  4445.1  336.07    4517  333.31  4560.6  334.82  4590.1  334.04    4603  331.55
    4611  332.68  4617.2  331.15  4646.7  332.36  4689.1  331.07    4697  329.11
  4725.1  328.25  4805.7  320.77    4822  317.95  4860.3  315.92  4887.9  311.77
  4937.4  316.46  4940.8  309.92  4943.5  309.42  4946.8  309.92    4949   314.2
  4976.1     310  4989.8  313.29  5000.3   311.3  5021.3  310.56  5040.8  316.74
    5046  314.65  5052.8  322.72  5063.3  325.08  5115.9  329.43  5142.2  329.49
#Mann= 3 ,-1 , 0
  4445.1     .16       0  4940.8     .07       0  4946.8     .16       0
Bank Sta=4937.4,4949
XS Rating Curve= 0 ,0
Exp/Cntr=0.3,0.1

Type RM Length L Ch R = 1 ,30256   ,121,121,121
BEGIN DESCRIPTION:
Mapping XS dd04a217
END DESCRIPTION:
XS GIS Cut Line= 4
3739057.50150913  10608498.44315      3738943.25     10608626.18
      3738666.55     10608807.04      3738593.95     10608874.57
#Sta/Elev= 30
  4649.6  335.25  4663.8  334.34  4713.1  335.51  4805.1  332.75  4812.6  331.45
  4834.4  329.79  4840.3  328.13  4849.2  327.25  4855.5  323.44  4885.1  316.97
  4912.7  314.22    4943  314.41  4964.1  312.93    4970  312.77  4979.2  310.72
  4985.1  311.08  4989.6  309.56  4992.3  309.06  4995.6  309.56  5000.3  313.25
  5006.2  311.74  5015.4  316.27  5021.3  316.81  5078.6  318.93  5087.8  318.35
  5129.9  322.67    5145     322  5222.4  326.26  5229.3  325.78  5250.7  328.44
#Mann= 3 ,-1 , 0
  4649.6     .16       0  4989.6     .07       0  4995.6     .16       0
Bank Sta=4964.1,5000.3
XS Rating Curve= 0 ,0
Exp/Cntr=0.3,0.1

Type RM Length L Ch R = 1 ,30135   ,61,61,61
BEGIN DESCRIPTION:
Mapping XS 54bb4b5d
END DESCRIPTION:
XS GIS Cut Line= 4
3738902.5346644510608392.5886286      3738782.43     10608542.33
      3738708.21     10608650.79      3738613.65     10608798.66
#Sta/Elev= 30
  4661.9  337.05  4676.3   336.1  4769.1  335.98  4797.9   333.7  4818.7  334.54
  4839.5  332.82  4847.5  331.77  4852.1  329.85  4868.6  329.34  4875.5  327.46
  4883.5  322.83  4898.4  319.24  4904.5  318.92  4911.8  316.32  4948.2  312.64
  4970.2  311.48  4976.2   310.8  4978.9  307.35  4981.6  306.85  4984.9  307.35
  5006.4  311.58  5033.5  312.76  5042.8  313.61  5048.7  315.21    5064  315.53
  5085.1   318.1  5100.3  318.14  5127.4  320.91  5157.8  322.43  5160.8  323.61
#Mann= 3 ,-1 , 0
  4661.9     .16       0  4978.9     .07       0  4984.9     .16       0
Bank Sta=4970.2,5006.4
XS Rating Curve= 0 ,0
Exp/Cntr=0.3,0.1

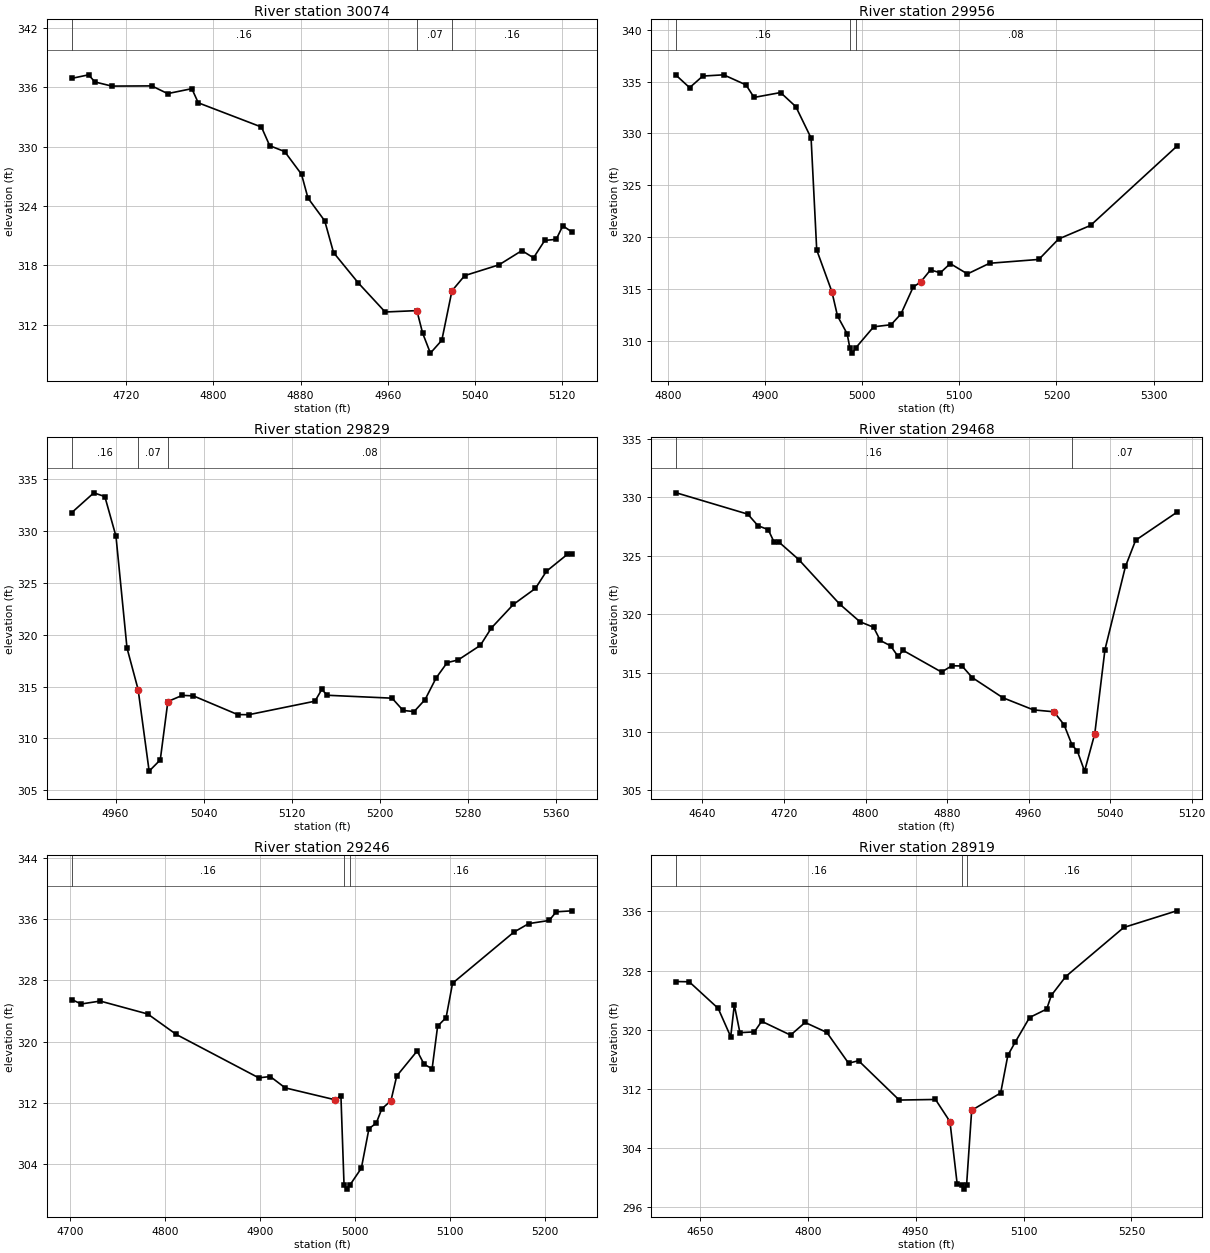
Type RM Length L Ch R = 1 ,30074   ,118,118,118
BEGIN DESCRIPTION:
Mapping XS b9113b89
END DESCRIPTION:
XS GIS Cut Line= 3
3738804.53977625 10608365.043061      3738654.39     10608610.86
       3738602.3      10608774.1
#Sta/Elev= 30
  4669.9  336.92  4685.4  337.28  4691.2  336.56  4706.7  336.14  4743.4  336.16
    4758  335.38  4780.2  335.88  4786.1  334.45  4844.1     332  4851.7  330.11
  4865.4  329.52  4880.9  327.22  4886.8  324.82  4902.2  322.51  4910.3   319.3
  4933.1  316.22  4957.7  313.29  4986.8  313.43  4992.1  311.15  4999.2  309.13
  5009.7  310.43    5019  315.43  5030.7  316.97  5062.2  318.06  5083.2   319.5
  5093.9  318.77  5104.2  320.53  5114.7  320.64  5120.8  322.01  5129.3  321.37
#Mann= 3 ,-1 , 0
  4669.9     .16       0  4986.8     .07       0    5019     .16       0
Bank Sta=4986.8,5019
XS Rating Curve= 0 ,0
Exp/Cntr=0.3,0.1

Type RM Length L Ch R = 1 ,29956   ,127,127,127
BEGIN DESCRIPTION:
MACK CREEK 60.0
END DESCRIPTION:
XS GIS Cut Line= 3
3738706.4363534910608378.3499494      3738599.61     10608560.19
      3738549.61     10608860.15
#Sta/Elev= 30
  4808.8  335.59  4822.5  334.41    4836  335.53  4857.5  335.65  4880.5  334.68
  4888.8  333.47  4916.1  333.94  4931.8  332.58  4947.5  329.55  4953.3  318.75
  4968.9  314.73  4974.7  312.38  4984.6  310.67  4987.4   309.3  4990.1   308.8
  4993.4   309.3  5011.9  311.34  5029.8  311.54    5040  312.58  5052.6  315.18
  5060.2  315.65  5070.4  316.83  5080.5  316.55  5090.7  317.44  5108.4  316.44
  5131.2  317.47  5181.9  317.84  5202.2  319.81  5235.1  321.12  5323.8  328.75
#Mann= 3 ,-1 , 0
  4808.8     .16       0  4987.4     .07       0  4993.4     .08       0
Bank Sta=4968.9,5060.2
XS Rating Curve= 0 ,0
Exp/Cntr=0.3,0.1

Type RM Length L Ch R = 1 ,29829   ,361,361,361
BEGIN DESCRIPTION:
Mapping XS 4d929c8c
END DESCRIPTION:
XS GIS Cut Line= 3
3738522.8791320410608390.1839363      3738505.09     10608581.35
      3738501.62     10608843.53
#Sta/Elev= 30
  4920.2  331.73  4940.3  333.64  4950.3  333.28  4960.4  329.46  4970.4  318.71
  4980.5  314.71  4990.5  306.86  5000.6  307.94  5007.5  313.56  5020.6  314.15
  5030.7   314.1  5070.9   312.3  5080.9  312.29    5141  313.59  5147.2  314.72
  5152.2  314.16    5211  313.88    5221   312.7    5231  312.59    5241  313.75
    5251  315.83    5261   317.3    5271  317.56  5291.1  318.96  5301.1  320.63
  5321.1   322.9  5341.1  324.44  5351.1  326.09  5370.2  327.73  5374.4  327.73
#Mann= 3 ,-1 , 0
  4920.2     .16       0  4980.5     .07       0  5007.5     .08       0
Bank Sta=4980.5,5007.5
XS Rating Curve= 0 ,0
Exp/Cntr=0.3,0.1

Type RM Length L Ch R = 1 ,29468   ,222,222,222
BEGIN DESCRIPTION:
Mapping XS 6ff16cb9
END DESCRIPTION:
XS GIS Cut Line= 4
        3738422.       10608357.      3738415.45     10608457.26
      3738413.07     10608553.57      3738430.44     10608850.45
#Sta/Elev= 30
  4614.4  330.39  4684.5  328.57  4694.5  327.58  4704.5  327.25  4710.5  326.15
  4715.5  326.15  4734.5  324.69  4774.5   320.9  4794.5  319.38  4807.9  318.91
  4814.5  317.78  4824.6  317.32  4831.9  316.42  4836.9  316.93  4874.6  315.08
  4884.7  315.62  4894.7   315.6  4904.7  314.61  4934.7  312.89  4964.8  311.85
  4984.8  311.69  4994.8  310.58  5002.7  308.83  5007.7  308.36  5014.9  306.62
  5024.9  309.81  5034.9     317    5055   324.1    5065  326.34  5105.3  328.72
#Mann= 2 ,-1 , 0
  4614.4     .16       0  5002.7     .07       0
Bank Sta=4984.8,5024.9
XS Rating Curve= 0 ,0
Exp/Cntr=0.3,0.1

Type RM Length L Ch R = 1 ,29246   ,327,327,327
BEGIN DESCRIPTION:
MACK CREEK 59.0
END DESCRIPTION:
XS GIS Cut Line= 3
3738348.3633617510608340.2123977      3738352.59     10608488.23
      3738161.64     10608814.59
#Sta/Elev= 30
    4702  325.49    4712  324.91    4732  325.29    4782   323.6    4812  320.93
  4898.7  315.26  4910.8  315.43  4926.5  313.95  4979.4  312.38  4985.1  312.95
  4988.4  301.22  4991.1  300.72  4994.4  301.22  5006.6  303.46  5014.6  308.62
  5022.3  309.35  5028.1  311.21  5037.7  312.27  5043.8   315.5  5065.3  318.77
  5072.5  317.05    5081  316.44  5086.8  322.01  5095.7  323.13  5102.5  327.62
  5166.9  334.29  5182.6  335.41  5204.1  335.82  5211.5  336.95  5228.2  337.08
#Mann= 3 ,-1 , 0
    4702     .16       0  4988.4     .07       0  4994.4     .16       0
Bank Sta=4979.4,5037.7
XS Rating Curve= 0 ,0
Exp/Cntr=0.3,0.1

Type RM Length L Ch R = 1 ,28919   ,381,381,381
BEGIN DESCRIPTION:
MACK CREEK 58.0
END DESCRIPTION:
XS GIS Cut Line= 2
      3738043.56     10608092.42      3737963.71     10608783.32
#Sta/Elev= 30
  4617.4  326.53  4635.3   326.5  4675.6   322.9    4693  319.07    4698  323.37
  4705.8  319.62  4725.9  319.73    4736  321.16  4776.2  319.29  4796.4     321
  4826.6  319.65  4856.8  315.49  4870.7  315.83  4927.2  310.51  4977.6  310.59
  4997.7   307.6  5007.8  299.13  5014.8  298.97  5017.6  298.47  5020.8  298.97
  5027.9  309.12  5068.2  311.47  5078.2  316.56  5088.3  318.32  5108.4  321.67
  5132.2  322.81  5138.6  324.66  5158.7  327.21  5239.3  333.84  5312.9  336.09
#Mann= 3 ,-1 , 0
  4617.4     .16       0  5014.8     .07       0  5020.8     .16       0
Bank Sta=4997.7,5027.9
XS Rating Curve= 0 ,0
Exp/Cntr=0.3,0.1

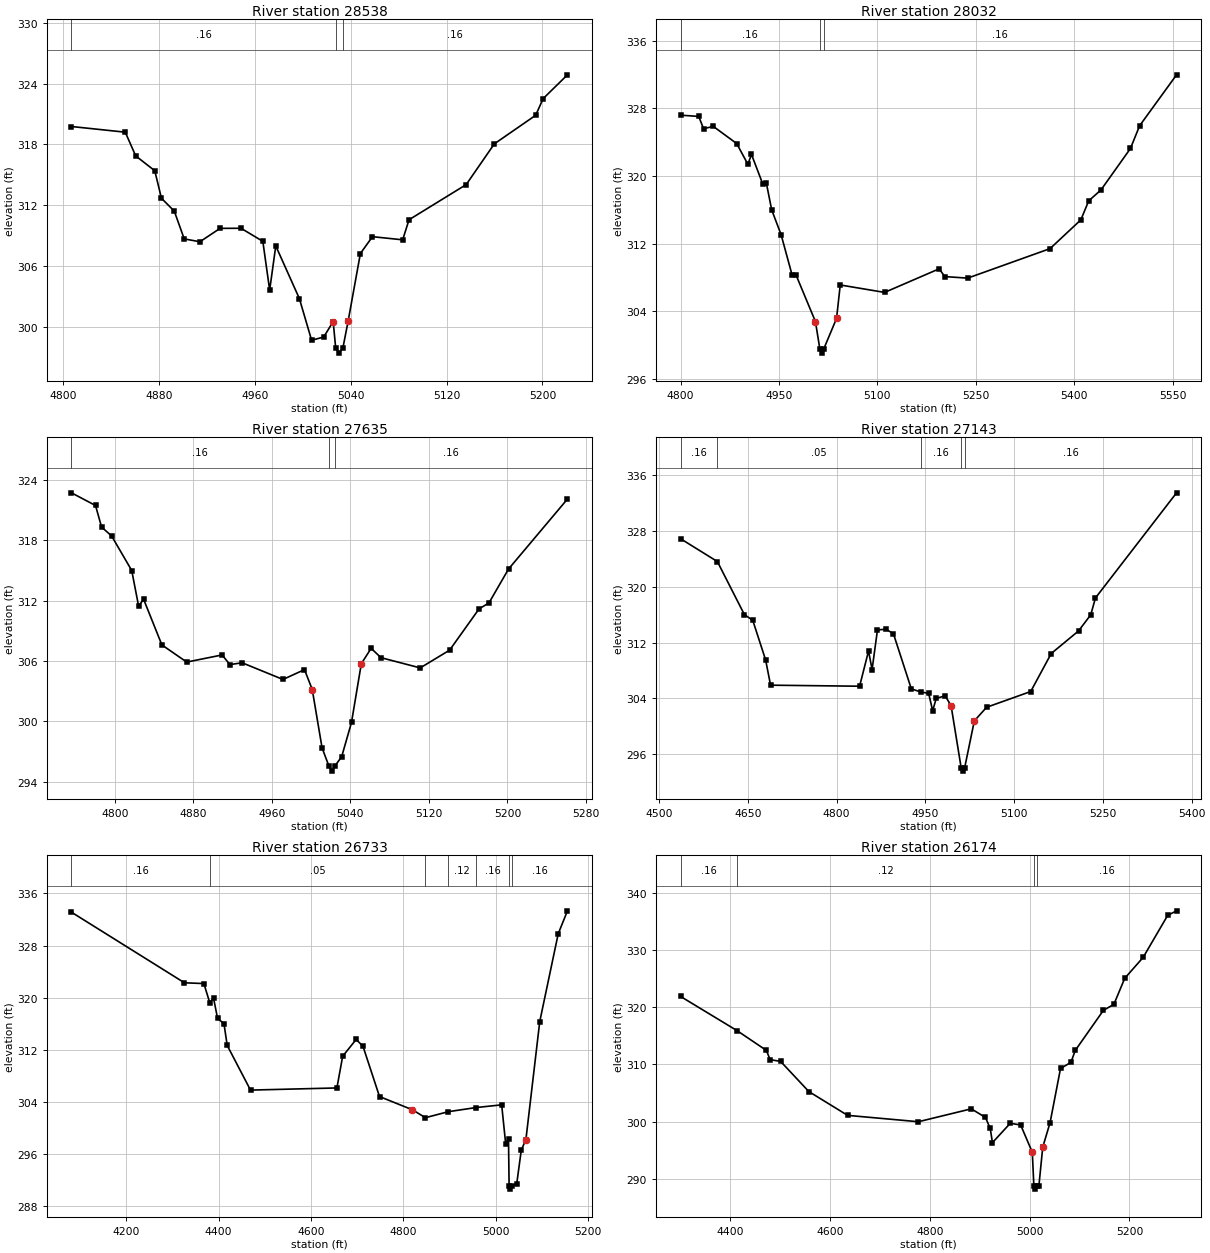
Type RM Length L Ch R = 1 ,28538   ,506,506,506
BEGIN DESCRIPTION:
MACK CREEK 57.0
END DESCRIPTION:
XS GIS Cut Line= 3
      3737749.61     10608260.18      3737699.61     10608389.36
      3737649.61     10608660.16
#Sta/Elev= 30
    4807  319.76  4851.9   319.2  4860.6  316.86  4876.5   315.4  4882.1  312.68
  4892.8  311.41  4901.1  308.67  4914.2  308.39    4931  309.71  4948.5  309.72
  4966.7  308.43  4972.4  303.62  4977.5  307.98  4997.2  302.78  5007.4  298.67
  5017.5  298.99  5025.4  300.51  5027.5   297.9  5030.2   297.4  5033.5   297.9
  5037.9  300.57  5048.1  307.23  5058.2  308.89  5083.4  308.58  5088.7  310.56
  5136.4  314.03  5159.9  318.05  5194.4  320.87  5200.6  322.51  5220.9  324.86
#Mann= 3 ,-1 , 0
    4807     .16       0  5027.5     .07       0  5033.5     .16       0
Bank Sta=5025.4,5037.9
XS Rating Curve= 0 ,0
Exp/Cntr=0.3,0.1

Type RM Length L Ch R = 1 ,28032   ,397,397,397
BEGIN DESCRIPTION:
MACK CREEK 56.0
END DESCRIPTION:
XS GIS Cut Line= 3
      3737480.68     10607995.32      3737315.73      10608333.9
      3737172.55     10608685.33
#Sta/Elev= 30
    4800   327.2  4827.7  327.05    4835   325.6  4849.9  325.87  4885.6  323.84
  4902.6  321.39  4908.1  322.56  4925.1   319.1  4930.7   319.2  4938.9     316
  4953.2  313.08  4970.2  308.24  4975.8  308.34  5005.6  302.79  5012.3  299.56
    5015  299.06  5018.3  299.56  5037.8  303.17  5043.4  307.12    5111  306.24
  5194.2  309.03  5202.8  308.11  5237.7  307.93  5363.3  311.42  5410.2  314.82
  5422.2  317.07  5440.9  318.36  5485.8  323.26  5499.8  325.95  5556.1  331.97
#Mann= 3 ,-1 , 0
    4800     .16       0  5012.3     .07       0  5018.3     .16       0
Bank Sta=5005.6,5037.8
XS Rating Curve= 0 ,0
Exp/Cntr=0.3,0.1

Type RM Length L Ch R = 1 ,27635   ,492,492,492
BEGIN DESCRIPTION:
MACK CREEK 55.0
END DESCRIPTION:
XS GIS Cut Line= 3
       3737099.6     10608060.24      3737049.61     10608289.36
      3737049.61     10608560.15
#Sta/Elev= 30
  4755.8  322.74  4780.3  321.48  4786.5  319.33  4796.7  318.45  4817.2  315.01
  4824.2  311.47  4829.3  312.15  4847.9  307.61  4873.2   305.9  4909.3  306.61
  4917.2  305.65  4929.7  305.83  4971.3  304.17  4993.2  305.15  5001.1  303.17
  5011.1  297.37  5018.1  295.55  5020.9  295.05  5024.1  295.55  5031.1  296.49
  5041.1   299.9  5051.1  305.74  5061.1  307.27  5071.1  306.34  5111.1  305.32
  5141.1  307.09  5171.1   311.2  5181.1  311.78  5201.1  315.16  5261.1  322.12
#Mann= 3 ,-1 , 0
  4755.8     .16       0  5018.1     .07       0  5024.1     .16       0
Bank Sta=5001.1,5051.1
XS Rating Curve= 0 ,0
Exp/Cntr=0.3,0.1

Type RM Length L Ch R = 1 ,27143   ,410,410,410
BEGIN DESCRIPTION:
MACK CREEK 54.0
END DESCRIPTION:
XS GIS Cut Line= 3
      3736899.64     10607910.15      3736649.61     10608289.36
      3736549.61     10608660.19
#Sta/Elev= 30
  4536.2  326.89  4598.4  323.62  4644.1  316.01  4658.2   315.2    4680   309.5
  4688.3   305.9  4838.8  305.75  4853.9   310.8  4859.9  308.14    4869  313.83
  4883.6  313.91    4896  313.27  4926.2  305.37  4942.1  304.93  4955.5  304.73
  4962.3  302.23  4968.3  304.01  4983.4  304.37  4993.4  302.97  5010.4  294.08
  5013.1  293.58  5016.4  294.08  5032.7  300.78  5053.4  302.73    5128  304.99
  5162.7  310.44  5208.8  313.67  5229.5  315.99  5237.4   318.4  5374.5  333.47
#Mann= 5 ,-1 , 0
  4536.2     .16       0  4598.4     .05       0  4942.1     .16       0
  5010.4     .07       0  5016.4     .16       0
Bank Sta=4993.4,5032.7
XS Rating Curve= 0 ,0
Exp/Cntr=0.3,0.1

Type RM Length L Ch R = 1 ,26733   ,559,559,559
BEGIN DESCRIPTION:
MACK CREEK 53.0
END DESCRIPTION:
XS GIS Cut Line= 3
      3736849.62     10607710.17      3736299.61     10608489.36
      3736299.61      10608610.2
#Sta/Elev= 30
  4081.1  333.11  4325.9  322.29    4368  322.17  4380.6  319.26  4388.9  319.95
  4397.6  316.85  4411.6     316  4418.5  312.69    4469  305.84  4656.2  306.17
  4668.7  311.03    4698  313.61  4712.8  312.54  4748.5  304.85  4819.9  302.82
    4848  301.61  4897.6  302.53  4957.2  303.16  5013.2  303.58  5021.8  297.65
    5028  298.33  5029.3  291.16  5032.1  290.66  5035.3  291.16  5045.7  291.42
  5055.7  296.65  5065.7  298.26  5095.7  316.35  5135.7   329.8  5155.7  333.32
#Mann= 7 ,-1 , 0
  4081.1     .16       0  4380.6     .05       0    4848     .16       0
  4897.6     .12       0  4957.2     .16       0  5029.3     .07       0
  5035.3     .16       0
Bank Sta=4819.9,5065.7
XS Rating Curve= 0 ,0
Exp/Cntr=0.3,0.1

Type RM Length L Ch R = 1 ,26174   ,336,336,336
BEGIN DESCRIPTION:
MACK CREEK 52.0
END DESCRIPTION:
XS GIS Cut Line= 3
      3736482.41     10607669.82      3736026.67     10608090.84
      3735809.66     10608394.65
#Sta/Elev= 30
  4300.5  321.87  4414.1  315.88  4472.5  312.45  4479.9  310.84  4500.9  310.54
  4557.6  305.27  4635.2  301.12    4777  300.01    4883  302.26  4911.4  300.76
    4921  298.83  4925.4  296.36    4961  299.73  4981.9  299.45  5005.3  294.67
  5008.4  288.75  5011.2  288.25  5014.4  288.75  5018.5  288.85  5026.2  295.58
  5040.9  299.86  5061.8   309.3  5082.7  310.37  5091.3  312.45  5147.8  319.45
  5168.7  320.49  5190.5  325.04  5227.4  328.69  5276.5  336.01  5294.3  336.81
#Mann= 4 ,-1 , 0
  4300.5     .16       0  4414.1     .12       0  5008.4     .07       0
  5014.4     .16       0
Bank Sta=5005.3,5026.2
XS Rating Curve= 0 ,0
Exp/Cntr=0.3,0.1

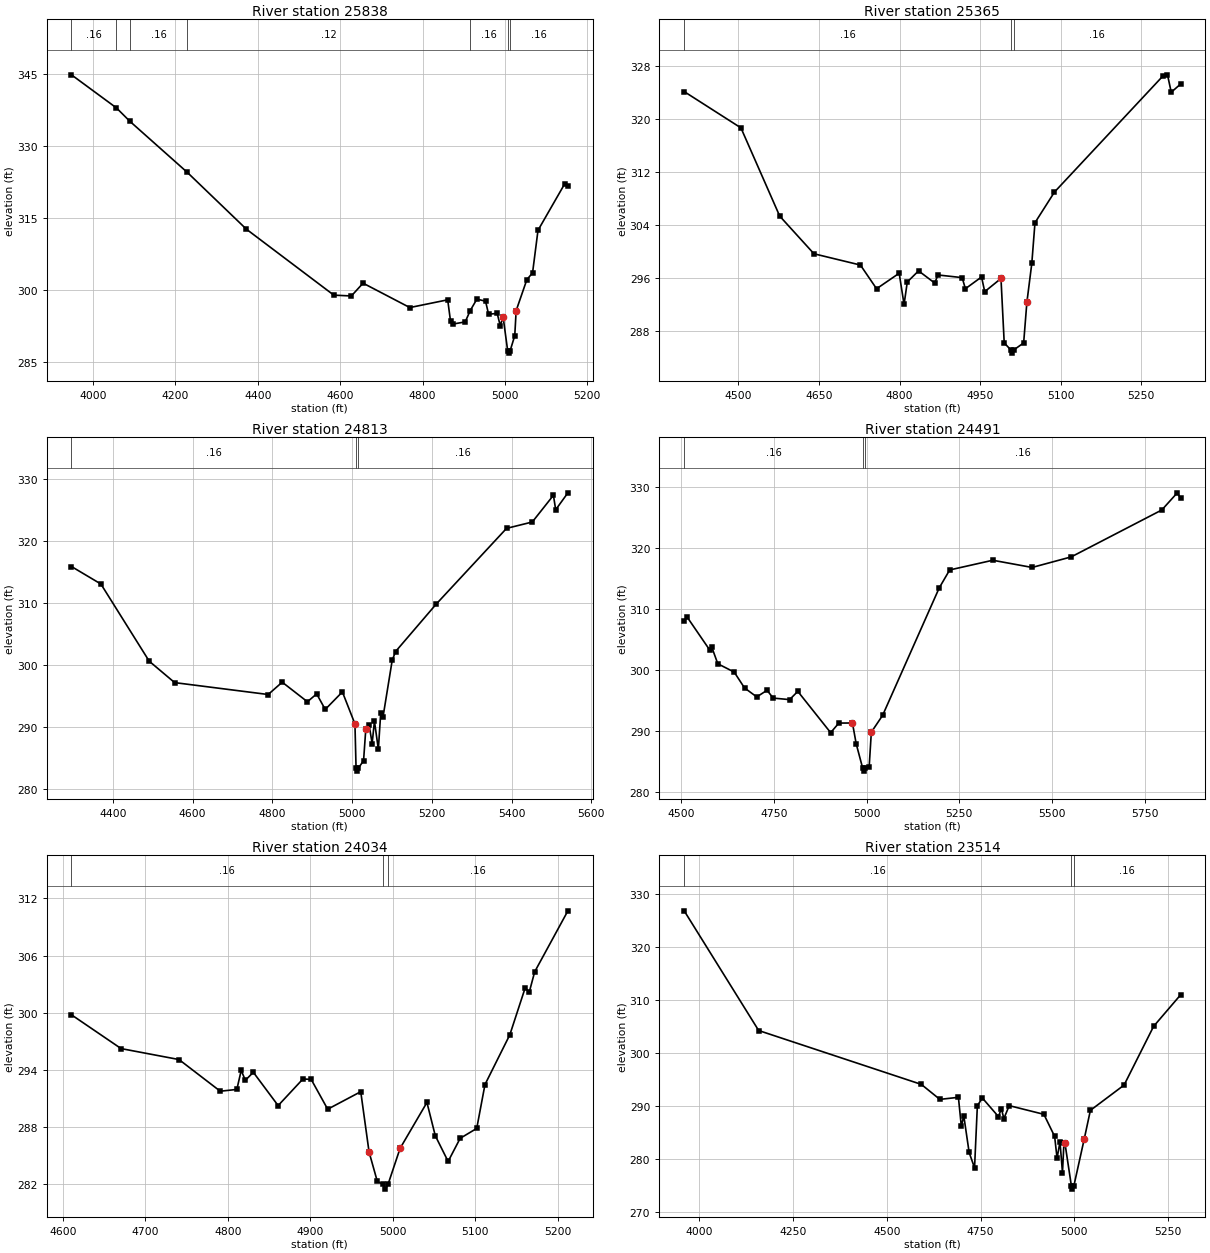
Type RM Length L Ch R = 1 ,25838   ,473,473,473
BEGIN DESCRIPTION:
MACK CREEK 51.0
END DESCRIPTION:
XS GIS Cut Line= 3
      3736499.62     10607260.17      3735699.61     10607989.36
      3735599.62     10608060.18
#Sta/Elev= 30
  3947.9  344.78  4057.1   337.9  4089.4  335.14  4229.1   324.5  4372.6  312.69
  4584.7  298.99  4627.3  298.82  4655.7  301.48  4769.2  296.41  4861.1  298.02
    4868  293.57  4875.2     293  4903.6  293.43  4915.8  295.78    4932  298.17
    4953  297.73  4960.4  295.02  4981.3   295.2  4988.7  292.62  4995.5  294.53
  5006.7  287.44  5009.5  286.94  5012.7  287.44  5023.9  290.57  5027.3  295.77
  5053.3  302.22  5067.1  303.62  5080.3  312.46  5145.5  322.18  5152.9  321.67
#Mann= 7 ,-1 , 0
  3947.9     .16       0  4057.1     .12       0  4089.4     .16       0
  4229.1     .12       0  4915.8     .16       0  5006.7     .07       0
  5012.7     .16       0
Bank Sta=4995.5,5027.3
XS Rating Curve= 0 ,0
Exp/Cntr=0.3,0.1

Type RM Length L Ch R = 1 ,25365   ,552,552,552
BEGIN DESCRIPTION:
MACK CREEK 50.0
END DESCRIPTION:
XS GIS Cut Line= 3
      3736030.99     10607335.64      3735592.64     10607626.43
      3735375.63     10607960.63
#Sta/Elev= 30
  4398.9  324.12  4504.6  318.64  4576.8  305.32  4640.6  299.63  4727.1  297.93
  4757.2  294.35  4799.3  296.69  4808.4  291.98  4814.4  295.37  4835.4  297.05
  4865.5  295.21  4871.5  296.43  4916.6  296.03  4922.6  294.35  4952.7  296.13
  4958.6  293.91  4988.9   295.9  4994.9  286.18    5007  285.13  5009.8  284.63
    5013  285.13  5031.1  286.17  5037.1  292.28  5046.3  298.18  5052.2  304.32
  5088.5  308.95  5290.8   326.5    5299  326.65    5306  324.02  5323.4  325.26
#Mann= 3 ,-1 , 0
  4398.9     .16       0    5007     .07       0    5013     .16       0
Bank Sta=4988.9,5037.1
XS Rating Curve= 0 ,0
Exp/Cntr=0.3,0.1

Type RM Length L Ch R = 1 ,24813   ,322,322,322
BEGIN DESCRIPTION:
MACK CREEK 49.0
END DESCRIPTION:
XS GIS Cut Line= 3
      3735883.86     10607040.29      3735425.51     10607418.78
       3735099.1     10607981.31
#Sta/Elev= 30
  4296.2  315.87  4369.9  313.05  4491.1  300.59  4554.9  297.13  4789.4  295.21
  4824.6   297.2  4887.8  294.04    4911  295.31  4932.5   292.8  4975.5  295.63
    5007  290.46  5009.8  283.34  5012.6  282.84  5015.8  283.34  5028.6  284.53
  5034.3   289.7  5042.6  290.29  5050.1  287.29  5055.9   290.9  5065.7  286.37
  5071.6  292.19  5077.4  291.59  5100.4  300.72  5108.9  302.15  5210.7   309.8
  5387.1  322.03  5451.7  323.06  5504.7  327.37  5510.4  325.04    5541  327.77
#Mann= 3 ,-1 , 0
  4296.2     .16       0  5009.8     .07       0  5015.8     .16       0
Bank Sta=5007,5034.3
XS Rating Curve= 0 ,0
Exp/Cntr=0.3,0.1

Type RM Length L Ch R = 1 ,24491   ,457,457,457
BEGIN DESCRIPTION:
MACK CREEK 48.0
END DESCRIPTION:
XS GIS Cut Line= 3
      3735803.94     10607022.97      3735415.09     10607224.34
       3734529.7     10607387.53
#Sta/Elev= 30
  4508.3  308.11    4516   308.7  4576.7  303.32  4582.4   303.8  4598.9  301.03
  4643.1  299.67  4670.9  297.08  4703.9   295.6  4731.7  296.69  4748.2  295.41
  4792.5  295.16  4814.6  296.51  4903.1  289.75  4925.3  291.32  4961.9  291.33
  4972.1   287.9  4989.4  283.95  4992.2  283.45  4995.4  283.95  5006.9  284.09
  5012.8  289.83  5043.3  292.59  5195.8  313.45    5224  316.39  5340.2  317.98
  5446.2   316.8  5551.7  318.53  5795.8  326.21  5837.6  329.02  5846.5  328.12
#Mann= 3 ,-1 , 0
  4508.3     .16       0  4989.4     .07       0  4995.4     .16       0
Bank Sta=4961.9,5012.8
XS Rating Curve= 0 ,0
Exp/Cntr=0.3,0.1

Type RM Length L Ch R = 1 ,24034   ,520,520,520
BEGIN DESCRIPTION:
MACK CREEK 47.0
END DESCRIPTION:
XS GIS Cut Line= 3
      3735699.63     10606860.19      3735299.61     10606889.36
      3735099.57     10606910.19
#Sta/Elev= 30
  4610.3  299.77  4670.5  296.22  4740.7  295.07  4790.8  291.74  4810.9  291.93
  4816.2  293.93  4821.2  292.89  4830.9  293.73    4861  290.23  4891.1  293.03
  4901.1  292.98  4921.1  289.85  4961.2  291.69  4971.3  285.35  4981.3  282.26
  4988.3  281.95  4991.1  281.45  4994.3  281.95  5008.9  285.73  5041.5  290.56
  5051.6  287.07  5067.2  284.36  5081.8  286.79  5101.9  287.83  5111.9  292.44
  5142.1  297.68  5160.7  302.61  5165.7  302.18  5172.2  304.29  5212.5   310.7
#Mann= 3 ,-1 , 0
  4610.3     .16       0  4988.3     .07       0  4994.3     .16       0
Bank Sta=4971.3,5008.9
XS Rating Curve= 0 ,0
Exp/Cntr=0.3,0.1

Type RM Length L Ch R = 1 ,23514   ,464,464,464
BEGIN DESCRIPTION:
MACK CREEK 46.0
END DESCRIPTION:
XS GIS Cut Line= 3
      3735699.59     10605760.21      3735049.61     10606539.36
      3734749.62     10606610.19
#Sta/Elev= 30
  3960.2  326.88  4158.7   304.3  4592.1  294.14  4641.6  291.31    4691   291.7
  4698.8   286.2  4705.3  288.22  4719.6   281.3    4734  278.39  4741.5  290.12
  4754.8  291.57  4797.7  288.06  4805.5  289.57  4812.1  287.68  4826.4  290.13
  4918.8  288.49  4947.4  284.33  4953.9  280.22  4961.7  283.29  4968.3   277.5
  4972.2  283.05  4974.9  283.05  4992.3  274.88    4995  274.38  4998.3  274.88
  5026.2   283.8  5042.7  289.24  5132.5  294.01  5211.2  305.09  5283.1  311.03
#Mann= 3 ,-1 , 0
  3960.2     .16       0  4992.3     .07       0  4998.3     .16       0
Bank Sta=4974.9,5026.2
XS Rating Curve= 0 ,0
Exp/Cntr=0.3,0.1

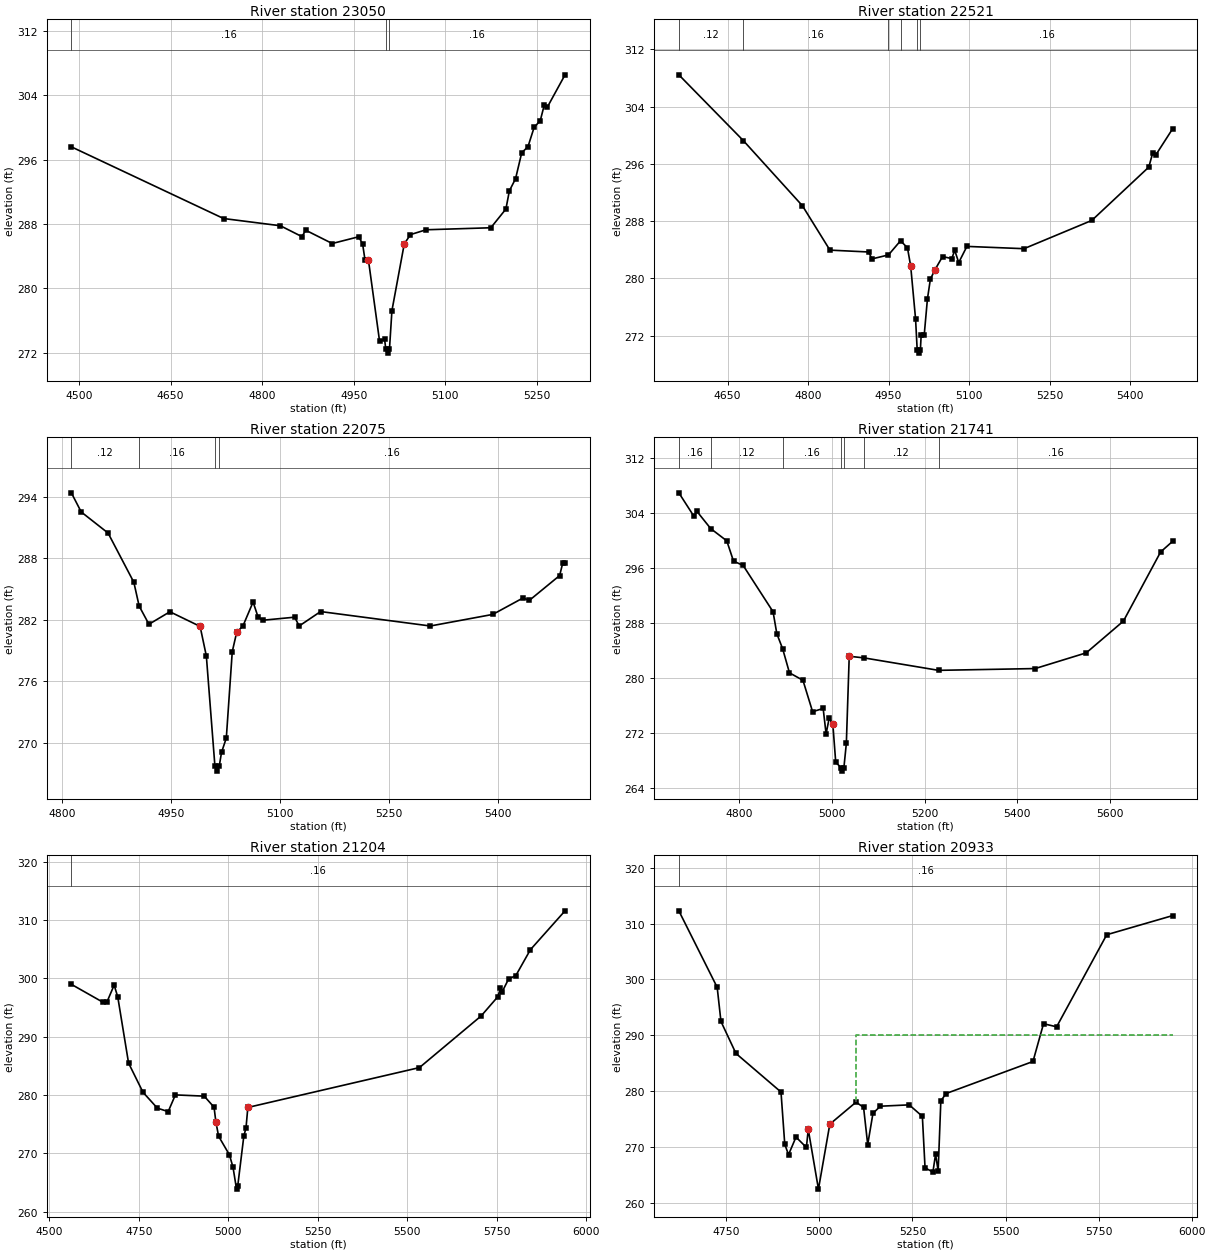
Type RM Length L Ch R = 1 ,23050   ,529,529,529
BEGIN DESCRIPTION:
MACK CREEK 45.0
END DESCRIPTION:
XS GIS Cut Line= 3
      3735099.59     10605860.21      3734799.61     10606239.36
      3734749.61     10606560.21
#Sta/Elev= 30
  4487.6  297.61  4736.8  288.69  4829.8  287.79    4865  286.44  4871.4  287.23
  4914.7  285.58    4958  286.42  4964.4  285.54  4968.4   283.5    4974   283.5
  4992.2  273.41  5000.4  273.65  5002.4  272.44  5005.2  271.94  5008.4  272.44
  5012.4  277.22  5032.6  285.53  5042.8  286.69  5068.3  287.29  5174.3  287.54
    5199  289.87  5204.7  292.14  5214.8  293.64  5224.9  296.88  5235.1  297.62
  5245.2  300.03  5255.3  300.88  5261.8  302.81  5266.9  302.56  5295.8  306.57
#Mann= 3 ,-1 , 0
  4487.6     .16       0  5002.4     .07       0  5008.4     .16       0
Bank Sta=4974,5032.6
XS Rating Curve= 0 ,0
Exp/Cntr=0.3,0.1

Type RM Length L Ch R = 1 ,22521   ,446,446,446
BEGIN DESCRIPTION:
MACK CREEK 44.0
END DESCRIPTION:
XS GIS Cut Line= 3
      3734799.63     10605660.16      3734549.61     10606039.36
      3734349.63     10606460.15
#Sta/Elev= 30
  4559.1  308.43  4679.3  299.24  4789.5  290.13  4840.7  283.94  4912.9  283.68
  4918.9  282.71  4949.8  283.27  4972.3  285.25  4985.2  284.26  4991.2  281.72
  5000.3  274.33  5003.3  270.05    5006  269.55  5009.3  270.05  5010.8  272.15
  5016.5  272.15  5022.4  277.11  5027.9  279.88  5036.4  281.19  5050.6  283.04
  5067.8  282.76  5073.3  283.91  5080.7   282.2    5096  284.46  5202.4  284.14
  5328.8  288.09    5435  295.54  5442.4  297.55  5447.9  297.22  5479.2  300.87
#Mann= 6 ,-1 , 0
  4559.1     .12       0  4679.3     .16       0  4949.8     .05       0
  4972.3     .16       0  5003.3     .07       0  5009.3     .16       0
Bank Sta=4991.2,5036.4
XS Rating Curve= 0 ,0
Exp/Cntr=0.3,0.1

Type RM Length L Ch R = 1 ,22075   ,334,334,334
BEGIN DESCRIPTION:
MACK CREEK 43.0
END DESCRIPTION:
XS GIS Cut Line= 3
      3734399.63     10605560.17      3734299.61     10605689.36
      3733999.61     10606110.19
#Sta/Elev= 30
  4812.6   294.4  4826.2  292.53  4863.2  290.47  4898.7  285.66    4906  283.34
  4919.5  281.56  4948.4  282.78    4990  281.35  4998.6  278.46  5010.4  267.71
  5013.1  267.21  5016.4  267.71  5019.5  269.04  5026.1  270.44  5034.3  278.88
  5040.4  280.77    5049  281.39    5063  283.73  5069.9  282.26  5076.1  281.95
  5120.3  282.25  5126.5  281.39    5156   282.8  5307.2  281.39  5393.2  282.52
    5435  284.13  5443.6  283.89  5485.4  286.32  5489.7  287.56  5492.8  287.56
#Mann= 4 ,-1 , 0
  4812.6     .12       0    4906     .16       0  5010.4     .07       0
  5016.4     .16       0
Bank Sta=4990,5040.4
XS Rating Curve= 0 ,0
Exp/Cntr=0.3,0.1

Type RM Length L Ch R = 1 ,21741   ,537,537,537
BEGIN DESCRIPTION:
MACK CREEK 42.0
END DESCRIPTION:
XS GIS Cut Line= 3
       3734276.2      10605241.7      3733949.82     10605672.25
      3733918.61     10606195.85
#Sta/Elev= 30
    4670  306.94  4702.6  303.52  4708.9  304.25  4738.8  301.73  4773.4  299.95
  4787.9     297  4808.7  296.37  4873.2  289.63  4881.4  286.42    4894  284.22
  4908.6  280.74  4937.7  279.65  4958.5  275.08  4981.3  275.55  4987.6  271.85
  4994.4  274.19  5002.2  273.22  5008.4  267.71    5020  266.93  5022.7  266.43
    5026  266.93  5031.3  270.48  5037.5  283.15  5069.7  282.91  5230.1   281.1
  5438.6  281.36  5548.8  283.65  5628.9  288.27  5709.1  298.33  5734.8  299.87
#Mann= 7 ,-1 , 0
    4670     .16       0  4738.8     .12       0    4894     .16       0
    5020     .07       0    5026     .16       0  5069.7     .12       0
  5230.1     .16       0
Bank Sta=5002.2,5037.5
XS Rating Curve= 0 ,0
Exp/Cntr=0.3,0.1

Type RM Length L Ch R = 1 ,21204   ,271,271,271
BEGIN DESCRIPTION:
MACK CREEK 41.0
END DESCRIPTION:
XS GIS Cut Line= 3
      3733790.09     10604981.31      3733717.18     10605620.17
      3733845.58     10606345.49
#Sta/Elev= 30
  4561.2  298.97  4650.7  295.86  4660.7  295.95  4680.8  298.84  4690.9  296.81
  4721.1  285.48  4761.4  280.48  4801.6  277.76  4831.8  277.17  4851.9  280.03
  4932.5  279.82    4960  277.92    4965  275.44  4972.7  272.95  5002.9  269.77
    5013  267.63  5022.8  263.89  5026.1  264.39  5043.2  272.98  5049.3  274.39
  5054.4  277.88    5534  284.71  5706.3  293.55  5752.6  296.82  5760.4  298.28
  5765.5  297.74  5783.1  299.88  5803.4  300.48    5844   304.9  5940.8  311.56
#Mann= 1 ,-1 , 0
  4561.2     .16       0
Bank Sta=4965,5054.4
XS Rating Curve= 0 ,0
Exp/Cntr=0.3,0.1

Type RM Length L Ch R = 1 ,20933   ,513,513,513
BEGIN DESCRIPTION:
MACK CREEK 40.0
END DESCRIPTION:
XS GIS Cut Line= 3
      3733578.28     10604897.99      3733512.32     10605415.31
      3732953.95     10605994.48
#Sta/Elev= 30
  4622.6  312.29  4725.6  298.59  4735.7  292.48    4776  286.75    4897  279.84
  4907.1  270.49  4917.2  268.62  4937.3  271.77  4965.2  269.92  4970.2  273.14
  4997.6  262.45  5028.1  274.08  5098.6  278.03  5118.8  277.09  5129.9  270.43
    5144  276.02  5163.7   277.3  5241.4  277.54  5276.7  275.48  5283.9  266.26
    5305  265.51  5312.2   268.7  5319.1   265.7  5326.3  278.26  5340.5  279.57
  5573.8  285.31  5602.1  292.07  5637.3  291.52  5771.9  308.01  5948.6  311.43
#Mann= 1 ,-1 , 0
  4622.6     .16       0
#XS Ineff= 2 , 0
       0                 5097.95       0     290
Permanent Ineff=
       F       F
Bank Sta=4970.2,5028.1
XS Rating Curve= 0 ,0
Exp/Cntr=0.3,0.1