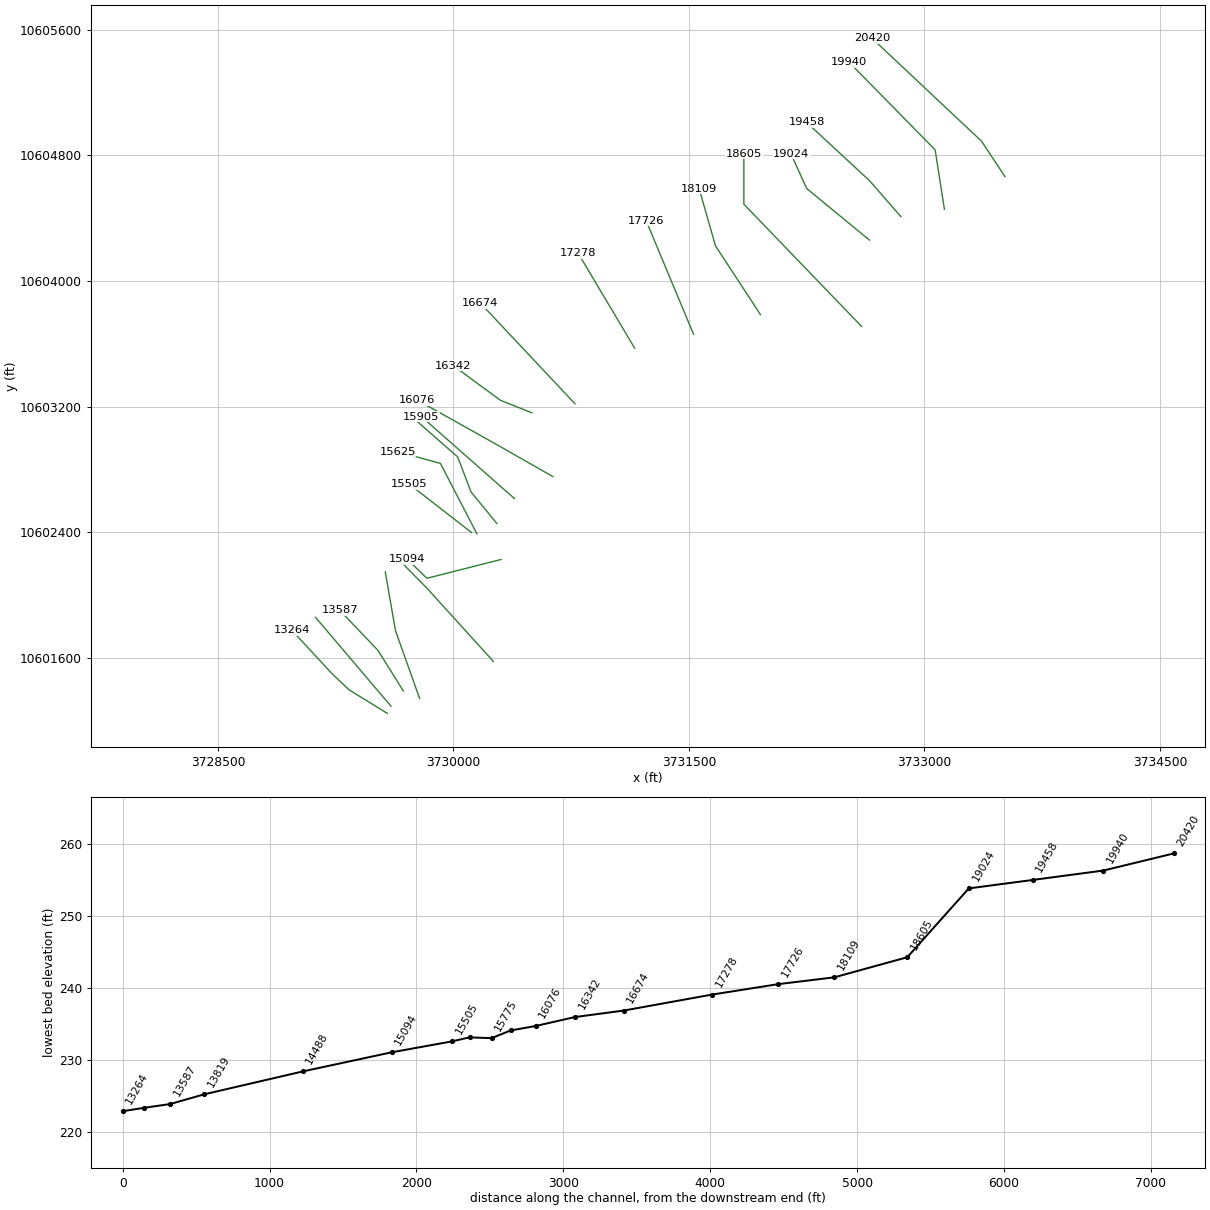
HEC-RAS study MACK CREEK.prj: MACK CREEK Base Level Engineering

--- MACK CREEK.g01 (geometry) --- (continued)

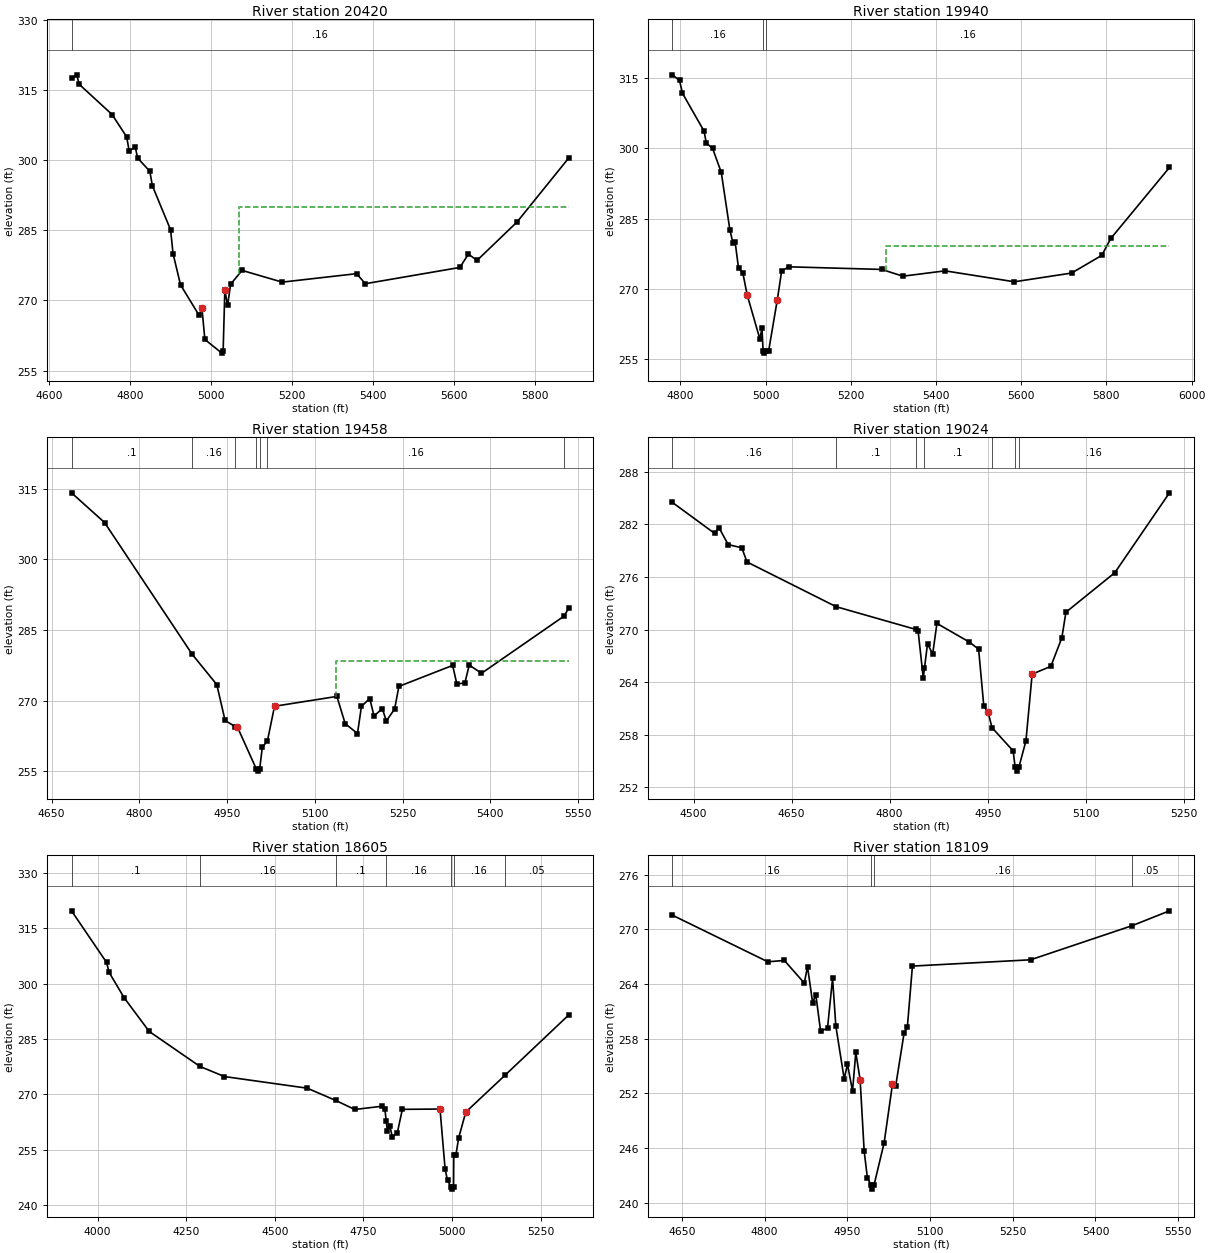
Type RM Length L Ch R = 1 ,20420   ,480,480,480
BEGIN DESCRIPTION:
Mapping XS 8b3f9f13
END DESCRIPTION:
XS GIS Cut Line= 3
      3733512.29     10604665.35      3733363.01       10604891.
      3732666.23     10605546.19
#Sta/Elev= 30
  4655.8  317.48  4668.7  318.26  4674.7  316.24  4755.9  309.77    4792  304.98
    4798     302  4813.1  302.82  4819.1  300.44  4849.2  297.62  4855.2  294.57
  4900.4  285.09  4906.4  280.02  4924.9  273.33  4970.8   266.8  4977.7  268.39
    4985  261.64  5026.9  258.72  5030.1  259.22  5034.3  272.21  5041.2  268.92
  5048.5  273.45  5076.8  276.42  5175.9  273.91  5359.6  275.72  5381.1  273.57
  5614.5  277.05  5635.6   279.9    5657  278.56  5755.7  286.78  5882.8  300.42
#Mann= 1 ,-1 , 0
  4655.8     .16       0
#XS Ineff= 2 , 0
       0                 5068.52       0     290
Permanent Ineff=
       F       F
Bank Sta=4977.7,5034.3
XS Rating Curve= 0 ,0
Exp/Cntr=0.3,0.1

Type RM Length L Ch R = 1 ,19940   ,482,482,482
BEGIN DESCRIPTION:
Mapping XS c49f60c5
END DESCRIPTION:
XS GIS Cut Line= 3
       3733126.9     10604456.97      3733067.87     10604835.45
      3732519.27     10605394.47
#Sta/Elev= 30
  4781.6  315.63  4798.3  314.43  4805.1  311.71  4855.7  303.65  4861.1   301.1
  4875.9  299.95  4896.2  294.84  4916.4  282.59  4923.9   279.7  4928.9  279.91
  4936.7  274.43  4946.8  273.43  4956.9  268.77  4986.7  259.37  4991.7  261.62
  4994.4  256.84  4997.1  256.34  5000.4  256.84  5007.5  256.89  5027.8  267.74
  5037.9  273.84  5054.6  274.73  5272.8  274.17  5322.4  272.73  5421.4  273.87
    5584  271.54  5718.3   273.4    5789  277.16  5810.3  280.77  5947.9  295.89
#Mann= 3 ,-1 , 0
  4781.6     .16       0  4994.4     .07       0  5000.4     .16       0
#XS Ineff= 2 , 0
                          5281.7          279.09
Permanent Ineff=
       F       F
Bank Sta=4956.9,5027.8
XS Rating Curve= 0 ,0
Exp/Cntr=0.3,0.1

Type RM Length L Ch R = 1 ,19458   ,434,434,434
BEGIN DESCRIPTION:
MACK CREEK 37.0
END DESCRIPTION:
XS GIS Cut Line= 3
      3732849.62     10604410.18      3732649.61     10604639.36
      3732249.63     10605010.17
#Sta/Elev= 30
  4684.1  314.15  4740.6  307.84  4890.4  279.84  4932.4  273.42  4946.6  265.79
  4963.7   264.5  4967.5  264.45  4999.8  255.53  5002.5  255.03  5005.8  255.53
  5010.2  260.07  5019.1  261.51  5031.1  268.81  5137.7   270.9  5151.9  265.12
  5172.9  263.02  5179.7  268.79  5193.9  270.45  5201.2  266.75  5215.4  268.31
  5222.2  265.69  5236.4  268.21  5243.7  273.03  5335.6  277.49  5342.8  273.51
  5356.6   273.8  5363.9  277.57  5384.9  275.81  5525.9  287.95  5533.7  289.58
#Mann= 7 ,-1 , 0
  4684.1      .1       0  4890.4     .16       0  4963.7      .1       0
  4999.8     .07       0  5005.8      .1       0  5019.1     .16       0
  5525.9     .05       0
#XS Ineff= 2 , 0
                         5136.36          278.47
Permanent Ineff=
       F       F
Bank Sta=4967.5,5031.1
XS Rating Curve= 0 ,0
Exp/Cntr=0.3,0.1

Type RM Length L Ch R = 1 ,19024   ,419,419,419
BEGIN DESCRIPTION:
MACK CREEK 36.0
END DESCRIPTION:
XS GIS Cut Line= 3
      3732649.64     10604260.16      3732249.61     10604589.36
       3732149.6      10604810.2
#Sta/Elev= 30
  4467.7  284.51  4532.3  280.98  4538.8  281.65  4553.1   279.7  4573.9  279.34
  4581.8  277.72  4718.2  272.62  4840.4  270.02  4843.7  269.79  4851.5  264.49
  4853.3  265.57    4858  268.39  4865.9  267.22  4872.4  270.71  4921.9  268.59
  4936.2  267.77  4944.1   261.3  4950.6   260.6  4956.7  258.82    4989  256.17
    4992  254.36  4994.8  253.86    4998  254.36  5008.6  257.31  5018.1  264.93
  5046.7  265.81  5063.5  269.06  5069.8  271.99  5144.6   276.5  5228.2  285.61
#Mann= 7 ,-1 , 0
  4467.7     .16       0  4718.2      .1       0  4840.4     .16       0
  4853.3      .1       0  4956.7     .16       0    4992     .07       0
    4998     .16       0
Bank Sta=4950.6,5018.1
XS Rating Curve= 0 ,0
Exp/Cntr=0.3,0.1

Type RM Length L Ch R = 1 ,18605   ,496,496,496
BEGIN DESCRIPTION:
MACK CREEK 35.0
END DESCRIPTION:
XS GIS Cut Line= 3
      3732599.58     10603710.22      3731849.61     10604489.36
      3731849.61     10604810.22
#Sta/Elev= 30
  3926.6  319.75  4025.5  305.76  4032.7  303.06  4075.1  296.18  4145.9  287.04
    4289  277.56  4357.9  274.82  4591.5  271.67  4671.7  268.36  4725.8  265.89
  4803.4  266.78  4810.7  266.01  4814.5  262.79  4817.6  260.16  4824.8  261.46
  4831.7  258.37  4845.9  259.63    4860  265.93  4966.3  266.01  4980.5  249.88
  4987.4  246.65  4998.5   244.8  5001.3   244.3  5004.5   244.8  5005.1  253.52
    5011  253.52  5018.9  258.18  5038.9  265.18    5149  275.11  5328.9  291.47
#Mann= 7 ,-1 , 0
  3926.6      .1       0    4289     .16       0  4671.7      .1       0
  4814.5     .16       0  4998.5     .07       0  5004.5     .16       0
    5149     .05       0
Bank Sta=4966.3,5038.9
XS Rating Curve= 0 ,0
Exp/Cntr=0.3,0.1

Type RM Length L Ch R = 1 ,18109   ,383,383,383
BEGIN DESCRIPTION:
MACK CREEK 34.0
END DESCRIPTION:
XS GIS Cut Line= 3
      3731955.51     10603785.25      3731669.03     10604223.65
      3731565.29     10604586.72
#Sta/Elev= 30
  4632.9  271.55    4806  266.44  4835.8  266.59    4872  264.11  4877.9   265.9
  4887.1  261.97    4893   262.8  4901.6  258.82  4914.1  259.16  4923.3  264.63
  4929.2   259.4  4944.4  253.58  4950.3  255.22  4959.5  252.26  4965.4   256.5
  4973.3  253.48  4980.6  245.67  4986.5  242.72  4992.7  242.01  4995.4  241.51
  4998.7  242.01  5016.8  246.59  5031.9  253.01  5037.8  252.84    5053  258.63
  5058.9  259.26  5068.1  265.97  5282.4  266.66  5466.9  270.41  5534.2  272.03
#Mann= 4 ,-1 , 0
  4632.9     .16       0  4992.7     .07       0  4998.7     .16       0
  5466.9     .05       0
Bank Sta=4973.3,5031.9
XS Rating Curve= 0 ,0
Exp/Cntr=0.3,0.1

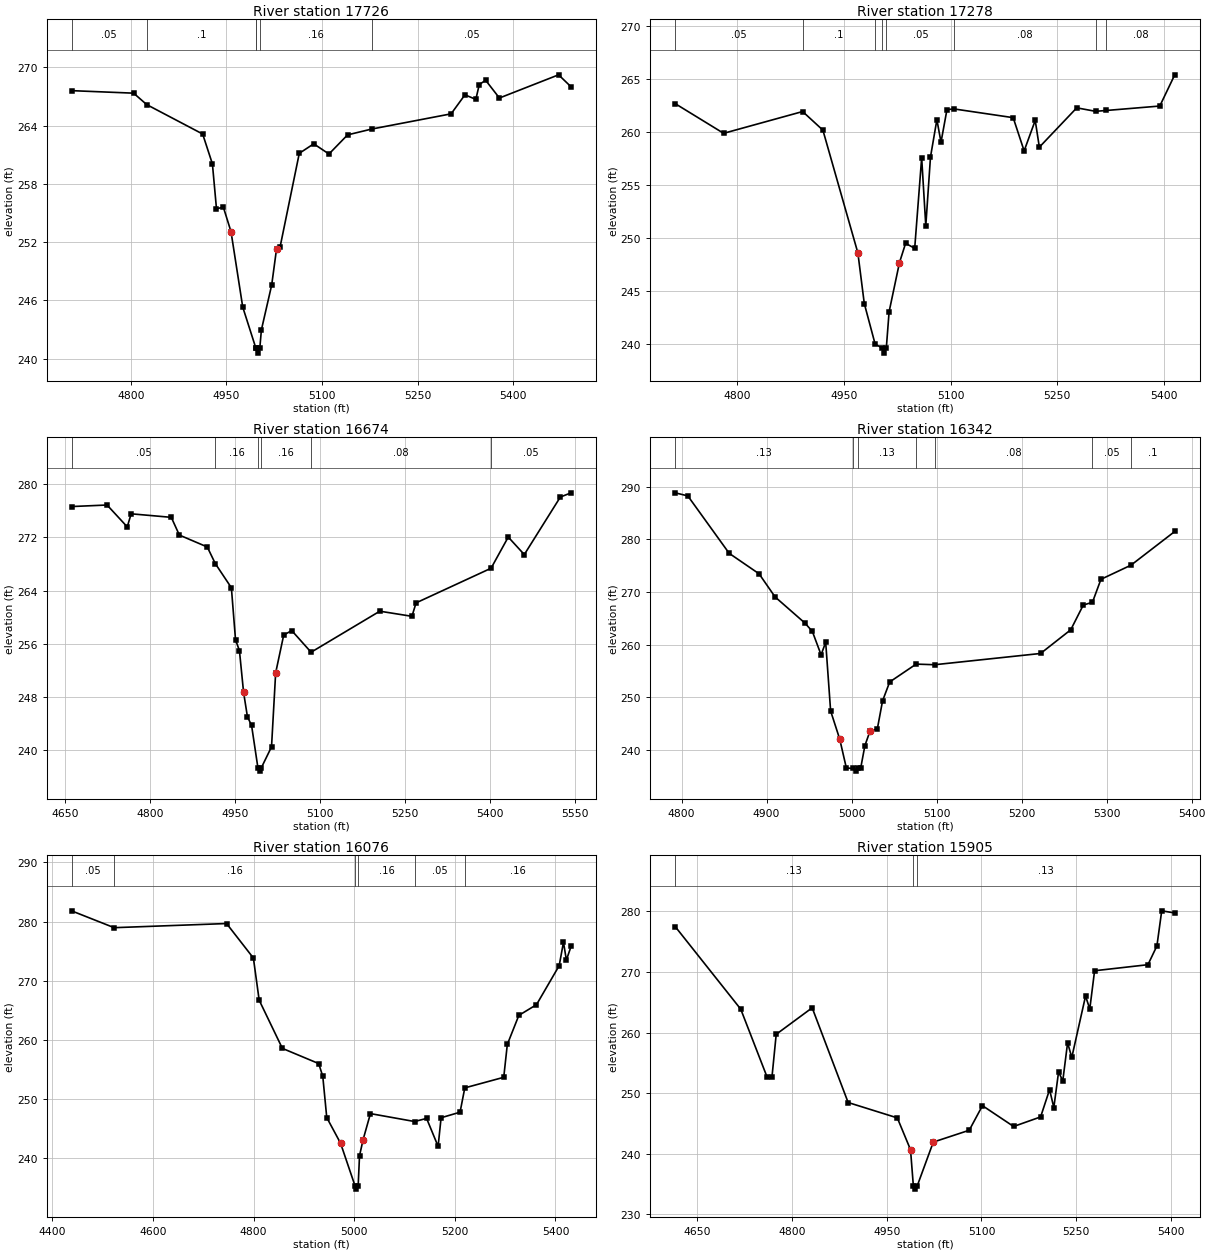
Type RM Length L Ch R = 1 ,17726   ,448,448,448
BEGIN DESCRIPTION:
Mapping XS 393b6878
END DESCRIPTION:
XS GIS Cut Line= 2
       3731529.4     10603660.17      3731227.34     10604384.08
#Sta/Elev= 30
  4706.7  267.61  4804.2  267.35  4824.8  266.17  4912.6  263.14  4927.9  260.06
  4934.3  255.44  4945.1   255.6  4957.1  253.08  4975.5  245.31    4996   241.1
  4996.3  241.06    4999  240.56  5002.3  241.06  5004.8  242.95    5021  247.59
  5028.6   251.3    5034  251.45  5064.3  261.15    5087  262.13  5110.9  261.08
  5140.1  263.05  5177.8  263.65  5302.7  265.22  5324.4  267.18  5341.5  266.71
  5346.9  268.24  5356.9  268.68  5378.5  266.85  5471.4  269.24  5491.1     268
#Mann= 6 ,-1 , 0
  4706.7     .05       0  4824.8      .1       0    4996     .16       0
  4996.3     .07       0  5002.3     .16       0  5177.8     .05       0
Bank Sta=4957.1,5028.6
XS Rating Curve= 0 ,0
Exp/Cntr=0.3,0.1

Type RM Length L Ch R = 1 ,17278   ,604,604,604
BEGIN DESCRIPTION:
Mapping XS e54ea61c
END DESCRIPTION:
XS GIS Cut Line= 2
      3731154.42      10603571.6      3730795.23     10604175.45
#Sta/Elev= 30
  4712.5  262.71  4780.7   259.9  4891.8  261.96  4920.3   260.2  4969.5  248.59
  4978.5  243.81  4993.8  239.96  5003.5  239.62  5006.3  239.12  5009.5  239.62
  5013.4  243.03    5028  247.68  5036.6   249.5  5049.4  249.03  5059.2  257.59
    5065  251.16  5071.6  257.66  5080.6  261.19  5086.4  259.06  5094.8  262.15
  5105.3   262.2  5187.9  261.38  5203.3  258.24  5218.9  261.12  5224.7  258.59
  5277.3  262.31  5303.7  261.98  5318.9  262.06  5394.1  262.48  5415.1  265.43
#Mann= 8 ,-1 , 0
  4712.5     .05       0  4891.8      .1       0  4993.8     .05       0
  5003.5     .04       0  5009.5     .05       0  5105.3     .08       0
  5303.7     .05       0  5318.9     .08       0
Bank Sta=4969.5,5028
XS Rating Curve= 0 ,0
Exp/Cntr=0.3,0.1

Type RM Length L Ch R = 1 ,16674   ,332,332,332
BEGIN DESCRIPTION:
MACK CREEK 31.0
END DESCRIPTION:
XS GIS Cut Line= 2
      3730774.94      10603216.7       3730171.6      10603859.1
#Sta/Elev= 30
  4661.8  276.61  4724.5  276.84  4760.1  273.56    4767  275.52  4837.8  274.99
    4852  272.33  4901.3  270.54  4915.4  268.05  4943.8  264.42  4951.1  256.61
    4958  254.98  4965.3  248.73  4972.1  245.05  4979.4  243.76  4990.6  237.39
  4993.4  236.89  4996.6  237.39  5014.6  240.53  5021.9  251.64  5036.1  257.32
  5050.3  257.99  5084.4  254.74  5205.6   260.9  5262.3  260.13  5269.6  262.15
  5401.9  267.35  5432.2  272.03  5460.5   269.4  5524.1  278.04  5543.1  278.67
#Mann= 6 ,-1 , 0
  4661.8     .05       0  4915.4     .16       0  4990.6     .07       0
  4996.6     .16       0  5084.4     .08       0  5401.9     .05       0
Bank Sta=4965.3,5021.9
XS Rating Curve= 0 ,0
Exp/Cntr=0.3,0.1

Type RM Length L Ch R = 1 ,16342   ,266,266,266
BEGIN DESCRIPTION:
MACK CREEK 30.0
END DESCRIPTION:
XS GIS Cut Line= 3
      3730499.65     10603160.17      3730299.61     10603239.36
      3729999.58     10603460.21
#Sta/Elev= 30
  4792.4  288.83  4807.3  288.25    4856  277.34  4891.1  273.46    4910  269.06
  4945.1   264.1  4953.8  262.52  4964.1  258.07  4969.5  260.47  4975.3  247.42
    4986  242.07  4993.8  236.59  5001.9  236.49  5004.6  235.99  5007.9  236.49
  5010.6  236.49  5015.6  240.82  5021.8  243.67  5030.2  243.96  5036.4  249.33
  5044.8  252.92  5075.9  256.31  5097.6  256.19  5222.3  258.33  5257.8  262.83
  5272.5  267.52  5283.3  268.05  5293.3  272.41  5328.7   275.1  5380.1  281.49
#Mann= 7 ,-1 , 0
  4792.4     .13       0  5001.9     .07       0  5007.9     .13       0
  5075.9     .05       0  5097.6     .08       0  5283.3     .05       0
  5328.7      .1       0
Bank Sta=4986,5021.8
XS Rating Curve= 0 ,0
Exp/Cntr=0.3,0.1

Type RM Length L Ch R = 1 ,16076   ,171,171,171
BEGIN DESCRIPTION:
Mapping XS afd32863
END DESCRIPTION:
XS GIS Cut Line= 3
      3730633.59     10602753.36      3730249.88     10602972.12
      3729768.95     10603241.24
#Sta/Elev= 30
  4438.3  281.81    4523  278.96  4746.4  279.66  4799.7  273.83  4811.2   266.7
  4857.3  258.55  4929.5  255.98  4937.6  253.82  4945.5  246.85  4972.9  242.52
  5001.9  235.25  5004.6  234.75  5007.9  235.25  5010.6  240.39  5017.8  243.14
  5032.3  247.52  5120.1  246.18  5143.9  246.71  5166.8  241.98  5172.7  246.82
  5210.4  247.76  5219.8  251.87  5297.2  253.66  5304.3  259.21  5327.2  264.13
  5362.3  265.94  5407.4  272.54  5415.9   276.5  5421.7  273.48  5431.1  275.83
#Mann= 6 ,-1 , 0
  4438.3     .05       0    4523     .16       0  5001.9     .07       0
  5007.9     .16       0  5120.1     .05       0  5219.8     .16       0
Bank Sta=4972.9,5017.8
XS Rating Curve= 0 ,0
Exp/Cntr=0.3,0.1

Type RM Length L Ch R = 1 ,15905   ,130,130,130
BEGIN DESCRIPTION:
Mapping XS 770d6008
END DESCRIPTION:
XS GIS Cut Line= 2
      3730388.81     10602613.25      3729795.91     10603135.94
#Sta/Elev= 30
  4615.4  277.52  4719.2  263.86    4761  252.61  4768.6  252.65  4775.3  259.71
  4832.2  264.09  4889.1  248.44  4966.9   245.9  4987.8  240.64  4992.3  234.63
  4995.1  234.13  4998.3  234.63  5023.8   241.9  5080.7  243.86  5101.6  247.92
  5150.9  244.48  5193.6  246.06  5207.8  250.57  5214.5   247.6    5222  253.47
  5228.7  252.03  5236.3  258.32  5242.9  255.88  5264.7  266.03  5271.4  263.89
    5279  270.21  5363.4  271.21  5377.6  274.31  5385.2  280.11  5405.8  279.76
#Mann= 3 ,-1 , 0
  4615.4     .13       0  4992.3     .07       0  4998.3     .13       0
Bank Sta=4987.8,5023.8
XS Rating Curve= 0 ,0
Exp/Cntr=0.3,0.1

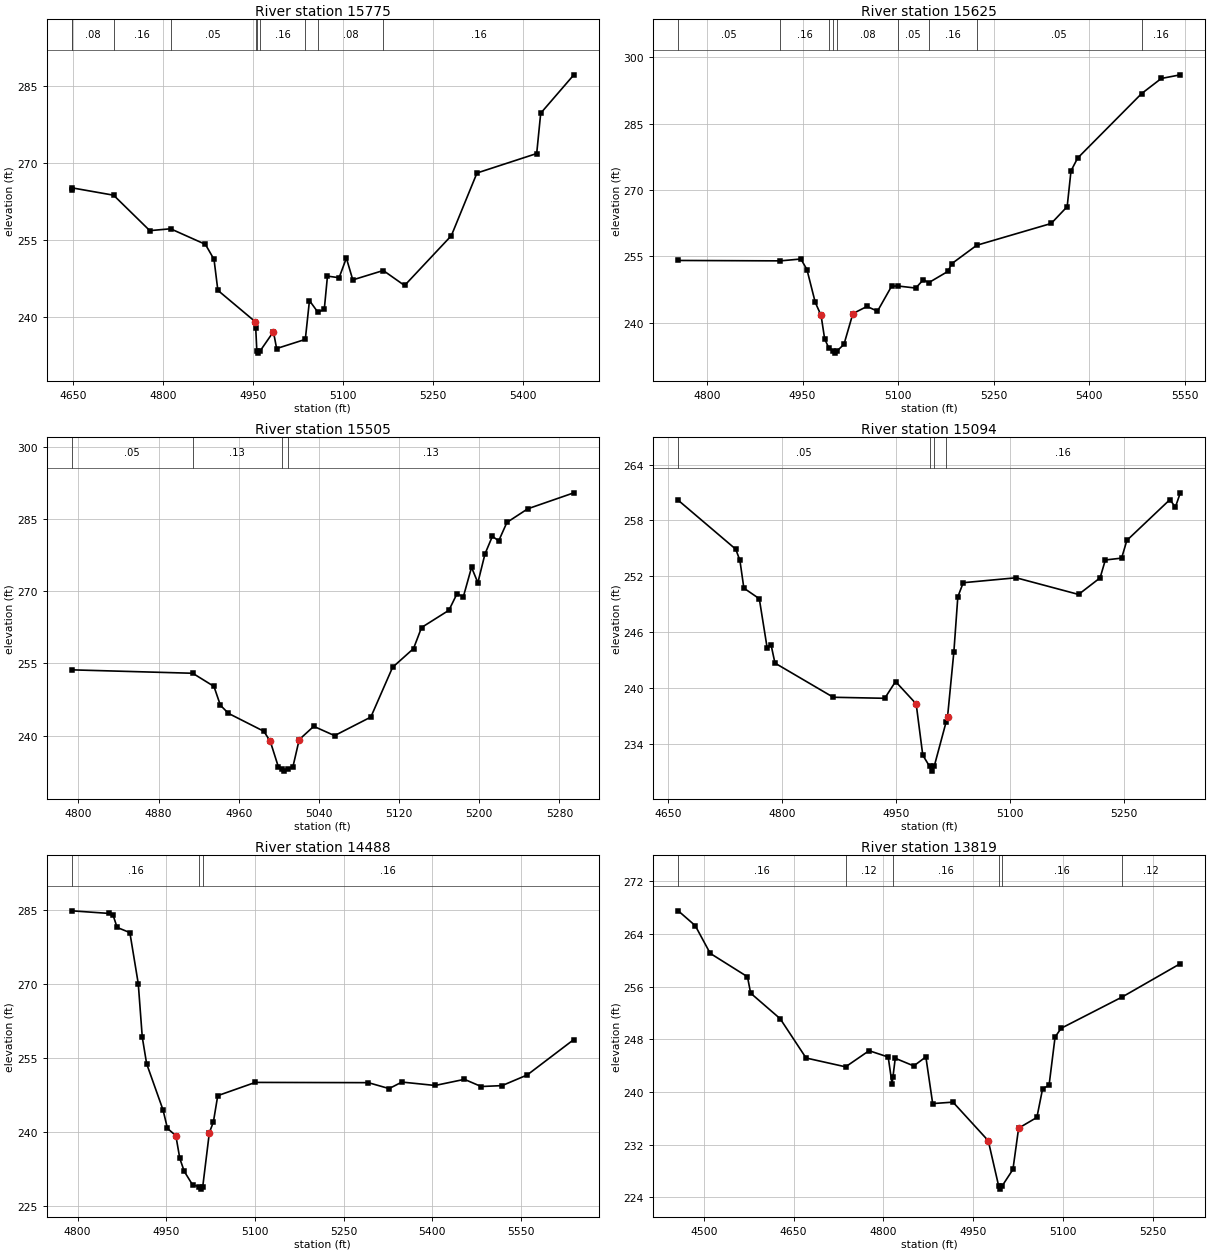
Type RM Length L Ch R = 1 ,15775   ,150,150,150
BEGIN DESCRIPTION:
MACK CREEK 29.0
END DESCRIPTION:
XS GIS Cut Line= 4
      3730276.81     10602454.42      3730112.75     10602654.94
      3730026.81     10602878.89      3729773.11     10603101.53
#Sta/Elev= 30
  4648.3  264.76    4649  265.14    4718  263.72  4778.3  256.84  4812.9   257.2
  4870.9  254.18  4885.3  251.26  4891.7  245.25  4954.3  239.13  4954.8  237.92
  4956.6  233.56  4959.4  233.06  4962.6  233.56  4984.3  237.22  4989.6  233.95
  5037.4  235.73  5044.3  243.26  5058.3  241.01    5069  241.55  5074.3  248.01
  5093.7   247.7  5105.8  251.52  5116.5  247.28  5167.3   249.1  5202.8  246.19
  5280.7  255.86  5323.4  268.03  5422.9  271.81  5429.6  279.64  5484.8  287.09
#Mann= 10 ,-1 , 0
  4648.3     .16       0    4649     .08       0    4718     .16       0
  4812.9     .05       0  4954.8     .16       0  4956.6     .07       0
  4962.6     .16       0  5037.4     .05       0  5058.3     .08       0
  5167.3     .16       0
Bank Sta=4954.3,4984.3
XS Rating Curve= 0 ,0
Exp/Cntr=0.3,0.1

Type RM Length L Ch R = 1 ,15625   ,120,120,120
BEGIN DESCRIPTION:
MACK CREEK 28.0
END DESCRIPTION:
XS GIS Cut Line= 3
      3730149.21      10602389.3      3729917.44     10602837.23
       3729644.3     10602912.66
#Sta/Elev= 30
  4754.9  254.09  4915.1     254  4947.3  254.42  4956.8  252.05  4969.8  244.65
    4979  241.68  4984.6  236.39    4991  234.38  4998.1  233.67  5000.9  233.17
  5004.1  233.67  5014.9  235.15  5028.9  242.09    5051  243.71  5067.5  242.64
  5089.7  248.29  5099.3  248.33  5127.5  247.86  5139.6  249.77  5147.6  249.05
  5178.2  251.64  5183.9  253.35  5223.2  257.52    5340  262.44  5365.1  266.24
  5371.1  274.32  5381.5   277.2  5481.9  291.77  5512.8  295.18  5542.6     296
#Mann= 9 ,-1 , 0
  4754.9     .05       0  4915.1     .16       0    4991     .08       0
  4998.1     .07       0  5004.1     .08       0  5099.3     .05       0
  5147.6     .16       0  5223.2     .05       0  5481.9     .16       0
Bank Sta=4979,5028.9
XS Rating Curve= 0 ,0
Exp/Cntr=0.3,0.1

Type RM Length L Ch R = 1 ,15505   ,411,411,411
BEGIN DESCRIPTION:
Mapping XS 1160fd7f
END DESCRIPTION:
XS GIS Cut Line= 2
      3730115.38      10602397.1      3729719.56     10602704.39
#Sta/Elev= 30
  4793.3  253.66    4914  252.95  4935.2  250.22  4941.6  246.31  4949.7  244.61
    4985  240.89  4991.4  238.81  4999.5  233.49  5002.8  233.11  5005.6  232.61
  5008.8  233.11    5014  233.49  5020.3  239.16  5034.8  241.92  5055.6  239.99
  5091.8  243.85  5113.5  254.19  5134.4  258.08  5142.4  262.46  5169.7  266.04
  5177.8  269.48  5184.1  268.83  5192.3  274.97  5198.6  271.76  5205.7  277.74
  5213.1  281.42  5219.4  280.46  5227.6   284.3  5248.4  287.13  5294.4  290.45
#Mann= 4 ,-1 , 0
  4793.3     .05       0    4914     .13       0  5002.8     .07       0
  5008.8     .13       0
Bank Sta=4991.4,5020.3
XS Rating Curve= 0 ,0
Exp/Cntr=0.3,0.1

Type RM Length L Ch R = 1 ,15094   ,606,606,606
BEGIN DESCRIPTION:
MACK CREEK 27.0
END DESCRIPTION:
XS GIS Cut Line= 3
      3730302.88     10602225.26       3729831.5     10602105.46
      3729706.43     10602226.33
#Sta/Elev= 30
  4663.6  260.17  4739.2  254.92  4744.7  253.72  4749.9  250.74  4770.2   249.6
  4780.5  244.34  4785.7  244.64  4790.8  242.69  4867.5  239.02  4935.2  238.91
  4949.4  240.71  4976.5  238.31  4985.2  232.81  4994.2  231.59  4996.9  231.09
  5000.2  231.59  5015.8  236.34  5017.8  236.93  5026.1   243.9  5031.3   249.8
  5038.4  251.32    5108  251.85  5190.1  250.06  5218.4  251.84  5225.3  253.76
  5246.7  253.96  5253.6  255.86  5310.2  260.24  5317.4  259.43  5323.9  260.97
#Mann= 4 ,-1 , 0
  4663.6     .05       0  4994.2     .03       0  5000.2     .05       0
  5015.8     .16       0
Bank Sta=4976.5,5017.8
XS Rating Curve= 0 ,0
Exp/Cntr=0.3,0.1

Type RM Length L Ch R = 1 ,14488   ,669,669,669
BEGIN DESCRIPTION:
MACK CREEK 26.0
END DESCRIPTION:
XS GIS Cut Line= 3
      3730254.08      10601576.1      3729833.09     10602040.49
      3729676.99     10602199.31
#Sta/Elev= 30
  4790.1  284.76  4852.6  284.24  4860.1  283.85  4866.8   281.4  4888.4  280.35
  4902.6  270.02  4909.4  259.17  4916.8   253.8  4944.5  244.46    4952  240.72
  4966.2  239.25  4972.9  234.64  4980.4  232.03  4994.5  229.29  5005.7  228.93
  5008.5  228.43  5011.7  228.93  5022.9  239.86  5029.7  242.02  5037.1  247.35
  5100.6  250.03  5291.9  249.98    5327  248.78  5348.7   250.1  5404.8  249.41
  5454.5  250.65  5482.8   249.2  5518.1  249.38  5560.6  251.53  5639.6  258.71
#Mann= 3 ,-1 , 0
  4790.1     .16       0  5005.7     .07       0  5011.7     .16       0
Bank Sta=4966.2,5022.9
XS Rating Curve= 0 ,0
Exp/Cntr=0.3,0.1

Type RM Length L Ch R = 1 ,13819   ,232,232,232
BEGIN DESCRIPTION:
MACK CREEK 25.0
END DESCRIPTION:
XS GIS Cut Line= 3
      3729784.62     10601339.85      3729630.98     10601772.12
      3729566.04     10602146.16
#Sta/Elev= 30
  4457.3  267.52  4485.7  265.27  4510.7  261.06  4572.9  257.51  4578.2  255.02
  4627.5  251.14  4670.8  245.17  4736.8  243.83    4776  246.28  4807.9  245.32
  4814.4  241.24  4815.8  242.27  4819.7  245.13  4850.6  243.97  4870.8  245.34
  4882.2  238.25  4916.1  238.47    4975  232.61  4992.3  225.76  4995.1  225.26
  4998.3  225.76  5016.2  228.25  5025.7  234.52  5056.2  236.15  5065.8  240.53
  5076.5     241  5086.6  248.37  5096.8  249.69  5198.7  254.44  5295.7   259.5
#Mann= 6 ,-1 , 0
  4457.3     .16       0  4736.8     .12       0  4815.8     .16       0
  4992.3     .07       0  4998.3     .16       0  5198.7     .12       0
Bank Sta=4975,5025.7
XS Rating Curve= 0 ,0
Exp/Cntr=0.3,0.1

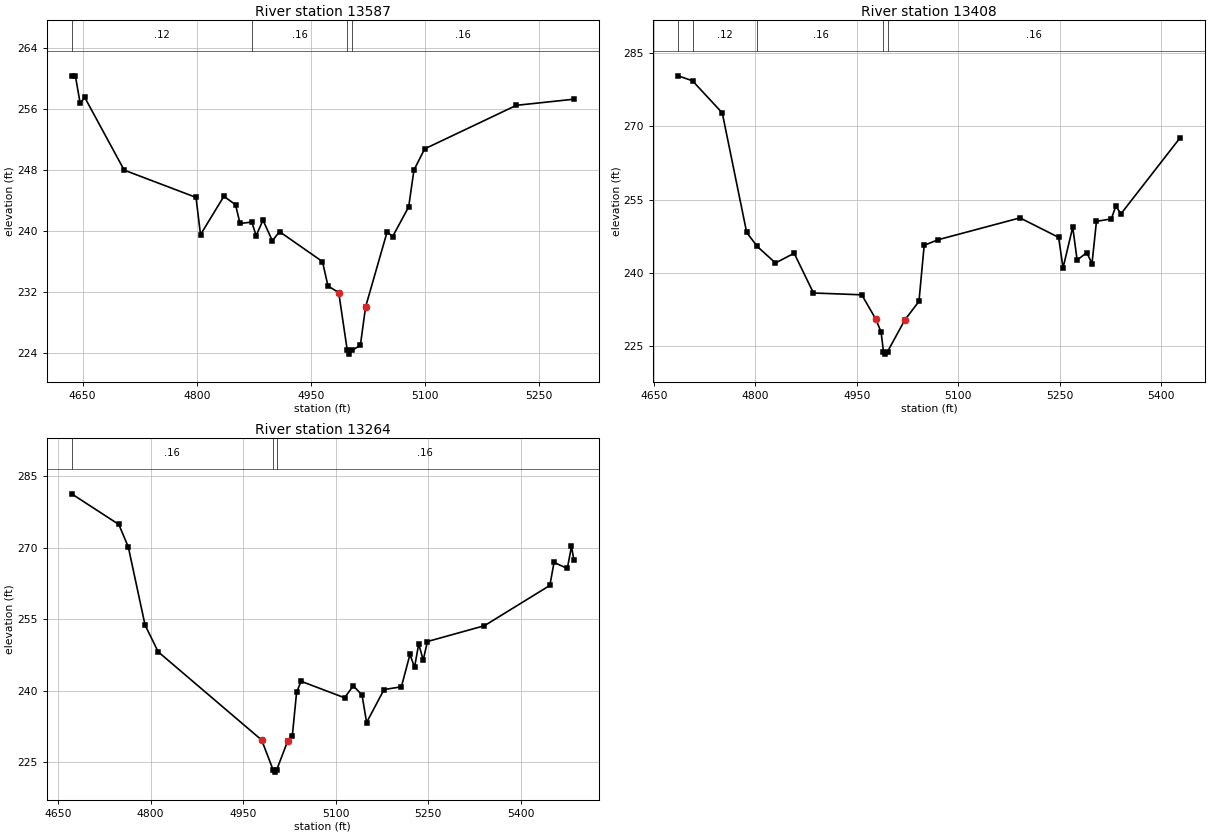
Type RM Length L Ch R = 1 ,13587   ,179,179,179
BEGIN DESCRIPTION:
Mapping XS f3205d51
END DESCRIPTION:
XS GIS Cut Line= 3
      3729681.31     10601386.88      3729519.84     10601645.58
      3729275.08      10601902.5
#Sta/Elev= 30
  4635.6  260.33  4640.5  260.33  4646.8  256.71  4652.7  257.52  4704.6  247.99
    4799  244.42  4804.9  239.54  4835.6  244.56  4850.9  243.47  4856.8  241.01
  4872.3  241.19    4878  239.41    4887  241.44  4899.3  238.74  4908.7  239.94
  4965.1  236.02  4972.4  232.83  4986.5  231.96  4997.7  224.41  5000.4  223.91
  5003.7  224.41  5014.9  225.04  5021.8  230.09  5050.1  239.91  5057.3  239.29
  5078.4  243.18  5085.3  247.99  5099.4  250.77  5219.9  256.47  5295.4  257.27
#Mann= 4 ,-1 , 0
  4635.6     .12       0  4872.3     .16       0  4997.7     .07       0
  5003.7     .16       0
Bank Sta=4986.5,5021.8
XS Rating Curve= 0 ,0
Exp/Cntr=0.3,0.1

Type RM Length L Ch R = 1 ,13408   ,144,144,144
BEGIN DESCRIPTION:
MACK CREEK 24.0
END DESCRIPTION:
XS GIS Cut Line= 2
      3729602.31     10601290.38      3729121.75     10601856.66
#Sta/Elev= 30
  4685.9  280.29  4707.2  279.27  4751.2   272.7  4787.3  248.26    4803  245.39
  4829.9  242.02  4857.5  244.01  4886.1  235.88  4957.5  235.51  4978.4  230.51
  4986.1  227.88  4989.6  223.88  4992.4  223.38  4995.6  223.88  5021.2  230.37
  5042.1  234.16  5049.8  245.63  5070.6  246.78  5191.5  251.24  5248.6  247.26
  5255.2  241.01  5269.5  249.35    5276  242.61  5290.3  244.13    5298   241.9
  5304.6  250.53  5326.6  251.04  5333.2  253.63  5340.9  252.08  5428.6  267.67
#Mann= 5 ,-1 , 0
  4685.9     .16       0  4707.2     .12       0    4803     .16       0
  4989.6     .07       0  4995.6     .16       0
Bank Sta=4978.4,5021.2
XS Rating Curve= 0 ,0
Exp/Cntr=0.3,0.1

Type RM Length L Ch R = 1 ,13264   ,181,181,181
BEGIN DESCRIPTION:
Mapping XS f035166f
END DESCRIPTION:
XS GIS Cut Line= 4
      3729578.87     10601244.54      3729334.08     10601395.58
      3729224.71     10601499.75      3728969.78     10601775.48
#Sta/Elev= 30
  4672.1   281.3  4748.6  274.87    4764  270.13  4791.1  253.77  4812.4  248.15
  4980.2  229.64  4998.6  223.41  5001.3  222.91  5004.6  223.41  5022.6  229.51
  5029.9  230.56  5036.8  239.64    5044  241.97  5114.6  238.51  5128.7  241.02
  5142.9  239.09  5150.3  233.32  5178.6  240.24  5206.7  240.81  5220.6   247.6
    5228   244.9  5234.8  249.81  5242.1  246.41  5248.9  250.31  5341.4  253.63
  5447.4  262.08  5454.2  266.91  5475.7  265.64  5482.5  270.27  5486.3  267.49
#Mann= 3 ,-1 , 0
  4672.1     .16       0  4998.6     .07       0  5004.6     .16       0
Bank Sta=4980.2,5022.6
XS Rating Curve= 0 ,0
Exp/Cntr=0.3,0.1