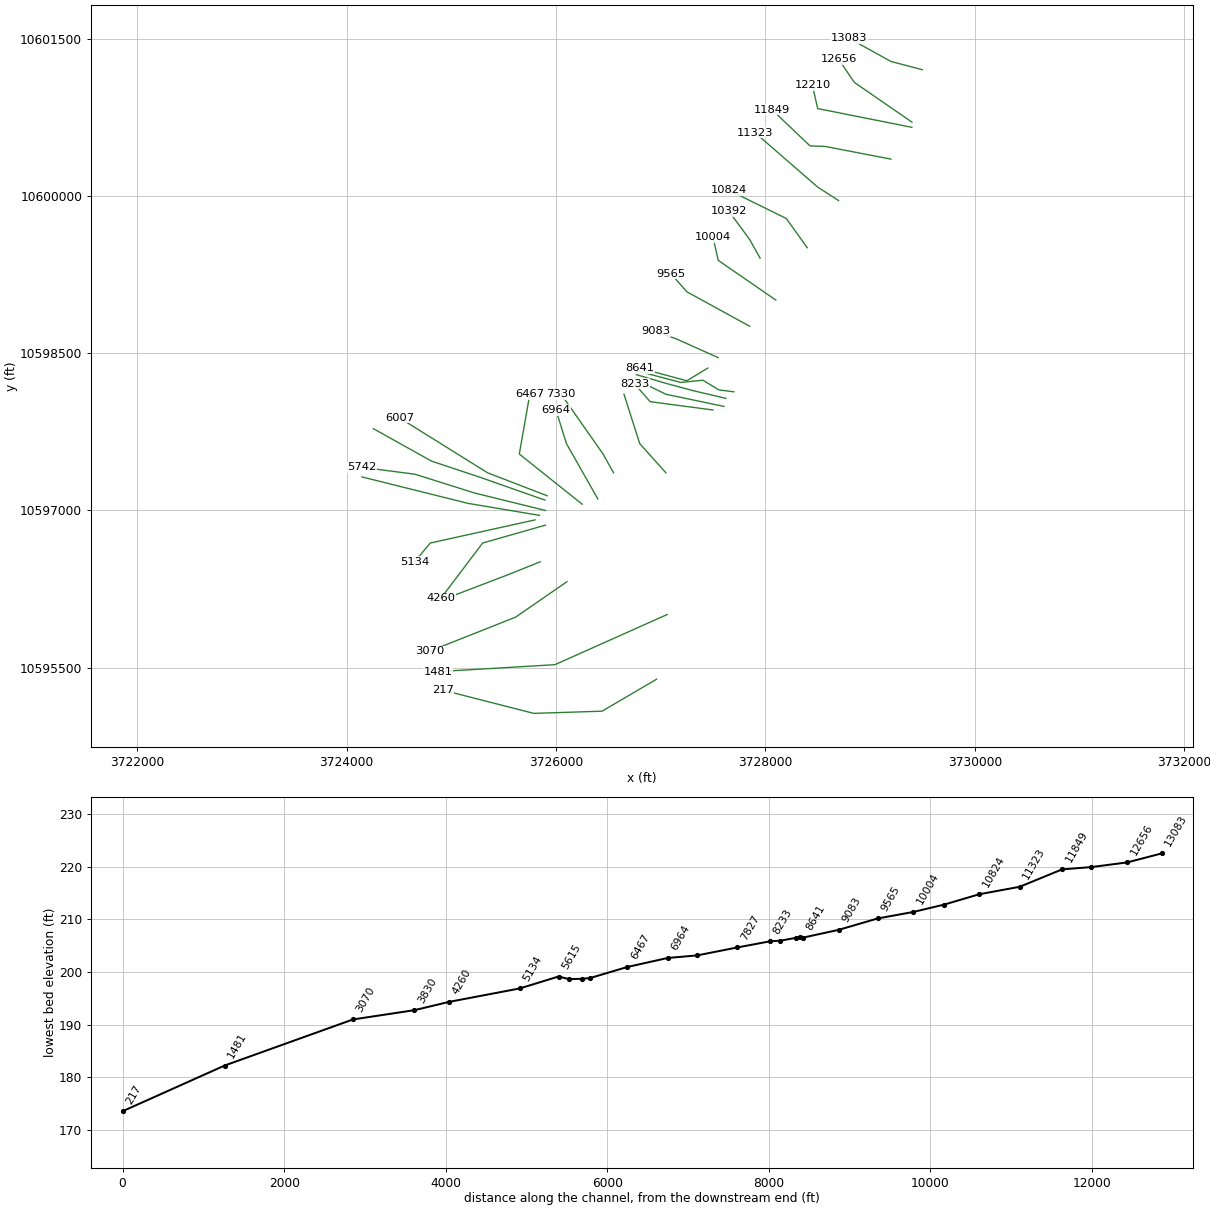
HEC-RAS study MACK CREEK.prj: MACK CREEK Base Level Engineering

--- MACK CREEK.g01 (geometry) --- (continued)

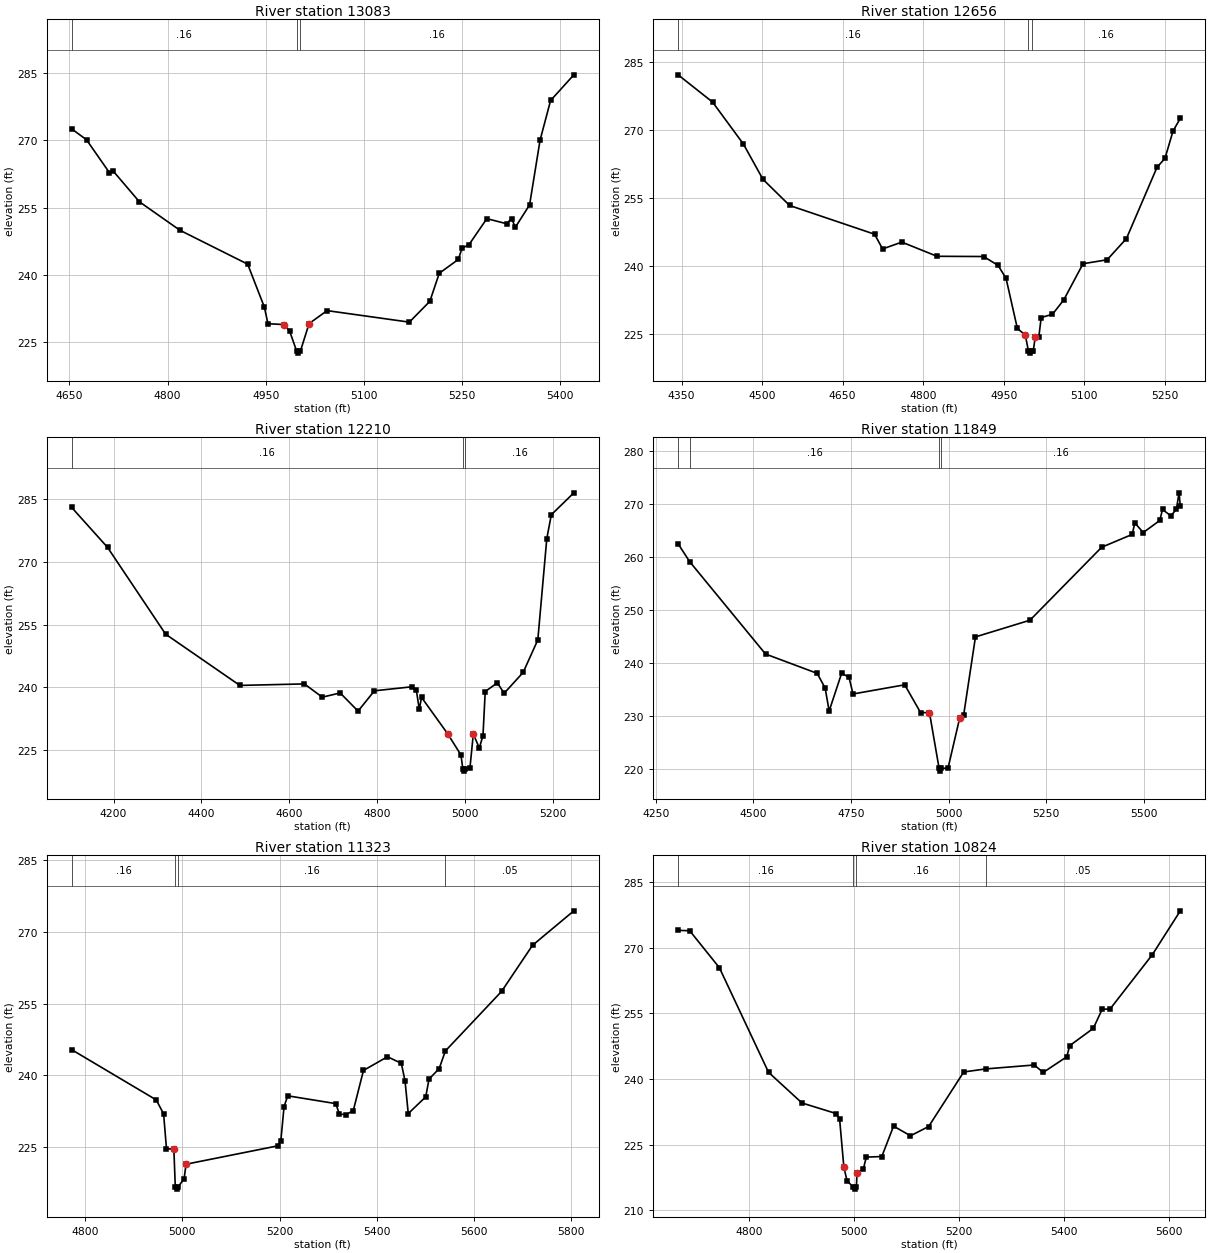
Type RM Length L Ch R = 1 ,13083   ,427,427,427
BEGIN DESCRIPTION:
MACK CREEK 23.0
END DESCRIPTION:
XS GIS Cut Line= 3
      3729499.62     10601210.19      3729199.61     10601289.36
       3728799.6     10601510.19
#Sta/Elev= 30
  4653.4  272.57  4676.1  270.14  4711.2  262.78  4716.4  263.24  4756.8  256.32
  4818.9  249.95  4922.3   242.4  4947.8  232.82  4953.3  229.12  4978.3  228.93
  4986.5  227.44    4997  223.06  4999.8  222.56    5003  223.06  5016.1  229.14
  5043.6  232.04  5169.3  229.47  5200.6  234.11    5215  240.37  5244.1  243.45
  5249.8  245.97  5260.2   246.7  5287.7  252.55  5317.8  251.42  5325.5  252.58
  5331.2  250.62    5353  255.62    5369  270.05  5385.1   278.9  5420.6  284.62
#Mann= 3 ,-1 , 0
  4653.4     .16       0    4997     .07       0    5003     .16       0
Bank Sta=4978.3,5016.1
XS Rating Curve= 0 ,0
Exp/Cntr=0.3,0.1

Type RM Length L Ch R = 1 ,12656   ,446,446,446
BEGIN DESCRIPTION:
MACK CREEK 22.0
END DESCRIPTION:
XS GIS Cut Line= 3
       3729399.6     10600710.19      3728849.61     10601089.36
       3728699.6      10601310.2
#Sta/Elev= 30
  4343.7  282.24  4407.9  276.22  4465.2  266.98  4501.6   259.2  4551.3  253.42
  4709.5  247.08  4724.4  243.83  4760.2  245.34  4825.8  242.21  4912.4  242.16
  4939.4  240.21  4954.3  237.33  4975.3   226.3  4990.1  224.82  4995.9  221.35
  4998.7  220.85  5001.9  221.35    5005  221.42  5008.7  224.46  5015.3  224.46
  5019.7   228.7  5040.7  229.42  5061.7  232.59  5097.6  240.57  5142.4  241.44
  5178.4  246.12  5235.3  261.83  5250.2  263.83  5265.2  269.86  5278.7  272.64
#Mann= 3 ,-1 , 0
  4343.7     .16       0  4995.9     .07       0  5001.9     .16       0
Bank Sta=4990.1,5008.7
XS Rating Curve= 0 ,0
Exp/Cntr=0.3,0.1

Type RM Length L Ch R = 1 ,12210   ,361,361,361
BEGIN DESCRIPTION:
MACK CREEK 21.0
END DESCRIPTION:
XS GIS Cut Line= 3
      3729399.58     10600660.19      3728499.61     10600839.36
       3728449.6     10601060.23
#Sta/Elev= 30
  4104.4     283  4186.1  273.46  4318.5   252.7  4487.6  240.45  4634.6  240.81
  4675.4  237.64  4716.1  238.65  4756.9  234.31  4794.2  239.16  4879.3  240.12
  4889.5  239.43  4896.4  234.73  4901.5  237.59  4960.9  228.91  4991.4  223.81
  4995.6  220.46  4998.4  219.96  5001.6  220.46  5011.8  220.73  5019.5  228.85
  5033.1  225.49  5041.5  228.43  5046.6  238.99  5074.2  241.07  5089.7  238.57
  5132.9  243.54  5166.4  251.32  5186.9  275.56  5197.2  281.25  5248.5  286.49
#Mann= 3 ,-1 , 0
  4104.4     .16       0  4995.6     .07       0  5001.6     .16       0
Bank Sta=4960.9,5019.5
XS Rating Curve= 0 ,0
Exp/Cntr=0.3,0.1

Type RM Length L Ch R = 1 ,11849   ,526,526,526
BEGIN DESCRIPTION:
MACK CREEK 20.0
END DESCRIPTION:
XS GIS Cut Line= 4
      3729199.38     10600356.47      3728570.07     10600477.99
      3728426.84     10600482.33      3728063.42     10600828.45
#Sta/Elev= 30
  4307.1  262.41    4337  259.02  4530.9  241.62  4663.3  237.97  4683.7  235.18
  4693.9  230.87  4725.9     238  4744.8  237.22    4755  234.08  4887.4  235.81
  4928.1  230.56  4950.8  230.57  4975.5  220.02  4978.3  219.52  4981.5  220.02
  4998.5  220.13  5028.5  229.64  5038.5  230.17  5068.6  244.85  5208.2     248
  5391.8  261.77  5469.9  264.19  5476.8  266.37  5498.2  264.54  5540.6  266.82
  5547.6   268.9    5569  267.69  5583.1  268.93    5590  272.04  5593.2  269.53
#Mann= 4 ,-1 , 0
  4307.1      .1       0    4337     .16       0  4975.5     .07       0
  4981.5     .16       0
Bank Sta=4950.8,5028.5
XS Rating Curve= 0 ,0
Exp/Cntr=0.3,0.1

Type RM Length L Ch R = 1 ,11323   ,499,499,499
BEGIN DESCRIPTION:
MACK CREEK 19.0
END DESCRIPTION:
XS GIS Cut Line= 3
      3728699.65     10599960.16      3728499.61     10600089.36
      3727899.58     10600610.22
#Sta/Elev= 30
  4772.5  245.37  4946.4  234.87  4961.6  231.95  4967.5  224.65  4982.7  224.57
  4985.6  216.71  4988.4  216.21  4991.6  216.71  5003.8  218.38  5007.7  221.42
    5196  225.25  5202.6  226.25  5209.3  233.48  5216.9  235.72  5315.6  234.09
  5323.2  231.87  5337.5  231.81  5351.7  232.65  5372.6  241.03    5422  243.89
  5450.5  242.51  5458.1   238.8  5464.7  232.01  5500.6   235.5  5507.4  239.21
  5528.3  241.42    5541   245.1  5656.6  257.55  5720.2  267.19  5805.2   274.4
#Mann= 4 ,-1 , 0
  4772.5     .16       0  4985.6     .07       0  4991.6     .16       0
    5541     .05       0
Bank Sta=4982.7,5007.7
XS Rating Curve= 0 ,0
Exp/Cntr=0.3,0.1

Type RM Length L Ch R = 1 ,10824   ,432,432,432
BEGIN DESCRIPTION:
MACK CREEK 18.0
END DESCRIPTION:
XS GIS Cut Line= 3
       3728399.6      10599510.2      3728199.61     10599789.36
      3727649.58      10600060.2
#Sta/Elev= 30
  4665.5  274.02  4687.6  273.93  4744.1  265.47  4837.7  241.54  4901.3  234.52
  4966.4   232.1    4973  230.94  4981.2  219.81  4987.3  216.68    4999   215.3
  5001.8   214.8    5005   215.3  5006.3  218.44  5018.3  219.41  5023.9  222.13
  5053.5  222.26  5075.8  229.22  5108.1  227.01  5142.7  229.13  5209.5  241.61
  5251.3  242.31  5343.9  243.21  5360.8   241.5  5405.8  245.09  5411.3  247.63
  5456.3  251.59  5473.2  255.97  5488.2  256.02  5568.6  268.43    5622  278.49
#Mann= 4 ,-1 , 0
  4665.5     .16       0    4999     .07       0    5005     .16       0
  5251.3     .05       0
Bank Sta=4981.2,5006.3
XS Rating Curve= 0 ,0
Exp/Cntr=0.3,0.1

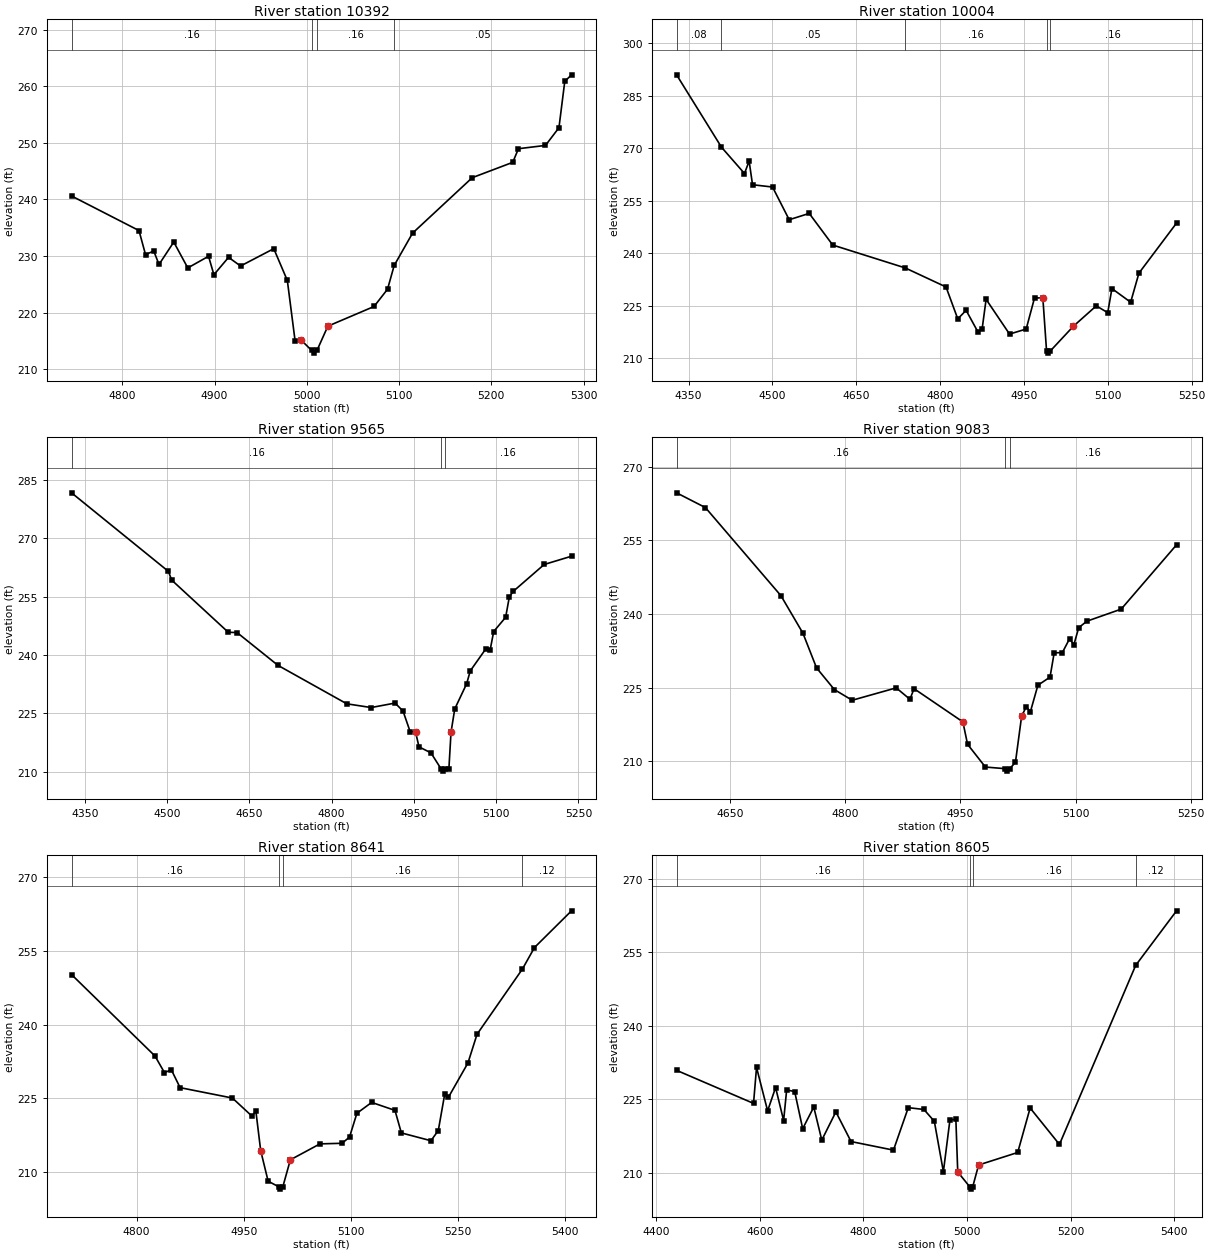
Type RM Length L Ch R = 1 ,10392   ,388,388,388
BEGIN DESCRIPTION:
MACK CREEK 17.0
END DESCRIPTION:
XS GIS Cut Line= 3
      3727949.61     10599410.18      3727849.61     10599589.36
      3727649.59     10599860.21
#Sta/Elev= 30
    4745   240.6  4818.1  234.49  4825.2  230.24  4834.1  230.88  4839.8   228.5
  4855.8  232.46    4871  227.89  4893.5  229.95  4899.3  226.69  4915.2  229.76
  4928.2  228.23  4964.2  231.29  4978.9  225.67  4987.3  215.01  4993.5   215.2
  5005.1  213.34  5007.9  212.84  5011.1  213.34  5022.8   217.6  5072.9  221.08
  5087.5  224.13  5094.7  228.32  5114.6  234.03  5179.3  243.83  5223.2  246.54
  5229.4  248.95  5258.7  249.53  5273.3  252.66  5279.6  260.84  5286.9     262
#Mann= 4 ,-1 , 0
    4745     .16       0  5005.1     .07       0  5011.1     .16       0
  5094.7     .05       0
Bank Sta=4993.5,5022.8
XS Rating Curve= 0 ,0
Exp/Cntr=0.3,0.1

Type RM Length L Ch R = 1 ,10004   ,439,439,439
BEGIN DESCRIPTION:
MACK CREEK 16.0
END DESCRIPTION:
XS GIS Cut Line= 3
      3728099.61     10599010.19      3727549.61     10599389.36
       3727499.6     10599610.23
#Sta/Elev= 30
  4328.4  291.01  4408.7  270.32  4449.9  262.79  4458.2  266.34  4464.3  259.58
  4500.1  258.92  4529.9  249.57  4565.7  251.38  4607.8  242.33  4737.3   235.8
  4810.5  230.34  4831.5  221.21  4846.4  223.66  4867.3  217.56    4875  218.24
  4882.2   226.8  4924.1  216.87  4953.9  218.31  4968.8   227.2  4983.7  227.22
  4990.4  211.92  4993.1  211.42  4996.4  211.92  5038.3   219.1  5079.3  224.94
  5099.8  222.99  5107.3  229.88  5140.8  225.98  5155.6  234.29  5222.9  248.61
#Mann= 5 ,-1 , 0
  4328.4     .08       0  4408.7     .05       0  4737.3     .16       0
  4990.4     .07       0  4996.4     .16       0
Bank Sta=4983.7,5038.3
XS Rating Curve= 0 ,0
Exp/Cntr=0.3,0.1

Type RM Length L Ch R = 1 ,9565    ,482,482,482
BEGIN DESCRIPTION:
MACK CREEK 15.0
END DESCRIPTION:
XS GIS Cut Line= 3
       3727849.6     10598760.19      3727249.61     10599089.36
       3727099.6      10599260.2
#Sta/Elev= 30
  4325.7  281.62  4502.4  261.45  4508.2  259.24  4611.5  245.83  4627.6  245.75
  4702.1  237.34  4827.6  227.47  4872.1  226.51  4915.7  227.66  4930.2   225.6
  4943.2   220.3    4953  220.26  4959.3  216.42  4981.1  214.88  4999.9  210.69
  5002.6  210.19  5005.9  210.69  5013.8  210.75  5017.7  220.16  5024.5  226.15
  5046.2  232.62  5052.8  235.92  5081.3   241.6  5088.9  241.18  5095.5  246.02
  5117.3  249.67    5124  254.88  5130.9   256.3  5187.6  263.23  5237.4  265.35
#Mann= 3 ,-1 , 0
  4325.7     .16       0  4999.9     .07       0  5005.9     .16       0
Bank Sta=4953,5017.7
XS Rating Curve= 0 ,0
Exp/Cntr=0.3,0.1

Type RM Length L Ch R = 1 ,9083    ,442,442,442
BEGIN DESCRIPTION:
MACK CREEK 14.0
END DESCRIPTION:
XS GIS Cut Line= 3
       3727549.6     10598460.19      3727149.61     10598639.36
      3726949.57      10598710.2
#Sta/Elev= 30
  4580.7  264.65  4618.2  261.65  4716.5  243.72  4745.1  236.09  4762.8  229.04
    4786  224.62  4809.2  222.45  4866.5  224.97  4884.3  222.65  4889.7   224.8
  4953.2  218.05  4959.3  213.49  4982.5  208.86  5008.2  208.53  5010.9  208.03
  5014.2  208.53  5021.6  209.82  5029.6  219.16  5035.7  221.16    5041  220.08
  5050.8   225.5  5066.6  227.16    5072   232.1  5082.6  232.14  5092.2  235.01
  5097.5  233.68  5103.9  237.21  5114.5  238.53  5159.2  240.99  5231.2  254.07
#Mann= 3 ,-1 , 0
  4580.7     .16       0  5008.2     .07       0  5014.2     .16       0
Bank Sta=4953.2,5029.6
XS Rating Curve= 0 ,0
Exp/Cntr=0.3,0.1

Type RM Length L Ch R = 1 ,8641    ,36,36,36
BEGIN DESCRIPTION:
MACK CREEK 13.0
END DESCRIPTION:
XS GIS Cut Line= 3
      3727449.61     10598360.19      3727249.61     10598239.36
      3726799.62     10598360.19
#Sta/Elev= 30
    4709  250.17  4825.8  233.61    4839  230.24  4848.7   230.8  4860.9  227.18
  4934.1  225.07  4961.7  221.36  4966.9  222.47  4973.7  214.36  4984.1  208.16
  4998.7  207.05  5001.4  206.55  5004.7  207.05  5015.2  212.51  5056.6  215.75
  5087.6  215.87    5098  217.14  5108.3  221.97    5129  224.18  5161.6  222.56
  5170.5  217.98  5211.9  216.39  5222.2  218.46  5231.3  225.96  5236.4  225.23
  5263.7   232.2  5276.4  238.03  5339.9  251.29  5356.8  255.67  5408.6  263.13
#Mann= 4 ,-1 , 0
    4709     .16       0  4998.7     .07       0  5004.7     .16       0
  5339.9     .12       0
Bank Sta=4973.7,5015.2
XS Rating Curve= 0 ,0
Exp/Cntr=0.3,0.1

Type RM Length L Ch R = 1 ,8605    ,55,55,55
BEGIN DESCRIPTION:
Mapping XS 0f879fe3
END DESCRIPTION:
XS GIS Cut Line= 5
      3727699.41     10598133.58      3727556.18     10598151.81
      3727403.84     10598244.25       3727191.6     10598223.42
      3726776.21      10598332.8
#Sta/Elev= 30
  4439.2  230.89  4587.8  224.15  4593.6  231.48    4615  222.63  4630.4  227.38
  4645.9  220.66  4651.8  226.92  4667.3  226.54  4682.7  218.99  4704.1   223.4
  4719.6  216.67  4746.8  222.42  4776.1  216.37    4858  214.62  4886.6  223.28
  4916.8  222.91  4936.9   220.5  4954.4  210.22    4967  220.75  4978.5  220.91
  4982.1  210.18  5005.1  207.17  5007.9  206.67  5011.1  207.17  5022.4  211.59
  5097.9  214.14  5121.9  223.21  5178.5  215.78  5325.7  252.29  5404.6  263.41
#Mann= 4 ,-1 , 0
  4439.2     .16       0  5005.1     .07       0  5011.1     .16       0
  5325.7     .12       0
Bank Sta=4982.1,5022.4
XS Rating Curve= 0 ,0
Exp/Cntr=0.3,0.1

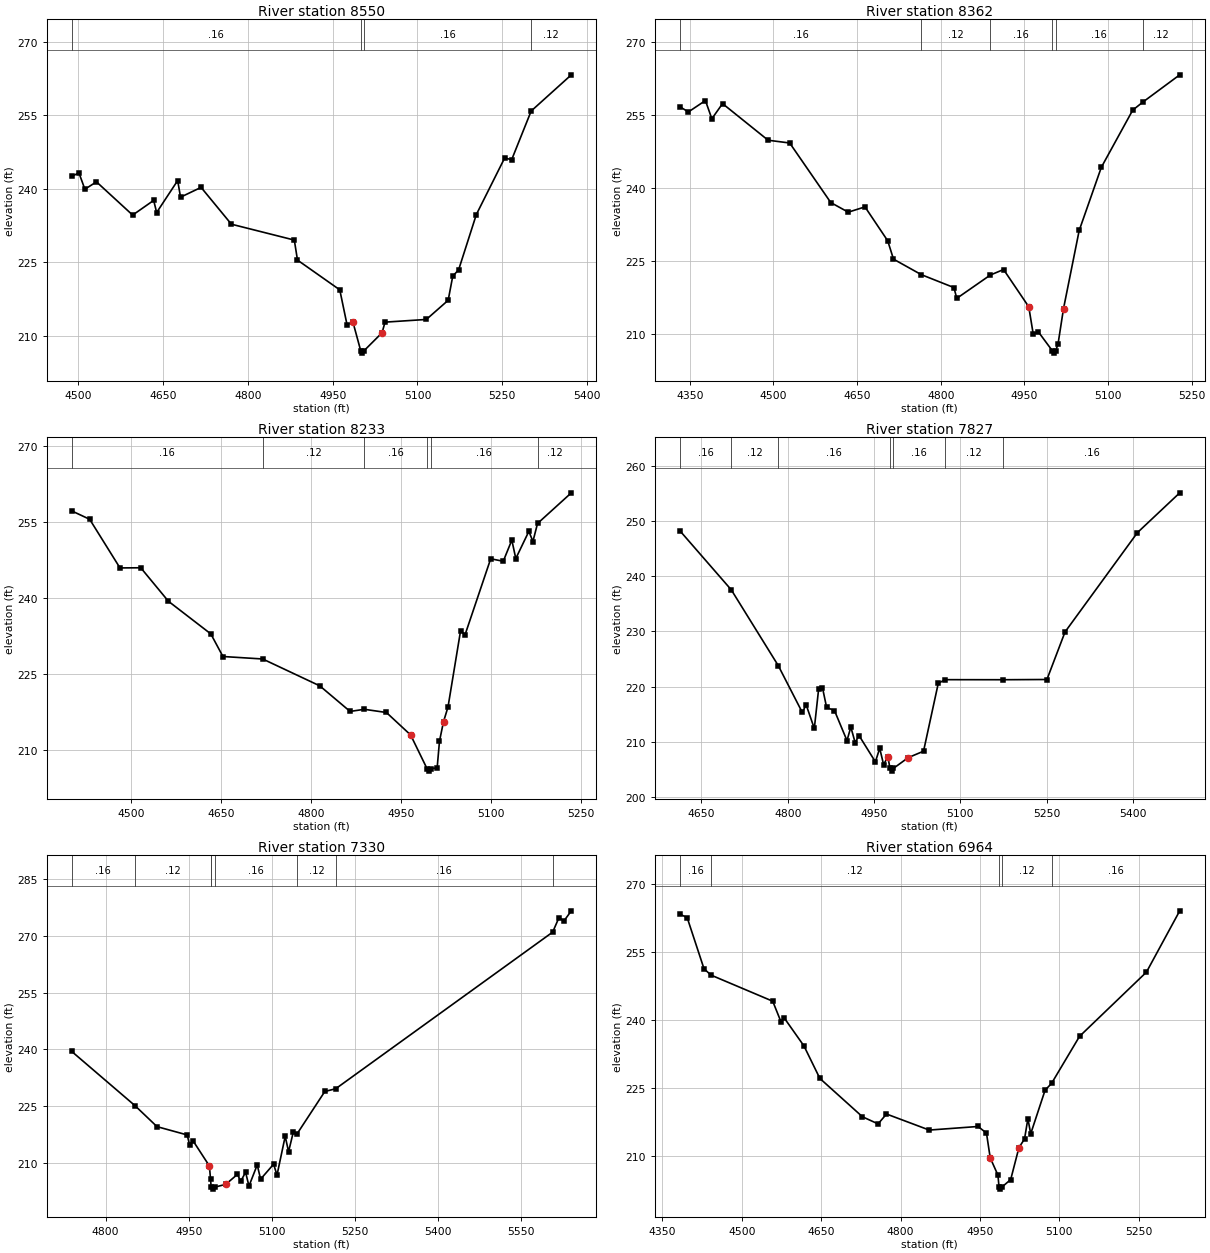
Type RM Length L Ch R = 1 ,8550    ,188,188,188
BEGIN DESCRIPTION:
Mapping XS 34f537d9
END DESCRIPTION:
XS GIS Cut Line= 4
      3727622.58     10598071.08      3727312.69     10598143.99
      3727050.97     10598214.31      3726768.45     10598297.63
#Sta/Elev= 30
  4488.2  242.54  4501.3  243.27  4511.8  239.93  4532.3  241.44  4596.3  234.66
  4633.5  237.66  4638.7  235.18  4675.9   241.7    4681  238.31  4717.3  240.31
  4770.9   232.8  4882.2  229.56  4887.8  225.48  4962.6  219.41  4975.4  212.31
  4985.8  212.86  4999.6     207  5002.3   206.5  5005.6     207  5037.4  210.66
  5042.6  212.82  5115.7  213.37  5154.3  217.28  5162.4   222.2  5172.8   223.5
  5204.1  234.77  5254.2  246.31  5266.6  245.96  5301.1  255.89  5372.1  263.27
#Mann= 4 ,-1 , 0
  4488.2     .16       0  4999.6     .07       0  5005.6     .16       0
  5301.1     .12       0
Bank Sta=4985.8,5037.4
XS Rating Curve= 0 ,0
Exp/Cntr=0.3,0.1

Type RM Length L Ch R = 1 ,8362    ,129,129,129
BEGIN DESCRIPTION:
Mapping XS 79d62f09
END DESCRIPTION:
XS GIS Cut Line= 3
      3727604.35     10597994.26      3727050.97     10598110.14
      3726753.03     10598253.93
#Sta/Elev= 30
  4332.4  256.72  4347.5  255.64  4378.1  257.99  4389.6  254.24  4408.8  257.36
  4490.5  249.82  4529.2  249.25  4602.9  236.98  4634.2     235  4664.2  236.09
    4705   229.1  4715.3  225.33  4765.1  222.14  4823.7  219.47  4828.8  217.25
  4888.9  222.05  4912.7  223.19  4957.9  215.51  4965.9  209.88  4974.9  210.38
  5000.1  206.47  5002.8  205.97  5006.1  206.47  5010.3  207.79  5020.2  215.14
  5048.3  231.23    5088  244.24  5144.3  256.02  5162.3  257.66  5228.6  263.29
#Mann= 6 ,-1 , 0
  4332.4     .16       0  4765.1     .12       0  4888.9     .16       0
  5000.1     .07       0  5006.1     .16       0  5162.3     .12       0
Bank Sta=4957.9,5020.2
XS Rating Curve= 0 ,0
Exp/Cntr=0.3,0.1

Type RM Length L Ch R = 1 ,8233    ,406,406,406
BEGIN DESCRIPTION:
MACK CREEK 12.0
END DESCRIPTION:
XS GIS Cut Line= 3
       3727499.6     10597960.19      3726899.61     10598039.36
      3726749.63     10598210.17
#Sta/Elev= 30
    4401  257.22  4431.2  255.55  4481.7  245.95  4516.3  245.98  4562.4  239.37
    4633  232.93  4653.2  228.47  4719.4  227.98  4814.5  222.68    4865  217.63
  4888.7  218.05  4925.5  217.42  4965.8  212.99  4993.1  206.35  4995.9  205.85
  4999.1  206.35    5010  206.48  5013.9  211.76  5020.6  215.61  5028.1  218.51
    5049  233.54  5056.6   232.8  5099.2  247.76  5120.1  247.26  5134.4  251.44
    5141   247.8  5162.8  253.18  5169.5  251.16  5177.2  254.72  5233.5  260.77
#Mann= 6 ,-1 , 0
    4401     .16       0  4719.4     .12       0  4888.7     .16       0
  4993.1     .07       0  4999.1     .16       0  5177.2     .12       0
Bank Sta=4965.8,5020.6
XS Rating Curve= 0 ,0
Exp/Cntr=0.3,0.1

Type RM Length L Ch R = 1 ,7827    ,497,497,497
BEGIN DESCRIPTION:
MACK CREEK 11.0
END DESCRIPTION:
XS GIS Cut Line= 3
      3727049.59     10597360.21      3726799.61     10597639.36
       3726649.6     10598110.22
#Sta/Elev= 30
  4612.6  248.19  4701.9   237.5  4783.5  223.79  4825.3  215.31    4832  216.69
  4846.2   212.4  4853.7  219.53  4860.4  219.79  4867.6  216.21  4881.3  215.64
    4903  210.21  4909.7  212.66  4917.2  209.84  4923.9  211.13  4952.4  206.36
  4959.9  208.82  4966.6  205.88  4974.1  207.25  4977.8  205.18  4980.5  204.68
  4983.8  205.18  5009.2  207.11  5036.1  208.29  5061.7  220.58  5073.7  221.24
  5174.8  221.23  5250.6  221.27  5282.1  229.88    5408  247.87  5481.5  255.07
#Mann= 7 ,-1 , 0
  4612.6     .16       0  4701.9     .12       0  4783.5     .16       0
  4977.8     .07       0  4983.8     .16       0  5073.7     .12       0
  5174.8     .16       0
Bank Sta=4974.1,5009.2
XS Rating Curve= 0 ,0
Exp/Cntr=0.3,0.1

Type RM Length L Ch R = 1 ,7330    ,366,366,366
BEGIN DESCRIPTION:
MACK CREEK 10.0
END DESCRIPTION:
XS GIS Cut Line= 3
      3726549.61     10597360.18      3726449.61     10597539.36
      3726049.62     10598110.17
#Sta/Elev= 30
  4738.6  239.53  4853.2  225.18  4892.9  219.65  4947.4  217.46  4951.7  214.83
  4957.8  215.95  4987.5  209.27  4989.5  205.77  4990.7  203.67  4993.4  203.17
  4996.7  203.67  5017.1  204.44    5038  207.06  5044.1  205.27  5052.8  207.62
  5058.9  203.98  5073.8  209.56  5079.9   205.8  5103.4  209.75  5109.5  206.86
  5124.3   217.1  5130.4  213.05  5139.1  218.31  5145.8  217.76  5195.8  228.92
  5215.5  229.65  5607.1  270.95  5618.6  274.81  5627.3  273.86  5640.8  276.57
#Mann= 8 ,-1 , 0
  4738.6     .16       0  4853.2     .12       0  4989.5     .16       0
  4990.7     .07       0  4996.7     .16       0  5145.8     .12       0
  5215.5     .16       0  5607.1     .12       0
Bank Sta=4987.5,5017.1
XS Rating Curve= 0 ,0
Exp/Cntr=0.3,0.1

Type RM Length L Ch R = 1 ,6964    ,497,497,497
BEGIN DESCRIPTION:
MACK CREEK 9.0
END DESCRIPTION:
XS GIS Cut Line= 3
      3726399.62     10597110.17      3726099.61     10597639.36
       3725999.6     10597960.21
#Sta/Elev= 30
    4383  263.35  4396.7  262.57  4428.5  251.29  4441.7   249.9  4558.3  244.14
  4574.2  239.52  4579.9  240.47  4617.4  234.26  4647.4   227.1  4727.9  218.64
  4757.4  217.07  4773.3  219.25  4854.1  215.71  4946.3   216.5  4962.2  215.05
  4969.3  209.58  4983.9  205.76  4985.9  203.18  4988.7  202.68  4991.9  203.18
    5008   204.8  5023.6  211.86  5034.1  213.73  5040.5  218.23  5045.8  214.89
    5073  224.52  5085.1  225.99  5138.1  236.39  5264.5  250.56  5327.4  264.08
#Mann= 5 ,-1 , 0
    4383     .16       0  4441.7     .12       0  4985.9     .07       0
  4991.9     .12       0  5085.1     .16       0
Bank Sta=4969.3,5023.6
XS Rating Curve= 0 ,0
Exp/Cntr=0.3,0.1

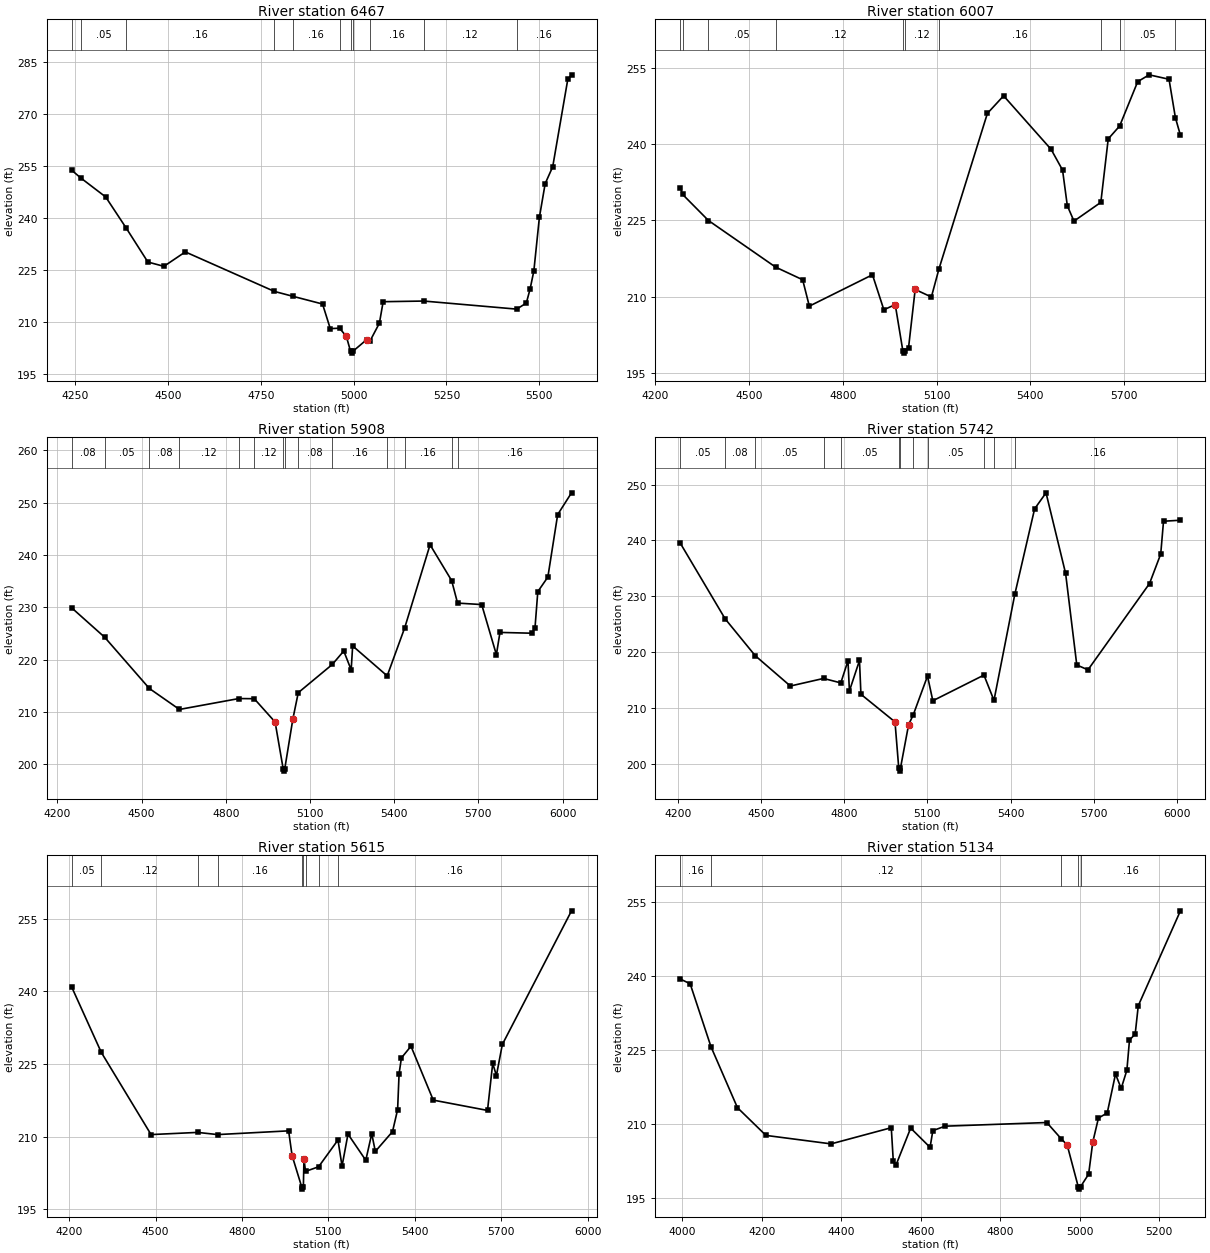
Type RM Length L Ch R = 1 ,6467    ,460,460,460
BEGIN DESCRIPTION:
MACK CREEK 8.0
END DESCRIPTION:
XS GIS Cut Line= 3
      3726249.58     10597060.21      3725649.61     10597539.36
       3725749.6     10598110.15
#Sta/Elev= 30
  4239.6  253.76    4264  251.53  4331.6  246.01  4386.9  237.04  4445.3  227.24
  4488.5     226  4546.2  230.16  4786.4  218.76  4836.7  217.34    4916  215.13
  4936.8  208.04  4961.8  208.16  4980.1  205.81  4991.5  201.47  4994.2  200.97
  4997.5  201.47    5035  204.87  5043.4  204.37  5069.2  209.61  5079.3   215.8
  5188.8  215.99  5439.2  213.66  5465.1  215.41  5475.3  219.47  5485.4  224.68
  5500.3  240.11  5515.9  249.85  5536.2  254.71  5576.8  279.89  5586.9  281.23
#Mann= 11 ,-1 , 0
  4239.6     .16       0    4264     .05       0  4386.9     .16       0
  4786.4     .05       0  4836.7     .16       0  4961.8     .12       0
  4991.5     .07       0  4997.5     .12       0  5043.4     .16       0
  5188.8     .12       0  5439.2     .16       0
Bank Sta=4980.1,5035
XS Rating Curve= 0 ,0
Exp/Cntr=0.3,0.1

Type RM Length L Ch R = 1 ,6007    ,99,99,99
BEGIN DESCRIPTION:
Mapping XS c2dfa161
END DESCRIPTION:
XS GIS Cut Line= 3
      3725914.82     10597141.05      3725347.12      10597359.8
      3724504.54     10597885.11
#Sta/Elev= 30
  4279.9  231.38  4286.5  230.11  4369.6  224.96  4584.8  215.79  4671.3  213.31
  4692.7  208.12  4894.9  214.29  4931.4   207.4  4967.8  208.43  4992.1  199.38
  4994.9  198.88  4998.1  199.38  5010.5  199.96  5031.7   211.4  5083.6  209.92
  5107.9  215.45    5263  246.03  5314.9  249.48  5467.1  238.95  5503.7  234.88
    5519  227.86  5540.3  224.84  5626.3  228.53    5650  241.01  5686.6  243.55
  5744.4  252.27    5781  253.61  5844.7  252.74  5865.1  245.19  5881.2  241.73
#Mann= 10 ,-1 , 0
  4279.9     .08       0  4286.5     .16       0  4369.6     .05       0
  4584.8     .12       0  4992.1     .07       0  4998.1     .12       0
  5107.9     .16       0  5626.3     .08       0  5686.6     .05       0
  5865.1     .16       0
Bank Sta=4967.8,5031.7
XS Rating Curve= 0 ,0
Exp/Cntr=0.3,0.1

Type RM Length L Ch R = 1 ,5908    ,166,166,166
BEGIN DESCRIPTION:
MACK CREEK 7.0
END DESCRIPTION:
XS GIS Cut Line= 4
      3725894.02     10597099.37      3725287.23     10597312.92
      3724810.67     10597471.78      3724255.97     10597781.67
#Sta/Elev= 30
  4250.6  229.93  4368.6  224.29  4527.7  214.51  4634.9   210.5  4846.6  212.58
  4901.4  212.55  4975.7   208.1  5004.3  199.22  5007.1  198.72  5010.3  199.22
  5038.9  208.65  5058.2   213.7  5179.4  219.09  5220.3  221.66  5246.7  218.06
    5252  222.63    5375  216.91  5437.6  226.13  5527.7  241.95  5604.6  235.11
  5625.7  230.81  5711.6  230.53    5764  220.96  5776.7  225.21  5889.8  225.06
  5901.4     226  5911.5     233  5947.3  235.78  5982.3  247.72  6031.6  251.87
#Mann= 14 ,-1 , 0
  4250.6     .08       0  4368.6     .05       0  4527.7     .08       0
  4634.9     .12       0  4846.6     .08       0  4901.4     .12       0
  5004.3     .07       0  5010.3     .12       0  5058.2     .08       0
  5179.4     .16       0    5375     .08       0  5437.6     .16       0
  5604.6     .05       0  5625.7     .16       0
Bank Sta=4975.7,5038.9
XS Rating Curve= 0 ,0
Exp/Cntr=0.3,0.1

Type RM Length L Ch R = 1 ,5742    ,127,127,127
BEGIN DESCRIPTION:
MACK CREEK 6.0
END DESCRIPTION:
XS GIS Cut Line= 4
      3725899.17     10597000.43      3725222.12     10597167.09
      3724651.81     10597346.78      3724149.22     10597411.88
#Sta/Elev= 30
  4210.1  239.47  4371.2  225.96  4479.6  219.36  4606.3  213.92  4725.9  215.28
  4788.1  214.48  4813.9  218.45  4819.1  213.03  4855.4   218.5  4860.6  212.44
  4983.4  207.49    4997  199.17  4999.7  198.67    5003  199.17  5032.4  206.98
  5049.4  208.78  5100.6  215.71  5119.7  211.28    5304  215.88  5340.1  211.35
  5415.5  230.42  5486.6  245.67  5527.7  248.54  5598.3   234.1  5638.6  217.69
  5678.9  216.82  5900.8  232.29  5941.1  237.57  5951.2  243.45  6012.1  243.63
#Mann= 12 ,-1 , 0
  4210.1     .05       0  4371.2     .08       0  4479.6     .05       0
  4725.9     .08       0  4788.1     .05       0    4997     .03       0
    5003     .05       0  5049.4      .1       0  5100.6     .05       0
    5304     .16       0  5340.1     .05       0  5415.5     .16       0
Bank Sta=4983.4,5032.4
XS Rating Curve= 0 ,0
Exp/Cntr=0.3,0.1

Type RM Length L Ch R = 1 ,5615    ,481,481,481
BEGIN DESCRIPTION:
Mapping XS d6a3f6d1
END DESCRIPTION:
XS GIS Cut Line= 3
       3725841.9     10596953.55      3725159.62     10597068.13
      3724146.57     10597320.74
#Sta/Elev= 30
  4208.2  240.99  4311.5  227.41  4484.3  210.43  4646.2  210.88  4715.3  210.43
  4961.9   211.2  4973.9   206.1  5007.1  199.66  5009.8  199.16  5013.1  199.66
  5015.2  205.45  5020.5  202.82    5066  203.78  5133.2  209.31  5147.4  203.92
    5168  210.53  5229.8  205.12  5250.5  210.61  5262.9  206.95  5322.6  211.04
  5340.3  215.59  5345.4  222.99  5353.5  226.27  5386.7  228.69  5464.1  217.55
  5652.4  215.42  5670.5  225.15  5683.3  222.61  5703.9  229.05  5944.1  256.66
#Mann= 9 ,-1 , 0
  4208.2     .05       0  4311.5     .12       0  4646.2     .05       0
  4715.3     .16       0  5007.1     .07       0  5013.1     .16       0
  5020.5     .12       0    5066     .05       0  5133.2     .16       0
Bank Sta=4973.9,5015.2
XS Rating Curve= 0 ,0
Exp/Cntr=0.3,0.1

Type RM Length L Ch R = 1 ,5134    ,874,874,874
BEGIN DESCRIPTION:
MACK CREEK 5.0
END DESCRIPTION:
XS GIS Cut Line= 3
      3725799.66      10596910.2      3724799.61     10596689.36
      3724649.61      10596510.2
#Sta/Elev= 30
  3995.6  239.46    4020  238.52  4072.5  225.74    4139   213.4  4210.7  207.78
  4374.6  206.06    4526  209.34  4531.1  202.54  4538.4  201.87  4574.8  209.26
  4623.6  205.36  4630.6  208.75  4661.3  209.65  4917.3  210.39    4953  207.14
  4968.5  205.84  4996.3  197.39    4999  196.89  5002.3  197.39  5022.5  199.93
  5032.9  206.41  5047.2   211.3  5069.3  212.33  5090.1  220.21  5104.4   217.3
  5118.7  220.99  5125.3   227.1  5139.6  228.33  5147.4  234.07  5253.4   253.3
#Mann= 5 ,-1 , 0
  3995.6     .16       0  4072.5     .12       0    4953     .16       0
  4996.3     .07       0  5002.3     .16       0
Bank Sta=4968.5,5032.9
XS Rating Curve= 0 ,0
Exp/Cntr=0.3,0.1

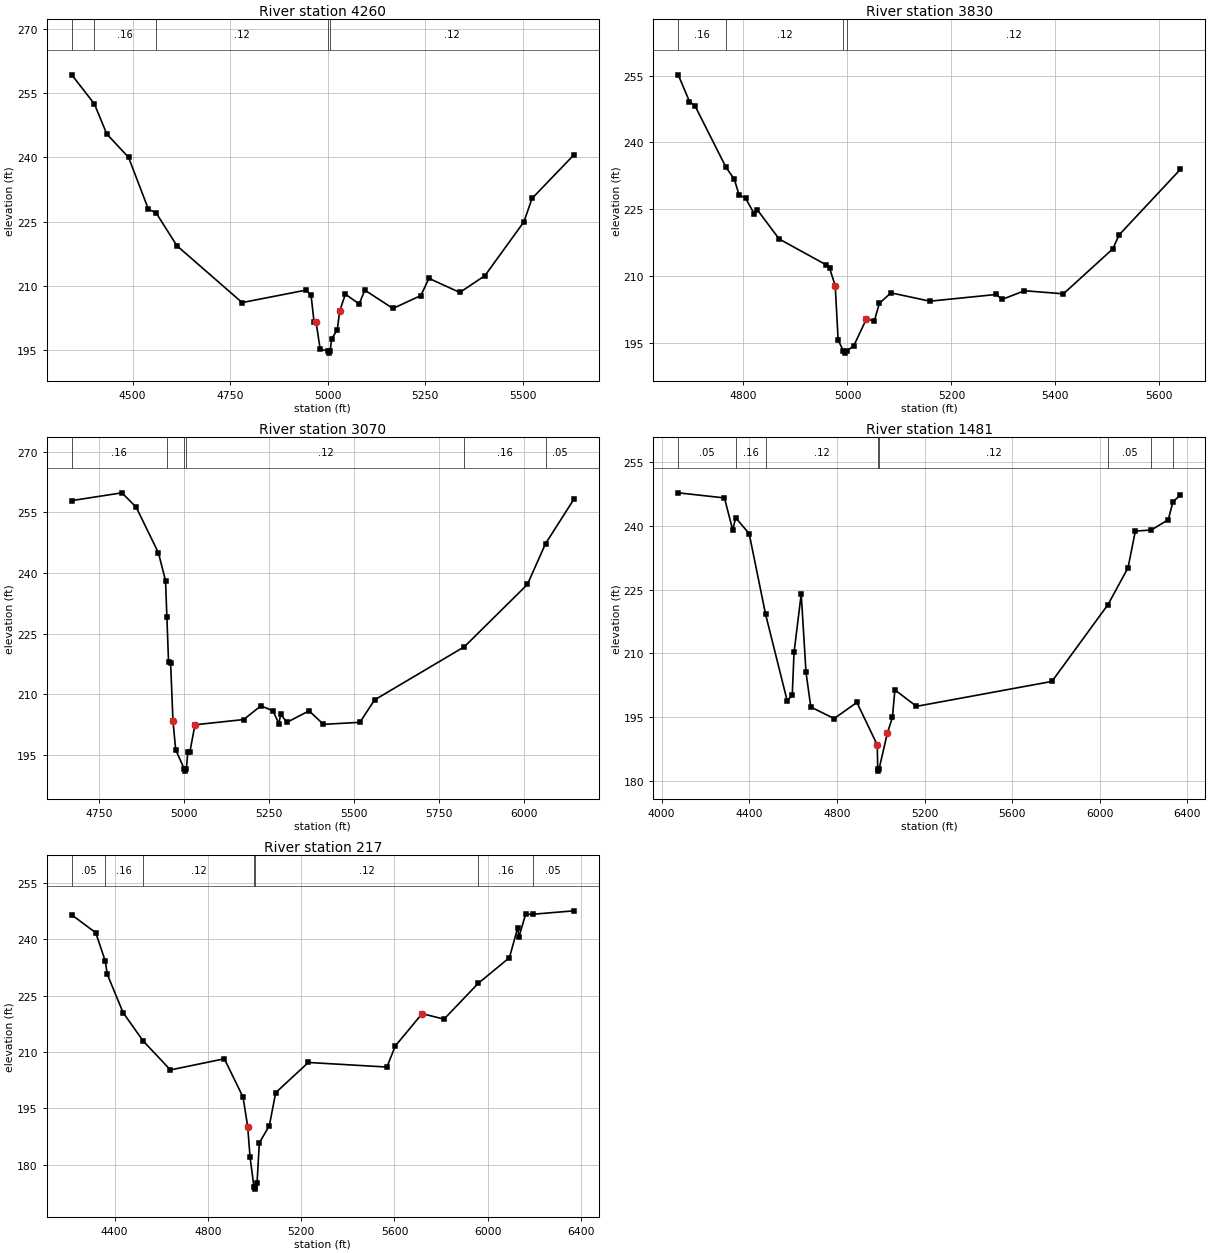
Type RM Length L Ch R = 1 ,4260    ,430,430,430
BEGIN DESCRIPTION:
MACK CREEK 4.0
END DESCRIPTION:
XS GIS Cut Line= 3
      3725899.62     10596860.19      3725299.61     10596689.36
      3724899.61     10596160.18
#Sta/Elev= 30
  4344.1  259.25  4402.1  252.45  4433.9  245.44  4489.7     240  4540.7  227.88
  4560.1  227.08  4613.6  219.39  4780.8  206.13  4944.3  209.03  4957.6  207.86
  4965.4  201.49  4970.6  201.49    4981  195.22  5000.8  194.84  5003.6  194.34
  5006.8  194.84  5010.1  197.65  5024.7  199.74  5030.9  204.12  5045.5  208.09
  5080.9  205.81  5095.4  209.03  5167.5  204.76    5239  207.76  5259.8  211.78
  5338.9  208.49  5403.4  212.41  5503.3  224.97  5524.1  230.42  5631.3  240.57
#Mann= 5 ,-1 , 0
  4344.1     .05       0  4402.1     .16       0  4560.1     .12       0
  5000.8     .07       0  5006.8     .12       0
Bank Sta=4970.6,5030.9
XS Rating Curve= 0 ,0
Exp/Cntr=0.3,0.1

Type RM Length L Ch R = 1 ,3830    ,760,760,760
BEGIN DESCRIPTION:
MACK CREEK 3.0
END DESCRIPTION:
XS GIS Cut Line= 3
      3725849.65     10596510.21      3725549.61     10596389.36
      3724949.65      10596160.2
#Sta/Elev= 30
  4674.5  255.17  4696.1  249.18  4706.9  248.18  4766.5  234.39  4782.4  231.75
  4791.4  228.25  4803.9  227.52  4820.9  223.96  4826.3  224.94  4868.6  218.36
  4957.9  212.63  4965.6  211.81  4976.4  207.91  4982.1  195.64  4992.3  193.26
    4995  192.76  4998.3  193.26  5011.8  194.32  5036.6  200.47  5051.5  199.92
  5061.3  203.92  5083.6  206.28  5158.5  204.41  5285.8  205.91  5297.7  204.82
  5340.5  206.75  5415.4  206.06  5510.3  216.14  5522.5  219.28  5640.2  233.95
#Mann= 4 ,-1 , 0
  4674.5     .16       0  4766.5     .12       0  4992.3     .07       0
  4998.3     .12       0
Bank Sta=4976.4,5036.6
XS Rating Curve= 0 ,0
Exp/Cntr=0.3,0.1

Type RM Length L Ch R = 1 ,3070    ,1589,1589,1589
BEGIN DESCRIPTION:
Mapping XS 4c3519e7
END DESCRIPTION:
XS GIS Cut Line= 3
      3726104.79     10596320.01      3725614.34     10595981.47
       3724794.3     10595656.05
#Sta/Elev= 30
  4668.5  257.94  4816.2  259.86  4858.1  256.31  4923.7     245  4944.6  238.09
  4948.5  229.21  4953.4  218.05  4959.5  217.85  4966.4  203.47  4974.4   196.3
  4999.9   191.5  5002.6     191  5005.9   191.5  5010.2  195.81  5016.3  195.79
  5031.2  202.47  5174.5  203.76  5225.2  207.14    5261  205.94  5278.2  202.73
  5283.6  205.08  5301.8  203.08  5367.3  205.92  5409.4  202.57    5517  203.08
    5560  208.62  5824.5  221.78    6010  237.19  6063.3  247.28  6146.7  258.26
#Mann= 6 ,-1 , 0
  4668.5     .16       0  4948.5     .12       0  4999.9     .07       0
  5005.9     .12       0  5824.5     .16       0  6063.3     .05       0
Bank Sta=4966.4,5031.2
XS Rating Curve= 0 ,0
Exp/Cntr=0.3,0.1

Type RM Length L Ch R = 1 ,1481    ,1264,1264,1264
BEGIN DESCRIPTION:
MACK CREEK 1.0
END DESCRIPTION:
XS GIS Cut Line= 3
      3727062.15     10596006.28      3725989.28     10595527.13
      3724874.73     10595461.16
#Sta/Elev= 30
  4075.8  247.76  4286.7  246.56  4324.4  239.02  4338.1  241.89  4399.5  238.15
  4474.3   219.2  4572.9  198.83  4596.1  200.06  4604.3  210.18  4637.1  223.92
    4659  205.48  4680.9  197.33  4787.3  194.62  4891.1  198.41    4984  188.43
  4986.4  182.74  4989.2  182.24  4992.4  182.74  5030.4  191.23  5053.3  194.87
  5064.6  201.37  5162.9  197.49  5781.4  203.36  6037.4  221.46  6128.5   230.1
  6162.1  238.75  6235.2  239.01  6312.3  241.43    6334  245.68  6367.3  247.21
#Mann= 8 ,-1 , 0
  4075.8     .05       0  4338.1     .16       0  4474.3     .12       0
  4986.4     .07       0  4992.4     .12       0  6037.4     .05       0
  6235.2     .08       0    6334     .05       0
Bank Sta=4984,5030.4
XS Rating Curve= 0 ,0
Exp/Cntr=0.3,0.1

Type RM Length L Ch R = 1 ,217     ,0,0,0
BEGIN DESCRIPTION:
MACK CREEK 2.0
END DESCRIPTION:
XS GIS Cut Line= 4
      3726960.88     10595388.46      3726440.01     10595082.89
      3725787.23     10595062.05      3724919.22     10595284.26
#Sta/Elev= 30
  4216.1  246.48  4318.8  241.76  4359.8  234.21  4368.3   230.7    4436  220.52
  4521.9  212.98  4639.2  205.25  4870.4  208.22  4950.5  198.02  4970.5  190.19
  4980.5  182.07  4997.5  174.05  5000.2  173.55  5003.5  174.05  5010.5  175.07
  5020.5  185.87  5063.4  190.44  5090.5   199.2  5230.6  207.24  5567.5  206.02
  5603.2   211.6  5718.4  220.22  5812.4  218.76  5958.6  228.25  6092.9  235.12
  6128.5  243.09  6133.7  240.62  6162.2  246.66  6192.9  246.66  6369.1  247.57
#Mann= 7 ,-1 , 0
  4216.1     .05       0  4359.8     .16       0  4521.9     .12       0
  4997.5     .07       0  5003.5     .12       0  5958.6     .16       0
  6192.9     .05       0
Bank Sta=4970.5,5718.4
XS Rating Curve= 0 ,0
Exp/Cntr=0.3,0.1

Chan Stop Cuts=-1
Use User Specified Reach Order=0
Composite Channel Slope=5