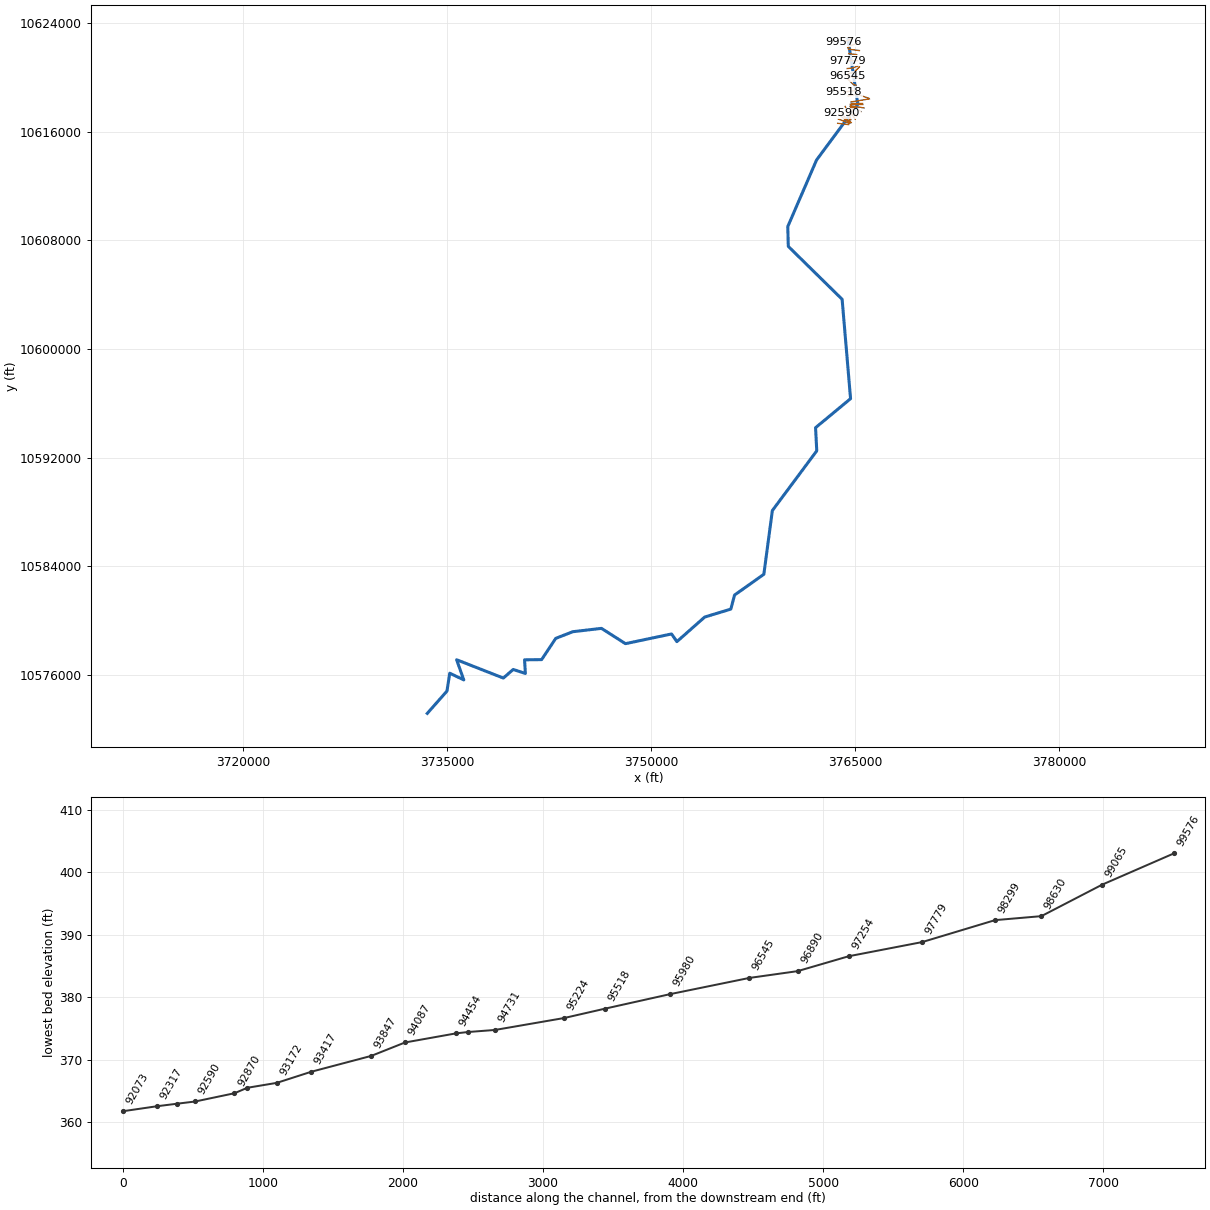
--- MANSON CREEK.prj (project) ---

Proj Title=MANSON CREEK Base Level Engineering
Current Plan=p01
Default Exp/Contr=0.3,0.1
English Units
Geom File=g01
Flow File=f01
Plan File=p01
Y Axis Title=Elevation
X Axis Title(PF)=Main Channel Distance
X Axis Title(XS)=Station
BEGIN DESCRIPTION:
MANSON CREEK
END DESCRIPTION:
DSS File=dss
DSS Export Rating Curves= 0
DSS Export Rating Curve Sorted= 0
DSS Export Volume Flow Curves= 0
DXF OffsetX= 0
DXF OffsetY= 0
DXF ScaleX= 1
DXF ScaleY= 10

--- MANSON CREEK.p01 (plan) ---

Plan Title=Multiple Run
Program Version=4.10
Short Identifier=Multiple Run
Geom File=g01
Flow File=f01
Subcritical Flow
K Sum by GR= 0
Std Step Tol= 0.01
Critical Tol= 0.01
Num of Std Step Trials= 20
Max Error Tol= 0.3
Flow Tol Ratio= 0.001
Split Flow NTrial= 30
Split Flow Tol= 0.02
Split Flow Ratio= 0.02
Log Output Level= 0
Friction Slope Method= 1
Unsteady Friction Slope Method= 2
Unsteady Bridges Friction Slope Method= 1
Parabolic Critical Depth
Global Vel Dist= 1 , 1 , 1
Global Log Level= 0
CheckData=True
Encroach Param=-1 ,0,0, 0
BEGIN DESCRIPTION:
Multiple Run
END DESCRIPTION:
Computation Interval=1HOUR
Output Interval=1HOUR
Run HTab= 0
Run UNet= 0
Run PostProcess= 0
Run WQNet= 0
UNET Theta= 1
UNET Theta Warmup= 1
UNET ZTol= 0.02
UNET ZSATol= 0.05
UNET MxIter= 20
UNET MaxInSteps= 0
UNET DtIC= 0
UNET DtMin= 0
UNET MaxCRTS= 20
UNET WFStab= 2
UNET SFStab= 1
UNET WFX= 1
UNET SFX= 1
UNET DSS MLevel= 4
UNET DZMax Abort= 100
UNET Convert EG Bridges= 0
UNET Use Existing IB Tables=-1
UNET Froude Reduction=False
UNET Froude Limit= 1
UNET Froude Power= 10
UNET Time Slicing=0,0, 5
UNET Junction Losses=0
Instantaneous Interval=1HOUR
DSS File=dss
Write IC File= 0
Write IC File at Sim End=0
Echo Input=False
Echo Parameters=False
Echo Output=False
Write Detailed= 0
WQ AD Non Conservative
WQ ULTIMATE=-1
WQ Max Comp Step=1HOUR
WQ Output Interval=15MIN
WQ Output Selected Increments= 0
WQ Output face flow=0
WQ Output face velocity=0
WQ Output face area=0
WQ Output face dispersion=0
WQ Output cell volume=0
WQ Output cell surface area=0
WQ Output cell continuity=0
WQ Output cumulative cell continuity=0
WQ Output face conc=0
WQ Output face dconc_dx=0
WQ Output face courant=0
WQ Output face peclet=0
WQ Output face adv mass=0
WQ Output face disp mass=0
WQ Output cell mass=0
WQ Output cell source sink temp=0
WQ Output cell source sink nsm=0
WQ Output MaxMinRange=-1
WQ Daily Max Min Mean=-1
WQ Daily Range=0
WQ Daily Time=0
WQ Create Restart=0
WQ Fixed Restart=0
WQ System Summary=0
WQ Use Fixed Temperature=0
Sorting and Armoring Iterations= 10
XS Update Threshold= 0.02
Hydraulics Update Threshold= 0.02
Energy Slope Method= 1
Volume Change Method= 0
XS Weighting Method= 0
Number of US Weighted Cross Sections= 1
Number of DS Weighted Cross Sections= 1
Upstream XS Weight=0.25
Main XS Weight=0.5
Downstream XS Weight=0.25
Number of DS XS's Weighted with US Boundary= 1
Upstream Boundary Weight= 1
Weight of XSs Associated with US Boundary= 0
Number of US XS's Weighted with DS Boundary= 1
Downstream Boundary Weight= 0.5
Weight of XSs Associated with DS Boundary= 0.5
Sediment Output Level= 4
Mass or Volume Output= 0
Output Increment Type= 1
Profile and TS Output Increment= 10
XS Output Flag= 0
XS Output Increment= 10
Disregard all LS=0
Disregard all Conn=0
Disregard all Breaches=0
Disregard all Pumps=0

--- MANSON CREEK.f01 (steady flow) ---

Flow Title=Multiple
Program Version=4.10
Number of Profiles= 7
Profile Names=10-year,25-year,50-year,1pct_min,100-year,1pct_plu,500-year
River Rch & RM=MANSON CREEK,Reach-1         ,99576
     737    1012    1242    1121    1516    2051    2266
River Rch & RM=MANSON CREEK,Reach-1         ,98630
     916    1271    1571    1427    1930    2609    2920
River Rch & RM=MANSON CREEK,Reach-1         ,95224
    1391    1965    2458    2255    3049    4123    4711
River Rch & RM=MANSON CREEK,Reach-1         ,94731
    1391    1965    2458    2255    3049    4123    4711
River Rch & RM=MANSON CREEK,Reach-1         ,88662
    1880    2682    3378    3116    4214    5699    6584
River Rch & RM=MANSON CREEK,Reach-1         ,88237
    1880    2682    3378    3116    4214    5699    6584
River Rch & RM=MANSON CREEK,Reach-1         ,80352
    2938    4268    5440    5073    6861    9278   10957
River Rch & RM=MANSON CREEK,Reach-1         ,78121
    3079    4468    5692    5302    7170    9697   11427
River Rch & RM=MANSON CREEK,Reach-1         ,77561
    3079    4468    5692    5302    7170    9697   11427
River Rch & RM=MANSON CREEK,Reach-1         ,72037
    4813    7081    9106    8554   11569   15645   18745
River Rch & RM=MANSON CREEK,Reach-1         ,70395
    4861    7152    9198    8639   11683   15800   18928
River Rch & RM=MANSON CREEK,Reach-1         ,65911
    4861    7152    9198    8639   11683   15800   18928
River Rch & RM=MANSON CREEK,Reach-1         ,64252
    4766    6992    8973    8410   11373   15381   18346
River Rch & RM=MANSON CREEK,Reach-1         ,58235
    4799    7041    9038    8472   11457   15494   18485
River Rch & RM=MANSON CREEK,Reach-1         ,57653
    5939    8762   11288   10616   14357   19417   23315
River Rch & RM=MANSON CREEK,Reach-1         ,56090
    5939    8762   11288   10616   14357   19417   23315
River Rch & RM=MANSON CREEK,Reach-1         ,55549
    5939    8762   11288   10616   14357   19417   23315
River Rch & RM=MANSON CREEK,Reach-1         ,54470
    5939    8762   11288   10616   14357   19417   23315
River Rch & RM=MANSON CREEK,Reach-1         ,53975
    5939    8762   11288   10616   14357   19417   23315
River Rch & RM=MANSON CREEK,Reach-1         ,51935
    5796    8518   10946   10265   13883   18775   22419
River Rch & RM=MANSON CREEK,Reach-1         ,45305
    5884    8649   11115   10425   14098   19066   22768
River Rch & RM=MANSON CREEK,Reach-1         ,43667
    5908    8684   11159   10465   14153   19140   22854
River Rch & RM=MANSON CREEK,Reach-1         ,41136
    6121    8999   11567   10849   14672   19842   23697
River Rch & RM=MANSON CREEK,Reach-1         ,38725
    6121    8989   11544   10818   14631   19786   23588
River Rch & RM=MANSON CREEK,Reach-1         ,37246
    6169    9057   11629   10895   14735   19927   23745
River Rch & RM=MANSON CREEK,Reach-1         ,36485
    6169    9057   11629   10895   14735   19927   23745
River Rch & RM=MANSON CREEK,Reach-1         ,32970
    6209    9110   11692   10949   14808   20026   23840
River Rch & RM=MANSON CREEK,Reach-1         ,31299
    6941   10190   13083   12253   16571   22410   26678
River Rch & RM=MANSON CREEK,Reach-1         ,29545
    6941   10190   13083   12253   16571   22410   26678
River Rch & RM=MANSON CREEK,Reach-1         ,23653
    7018   10300   13223   12381   16744   22644   26946
River Rch & RM=MANSON CREEK,Reach-1         ,22567
    7018   10300   13223   12381   16744   22644   26946
River Rch & RM=MANSON CREEK,Reach-1         ,18128
    7042   10334   13266   12421   16798   22717   27027
River Rch & RM=MANSON CREEK,Reach-1         ,14912
    7108   10411   13346   12477   16874   22820   27069
Boundary for River Rch & Prof#=MANSON CREEK,Reach-1         , 1
Up Type= 0
Dn Type= 3
Dn Slope=0.001
Boundary for River Rch & Prof#=MANSON CREEK,Reach-1         , 2
Up Type= 0
Dn Type= 3
Dn Slope=0.001
Boundary for River Rch & Prof#=MANSON CREEK,Reach-1         , 3
Up Type= 0
Dn Type= 3
Dn Slope=0.001
Boundary for River Rch & Prof#=MANSON CREEK,Reach-1         , 4
Up Type= 0
Dn Type= 3
Dn Slope=0.001
Boundary for River Rch & Prof#=MANSON CREEK,Reach-1         , 5
Up Type= 0
Dn Type= 3
Dn Slope=0.001
Boundary for River Rch & Prof#=MANSON CREEK,Reach-1         , 6
Up Type= 0
Dn Type= 3
Dn Slope=0.001
Boundary for River Rch & Prof#=MANSON CREEK,Reach-1         , 7
Up Type= 0
Dn Type= 3
Dn Slope=0.001
DSS Import GetInterval= 0
DSS Import GetPeak= 0
DSS Import FillOption= 0

--- MANSON CREEK.g01 (geometry) ---

Geom Title=Existing Conditions
Program Version=4.10

River Reach=MANSON CREEK    ,Reach-1
Reach XY= 30
      3764459.29     10622800.27      3765185.75       10618013.
        3762149.       10613910.        3760030.       10609010.
       3760069.5       10607550.        3764027.       10603659.
      3764647.75       10596346.        3762074.       10594213.
       3762162.5       10592508.        3758897.       10588114.
      3758271.25       10583424.      3756117.75       10581897.
      3755843.75       10580864.        3753921.       10580277.
      3751878.25       10578471.        3751484.       10579035.
       3748096.5       10578320.      3746332.25       10579446.
      3744224.25       10579200.       3742969.5       10578710.
      3741931.25       10577146.        3740675.       10577132.
      3740736.75       10576127.      3739842.25       10576422.
      3739114.75       10575790.      3735679.25       10577138.
       3736206.5       10575656.        3735174.       10576145.
      3734968.75       10574828.       3733522.5       10573191.

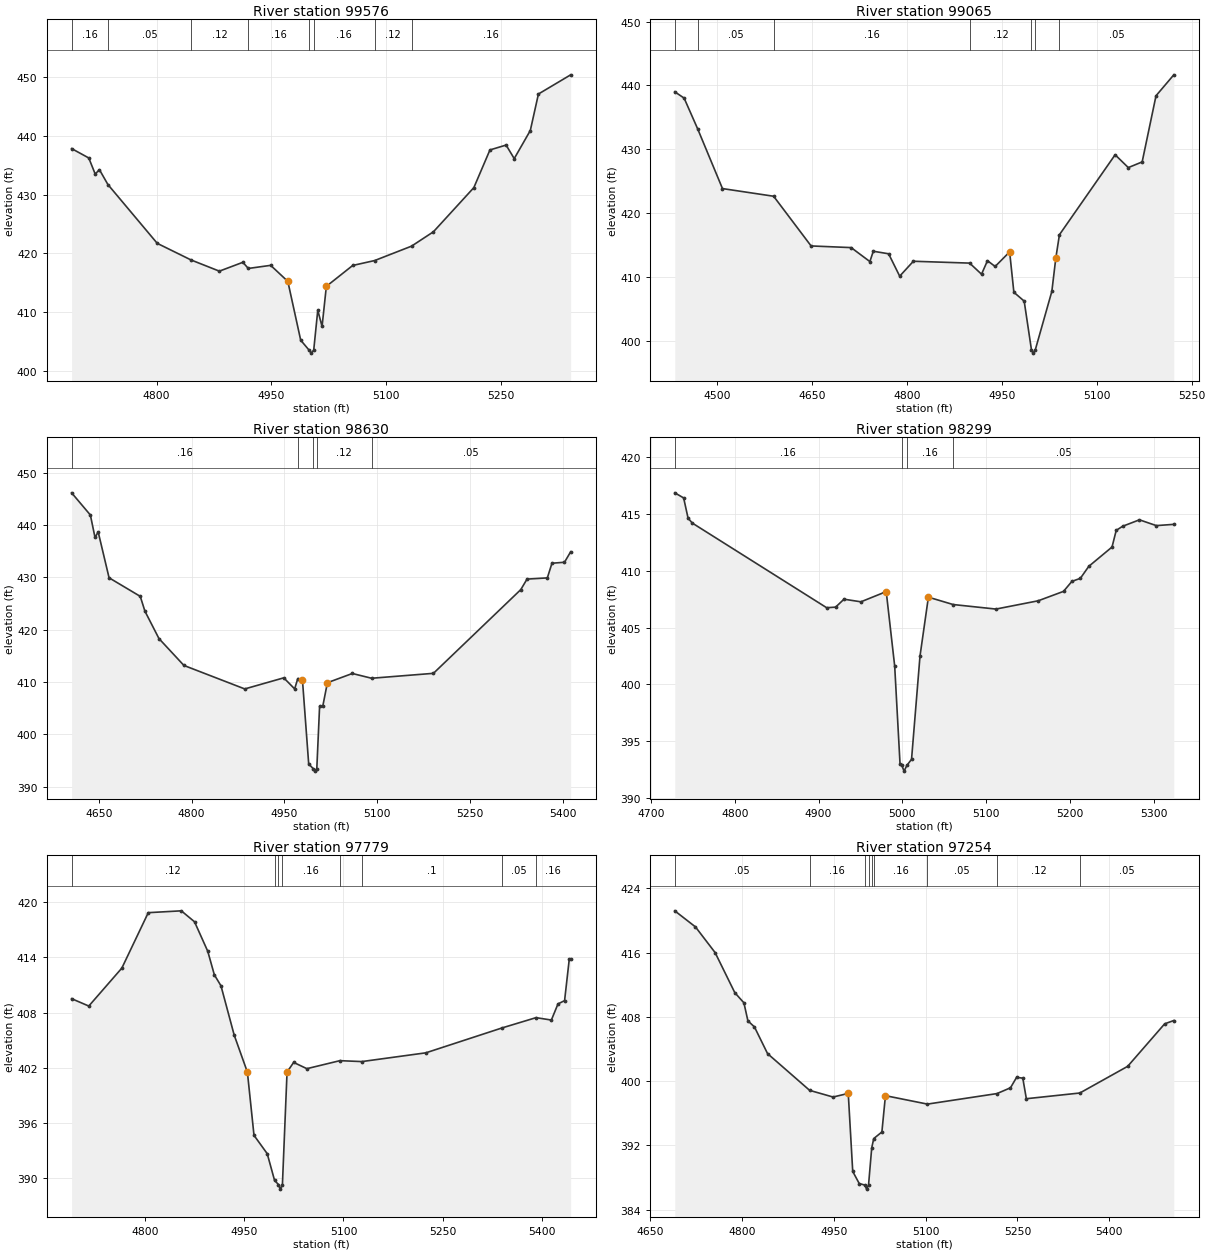
Type RM Length L Ch R = 1 ,99576   ,511,511,511
BEGIN DESCRIPTION:
MANSON CREEK 153.0
END DESCRIPTION:
XS GIS Cut Line= 3
      3764749.61     10622860.19      3764449.61     10622710.19
      3764149.65      10622610.2
#Sta/Elev= 30
  4689.1  437.88  4711.5  436.28  4719.9  433.54  4725.4  434.29  4736.5  431.75
  4800.9  421.73    4845   418.9    4882  416.99  4912.7   418.5  4919.8  417.45
    4949  417.98  4971.4  415.25  4988.2  405.23  4999.2  403.52  5001.9  403.02
  5005.2  403.52  5010.5  410.33  5016.1  407.56  5021.7   414.4  5056.1  417.96
  5084.8   418.8  5132.9  421.25  5161.5   423.7  5214.3  431.23  5235.3  437.65
  5256.4  438.48    5267  436.17    5288  440.96  5298.6  447.18  5340.7  450.45
#Mann= 8 ,-1 , 0
  4689.1     .16       0  4736.5     .05       0    4845     .12       0
  4919.8     .16       0  4999.2     .07       0  5005.2     .16       0
  5084.8     .12       0  5132.9     .16       0
Bank Sta=4971.4,5021.7
XS Rating Curve= 0 ,0
Exp/Cntr=0.3,0.1

Type RM Length L Ch R = 1 ,99065   ,435,435,435
BEGIN DESCRIPTION:
MANSON CREEK 152.0
END DESCRIPTION:
XS GIS Cut Line= 3
      3765149.62     10622510.19      3764649.61     10622310.19
      3764449.63      10622160.2
#Sta/Elev= 30
  4433.2  438.99    4448     438  4469.4  433.18  4508.6  423.82  4589.4  422.62
  4648.6  414.83  4711.9  414.57  4741.5  412.38  4746.9     414  4771.1   413.6
  4788.6  410.09  4810.2  412.43  4899.1  412.14  4917.9   410.4  4927.3  412.52
  4939.4  411.61  4962.3   413.9    4969  407.57  4985.3  406.18  4996.8  398.53
  4999.6  398.03  5002.8  398.53    5029  407.71  5035.3  412.95    5041  416.59
    5129  429.12  5149.8  427.11  5171.7     428  5193.6  438.37  5221.7  441.65
#Mann= 7 ,-1 , 0
  4433.2     .16       0  4469.4     .05       0  4589.4     .16       0
  4899.1     .12       0  4996.8     .07       0  5002.8     .12       0
    5041     .05       0
Bank Sta=4962.3,5035.3
XS Rating Curve= 0 ,0
Exp/Cntr=0.3,0.1

Type RM Length L Ch R = 1 ,98630   ,331,331,331
BEGIN DESCRIPTION:
MANSON CREEK 151.0
END DESCRIPTION:
XS GIS Cut Line= 3
      3765299.63     10621960.19      3764899.61     10622010.19
      3764499.66     10622060.18
#Sta/Elev= 30
  4606.2  446.14  4636.5   441.9    4644  437.61  4649.1  438.68  4666.7  429.91
  4717.1  426.36  4724.6  423.54  4747.3   418.3  4787.6  413.17  4885.9  408.68
  4948.9   410.8  4966.5  408.69  4971.6  410.67  4979.1   410.4  4989.2  394.34
  4996.3  393.48    4999  392.98  5002.3  393.48  5006.8  405.36  5011.9  405.36
  5019.4  409.87  5059.7  411.63  5090.8  410.72  5190.7  411.66  5331.8  427.65
  5341.9  429.66  5374.7  429.89  5382.2  432.69  5402.4  432.88  5412.4  434.88
#Mann= 5 ,-1 , 0
  4606.2     .16       0  4971.6     .12       0  4996.3     .07       0
  5002.3     .12       0  5090.8     .05       0
Bank Sta=4979.1,5019.4
XS Rating Curve= 0 ,0
Exp/Cntr=0.3,0.1

Type RM Length L Ch R = 1 ,98299   ,520,520,520
BEGIN DESCRIPTION:
MANSON CREEK 150.0
END DESCRIPTION:
XS GIS Cut Line= 2
      3765100.13     10621663.27      3764508.89     10621733.59
#Sta/Elev= 30
  4728.4  416.88    4739  416.43  4744.3  414.64  4749.4  414.21  4909.6  406.75
  4920.3   406.8  4930.3   407.5  4950.5  407.27  4980.7  408.17  4990.8   401.6
  4997.2  392.94  4999.3  392.84    5002  392.34  5005.3  392.84  5010.9  393.38
    5021  402.49    5031  407.68  5060.5  407.03  5111.6  406.63    5162  407.36
  5192.2  408.19  5202.2  409.07  5212.3  409.34  5222.4   410.4  5250.1   412.1
  5255.1  413.57  5262.7  413.93  5282.8   414.5  5302.9  413.99  5323.8   414.1
#Mann= 4 ,-1 , 0
  4728.4     .16       0  4999.3     .07       0  5005.3     .16       0
  5060.5     .05       0
Bank Sta=4980.7,5031
XS Rating Curve= 0 ,0
Exp/Cntr=0.3,0.1

Type RM Length L Ch R = 1 ,97779   ,525,525,525
BEGIN DESCRIPTION:
MANSON CREEK 149.0
END DESCRIPTION:
XS GIS Cut Line= 2
      3765175.62     10621210.15      3764420.42     10621212.76
#Sta/Elev= 30
  4688.6  409.51  4714.6  408.71  4764.6  412.83  4804.6  418.85  4854.6  419.05
  4874.6  417.86  4894.6  414.66  4904.6   412.1  4914.6  410.91  4934.6  405.56
  4954.6  401.53  4964.6  394.67  4984.6  392.68  4995.7  389.78  5001.6  389.33
  5004.4  388.83  5007.6  389.33  5014.6  401.54  5024.6  402.59  5044.6  401.91
  5094.6  402.78  5127.7  402.68  5224.6  403.63  5340.2  406.34  5391.4  407.45
  5414.6  407.19  5424.6  408.94  5434.6   409.3  5441.7  413.81  5443.8  413.81
#Mann= 8 ,-1 , 0
  4688.6     .12       0  4995.7     .16       0  5001.6     .07       0
  5007.6     .16       0  5094.6     .05       0  5127.7      .1       0
  5340.2     .05       0  5391.4     .16       0
Bank Sta=4954.6,5014.6
XS Rating Curve= 0 ,0
Exp/Cntr=0.3,0.1

Type RM Length L Ch R = 1 ,97254   ,364,364,364
BEGIN DESCRIPTION:
MANSON CREEK 148.0
END DESCRIPTION:
XS GIS Cut Line= 3
      3765191.25     10620824.74      3764826.64     10620686.71
       3764404.8     10620637.24
#Sta/Elev= 30
  4690.6  421.19  4724.4  419.19  4756.5  415.99  4788.6  411.01  4803.5  409.74
    4810   407.5  4820.7  406.74  4842.1  403.42  4910.8  398.85    4949  398.02
  4973.8  398.47  4981.1  388.76  4991.7  387.26  5000.9  387.06  5003.7  386.56
  5006.9  387.06  5012.1  391.69  5015.4  392.85  5028.7  393.67  5034.5  398.19
    5103  397.14  5216.6  398.45  5238.6  399.17  5248.6  400.47  5258.7  400.37
  5264.5  397.81  5351.8  398.52  5429.9  401.84  5490.3  407.13  5505.2  407.54
#Mann= 9 ,-1 , 0
  4690.6     .05       0  4910.8     .16       0  5000.9     .07       0
  5006.9     .16       0  5012.1     .05       0  5015.4     .16       0
    5103     .05       0  5216.6     .12       0  5351.8     .05       0
Bank Sta=4973.8,5034.5
XS Rating Curve= 0 ,0
Exp/Cntr=0.3,0.1

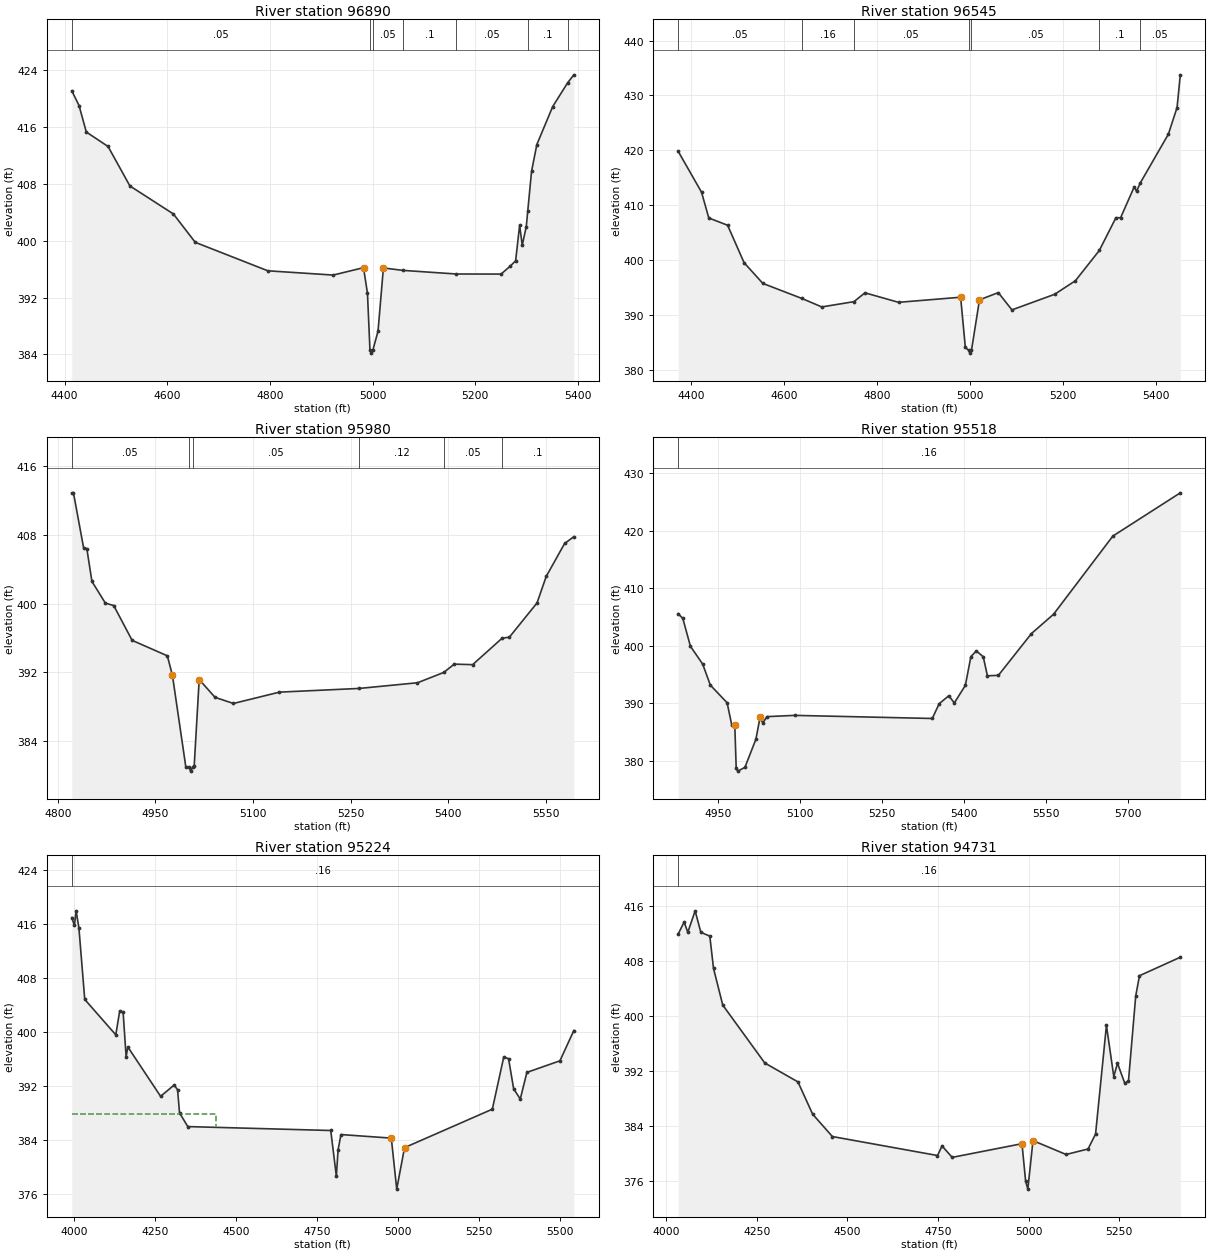
Type RM Length L Ch R = 1 ,96890   ,345,345,345
BEGIN DESCRIPTION:
MANSON CREEK 147.0
END DESCRIPTION:
XS GIS Cut Line= 3
      3765299.63     10620760.21      3764899.61     10620360.19
      3764499.64      10620260.2
#Sta/Elev= 30
    4414  421.12  4428.2  419.03  4442.3  415.31  4484.7  413.27  4527.2  407.72
    4612  403.77  4654.5  399.78  4795.9  395.77  4923.2  395.17  4982.3  396.21
    4990  392.61  4994.8  384.68  4997.5  384.18  5000.8  384.68  5010.6  387.28
    5021  396.17  5058.9  395.83    5163  395.32  5250.3  395.31  5268.3  396.44
  5278.6  397.18  5286.4  402.19  5291.5  399.39  5299.3  401.97  5302.2  404.16
  5309.6  409.76  5319.9  413.54  5350.8  418.89    5380  422.25    5392  423.36
#Mann= 7 ,-1 , 0
    4414     .05       0  4994.8     .03       0  5000.8     .05       0
  5058.9      .1       0    5163     .05       0  5302.2      .1       0
    5380     .05       0
Bank Sta=4982.3,5021
XS Rating Curve= 0 ,0
Exp/Cntr=0.3,0.1

Type RM Length L Ch R = 1 ,96545   ,565,565,565
BEGIN DESCRIPTION:
MANSON CREEK 146.0
END DESCRIPTION:
XS GIS Cut Line= 3
      3765488.11     10619858.59      3764938.62     10620001.82
      3764432.72     10620079.65
#Sta/Elev= 30
  4372.8  419.82  4422.9  412.39  4438.5   407.7    4479  406.37  4514.3  399.57
  4554.8  395.78  4638.8  393.04  4681.5   391.5  4750.6  392.46  4774.3  394.07
  4846.6  392.34  4980.1  393.27  4990.2  384.15  4997.4  383.59  5000.1  383.09
  5003.4  383.59  5020.6  392.79  5061.1  394.11  5090.4  390.96  5182.5  393.81
  5226.9  396.27  5278.3  401.78    5314  407.74  5324.1  407.74  5353.4  413.36
  5358.5  412.56  5366.1  414.03  5426.8  422.95  5445.5  427.81  5452.5  433.76
#Mann= 7 ,-1 , 0
  4372.8     .05       0  4638.8     .16       0  4750.6     .05       0
  4997.4     .03       0  5003.4     .05       0  5278.3      .1       0
  5366.1     .05       0
Bank Sta=4980.1,5020.6
XS Rating Curve= 0 ,0
Exp/Cntr=0.3,0.1

Type RM Length L Ch R = 1 ,95980   ,462,462,462
BEGIN DESCRIPTION:
MANSON CREEK 145.0
END DESCRIPTION:
XS GIS Cut Line= 3
      3765049.64     10619410.18      3764849.61     10619460.19
      3764449.59     10619860.21
#Sta/Elev= 30
  4821.3  412.91  4823.9  412.91  4839.4  406.54  4844.5  406.39  4852.3  402.59
  4872.9  400.07  4885.8  399.78  4914.1  395.73  4968.2  393.93    4976  391.68
  4996.6  381.01  5001.3     381    5004   380.5  5007.3     381  5009.5  381.06
  5017.2  391.17  5041.6  389.09  5069.9  388.38  5140.6   389.7  5263.1  390.13
  5352.8  390.79  5393.1  391.99  5409.3  392.96  5437.6   392.9  5482.8  395.97
  5494.2  396.11  5536.6  400.09  5550.7  403.17    5579  407.01  5593.2   407.8
#Mann= 6 ,-1 , 0
  4821.3     .05       0  5001.3     .03       0  5007.3     .05       0
  5263.1     .12       0  5393.1     .05       0  5482.8      .1       0
Bank Sta=4976,5017.2
XS Rating Curve= 0 ,0
Exp/Cntr=0.3,0.1

Type RM Length L Ch R = 1 ,95518   ,294,294,294
BEGIN DESCRIPTION:
MANSON CREEK 144.0
END DESCRIPTION:
XS GIS Cut Line= 3
      3765049.59     10619060.18      3764949.61     10619010.19
      3764149.62     10618910.19
#Sta/Elev= 30
  4877.7  405.55  4886.1  404.72    4900  399.89  4922.4  396.79  4936.4  393.14
  4967.1  390.07  4975.5  386.23  4981.1  386.23  4983.7  378.69  4986.4  378.19
  4999.6  378.84  5019.7  383.73  5027.3  387.54  5032.3  386.55  5039.9  387.66
  5090.3  387.88  5342.2  387.34  5354.8  389.91  5372.4  391.29  5382.5  390.04
  5402.7   393.1  5412.8   398.1  5422.8  399.08  5435.4  398.07    5443  394.76
  5463.1  394.84  5523.6  402.11  5563.9  405.45  5672.3  419.04  5795.7  426.56
#Mann= 1 ,-1 , 0
  4877.7     .16       0
Bank Sta=4981.1,5027.3
XS Rating Curve= 0 ,0
Exp/Cntr=0.3,0.1

Type RM Length L Ch R = 1 ,95224   ,493,493,493
BEGIN DESCRIPTION:
MANSON CREEK 143.0
END DESCRIPTION:
XS GIS Cut Line= 3
      3765970.53     10618462.06      3765102.52     10618744.16
      3764477.54     10618613.96
#Sta/Elev= 30
  3991.8  416.93    4000  415.77  4005.2  417.93  4013.8  415.42  4031.9   404.8
  4127.8  399.55    4140  403.12  4150.5  402.86  4159.7  396.31    4165  397.75
  4266.2  390.44  4308.2  392.11  4318.7   391.4  4324.7  387.98  4350.3  385.95
  4791.9  385.37  4809.2   378.6  4814.5  382.49  4823.4  384.77    4979  384.24
  4995.7  376.68  5019.8  382.83  5291.1  388.53  5326.3  396.25  5341.2  396.02
  5356.9  391.55  5377.4  390.03  5397.8  393.98  5499.9   395.7  5542.9  400.19
#Mann= 1 ,-1 , 0
  3991.8     .16       0
#XS Ineff= 2 , 0
         4438.18  387.83
Permanent Ineff=
       F       F
Bank Sta=4979,5019.8
XS Rating Curve= 0 ,0
Exp/Cntr=0.3,0.1

Type RM Length L Ch R = 1 ,94731   ,192,192,192
BEGIN DESCRIPTION:
MANSON CREEK 142.0
END DESCRIPTION:
XS GIS Cut Line= 2
      3766035.63     10618405.61      3764668.45     10618175.58
#Sta/Elev= 30
  4032.8   411.9    4049  413.62  4059.2  412.13  4079.5  415.26  4095.2  412.13
    4120  411.58  4130.2  406.89  4155.7  401.55  4271.8  393.12  4363.4  390.37
    4404  385.67  4458.5  382.42  4748.7  379.66  4761.3  381.05  4789.3  379.39
    4982  381.38  4992.1   375.9  4998.2  374.77  5012.4  381.83  5103.7  379.81
  5164.5  380.61  5185.2  382.79  5215.2  398.59  5235.5  391.15  5245.7  393.08
  5265.9  390.17  5276.1  390.52  5296.1  402.89  5306.5  405.82  5419.2  408.51
#Mann= 1 ,-1 , 0
  4032.8     .16       0
Bank Sta=4982,5012.4
XS Rating Curve= 0 ,0
Exp/Cntr=0.3,0.1

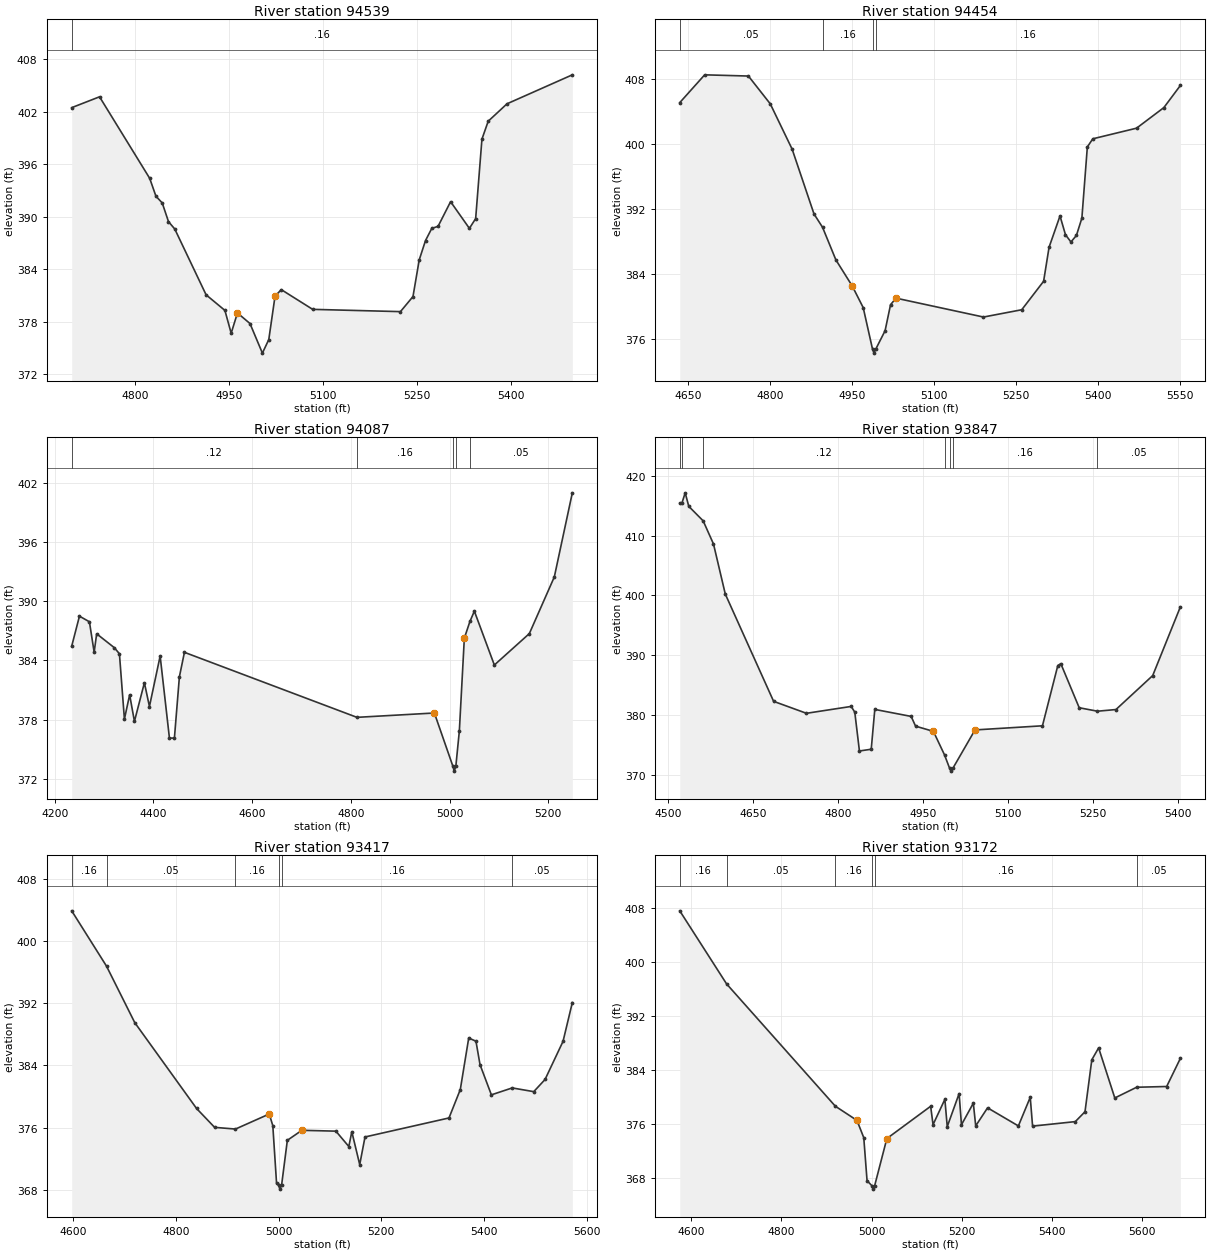
Type RM Length L Ch R = 1 ,94539   ,85,85,85
BEGIN DESCRIPTION:
Mapping XS 8138f301
END DESCRIPTION:
XS GIS Cut Line= 2
      3765454.04     10618071.42      3764655.44     10618071.42
#Sta/Elev= 30
  4699.4  402.48  4743.8  403.72  4823.8  394.41  4833.8  392.36  4843.8   391.6
  4853.8  389.46  4863.8  388.62  4913.8   381.1  4943.8  379.32  4953.8  376.71
  4963.8  379.03  4983.8  377.82  5003.6  374.44  5013.8  375.99  5023.8  380.96
  5033.8  381.69  5083.8  379.44  5223.8  379.18  5243.8   380.9  5253.8   385.1
  5263.8   387.3  5273.8  388.69  5283.8  388.92  5303.8  391.74  5333.8  388.69
  5343.8  389.81  5353.8  398.88  5363.8  400.93  5393.8  402.92    5498  406.23
#Mann= 1 ,-1 , 0
  4699.4     .16       0
Bank Sta=4963.8,5023.8
XS Rating Curve= 0 ,0
Exp/Cntr=0.3,0.1

Type RM Length L Ch R = 1 ,94454   ,367,367,367
BEGIN DESCRIPTION:
Mapping XS 41107797
END DESCRIPTION:
XS GIS Cut Line= 2
      3765545.19     10617993.29      3764629.44     10618001.97
#Sta/Elev= 30
  4634.8  405.12  4680.4  408.55  4760.4   408.4  4800.4  404.97  4840.4  399.38
  4880.4  391.39    4896  389.75  4920.4  385.73  4950.4   382.5  4970.4  379.84
  4987.4  374.73  4990.2  374.23  4993.4  374.73  5010.4  376.99  5020.4   380.2
  5030.4  381.01  5190.4  378.68  5260.4  379.58  5300.4  383.09  5310.4  387.29
  5330.4  391.15  5340.4  388.83  5350.4  387.94  5360.4  388.74  5370.4  390.88
  5380.4  399.66  5390.4  400.66  5470.4  401.97  5520.4  404.51  5550.6  407.24
#Mann= 4 ,-1 , 0
  4634.8     .05       0    4896     .16       0  4987.4     .07       0
  4993.4     .16       0
Bank Sta=4950.4,5030.4
XS Rating Curve= 0 ,0
Exp/Cntr=0.3,0.1

Type RM Length L Ch R = 1 ,94087   ,240,240,240
BEGIN DESCRIPTION:
MANSON CREEK 141.0
END DESCRIPTION:
XS GIS Cut Line= 3
      3765645.06     10617737.22      3764972.31     10617845.72
      3764643.53     10617897.64
#Sta/Elev= 30
  4234.4  385.44  4250.1  388.49  4270.3  387.92  4279.9  384.83    4285   386.7
    4321  385.28  4331.1  384.67  4341.2  378.04  4351.8  380.51  4361.5  377.81
  4381.7  381.73  4391.9  379.32  4413.6  384.44  4432.4  376.12  4442.5  376.11
  4452.6  382.34  4462.8  384.82  4812.3  378.22  4969.2  378.66  5006.7  373.26
  5009.4  372.76  5012.7  373.26  5019.8  376.84  5029.9  386.25  5041.2  387.95
  5050.2     389  5090.7  383.53  5161.6  386.72  5212.2  392.47  5248.7  401.01
#Mann= 5 ,-1 , 0
  4234.4     .12       0  4812.3     .16       0  5006.7     .07       0
  5012.7     .16       0  5041.2     .05       0
Bank Sta=4969.2,5029.9
XS Rating Curve= 0 ,0
Exp/Cntr=0.3,0.1

Type RM Length L Ch R = 1 ,93847   ,430,430,430
BEGIN DESCRIPTION:
Mapping XS f422baae
END DESCRIPTION:
XS GIS Cut Line= 3
      3765410.68     10617468.11      3765089.49     10617715.52
      3764634.18     10617858.61
#Sta/Elev= 30
  4521.2  415.43    4525  415.43  4530.8  417.16  4537.1   414.9  4562.5  412.47
  4580.7   408.6  4601.5  400.23  4686.7  382.29  4744.6  380.29  4823.5  381.44
  4829.8  380.48    4838  373.99  4858.8  374.28  4865.1  380.94  4929.2  379.77
    4937  378.14  4968.4  377.27    4988  373.34  4996.9  371.12  4999.6  370.62
  5002.9  371.12  5041.8  377.51  5160.7   378.2  5187.8  388.28  5193.1  388.59
  5225.5  381.22  5257.7  380.64  5290.3  380.92  5355.1   386.6  5403.9  398.09
#Mann= 7 ,-1 , 0
  4521.2     .05       0    4525     .16       0  4562.5     .12       0
    4988     .16       0  4996.9     .07       0  5002.9     .16       0
  5257.7     .05       0
Bank Sta=4968.4,5041.8
XS Rating Curve= 0 ,0
Exp/Cntr=0.3,0.1

Type RM Length L Ch R = 1 ,93417   ,245,245,245
BEGIN DESCRIPTION:
Mapping XS 836b4c88
END DESCRIPTION:
XS GIS Cut Line= 4
      3765100.11      10617137.2      3764792.79     10617465.36
      3764881.33     10617717.96      3764653.57     10617837.76
#Sta/Elev= 30
  4597.3  403.93  4665.1   396.8  4720.1  389.52  4840.3  378.47  4875.5  376.03
  4916.1  375.81  4981.9  377.75  4988.8  376.25  4996.1  368.84  4999.9  368.57
  5002.7  368.07  5005.9  368.57  5017.1  374.36  5045.4  375.65  5111.6  375.54
  5136.8  373.56  5142.6  375.47    5158  371.23  5168.3  374.79  5331.8  377.24
  5353.8   380.9  5370.2  387.54  5384.3  387.13  5392.2  384.11  5414.3  380.22
  5454.9  381.11  5496.8  380.63  5518.8   382.2  5553.8  387.11  5571.9  392.11
#Mann= 6 ,-1 , 0
  4597.3     .16       0  4665.1     .05       0  4916.1     .16       0
  4999.9     .07       0  5005.9     .16       0  5454.9     .05       0
Bank Sta=4981.9,5045.4
XS Rating Curve= 0 ,0
Exp/Cntr=0.3,0.1

Type RM Length L Ch R = 1 ,93172   ,211,211,211
BEGIN DESCRIPTION:
MANSON CREEK 140.0
END DESCRIPTION:
XS GIS Cut Line= 4
      3764988.12     10616913.24      3764727.68     10617309.11
      3764857.89     10617697.13      3764667.78     10617820.92
#Sta/Elev= 30
  4574.8  407.52  4678.6   396.7  4919.8  378.58  4967.7  376.48  4982.8  373.92
  4990.1  367.55  5000.9   366.8  5003.6   366.3  5006.9   366.8    5034  373.79
  5131.1  378.57  5136.4  375.85  5162.6   379.6  5167.9  375.56  5194.2  380.45
  5199.4  375.83  5225.7  379.03    5231  375.67  5257.3  378.34  5325.6  375.66
  5351.9   379.9  5357.1  375.63  5451.8   376.3  5473.3  377.76  5488.4  385.45
  5503.5  387.22  5539.4   379.8  5587.8  381.39  5654.4   381.5  5684.8  385.67
#Mann= 6 ,-1 , 0
  4574.8     .16       0  4678.6     .05       0  4919.8     .16       0
  5000.9     .07       0  5006.9     .16       0  5587.8     .05       0
Bank Sta=4967.7,5034
XS Rating Curve= 0 ,0
Exp/Cntr=0.3,0.1

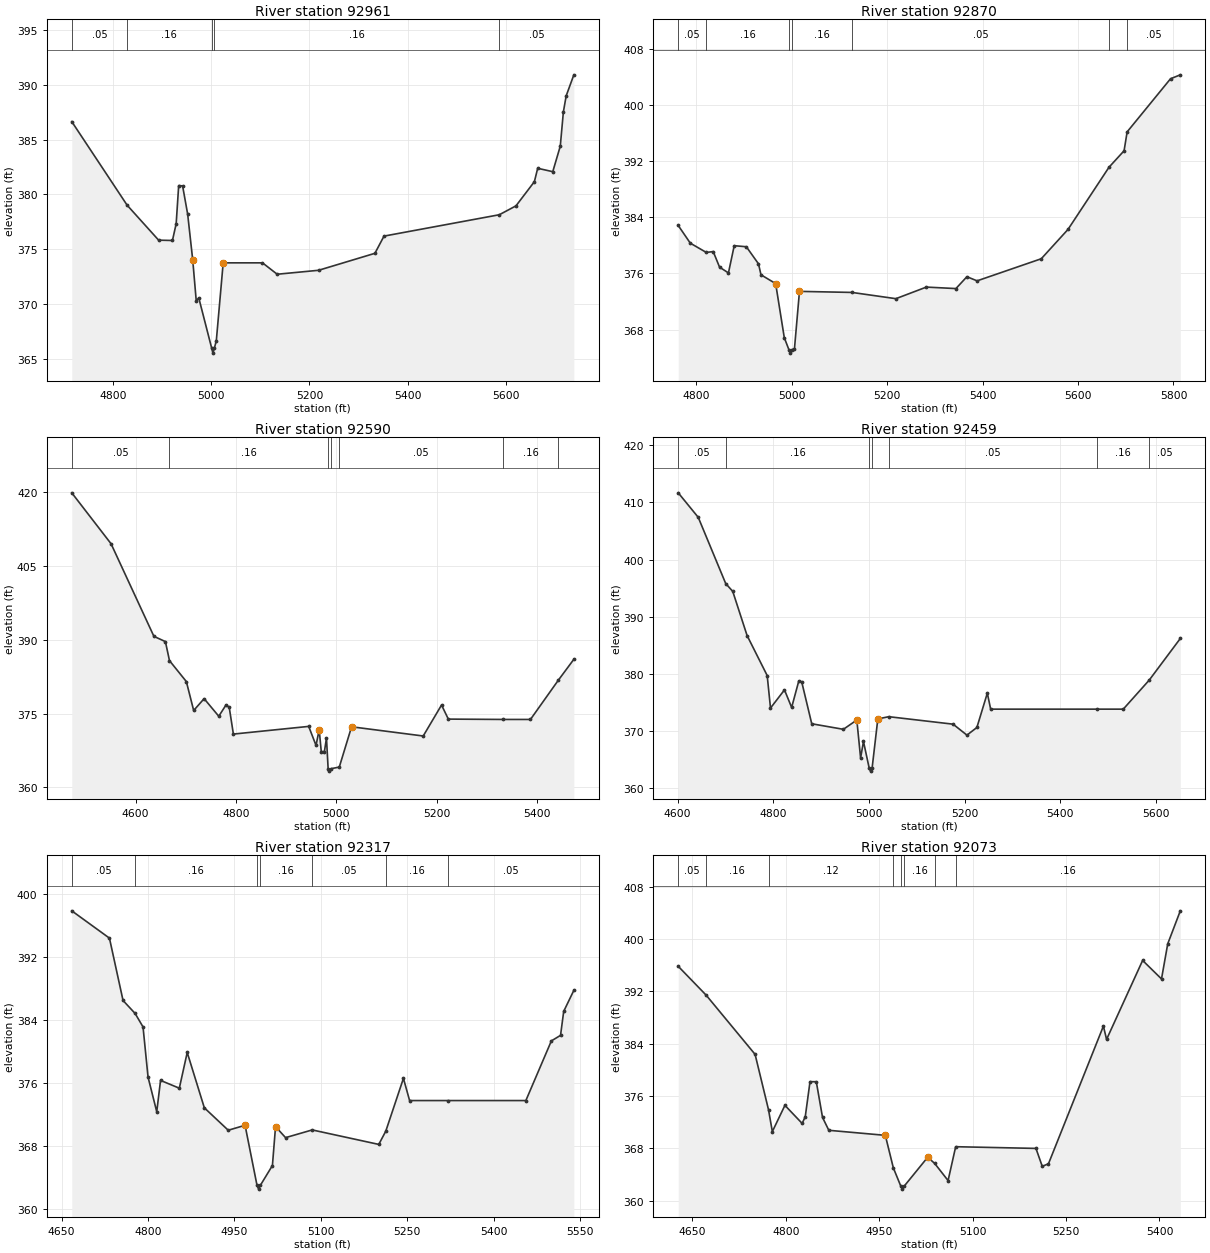
Type RM Length L Ch R = 1 ,92961   ,91,91,91
BEGIN DESCRIPTION:
MANSON CREEK 139.0
END DESCRIPTION:
XS GIS Cut Line= 4
      3764667.78     10616871.62      3764576.64     10617228.38
       3764738.1     10617642.44      3764634.28     10617824.13
#Sta/Elev= 30
  4716.3  386.64    4829  379.01  4893.1  375.82  4921.2  375.79  4928.8  377.32
  4933.9   380.8  4941.9  380.77  4952.2  378.19  4962.5  374.01  4969.6   370.3
  4974.8  370.55  5000.8  366.01  5003.6  365.51  5006.8  366.01  5010.5  366.64
  5024.5  373.75  5104.5  373.75  5134.4  372.71  5218.6  373.07  5333.3  374.62
  5351.8  376.19  5586.5  378.14  5620.4  378.95  5657.9  381.16  5664.6  382.38
  5695.3  382.07  5710.6   384.4  5716.9  387.53  5722.6  388.99  5738.2  390.91
#Mann= 5 ,-1 , 0
  4716.3     .05       0    4829     .16       0  5000.8     .07       0
  5006.8     .16       0  5586.5     .05       0
Bank Sta=4962.5,5024.5
XS Rating Curve= 0 ,0
Exp/Cntr=0.3,0.1

Type RM Length L Ch R = 1 ,92870   ,280,280,280
BEGIN DESCRIPTION:
Mapping XS b9445f47
END DESCRIPTION:
XS GIS Cut Line= 2
       3764613.1      10616861.2      3764256.34     10617850.75
#Sta/Elev= 30
  4762.5  382.83  4787.8  380.31  4821.3  378.99  4835.8  379.11  4849.1  376.89
  4867.7  376.07  4879.8  379.95  4905.2   379.8  4930.6  377.37  4935.9   375.8
  4966.6  374.55  4984.7  366.84  4994.3  365.14    4997  364.64  5000.3  365.14
  5005.9  365.18  5016.5  373.44  5126.4  373.29  5218.5   372.4  5282.3  374.05
  5344.3  373.84  5367.3  375.53  5388.6  374.94  5523.1  378.09  5579.1  382.27
    5665  391.13  5696.6  393.48    5703  396.17  5793.9  403.74  5814.4   404.3
#Mann= 7 ,-1 , 0
  4762.5     .05       0  4821.3     .16       0  4994.3     .07       0
  5000.3     .16       0  5126.4     .05       0    5665     .16       0
    5703     .05       0
Bank Sta=4966.6,5016.5
XS Rating Curve= 0 ,0
Exp/Cntr=0.3,0.1

Type RM Length L Ch R = 1 ,92590   ,131,131,131
BEGIN DESCRIPTION:
MANSON CREEK 138.0
END DESCRIPTION:
XS GIS Cut Line= 3
      3764699.65     10616660.16      3764299.61     10616960.19
      3763999.64     10617360.15
#Sta/Elev= 30
    4473  419.81  4551.2  409.48  4636.6  390.68  4659.5  389.61  4667.6  385.75
  4701.2   381.5  4715.8  375.63  4736.6  378.03  4765.8  374.46  4780.3  376.77
  4786.6  376.28  4794.9  370.84  4944.9   372.4  4959.5  368.54  4965.8  371.74
  4969.9  367.29  4976.2  367.29  4980.3  370.04  4983.6  363.82  4986.3  363.32
  4989.6  363.82  5005.8  364.14  5030.3  372.32    5173  370.45  5209.5  376.74
    5223  373.88  5332.2  373.81  5386.6  373.81  5442.2  381.79    5473  386.02
#Mann= 7 ,-1 , 0
    4473     .05       0  4667.6     .16       0  4983.6     .07       0
  4989.6     .16       0  5005.8     .05       0  5332.2     .16       0
  5442.2     .05       0
Bank Sta=4965.8,5030.3
XS Rating Curve= 0 ,0
Exp/Cntr=0.3,0.1

Type RM Length L Ch R = 1 ,92459   ,142,142,142
BEGIN DESCRIPTION:
Mapping XS 46106cbe
END DESCRIPTION:
XS GIS Cut Line= 3
      3764629.86      10616632.3      3764205.36     10616916.16
      3763784.08     10617251.63
#Sta/Elev= 30
  4601.5  411.68  4643.3  407.39  4700.7   395.8  4715.4  394.43  4745.4  386.69
  4787.4  379.69  4794.3     374  4823.5  377.18  4838.5  374.11  4853.5  378.77
  4859.5   378.6  4880.5  371.25  4946.6  370.28  4974.7  371.91  4982.6  365.26
  4988.6  368.15  5000.6  363.46  5003.4  362.96  5006.6  363.46  5018.6   372.1
  5041.5  372.49  5175.9  371.18  5204.8  369.26  5225.6   370.6  5247.4  376.61
  5254.4  373.81  5476.5  373.81  5531.5  373.81  5585.8   378.9  5650.7  386.18
#Mann= 7 ,-1 , 0
  4601.5     .05       0  4700.7     .16       0  5000.6     .07       0
  5006.6     .16       0  5041.5     .05       0  5476.5     .16       0
  5585.8     .05       0
Bank Sta=4974.7,5018.6
XS Rating Curve= 0 ,0
Exp/Cntr=0.3,0.1

Type RM Length L Ch R = 1 ,92317   ,244,244,244
BEGIN DESCRIPTION:
Mapping XS 765bfd44
END DESCRIPTION:
XS GIS Cut Line= 3
      3764551.68     10616598.47      3764124.63     10616778.14
      3763743.18     10616923.46
#Sta/Elev= 30
  4667.7  397.91  4733.1  394.44  4756.7  386.52  4777.7  384.87  4791.4  383.16
  4800.1  376.79  4815.2  372.39  4821.8  376.37  4854.4  375.38  4868.1  379.92
  4897.8  372.89  4939.3  370.04  4968.5  370.67  4989.2  363.06    4992  362.56
  4995.2  363.06    5016  365.56  5021.4   370.5  5038.8   369.1  5085.1  370.08
  5200.6  368.24  5212.8  369.93  5243.4  376.63  5254.1  373.81  5320.2  373.81
  5455.9  373.81  5500.2  381.39  5516.1  382.09  5521.6  385.14  5539.2  387.81
#Mann= 7 ,-1 , 0
  4667.7     .05       0  4777.7     .16       0  4989.2     .07       0
  4995.2     .16       0  5085.1     .05       0  5212.8     .16       0
  5320.2     .05       0
Bank Sta=4968.5,5021.4
XS Rating Curve= 0 ,0
Exp/Cntr=0.3,0.1

Type RM Length L Ch R = 1 ,92073   ,415,415,415
BEGIN DESCRIPTION:
MANSON CREEK 137.0
END DESCRIPTION:
XS GIS Cut Line= 3
      3764499.57     10616510.19      3764099.61     10616560.19
      3763699.59     10616610.19
#Sta/Elev= 30
  4627.3  395.85  4672.2  391.43  4750.7  382.38  4772.3  373.89  4778.4  370.56
  4798.6  374.58  4826.3  371.81  4831.3  372.86  4838.9   378.2    4849  378.19
    4859  372.73  4869.1  370.76  4959.8  369.99  4972.7  365.01  4984.5  362.26
  4987.3  361.76  4990.5  362.26  5027.9  366.64  5039.1  365.69  5060.6  363.07
  5072.8  368.25  5201.7  367.99  5211.8  365.25  5221.8  365.64    5310   386.7
  5315.1  384.67    5373  396.75  5403.3  393.92  5413.3  399.29  5433.5  404.34
#Mann= 8 ,-1 , 0
  4627.3     .05       0  4672.2     .16       0  4772.3     .12       0
  4972.7     .16       0  4984.5     .07       0  4990.5     .16       0
  5039.1     .05       0  5072.8     .16       0
Bank Sta=4959.8,5027.9
XS Rating Curve= 0 ,0
Exp/Cntr=0.3,0.1