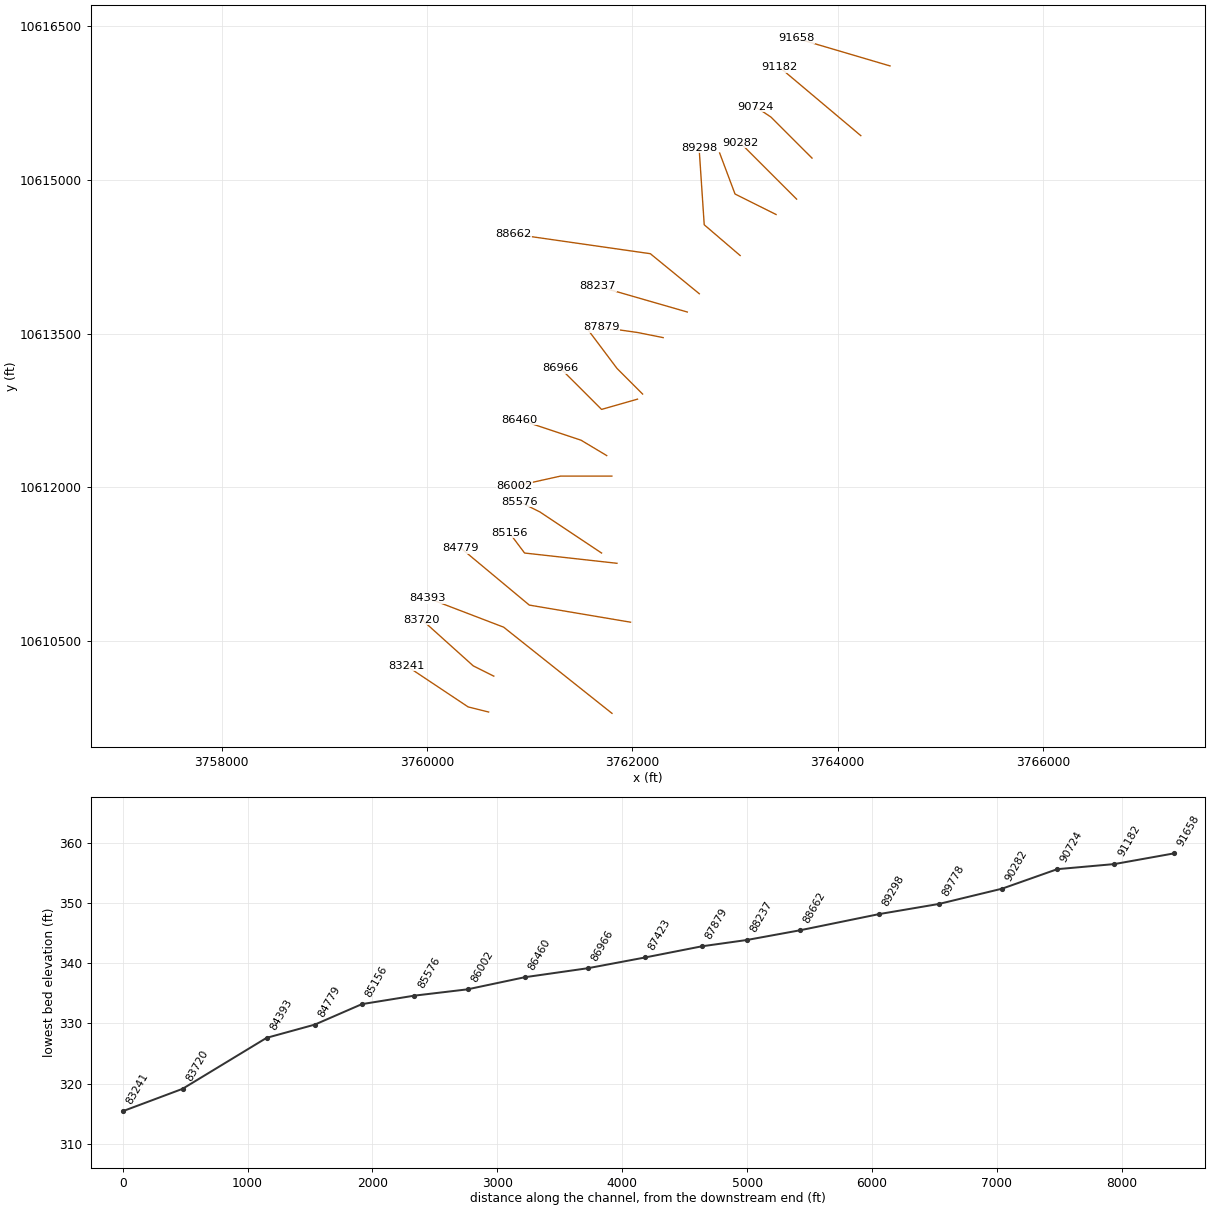
HEC-RAS study MANSON CREEK.prj: MANSON CREEK Base Level Engineering

--- MANSON CREEK.g01 (geometry) --- (continued)

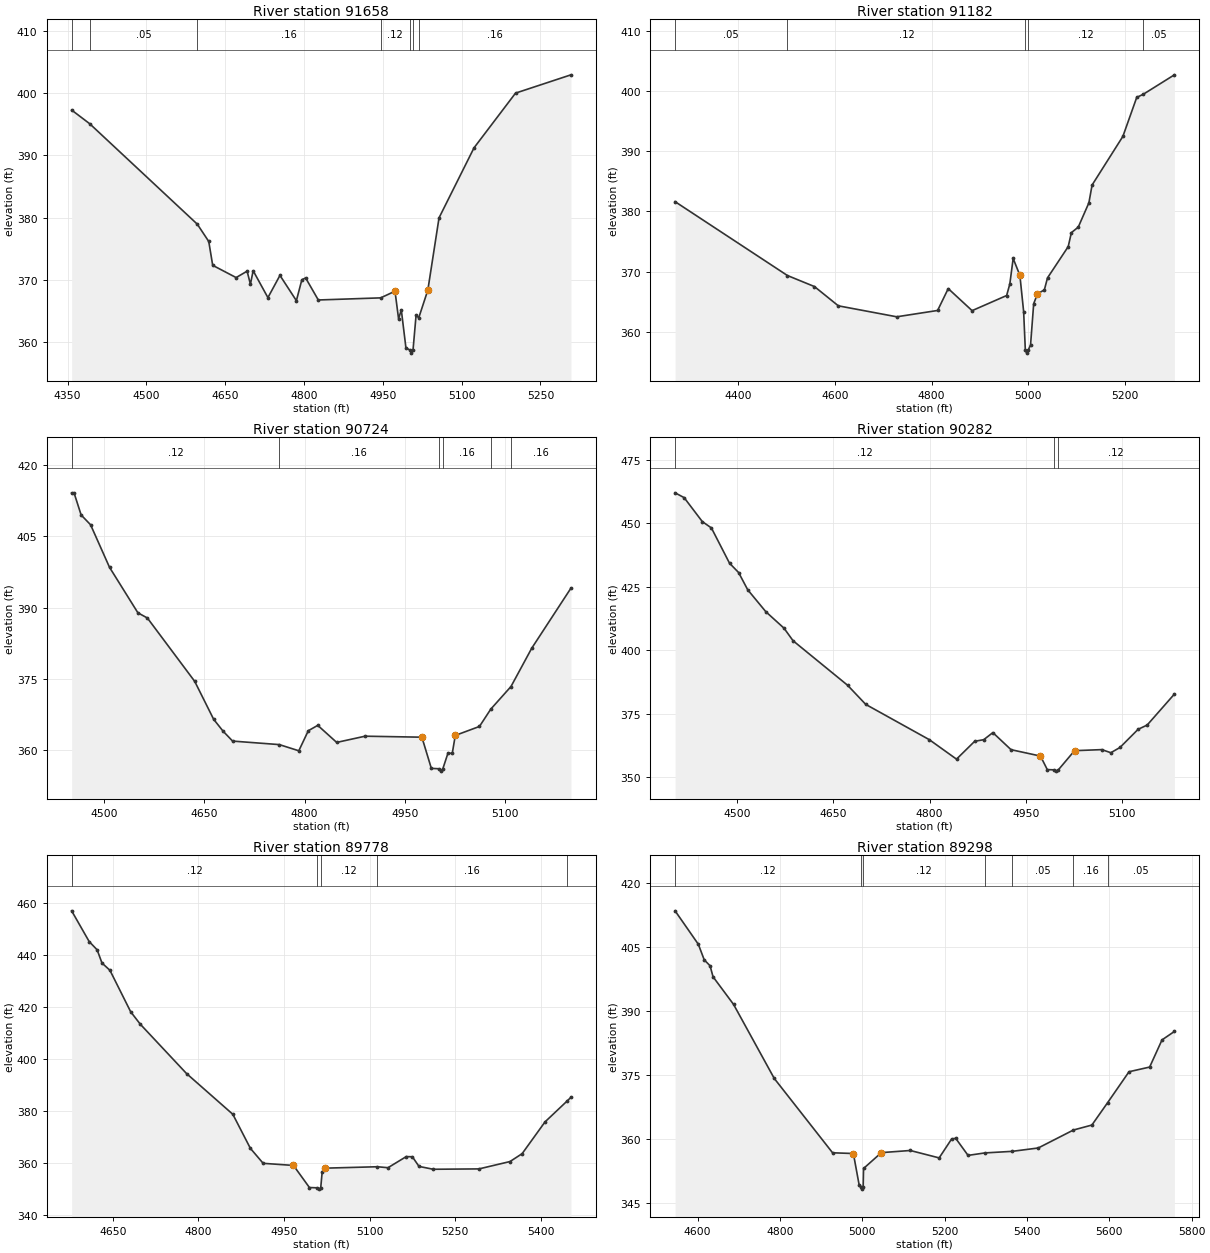
Type RM Length L Ch R = 1 ,91658   ,476,476,476
BEGIN DESCRIPTION:
MANSON CREEK 136.0
END DESCRIPTION:
XS GIS Cut Line= 2
       3764509.9     10616108.52      3763598.39     10616377.64
#Sta/Elev= 30
  4357.6  397.29    4392  395.09  4596.8  378.95  4618.6  376.17  4626.1  372.34
  4670.7  370.37  4691.6   371.4  4697.9   369.3  4703.1  371.47  4731.2  367.15
  4754.1  370.72  4785.4  366.66  4795.8  370.02    4803  370.31  4827.1  366.77
  4945.8  367.11  4973.1  368.18  4979.9  363.74  4985.1  365.18  4993.9  359.07
  5001.4  358.73  5004.1  358.23  5007.4  358.73  5013.2  364.31  5018.3  363.91
  5035.6  368.36  5056.9  379.97  5123.5  391.22  5202.5  400.01    5308  402.95
#Mann= 7 ,-1 , 0
  4357.6      .1       0    4392     .05       0  4596.8     .16       0
  4945.8     .12       0  5001.4     .07       0  5007.4     .12       0
  5018.3     .16       0
Bank Sta=4973.1,5035.6
XS Rating Curve= 0 ,0
Exp/Cntr=0.3,0.1

Type RM Length L Ch R = 1 ,91182   ,458,458,458
BEGIN DESCRIPTION:
MANSON CREEK 135.0
END DESCRIPTION:
XS GIS Cut Line= 2
      3764224.94     10615429.03      3763434.25     10616094.88
#Sta/Elev= 30
    4269   381.6  4501.6  369.34  4557.5  367.51    4607  364.31  4727.9  362.49
  4812.5  363.54  4834.5  367.17  4883.9  363.51  4955.4  366.02    4962  367.94
  4968.9  372.17  4982.8  369.38  4990.6  363.35  4994.1  356.96  4996.9  356.46
  5000.1  356.96  5004.9  357.81  5011.4  364.66  5019.2   366.3  5033.5  366.96
    5040  368.95  5082.9  374.14  5089.4  376.45  5103.7  377.38  5125.7  381.41
  5132.3  384.36  5196.1  392.44  5224.7   398.9  5238.2  399.42  5302.7  402.65
#Mann= 5 ,-1 , 0
    4269     .05       0  4501.6     .12       0  4994.1     .07       0
  5000.1     .12       0  5238.2     .05       0
Bank Sta=4982.8,5019.2
XS Rating Curve= 0 ,0
Exp/Cntr=0.3,0.1

Type RM Length L Ch R = 1 ,90724   ,442,442,442
BEGIN DESCRIPTION:
MANSON CREEK 134.0
END DESCRIPTION:
XS GIS Cut Line= 3
      3763749.63     10615210.16      3763349.61     10615610.19
      3763199.61     10615710.19
#Sta/Elev= 30
    4452  414.16  4455.6  414.16  4466.2   409.5  4480.3  407.44  4508.6  398.49
    4551  388.92  4565.2  387.82  4635.9  374.49  4664.2  366.51  4678.3  364.01
  4692.5  361.93  4762.3  361.19  4791.4  359.89  4805.6  364.11  4819.7  365.24
    4848  361.65  4890.4  362.96  4975.3  362.75  4989.4  356.19  5000.6  356.11
  5003.3  355.61  5006.6  356.11  5014.2  359.37  5020.7  359.37  5025.2  363.12
  5061.3  365.01  5078.2  368.65  5108.4  373.41  5139.4  381.47    5198  394.11
#Mann= 6 ,-1 , 0
    4452     .12       0  4762.3     .16       0  5000.6     .07       0
  5006.6     .16       0  5078.2     .12       0  5108.4     .16       0
Bank Sta=4975.3,5025.2
XS Rating Curve= 0 ,0
Exp/Cntr=0.3,0.1

Type RM Length L Ch R = 1 ,90282   ,504,504,504
BEGIN DESCRIPTION:
MANSON CREEK 133.0
END DESCRIPTION:
XS GIS Cut Line= 3
      3763599.61     10614810.19      3763199.61     10615210.19
      3763049.62     10615360.18
#Sta/Elev= 30
  4403.6  461.96  4417.7  460.07    4446  450.64  4460.2  448.13  4488.4  434.26
  4502.6  430.56  4516.7   423.8    4545  415.14  4573.3  408.66  4587.4  403.71
  4672.3  386.19  4700.6  378.65  4799.6  364.76    4842  357.09  4870.3  364.12
  4884.4  364.75  4898.6  367.54  4926.9  360.82  4972.8   358.3  4983.4  352.97
  4994.6  352.87  4997.3  352.37  5000.6  352.87  5025.8  360.42  5068.3  360.84
  5082.4  359.62  5096.6  361.68  5124.8  368.82    5139  370.52  5181.4  382.71
#Mann= 3 ,-1 , 0
  4403.6     .12       0  4994.6     .07       0  5000.6     .12       0
Bank Sta=4972.8,5025.8
XS Rating Curve= 0 ,0
Exp/Cntr=0.3,0.1

Type RM Length L Ch R = 1 ,89778   ,480,480,480
BEGIN DESCRIPTION:
MANSON CREEK 132.0
END DESCRIPTION:
XS GIS Cut Line= 3
      3763399.59      10614660.2      3762999.61     10614860.19
      3762849.61      10615260.2
#Sta/Elev= 30
  4578.1  457.03  4608.8   445.2  4622.8     442  4631.2  436.94  4645.2  434.11
  4681.5  418.15  4698.3  413.37  4779.3  394.36  4860.4  378.66  4891.1  365.55
  4913.5  359.78  4966.6  358.96  4994.5  350.46  5008.3  350.34  5011.1  349.84
  5014.3  350.34  5016.9  356.59  5022.5  357.92  5113.5  358.46  5132.1  358.09
  5164.1  362.37  5174.8   362.3  5186.4  358.59  5211.3  357.49  5291.4  357.63
  5345.7  360.46    5367   363.5  5407.1  375.74  5445.7  383.76  5452.5  385.22
#Mann= 5 ,-1 , 0
  4578.1     .12       0  5008.3     .07       0  5014.3     .12       0
  5113.5     .16       0  5445.7     .05       0
Bank Sta=4966.6,5022.5
XS Rating Curve= 0 ,0
Exp/Cntr=0.3,0.1

Type RM Length L Ch R = 1 ,89298   ,636,636,636
BEGIN DESCRIPTION:
MANSON CREEK 131.0
END DESCRIPTION:
XS GIS Cut Line= 3
      3763049.59     10614260.21      3762699.61     10614560.19
      3762649.61     10615310.18
#Sta/Elev= 30
  4545.5  413.56    4602   405.7  4616.3  402.04  4630.5  400.64  4637.7  398.06
  4687.6  391.56  4786.4  374.16    4928  356.69  4978.5  356.52  4992.7  349.04
  4996.3  348.65  4999.1  348.15  5002.3  348.65  5003.2     353  5046.5  356.73
  5116.7  357.23  5186.8  355.49  5216.9  359.91  5226.9   360.1    5257  356.08
    5298  356.66  5364.3  357.03  5427.4  357.82  5512.8  362.04  5557.7  363.21
  5595.9  368.47  5647.9  375.74    5698  376.84    5728  383.22  5758.1  385.21
#Mann= 7 ,-1 , 0
  4545.5     .12       0  4996.3     .07       0  5002.3     .12       0
    5298     .16       0  5364.3     .05       0  5512.8     .16       0
  5595.9     .05       0
Bank Sta=4978.5,5046.5
XS Rating Curve= 0 ,0
Exp/Cntr=0.3,0.1

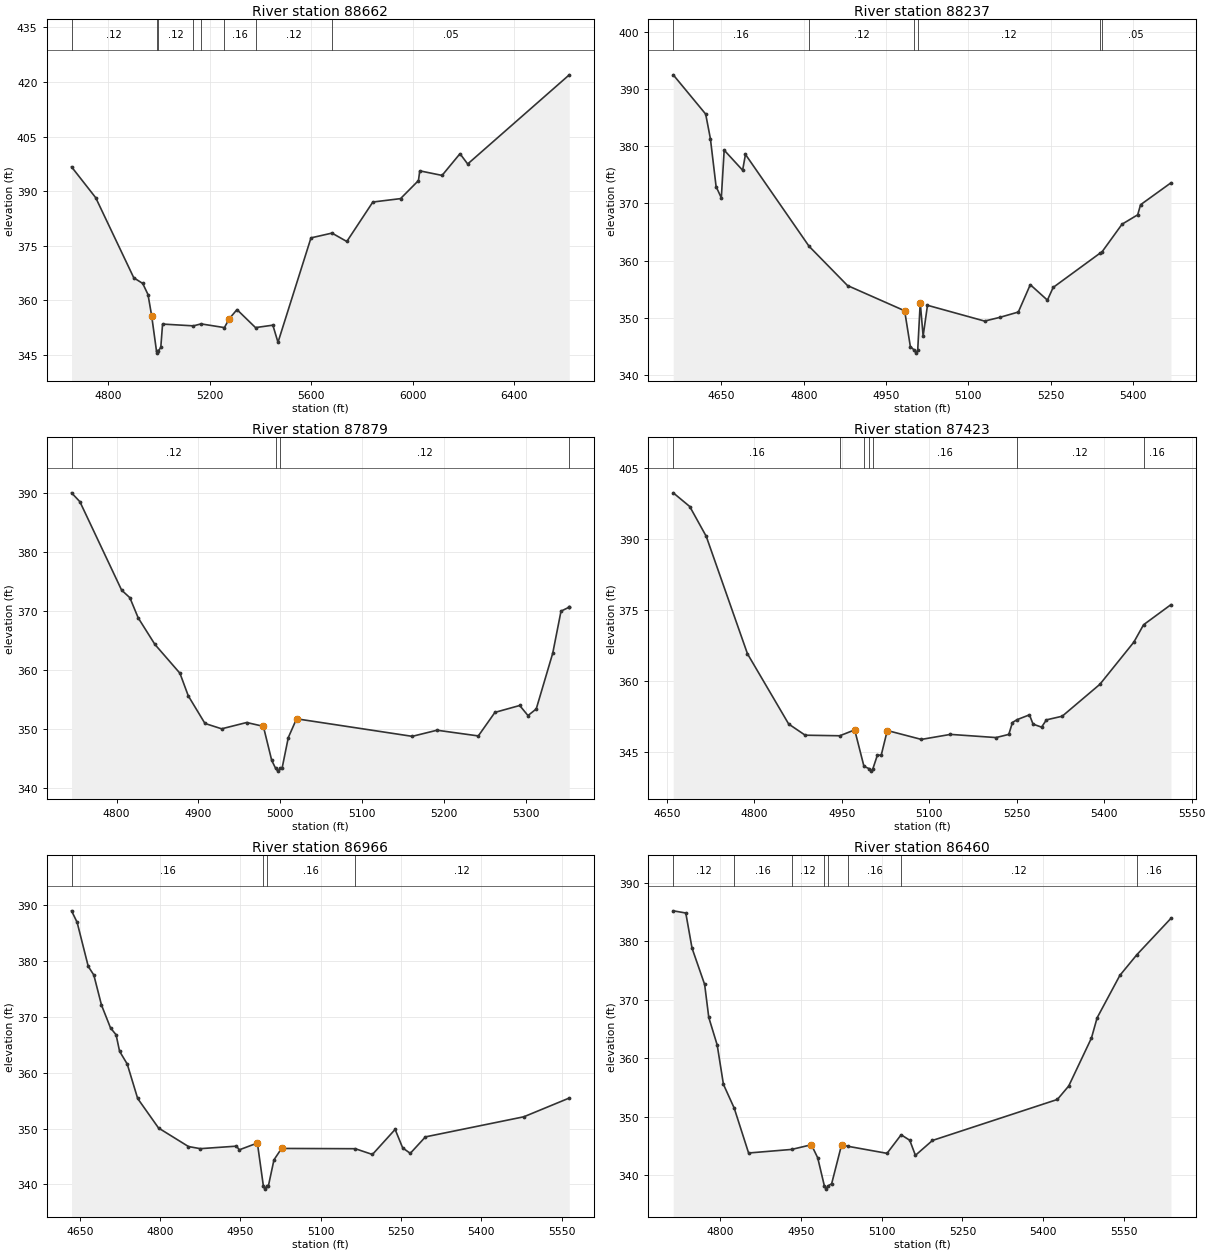
Type RM Length L Ch R = 1 ,88662   ,425,425,425
BEGIN DESCRIPTION:
MANSON CREEK 130.0
END DESCRIPTION:
XS GIS Cut Line= 3
      3762651.81     10613887.67      3762174.37     10614278.31
      3760843.26     10614469.09
#Sta/Elev= 30
  4655.2  396.67  4750.5  388.18  4900.5  366.16  4935.7  364.61  4956.5  361.56
  4970.9  355.72  4990.1  345.95  4992.9  345.45  4996.1  345.95  5006.9  347.01
  5013.9  353.44  5135.5  352.95  5165.5  353.49  5257.6  352.47    5277  354.93
  5307.2  357.42  5380.2  352.47  5448.6  353.14  5468.8  348.42  5598.8  377.14
  5681.6  378.46    5740  376.15  5842.6     387  5951.8  387.94  6022.4   392.9
  6027.5  395.58  6115.4  394.32  6186.1  400.29  6216.4  397.46  6616.8  421.98
#Mann= 8 ,-1 , 0
  4655.2     .12       0  4990.1     .07       0  4996.1     .12       0
  5135.5     .16       0  5165.5     .12       0  5257.6     .16       0
  5380.2     .12       0  5681.6     .05       0
Bank Sta=4970.9,5277
XS Rating Curve= 0 ,0
Exp/Cntr=0.3,0.1

Type RM Length L Ch R = 1 ,88237   ,358,358,358
BEGIN DESCRIPTION:
MANSON CREEK 129.0
END DESCRIPTION:
XS GIS Cut Line= 2
      3762534.63     10613709.73      3761663.38     10613961.13
#Sta/Elev= 30
  4562.2  392.47  4621.3  385.61  4629.9  381.32  4640.3  372.94  4649.8  370.97
    4655  379.31  4688.6   375.8  4693.8  378.56  4809.6  362.52  4879.7  355.65
  4983.8  351.24  4994.2  344.99  5001.6  344.34  5004.3  343.84  5007.6  344.34
  5012.2  352.66  5017.5  346.82  5025.4   352.2  5129.5  349.44  5157.2  350.09
  5190.9  351.02  5212.7   355.8  5243.9   353.1  5254.4  355.32  5339.4  361.28
  5342.7  361.44  5379.9  366.37  5408.4  368.01  5413.6  369.77    5469   373.6
#Mann= 6 ,-1 , 0
  4562.2     .16       0  4809.6     .12       0  5001.6     .07       0
  5007.6     .12       0  5339.4     .16       0  5342.7     .05       0
Bank Sta=4983.8,5012.2
XS Rating Curve= 0 ,0
Exp/Cntr=0.3,0.1

Type RM Length L Ch R = 1 ,87879   ,456,456,456
BEGIN DESCRIPTION:
MANSON CREEK 128.0
END DESCRIPTION:
XS GIS Cut Line= 3
      3762299.57      10613460.2      3762049.61     10613510.19
      3761699.58     10613560.19
#Sta/Elev= 30
    4745  390.08  4755.2  388.57  4806.2  373.55  4816.3  372.26  4826.5  368.83
  4846.9  364.33  4877.5  359.43  4887.7  355.59  4908.1   350.9  4928.5  349.99
  4959.1  351.06  4979.5  350.41  4989.7  344.63  4994.4   343.3  4997.1   342.8
  5000.4   343.3  5002.4   343.3    5010  348.51  5020.1  351.69  5161.5  348.71
  5191.8  349.75  5242.3  348.78  5262.6  352.78  5292.9  353.95    5303  352.24
  5313.1  353.36  5333.3  362.85  5343.4  369.98  5353.3  370.65  5353.5  370.65
#Mann= 4 ,-1 , 0
    4745     .12       0  4994.4     .07       0  5000.4     .12       0
  5353.3     .16       0
Bank Sta=4979.5,5020.1
XS Rating Curve= 0 ,0
Exp/Cntr=0.3,0.1

Type RM Length L Ch R = 1 ,87423   ,457,457,457
BEGIN DESCRIPTION:
MANSON CREEK 127.0
END DESCRIPTION:
XS GIS Cut Line= 3
      3762099.63     10612910.16      3761849.61     10613160.19
       3761549.6      10613560.2
#Sta/Elev= 30
  4660.9  399.73  4689.2  396.84  4717.5  390.54  4788.2  365.73  4858.9  350.89
  4887.2  348.53  4946.5  348.41  4972.1  349.65    4988  341.95  4997.3  341.44
  5000.1  340.94  5003.3  341.44    5011  344.31  5017.6  344.31    5028  349.52
  5086.4  347.64  5136.4   348.7  5214.5  348.03  5236.4   348.7  5242.6  351.21
  5250.7  351.82  5271.8  352.83    5278  350.87  5292.6  350.23  5300.9  351.77
    5328  352.54  5392.6  359.28  5450.9   368.2  5467.5  371.86  5514.5  376.11
#Mann= 7 ,-1 , 0
  4660.9     .16       0  4946.5     .12       0    4988     .16       0
  4997.3     .07       0  5003.3     .16       0  5250.7     .12       0
  5467.5     .16       0
Bank Sta=4972.1,5028
XS Rating Curve= 0 ,0
Exp/Cntr=0.3,0.1

Type RM Length L Ch R = 1 ,86966   ,506,506,506
BEGIN DESCRIPTION:
MANSON CREEK 126.0
END DESCRIPTION:
XS GIS Cut Line= 3
      3762049.58     10612860.18      3761699.61     10612760.19
      3761299.58     10613160.22
#Sta/Elev= 30
  4634.7  389.02  4645.1  386.96  4665.9  379.06  4676.3  377.52  4690.6  372.14
  4707.5  368.04  4717.9  366.81  4724.4  363.86  4738.7  361.57  4758.2   355.4
  4797.2  350.11  4853.1  346.79  4875.2  346.41  4942.8  346.86    4948   346.2
  4981.8  347.42  4993.1  339.66  4995.8  339.16  4999.1  339.66  5002.2  339.66
  5012.8  344.41    5027  346.45  5164.7   346.4  5196.7  345.37  5239.1  349.86
  5253.2  346.55  5267.4  345.57  5295.7  348.52  5479.5  352.12  5564.4  355.48
#Mann= 4 ,-1 , 0
  4634.7     .16       0  4993.1     .07       0  4999.1     .16       0
  5164.7     .12       0
Bank Sta=4981.8,5027
XS Rating Curve= 0 ,0
Exp/Cntr=0.3,0.1

Type RM Length L Ch R = 1 ,86460   ,458,458,458
BEGIN DESCRIPTION:
MANSON CREEK 125.0
END DESCRIPTION:
XS GIS Cut Line= 3
      3761749.57     10612310.21      3761499.61     10612460.19
      3760899.56      10612660.2
#Sta/Elev= 30
  4713.1  385.18  4736.4  384.81    4748  378.81  4771.4  372.61  4779.1  366.97
  4794.7  362.27  4806.3  355.55  4826.3  351.49    4853  343.83    4933  344.44
  4969.6  345.24  4981.3  343.01  4993.8  338.16  4996.6  337.66  4999.8  338.16
  5007.2  338.59  5025.7  345.25    5037  344.98    5110  343.77  5136.2  346.94
  5152.2     346  5162.7  343.43  5194.3  345.97  5426.2  352.97  5447.3  355.27
  5489.5  363.46    5500  366.91  5542.2  374.15  5573.9   377.7  5637.1   383.9
#Mann= 8 ,-1 , 0
  4713.1     .12       0  4826.3     .16       0    4933     .12       0
  4993.8     .07       0  4999.8     .12       0    5037     .16       0
  5136.2     .12       0  5573.9     .16       0
Bank Sta=4969.6,5025.7
XS Rating Curve= 0 ,0
Exp/Cntr=0.3,0.1

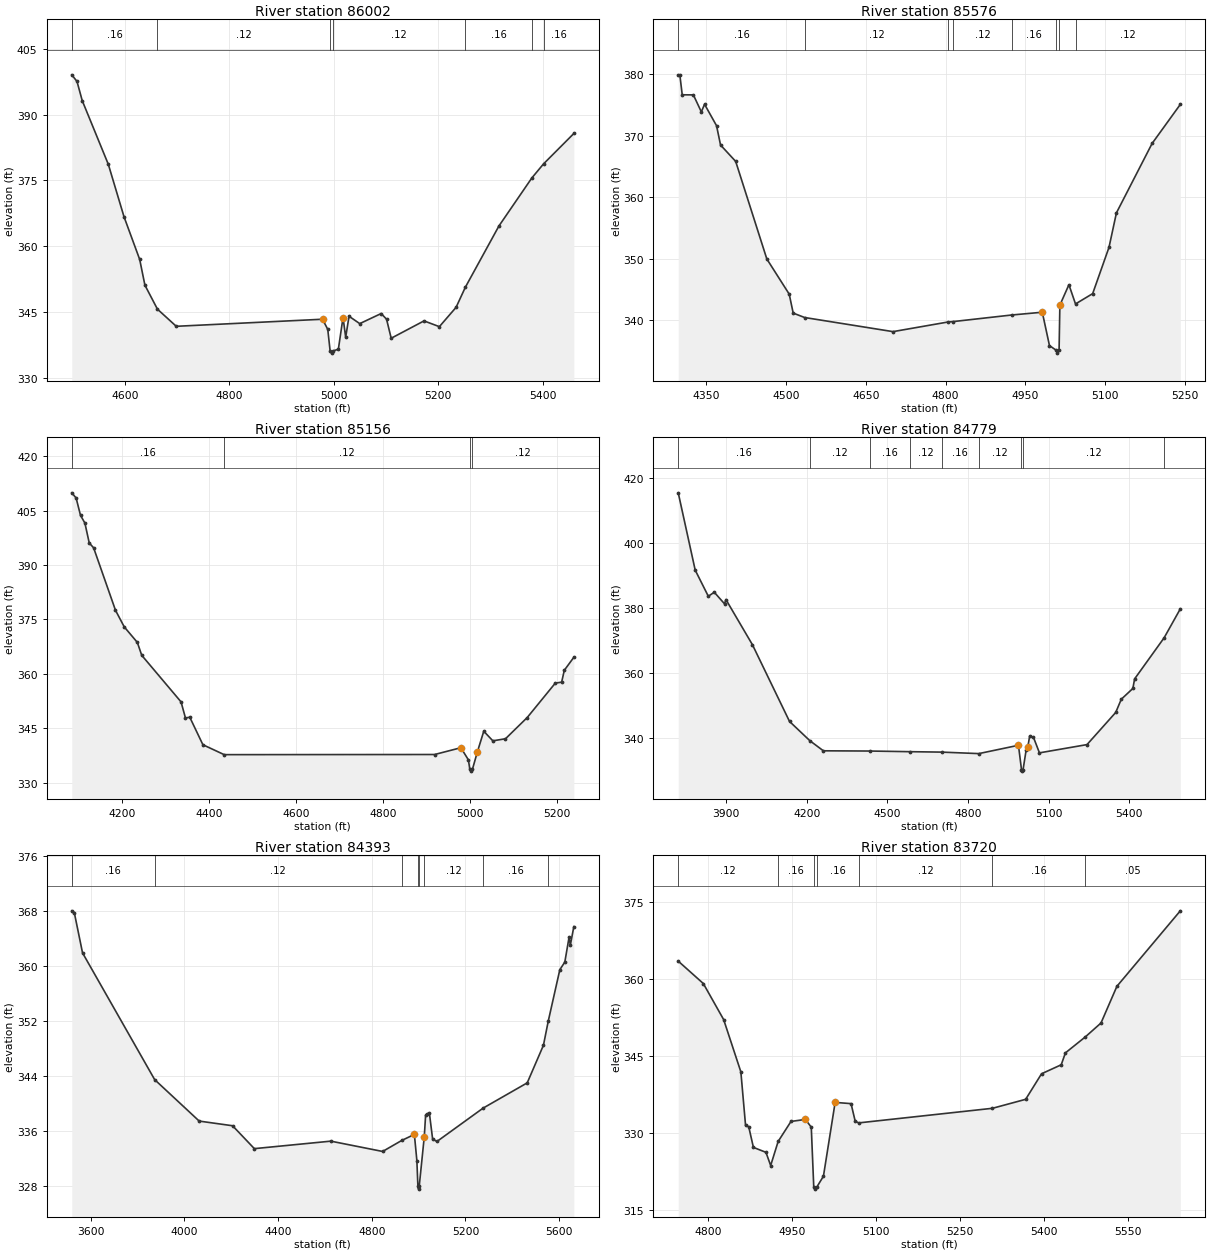
Type RM Length L Ch R = 1 ,86002   ,426,426,426
BEGIN DESCRIPTION:
MANSON CREEK 124.0
END DESCRIPTION:
XS GIS Cut Line= 3
      3761799.63     10612110.19      3761299.61     10612110.19
       3760849.6     10612010.19
#Sta/Elev= 30
  4498.4  399.04  4508.4  397.54  4518.4  393.17  4568.4  378.64  4598.4  366.71
  4628.4  356.99  4638.4  351.13  4662.4  345.66  4698.4  341.76  4978.4  343.37
  4988.4  341.05  4992.9  336.15  4995.7  335.65  4998.9  336.15  5008.7  336.56
  5017.6  343.75  5022.7  339.27  5029.1  344.05  5049.6  342.37  5090.6  344.67
  5100.9  343.38  5109.8  339.04  5172.6  342.99    5202  341.68    5234  346.08
  5251.7  350.65    5316  364.61    5379  375.55  5401.5  378.77  5459.4  385.68
#Mann= 7 ,-1 , 0
  4498.4     .16       0  4662.4     .12       0  4992.9     .07       0
  4998.9     .12       0  5251.7     .16       0    5379     .12       0
  5401.5     .16       0
Bank Sta=4978.4,5017.6
XS Rating Curve= 0 ,0
Exp/Cntr=0.3,0.1

Type RM Length L Ch R = 1 ,85576   ,420,420,420
BEGIN DESCRIPTION:
MANSON CREEK 123.0
END DESCRIPTION:
XS GIS Cut Line= 3
      3761699.58     10611360.21      3761099.61     10611760.19
       3760899.6     10611860.19
#Sta/Elev= 30
    4297  379.92    4300  379.92  4304.5  376.67  4325.5  376.65  4340.5  373.88
  4346.5  375.13  4369.1  371.63  4376.6  368.49  4405.1  365.82  4463.7  349.93
  4505.8  344.21  4513.3  341.12  4534.8   340.4  4701.1   338.1  4805.3  339.68
  4814.6  339.74  4924.6  340.81    4982  341.26  4995.5  335.83  5007.6   335.1
  5010.3   334.6  5013.6   335.1  5015.1  342.42  5032.1  345.74  5044.5  342.61
  5076.8  344.29  5107.5  351.82  5121.5  357.44  5188.6  368.74  5241.7   375.1
#Mann= 8 ,-1 , 0
    4297     .16       0  4534.8     .12       0  4805.3     .16       0
  4814.6     .12       0  4924.6     .16       0  5007.6     .07       0
  5013.6     .16       0  5044.5     .12       0
Bank Sta=4982,5015.1
XS Rating Curve= 0 ,0
Exp/Cntr=0.3,0.1

Type RM Length L Ch R = 1 ,85156   ,377,377,377
BEGIN DESCRIPTION:
MANSON CREEK 122.0
END DESCRIPTION:
XS GIS Cut Line= 3
      3761849.59     10611260.19      3760949.61     10611360.19
      3760799.62     10611560.18
#Sta/Elev= 30
  4083.7  409.88  4093.7  408.46  4103.8  403.68  4113.9  401.55  4123.9  396.07
    4134  394.72  4184.3  377.52  4204.4  372.95  4234.6  368.66  4244.7  365.11
  4335.2  352.27  4345.3  347.85  4355.3  348.04  4385.5  340.46  4434.5  337.73
  4918.8  337.77  4979.2  339.64  4996.5   336.3  4999.8  333.69  5002.5  333.19
  5005.8  333.69  5017.3  338.54  5031.9  344.18  5052.8  341.54  5081.9  342.11
  5131.9  347.96  5196.5  357.44  5211.1  357.71  5217.3  360.99  5239.2  364.56
#Mann= 4 ,-1 , 0
  4083.7     .16       0  4434.5     .12       0  4999.8     .07       0
  5005.8     .12       0
Bank Sta=4979.2,5017.3
XS Rating Curve= 0 ,0
Exp/Cntr=0.3,0.1

Type RM Length L Ch R = 1 ,84779   ,386,386,386
BEGIN DESCRIPTION:
MANSON CREEK 121.0
END DESCRIPTION:
XS GIS Cut Line= 3
      3761981.81     10610686.01      3760995.74     10610852.67
      3760329.05     10611408.25
#Sta/Elev= 30
  3722.2  415.39  3785.3  391.62  3834.1  383.58  3856.3  384.81  3894.5  381.24
  3899.6  382.57  3998.3  368.66  4136.2  345.08    4212  339.14  4262.2  336.04
  4435.4  335.97  4585.2  335.77  4701.8  335.64  4840.4  335.18  4987.9  337.74
  4999.2  330.29    5002  329.79  5005.2  330.29  5016.5  336.26  5023.1  337.36
  5029.6  340.57  5043.9  340.17    5066  335.41    5243  337.95  5349.8  347.84
  5370.6  351.91  5413.6  355.22  5420.1  358.16  5529.8  370.79  5590.1   379.7
#Mann= 9 ,-1 , 0
  3722.2     .16       0    4212     .12       0  4435.4     .16       0
  4585.2     .12       0  4701.8     .16       0  4840.4     .12       0
  4999.2     .07       0  5005.2     .12       0  5529.8     .16       0
Bank Sta=4987.9,5023.1
XS Rating Curve= 0 ,0
Exp/Cntr=0.3,0.1

Type RM Length L Ch R = 1 ,84393   ,673,673,673
BEGIN DESCRIPTION:
MANSON CREEK 120.0
END DESCRIPTION:
XS GIS Cut Line= 3
      3761801.33     10609797.09      3760745.74     10610637.39
      3760003.67     10610921.74
#Sta/Elev= 30
  3518.9  368.08  3529.7  367.82  3564.9  361.96  3872.9  343.52    4063  337.49
  4205.6  336.81  4298.5  333.48  4625.2  334.57  4846.3  333.07  4927.8  334.67
  4981.8  335.55  4992.5  331.75  4996.8  328.09  4999.5  327.59  5002.8  328.09
  5024.2  335.24  5029.8  338.32  5035.3  338.52    5046  338.64  5059.8  334.87
  5078.2  334.52  5275.1  339.37  5463.7  343.05    5533  348.52  5553.4  352.01
  5602.9  359.51  5624.3  360.63  5642.4  364.24  5647.8  363.09  5662.8  365.78
#Mann= 8 ,-1 , 0
  3518.9     .16       0  3872.9     .12       0  4927.8     .16       0
  4996.8     .07       0  5002.8     .16       0  5024.2     .12       0
  5275.1     .16       0  5553.4     .05       0
Bank Sta=4981.8,5024.2
XS Rating Curve= 0 ,0
Exp/Cntr=0.3,0.1

Type RM Length L Ch R = 1 ,83720   ,479,479,479
BEGIN DESCRIPTION:
MANSON CREEK 119.0
END DESCRIPTION:
XS GIS Cut Line= 3
      3760649.65     10610160.17      3760449.61     10610260.19
      3759949.63     10610710.17
#Sta/Elev= 30
  4746.7  363.55  4791.5  359.18  4827.8  352.15  4858.5  341.97  4866.9  331.52
  4872.5  331.29  4880.9  327.25  4903.3  326.29  4911.7  323.72  4925.1  328.42
    4948  332.31  4973.7   332.7  4984.2  331.19  4988.6  319.62  4991.4  319.12
  4994.6  319.62  5005.9  321.63  5026.8  336.02  5055.2  335.78  5062.7  332.32
  5069.1  332.03  5307.6  334.87  5366.9  336.62  5395.3   341.6  5430.4  343.35
  5437.9  345.67  5473.4  348.78  5501.4  351.49  5529.8  358.64    5643  373.35
#Mann= 7 ,-1 , 0
  4746.7     .12       0  4925.1     .16       0  4988.6     .07       0
  4994.6     .16       0  5069.1     .12       0  5307.6     .16       0
  5473.4     .05       0
Bank Sta=4973.7,5026.8
XS Rating Curve= 0 ,0
Exp/Cntr=0.3,0.1

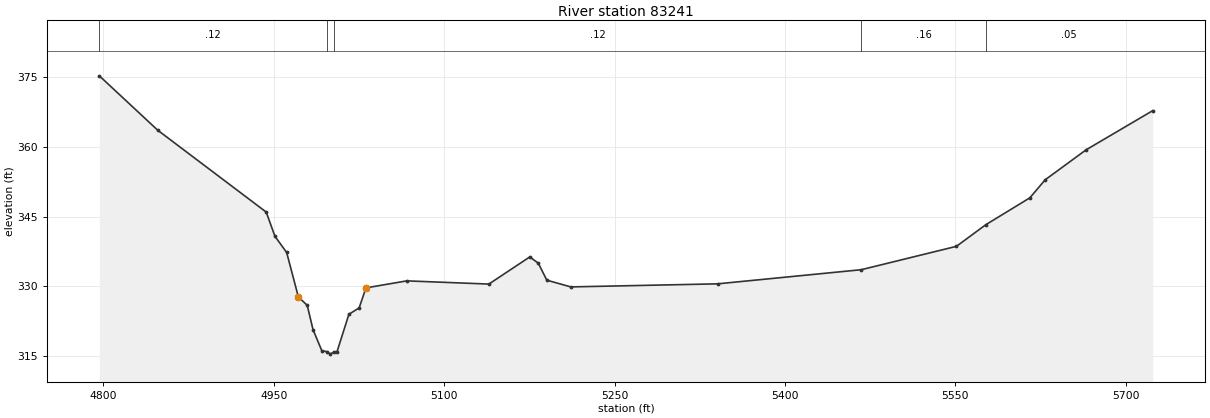
Type RM Length L Ch R = 1 ,83241   ,217,217,217
BEGIN DESCRIPTION:
MANSON CREEK 118.0
END DESCRIPTION:
XS GIS Cut Line= 3
       3760599.6     10609810.19      3760399.61     10609860.19
      3759799.57     10610260.21
#Sta/Elev= 30
  4796.4  375.27  4847.9  363.55  4943.3  345.96    4951  340.74  4961.3  337.27
  4971.6  327.71  4979.4   325.9  4984.5  320.68  4992.2  316.16    4997   315.9
  4999.7   315.4    5003   315.9  5005.6   315.9  5016.1  323.98  5025.1  325.34
  5031.1  329.65  5067.1  331.16  5139.3  330.47  5175.3  336.31  5182.8  334.97
  5190.3  331.31  5211.4  329.86  5340.6  330.52  5467.1  333.56  5550.9  338.59
  5576.8  343.25  5615.5  349.02    5629   352.9  5665.1  359.36  5723.7  367.78
#Mann= 5 ,-1 , 0
  4796.4     .12       0    4997     .07       0    5003     .12       0
  5467.1     .16       0  5576.8     .05       0
Bank Sta=4971.6,5031.1
XS Rating Curve= 0 ,0
Exp/Cntr=0.3,0.1