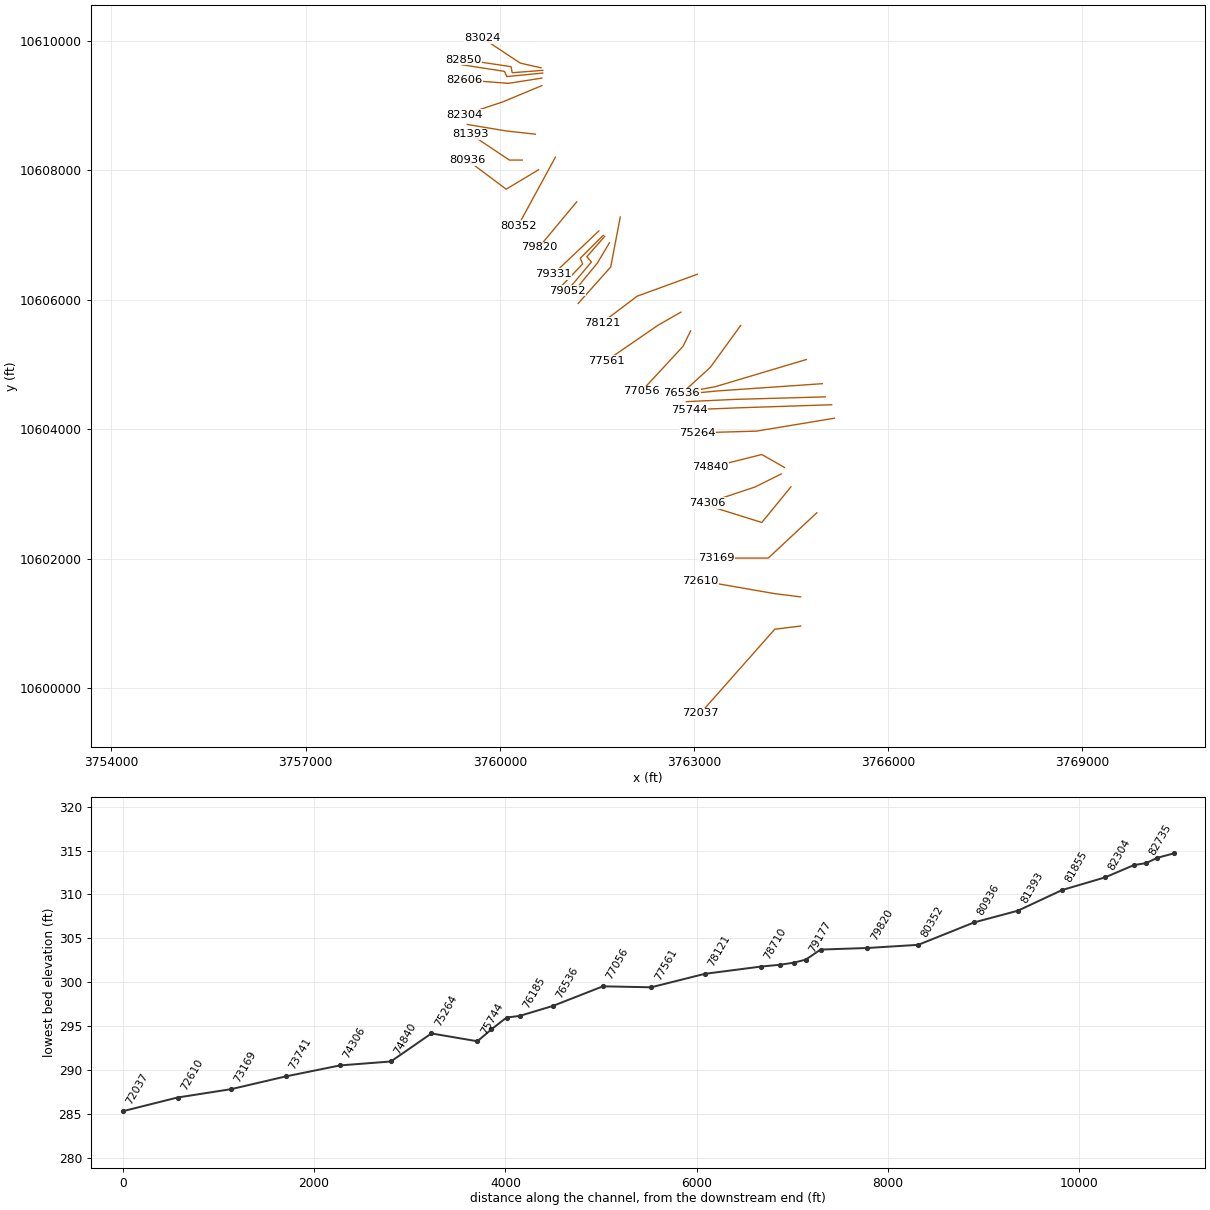
HEC-RAS study MANSON CREEK.prj: MANSON CREEK Base Level Engineering

--- MANSON CREEK.g01 (geometry) --- (continued)

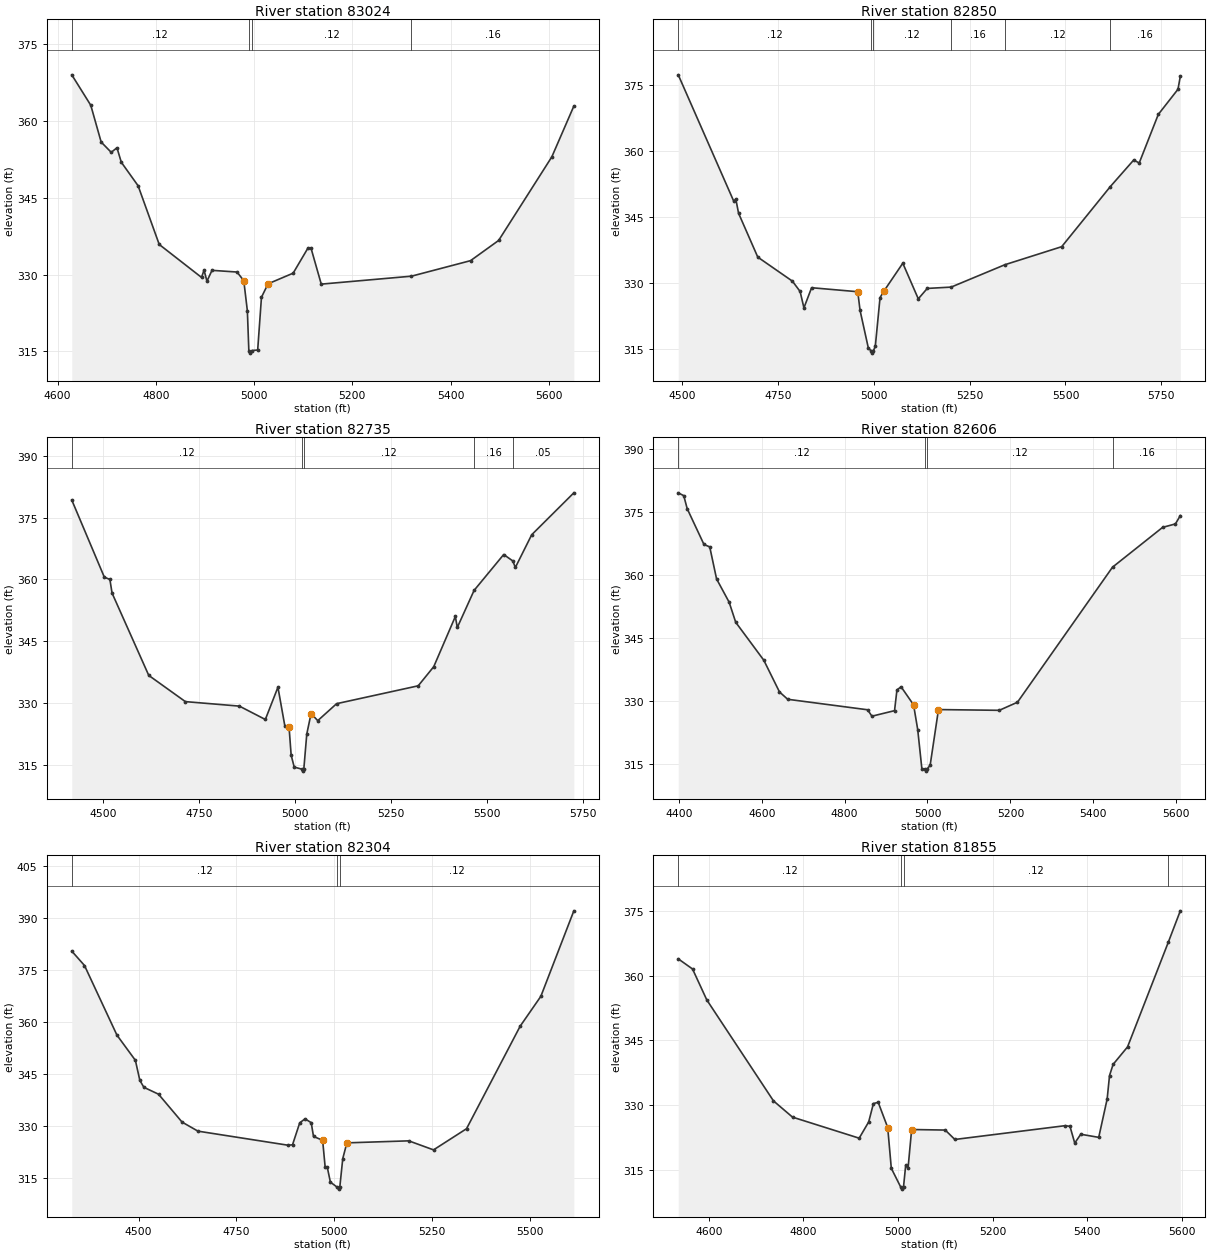
Type RM Length L Ch R = 1 ,83024   ,174,174,174
BEGIN DESCRIPTION:
Mapping XS c204af09
END DESCRIPTION:
XS GIS Cut Line= 3
      3760637.91      10609585.6       3760317.6     10609658.52
      3759739.46     10610041.34
#Sta/Elev= 30
  4628.9  368.96  4667.6  363.02  4688.7  355.85  4709.2  353.84  4720.9  354.73
  4729.7  351.91  4763.9  347.32  4806.9  335.87    4893  329.44  4898.1  330.85
  4904.1  328.71  4914.3  330.82  4965.2  330.49    4979  328.81  4986.3  322.92
  4989.3  315.17    4992  314.67  4995.3  315.17  5007.3  315.28    5015  325.57
  5028.4  328.19  5079.5  330.27  5109.7  335.18  5115.7   335.2  5136.7  328.13
  5320.3  329.68  5440.6  332.71  5497.7  336.65    5606  352.96  5650.8  362.86
#Mann= 4 ,-1 , 0
  4628.9     .12       0  4989.3     .07       0  4995.3     .12       0
  5320.3     .16       0
Bank Sta=4979,5028.4
XS Rating Curve= 0 ,0
Exp/Cntr=0.3,0.1

Type RM Length L Ch R = 1 ,82850   ,115,115,115
BEGIN DESCRIPTION:
Mapping XS c0c359c1
END DESCRIPTION:
XS GIS Cut Line= 4
      3760666.52     10609546.53       3760192.6     10609510.08
      3760174.37     10609603.83      3759443.62     10609713.05
#Sta/Elev= 30
  4489.9  377.31    4635  348.58    4640  349.17  4647.3   345.9  4697.4  335.95
  4787.7   330.5  4807.8  328.16  4817.8  324.44  4837.8  329.01  4958.2   328.1
  4964.2  323.87  4985.7  315.37  4992.9  314.67  4995.6  314.17  4998.9  314.67
    5004  315.74  5016.3  326.76  5026.5  328.25  5075.7  334.57  5116.1  326.49
  5139.5  328.85  5201.8  329.15  5342.1  334.23  5490.2  338.32  5616.7  351.92
    5678  357.98  5692.4  357.31  5742.2  368.33  5793.5  374.03  5799.6  376.97
#Mann= 6 ,-1 , 0
  4489.9     .12       0  4992.9     .07       0  4998.9     .12       0
  5201.8     .16       0  5342.1     .12       0  5616.7     .16       0
Bank Sta=4958.2,5026.5
XS Rating Curve= 0 ,0
Exp/Cntr=0.3,0.1

Type RM Length L Ch R = 1 ,82735   ,129,129,129
BEGIN DESCRIPTION:
MANSON CREEK 117.0
END DESCRIPTION:
XS GIS Cut Line= 4
      3760663.97     10609504.87      3760109.27     10609450.18
      3760072.81     10609530.91      3759419.12     10609632.48
#Sta/Elev= 30
  4418.5  379.25  4503.3  360.56  4517.8     360  4523.4  356.71    4619  336.76
  4714.3  330.41    4855  329.32  4922.6  326.08  4955.4   333.9  4973.2  324.61
  4984.3  324.33  4989.8  317.44  4997.8  314.55  5016.8  314.07  5019.5  313.57
  5022.8  314.07  5030.5  322.55  5041.7  327.52  5059.1   325.8  5108.2  329.91
  5320.7  334.24  5361.2  338.88  5417.4  351.03  5422.5  348.37  5466.2  357.35
  5543.3  366.04  5566.9   364.5  5573.7  362.91  5616.3  370.84    5726  380.99
#Mann= 5 ,-1 , 0
  4418.5     .12       0  5016.8     .07       0  5022.8     .12       0
  5466.2     .16       0  5566.9     .05       0
Bank Sta=4984.3,5041.7
XS Rating Curve= 0 ,0
Exp/Cntr=0.3,0.1

Type RM Length L Ch R = 1 ,82606   ,302,302,302
BEGIN DESCRIPTION:
Mapping XS 8661175e
END DESCRIPTION:
XS GIS Cut Line= 3
      3760650.97     10609426.75      3760135.31     10609346.02
      3759447.82      10609398.1
#Sta/Elev= 30
  4398.6  379.66  4411.9  378.98  4420.2  375.89  4460.7  367.35  4474.6  366.78
  4491.1  359.14  4521.4   353.6  4537.3  348.81  4605.1  339.76  4642.9  332.21
  4662.7  330.46  4855.5  327.96  4865.9  326.43  4920.5  327.75  4926.3  332.69
  4936.3  333.44  4966.4  329.14  4976.4  323.25  4986.4  313.93  4993.5  313.84
  4996.2  313.34  4999.5  313.84  5006.5   314.8  5026.5  328.01  5173.2  327.83
  5217.1  329.76  5446.4  361.94  5567.3  371.43  5598.2  372.25    5610  374.24
#Mann= 4 ,-1 , 0
  4398.6     .12       0  4993.5     .07       0  4999.5     .12       0
  5446.4     .16       0
Bank Sta=4966.4,5026.5
XS Rating Curve= 0 ,0
Exp/Cntr=0.3,0.1

Type RM Length L Ch R = 1 ,82304   ,449,449,449
BEGIN DESCRIPTION:
MANSON CREEK 116.0
END DESCRIPTION:
XS GIS Cut Line= 3
      3760649.63      10609310.2      3760049.61     10609060.19
      3759449.59     10608860.18
#Sta/Elev= 30
  4329.4  380.41  4361.9  376.27  4444.8  356.24  4491.9  348.99  4503.3  343.22
  4513.6  341.23    4551  339.25  4611.1  331.23  4651.7  328.62  4881.9  324.57
  4893.3   324.7  4911.7  331.01  4925.3  332.16    4941  331.06  4946.9   327.1
  4970.2  325.99  4976.7  318.22  4982.1  318.22    4990  313.96    5008  312.44
  5010.8  311.94    5014  312.44  5021.6  320.71  5032.1  325.25  5190.2  325.83
  5253.5  323.23  5337.8  329.32  5474.8  358.82  5527.6   367.4  5611.9     392
#Mann= 3 ,-1 , 0
  4329.4     .12       0    5008     .07       0    5014     .12       0
Bank Sta=4970.2,5032.1
XS Rating Curve= 0 ,0
Exp/Cntr=0.3,0.1

Type RM Length L Ch R = 1 ,81855   ,462,462,462
BEGIN DESCRIPTION:
MANSON CREEK 115.0
END DESCRIPTION:
XS GIS Cut Line= 3
      3760549.63     10608560.19      3760099.61     10608610.19
      3759499.58     10608710.19
#Sta/Elev= 30
  4535.4  363.88  4565.6  361.53  4595.8  354.35  4736.7  330.95  4776.9  327.19
  4917.8  322.31  4937.9  326.08  4947.9  330.34    4958  330.62  4978.1  324.78
  4985.7  315.33  5005.5     311  5008.2   310.5  5011.5     311  5016.1  316.01
  5021.1  315.39  5028.7  324.32  5099.7  324.19    5120  322.01  5353.2  325.21
  5363.3  325.05  5373.4  321.17  5386.1  323.22  5424.1   322.5  5441.9   331.4
  5446.9  336.83  5454.5  339.42    5485  343.47  5571.3  367.78  5596.5  375.01
#Mann= 4 ,-1 , 0
  4535.4     .12       0  5005.5     .07       0  5011.5     .12       0
  5571.3     .16       0
Bank Sta=4978.1,5028.7
XS Rating Curve= 0 ,0
Exp/Cntr=0.3,0.1

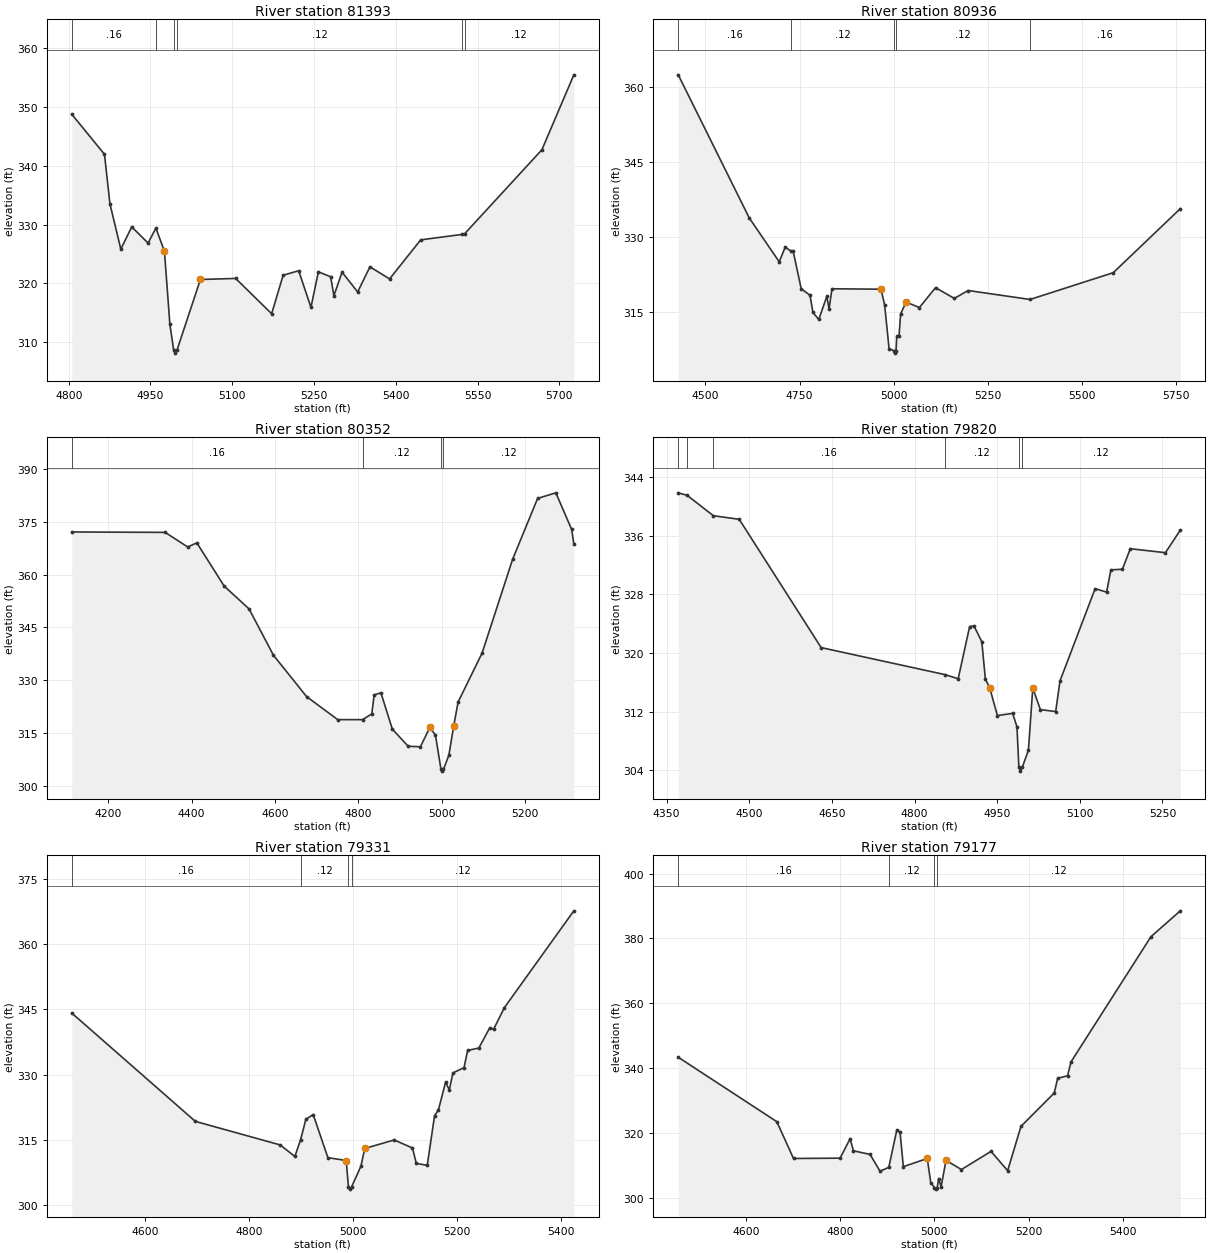
Type RM Length L Ch R = 1 ,81393   ,457,457,457
BEGIN DESCRIPTION:
MANSON CREEK 114.0
END DESCRIPTION:
XS GIS Cut Line= 3
      3760349.58     10608160.19      3760149.61     10608160.19
      3759549.59      10608560.2
#Sta/Elev= 30
  4805.6  348.77  4865.6  341.96  4875.6  333.54  4895.6  325.83  4915.6  329.62
  4945.6  326.86  4959.9  329.41  4975.6  325.48  4985.6  313.03  4992.6  308.65
  4995.3  308.15  4998.6  308.65  5041.6  320.67  5106.2  320.85  5172.3  314.85
  5193.4  321.39  5221.9  322.16  5244.4  315.93    5258  321.97  5280.5  321.14
  5286.5  317.91  5301.5  321.91  5330.1  318.55  5352.6  322.82  5388.7  320.77
  5445.7  327.41  5522.1  328.34  5526.8  328.49  5668.1  342.73  5726.7  355.47
#Mann= 6 ,-1 , 0
  4805.6     .16       0  4959.9     .12       0  4992.6     .07       0
  4998.6     .12       0  5522.1     .16       0  5526.8     .12       0
Bank Sta=4975.6,5041.6
XS Rating Curve= 0 ,0
Exp/Cntr=0.3,0.1

Type RM Length L Ch R = 1 ,80936   ,584,584,584
BEGIN DESCRIPTION:
MANSON CREEK 113.0
END DESCRIPTION:
XS GIS Cut Line= 3
      3760599.61     10608010.19      3760099.61     10607710.19
       3759499.6     10608160.19
#Sta/Elev= 30
    4428  362.42  4616.5  333.84  4696.2  325.05  4711.8  327.97  4728.4  327.17
  4733.2  327.16  4754.5  319.68  4777.9  318.38  4785.6  314.95  4801.2  313.54
  4822.6  318.18  4828.4  315.62  4836.2  319.68  4966.4  319.59  4976.1   316.4
  4987.8  307.73  5000.3  307.32  5003.1  306.82  5006.3  307.32  5008.2  310.16
  5014.2  310.16  5018.4  314.63    5033  317.02  5068.4  315.93  5111.1   319.9
  5161.1  317.75  5197.6  319.33  5362.1  317.54    5583  322.89  5761.1  335.68
#Mann= 5 ,-1 , 0
    4428     .16       0  4728.4     .12       0  5000.3     .07       0
  5006.3     .12       0  5362.1     .16       0
Bank Sta=4966.4,5033
XS Rating Curve= 0 ,0
Exp/Cntr=0.3,0.1

Type RM Length L Ch R = 1 ,80352   ,532,532,532
BEGIN DESCRIPTION:
MANSON CREEK 112.0
END DESCRIPTION:
XS GIS Cut Line= 2
      3760860.11     10608205.01      3760284.17      10607146.8
#Sta/Elev= 30
  4112.3  372.09  4336.4  371.97  4390.6  367.83  4412.4  369.01  4477.9  356.76
  4537.8  350.26    4596  337.18  4675.7  325.41  4750.5  318.87  4810.1  318.87
  4832.2  320.49  4837.9  325.86  4854.1   326.5  4881.6  316.16  4919.6  311.33
  4948.9  311.17  4971.7  316.69  4985.1  314.44  4998.3  304.77    5001  304.27
  5004.3  304.77  5017.2  308.79  5028.8  317.05  5039.3  323.85  5096.9  337.73
  5170.3  364.39  5230.2  381.61  5273.9  383.19  5311.9   372.8  5317.1  368.65
#Mann= 4 ,-1 , 0
  4112.3     .16       0  4810.1     .12       0  4998.3     .07       0
  5004.3     .12       0
Bank Sta=4971.7,5028.8
XS Rating Curve= 0 ,0
Exp/Cntr=0.3,0.1

Type RM Length L Ch R = 1 ,79820   ,489,489,489
BEGIN DESCRIPTION:
MANSON CREEK 111.0
END DESCRIPTION:
XS GIS Cut Line= 2
      3761189.99     10607515.28      3760606.85     10606814.99
#Sta/Elev= 30
  4371.1  341.85  4387.4   341.5  4434.9  338.73  4481.8  338.24  4630.5  320.75
  4855.8  317.06  4879.2   316.5    4900  323.61  4907.8  323.71  4922.1  321.56
  4928.6  316.44  4936.4  315.29  4950.3  311.49  4978.1  311.78  4985.9  309.95
  4989.4  304.41  4992.2  303.91  4995.4  304.41  5006.7  306.75  5014.6  315.22
  5028.4   312.3  5056.2  312.03    5064   316.2  5127.8  328.79  5148.6  328.31
  5156.4  331.35  5177.3  331.43  5191.6  334.23  5255.4  333.69  5282.4  336.77
#Mann= 6 ,-1 , 0
  4371.1     .16       0  4387.4     .12       0  4434.9     .16       0
  4855.8     .12       0  4989.4     .07       0  4995.4     .12       0
Bank Sta=4936.4,5014.6
XS Rating Curve= 0 ,0
Exp/Cntr=0.3,0.1

Type RM Length L Ch R = 1 ,79331   ,154,154,154
BEGIN DESCRIPTION:
Mapping XS b1357413
END DESCRIPTION:
XS GIS Cut Line= 2
      3761531.14     10607064.76      3760830.65     10606400.73
#Sta/Elev= 30
  4458.9  344.15  4696.5  319.28  4859.5  313.88  4887.8  311.23  4898.8  315.07
  4908.9  319.75    4923  320.86  4951.3  310.95  4986.5   310.3  4990.8  304.23
  4993.5  303.73  4996.8  304.23  5014.8     309  5022.1  313.06  5078.7  315.02
  5113.9  313.17  5121.2  309.64  5142.3  309.19  5156.4  320.63  5163.7  321.89
  5177.5  328.27  5184.7  326.51  5191.6  330.41    5213  331.62  5219.9  335.57
  5241.4  336.12  5262.4  340.75  5269.7  340.41  5290.7  345.42  5424.1  367.62
#Mann= 4 ,-1 , 0
  4458.9     .16       0  4898.8     .12       0  4990.8     .07       0
  4996.8     .12       0
Bank Sta=4986.5,5022.1
XS Rating Curve= 0 ,0
Exp/Cntr=0.3,0.1

Type RM Length L Ch R = 1 ,79177   ,125,125,125
BEGIN DESCRIPTION:
MANSON CREEK 110.0
END DESCRIPTION:
XS GIS Cut Line= 4
      3761598.88     10606997.09      3761244.68     10606642.89
      3761281.14     10606554.35      3760955.63     10606215.82
#Sta/Elev= 30
    4456  343.31  4665.4  323.41  4700.8  312.05  4799.8  312.15    4821  318.16
  4828.1  314.42  4863.4  313.31  4884.6  308.11  4903.2  309.32    4920  320.72
  4927.1  320.19  4934.1  309.53  4984.9  312.05  4992.3   304.6  5000.1  303.09
  5002.8  302.59  5006.1  303.09  5008.9  305.85  5014.3  303.33  5024.7  311.48
  5057.4  308.64  5120.3  314.25  5155.6  308.29  5183.9  321.97  5254.6  332.27
  5261.8   336.8  5282.9  337.59  5290.1  341.86  5459.9  380.52  5522.3  388.51
#Mann= 4 ,-1 , 0
    4456     .16       0  4903.2     .12       0  5000.1     .07       0
  5006.1     .12       0
Bank Sta=4984.9,5024.7
XS Rating Curve= 0 ,0
Exp/Cntr=0.3,0.1

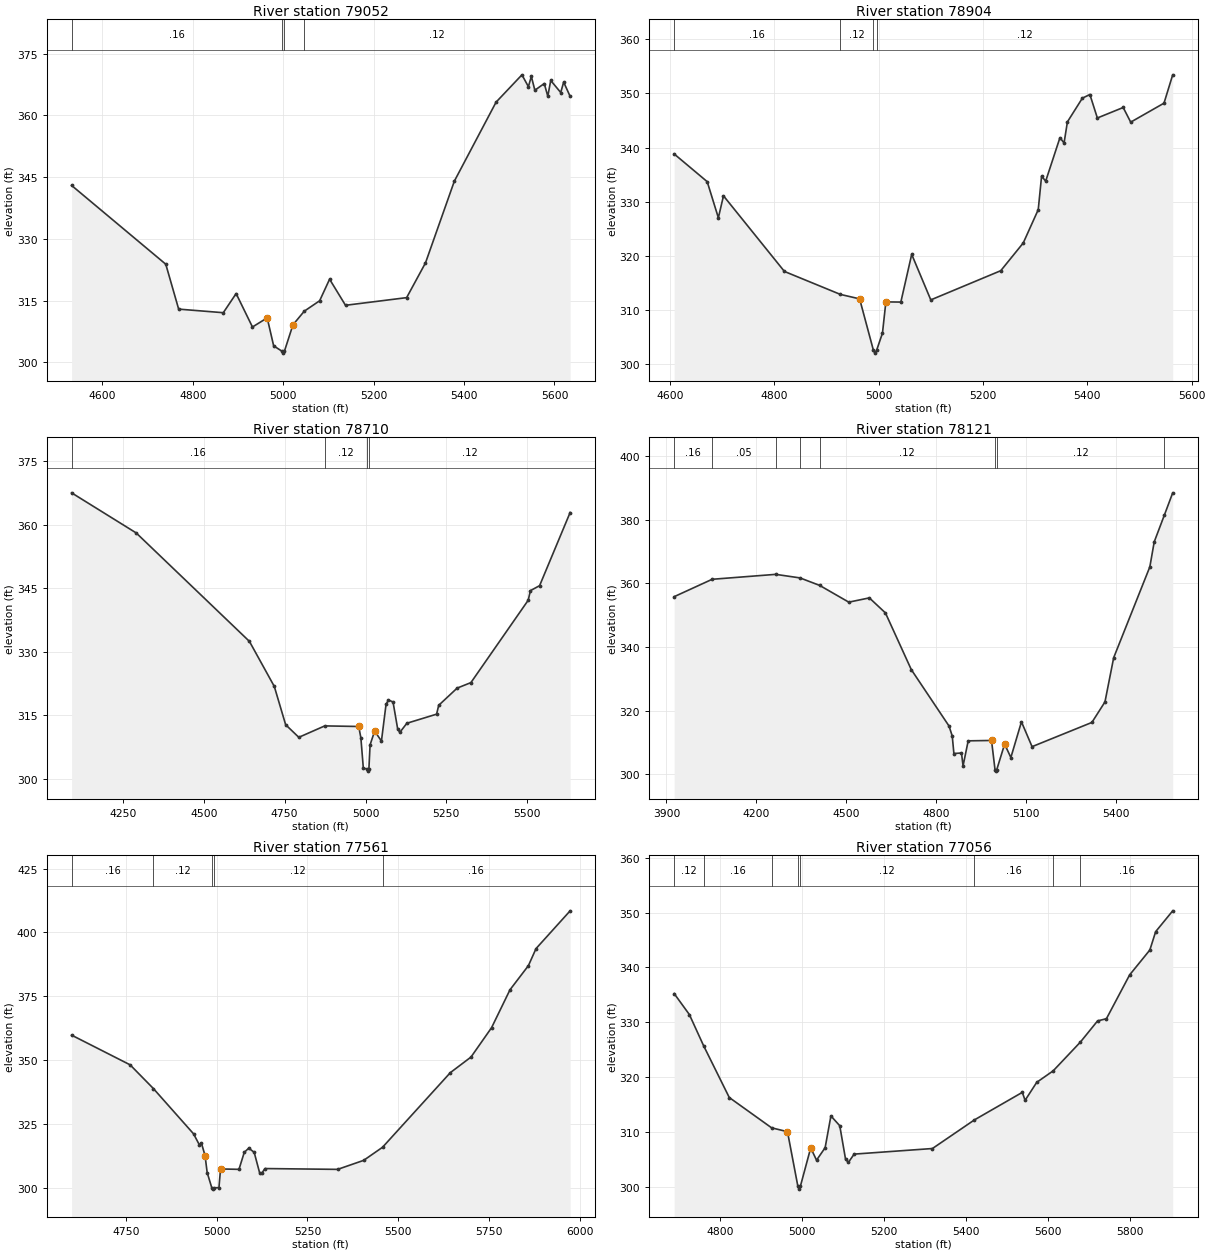
Type RM Length L Ch R = 1 ,79052   ,148,148,148
BEGIN DESCRIPTION:
Mapping XS dd8b103c
END DESCRIPTION:
XS GIS Cut Line= 4
      3761622.27     10606981.41      3761346.25     10606666.33
      3761416.56      10606585.6      3761045.35      10606144.3
#Sta/Elev= 30
    4532  342.98  4740.3  323.84  4768.8  312.93  4867.5  312.06  4895.9  316.71
    4932  308.59  4964.6   310.8  4978.9  304.01  4996.8  302.74  4999.5  302.24
  5002.8  302.74  5021.6  309.12  5046.6  312.43  5080.6  314.96  5102.6   320.2
  5137.8  313.86    5273  315.72  5314.7  324.16  5378.6  344.04  5470.8  363.21
    5528  369.85  5542.3  366.97  5548.8  369.46  5556.6  366.11  5577.4  367.73
  5585.2  364.65  5591.7  368.48  5613.8  365.55  5620.3  368.08  5634.6  364.61
#Mann= 4 ,-1 , 0
    4532     .16       0  4996.8     .07       0  5002.8     .16       0
  5046.6     .12       0
Bank Sta=4964.6,5021.6
XS Rating Curve= 0 ,0
Exp/Cntr=0.3,0.1

Type RM Length L Ch R = 1 ,78904   ,194,194,194
BEGIN DESCRIPTION:
Mapping XS 037ad34b
END DESCRIPTION:
XS GIS Cut Line= 3
      3761695.21     10606882.49       3761507.7     10606567.37
      3761133.63     10606112.77
#Sta/Elev= 30
  4608.3  338.82  4671.6   333.7    4693  327.02  4702.8  331.08  4819.6   317.1
  4926.7  312.86  4963.7  312.03  4990.2   302.5  4992.9     302  4996.2   302.5
  5007.5  305.71    5014  311.47  5042.7  311.44  5063.5  320.26  5100.1  311.84
  5234.2  317.24  5277.3  322.37    5306  328.52  5312.4  334.71  5320.3   333.8
  5347.6  341.83  5355.5  340.85  5361.9  344.75  5390.6  349.14    5405  349.81
  5419.3  345.47  5468.8  347.41  5483.2   344.7    5547  348.21  5563.7  353.45
#Mann= 4 ,-1 , 0
  4608.3     .16       0  4926.7     .12       0  4990.2     .07       0
  4996.2     .12       0
Bank Sta=4963.7,5014
XS Rating Curve= 0 ,0
Exp/Cntr=0.3,0.1

Type RM Length L Ch R = 1 ,78710   ,589,589,589
BEGIN DESCRIPTION:
MANSON CREEK 109.0
END DESCRIPTION:
XS GIS Cut Line= 3
      3761862.31     10607280.35      3761714.75     10606507.83
        3761212.     10605944.41
#Sta/Elev= 30
  4091.1  367.57  4290.9  358.09    4641  332.46  4717.9  321.82    4753  312.77
  4793.7  309.79    4874  312.49  4978.9  312.35  4985.6  309.69  4993.2  302.52
  5004.4   302.3  5007.1   301.8  5010.4   302.3  5014.1  308.01  5028.3  311.28
  5049.2  308.89  5063.4  317.55  5070.9  318.63  5085.1  318.13  5099.3  311.83
    5106  310.95  5127.8  313.11  5219.7  315.26  5226.4  317.36  5283.3  321.42
  5325.9  322.72  5503.1  342.19  5509.8  344.45  5538.3  345.63  5632.7  362.92
#Mann= 4 ,-1 , 0
  4091.1     .16       0    4874     .12       0  5004.4     .07       0
  5010.4     .12       0
Bank Sta=4978.9,5028.3
XS Rating Curve= 0 ,0
Exp/Cntr=0.3,0.1

Type RM Length L Ch R = 1 ,78121   ,560,560,560
BEGIN DESCRIPTION:
MANSON CREEK 108.0
END DESCRIPTION:
XS GIS Cut Line= 3
      3763051.58     10606394.99      3762122.73     10606056.44
       3761584.6      10605648.5
#Sta/Elev= 30
    3926  355.81  4052.8  361.28  4264.9  362.83  4346.1  361.71  4411.7  359.35
  4508.8  354.09  4577.4  355.43  4631.1  350.71  4717.5  332.87  4843.4  315.14
  4854.1  312.01  4859.6  306.51  4884.9  306.67  4890.2  302.62  4907.3  310.49
  4985.2  310.61  4996.8  301.47  4999.5  300.97  5002.8  301.47  5028.9  309.46
  5049.7  305.25  5085.1  316.47  5120.5  308.66  5320.2  316.28  5363.8  322.73
  5392.9  336.63  5513.6  365.19  5528.2  373.04  5561.8  381.39  5589.9  388.46
#Mann= 8 ,-1 , 0
    3926     .16       0  4052.8     .05       0  4264.9     .12       0
  4346.1     .16       0  4411.7     .12       0  4996.8     .07       0
  5002.8     .12       0  5561.8     .16       0
Bank Sta=4985.2,5028.9
XS Rating Curve= 0 ,0
Exp/Cntr=0.3,0.1

Type RM Length L Ch R = 1 ,77561   ,505,505,505
BEGIN DESCRIPTION:
MANSON CREEK 107.0
END DESCRIPTION:
XS GIS Cut Line= 3
      3762799.59     10605810.18      3762449.61     10605610.19
      3761649.63      10605060.2
#Sta/Elev= 30
    4600  359.77  4761.2  348.14  4825.3  338.86  4936.2  321.09    4952  316.81
  4957.7  317.53  4967.8  312.59  4973.6  305.95  4986.4  299.94  4989.2  299.44
  4992.4  299.94  5006.1  300.03  5010.5  307.35  5061.3  307.19  5075.9  313.86
  5088.3  315.49  5103.2  313.85  5118.1  305.88  5124.4  305.75    5133   307.5
  5333.2  307.18  5404.9  310.71  5456.9  315.84  5643.8  345.08  5700.6  351.17
  5757.4  362.69  5808.2  377.55  5858.9  386.99  5879.9  393.67  5973.9  408.47
#Mann= 5 ,-1 , 0
    4600     .16       0  4825.3     .12       0  4986.4     .07       0
  4992.4     .12       0  5456.9     .16       0
Bank Sta=4967.8,5010.5
XS Rating Curve= 0 ,0
Exp/Cntr=0.3,0.1

Type RM Length L Ch R = 1 ,77056   ,520,520,520
BEGIN DESCRIPTION:
MANSON CREEK 106.0
END DESCRIPTION:
XS GIS Cut Line= 3
      3762949.77     10605520.96      3762832.57     10605282.21
      3762186.67     10604584.29
#Sta/Elev= 30
  4688.1  335.24  4725.2  331.41  4759.9  325.73  4822.6  316.27  4925.9  310.74
  4964.7  310.03  4990.1  300.05  4992.8  299.55  4996.1  300.05  5021.4  307.08
  5035.6  304.83  5056.6  307.11  5070.7  312.91  5092.3  311.12  5106.4  305.03
  5113.3  304.42  5127.4  305.94  5318.5  306.96  5420.9  312.18  5537.9  317.21
  5544.7  315.76  5573.1  319.04  5613.3  321.14  5679.6  326.38  5721.6  330.25
  5743.2  330.65  5799.9  338.65  5849.2  343.19  5863.4  346.54    5905  350.34
#Mann= 8 ,-1 , 0
  4688.1     .12       0  4759.9     .16       0  4925.9     .12       0
  4990.1     .07       0  4996.1     .12       0  5420.9     .16       0
  5613.3     .12       0  5679.6     .16       0
Bank Sta=4964.7,5021.4
XS Rating Curve= 0 ,0
Exp/Cntr=0.3,0.1

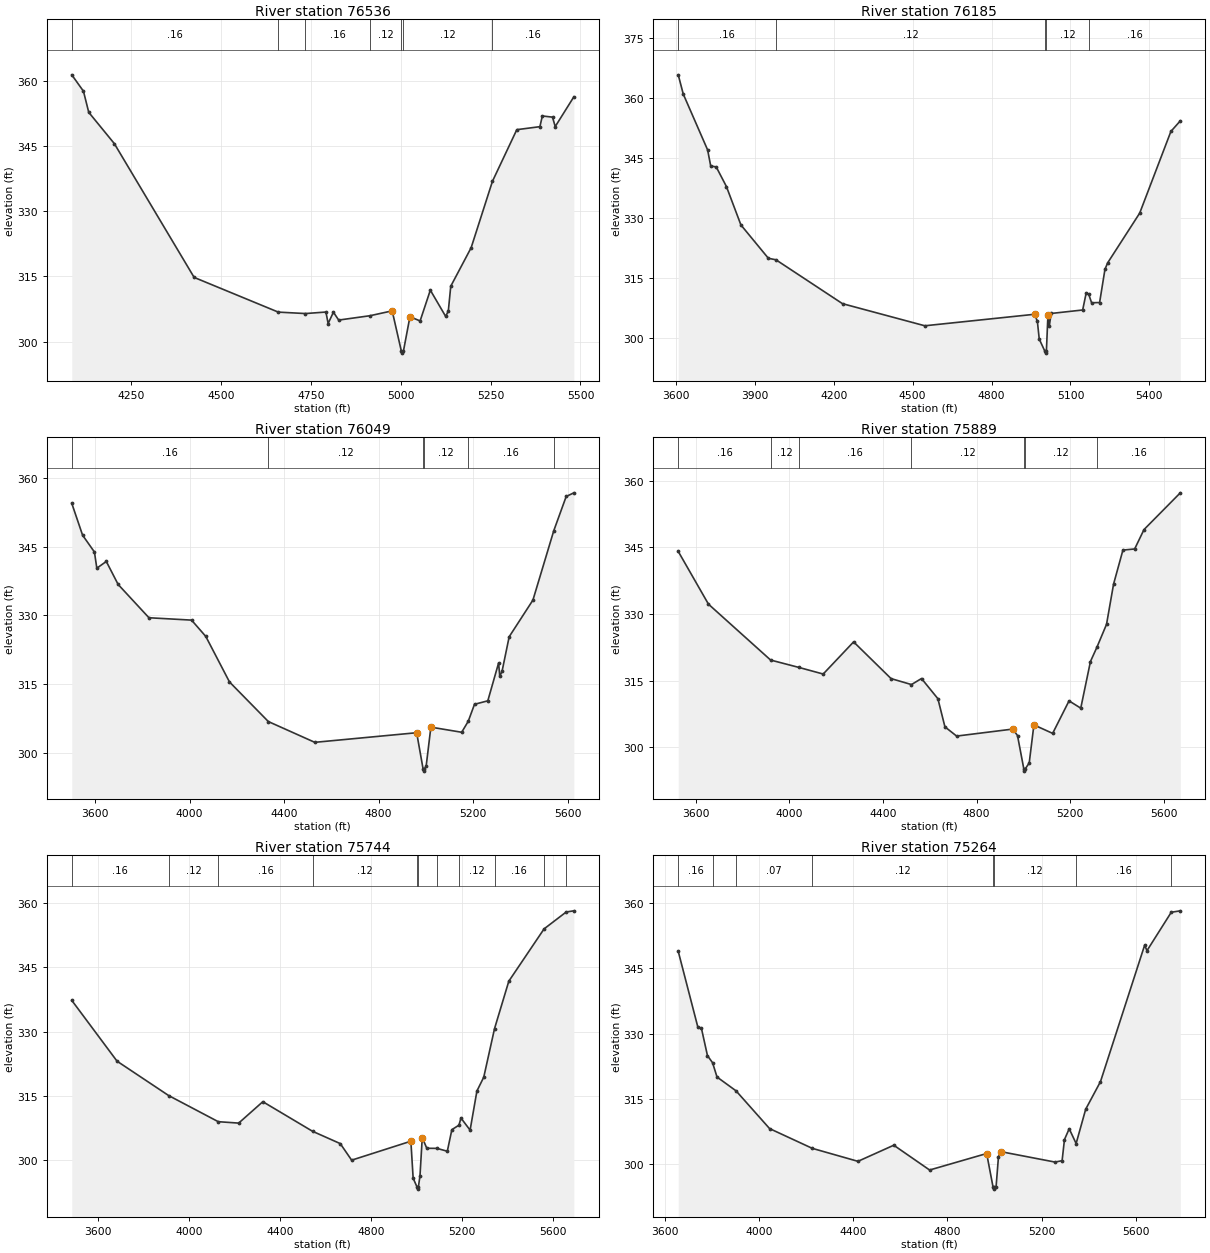
Type RM Length L Ch R = 1 ,76536   ,351,351,351
BEGIN DESCRIPTION:
MANSON CREEK 105.0
END DESCRIPTION:
XS GIS Cut Line= 3
      3763722.33     10605603.39      3763253.58     10604956.69
      3762812.07     10604554.14
#Sta/Elev= 30
  4085.4  361.32  4117.9  357.55  4132.6   352.7  4203.7  345.51  4425.7  314.74
  4659.7  306.76  4735.3  306.43  4792.2  306.78  4798.3  304.14    4813  306.74
  4827.7  304.93  4914.6  305.93  4976.4  307.05  5001.8  297.83  5004.6  297.33
  5007.8  297.83  5025.8   305.7  5054.1  304.73  5082.5  311.81  5125.1  305.78
  5132.5  306.98  5139.3  312.71    5196  321.57  5255.3  336.85    5323  348.71
  5387.2   349.4    5394  351.86  5422.3  351.59  5429.8  349.42  5481.6  356.26
#Mann= 7 ,-1 , 0
  4085.4     .16       0  4659.7     .12       0  4735.3     .16       0
  4914.6     .12       0  5001.8     .07       0  5007.8     .12       0
  5255.3     .16       0
Bank Sta=4976.4,5025.8
XS Rating Curve= 0 ,0
Exp/Cntr=0.3,0.1

Type RM Length L Ch R = 1 ,76185   ,136,136,136
BEGIN DESCRIPTION:
Mapping XS a4c53317
END DESCRIPTION:
XS GIS Cut Line= 3
      3764737.99     10605078.23      3763327.37     10604657.21
      3762897.73      10604579.1
#Sta/Elev= 30
  3608.7  365.79  3627.9  360.96  3720.4  347.01  3732.2  342.98  3753.1  342.76
  3791.9  337.85    3847  328.24  3951.4   319.9  3980.1  319.53  4233.2  308.55
  4546.2  303.02  4963.7   305.9  4974.1  304.12  4981.2  299.69  5002.4  296.68
  5005.2  296.18  5008.4  296.68  5014.3  305.83  5019.5  302.96  5026.3   306.1
  5146.3  306.97  5159.8  311.28  5169.3   310.9  5180.2  308.77  5210.7  308.84
    5231  317.14  5241.2  318.75  5363.1   331.2  5481.7  351.63  5517.5  354.28
#Mann= 5 ,-1 , 0
  3608.7     .16       0  3980.1     .12       0  5002.4     .07       0
  5008.4     .12       0  5169.3     .16       0
Bank Sta=4963.7,5014.3
XS Rating Curve= 0 ,0
Exp/Cntr=0.3,0.1

Type RM Length L Ch R = 1 ,76049   ,160,160,160
BEGIN DESCRIPTION:
MANSON CREEK 104.0
END DESCRIPTION:
XS GIS Cut Line= 3
      3764985.32     10604704.95      3763357.75     10604592.11
      3762867.34     10604544.37
#Sta/Elev= 30
  3501.7  354.51  3547.5  347.54  3597.6  343.87  3607.7  340.33  3647.8  341.81
  3697.9  336.78  3828.2  329.51  4008.6  328.99  4068.8  325.42    4169  315.48
  4333.4  306.83  4529.9  302.29  4960.9  304.39    4988   296.5  4990.7     296
    4994   296.5    5001  297.06    5021  305.61  5151.4  304.49  5179.1  306.89
  5205.6   310.6  5261.9  311.36  5307.5  319.62  5312.5  316.73  5322.2  317.82
  5352.3  325.36  5452.8  333.37  5541.1  348.54  5593.5     356  5625.9   356.8
#Mann= 6 ,-1 , 0
  3501.7     .16       0  4333.4     .12       0    4988     .07       0
    4994     .12       0  5179.1     .16       0  5541.1     .05       0
Bank Sta=4960.9,5021
XS Rating Curve= 0 ,0
Exp/Cntr=0.3,0.1

Type RM Length L Ch R = 1 ,75889   ,145,145,145
BEGIN DESCRIPTION:
MANSON CREEK 103.0
END DESCRIPTION:
XS GIS Cut Line= 3
      3765028.72     10604500.96      3763631.18      10604461.9
      3762884.67     10604427.18
#Sta/Elev= 30
  3524.9  344.11  3654.1  332.23  3919.6  319.65  4040.4  317.99  4144.3   316.5
  4274.3  323.74  4434.4  315.47  4521.5  314.13  4564.4  315.49  4634.4  310.95
  4664.5  304.61  4714.5  302.53  4954.6  304.11  4974.6  302.65  5001.6  295.14
  5004.4  294.64  5007.6  295.14  5024.7  296.49  5044.7  305.05  5124.8  303.14
  5194.8  310.46  5244.9  308.82  5286.3  319.32  5313.7   322.5    5355  327.69
  5385.1  336.75  5425.1  344.41  5475.2  344.66  5515.2  349.03  5670.3   357.3
#Mann= 7 ,-1 , 0
  3524.9     .16       0  3919.6     .12       0  4040.4     .16       0
  4521.5     .12       0  5001.6     .07       0  5007.6     .12       0
  5313.7     .16       0
Bank Sta=4954.6,5044.7
XS Rating Curve= 0 ,0
Exp/Cntr=0.3,0.1

Type RM Length L Ch R = 1 ,75744   ,480,480,480
BEGIN DESCRIPTION:
Mapping XS e5f6276c
END DESCRIPTION:
XS GIS Cut Line= 3
      3765128.54     10604379.43      3763687.61     10604331.69
      3762924.13     10604301.33
#Sta/Elev= 30
  3484.5   337.3  3683.5  323.12  3910.2  315.11    4128  309.02  4217.8  308.69
  4323.9  313.68  4542.4  306.78  4664.1  303.91  4714.1  300.05  4974.3  304.47
  4984.3  295.85  5001.3   293.8    5004   293.3  5007.3   293.8  5014.3  296.37
  5024.3   305.3  5044.3  302.82  5088.9   302.8  5134.4  302.13  5154.4  307.16
  5185.5  308.21  5194.4  309.87  5234.5  307.05  5264.5  316.18  5294.5  319.39
  5341.9  330.72  5404.6  341.77  5559.5  353.96  5656.8   357.9  5690.3  358.17
#Mann= 11 ,-1 , 0
  3484.5     .16       0  3910.2     .12       0    4128     .16       0
  4542.4     .12       0  5001.3     .07       0  5007.3     .12       0
  5088.9     .05       0  5185.5     .12       0  5341.9     .16       0
  5559.5     .12       0  5656.8     .16       0
Bank Sta=4974.3,5024.3
XS Rating Curve= 0 ,0
Exp/Cntr=0.3,0.1

Type RM Length L Ch R = 1 ,75264   ,424,424,424
BEGIN DESCRIPTION:
Mapping XS b47e7ecb
END DESCRIPTION:
XS GIS Cut Line= 3
      3765171.98      10604171.1      3763965.39     10603971.45
      3763058.26     10603945.41
#Sta/Elev= 30
    3658  348.95  3741.5  331.44  3756.1   331.3    3782  324.93  3803.7  323.29
  3822.6     320  3903.3  316.82  4045.6  308.13  4226.8  303.58  4420.6  300.59
  4572.6   304.3  4724.7  298.59  4966.8  302.39  4993.8  294.69  4996.6  294.19
  4999.8  294.69  5006.8  294.75  5016.8  301.61  5026.8  302.82  5256.9  300.42
  5286.9  300.74  5296.9   305.6    5317  308.09  5346.4  304.69    5387  312.59
  5449.8  318.95  5637.1  350.35  5647.1   349.1  5750.1  357.94  5788.5  358.27
#Mann= 8 ,-1 , 0
    3658     .16       0  3803.7     .12       0  3903.3     .07       0
  4226.8     .12       0  4993.8     .07       0  4999.8     .12       0
  5346.4     .16       0  5750.1     .05       0
Bank Sta=4966.8,5026.8
XS Rating Curve= 0 ,0
Exp/Cntr=0.3,0.1

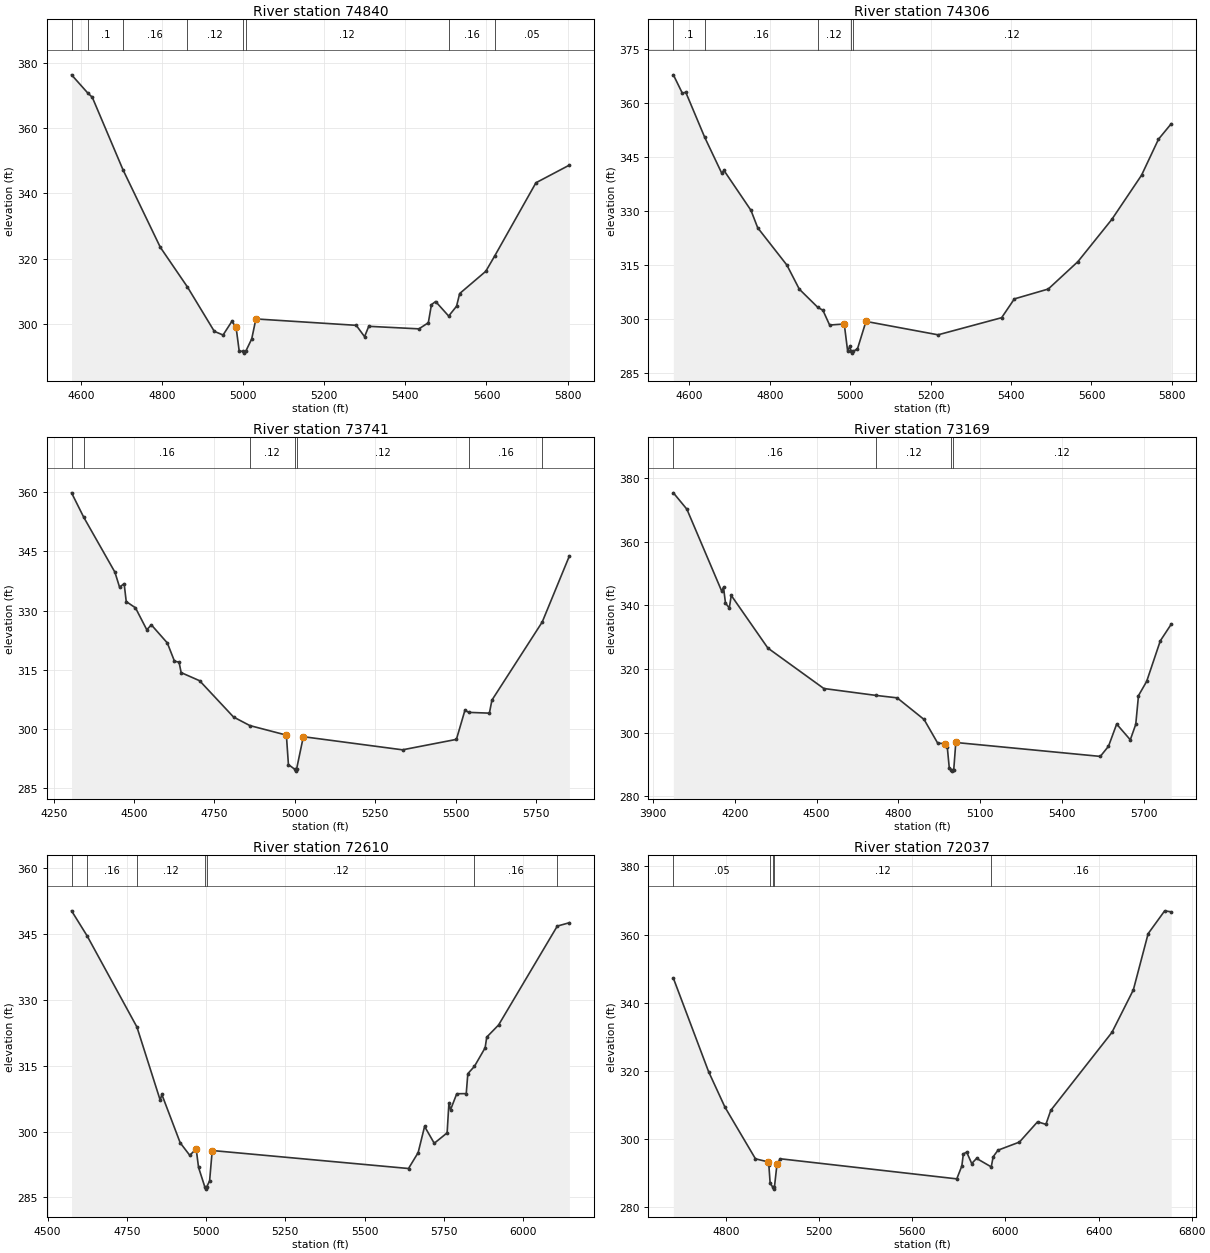
Type RM Length L Ch R = 1 ,74840   ,534,534,534
BEGIN DESCRIPTION:
MANSON CREEK 102.0
END DESCRIPTION:
XS GIS Cut Line= 3
      3764399.57     10603410.21      3764049.61     10603610.19
       3763249.6     10603410.19
#Sta/Elev= 30
  4576.8   376.3  4616.6  370.75  4627.9  369.42  4703.6  347.21  4795.6  323.46
  4862.7  311.25  4928.8  297.68  4950.4  296.55    4972  300.71  4982.4  299.03
  4990.2  291.66  5000.1   291.5  5002.8     291  5006.1   291.5  5021.1  295.36
  5031.4  301.48  5278.8  299.52  5299.4  296.04  5309.7  299.22  5433.4  298.44
  5456.6  300.31  5464.3  305.86  5474.6  306.82  5506.8  302.36  5526.2  305.37
  5533.9  309.26  5598.3  316.08  5620.8  320.89    5722  343.22  5804.5  348.63
#Mann= 8 ,-1 , 0
  4576.8     .16       0  4616.6      .1       0  4703.6     .16       0
  4862.7     .12       0  5000.1     .07       0  5006.1     .12       0
  5506.8     .16       0  5620.8     .05       0
Bank Sta=4982.4,5031.4
XS Rating Curve= 0 ,0
Exp/Cntr=0.3,0.1

Type RM Length L Ch R = 1 ,74306   ,565,565,565
BEGIN DESCRIPTION:
MANSON CREEK 101.0
END DESCRIPTION:
XS GIS Cut Line= 3
      3764349.63      10603310.2      3763949.61     10603110.19
      3763199.62     10602860.19
#Sta/Elev= 30
  4560.5  367.75  4582.9  362.64  4591.3  362.93  4638.4  350.43  4680.7  340.48
  4686.3  341.23  4753.4  330.17  4770.2  325.32  4842.8  314.97  4873.6   308.3
  4919.7  303.24  4932.3  302.45    4949  298.34  4985.4  298.63  4993.8  291.13
  4999.4  292.51  5001.9  291.05  5004.7  290.55  5007.9  291.05  5018.3  291.75
  5039.4  299.35  5218.6  295.63  5376.7  300.38  5408.3  305.59  5492.6  308.33
  5566.4  315.94  5650.7  327.65  5724.5  339.89  5766.7  349.89  5798.3  354.17
#Mann= 5 ,-1 , 0
  4560.5      .1       0  4638.4     .16       0  4919.7     .12       0
  5001.9     .07       0  5007.9     .12       0
Bank Sta=4985.4,5039.4
XS Rating Curve= 0 ,0
Exp/Cntr=0.3,0.1

Type RM Length L Ch R = 1 ,73741   ,572,572,572
BEGIN DESCRIPTION:
MANSON CREEK 100.0
END DESCRIPTION:
XS GIS Cut Line= 3
       3764499.6     10603110.17      3764049.61     10602560.19
      3763249.58      10602810.2
#Sta/Elev= 30
  4305.5  359.86  4343.3  353.68  4440.4  339.74  4454.8  335.95  4469.1  336.83
  4475.6  332.29  4504.3  330.71  4539.5  325.15  4553.8  326.38  4603.4   321.8
  4625.6  317.19    4640  316.92  4646.4  314.28  4703.9  312.22  4809.4  303.02
  4860.2  300.85  4973.8  298.43  4980.2  290.96  4999.5   289.8  5002.2   289.3
  5005.5   289.8  5026.6  298.03  5335.1   294.7  5502.8  297.35  5529.5  304.78
  5540.7   304.2  5605.4     304  5613.3   307.3  5769.8  327.11  5854.3  343.86
#Mann= 7 ,-1 , 0
  4305.5     .05       0  4343.3     .16       0  4860.2     .12       0
  4999.5     .07       0  5005.5     .12       0  5540.7     .16       0
  5769.8     .12       0
Bank Sta=4973.8,5026.6
XS Rating Curve= 0 ,0
Exp/Cntr=0.3,0.1

Type RM Length L Ch R = 1 ,73169   ,559,559,559
BEGIN DESCRIPTION:
MANSON CREEK 99.0
END DESCRIPTION:
XS GIS Cut Line= 3
       3764899.6     10602710.18      3764149.61     10602010.19
      3763349.61     10602010.19
#Sta/Elev= 30
  3974.9  375.39  4024.5  370.24    4152   344.5  4158.8  345.66  4166.1  340.68
  4180.1  339.16  4187.2  343.12  4321.5  326.56  4526.7  313.84  4718.7  311.66
  4795.6   310.9  4894.5  304.09  4944.4  296.65  4972.7  296.47  4979.5  295.44
  4986.9  288.79  4994.4  288.35  4997.1  287.85  5000.4  288.35  5003.3  288.35
  5010.8  296.86  5540.8  292.48  5570.8  295.67  5600.8  302.65  5650.8   297.7
  5670.8  302.57  5680.8   311.6  5710.8  316.08  5760.8  328.83  5800.8  334.06
#Mann= 4 ,-1 , 0
  3974.9     .16       0  4718.7     .12       0  4994.4     .07       0
  5000.4     .12       0
Bank Sta=4972.7,5010.8
XS Rating Curve= 0 ,0
Exp/Cntr=0.3,0.1

Type RM Length L Ch R = 1 ,72610   ,573,573,573
BEGIN DESCRIPTION:
MANSON CREEK 98.0
END DESCRIPTION:
XS GIS Cut Line= 3
      3764649.64     10601410.19      3764249.61     10601460.19
      3763099.61     10601660.19
#Sta/Elev= 30
  4575.8  350.33  4624.9  344.62    4782  323.85  4855.5  307.15  4860.5   308.5
  4918.5  297.46  4948.7   294.6  4968.9  296.07  4976.4  291.85  4996.2   287.4
    4999   286.9  5002.2   287.4  5011.3  288.81  5019.5   295.7  5638.7   291.6
  5669.1  295.22  5689.4  301.19  5719.9  297.35  5760.5  299.72  5766.2  306.58
  5771.3     305  5790.9  308.64  5820.8  308.67  5825.8  313.21  5846.7  314.89
  5880.4  319.11  5885.5  321.55  5922.9  324.32    6108  346.85  6146.2  347.62
#Mann= 7 ,-1 , 0
  4575.8     .05       0  4624.9     .16       0    4782     .12       0
  4996.2     .07       0  5002.2     .12       0  5846.7     .16       0
    6108     .05       0
Bank Sta=4968.9,5019.5
XS Rating Curve= 0 ,0
Exp/Cntr=0.3,0.1

Type RM Length L Ch R = 1 ,72037   ,445,445,445
BEGIN DESCRIPTION:
MANSON CREEK 97.0
END DESCRIPTION:
XS GIS Cut Line= 3
      3764649.63     10600960.19      3764249.61     10600910.19
       3763099.6     10599610.18
#Sta/Elev= 30
  4573.3  347.21  4724.5  319.82    4795  309.37    4926  294.23  4979.8  293.34
  4983.5  292.46  4989.1  287.04  5001.4  285.84  5004.2  285.34  5007.4  285.84
  5018.7   292.8  5032.9  294.24  5790.9  288.35  5812.5   292.1  5819.2  295.67
  5833.4   296.2  5855.1  292.84    5876  294.35    5939  291.86  5947.2  294.83
    5968  296.76  6060.1  299.14    6138  305.09  6173.8  304.34  6194.7  308.44
  6457.4   331.3  6549.4  343.76    6613  360.26  6684.1  366.96  6712.1  366.66
#Mann= 5 ,-1 , 0
  4573.3     .05       0  4989.1     .12       0  5001.4     .07       0
  5007.4     .12       0    5939     .16       0
Bank Sta=4979.8,5018.7
XS Rating Curve= 0 ,0
Exp/Cntr=0.3,0.1