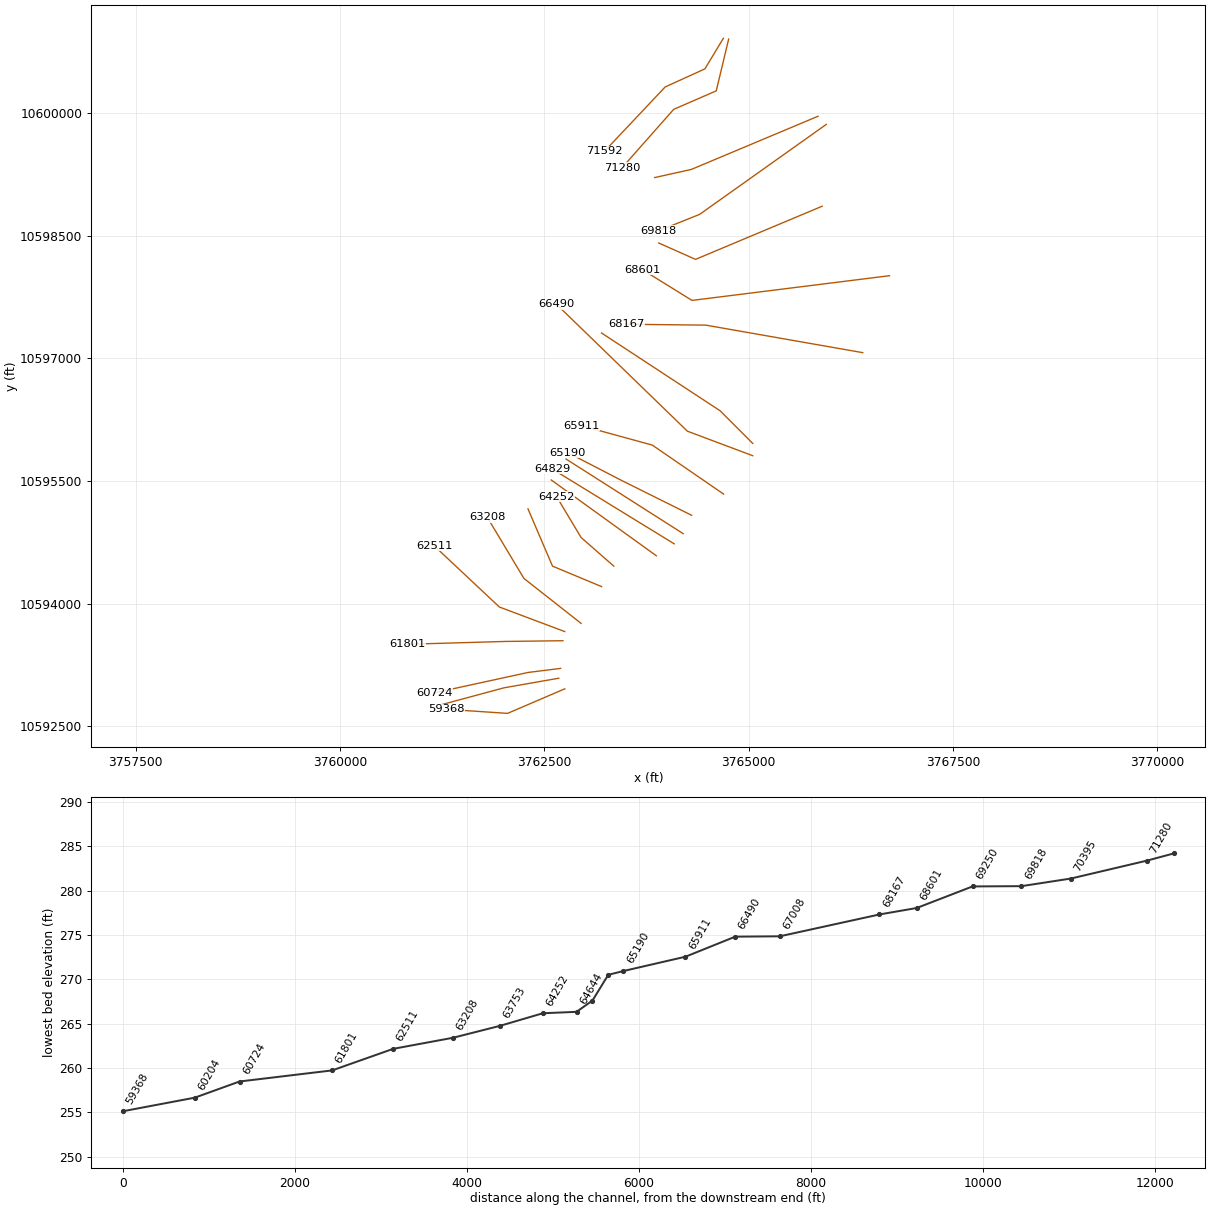
HEC-RAS study MANSON CREEK.prj: MANSON CREEK Base Level Engineering

--- MANSON CREEK.g01 (geometry) --- (continued)

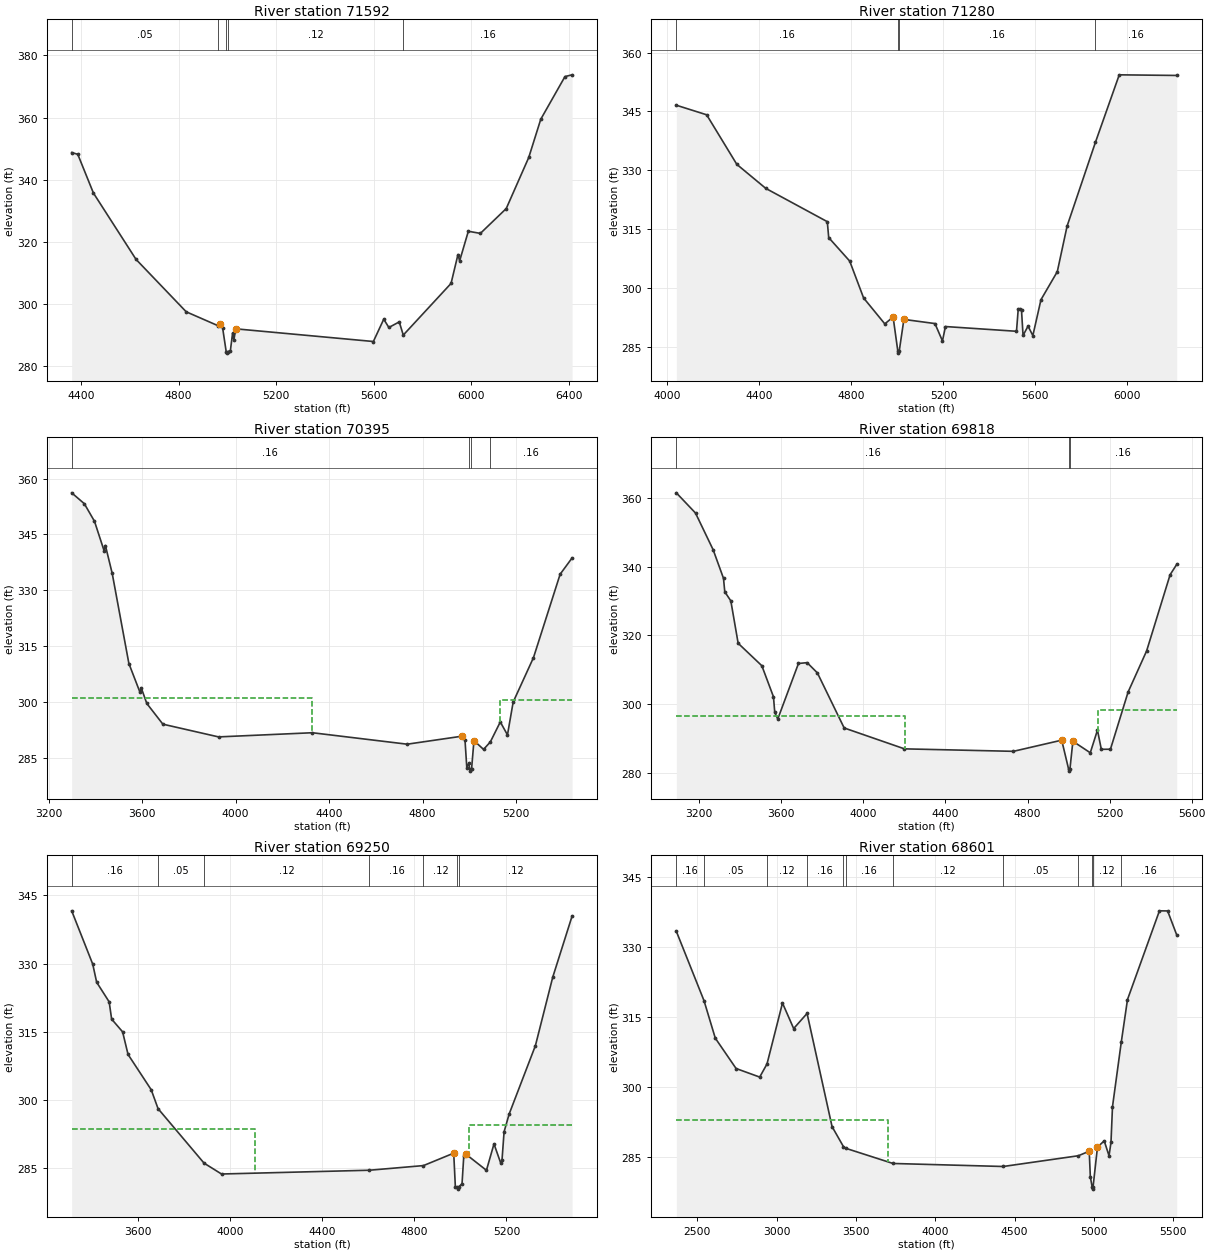
Type RM Length L Ch R = 1 ,71592   ,312,312,312
BEGIN DESCRIPTION:
MANSON CREEK 96.0
END DESCRIPTION:
XS GIS Cut Line= 4
      3764690.13     10600912.35      3764464.45     10600539.12
      3763978.34     10600317.77      3763236.17      10599532.2
#Sta/Elev= 30
  4361.5  348.74  4386.5  348.16  4450.6   335.7  4625.2  314.36  4830.9  297.49
  4960.3  293.05  4967.8  293.46  4980.2  292.28  4994.7  284.69  4997.5  284.19
  5000.7  284.69  5011.7  284.83  5020.8  290.53  5026.3   288.4  5033.7  292.01
    5598  287.93  5640.5   295.1  5661.5  292.44    5704  294.24  5720.6     290
  5916.4  306.62  5944.7  315.91  5951.6  313.88  5987.2   323.4  6036.6  322.72
  6142.6  330.71  6234.8  347.14  6284.1  359.45  6383.3  373.18  6412.5  373.74
#Mann= 5 ,-1 , 0
  4361.5     .05       0  4960.3     .12       0  4994.7     .07       0
  5000.7     .12       0  5720.6     .16       0
Bank Sta=4967.8,5033.7
XS Rating Curve= 0 ,0
Exp/Cntr=0.3,0.1

Type RM Length L Ch R = 1 ,71280   ,885,885,885
BEGIN DESCRIPTION:
MANSON CREEK 95.0
END DESCRIPTION:
XS GIS Cut Line= 4
      3764755.25     10600903.72      3764603.34     10600270.03
      3764082.51     10600044.33      3763448.85     10599328.21
#Sta/Elev= 30
  4038.8   346.6  4170.6  344.16  4301.8  331.52  4427.8  325.39  4695.2   316.9
  4701.3  312.84  4792.6  306.85    4853  297.45  4945.2  290.84  4981.3  292.59
  5001.8  283.88  5004.5  283.38  5007.8  283.88  5028.2  291.98  5163.2  290.92
  5195.8  286.49  5208.9  290.16  5517.7  288.95  5525.3  294.69  5531.9  294.66
  5539.5   294.3  5546.2  287.89  5567.9  290.27  5588.8  287.85  5624.1  297.01
  5695.1  304.16  5737.7  315.78  5860.7  337.12  5964.4  354.35  6214.3  354.19
#Mann= 4 ,-1 , 0
  4038.8     .16       0  5001.8     .07       0  5007.8     .16       0
  5860.7     .16       0
Bank Sta=4981.3,5028.2
XS Rating Curve= 0 ,0
Exp/Cntr=0.3,0.1

Type RM Length L Ch R = 1 ,70395   ,577,577,577
BEGIN DESCRIPTION:
MANSON CREEK 94.0
END DESCRIPTION:
XS GIS Cut Line= 3
      3765849.57     10599960.17      3764299.61     10599310.19
      3763849.62     10599210.19
#Sta/Elev= 30
  3298.3  356.17  3352.5  353.24  3395.9  348.52  3437.1  340.58  3442.6  342.01
  3471.8  334.49  3543.1  310.29  3590.6  302.55    3596  303.74  3619.8  299.55
  3688.6  293.98  3926.8  290.56  4328.4  291.68  4734.2   288.6  4969.9  290.76
  4981.6  289.75  4989.3  282.33  4998.2   283.5  5003.1  281.36  5006.4  281.86
  5009.8  281.96    5020  289.57    5061   287.2    5090   289.2  5132.7  294.58
  5163.4   291.1  5187.8  299.93  5274.8  311.88  5388.8  334.29    5440  338.67
#Mann= 4 ,-1 , 0
  3298.3     .16       0  4998.2     .07       0  5006.4     .16       0
    5090     .16       0
#XS Ineff= 2 , 0
         4328.12  301.03  5132.1          300.53
Permanent Ineff=
       F       F
Bank Sta=4969.9,5020
XS Rating Curve= 0 ,0
Exp/Cntr=0.3,0.1

Type RM Length L Ch R = 1 ,69818   ,568,568,568
BEGIN DESCRIPTION:
MANSON CREEK 93.0
END DESCRIPTION:
XS GIS Cut Line= 3
       3765949.6     10599860.18      3764399.61     10598760.19
      3763899.57     10598560.17
#Sta/Elev= 30
  3088.1  361.47  3181.6  355.59  3267.7  344.89  3318.1  336.59  3324.3  332.67
  3353.8  330.03  3389.5   317.7    3505  311.16  3561.7  302.12  3567.9  297.59
  3582.6  295.67  3683.5  311.82  3725.7  312.06  3775.8  309.07  3906.2  293.06
  4200.2  286.98  4731.2  286.26  4966.6  289.51  5000.6     281  5003.3   280.5
  5006.6     281  5021.1  289.19  5105.9  285.84  5140.9  292.43  5159.7  286.85
  5204.2  286.87  5290.3  303.52  5380.5  315.47    5495  337.64  5527.3  340.65
#Mann= 3 ,-1 , 0
  3088.1     .16       0  5000.6     .07       0  5006.6     .16       0
#XS Ineff= 2 , 0
         4203.41   296.4 5142.61          298.27
Permanent Ineff=
       F       F
Bank Sta=4966.6,5021.1
XS Rating Curve= 0 ,0
Exp/Cntr=0.3,0.1

Type RM Length L Ch R = 1 ,69250   ,649,649,649
BEGIN DESCRIPTION:
MANSON CREEK 92.0
END DESCRIPTION:
XS GIS Cut Line= 3
      3765899.64      10598860.2      3764349.61     10598210.19
      3763899.65     10598410.17
#Sta/Elev= 30
  3311.7  341.58  3403.1  329.87  3420.2  325.89  3474.4   321.6  3485.2   317.8
  3532.8  315.01  3556.5  310.04  3657.1  302.29  3686.8  298.14  3886.5  286.18
  3962.4  283.79    4605  284.62  4839.5  285.64  4970.8  288.37  4977.9  280.99
  4986.8  280.97  4989.5  280.47  4992.8  280.97  5006.9  281.65  5014.4  287.67
  5024.6  288.11  5112.9   284.6  5145.7   290.4  5175.1  286.17  5180.6  286.89
  5189.5  293.05  5211.4  296.94  5325.6  311.98  5400.8     327  5484.9  340.43
#Mann= 7 ,-1 , 0
  3311.7     .16       0  3686.8     .05       0  3886.5     .12       0
    4605     .16       0  4839.5     .12       0  4986.8     .07       0
  4992.8     .12       0
#XS Ineff= 2 , 0
         4106.53  293.67 5038.35          294.54
Permanent Ineff=
       F       F
Bank Sta=4970.8,5024.6
XS Rating Curve= 0 ,0
Exp/Cntr=0.3,0.1

Type RM Length L Ch R = 1 ,68601   ,434,434,434
BEGIN DESCRIPTION:
MANSON CREEK 91.0
END DESCRIPTION:
XS GIS Cut Line= 3
      3766723.25     10598010.66      3764306.59     10597708.58
      3763696.99     10598086.11
#Sta/Elev= 30
  2368.4  333.41  2542.8  318.51  2613.9  310.46  2744.9  303.94  2893.7   302.1
  2939.7  304.92  3037.2     318  3107.7  312.52  3192.1  315.77  3349.6  291.46
  3421.1  287.18  3435.7  286.81  3733.3  283.55  4427.7   282.9  4901.2  285.21
  4969.6  286.18  4976.7  280.67  4987.9  278.54  4990.6  278.04  4993.9  278.54
  5021.6  287.07  5064.1   288.4  5094.4   285.2  5106.7  288.07  5116.2  295.74
  5171.5  309.59  5210.7  318.75    5412   337.8  5463.5  337.78  5520.9  332.62
#Mann= 12 ,-1 , 0
  2368.4     .16       0  2542.8     .05       0  2939.7     .12       0
  3192.1     .16       0  3421.1     .05       0  3435.7     .16       0
  3733.3     .12       0  4427.7     .05       0  4901.2     .12       0
  4987.9     .07       0  4993.9     .12       0  5171.5     .16       0
#XS Ineff= 2 , 0
         3702.27  292.95
Permanent Ineff=
       F       F
Bank Sta=4969.6,5021.6
XS Rating Curve= 0 ,0
Exp/Cntr=0.3,0.1

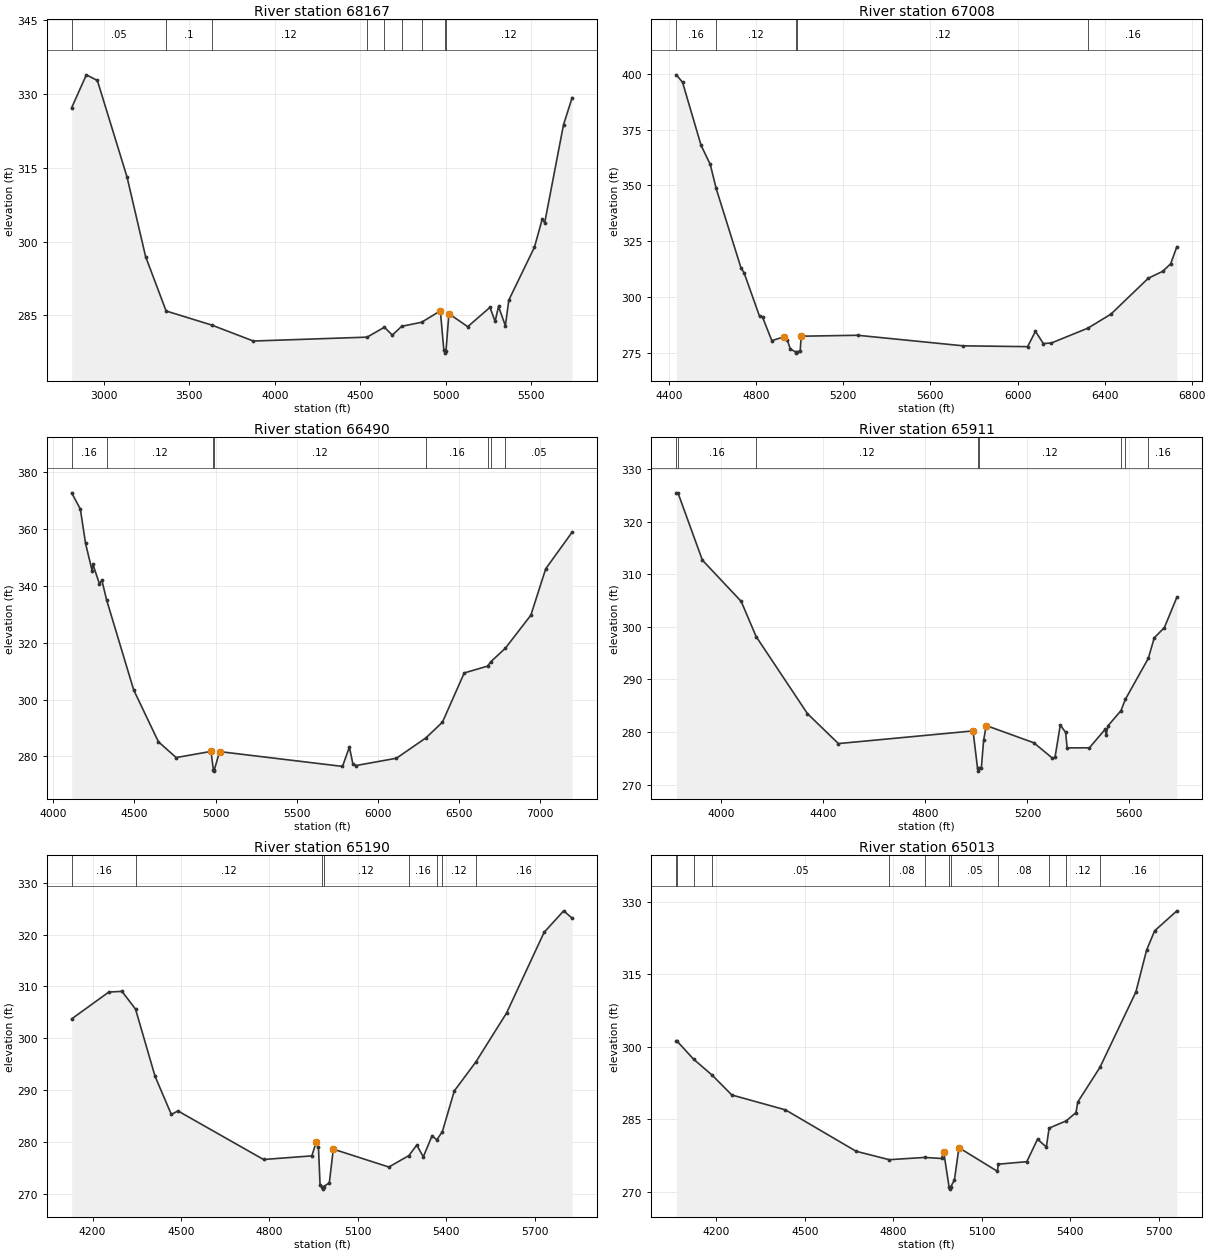
Type RM Length L Ch R = 1 ,68167   ,1159,1159,1159
BEGIN DESCRIPTION:
MANSON CREEK 90.0
END DESCRIPTION:
XS GIS Cut Line= 3
       3766396.2      10597069.9      3764475.59     10597406.27
      3763498.99     10597417.13
#Sta/Elev= 30
  2812.3  327.22    2898   333.9  2962.5  332.75  3135.8  313.14  3244.5  296.94
  3364.4  285.88  3629.9  283.03  3874.8  279.77  4539.7  280.56  4640.8  282.58
    4687  280.97  4741.9  282.76  4858.4  283.59  4968.1  285.91  4988.1  278.04
  4995.1  277.81  4997.9  277.31  5001.1  277.81  5018.1  285.33  5128.1  282.69
  5258.2  286.62  5288.2  283.76  5308.2   286.8  5348.2  282.87  5368.2  288.09
  5518.2  298.85  5563.8  304.56  5578.2  303.84  5688.2  323.76  5738.8  329.27
#Mann= 9 ,-1 , 0
  2812.3     .05       0  3364.4      .1       0  3629.9     .12       0
  4539.7     .05       0  4640.8     .12       0  4741.9     .16       0
  4858.4     .12       0  4995.1     .07       0  5001.1     .12       0
Bank Sta=4968.1,5018.1
XS Rating Curve= 0 ,0
Exp/Cntr=0.3,0.1

Type RM Length L Ch R = 1 ,67008   ,518,518,518
BEGIN DESCRIPTION:
MANSON CREEK 89.0
END DESCRIPTION:
XS GIS Cut Line= 3
      3765049.62     10595960.17      3764649.61     10596360.19
      3763199.61     10597310.19
#Sta/Elev= 30
    4433   399.5  4461.3  396.13  4546.2  367.95  4588.6  359.37  4615.5  348.65
    4730  312.95  4744.1  310.81  4814.9  291.35    4829  290.86  4871.4  280.44
    4928  282.19  4942.1  280.84  4956.3   276.7  4981.6  275.35  4984.3  274.85
  4987.6  275.35  5001.7  275.83  5006.3  282.43  5265.5  282.85  5750.9  278.12
  6046.4  277.75  6082.5  284.62  6118.7  279.15  6154.9  279.36  6323.7  286.05
  6429.2  292.32    6601  308.41  6667.4   311.5  6703.6  314.88  6732.2  322.54
#Mann= 5 ,-1 , 0
    4433     .16       0  4615.5     .12       0  4981.6     .07       0
  4987.6     .12       0  6323.7     .16       0
Bank Sta=4928,5006.3
XS Rating Curve= 0 ,0
Exp/Cntr=0.3,0.1

Type RM Length L Ch R = 1 ,66490   ,579,579,579
BEGIN DESCRIPTION:
MANSON CREEK 88.0
END DESCRIPTION:
XS GIS Cut Line= 3
      3765049.62     10595810.18      3764249.61     10596110.19
      3762649.59      10597660.2
#Sta/Elev= 30
  4113.6  372.73    4167     367  4199.1  354.91  4239.1  345.39  4244.4  347.55
  4284.5   340.7  4299.6  341.97  4328.3  335.11  4495.4  303.38  4647.6  285.14
  4757.1  279.58  4971.5  281.75  4986.2  275.31    4989  274.81  4992.2  275.31
  5024.5  281.68  5781.3  276.47  5823.7  283.28    5845  277.44  5866.2  276.79
  6113.6  279.35  6294.5  286.49  6396.6  292.01  6530.9  309.35  6674.7  311.76
    6694  313.26    6784  318.04  6941.1  329.67    7033  346.02  7195.7  358.91
#Mann= 8 ,-1 , 0
  4113.6     .16       0  4328.3     .12       0  4986.2     .07       0
  4992.2     .12       0  6294.5     .16       0  6674.7     .05       0
    6694     .16       0    6784     .05       0
Bank Sta=4971.5,5024.5
XS Rating Curve= 0 ,0
Exp/Cntr=0.3,0.1

Type RM Length L Ch R = 1 ,65911   ,721,721,721
BEGIN DESCRIPTION:
MANSON CREEK 87.0
END DESCRIPTION:
XS GIS Cut Line= 3
      3764693.36     10595340.86        3763821.      10595939.8
      3762948.64      10596178.5
#Sta/Elev= 30
  3823.5  325.49  3830.4  325.38  3925.3  312.69  4077.6  304.84  4136.1  298.15
  4337.5  283.48  4458.8  277.79  4986.8   280.2  5004.5  273.05  5007.3  272.55
  5010.5  273.05  5019.4  273.22  5028.3  278.44  5038.6  281.22  5225.2  277.94
  5297.8  275.03  5308.2  275.18  5328.9  281.33  5349.7  279.92  5355.8  276.97
    5443  276.99  5504.2  280.47  5509.3  279.46  5515.5  281.15  5566.9  284.06
  5584.5  286.25  5674.1  294.01  5697.4  297.91  5737.1  299.86  5786.1  305.64
#Mann= 8 ,-1 , 0
  3823.5     .12       0  3830.4     .16       0  4136.1     .12       0
  5004.5     .07       0  5010.5     .12       0  5566.9     .16       0
  5584.5     .12       0  5674.1     .16       0
Bank Sta=4986.8,5038.6
XS Rating Curve= 0 ,0
Exp/Cntr=0.3,0.1

Type RM Length L Ch R = 1 ,65190   ,177,177,177
BEGIN DESCRIPTION:
Mapping XS 233b426f
END DESCRIPTION:
XS GIS Cut Line= 3
       3764302.4     10595081.63      3763443.04     10595508.71
      3762786.76     10595847.27
#Sta/Elev= 30
  4129.1  303.75  4255.1  308.92  4299.8  309.05  4345.7  305.63  4411.9  292.69
  4467.2  285.33  4489.6  286.01  4779.9  276.65  4943.9  277.35  4958.6  279.98
  4966.3  279.13  4971.9  271.65  4977.9  271.44  4980.6  270.94  4983.9  271.44
  5003.2  272.14  5016.7  278.65  5205.1   275.2  5273.1   277.4    5300  279.43
  5322.1  277.16  5351.4  281.17  5368.3  280.47  5386.7  282.01  5427.3  289.87
  5500.2  295.43  5604.6  304.88  5731.9  320.42  5798.4  324.57  5827.2  323.14
#Mann= 8 ,-1 , 0
  4129.1     .16       0  4345.7     .12       0  4977.9     .07       0
  4983.9     .12       0  5273.1     .16       0  5368.3     .05       0
  5386.7     .12       0  5500.2     .16       0
Bank Sta=4958.6,5016.7
XS Rating Curve= 0 ,0
Exp/Cntr=0.3,0.1

Type RM Length L Ch R = 1 ,65013   ,184,184,184
BEGIN DESCRIPTION:
MANSON CREEK 86.0
END DESCRIPTION:
XS GIS Cut Line= 2
      3764198.28     10594857.64        3762766.      10595769.1
#Sta/Elev= 30
  4064.2  301.27  4065.1  301.27  4122.5  297.44  4185.3  294.14  4252.3  290.02
  4434.1  286.94  4673.7  278.36  4786.1  276.61  4906.3  277.08  4963.5  276.86
  4970.9  278.25    4989  271.01  4991.8  270.51    4995  271.01  5007.3  272.41
  5022.5   279.1  5152.9  274.21  5156.2  275.68  5252.8   276.2  5289.2  280.86
  5319.1  279.24  5328.5  283.16    5387  284.67  5419.6  286.37  5425.7  288.56
  5500.7  295.73  5622.8  311.37  5659.2  320.06  5686.5  324.05  5761.9  328.19
#Mann= 12 ,-1 , 0
  4064.2     .16       0  4065.1     .05       0  4122.5     .16       0
  4185.3     .05       0  4786.1     .08       0  4906.3     .05       0
    4989     .04       0    4995     .05       0  5156.2     .08       0
  5328.5     .05       0    5387     .12       0  5500.7     .16       0
Bank Sta=4970.9,5022.5
XS Rating Curve= 0 ,0
Exp/Cntr=0.3,0.1

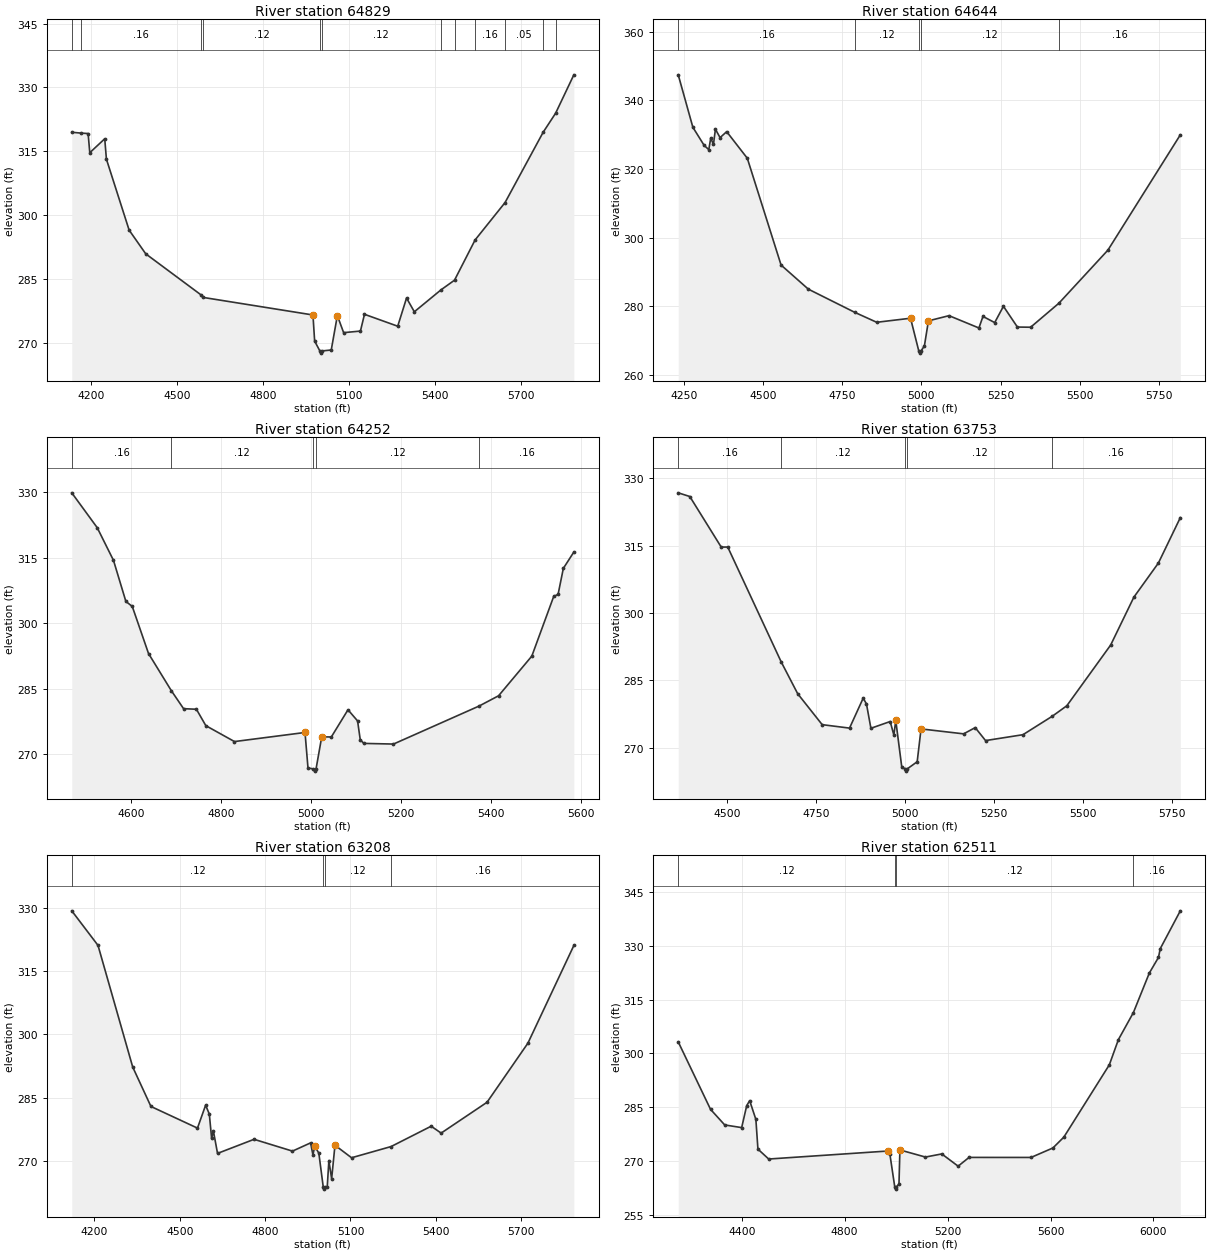
Type RM Length L Ch R = 1 ,64829   ,185,185,185
BEGIN DESCRIPTION:
MANSON CREEK 85.0
END DESCRIPTION:
XS GIS Cut Line= 2
      3764088.88     10594732.66      3762594.33     10595649.18
#Sta/Elev= 30
  4131.8  319.48  4165.1  319.28  4188.9  319.18  4194.7  314.68  4246.9  317.95
  4252.8  313.16  4332.1   296.5  4390.1  290.93  4582.9   281.3  4591.7  280.68
    4974  276.57  4979.9  270.44  4998.2  268.11  5000.9  267.61  5004.2  268.11
  5037.9  268.35  5059.2  276.42  5081.1  272.42  5139.8  272.79  5153.9  276.73
    5270  273.93  5300.8  280.55    5328  277.32  5421.3  282.48  5468.3  284.74
  5540.2  294.19  5644.8  302.97  5777.8  319.48  5821.4  323.96    5885  332.97
#Mann= 12 ,-1 , 0
  4131.8     .05       0  4165.1     .16       0  4582.9     .05       0
  4591.7     .12       0  4998.2     .07       0  5004.2     .12       0
  5421.3     .16       0  5468.3     .05       0  5540.2     .16       0
  5644.8     .05       0  5777.8     .16       0  5821.4     .05       0
Bank Sta=4974,5059.2
XS Rating Curve= 0 ,0
Exp/Cntr=0.3,0.1

Type RM Length L Ch R = 1 ,64644   ,392,392,392
BEGIN DESCRIPTION:
Mapping XS a8bbdab8
END DESCRIPTION:
XS GIS Cut Line= 2
      3763870.14     10594586.82      3762584.18     10595513.55
#Sta/Elev= 30
  4232.2  347.46  4278.4  332.17    4314  326.89  4328.7  325.65  4334.8  329.02
  4343.4  327.19  4349.6  331.61  4364.3  329.15  4385.1   330.9  4450.2  323.15
  4556.9  292.01  4642.9  284.99  4788.8  278.26  4858.8  275.33  4965.6  276.51
    4992  266.84  4994.8  266.34    4998  266.84  5009.4  268.47  5022.1  275.75
  5087.1  277.26  5181.5  273.67  5194.3  277.04  5231.3  275.24  5258.9  279.99
    5303  273.94  5344.8  273.89    5434  280.89  5588.7  296.36  5817.3  329.96
#Mann= 5 ,-1 , 0
  4232.2     .16       0  4788.8     .12       0    4992     .07       0
    4998     .12       0    5434     .16       0
Bank Sta=4965.6,5022.1
XS Rating Curve= 0 ,0
Exp/Cntr=0.3,0.1

Type RM Length L Ch R = 1 ,64252   ,499,499,499
BEGIN DESCRIPTION:
MANSON CREEK 84.0
END DESCRIPTION:
XS GIS Cut Line= 3
      3763349.63     10594460.17      3762949.61     10594810.19
      3762649.62     10595310.16
#Sta/Elev= 30
    4469  329.82  4525.5  321.85  4561.6  314.38  4589.1  304.99  4603.3  303.84
  4639.4  293.07    4690  284.58  4717.2  280.46  4745.7  280.33  4766.6  276.58
  4830.2  272.94  4986.8  275.02  4993.4  266.91  5005.3  266.68  5008.1  266.18
  5011.3  266.68  5023.9  274.02  5045.2  273.99  5082.2  280.21  5103.5  277.66
  5109.4  273.38  5117.2  272.52  5183.2  272.37  5373.2  281.06  5416.5  283.41
  5490.3  292.48  5538.9  306.13  5548.6  306.59  5560.3  312.55  5583.6  316.28
#Mann= 5 ,-1 , 0
    4469     .16       0    4690     .12       0  5005.3     .07       0
  5011.3     .12       0  5373.2     .16       0
Bank Sta=4986.8,5023.9
XS Rating Curve= 0 ,0
Exp/Cntr=0.3,0.1

Type RM Length L Ch R = 1 ,63753   ,545,545,545
BEGIN DESCRIPTION:
MANSON CREEK 83.0
END DESCRIPTION:
XS GIS Cut Line= 3
      3763199.64     10594210.18      3762599.61     10594460.19
      3762299.61     10595160.18
#Sta/Elev= 30
  4362.1   326.8  4394.6  325.98  4482.9  314.71  4501.3  314.71  4651.7  289.09
    4698  282.01  4766.8  275.12  4843.7  274.35  4882.1  281.03  4891.3  279.74
  4903.8  274.31    4958  275.82  4968.3  272.81  4973.7  276.05  4990.5  265.72
  4999.9  265.26  5002.7  264.76  5005.9  265.26  5033.9  266.85  5044.8  274.17
  5164.4  273.07  5197.1  274.46  5226.1  271.57  5331.3  272.88  5413.6  276.99
  5454.6  279.33  5577.9  292.87  5643.2  303.55  5712.1  311.15  5773.7  321.27
#Mann= 5 ,-1 , 0
  4362.1     .16       0  4651.7     .12       0  4999.9     .07       0
  5005.9     .12       0  5413.6     .16       0
Bank Sta=4973.7,5044.8
XS Rating Curve= 0 ,0
Exp/Cntr=0.3,0.1

Type RM Length L Ch R = 1 ,63208   ,697,697,697
BEGIN DESCRIPTION:
MANSON CREEK 82.0
END DESCRIPTION:
XS GIS Cut Line= 3
       3762949.6     10593760.19      3762249.61     10594310.19
      3761799.59     10595060.22
#Sta/Elev= 30
  4120.3  329.24  4212.5  321.07  4334.5   292.3  4398.6  282.97  4562.2  277.85
  4590.8  283.27  4603.8  281.18  4611.9  275.43  4618.3  277.12  4632.7  271.87
  4761.1   275.2  4896.1  272.41  4959.9  274.36    4968  271.51  4974.4  273.59
  4988.8  271.92  5004.3  263.92  5007.1  263.42  5010.3  263.92  5018.3  263.93
  5024.1  270.17  5033.8  265.87  5045.5   273.8  5103.8  270.84  5242.8  273.49
  5383.7   278.3  5418.7  276.67    5580  283.96  5723.8  297.95  5885.2  321.04
#Mann= 4 ,-1 , 0
  4120.3     .12       0  5004.3     .07       0  5010.3     .12       0
  5242.8     .16       0
Bank Sta=4974.4,5045.5
XS Rating Curve= 0 ,0
Exp/Cntr=0.3,0.1

Type RM Length L Ch R = 1 ,62511   ,710,710,710
BEGIN DESCRIPTION:
MANSON CREEK 81.0
END DESCRIPTION:
XS GIS Cut Line= 3
      3762749.58      10593660.2      3761949.61     10593960.19
      3761149.57     10594710.22
#Sta/Elev= 30
  4153.3  303.21  4278.8  284.41  4333.9  280.06  4399.8  279.32  4419.4  285.45
  4430.9  286.83    4455   281.6    4463  273.32  4504.8  270.56  4967.6  272.79
  4975.6     272  4994.9  262.67  4997.6  262.17  5000.9  262.67  5011.1  263.65
  5014.7  273.09  5113.9  271.11  5177.4  271.98  5240.9  268.57  5283.4  271.01
  5524.2     271  5609.2  273.64  5651.7  276.66  5828.5  296.82  5863.7  303.84
  5922.1   311.4  5983.9   322.4  6019.5  326.76  6026.3  329.19  6104.3  339.74
#Mann= 4 ,-1 , 0
  4153.3     .12       0  4994.9     .07       0  5000.9     .12       0
  5922.1     .16       0
Bank Sta=4967.6,5014.7
XS Rating Curve= 0 ,0
Exp/Cntr=0.3,0.1

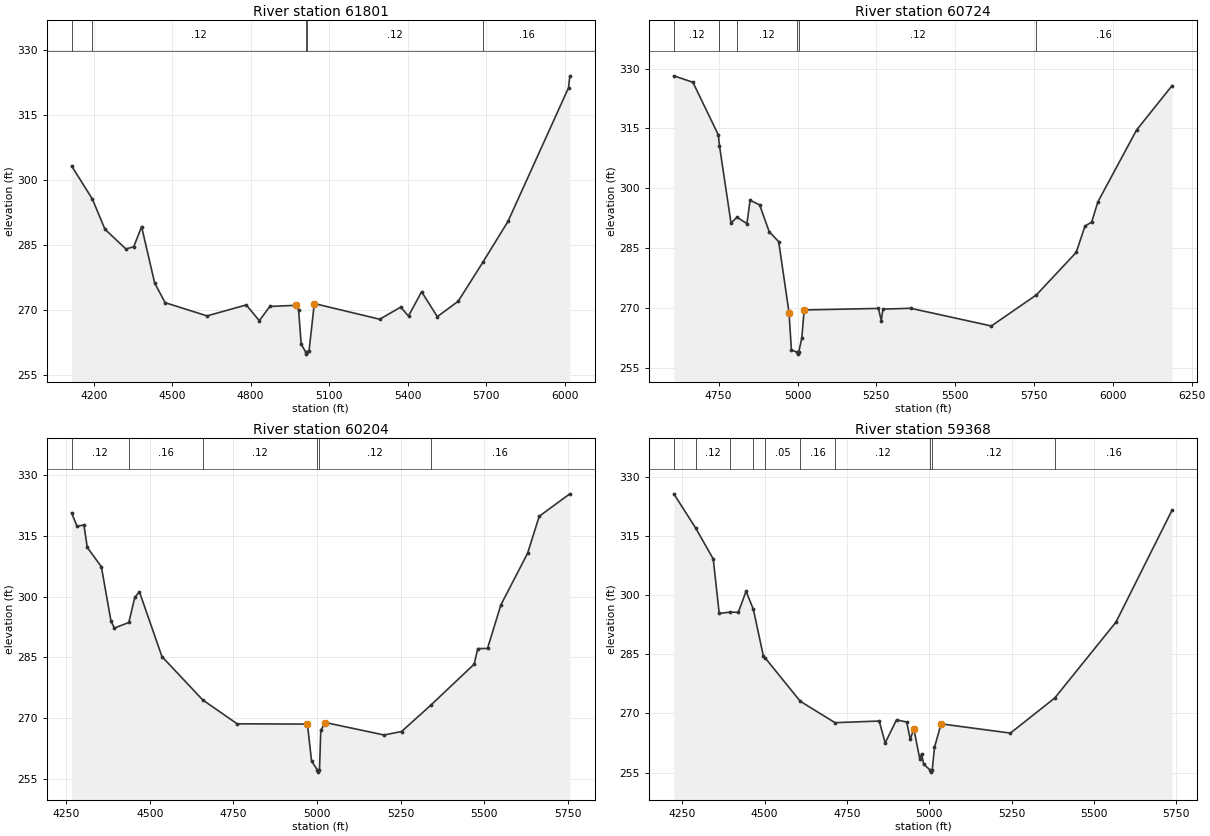
Type RM Length L Ch R = 1 ,61801   ,1077,1077,1077
BEGIN DESCRIPTION:
MANSON CREEK 80.0
END DESCRIPTION:
XS GIS Cut Line= 3
      3762727.23      10593548.3      3762024.12     10593539.62
      3760823.29     10593504.94
#Sta/Elev= 30
  4115.4   303.2  4194.7  295.58    4243  288.58    4323  284.03    4353  284.53
    4383  289.19    4433  276.16    4473  271.63  4633.1  268.57  4783.1   271.1
  4833.1  267.46  4873.1  270.75  4975.1  271.02  4983.1  269.93  4993.1  262.03
  5010.2  260.24  5012.9  259.74  5016.2  260.24  5023.2  260.54  5043.2  271.42
  5293.3   267.8  5373.3  270.59  5403.3  268.54  5453.3  274.15  5513.4  268.39
  5593.4  271.96  5689.1  281.12  5783.5  290.39  6014.9  321.25  6019.9  324.01
#Mann= 5 ,-1 , 0
  4115.4     .16       0  4194.7     .12       0  5010.2     .07       0
  5016.2     .12       0  5689.1     .16       0
Bank Sta=4975.1,5043.2
XS Rating Curve= 0 ,0
Exp/Cntr=0.3,0.1

Type RM Length L Ch R = 1 ,60724   ,520,520,520
BEGIN DESCRIPTION:
MANSON CREEK 79.0
END DESCRIPTION:
XS GIS Cut Line= 3
      3762699.58     10593210.18      3762299.61     10593160.19
      3761149.65      10592910.2
#Sta/Elev= 30
  4607.8  328.17  4668.2  326.56  4748.9  313.39  4752.6  310.62  4789.2  291.29
  4807.9  292.78  4839.6  291.17  4849.6  297.03  4879.9  295.85  4910.1  289.16
  4940.3  286.65  4973.1  268.88  4980.6  259.57  4997.8  258.99  5000.6  258.49
  5003.8  258.99  5013.4  262.42  5021.1  269.55  5256.5  269.93  5265.7  266.87
  5270.8  269.76  5358.8  269.97  5614.7  265.54  5757.2   273.3  5883.8  283.97
  5911.4  290.53  5932.9  291.58  5952.4  296.61  6075.2  314.61  6187.7  325.72
#Mann= 6 ,-1 , 0
  4607.8     .12       0  4752.6     .16       0  4807.9     .12       0
  4997.8     .07       0  5003.8     .12       0  5757.2     .16       0
Bank Sta=4973.1,5021.1
XS Rating Curve= 0 ,0
Exp/Cntr=0.3,0.1

Type RM Length L Ch R = 1 ,60204   ,836,836,836
BEGIN DESCRIPTION:
MANSON CREEK 78.0
END DESCRIPTION:
XS GIS Cut Line= 3
      3762675.87     10593089.94      3762006.64     10592972.76
      3761223.71     10592762.07
#Sta/Elev= 30
  4266.2  320.69  4282.7  317.35    4303   317.7  4313.2  312.15  4355.3  307.38
  4384.2   293.9  4394.4  292.24  4437.4  293.62  4455.3  299.82  4469.1  301.19
  4536.5   285.2  4658.1  274.52  4761.3   268.6  4971.6  268.53    4984  259.38
  5001.7  257.17  5004.4  256.67  5007.7  257.17  5011.5  266.99  5025.4  268.91
  5200.9  265.84  5253.2   266.7  5340.9  273.22  5470.3  283.33    5481  287.16
  5510.2  287.21  5550.2  297.96  5630.1  310.71  5664.8  319.83  5756.4  325.38
#Mann= 6 ,-1 , 0
  4266.2     .12       0  4437.4     .16       0  4658.1     .12       0
  5001.7     .07       0  5007.7     .12       0  5340.9     .16       0
Bank Sta=4971.6,5025.4
XS Rating Curve= 0 ,0
Exp/Cntr=0.3,0.1

Type RM Length L Ch R = 1 ,59368   ,595,595,595
BEGIN DESCRIPTION:
MANSON CREEK 77.0
END DESCRIPTION:
XS GIS Cut Line= 3
      3762749.64      10592960.2      3762049.61     10592660.19
      3761299.58     10592710.19
#Sta/Elev= 30
  4224.1  325.67  4290.3  317.01  4343.8  309.16  4361.9  295.38  4396.2  295.69
    4420  295.65  4443.5  300.98  4465.7   296.4  4496.1  284.54    4502  284.04
  4607.9  273.11  4713.7  267.67  4847.9  268.09    4866  262.54  4900.5   268.4
  4931.3  267.83  4942.2  263.48  4953.1  266.13  4971.2  258.44  4976.6  259.75
    4983  257.15  5002.8  255.64  5005.5  255.14  5008.8  255.64  5015.8  261.42
  5035.8  267.37  5246.3  265.03    5381  273.92    5567  293.16  5737.4  321.55
#Mann= 10 ,-1 , 0
  4224.1     .16       0  4290.3     .12       0  4396.2     .16       0
  4465.7     .12       0    4502     .05       0  4607.9     .16       0
  4713.7     .12       0  5002.8     .07       0  5008.8     .12       0
    5381     .16       0
Bank Sta=4953.1,5035.8
XS Rating Curve= 0 ,0
Exp/Cntr=0.3,0.1