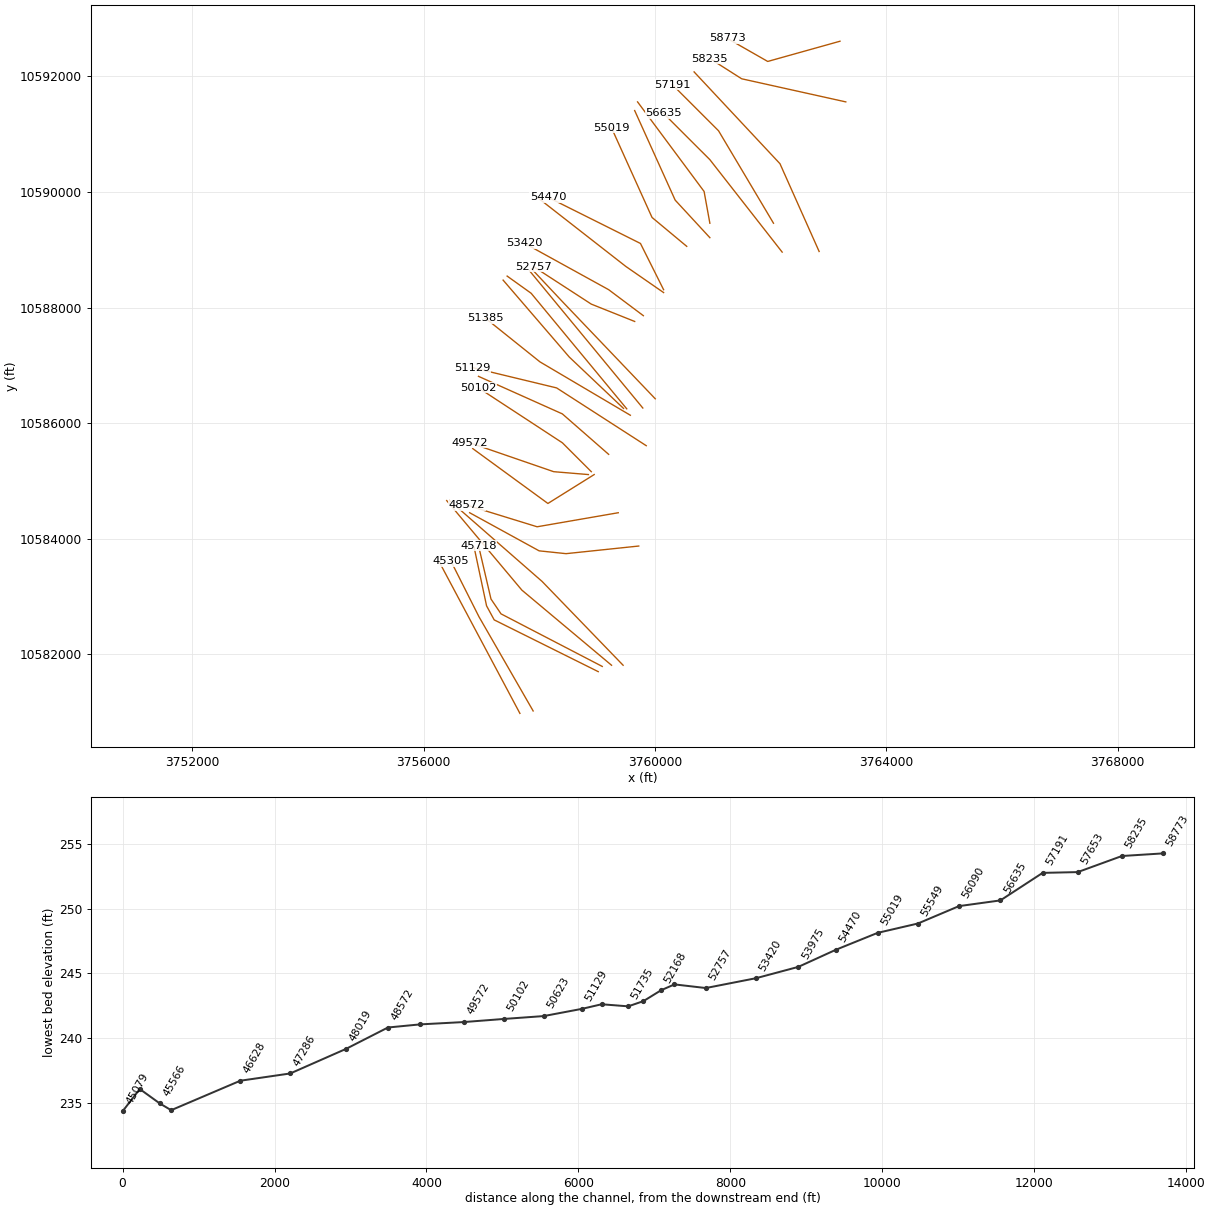
HEC-RAS study MANSON CREEK.prj: MANSON CREEK Base Level Engineering

--- MANSON CREEK.g01 (geometry) --- (continued)

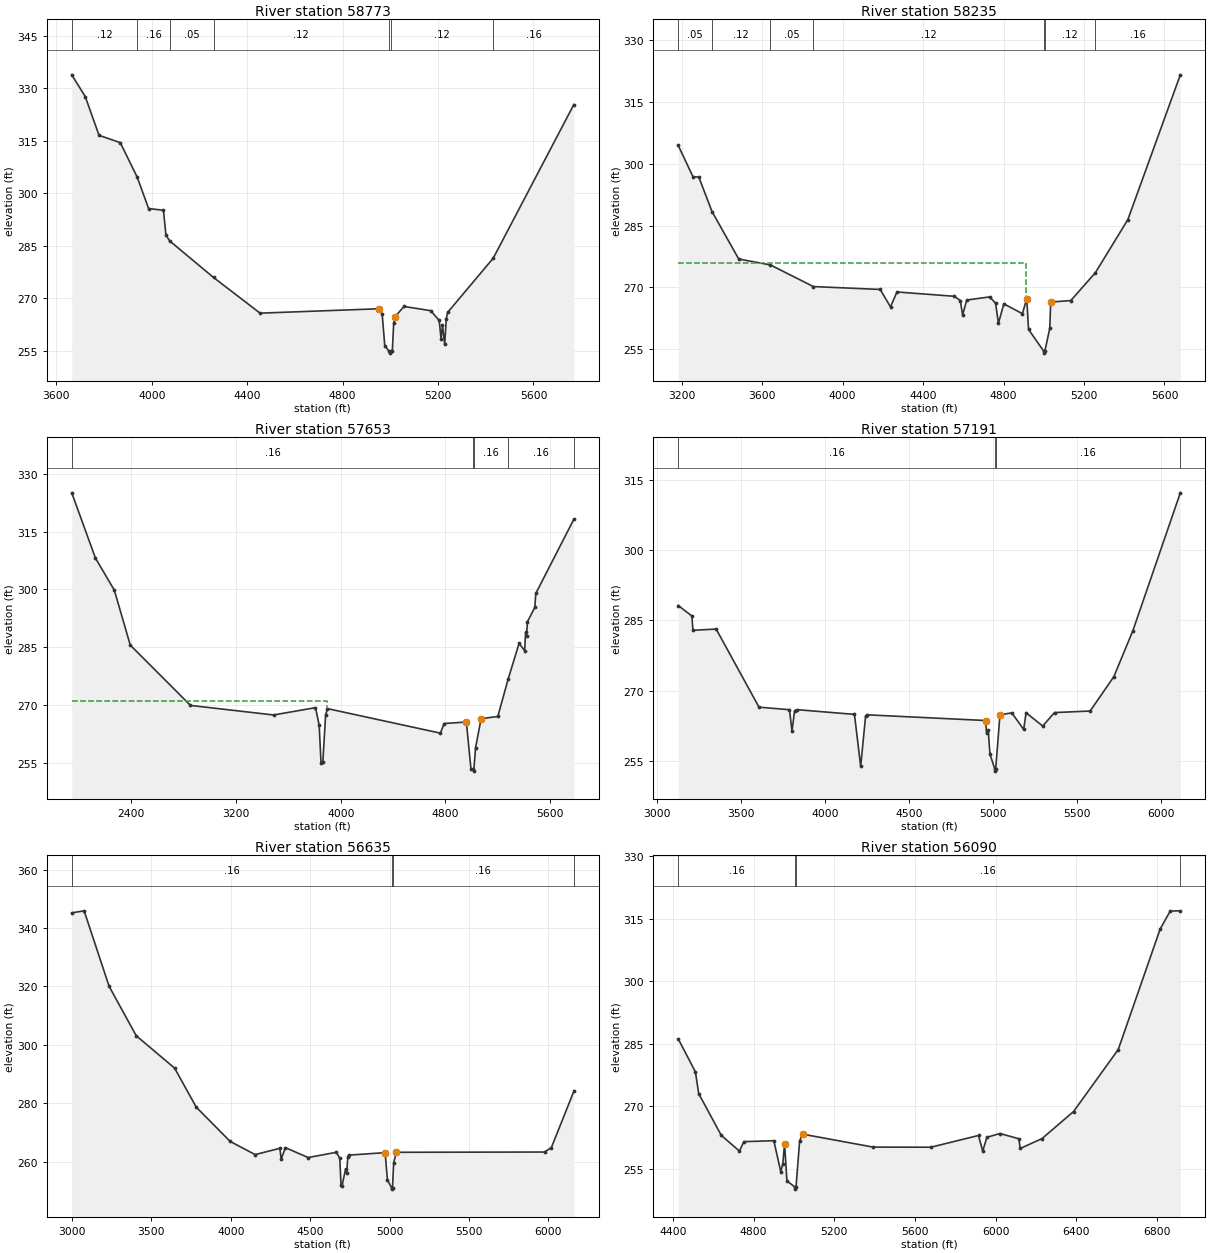
Type RM Length L Ch R = 1 ,58773   ,538,538,538
BEGIN DESCRIPTION:
MANSON CREEK 76.0
END DESCRIPTION:
XS GIS Cut Line= 3
      3763199.64      10592610.2      3761949.61     10592260.19
      3761249.64     10592660.17
#Sta/Elev= 30
  3664.9   333.9  3721.3  327.69  3779.2  316.58  3868.2  314.49  3939.3   304.6
  3986.9  295.63  4049.2  295.14  4059.5  288.08  4075.4  286.35    4259  275.91
  4454.2  265.69  4952.6  266.95  4965.9  265.44  4976.7  256.39  4995.3  254.75
    4998  254.25  5001.3  254.75  5008.4  254.87  5014.1   262.8  5020.6  264.71
  5057.3  267.61  5169.6   266.4  5204.9  263.59  5212.8  258.27  5218.6  262.25
  5227.9  256.75  5234.4  264.05  5240.1  265.89  5431.5  281.44  5769.2  325.39
#Mann= 7 ,-1 , 0
  3664.9     .12       0  3939.3     .16       0  4075.4     .05       0
    4259     .12       0  4995.3     .07       0  5001.3     .12       0
  5431.5     .16       0
Bank Sta=4952.6,5020.6
XS Rating Curve= 0 ,0
Exp/Cntr=0.3,0.1

Type RM Length L Ch R = 1 ,58235   ,582,582,582
BEGIN DESCRIPTION:
MANSON CREEK 75.0
END DESCRIPTION:
XS GIS Cut Line= 3
      3763299.64     10591560.18      3761499.61     10591960.19
      3760949.58     10592310.21
#Sta/Elev= 30
  3182.9  304.47  3255.9  296.91  3285.4  296.78  3350.8  288.42  3483.8  276.89
  3640.9  275.47  3854.7  270.21  4186.8  269.51  4238.1  265.28  4270.1   268.9
  4555.6  267.85  4585.1  266.81  4596.6  263.32  4617.1  266.94    4731   267.7
  4760.5  266.17  4774.6   261.3  4801.5  266.01  4893.7  263.64  4915.4  267.26
  4924.4   259.8  4999.5  254.55  5002.3  254.05  5005.5  254.55  5029.8  260.05
  5034.5  266.45  5134.4  266.82  5256.5  273.57    5418  286.47  5678.8  321.62
#Mann= 7 ,-1 , 0
  3182.9     .05       0  3350.8     .12       0  3640.9     .05       0
  3854.7     .12       0  4999.5     .07       0  5005.5     .12       0
  5256.5     .16       0
#XS Ineff= 2 , 0
          4910.8  276.03
Permanent Ineff=
       F       F
Bank Sta=4915.4,5034.5
XS Rating Curve= 0 ,0
Exp/Cntr=0.3,0.1

Type RM Length L Ch R = 1 ,57653   ,462,462,462
BEGIN DESCRIPTION:
MANSON CREEK 74.0
END DESCRIPTION:
XS GIS Cut Line= 3
      3762838.61     10588971.36      3762161.53     10590490.46
      3760677.14     10592079.01
#Sta/Elev= 30
  1944.7  325.07  2125.3  308.15  2270.1  299.78  2391.7  285.54  2852.1  269.87
  3487.1  267.39  3807.2  269.29  3835.5  264.78  3849.7  254.98  3863.8  255.29
  3884.8  267.38    3899  269.04  4762.2  262.67  4790.5  265.17  4960.5  265.56
  4995.7  253.36  5014.2  253.31  5016.9  252.81  5030.9  258.91  5073.4  266.44
  5200.9     267  5279.1  276.61  5363.6  285.99  5406.1  284.07  5413.4   288.9
  5420.2  287.99  5427.6  291.63  5483.7  295.32  5491.1  298.94    5782  318.21
#Mann= 5 ,-1 , 0
  1944.7     .16       0  5014.2     .07       0  5016.9     .16       0
  5279.1     .16       0    5782     .05       0
#XS Ineff= 2 , 0
         3897.73  271.13
Permanent Ineff=
       F       F
Bank Sta=4960.5,5073.4
XS Rating Curve= 0 ,0
Exp/Cntr=0.3,0.1

Type RM Length L Ch R = 1 ,57191   ,556,556,556
BEGIN DESCRIPTION:
MANSON CREEK 73.0
END DESCRIPTION:
XS GIS Cut Line= 3
      3762049.59     10589460.23      3761099.61     10591060.19
      3760299.61     10591860.18
#Sta/Elev= 30
  3124.2  288.19  3205.6  285.94  3211.8  282.88  3350.2  283.15  3605.4  266.44
  3787.1  265.89  3802.2  261.33  3817.8  265.69  3833.4   265.9  4174.4  264.89
  4211.4  253.79  4240.6  264.46  4248.4   264.8  4955.7  263.58  4961.7  260.81
  4971.3  261.59    4982  256.39  5010.2  253.25    5013  252.75  5016.2  253.25
  5041.5   264.8  5112.2  265.22  5182.9  261.67  5197.1  265.25  5296.1   262.4
  5366.8  265.28  5578.9  265.61  5720.3  272.97  5833.5  282.79  6116.3   312.3
#Mann= 4 ,-1 , 0
  3124.2     .16       0  5010.2     .07       0  5016.2     .16       0
  6116.3     .05       0
Bank Sta=4955.7,5041.5
XS Rating Curve= 0 ,0
Exp/Cntr=0.3,0.1

Type RM Length L Ch R = 1 ,56635   ,545,545,545
BEGIN DESCRIPTION:
MANSON CREEK 72.0
END DESCRIPTION:
XS GIS Cut Line= 3
      3762199.62     10588960.18      3760949.61     10590560.19
      3760149.59     10591360.21
#Sta/Elev= 30
  2999.1  345.21  3076.9   345.9  3234.3  320.05  3405.2  303.13  3646.7  292.06
  3783.2  278.68  3996.7  266.96  4153.9  262.45  4309.6  264.61  4317.7  260.91
  4344.9  264.83  4487.8  261.44  4665.9  263.25  4686.9  261.12  4694.9  251.99
  4701.2  251.84  4723.8   257.6  4730.1  256.04  4737.6  261.79  4744.6  262.27
  4972.5  263.12    4987  253.75  5012.9  251.13  5015.7  250.63  5018.9  251.13
  5026.3  259.74  5043.6  263.24    5977  263.33  6019.5  264.88  6160.9  284.12
#Mann= 4 ,-1 , 0
  2999.1     .16       0  5012.9     .07       0  5018.9     .16       0
  6160.9     .05       0
Bank Sta=4972.5,5043.6
XS Rating Curve= 0 ,0
Exp/Cntr=0.3,0.1

Type RM Length L Ch R = 1 ,56090   ,541,541,541
BEGIN DESCRIPTION:
MANSON CREEK 71.0
END DESCRIPTION:
XS GIS Cut Line= 3
      3760949.61     10589460.21      3760849.61     10590010.19
      3759699.62     10591560.17
#Sta/Elev= 30
  4426.2  286.17  4511.3  278.28  4527.8  273.05  4639.6  263.06  4729.8   259.3
  4751.4  261.56  4900.1  261.79  4934.4  254.39  4944.5  256.22  4953.4  261.07
  4964.9  252.19  5004.1  250.69  5006.9  250.19  5010.1  250.69    5028  261.74
  5042.6  263.36  5393.1  260.25    5679  260.23  5914.8  263.04  5935.6  259.29
  5956.4   262.6  6021.1  263.51  6115.1  262.25  6121.3  259.92  6229.8   262.3
    6386  268.78  6607.4  283.61  6815.6  312.52  6865.4  316.79  6915.2  316.84
#Mann= 4 ,-1 , 0
  4426.2     .16       0  5004.1     .07       0  5010.1     .16       0
  6915.2     .05       0
Bank Sta=4953.4,5042.6
XS Rating Curve= 0 ,0
Exp/Cntr=0.3,0.1

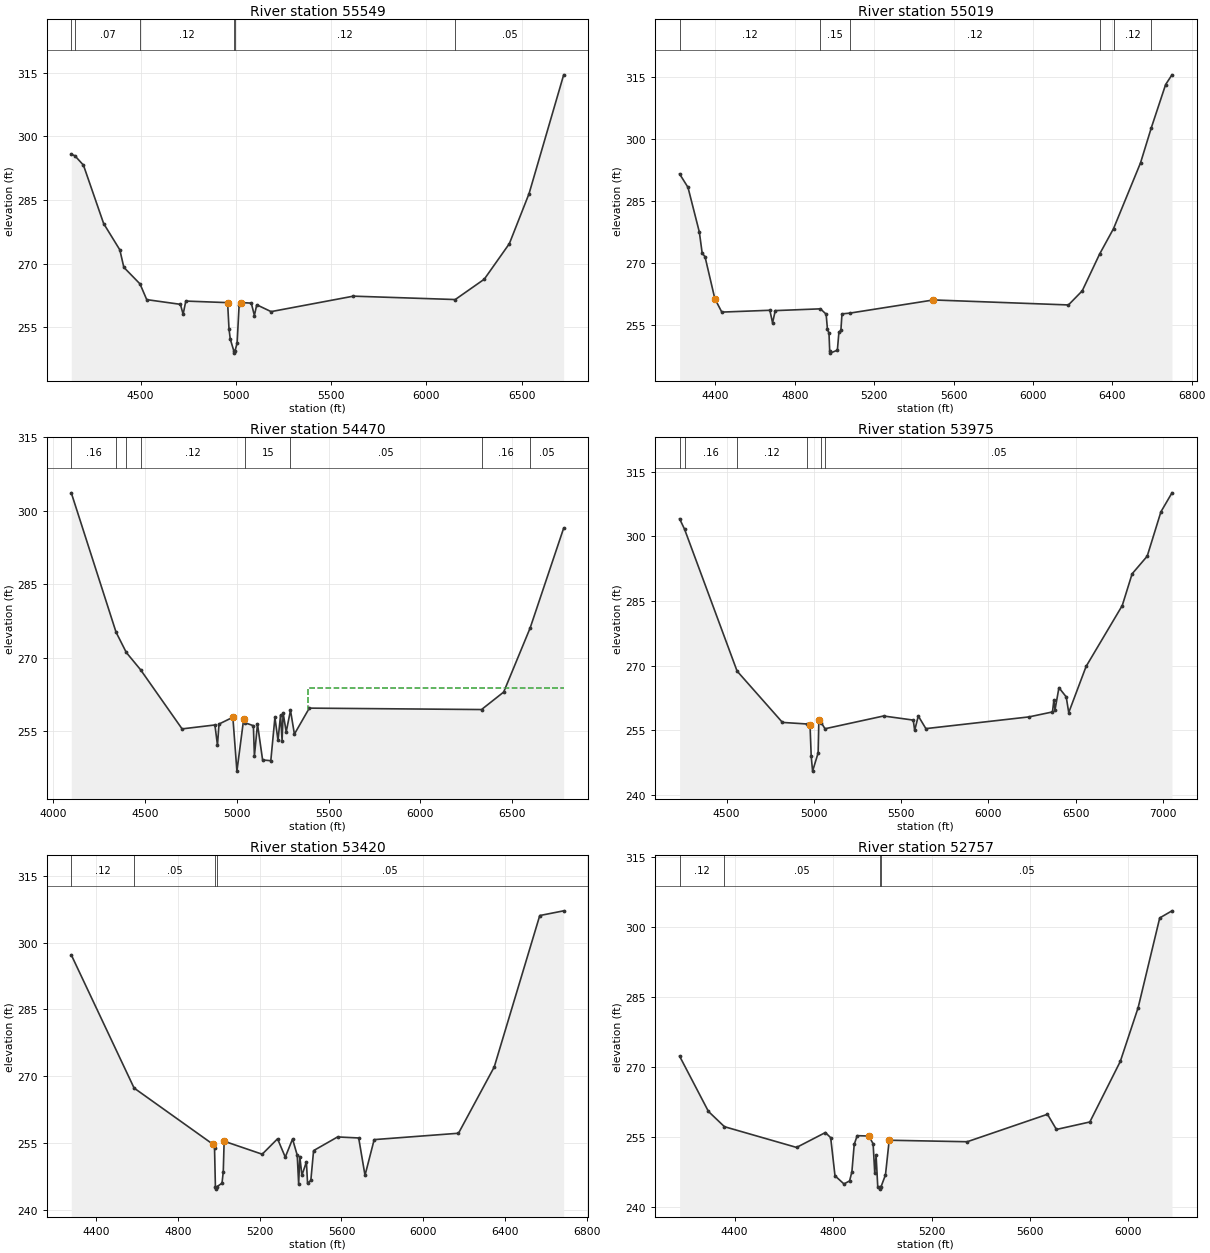
Type RM Length L Ch R = 1 ,55549   ,530,530,530
BEGIN DESCRIPTION:
MANSON CREEK 70.0
END DESCRIPTION:
XS GIS Cut Line= 3
      3760949.64     10589210.16      3760349.61     10589860.19
      3759649.59     10591410.22
#Sta/Elev= 30
  4135.9  295.79  4154.4  295.46  4199.7  293.23  4305.8  279.44  4390.8  273.23
  4411.8  269.11  4496.7  265.19    4532  261.48  4708.9  260.37  4723.1  258.04
  4737.3  261.14  4956.7  260.77  4964.1  254.52  4970.9  252.13  4989.5  249.35
  4992.2  248.85  4995.5  249.35  5006.6  251.23  5017.1  260.18  5029.3  260.78
  5081.1  260.66  5097.3  257.73  5109.7  260.26  5185.1  258.65  5617.2   262.3
  6151.9   261.5  6304.3   266.3    6436  274.69  6539.6  286.52  6721.3  314.55
#Mann= 6 ,-1 , 0
  4135.9     .05       0  4154.4     .07       0  4496.7     .12       0
  4989.5     .07       0  4995.5     .12       0  6151.9     .05       0
Bank Sta=4956.7,5029.3
XS Rating Curve= 0 ,0
Exp/Cntr=0.3,0.1

Type RM Length L Ch R = 1 ,55019   ,549,549,549
BEGIN DESCRIPTION:
MANSON CREEK 69.0
END DESCRIPTION:
XS GIS Cut Line= 3
      3760549.62     10589060.18      3759949.61     10589560.19
       3759249.6     10591110.21
#Sta/Elev= 30
    4219   291.5  4261.3  288.25  4318.6  277.43  4332.9  272.32  4347.2  271.46
  4396.7   261.3  4431.8  258.06    4674   258.5  4687.6  255.46  4701.3  258.42
  4929.1  258.85  4957.7  257.55  4964.2  253.94  4972.1  252.94  4975.6  248.63
  4978.3  248.13  5014.3  248.85    5022  253.17    5032  253.62  5037.5  257.63
  5076.8  257.81  5498.7     261    6179  259.79  6248.4   263.2  6336.1  272.11
  6406.4  278.28  6542.3  294.18  6596.8  302.69  6668.8  313.13  6700.8  315.48
#Mann= 6 ,-1 , 0
    4219     .12       0  4929.1     .15       0  5076.8     .12       0
  6336.1     .16       0  6406.4     .12       0  6596.8     .05       0
Bank Sta=4396.7,5498.7
XS Rating Curve= 0 ,0
Exp/Cntr=0.3,0.1

Type RM Length L Ch R = 1 ,54470   ,495,495,495
BEGIN DESCRIPTION:
MANSON CREEK 68.0
END DESCRIPTION:
XS GIS Cut Line= 3
      3760149.63     10588310.15      3759749.61     10589110.19
      3758149.63     10589910.18
#Sta/Elev= 30
  4097.8  303.68  4341.7  275.22  4397.6  271.07  4475.2  267.55  4701.6  255.46
  4880.5  256.26  4894.4  252.12  4902.8  256.45  4978.3  257.83  5000.4  246.83
    5037   257.4  5045.4   256.7  5090.1  256.11  5095.7   249.9  5112.5  256.45
  5140.4  249.11  5185.1  248.96  5207.5  257.79  5224.3  253.11  5238.2  258.28
  5246.6  253.07  5252.2  258.71    5269  254.86  5292.4  259.24  5313.7  254.39
  5394.8   259.7  6333.4  259.41  6454.1  262.98  6598.4  276.08  6781.1  296.48
#Mann= 8 ,-1 , 0
  4097.8     .16       0  4341.7     .05       0  4397.6     .16       0
  4475.2     .12       0  5045.4      15       0  5292.4     .05       0
  6333.4     .16       0  6598.4     .05       0
#XS Ineff= 2 , 0
                          5385.8          263.74
Permanent Ineff=
       F       F
Bank Sta=4978.3,5037
XS Rating Curve= 0 ,0
Exp/Cntr=0.3,0.1

Type RM Length L Ch R = 1 ,53975   ,555,555,555
BEGIN DESCRIPTION:
MANSON CREEK 67.0
END DESCRIPTION:
XS GIS Cut Line= 3
      3760149.65     10588260.16      3759499.61     10588710.19
      3757899.62     10589960.18
#Sta/Elev= 30
    4231  304.05  4259.6  301.62  4560.4  268.72  4820.3  256.81  4963.5  256.44
  4978.4  256.15  4985.1  248.94    4993  245.51  5024.8  249.74  5028.9   257.4
  5043.3  256.72  5064.1  255.34  5399.7   258.3  5569.7  257.35  5577.8  254.97
  5598.6   258.3    5642  255.37  6232.6  258.09  6367.4  259.24  6375.5  262.02
  6381.9  259.74  6404.4  264.87  6446.1  262.73  6460.5  259.09    6560   269.8
  6767.1  283.92  6823.6  291.28    6910  295.37  6988.6  305.66    7052  310.07
#Mann= 6 ,-1 , 0
    4231     .12       0  4259.6     .16       0  4560.4     .12       0
  4963.5     .05       0  5043.3     .12       0  5064.1     .05       0
Bank Sta=4978.4,5028.9
XS Rating Curve= 0 ,0
Exp/Cntr=0.3,0.1

Type RM Length L Ch R = 1 ,53420   ,663,663,663
BEGIN DESCRIPTION:
MANSON CREEK 66.0
END DESCRIPTION:
XS GIS Cut Line= 3
      3759799.62     10587860.18      3759199.61     10588310.19
      3757749.58     10589110.21
#Sta/Elev= 30
  4279.8  297.24  4586.7  267.34  4972.5   254.7  4979.8   253.8  4984.1  245.14
  4986.9  244.64  4990.1  245.14  5016.3  245.97  5022.5  248.57  5026.7   255.4
  5212.6  252.48  5287.7  255.94  5325.5  251.83    5361  255.89  5383.9  252.26
  5390.8   245.8  5396.5  251.96  5406.7  247.74  5428.7  250.75  5434.4  245.91
  5450.4  246.61  5463.8  253.29  5581.1  256.36  5684.2  256.13  5715.1  247.74
  5759.9  255.76  6171.9  257.19  6346.6  272.08    6569  306.08  6685.9  307.14
#Mann= 4 ,-1 , 0
  4279.8     .12       0  4586.7     .05       0  4984.1     .03       0
  4990.1     .05       0
Bank Sta=4972.5,5026.7
XS Rating Curve= 0 ,0
Exp/Cntr=0.3,0.1

Type RM Length L Ch R = 1 ,52757   ,413,413,413
BEGIN DESCRIPTION:
MANSON CREEK 65.0
END DESCRIPTION:
XS GIS Cut Line= 3
      3759649.64     10587760.18      3758899.61     10588060.19
       3757899.6     10588710.19
#Sta/Elev= 30
  4176.5  272.36  4293.7  260.52  4358.8  257.25  4651.8  252.81  4768.9     256
  4790.4  254.89  4807.9  246.74  4844.3  244.99  4867.2  245.64  4876.6  247.61
    4886  253.46  4898.1  255.33  4945.3  255.25  4962.8  253.59  4969.5  247.24
  4974.9  251.11  4981.6  244.38  4988.9  244.38  4991.6  243.88  4994.9  244.38
    5013  246.93  5028.1  254.35  5345.1  254.03  5671.2  259.91  5707.5  256.66
  5843.3  258.26  5967.1  271.24  6039.6  282.76  6127.2  301.96    6177  303.48
#Mann= 4 ,-1 , 0
  4176.5     .12       0  4358.8     .05       0  4988.9     .03       0
  4994.9     .05       0
Bank Sta=4945.3,5028.1
XS Rating Curve= 0 ,0
Exp/Cntr=0.3,0.1

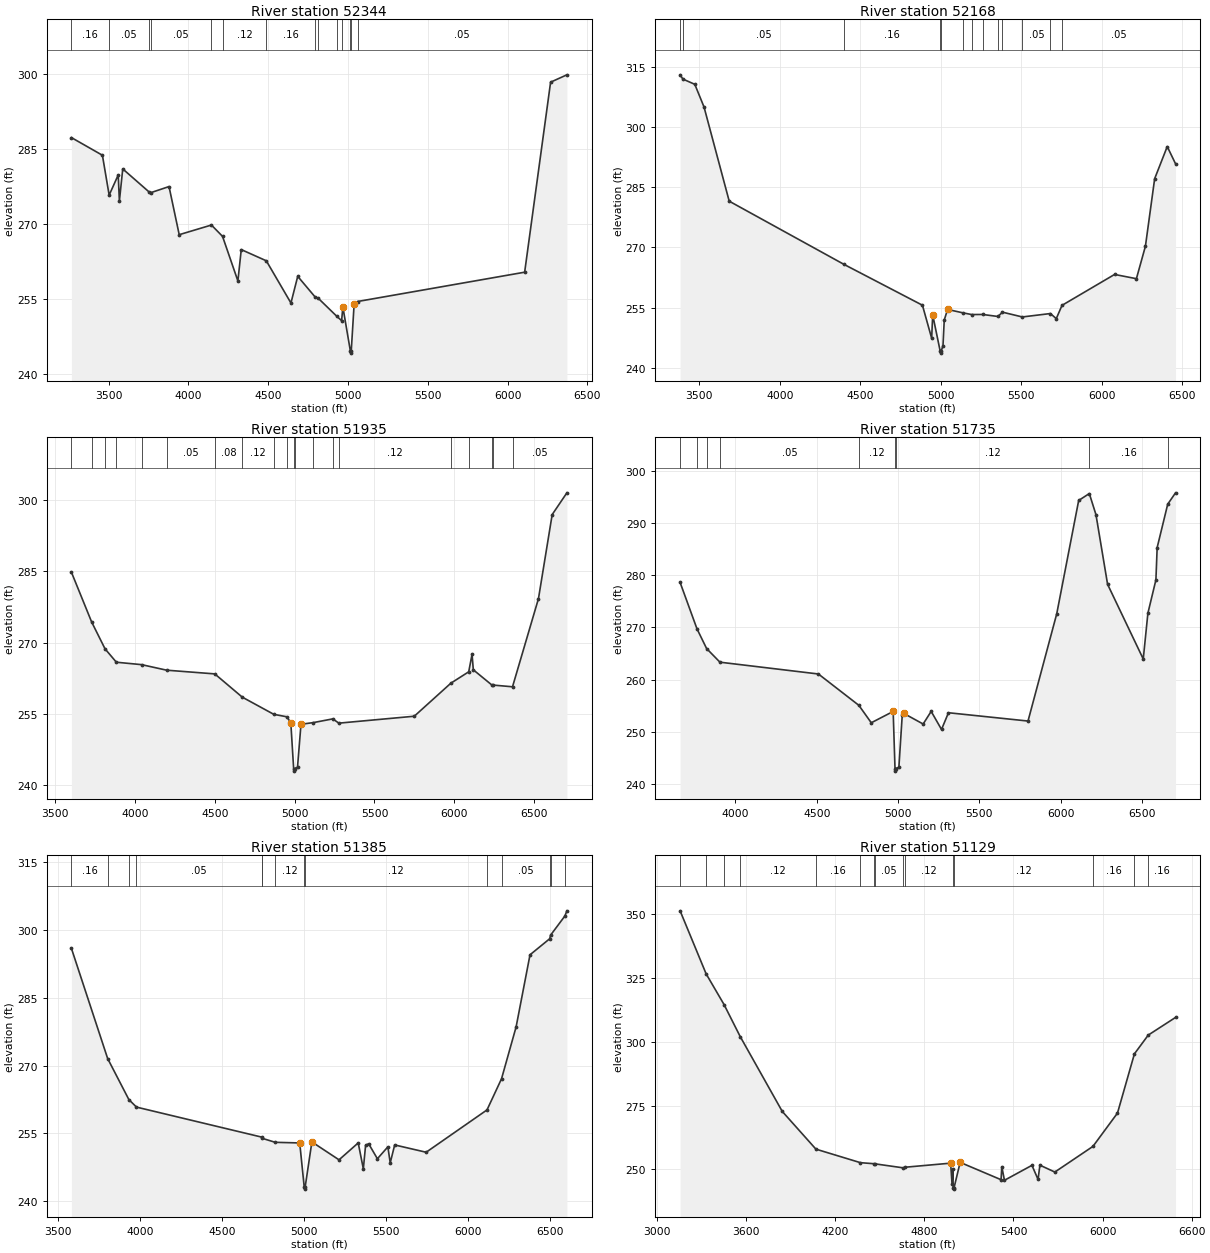
Type RM Length L Ch R = 1 ,52344   ,176,176,176
BEGIN DESCRIPTION:
Mapping XS 1747e0be
END DESCRIPTION:
XS GIS Cut Line= 3
      3760005.61      10586421.6      3758401.46     10588102.15
      3757866.74     10588671.58
#Sta/Elev= 30
  3267.1  287.25  3461.2  283.72  3503.4  275.75  3560.3  279.78  3567.5  274.55
  3588.6  280.99  3751.9  276.43  3766.2  276.26  3878.6  277.46  3942.4  267.84
  4144.3  269.77  4213.9   267.5  4310.1  258.59  4331.2  264.86  4488.1  262.62
  4642.5  254.18    4685  259.51  4794.6  255.36  4810.9  255.21    4929  251.55
  4960.1  250.65  4967.8   253.4  5014.5  244.66  5017.2  244.16  5020.5  244.66
  5038.5  253.99  5059.8  254.48  6106.9  260.34  6269.5  298.33  6371.5   299.8
#Mann= 14 ,-1 , 0
  3267.1     .16       0  3503.4     .05       0  3751.9     .16       0
  3766.2     .05       0  4144.3     .16       0  4213.9     .12       0
  4488.1     .16       0  4794.6     .05       0  4810.9     .12       0
    4929     .05       0  4960.1     .12       0  5014.5     .07       0
  5020.5     .12       0  5059.8     .05       0
Bank Sta=4967.8,5038.5
XS Rating Curve= 0 ,0
Exp/Cntr=0.3,0.1

Type RM Length L Ch R = 1 ,52168   ,233,233,233
BEGIN DESCRIPTION:
MANSON CREEK 64.0
END DESCRIPTION:
XS GIS Cut Line= 2
      3759790.35     10586261.86      3757832.69     10588636.05
#Sta/Elev= 30
  3380.8  312.96  3398.1   311.9  3472.1   310.6  3529.5  304.94  3685.8  281.52
  4397.4  265.82  4885.9  255.63  4943.2  247.42  4949.7  253.21  4996.2  244.21
  4998.9  243.71  5002.2  244.21  5013.5  245.51  5021.4  251.95  5042.2  254.58
  5136.8  253.74  5191.6  253.31    5260  253.33  5354.7  252.83  5383.2   253.9
  5506.4  252.71  5680.8  253.56  5717.2  252.29  5752.9   255.6  6079.4  263.29
  6214.9  262.23  6270.9  270.31  6328.3  287.12  6406.4  295.11    6458  290.82
#Mann= 13 ,-1 , 0
  3380.8     .16       0  3398.1     .05       0  4397.4     .16       0
  4996.2     .07       0  5002.2     .16       0  5136.8     .12       0
  5191.6     .16       0    5260     .12       0  5354.7     .05       0
  5383.2     .16       0  5506.4     .05       0  5680.8     .16       0
  5752.9     .05       0
Bank Sta=4949.7,5042.2
XS Rating Curve= 0 ,0
Exp/Cntr=0.3,0.1

Type RM Length L Ch R = 1 ,51935   ,200,200,200
BEGIN DESCRIPTION:
Mapping XS 40bee21c
END DESCRIPTION:
XS GIS Cut Line= 3
       3759512.6     10586247.94      3757859.79     10588247.98
      3757444.84     10588545.36
#Sta/Elev= 30
  3600.8  284.82  3727.4  274.33  3811.2  268.67  3882.4  265.84  4040.6  265.33
  4197.5  264.16  4499.1  263.38  4671.2  258.48    4869  254.85  4950.9  254.33
  4975.7  253.06  4993.5  243.37  4996.3  242.87  4999.5  243.37  5017.7  243.73
  5039.5  252.75  5115.7   253.1    5239  253.89  5276.6  252.99  5749.5  254.45
  5978.9  261.42  6090.7  263.82  6111.6  267.51  6119.5  264.24  6234.5  261.07
  6240.1  261.03  6365.2  260.66  6527.8  279.25  6613.8  296.98  6705.9  301.57
#Mann= 20 ,-1 , 0
  3600.8     .16       0  3727.4     .05       0  3811.2     .16       0
  3882.4     .05       0  4040.6     .08       0  4197.5     .05       0
  4499.1     .08       0  4671.2     .12       0    4869     .05       0
  4950.9     .12       0  4993.5     .03       0  4999.5     .05       0
  5115.7     .16       0    5239     .05       0  5276.6     .12       0
  5978.9     .16       0  6090.7     .12       0  6234.5     .05       0
  6240.1     .16       0  6365.2     .05       0
Bank Sta=4975.7,5039.5
XS Rating Curve= 0 ,0
Exp/Cntr=0.3,0.1

Type RM Length L Ch R = 1 ,51735   ,350,350,350
BEGIN DESCRIPTION:
Mapping XS af5279e5
END DESCRIPTION:
XS GIS Cut Line= 3
      3759457.02     10586254.92      3758519.51     10587143.81
      3757374.95     10588475.66
#Sta/Elev= 30
  3659.4   278.6  3763.1  269.73  3822.5  265.94  3904.5  263.33  4510.2  261.07
  4759.1  255.07  4835.5  251.73  4970.2   253.9  4981.5  242.97  4984.3  242.47
  4987.5  242.97  5005.4  243.23  5026.2   253.3  5033.9  253.55  5154.6  251.49
    5204  253.91  5267.6  250.45  5310.4  253.65  5799.8  252.06  5976.5   272.6
  6111.5   294.3  6176.9  295.62  6217.9  291.57  6289.3  278.24  6508.7  263.94
  6537.3  272.71  6586.6  279.09  6594.3  285.28  6659.3  293.59  6707.4  295.76
#Mann= 9 ,-1 , 0
  3659.4     .16       0  3763.1     .12       0  3822.5     .16       0
  3904.5     .05       0  4759.1     .12       0  4981.5     .07       0
  4987.5     .12       0  6176.9     .16       0  6659.3     .05       0
Bank Sta=4970.2,5033.9
XS Rating Curve= 0 ,0
Exp/Cntr=0.3,0.1

Type RM Length L Ch R = 1 ,51385   ,256,256,256
BEGIN DESCRIPTION:
MANSON CREEK 63.0
END DESCRIPTION:
XS GIS Cut Line= 3
      3759575.04     10586136.88      3758012.57     10587060.48
      3757069.51     10587816.31
#Sta/Elev= 30
  3579.6  295.95  3800.7  271.55  3930.2  262.46  3976.6   260.8  4741.1  254.15
  4745.2  253.87  4823.5     253  4972.8  252.86  5000.1  243.13  5002.9  242.63
  5006.1  243.13    5047  253.09  5212.7  249.12  5329.7  252.87    5361  247.13
  5374.8  252.33  5393.5  252.68  5446.7  249.36  5510.7  251.99  5525.1  248.45
  5552.3  252.42  5744.4   250.8  6115.8  260.18  6204.5  267.09  6293.4  278.57
  6378.2  294.54  6498.5   298.1  6503.8  298.89  6591.1  303.14  6603.2  304.28
#Mann= 14 ,-1 , 0
  3579.6     .16       0  3800.7     .12       0  3930.2     .16       0
  3976.6     .05       0  4741.1     .16       0  4745.2     .05       0
  4823.5     .12       0  5000.1     .07       0  5006.1     .12       0
  6115.8     .16       0  6204.5     .05       0  6498.5     .12       0
  6503.8     .05       0  6591.1      .1       0
Bank Sta=4972.8,5047
XS Rating Curve= 0 ,0
Exp/Cntr=0.3,0.1

Type RM Length L Ch R = 1 ,51129   ,506,506,506
BEGIN DESCRIPTION:
MANSON CREEK 62.0
END DESCRIPTION:
XS GIS Cut Line= 3
      3759849.63     10585610.18      3758299.61     10586610.19
      3756849.56      10586960.2
#Sta/Elev= 30
  3155.3  351.28  3330.6  326.59  3451.3  314.56  3560.2  302.01  3843.3  272.71
  4069.9  257.94  4369.7  252.64  4461.4  252.23  4469.3  252.17  4658.2  250.61
  4673.1  250.87  4977.1  252.45  4986.4  244.46  4992.3  250.09  4993.9  242.78
  4996.7  242.28  4999.9  242.78  5041.1  252.76  5316.6  245.97  5321.7  251.06
  5339.4  245.74  5524.6   251.6  5565.7  246.08  5578.2  251.66  5678.9  248.97
  5935.4  259.02  6100.6  272.06  6214.6  295.26  6307.8  302.61  6491.6  309.53
#Mann= 15 ,-1 , 0
  3155.3     .16       0  3330.6      .1       0  3451.3     .16       0
  3560.2     .12       0  4069.9     .16       0  4369.7     .05       0
  4461.4     .12       0  4469.3     .05       0  4658.2     .16       0
  4673.1     .12       0  4993.9     .07       0  4999.9     .12       0
  5935.4     .16       0  6214.6     .12       0  6307.8     .16       0
Bank Sta=4977.1,5041.1
XS Rating Curve= 0 ,0
Exp/Cntr=0.3,0.1

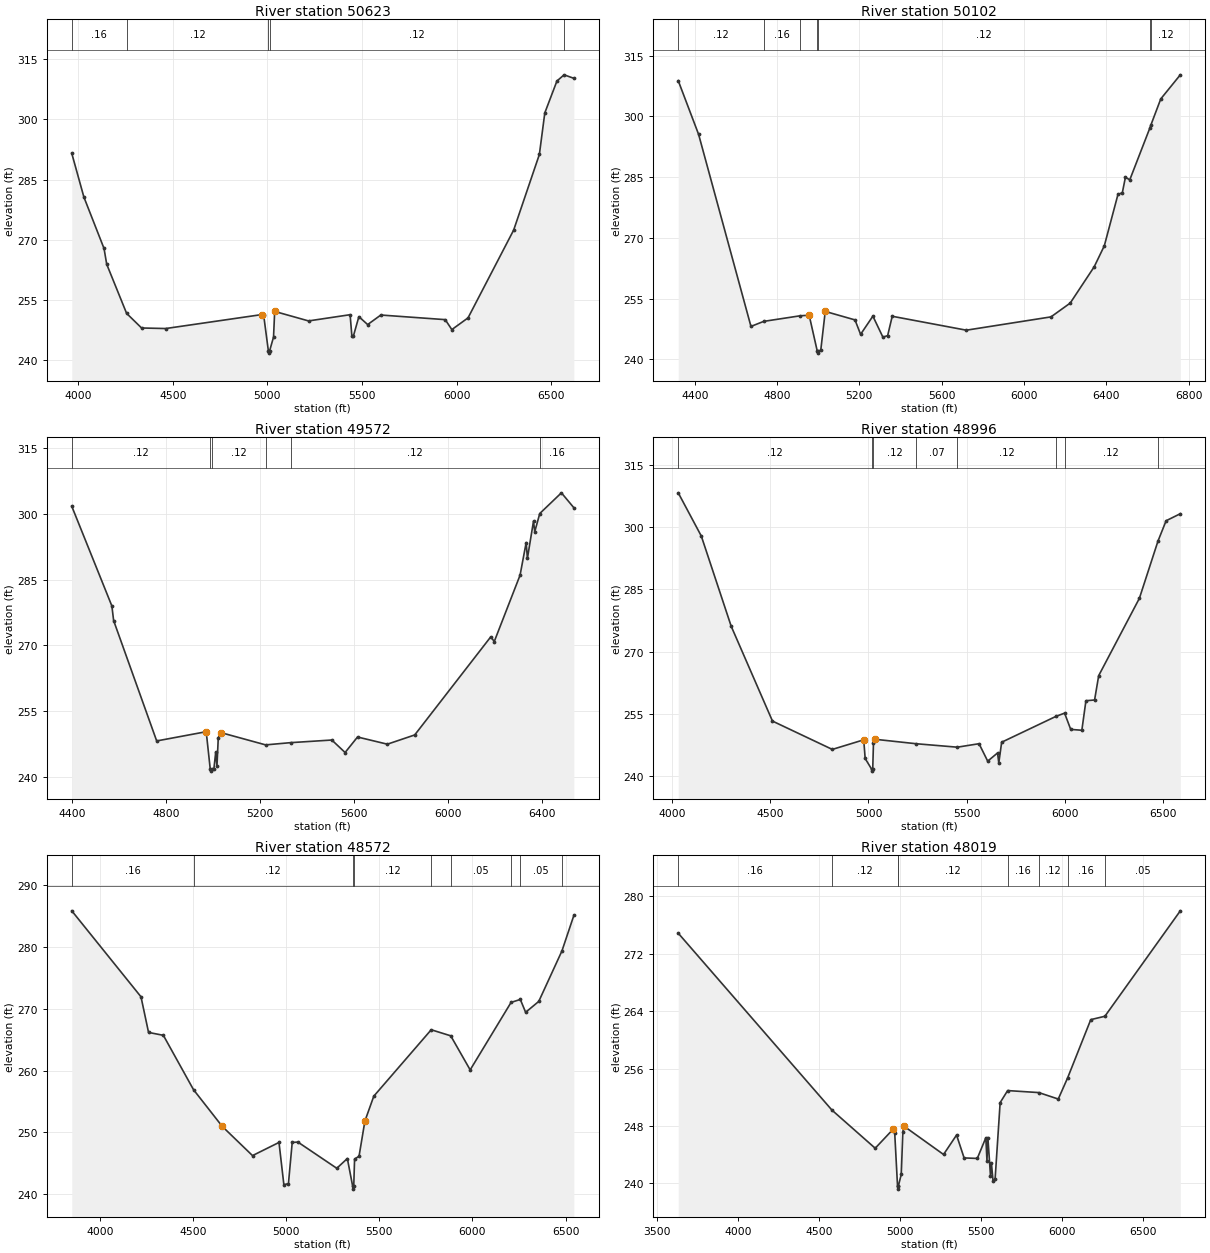
Type RM Length L Ch R = 1 ,50623   ,521,521,521
BEGIN DESCRIPTION:
MANSON CREEK 61.0
END DESCRIPTION:
XS GIS Cut Line= 3
       3759199.6      10585460.2      3758399.61     10586160.19
      3756949.63     10586810.18
#Sta/Elev= 30
  3966.5  291.53  4030.5  280.63  4136.9  267.81  4151.1  263.88  4256.2  251.63
  4335.2  247.99  4462.4  247.85    4973  251.35  4979.7  251.34  5005.1  242.22
  5007.9  241.72  5011.1  242.22  5032.2  245.71  5038.3  252.12  5217.1  249.75
  5436.7   251.3  5445.9  246.06  5454.4  246.03    5483  250.81  5529.4  248.84
  5598.9  251.22  5939.1  250.07  5974.1  247.59  6059.6  250.51  6300.7  272.41
  6436.4  291.25  6465.1  301.62  6529.2  309.57    6567  311.11  6618.5  310.24
#Mann= 5 ,-1 , 0
  3966.5     .16       0  4256.2     .12       0  5005.1     .07       0
  5011.1     .12       0    6567     .16       0
Bank Sta=4973,5038.3
XS Rating Curve= 0 ,0
Exp/Cntr=0.3,0.1

Type RM Length L Ch R = 1 ,50102   ,530,530,530
BEGIN DESCRIPTION:
MANSON CREEK 60.0
END DESCRIPTION:
XS GIS Cut Line= 3
      3758899.59     10585160.21      3758399.61     10585660.19
      3756949.59      10586610.2
#Sta/Elev= 30
  4319.5  308.84  4418.5  295.57    4673   248.1  4735.1  249.35    4911  250.72
  4955.9  250.88  4995.3     242    4998   241.5  5001.3     242  5012.4  242.23
  5034.1  251.81  5178.8  249.71  5205.9  246.14  5265.7  250.64  5314.4  245.45
  5337.4  245.82  5359.7  250.61    5720  247.17  6131.5  250.46  6224.9  253.87
  6341.6  262.85  6390.7  268.03  6457.1  280.74  6478.2  281.14  6493.3  284.97
  6514.4  284.33  6612.5   297.2  6616.3  297.78  6665.1  304.34  6760.1  310.29
#Mann= 7 ,-1 , 0
  4319.5     .12       0  4735.1     .16       0    4911     .12       0
  4995.3     .07       0  5001.3     .12       0  6612.5     .16       0
  6616.3     .12       0
Bank Sta=4955.9,5034.1
XS Rating Curve= 0 ,0
Exp/Cntr=0.3,0.1

Type RM Length L Ch R = 1 ,49572   ,576,576,576
BEGIN DESCRIPTION:
MANSON CREEK 59.0
END DESCRIPTION:
XS GIS Cut Line= 3
      3758849.58     10585110.19      3758249.61     10585160.19
      3756799.64     10585660.18
#Sta/Elev= 30
    4399  301.72  4569.6  278.96  4577.1  275.62  4760.2  248.15  4970.9  250.26
    4988  241.76  4990.8  241.26    4994  241.76  5003.7  241.83  5011.4   245.6
  5016.6   242.4  5022.2  248.86  5032.8  250.06  5223.7  247.25  5329.7  247.76
  5505.3  248.36  5561.7  245.51  5614.6  249.05  5741.5  247.41  5857.9  249.52
  6181.3  271.91  6196.3  270.85  6306.1     286    6332  293.44  6337.3  289.83
  6363.2  298.32  6368.5  295.93  6389.9  300.07  6481.9  304.79  6534.8  301.39
#Mann= 6 ,-1 , 0
    4399     .12       0    4988     .07       0    4994     .12       0
  5223.7     .07       0  5329.7     .12       0  6389.9     .16       0
Bank Sta=4970.9,5032.8
XS Rating Curve= 0 ,0
Exp/Cntr=0.3,0.1

Type RM Length L Ch R = 1 ,48996   ,424,424,424
BEGIN DESCRIPTION:
MANSON CREEK 58.0
END DESCRIPTION:
XS GIS Cut Line= 3
      3758949.57     10585110.17      3758149.61     10584610.19
      3756849.59      10585560.2
#Sta/Elev= 30
  4032.5  308.37  4149.8  297.92  4301.9   276.1  4511.8  253.18  4816.1  246.33
  4975.9  248.65  4983.2  244.14  5015.7  241.58  5018.5  241.08  5021.7  241.58
  5025.4  247.83  5033.4  248.78  5243.5   247.7  5451.7  246.87  5562.4  247.71
  5606.4  243.49  5656.6  245.48  5662.8  243.05  5677.4  248.07  5954.1  254.33
  5997.4   255.1  6028.6  251.17  6085.2  250.96    6106   258.1    6150  258.28
  6170.9  264.17  6377.9  282.87  6472.5  296.71  6513.8  301.62    6586  303.32
#Mann= 8 ,-1 , 0
  4032.5     .12       0  5015.7     .07       0  5021.7     .12       0
  5243.5     .07       0  5451.7     .12       0  5954.1     .16       0
  5997.4     .12       0  6472.5     .16       0
Bank Sta=4975.9,5033.4
XS Rating Curve= 0 ,0
Exp/Cntr=0.3,0.1

Type RM Length L Ch R = 1 ,48572   ,553,553,553
BEGIN DESCRIPTION:
MANSON CREEK 57.0
END DESCRIPTION:
XS GIS Cut Line= 3
      3759365.77     10584449.73      3757963.03     10584206.68
      3756747.71     10584581.69
#Sta/Elev= 30
  3849.1  285.84  4220.7  271.94  4261.3  266.18  4340.8  265.71  4502.7  256.92
  4657.1  250.98  4819.5  246.26  4961.6  248.39  4987.8  241.56  5012.3  241.72
  5032.6  248.39  5063.1  248.45  5271.9  244.21  5328.6  245.79    5357  241.34
  5359.8  240.84    5363  241.34  5367.4   245.7  5391.4  246.16  5422.8  251.84
  5470.6  255.87  5778.9  266.61  5883.6  265.63    5988  260.12  6207.5  271.03
  6257.3  271.51  6285.7  269.43  6356.2  271.19  6480.6  279.35  6544.6  285.09
#Mann= 9 ,-1 , 0
  3849.1     .16       0  4502.7     .12       0    5357     .07       0
    5363     .12       0  5778.9     .16       0  5883.6     .05       0
  6207.5     .12       0  6257.3     .05       0  6480.6     .16       0
Bank Sta=4657.1,5422.8
XS Rating Curve= 0 ,0
Exp/Cntr=0.3,0.1

Type RM Length L Ch R = 1 ,48019   ,733,733,733
BEGIN DESCRIPTION:
MANSON CREEK 56.0
END DESCRIPTION:
XS GIS Cut Line= 4
      3759719.95     10583873.34      3758463.03      10583741.4
      3757997.75     10583790.01       3756796.4     10584449.71
#Sta/Elev= 30
  3629.7  274.87  4579.3  250.21  4846.7  244.89  4957.3  247.54  4967.3  247.01
  4984.5  239.69  4987.2  239.19  4990.5  239.69  5007.6  241.24  5017.6  247.16
  5024.4  247.97    5269  244.02  5349.4  246.73    5396  243.54  5477.5  243.47
  5530.3  246.36  5537.2  243.18  5542.9  246.38    5559  241.08  5564.7  242.82
  5575.1  240.29  5587.4  240.54  5618.7  251.25    5665  252.93  5857.6  252.65
  5977.8  251.75  6036.2  254.73  6178.6  262.82  6265.9  263.29  6731.9  277.99
#Mann= 8 ,-1 , 0
  3629.7     .16       0  4579.3     .12       0  4984.5     .07       0
  4990.5     .12       0    5665     .16       0  5857.6     .12       0
  6036.2     .16       0  6265.9     .05       0
Bank Sta=4957.3,5024.4
XS Rating Curve= 0 ,0
Exp/Cntr=0.3,0.1

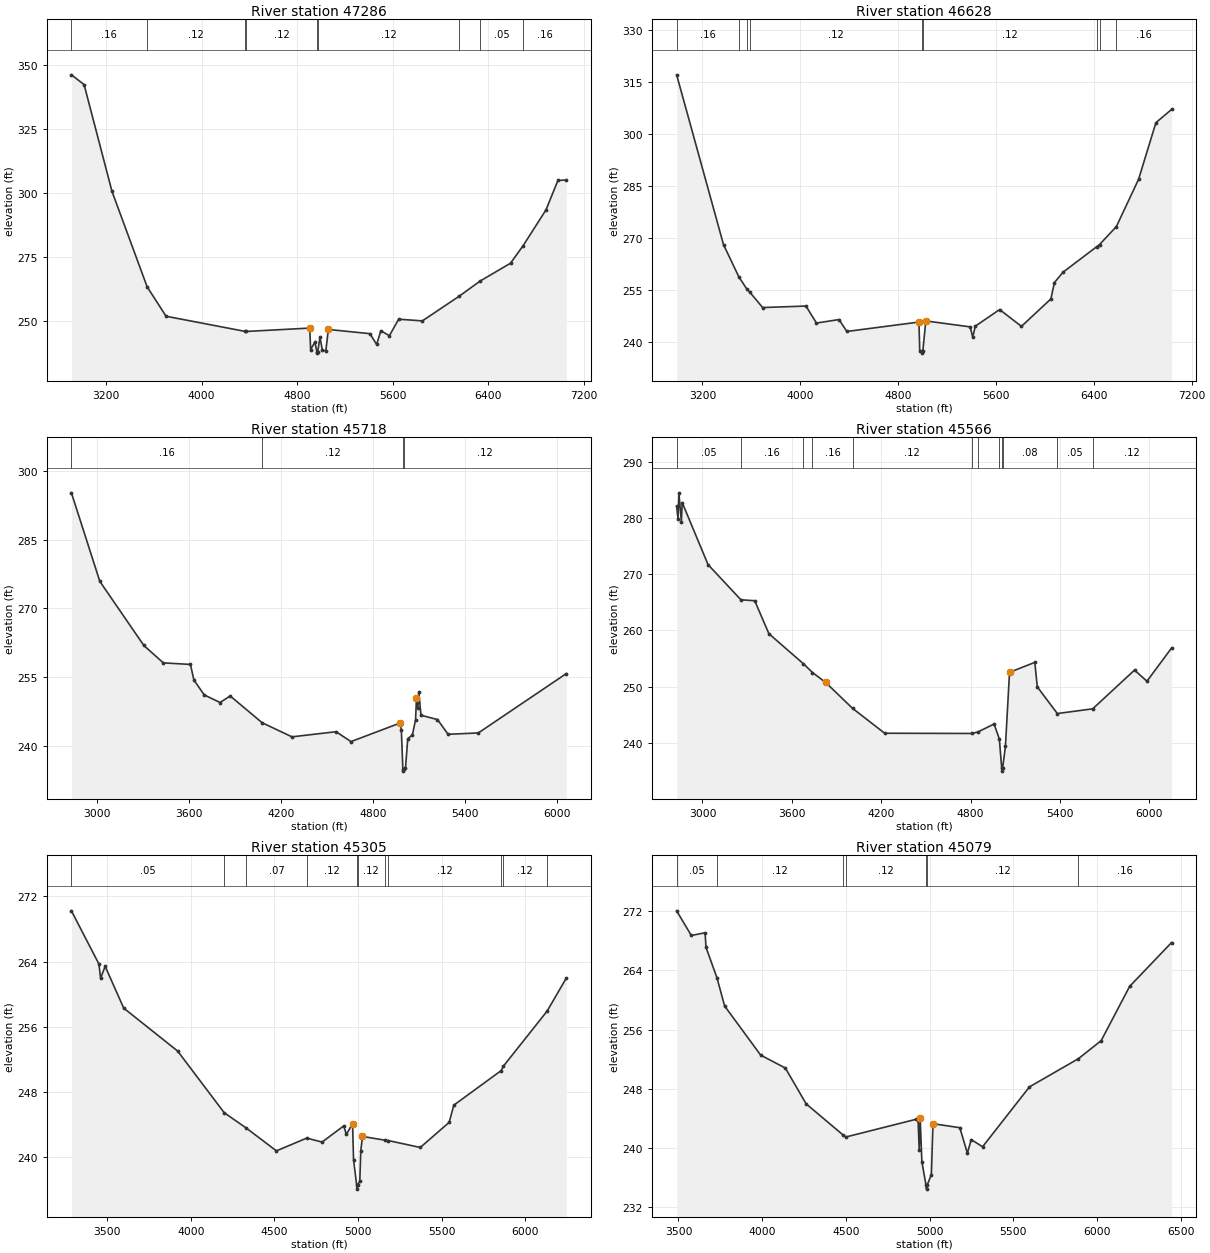
Type RM Length L Ch R = 1 ,47286   ,658,658,658
BEGIN DESCRIPTION:
MANSON CREEK 55.0
END DESCRIPTION:
XS GIS Cut Line= 3
      3759449.62     10581810.18      3758049.61     10583260.19
      3756449.61     10584660.18
#Sta/Elev= 30
  2910.8  346.21  3016.9  342.39  3250.3   300.6  3544.6  263.23    3703  251.73
  4360.5  245.84  4375.5  245.79  4905.2   247.1  4912.4  238.67  4947.7  241.61
  4965.6   237.8  4968.4   237.3  4971.6   237.8  4990.4  243.43  5011.3  238.41
  5039.8  238.21  5060.7  246.56  5408.1  244.92    5465   240.7  5500.1  246.08
  5571.3  244.11  5649.1  250.57  5847.5  249.92  6155.1  259.56  6332.5  265.56
    6585  272.48  6689.9   279.3    6882  293.36  6981.7  304.87  7052.4  305.05
#Mann= 9 ,-1 , 0
  2910.8     .16       0  3544.6     .12       0  4360.5     .07       0
  4375.5     .12       0  4965.6     .07       0  4971.6     .12       0
  6155.1     .16       0  6332.5     .05       0  6689.9     .16       0
Bank Sta=4905.2,5060.7
XS Rating Curve= 0 ,0
Exp/Cntr=0.3,0.1

Type RM Length L Ch R = 1 ,46628   ,910,910,910
BEGIN DESCRIPTION:
MANSON CREEK 54.0
END DESCRIPTION:
XS GIS Cut Line= 3
      3759249.57     10581810.22      3757699.61     10583110.19
      3756399.63     10584660.16
#Sta/Elev= 30
  2989.6  317.15  3372.7  268.09  3497.2  258.85  3563.3  255.24  3585.5  254.43
  3692.7  249.91  4046.7  250.34  4132.4  245.43  4317.2  246.44  4380.9     243
  4970.3  245.72  4976.8  237.38  4995.9  237.24  4998.6  236.74  5001.9  237.24
  5026.2  246.05  5389.2  244.32    5410  241.33  5430.8  244.53  5629.9  249.33
  5808.1  244.47  6048.8  252.41  6077.4  257.11    6148  260.12  6422.7  267.47
  6446.6  268.12    6584   273.3  6765.6  286.96  6907.4  303.33  7035.5  307.16
#Mann= 9 ,-1 , 0
  2989.6     .16       0  3497.2     .12       0  3563.3     .16       0
  3585.5     .12       0  4995.9     .07       0  5001.9     .12       0
  6422.7     .16       0  6446.6     .05       0    6584     .16       0
Bank Sta=4970.3,5026.2
XS Rating Curve= 0 ,0
Exp/Cntr=0.3,0.1

Type RM Length L Ch R = 1 ,45718   ,152,152,152
BEGIN DESCRIPTION:
Mapping XS f9a48b61
END DESCRIPTION:
XS GIS Cut Line= 4
        3759089.     10581789.62      3757338.96     10582699.37
      3757165.34     10582956.31      3756950.08     10583879.88
#Sta/Elev= 30
  2833.2  295.27  3018.6  275.93    3306  261.92  3433.1  258.12  3610.2  257.78
  3632.7  254.37  3700.3  251.12  3803.3  249.46  3869.6  250.89  4078.7  245.03
  4272.8  241.96  4560.3  243.08  4658.3  240.92  4977.8  244.97  4986.8  243.51
  4996.7  234.97  4999.4  234.47  5002.7  234.97  5013.8  235.11  5028.8  241.58
  5058.7  242.35  5079.7   245.7  5085.7  250.54  5094.7  248.18  5100.7  251.82
    5115  246.68  5222.3  245.74  5292.1  242.52  5489.3  242.81    6064  255.79
#Mann= 4 ,-1 , 0
  2833.2     .16       0  4078.7     .12       0  4996.7     .07       0
  5002.7     .12       0
Bank Sta=4977.8,5085.7
XS Rating Curve= 0 ,0
Exp/Cntr=0.3,0.1

Type RM Length L Ch R = 1 ,45566   ,261,261,261
BEGIN DESCRIPTION:
MANSON CREEK 53.0
END DESCRIPTION:
XS GIS Cut Line= 4
      3759019.52     10581699.36       3757220.9      10582595.2
      3757088.96     10582838.26      3756873.68     10583852.13
#Sta/Elev= 30
  2826.9  282.05  2836.2  279.77  2841.8  284.44  2858.6  279.33  2864.2  282.71
  3037.7  271.69  3258.2  265.44  3351.1  265.27  3446.2  259.41  3676.4  254.11
  3738.8  252.52  3826.8  250.76  4007.5  246.16  4223.3  241.73  4807.2  241.69
  4847.8  241.94  4957.8  243.37  4993.1   240.7    5009   235.5  5011.8     235
    5015   235.5  5033.9  239.39  5061.4  252.55  5231.2  254.32  5247.7  249.97
  5382.2  245.23  5619.8  246.07  5900.5  252.95  5983.8  250.97  6149.3  256.88
#Mann= 12 ,-1 , 0
  2826.9     .05       0  3258.2     .16       0  3676.4     .05       0
  3738.8     .16       0  4007.5     .12       0  4807.2     .05       0
  4847.8     .12       0  4993.1     .08       0    5009     .07       0
    5015     .08       0  5382.2     .05       0  5619.8     .12       0
Bank Sta=3826.8,5061.4
XS Rating Curve= 0 ,0
Exp/Cntr=0.3,0.1

Type RM Length L Ch R = 1 ,45305   ,226,226,226
BEGIN DESCRIPTION:
MANSON CREEK 52.0
END DESCRIPTION:
XS GIS Cut Line= 3
      3757894.51     10581018.82      3756957.01     10582650.76
      3756471.14     10583615.57
#Sta/Elev= 30
    3285  270.23  3449.6  263.71  3459.6  261.97    3487  263.42    3598   258.3
  3920.9  253.03  4199.1  245.48  4331.5  243.59  4512.1  240.79  4693.4  242.36
  4785.2  241.87  4914.7  243.85  4930.5  242.81  4967.8  244.14  4973.6  239.71
  4992.2   236.6  4994.9   236.1  4998.2   236.6    5011  237.07  5016.8  240.76
  5026.8  242.56  5162.3   242.1  5180.5  242.06    5373  241.21  5545.9  244.29
  5573.8   246.4  5857.4  250.64  5870.1  251.17    6132  257.93  6247.3  261.99
#Mann= 11 ,-1 , 0
    3285     .05       0  4199.1     .12       0  4331.5     .07       0
  4693.4     .12       0  4992.2     .07       0  4998.2     .12       0
  5162.3     .08       0  5180.5     .12       0  5857.4     .16       0
  5870.1     .12       0    6132     .16       0
Bank Sta=4967.8,5026.8
XS Rating Curve= 0 ,0
Exp/Cntr=0.3,0.1

Type RM Length L Ch R = 1 ,45079   ,474,474,474
BEGIN DESCRIPTION:
Mapping XS c43c6d82
END DESCRIPTION:
XS GIS Cut Line= 2
      3757665.35     10580977.14      3756277.27     10583586.73
#Sta/Elev= 30
    3489  272.08  3576.6  268.74  3658.8  269.11  3664.5  267.12  3729.6  263.02
  3775.6  259.19  3990.8  252.54  4138.1  250.79  4262.8  245.93  4481.6  241.75
  4499.5  241.45  4915.6  243.83  4930.9  243.69  4937.6   239.7  4943.3  243.99
  4953.6  238.09  4978.5  234.89  4981.3  234.39  4984.5  234.89  5010.2  236.37
  5019.8  243.25  5180.1  242.71  5225.4  239.25  5248.1   241.1  5316.1  240.13
  5596.1  248.24    5888  252.05  6024.3   254.5  6194.4  261.85  6444.8  267.79
#Mann= 7 ,-1 , 0
    3489     .05       0  3729.6     .12       0  4481.6     .07       0
  4499.5     .12       0  4978.5     .07       0  4984.5     .12       0
    5888     .16       0
Bank Sta=4943.3,5019.8
XS Rating Curve= 0 ,0
Exp/Cntr=0.3,0.1