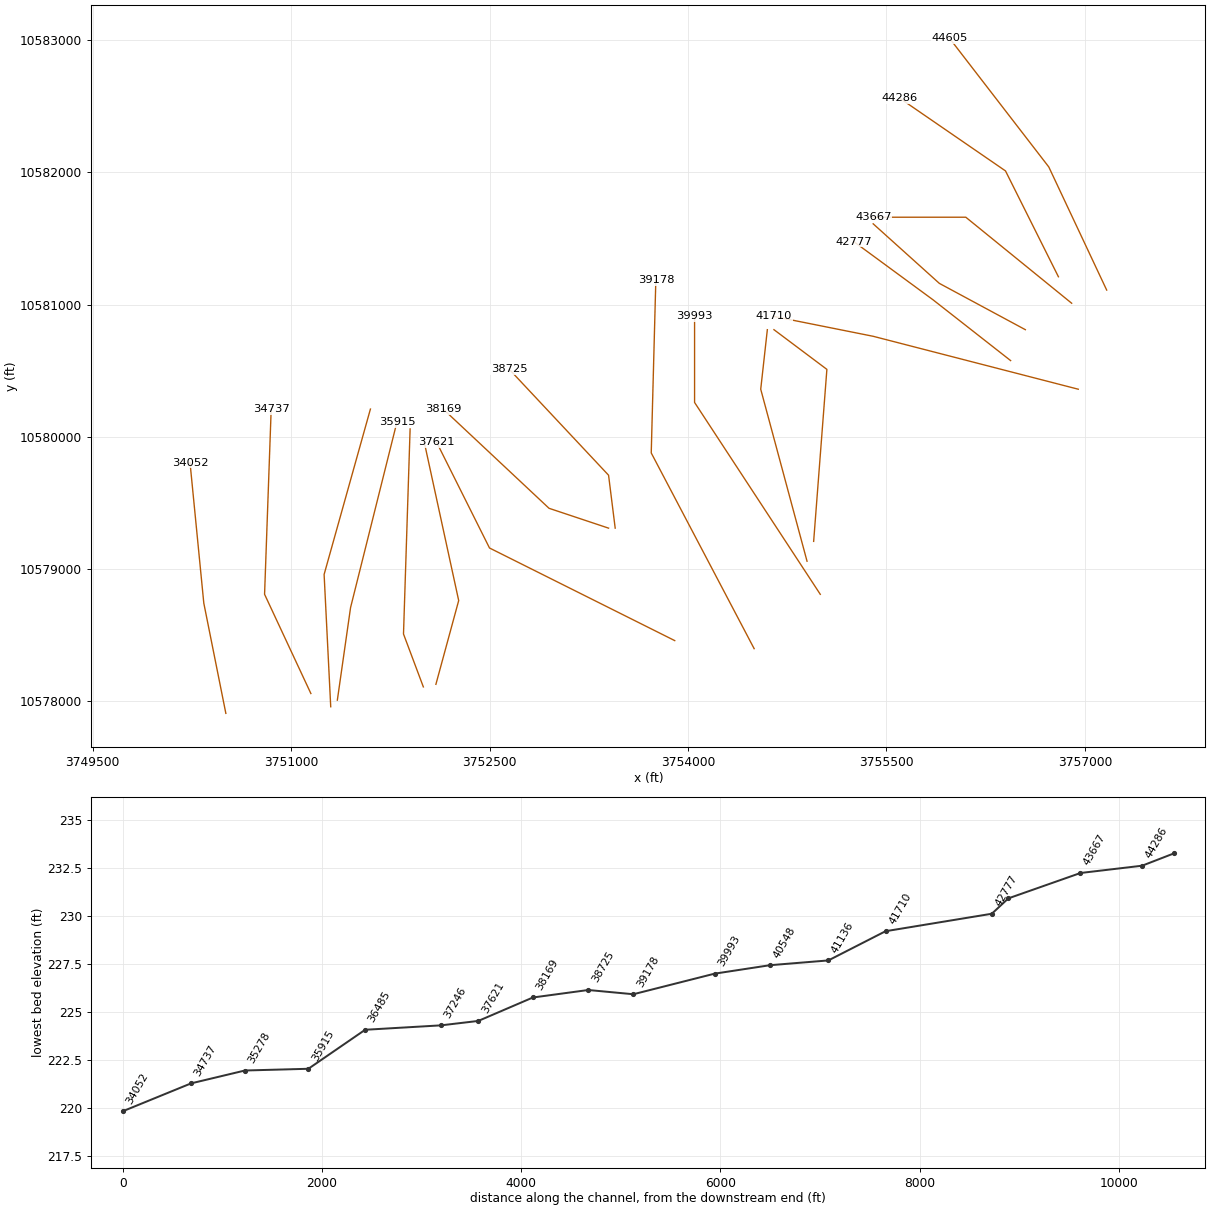
HEC-RAS study MANSON CREEK.prj: MANSON CREEK Base Level Engineering

--- MANSON CREEK.g01 (geometry) --- (continued)

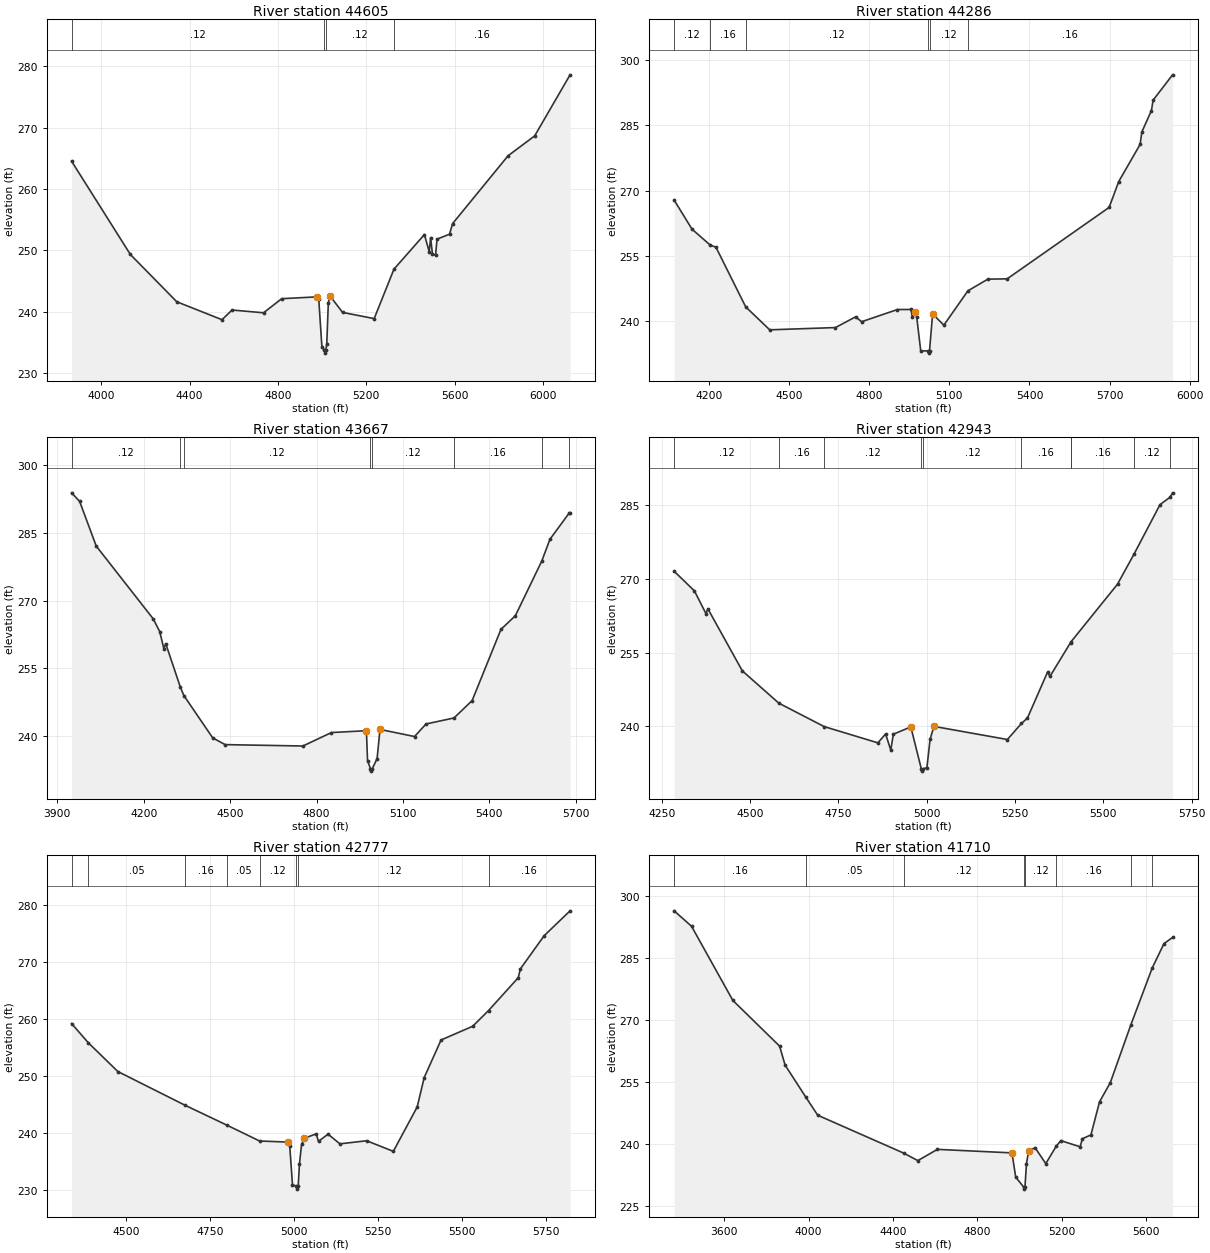
Type RM Length L Ch R = 1 ,44605   ,319,319,319
BEGIN DESCRIPTION:
MANSON CREEK 51.0
END DESCRIPTION:
XS GIS Cut Line= 3
       3757164.4     10581109.48      3756726.92     10582040.01
      3755976.93     10583012.21
#Sta/Elev= 30
  3866.2  264.55  4132.2  249.34  4342.1  241.63  4546.9   238.7  4592.5  240.28
  4734.9  239.83  4817.3  242.13  4978.4  242.43  4984.7  242.14  4999.2  234.22
  5010.7  233.75  5013.5  233.25  5016.7  233.75    5021  234.66  5028.2  241.45
  5034.5  242.64  5092.6  239.89  5235.7  238.88  5325.3  246.95    5463  252.59
  5484.8  249.78  5491.1  252.09  5499.3  249.46  5513.5  249.18  5520.1  251.84
  5576.7  252.65  5590.7  254.38  5841.7  265.44  5962.1  268.68  6122.3  278.64
#Mann= 4 ,-1 , 0
  3866.2     .12       0  5010.7     .07       0  5016.7     .12       0
  5325.3     .16       0
Bank Sta=4978.4,5034.5
XS Rating Curve= 0 ,0
Exp/Cntr=0.3,0.1

Type RM Length L Ch R = 1 ,44286   ,619,619,619
BEGIN DESCRIPTION:
MANSON CREEK 50.0
END DESCRIPTION:
XS GIS Cut Line= 3
      3756799.63     10581210.15      3756399.61     10582010.19
      3755599.61     10582560.19
#Sta/Elev= 30
  4070.3  267.82  4137.4  261.12  4205.4  257.46  4226.9  256.97  4338.2  243.25
  4428.1  237.97  4674.1  238.49  4749.6  240.96  4771.9  239.83  4906.1  242.64
  4956.4  242.65    4962  240.89  4972.2  242.13  4978.3  240.85  4993.2  233.14
    5020  233.11  5022.7  232.61    5026  233.11  5037.6  241.61  5079.8  239.05
  5169.7  246.94  5244.2  249.62  5316.7   249.7  5698.1  266.12    5734  272.06
  5814.2  280.63  5820.6  283.49  5856.4   288.4  5862.8   290.8  5935.6  296.62
#Mann= 6 ,-1 , 0
  4070.3     .12       0  4205.4     .16       0  4338.2     .12       0
    5020     .07       0    5026     .12       0  5169.7     .16       0
Bank Sta=4972.2,5037.6
XS Rating Curve= 0 ,0
Exp/Cntr=0.3,0.1

Type RM Length L Ch R = 1 ,43667   ,724,724,724
BEGIN DESCRIPTION:
MANSON CREEK 49.0
END DESCRIPTION:
XS GIS Cut Line= 3
      3756899.64     10581010.16      3756099.61     10581660.19
      3755399.63     10581660.19
#Sta/Elev= 30
  3949.6  293.84  3977.6  291.94  4035.1  282.06  4233.4  265.91  4255.7   263.1
    4270  259.32  4276.5  260.45  4327.4  250.79  4339.5  248.96  4439.5   239.6
  4482.6   238.1  4752.7  237.79  4851.8  240.77  4973.2  241.18  4977.2  234.58
  4987.4  232.73  4990.2  232.23  4993.4  232.73  5010.4  235.01  5020.4  241.46
  5140.4  239.89  5180.4  242.67  5277.4     244  5340.4  247.85  5440.4  263.61
  5490.4  266.63  5582.5  278.78  5610.4  283.55  5677.2  289.35  5680.4  289.39
#Mann= 8 ,-1 , 0
  3949.6     .12       0  4327.4     .16       0  4339.5     .12       0
  4987.4     .07       0  4993.4     .12       0  5277.4     .16       0
  5582.5     .12       0  5677.2     .16       0
Bank Sta=4973.2,5020.4
XS Rating Curve= 0 ,0
Exp/Cntr=0.3,0.1

Type RM Length L Ch R = 1 ,42943   ,166,166,166
BEGIN DESCRIPTION:
MANSON CREEK 48.0
END DESCRIPTION:
XS GIS Cut Line= 3
      3756549.64     10580810.17      3755899.61     10581160.19
      3755399.58     10581610.22
#Sta/Elev= 30
    4285  271.57  4342.6  267.56  4375.1  262.95  4380.8   263.9  4478.1   251.3
  4581.5  244.73  4709.8  239.97  4861.8  236.66  4883.7  238.47  4898.3  235.19
  4905.6  238.42  4955.1   239.9  4984.6  231.41  4987.3  230.91  4990.6  231.41
  5000.6   231.6  5009.5  237.36  5020.4  240.01  5228.4  237.34  5268.3  240.61
  5285.2  241.71  5342.1  251.06  5348.8  250.16  5407.3  257.06    5408  257.17
  5540.1  268.93  5587.1  275.08  5660.5  285.12  5688.6   286.6    5696  287.51
#Mann= 10 ,-1 , 0
    4285     .12       0  4581.5     .16       0  4709.8     .12       0
  4984.6     .07       0  4990.6     .12       0  5268.3     .16       0
  5407.3     .12       0    5408     .16       0  5587.1     .12       0
  5688.6     .16       0
Bank Sta=4955.1,5020.4
XS Rating Curve= 0 ,0
Exp/Cntr=0.3,0.1

Type RM Length L Ch R = 1 ,42777   ,1067,1067,1067
BEGIN DESCRIPTION:
MANSON CREEK 47.0
END DESCRIPTION:
XS GIS Cut Line= 3
      3756438.31      10580576.6      3755852.14     10581035.77
      3755256.19     10581473.44
#Sta/Elev= 30
  4336.9  259.21  4386.7  255.83  4474.6  250.78  4674.7  244.85  4800.8  241.31
  4896.5  238.57    4980  238.38  4986.4  237.64  4994.5  230.91  5005.5  230.61
  5008.2  230.11  5011.5  230.61  5015.3  234.56  5021.6  237.98  5029.7  239.05
    5065  239.82    5072   238.5  5100.3  239.77  5135.8  238.07  5215.3  238.61
  5294.7  236.75  5365.8  244.55  5386.6  249.71  5436.8  256.32  5530.9  258.73
  5578.3   261.5  5666.7  267.27  5672.9  268.81  5743.9  274.66  5820.9  279.02
#Mann= 8 ,-1 , 0
  4336.9     .16       0  4386.7     .05       0  4674.7     .16       0
  4800.8     .05       0  4896.5     .12       0  5005.5     .07       0
  5011.5     .12       0  5578.3     .16       0
Bank Sta=4980,5029.7
XS Rating Curve= 0 ,0
Exp/Cntr=0.3,0.1

Type RM Length L Ch R = 1 ,41710   ,574,574,574
BEGIN DESCRIPTION:
MANSON CREEK 46.0
END DESCRIPTION:
XS GIS Cut Line= 3
       3756949.6     10580360.19      3755399.61     10580760.19
      3754649.64     10580910.18
#Sta/Elev= 30
  3361.5  296.53  3444.1  292.81  3640.3  274.85  3862.1   263.8  3888.2  259.22
  3987.4  251.38  4043.1  247.08  4451.2  237.91  4518.2   236.1  4611.1  238.82
  4964.8  237.97  4982.7   232.1  5020.5   229.7  5023.2   229.2  5026.5   229.7
  5033.7  235.33  5043.9  238.44  5074.5  239.23  5125.4  235.37  5174.3  239.54
  5196.8  240.94  5288.6  239.43  5298.8  241.39  5339.6  242.32  5380.4  250.32
  5431.4  254.94  5528.9  268.92  5630.6  282.72  5686.3   288.6  5727.1  290.09
#Mann= 8 ,-1 , 0
  3361.5     .16       0  3987.4     .05       0  4451.2     .12       0
  5020.5     .07       0  5026.5     .12       0  5174.3     .16       0
  5528.9     .12       0  5630.6     .16       0
Bank Sta=4964.8,5043.9
XS Rating Curve= 0 ,0
Exp/Cntr=0.3,0.1

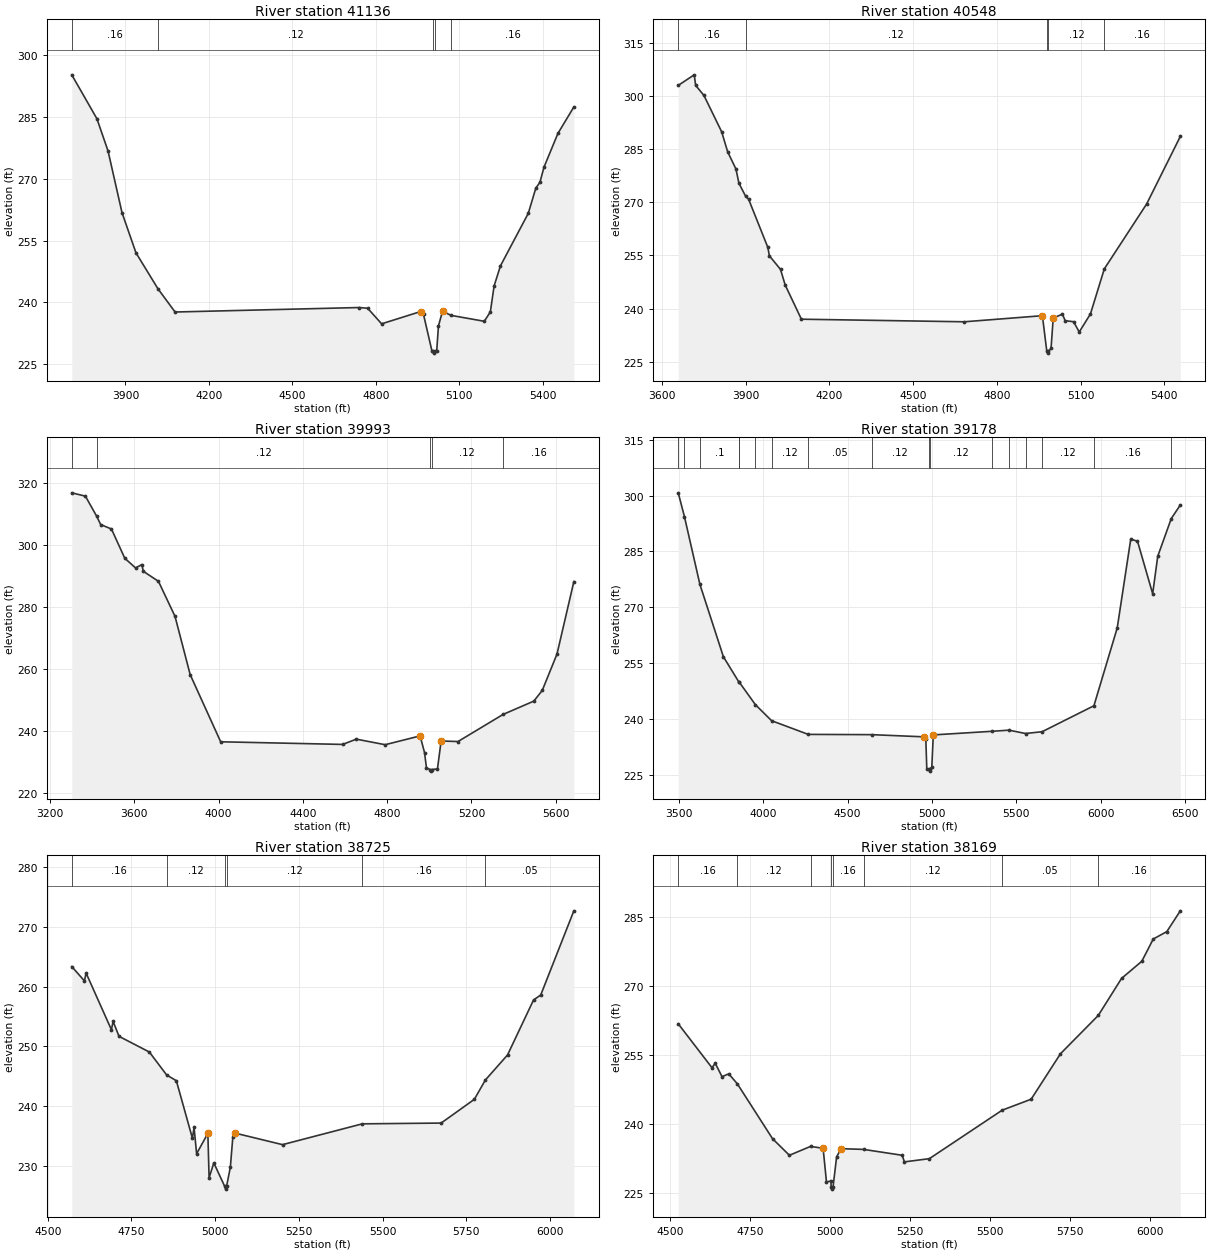
Type RM Length L Ch R = 1 ,41136   ,588,588,588
BEGIN DESCRIPTION:
MANSON CREEK 45.0
END DESCRIPTION:
XS GIS Cut Line= 3
      3754949.61     10579210.15      3755049.61     10580510.19
      3754649.59      10580810.2
#Sta/Elev= 30
  3707.2   295.3  3797.5  284.64  3837.6  276.78  3887.8  261.78  3937.9  252.05
  4016.8  243.32  4078.3  237.67  4740.3  238.76  4770.4  238.58  4820.5   234.8
  4960.9  237.79    4971  237.07    5001  228.28  5005.6  228.18  5008.3  227.68
  5011.6  228.18  5018.4  228.19  5024.6  234.27  5039.2  237.85    5070  236.85
  5189.2  235.42  5211.1  237.68  5224.6     244  5247.5   248.9  5347.5  261.66
  5374.6   267.8  5389.2  269.17  5403.8  272.85  5453.8  281.05  5511.1  287.49
#Mann= 5 ,-1 , 0
  3707.2     .16       0  4016.8     .12       0  5005.6     .07       0
  5011.6     .12       0    5070     .16       0
Bank Sta=4960.9,5039.2
XS Rating Curve= 0 ,0
Exp/Cntr=0.3,0.1

Type RM Length L Ch R = 1 ,40548   ,555,555,555
BEGIN DESCRIPTION:
MANSON CREEK 44.0
END DESCRIPTION:
XS GIS Cut Line= 3
      3754899.61     10579060.18      3754549.61     10580360.19
      3754599.61     10580810.21
#Sta/Elev= 30
  3658.5  302.95  3715.8  305.93    3721  302.94  3750.6  300.12  3813.9   289.9
  3835.7   284.2  3865.3  279.36    3876  275.35  3900.1  271.66  3910.4  270.89
  3979.6  257.25  3985.1  254.88    4025  251.05  4041.7  246.65  4099.8     237
  4683.8  236.27  4963.4  237.99  4979.2  227.93    4982  227.43  4985.2  227.93
  4994.4  228.78  5002.2  237.32    5035  238.43  5045.1  236.58  5075.2  236.29
  5095.4  233.38  5135.6  238.49  5185.3   251.2  5336.8  269.48  5457.6  288.55
#Mann= 5 ,-1 , 0
  3658.5     .16       0  3900.1     .12       0  4979.2     .07       0
  4985.2     .12       0  5185.3     .16       0
Bank Sta=4963.4,5002.2
XS Rating Curve= 0 ,0
Exp/Cntr=0.3,0.1

Type RM Length L Ch R = 1 ,39993   ,815,815,815
BEGIN DESCRIPTION:
MANSON CREEK 43.0
END DESCRIPTION:
XS GIS Cut Line= 3
      3754999.61     10578810.19      3754049.61     10580260.19
      3754049.61      10580910.2
#Sta/Elev= 30
  3302.6  316.81  3367.4  315.73  3420.1  309.34  3439.8  306.58    3491  305.13
  3554.3  295.69  3605.6  292.57  3635.8  293.67  3641.7  291.51  3714.1  288.25
  3792.8  276.93  3864.8  258.12  4009.5  236.46  4588.4  235.61  4653.5  237.31
  4790.4  235.52  4956.2  238.36  4977.3  232.97  4986.4  228.06  5004.5  227.49
  5007.2  226.99  5010.5  227.49  5038.6  227.71  5056.1  236.72  5136.1  236.54
  5349.9  245.28  5496.1  249.59  5536.1  253.03  5606.1  264.77  5686.1  288.16
#Mann= 5 ,-1 , 0
  3302.6     .16       0  3420.1     .12       0  5004.5     .07       0
  5010.5     .12       0  5349.9     .16       0
Bank Sta=4956.2,5056.1
XS Rating Curve= 0 ,0
Exp/Cntr=0.3,0.1

Type RM Length L Ch R = 1 ,39178   ,453,453,453
BEGIN DESCRIPTION:
MANSON CREEK 42.0
END DESCRIPTION:
XS GIS Cut Line= 3
      3754499.84      10578399.3      3753722.06     10579878.48
      3753756.78     10581184.02
#Sta/Elev= 30
  3495.4  300.77  3532.1  294.38  3623.9  276.14  3763.2  256.68  3854.6  249.92
    3858   249.8  3952.8   243.8  4049.1  239.48  4266.3   235.8  4642.3  235.73
  4953.9  235.14  4963.6  234.51  4969.3  226.49  4982.7  226.42  4985.4  225.92
  4988.7  226.42  4999.1     227  5007.7  235.66  5358.4  236.64  5456.6  236.94
  5554.8  236.04    5653  236.52  5960.3   243.5  6098.6  264.44  6178.7   288.3
  6218.7  287.76  6308.7  273.63  6338.7   283.7  6419.1  293.86  6472.6  297.49
#Mann= 17 ,-1 , 0
  3495.4      .1       0  3532.1     .12       0  3623.9      .1       0
  3854.6     .16       0    3858     .12       0  3952.8     .16       0
  4049.1     .12       0  4266.3     .05       0  4642.3     .12       0
  4982.7     .07       0  4988.7     .12       0  5358.4     .16       0
  5456.6     .12       0  5554.8     .16       0    5653     .12       0
  5960.3     .16       0  6419.1     .12       0
Bank Sta=4953.9,5007.7
XS Rating Curve= 0 ,0
Exp/Cntr=0.3,0.1

Type RM Length L Ch R = 1 ,38725   ,556,556,556
BEGIN DESCRIPTION:
MANSON CREEK 41.0
END DESCRIPTION:
XS GIS Cut Line= 3
      3753449.61     10579310.21      3753399.61     10579710.19
      3752649.59     10580510.21
#Sta/Elev= 30
  4571.8  263.37  4609.6  260.97  4614.6  262.28  4690.2   252.8  4695.2   254.2
  4712.9   251.7  4803.6  249.07  4855.1  245.24  4884.2  244.27  4932.1  234.66
  4937.1  236.45  4944.7  232.06  4978.3  235.47    4982  228.04  4996.1  230.52
  5028.3  226.64  5031.1  226.14  5034.3  226.64  5045.5  229.81  5052.8  234.79
  5059.6  235.51  5201.3  233.58  5439.6  237.06  5675.1  237.19  5774.3  241.16
  5807.3   244.4  5873.4  248.58  5951.1  257.78  5972.6  258.61  6071.5  272.69
#Mann= 6 ,-1 , 0
  4571.8     .16       0  4855.1     .12       0  5028.3     .07       0
  5034.3     .12       0  5439.6     .16       0  5807.3     .05       0
Bank Sta=4978.3,5059.6
XS Rating Curve= 0 ,0
Exp/Cntr=0.3,0.1

Type RM Length L Ch R = 1 ,38169   ,548,548,548
BEGIN DESCRIPTION:
MANSON CREEK 40.0
END DESCRIPTION:
XS GIS Cut Line= 3
       3753399.6     10579310.19      3752949.61     10579460.19
      3752149.63     10580210.17
#Sta/Elev= 30
  4524.8  261.79  4630.2  252.23  4640.7  253.16  4661.8  250.27  4682.9  250.88
  4709.8   248.7  4819.9  236.74  4872.6  233.13  4938.7  235.06  4978.1  234.65
  4988.6  227.32  5002.6  227.53  5003.2  226.25    5006  225.75  5009.2  226.25
  5020.4   232.8  5034.5  234.57  5104.8  234.41  5225.5  233.13  5232.4  231.69
  5310.5  232.39  5538.3  242.96    5629  245.35  5720.8  255.27  5839.1  263.62
  5911.8  271.68  5975.3  275.43    6011  280.27  6053.5  281.89  6095.7  286.42
#Mann= 8 ,-1 , 0
  4524.8     .16       0  4709.8     .12       0  4938.7     .16       0
  5003.2     .07       0  5009.2     .16       0  5104.8     .12       0
  5538.3     .05       0  5839.1     .16       0
Bank Sta=4978.1,5034.5
XS Rating Curve= 0 ,0
Exp/Cntr=0.3,0.1

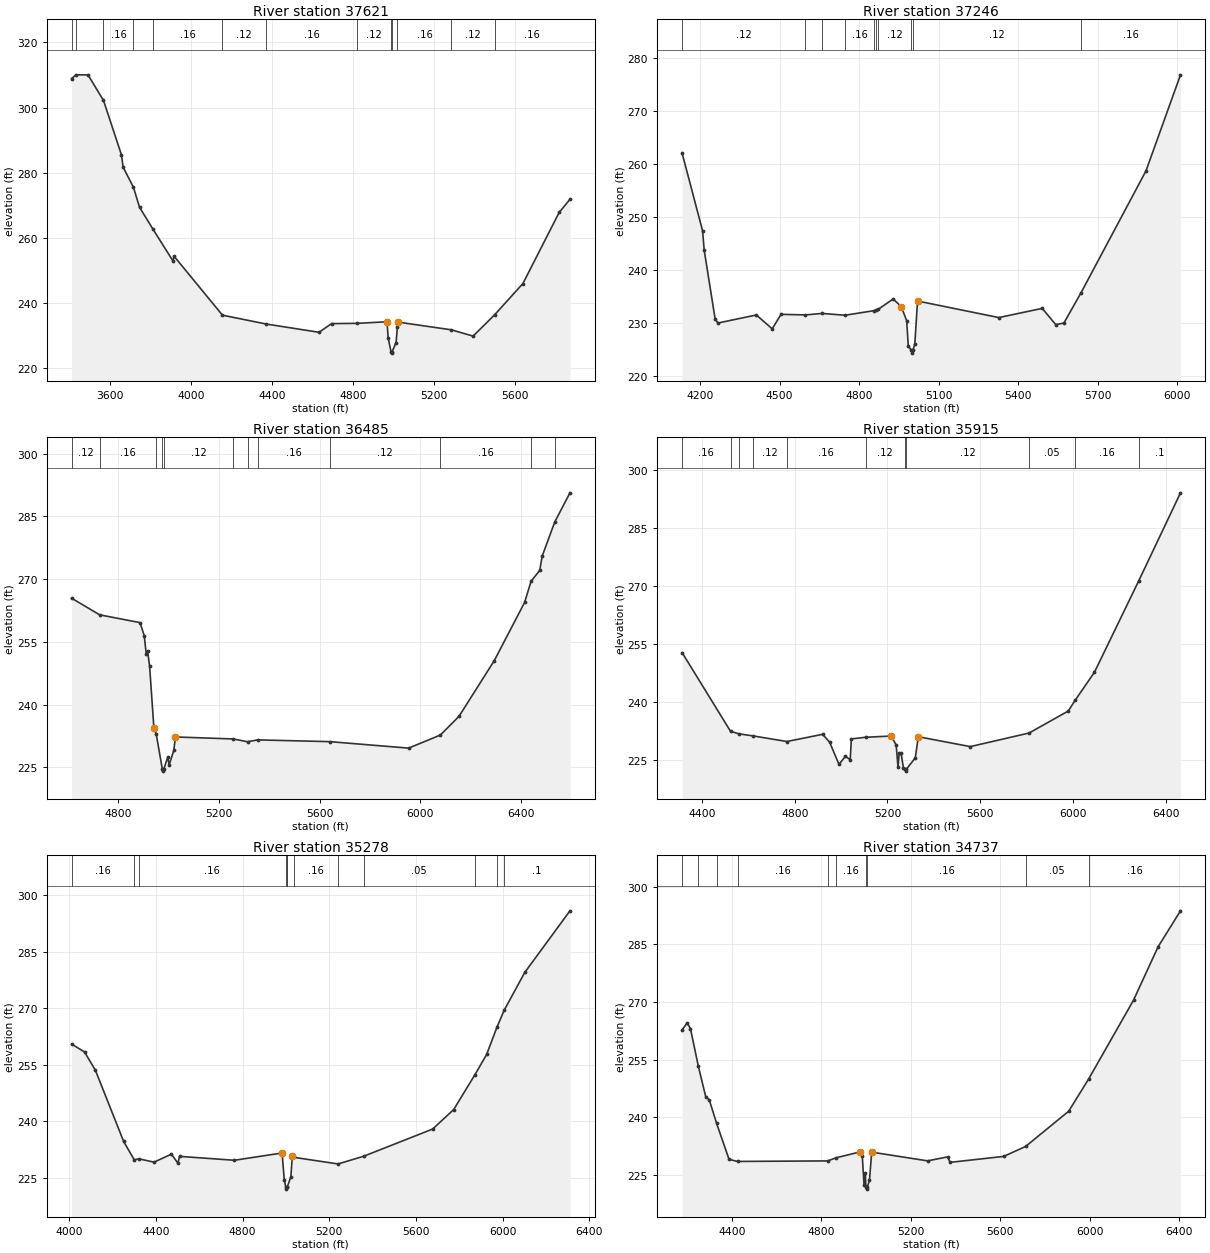
Type RM Length L Ch R = 1 ,37621   ,375,375,375
BEGIN DESCRIPTION:
MANSON CREEK 39.0
END DESCRIPTION:
XS GIS Cut Line= 3
      3753899.64     10578460.18      3752499.61     10579160.19
      3752099.61     10579960.18
#Sta/Elev= 30
  3411.9   308.9  3434.2  310.04    3493  310.01  3569.4  302.17  3657.9  285.48
  3666.3  281.65  3717.3  275.48  3747.3  269.34  3813.4  262.64  3912.2  252.86
  3917.8   254.3  4156.6  236.19  4371.9  233.48  4633.4  230.93  4694.9   233.6
  4822.6  233.68  4968.8  234.17  4974.4  229.22  4988.2  225.03  4990.9  224.53
  4994.2  225.03  5013.5  227.76  5019.9  232.57  5021.9  234.07  5286.6  231.69
  5393.6  229.75  5500.7  236.36  5639.6  245.92  5818.5  267.76  5871.6  271.78
#Mann= 13 ,-1 , 0
  3411.9     .16       0  3434.2     .12       0  3569.4     .16       0
  3717.3     .12       0  3813.4     .16       0  4156.6     .12       0
  4371.9     .16       0  4822.6     .12       0  4988.2     .07       0
  4994.2     .12       0  5019.9     .16       0  5286.6     .12       0
  5500.7     .16       0
Bank Sta=4968.8,5021.9
XS Rating Curve= 0 ,0
Exp/Cntr=0.3,0.1

Type RM Length L Ch R = 1 ,37246   ,761,761,761
BEGIN DESCRIPTION:
MANSON CREEK 38.0
END DESCRIPTION:
XS GIS Cut Line= 3
      3752094.57     10578129.92       3752266.8     10578762.76
      3752006.46     10579960.33
#Sta/Elev= 30
  4131.9  261.96  4209.1  247.34  4215.1  243.72  4256.5  230.72  4266.9  229.97
    4412  231.49  4471.9  228.88  4505.3  231.61  4597.5   231.5    4660  231.78
  4747.2  231.44  4857.2  232.31  4863.4  232.42  4872.9  232.58  4928.4   234.5
  4959.1  233.07  4979.6   230.4  4985.5  225.73    4997   224.8  4999.8   224.3
    5003   224.8  5010.3  226.04  5020.5  234.12  5327.5     231  5491.2  232.73
  5542.4  229.67  5573.1  229.97  5637.8  235.68    5883  258.64  6013.3  276.74
#Mann= 10 ,-1 , 0
  4131.9     .12       0  4597.5     .16       0    4660     .12       0
  4747.2     .16       0  4857.2     .12       0  4863.4     .16       0
  4872.9     .12       0    4997     .07       0    5003     .12       0
  5637.8     .16       0
Bank Sta=4959.1,5020.5
XS Rating Curve= 0 ,0
Exp/Cntr=0.3,0.1

Type RM Length L Ch R = 1 ,36485   ,570,570,570
BEGIN DESCRIPTION:
MANSON CREEK 37.0
END DESCRIPTION:
XS GIS Cut Line= 3
      3751999.62     10578110.17      3751849.61     10578510.19
      3751899.61     10580060.16
#Sta/Elev= 30
  4615.6  265.42  4727.1  261.44  4887.1  259.58    4904  256.47    4912  252.02
  4917.3  252.83  4925.3  249.15  4942.3  234.38  4951.5  232.94  4975.7  224.57
  4978.5  224.07  4981.7  224.57  4997.4  227.43  5002.8  225.56  5021.5  229.06
  5027.7  232.24  5257.8  231.76    5314  231.09  5354.1  231.54    5640  231.12
  5953.3  229.57  6079.2  232.69  6153.4  237.18  6293.5  250.51  6413.5  264.39
  6439.7  269.51  6473.6  272.04  6483.6   275.5  6533.2  283.62  6593.6  290.61
#Mann= 12 ,-1 , 0
  4615.6     .12       0  4727.1     .16       0  4951.5     .12       0
  4975.7     .07       0  4981.7     .12       0  5257.8     .16       0
    5314     .12       0  5354.1     .16       0    5640     .12       0
  6079.2     .16       0  6439.7      .1       0  6533.2     .05       0
Bank Sta=4942.3,5027.7
XS Rating Curve= 0 ,0
Exp/Cntr=0.3,0.1

Type RM Length L Ch R = 1 ,35915   ,637,637,637
BEGIN DESCRIPTION:
MANSON CREEK 36.0
END DESCRIPTION:
XS GIS Cut Line= 3
      3751349.61     10578010.21      3751449.61     10578710.19
      3751799.62     10580110.21
#Sta/Elev= 30
  4314.4  252.71  4523.1  232.36  4558.8   231.7  4620.2  231.16  4766.3  229.71
  4920.5  231.57  4950.8  229.53  4991.2  223.78    5019  225.91  5039.5  224.98
  5044.7  230.38    5106  230.81  5217.3  231.13  5237.9  228.74  5245.7  223.12
  5250.8  226.67  5258.6  226.78  5268.9  222.97  5276.2  222.54  5278.9  222.04
  5282.2  222.54  5320.4  225.49  5333.3  230.95  5557.5  228.39    5811   231.9
  5980.1  237.59  6010.6  240.43  6093.5  247.67  6283.5   271.2  6464.6   294.1
#Mann= 11 ,-1 , 0
  4314.4     .16       0  4523.1     .12       0  4558.8     .16       0
  4620.2     .12       0  4766.3     .16       0    5106     .12       0
  5276.2     .07       0  5282.2     .12       0    5811     .05       0
  6010.6     .16       0  6283.5      .1       0
Bank Sta=5217.3,5333.3
XS Rating Curve= 0 ,0
Exp/Cntr=0.3,0.1

Type RM Length L Ch R = 1 ,35278   ,541,541,541
BEGIN DESCRIPTION:
MANSON CREEK 35.0
END DESCRIPTION:
XS GIS Cut Line= 3
      3751299.61     10577960.15      3751249.61     10578960.19
      3751599.62     10580210.23
#Sta/Elev= 30
  4011.3  260.45  4071.4  258.33  4121.5  253.45  4251.6  234.59  4300.6  229.71
  4321.8  229.99  4391.8  229.11  4471.9  231.23  4501.9  228.84  4509.5  230.64
  4762.3  229.61  4982.5  231.54  4992.6  224.46  4999.6  222.45  5002.3  221.95
  5005.6  222.45  5006.6  222.55    5023  225.21  5029.6  230.61  5037.7  230.38
    5241  228.63  5359.1  230.68  5677.2  237.89  5774.4  243.07  5871.8  252.26
  5926.4  257.69  5974.8  265.04  6007.8  269.48  6102.2  279.44  6310.7   295.8
#Mann= 12 ,-1 , 0
  4011.3     .16       0  4300.6     .12       0  4321.8     .16       0
  4999.6     .07       0  5005.6     .16       0  5006.6     .12       0
  5037.7     .16       0    5241     .12       0  5359.1     .05       0
  5871.8      .1       0  5974.8     .16       0  6007.8      .1       0
Bank Sta=4982.5,5029.6
XS Rating Curve= 0 ,0
Exp/Cntr=0.3,0.1

Type RM Length L Ch R = 1 ,34737   ,685,685,685
BEGIN DESCRIPTION:
MANSON CREEK 34.0
END DESCRIPTION:
XS GIS Cut Line= 3
      3751149.61     10578060.18      3750799.61     10578810.19
      3750849.61     10580210.14
#Sta/Elev= 30
  4176.9  262.76    4199  264.56    4214   263.1  4248.9  253.39  4282.5  245.31
  4298.3  244.51  4330.7  238.46  4386.6  229.03  4424.9  228.49  4827.7  228.63
    4866  229.45    4973  230.98  4982.5  229.83  4990.4  222.35  4995.9   225.5
  4998.8  221.78  5001.5  221.28  5004.8  221.78  5014.6  223.66  5024.6  230.91
  5274.7  228.64  5364.8  229.69  5374.8  228.25  5614.9   229.8  5712.7  232.39
  5905.1  241.55  5995.1     250  6195.3  270.48  6305.4  284.41  6405.4  293.75
#Mann= 10 ,-1 , 0
  4176.9     .05       0  4248.9     .16       0  4330.7     .12       0
  4424.9     .16       0  4827.7     .12       0    4866     .16       0
  4998.8     .07       0  5004.8     .16       0  5712.7     .05       0
  5995.1     .16       0
Bank Sta=4973,5024.6
XS Rating Curve= 0 ,0
Exp/Cntr=0.3,0.1

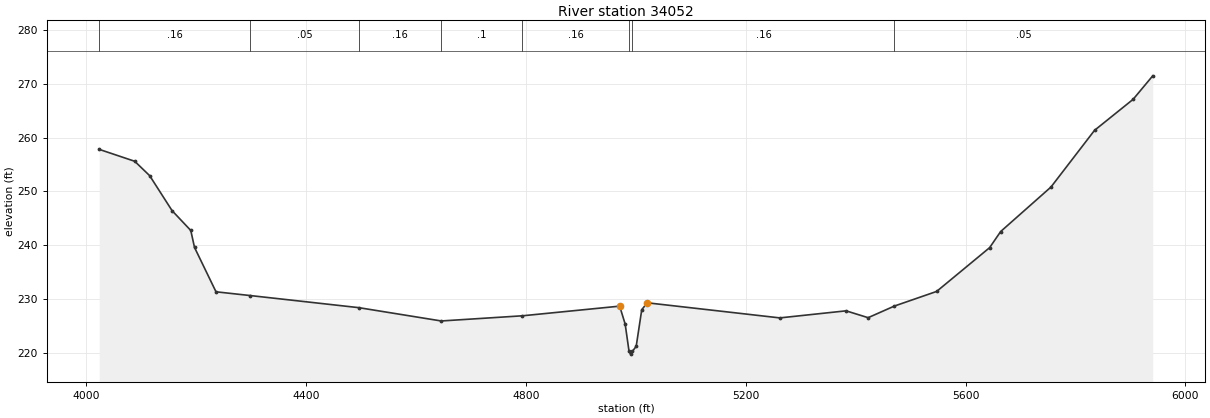
Type RM Length L Ch R = 1 ,34052   ,540,540,540
BEGIN DESCRIPTION:
MANSON CREEK 33.0
END DESCRIPTION:
XS GIS Cut Line= 3
      3750506.94     10577910.17      3750340.29     10578743.45
      3750236.16     10579805.57
#Sta/Elev= 30
  4023.7  257.81  4088.3   255.6  4115.5  252.93  4156.3  246.44  4190.3  242.77
  4197.1  239.62  4236.2  231.39    4298   230.7    4496  228.45  4646.1  225.98
  4793.8  226.94  4970.7  228.73  4980.7  225.42  4987.8  220.33  4990.5  219.83
  4993.8  220.33  5000.8  221.28  5010.9  228.07  5020.9  229.35  5262.1  226.55
  5382.7  227.86  5422.8  226.59  5470.7  228.75  5547.5  231.46  5643.9  239.58
    5664  242.57  5755.5  250.82  5834.8  261.34  5905.1   267.1  5940.7  271.45
#Mann= 8 ,-1 , 0
  4023.7     .16       0    4298     .05       0    4496     .16       0
  4646.1      .1       0  4793.8     .16       0  4987.8     .07       0
  4993.8     .16       0  5470.7     .05       0
Bank Sta=4970.7,5020.9
XS Rating Curve= 0 ,0
Exp/Cntr=0.3,0.1