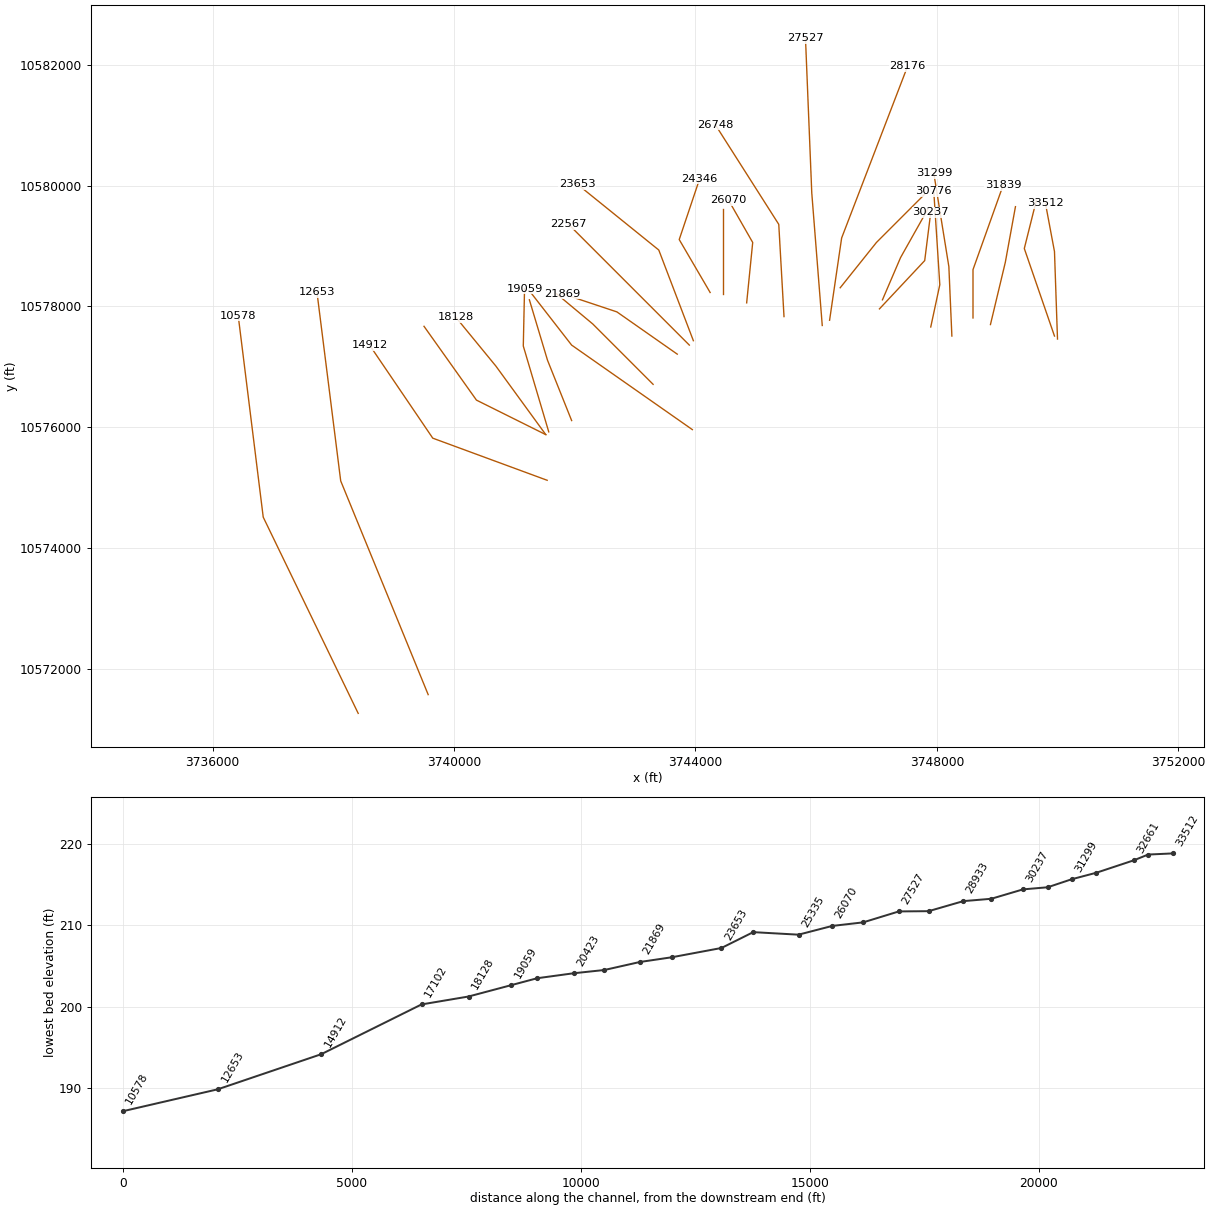
HEC-RAS study MANSON CREEK.prj: MANSON CREEK Base Level Engineering

--- MANSON CREEK.g01 (geometry) --- (continued)

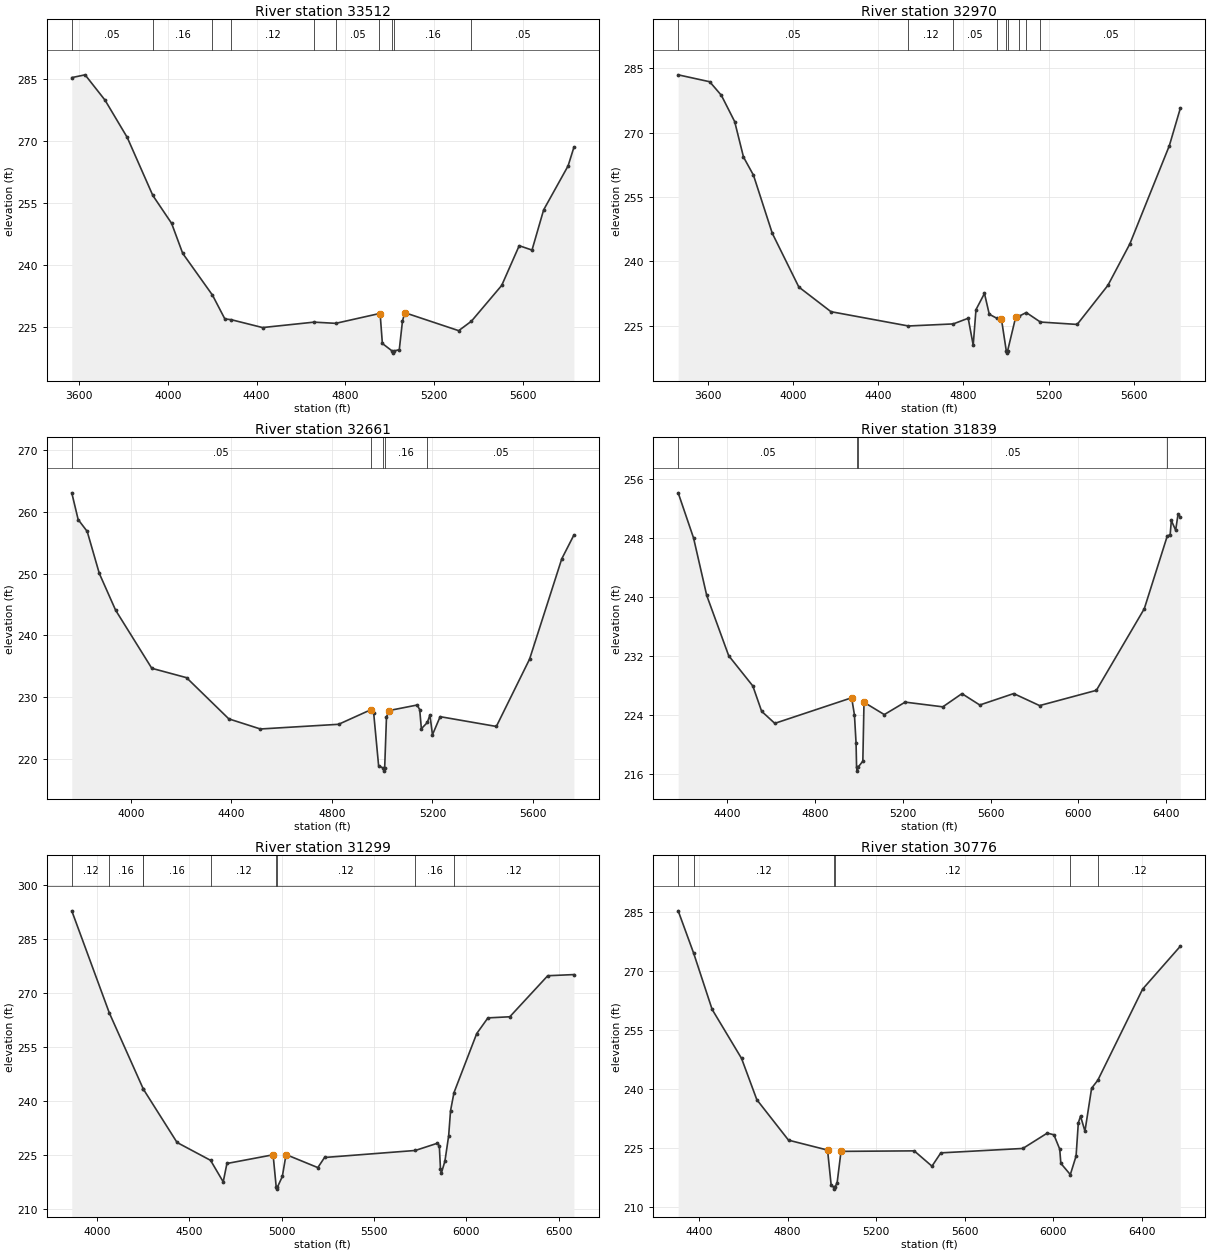
Type RM Length L Ch R = 1 ,33512   ,542,542,542
BEGIN DESCRIPTION:
MANSON CREEK 32.0
END DESCRIPTION:
XS GIS Cut Line= 3
      3749999.61     10577460.17      3749949.61     10578910.19
      3749799.61     10579710.17
#Sta/Elev= 30
  3566.8   285.4  3626.9  286.07  3716.9  279.94    3817  270.93  3932.4  256.91
  4017.1  250.17  4067.1  242.92  4201.4  232.82  4257.2  227.07  4286.2  226.88
  4427.3  224.98  4659.4  226.29  4757.4     226  4953.4  228.36  4957.6  228.33
  4967.7  221.13  5012.2   219.3  5014.9   218.8  5018.2   219.3    5044  219.63
  5058.4  226.55  5068.6  228.58  5311.9  224.23  5369.4  226.52    5506  235.17
  5584.9  244.77  5642.6  243.71  5695.1  253.43  5805.3  264.05  5831.6  268.55
#Mann= 10 ,-1 , 0
  3566.8     .05       0  3932.4     .16       0  4201.4     .05       0
  4286.2     .12       0  4659.4      .1       0  4757.4     .05       0
  4953.4     .16       0  5012.2     .07       0  5018.2     .16       0
  5369.4     .05       0
Bank Sta=4957.6,5068.6
XS Rating Curve= 0 ,0
Exp/Cntr=0.3,0.1

Type RM Length L Ch R = 1 ,32970   ,309,309,309
BEGIN DESCRIPTION:
MANSON CREEK 31.0
END DESCRIPTION:
XS GIS Cut Line= 3
      3749949.61     10577510.17      3749449.61     10578960.19
       3749649.6     10579760.17
#Sta/Elev= 30
  3460.2  283.45  3608.3  281.84    3663  278.68  3725.5  272.57    3767  264.31
  3813.8  260.09  3902.1  246.57  4026.9  234.05  4177.7  228.31  4541.6  224.98
  4752.2  225.46  4822.4  226.78  4845.9  220.51  4858.9  228.78  4898.8  232.56
  4921.3  227.72    4957  226.77  4978.4  226.63  5001.3  219.16  5004.1  218.66
  5007.3  219.16  5045.5  227.05  5061.5  227.26  5095.1  228.11  5161.3   225.9
  5334.2  225.34  5478.5  234.44  5581.5  244.08  5767.1  266.96  5818.6  275.65
#Mann= 9 ,-1 , 0
  3460.2     .05       0  4541.6     .12       0  4752.2     .05       0
    4957     .16       0  5001.3     .07       0  5007.3     .16       0
  5061.5     .05       0  5095.1     .16       0  5161.3     .05       0
Bank Sta=4978.4,5045.5
XS Rating Curve= 0 ,0
Exp/Cntr=0.3,0.1

Type RM Length L Ch R = 1 ,32661   ,822,822,822
BEGIN DESCRIPTION:
MANSON CREEK 30.0
END DESCRIPTION:
XS GIS Cut Line= 3
      3748888.68     10577700.57      3749134.87     10578730.46
      3749303.09     10579653.65
#Sta/Elev= 30
  3765.4  263.13  3790.8  258.79  3826.7  256.87    3875  250.04  3939.8  244.08
  4083.7  234.65  4221.8  233.13  4390.1  226.44  4515.6   224.8  4826.7  225.56
  4954.7  227.92  4956.2  227.91  4966.3  227.37  4985.9  218.84    5004  218.46
  5006.7  217.96    5010  218.46  5017.2  226.73  5027.3  227.79  5139.1  228.69
  5149.3  227.94    5156  224.84  5179.7  225.86    5190  227.08  5200.1  223.86
  5230.6   226.8  5454.2  225.21  5586.4  236.14  5714.4  252.42  5762.7  256.28
#Mann= 5 ,-1 , 0
  3765.4     .05       0  4954.7     .16       0    5004     .07       0
    5010     .16       0  5179.7     .05       0
Bank Sta=4956.2,5027.3
XS Rating Curve= 0 ,0
Exp/Cntr=0.3,0.1

Type RM Length L Ch R = 1 ,31839   ,540,540,540
BEGIN DESCRIPTION:
MANSON CREEK 29.0
END DESCRIPTION:
XS GIS Cut Line= 3
      3748599.61     10577810.16      3748599.61     10578610.19
       3749099.6     10580010.16
#Sta/Elev= 30
  4177.3  254.18  4247.3  248.06  4307.3  240.26  4407.3  232.09  4517.3  227.98
  4557.3  224.55  4617.3  222.91  4967.3  226.38    4980  224.05  4987.4  220.21
  4989.7  216.93  4992.5  216.43  4995.7  216.93  5018.2  217.78  5023.5  225.77
  5115.9   224.1  5210.9  225.79  5382.4  225.15  5469.5  226.94  5550.7   225.4
  5705.2  226.95  5823.1  225.32  6081.7  227.39  6299.9  238.46  6404.6  248.33
  6417.7   248.5  6423.1  250.43  6442.7  249.11  6453.8  251.31  6463.9  250.89
#Mann= 4 ,-1 , 0
  4177.3     .05       0  4989.7     .03       0  4995.7     .05       0
  6404.6     .16       0
Bank Sta=4967.3,5023.5
XS Rating Curve= 0 ,0
Exp/Cntr=0.3,0.1

Type RM Length L Ch R = 1 ,31299   ,523,523,523
BEGIN DESCRIPTION:
MANSON CREEK 28.0
END DESCRIPTION:
XS GIS Cut Line= 3
      3748249.61     10577510.22      3748199.61     10578660.19
      3747949.61      10580210.2
#Sta/Elev= 30
  3862.2  292.94  4065.6  264.59  4249.4  243.49  4250.4  243.38  4432.7  228.59
  4614.3  223.63  4682.9  217.65    4703  222.75  4953.2  225.17  4970.2  216.13
    4973  215.63  4976.2  216.13  5003.2  219.14  5023.4  225.23  5195.6  221.61
    5232  224.42  5723.8  226.37  5843.9  228.38    5854  227.65  5860.1  221.35
  5865.1  220.08  5884.4  223.42  5904.6  230.45  5914.8  237.41  5933.4  242.43
  6056.6  258.84  6117.3   263.2  6235.9  263.51  6441.5  274.91  6583.3  275.23
#Mann= 9 ,-1 , 0
  3862.2     .12       0  4065.6     .16       0  4249.4     .12       0
  4250.4     .16       0  4614.3     .12       0  4970.2     .07       0
  4976.2     .12       0  5723.8     .16       0  5933.4     .12       0
Bank Sta=4953.2,5023.4
XS Rating Curve= 0 ,0
Exp/Cntr=0.3,0.1

Type RM Length L Ch R = 1 ,30776   ,539,539,539
BEGIN DESCRIPTION:
MANSON CREEK 27.0
END DESCRIPTION:
XS GIS Cut Line= 3
      3747899.61     10577660.19      3748049.61     10578360.19
      3747949.61     10579910.18
#Sta/Elev= 30
  4305.6  285.19  4375.8  274.41    4459  260.21    4592  247.78    4661  237.32
  4804.2  227.06  4980.6  224.55  4996.8  215.73  5008.3  215.15    5011  214.65
  5014.3  215.15    5024   216.3  5041.5  224.22  5372.2  224.35  5452.4  220.47
  5492.5  223.84  5863.2  224.96  5973.5  228.85  6003.5  228.42  6029.8  224.79
  6034.8  221.19  6077.7  218.33  6103.7  223.04  6113.8  231.45  6123.8  233.15
  6143.8  229.34  6173.9  240.23    6202  242.26  6404.4  265.35  6574.7  276.21
#Mann= 6 ,-1 , 0
  4305.6     .16       0  4375.8     .12       0  5008.3     .07       0
  5014.3     .12       0  6077.7     .16       0    6202     .12       0
Bank Sta=4980.6,5041.5
XS Rating Curve= 0 ,0
Exp/Cntr=0.3,0.1

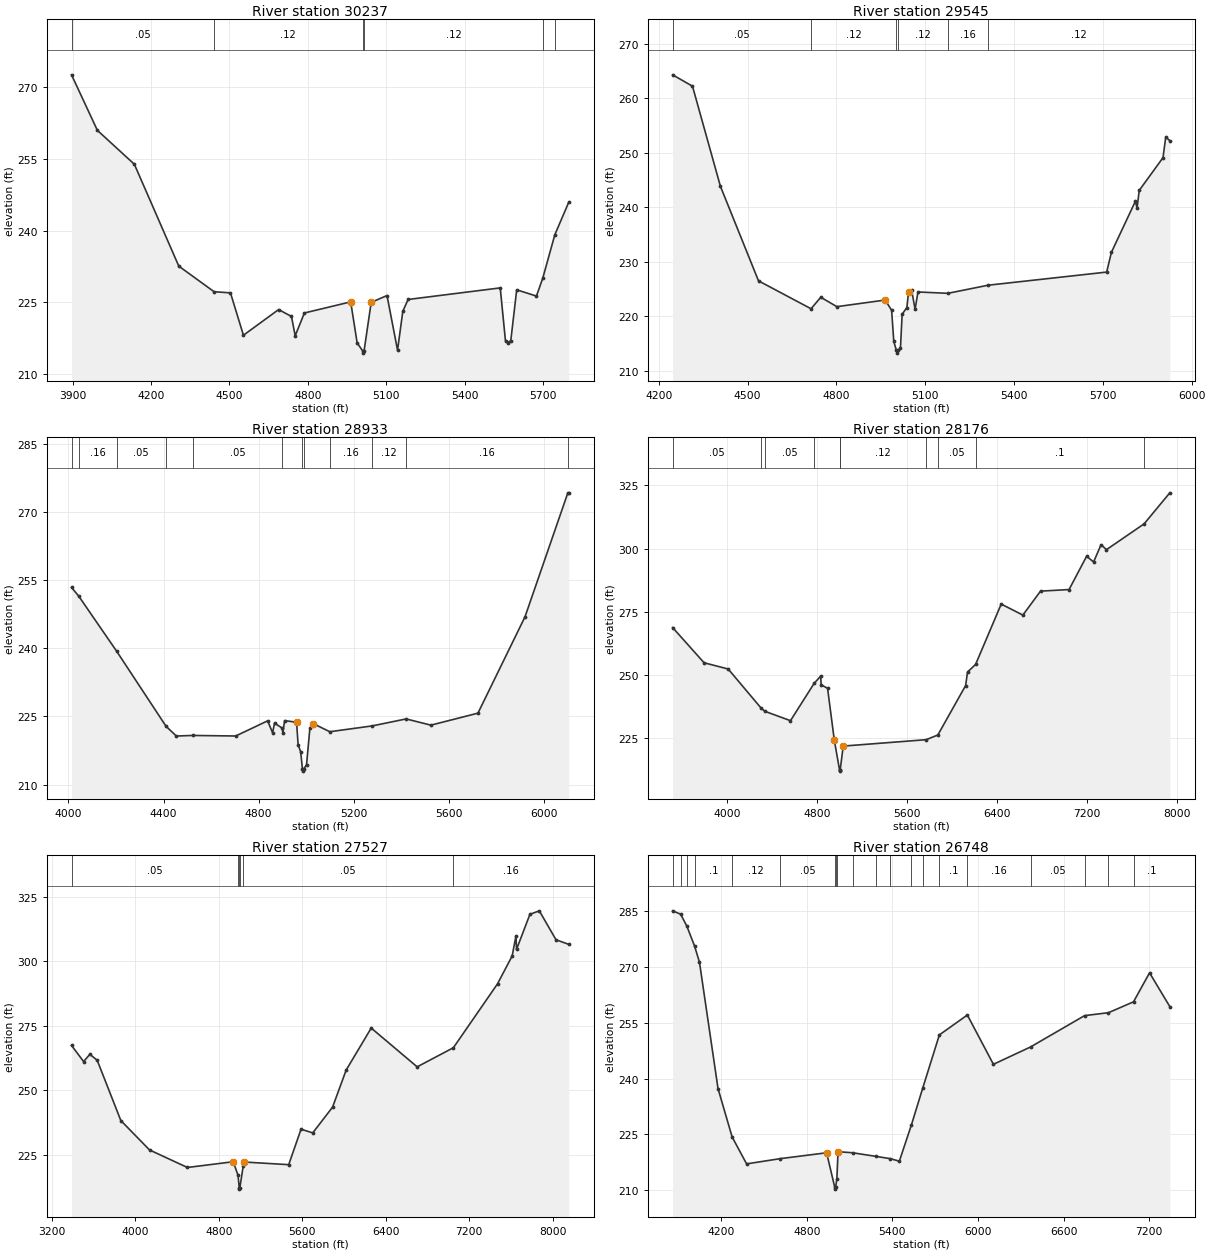
Type RM Length L Ch R = 1 ,30237   ,692,692,692
BEGIN DESCRIPTION:
MANSON CREEK 26.0
END DESCRIPTION:
XS GIS Cut Line= 3
      3747049.64     10577960.22      3747799.61     10578760.19
      3747899.61     10579560.22
#Sta/Elev= 30
  3895.5  272.54  3994.4  260.94    4136  253.85    4306  232.57  4441.1  227.22
  4503.8  226.98  4553.4  218.13    4688  223.49  4737.3  222.05  4751.5  218.02
  4786.7  222.78  4963.9   225.1  4988.6  216.53  5009.2  214.89  5011.9  214.39
  5015.2  214.89  5042.4     225  5102.9  226.42  5143.2  215.01  5163.4  223.13
  5183.5   225.6  5536.2  228.02  5556.4  216.87  5566.5  216.59  5576.6  217.01
  5599.2  227.62  5674.8  226.31  5698.8  230.02  5745.2  239.13  5798.3  245.91
#Mann= 6 ,-1 , 0
  3895.5     .05       0  4441.1     .12       0  5009.2     .07       0
  5015.2     .12       0  5698.8     .16       0  5745.2     .12       0
Bank Sta=4963.9,5042.4
XS Rating Curve= 0 ,0
Exp/Cntr=0.3,0.1

Type RM Length L Ch R = 1 ,29545   ,612,612,612
BEGIN DESCRIPTION:
MANSON CREEK 25.0
END DESCRIPTION:
XS GIS Cut Line= 3
      3747099.61     10578110.18      3747399.61     10578810.19
      3747849.63     10579610.22
#Sta/Elev= 30
  4246.7  264.34  4313.8  262.25  4408.1  243.88  4536.8  226.51  4714.3  221.39
  4747.2   223.5  4801.6  221.77  4964.8  222.99  4986.5   221.1  4993.8  215.38
  5002.6  213.74  5005.3  213.24  5008.6  213.74  5016.3  214.12    5022  220.38
  5037.9   221.6  5043.7  224.48  5053.9  224.86  5065.7  221.29  5075.5  224.47
  5176.5  224.22  5312.4  225.71  5712.9  228.12  5728.9  231.75  5809.8  241.11
  5815.6  239.91  5822.9  243.12  5903.2  249.13  5912.5  252.93  5926.2  252.25
#Mann= 6 ,-1 , 0
  4246.7     .05       0  4714.3     .12       0  5002.6     .07       0
  5008.6     .12       0  5176.5     .16       0  5312.4     .12       0
Bank Sta=4964.8,5043.7
XS Rating Curve= 0 ,0
Exp/Cntr=0.3,0.1

Type RM Length L Ch R = 1 ,28933   ,757,757,757
BEGIN DESCRIPTION:
MANSON CREEK 24.0
END DESCRIPTION:
XS GIS Cut Line= 3
      3746399.59     10578310.17      3746999.61     10579060.19
      3747799.63     10579860.21
#Sta/Elev= 30
  4012.8  253.41    4043  251.51  4202.3  239.39  4410.5  222.83  4453.8  220.68
  4523.1  220.81  4703.6  220.69    4838  224.03  4858.8  221.39  4866.8  223.52
  4898.7  222.45  4902.1  221.35  4909.3  224.08  4959.7  223.72  4966.1   218.8
  4976.8  217.22  4984.4  213.45  4987.2  212.95  4990.4  213.45  5001.6  214.37
  5015.7  222.39  5029.9  223.41  5099.6  221.63  5277.6  222.91  5420.5  224.45
  5524.8  223.08  5722.8  225.72  5920.8  246.95    6101  274.25  6104.7  274.26
#Mann= 12 ,-1 , 0
  4012.8     .05       0    4043     .16       0  4202.3     .05       0
  4410.5     .07       0  4523.1     .05       0  4898.7     .12       0
  4984.4     .07       0  4990.4     .12       0  5099.6     .16       0
  5277.6     .12       0  5420.5     .16       0    6101     .12       0
Bank Sta=4959.7,5029.9
XS Rating Curve= 0 ,0
Exp/Cntr=0.3,0.1

Type RM Length L Ch R = 1 ,28176   ,649,649,649
BEGIN DESCRIPTION:
Mapping XS 3239a64f
END DESCRIPTION:
XS GIS Cut Line= 3
      3746223.44     10577771.73      3746423.09     10579134.55
      3747516.83     10581981.73
#Sta/Elev= 30
  3511.5  268.66  3791.7  254.69  4006.3  252.22  4297.8   236.8  4332.6  235.45
    4561  231.73    4772  246.55  4829.6  249.37  4834.7  245.94  4891.3  244.57
  4951.3  224.01  4997.7  212.22  5000.4  211.72  5003.7  212.22  5030.7  221.65
  5770.2  224.19  5873.3  226.06  6120.8  245.67  6137.6  251.02  6209.2  254.02
  6437.5  277.97  6630.3   273.6  6787.5   283.1  7041.6  283.73  7198.1  296.93
  7260.2  294.68  7326.6  301.52  7374.9  299.55  7710.1  309.79  7938.9  322.09
#Mann= 10 ,-1 , 0
  3511.5     .05       0  4297.8     .16       0  4332.6     .05       0
    4772     .12       0  4997.7     .07       0  5003.7     .12       0
  5770.2      .1       0  5873.3     .05       0  6209.2      .1       0
  7710.1     .05       0
Bank Sta=4951.3,5030.7
XS Rating Curve= 0 ,0
Exp/Cntr=0.3,0.1

Type RM Length L Ch R = 1 ,27527   ,779,779,779
BEGIN DESCRIPTION:
Mapping XS 1cc03c8e
END DESCRIPTION:
XS GIS Cut Line= 3
      3746101.91     10577684.88       3745928.3     10579881.08
      3745824.13     10582441.81
#Sta/Elev= 30
  3388.2  267.41  3503.9  261.14  3564.1  263.95  3634.3  261.64  3860.8  238.28
  4135.8  226.88    4499  220.08  4938.3  222.31  4984.7  217.01  4995.5  212.19
  4998.3  211.69  5001.5  212.19  5033.5  220.49  5038.6  222.21    5470  221.17
  5588.3  234.92  5700.4  233.49  5890.6  243.48  6020.7  257.84  6260.9  274.13
  6701.3  259.09  7048.5   266.5  7471.9  291.29    7612  302.09  7648.7  309.93
  7653.7   304.6  7782.2  318.22  7872.2  319.57  8032.4  308.34  8154.1  306.58
#Mann= 6 ,-1 , 0
  3388.2     .05       0  4984.7     .12       0  4995.5     .07       0
  5001.5     .12       0  5033.5     .05       0  7048.5     .16       0
Bank Sta=4938.3,5038.6
XS Rating Curve= 0 ,0
Exp/Cntr=0.3,0.1

Type RM Length L Ch R = 1 ,26748   ,678,678,678
BEGIN DESCRIPTION:
Mapping XS 6de24cd9
END DESCRIPTION:
XS GIS Cut Line= 3
      3745468.23     10577832.42      3745381.43     10579360.24
       3744331.1     10581009.51
#Sta/Elev= 30
  3859.6  284.95  3915.8  284.05  3959.5  280.83  4013.8  275.47  4047.7   271.2
  4177.9   237.3  4276.8  224.33  4378.2  217.12  4615.8  218.53  4939.1  220.09
  4996.2  210.85  4998.9  210.35  5002.2  210.85  5011.2  213.16  5019.2  220.38
  5120.9   220.1  5288.2  219.11  5386.3  218.51  5449.1  217.84  5533.9  227.59
  5612.7   237.4  5729.8   251.7  5925.8  257.02  6108.5  243.81    6369  248.46
  6747.7  256.86  6914.9  257.64  7090.7  260.56  7203.1  268.33  7345.2  259.28
#Mann= 20 ,-1 , 0
  3859.6     .07       0  3915.8      .1       0  3959.5     .05       0
  4013.8      .1       0  4276.8     .12       0  4615.8     .05       0
  4996.2     .03       0  5002.2     .05       0  5011.2     .12       0
  5120.9     .05       0  5288.2     .07       0  5386.3     .12       0
  5533.9     .16       0  5612.7     .05       0  5729.8      .1       0
  5925.8     .16       0    6369     .05       0  6747.7      .1       0
  6914.9     .16       0  7090.7      .1       0
Bank Sta=4939.1,5019.2
XS Rating Curve= 0 ,0
Exp/Cntr=0.3,0.1

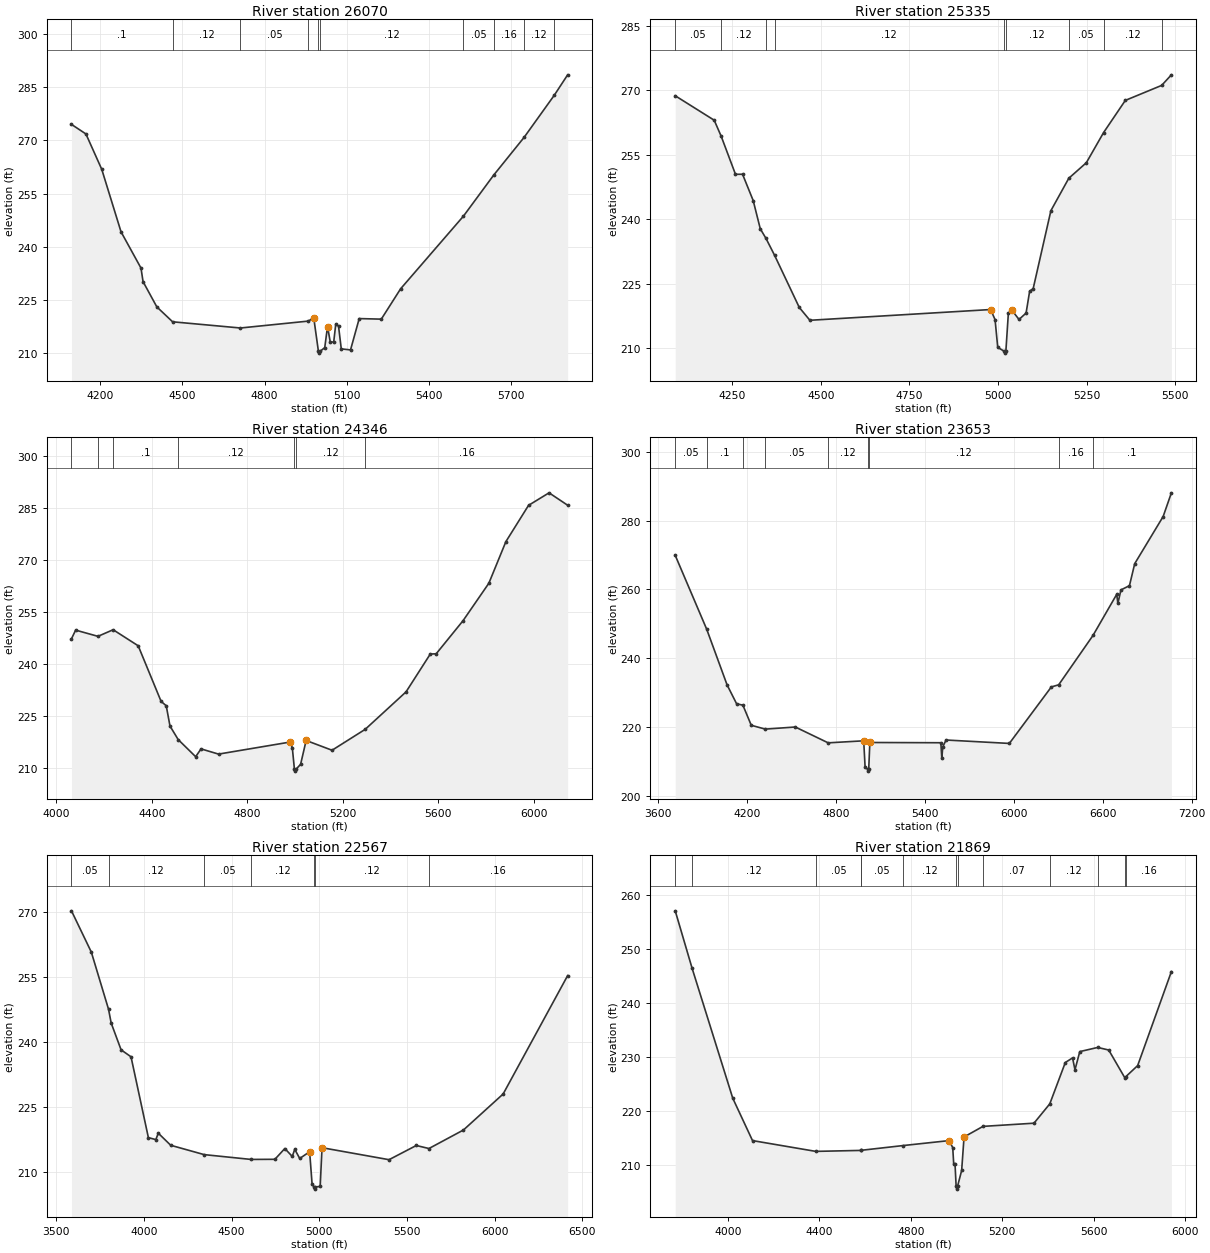
Type RM Length L Ch R = 1 ,26070   ,735,735,735
BEGIN DESCRIPTION:
MANSON CREEK 20.0
END DESCRIPTION:
XS GIS Cut Line= 3
       3744849.6     10578060.15      3744949.61     10579060.19
      3744549.59     10579760.23
#Sta/Elev= 30
    4095  274.53  4147.8  271.82  4205.6  261.82  4275.9  244.18  4348.8  233.93
  4356.3  230.11  4406.6  222.97  4464.2  218.76  4711.7  217.01  4959.8  218.96
  4979.4  219.91  4996.5  210.41  4999.3  209.91  5002.5  210.41  5019.6  211.47
  5029.7  217.42  5039.7  213.07  5052.3  213.04  5059.8   218.1  5069.9  217.55
  5079.9  211.11  5113.7  210.82  5145.4  219.67    5226  219.51  5296.5  228.08
  5525.9  248.61  5636.4  260.21    5747  270.83  5857.5  282.76  5906.3  288.53
#Mann= 10 ,-1 , 0
    4095      .1       0  4464.2     .12       0  4711.7     .05       0
  4959.8     .12       0  4996.5     .07       0  5002.5     .12       0
  5525.9     .05       0  5636.4     .16       0    5747     .12       0
  5857.5     .16       0
Bank Sta=4979.4,5029.7
XS Rating Curve= 0 ,0
Exp/Cntr=0.3,0.1

Type RM Length L Ch R = 1 ,25335   ,989,989,989
BEGIN DESCRIPTION:
MANSON CREEK 19.0
END DESCRIPTION:
XS GIS Cut Line= 3
      3744449.61      10578210.2      3744449.61     10579110.19
      3744449.61      10579610.2
#Sta/Elev= 30
  4089.4  268.71  4199.4  263.02  4219.1  259.29  4259.4  250.44  4279.4  250.45
  4309.4  244.33  4329.4  237.76  4345.6  235.51  4369.8  231.59  4439.4  219.47
  4469.4  216.48  4979.4  218.98  4991.9  216.62  4999.4  210.17  5016.4  209.34
  5019.1  208.84  5022.4  209.34  5029.4  218.16  5039.4  218.82  5059.4  216.67
  5079.4  218.16  5089.4  223.23  5099.4  223.85  5149.4  241.98  5199.9  249.52
  5249.4  253.13    5298  260.14  5359.4  267.63  5461.9  271.12  5489.4  273.58
#Mann= 9 ,-1 , 0
  4089.4     .05       0  4219.1     .12       0  4345.6      .1       0
  4369.8     .12       0  5016.4     .07       0  5022.4     .12       0
  5199.9     .05       0    5298     .12       0  5461.9     .16       0
Bank Sta=4979.4,5039.4
XS Rating Curve= 0 ,0
Exp/Cntr=0.3,0.1

Type RM Length L Ch R = 1 ,24346   ,693,693,693
BEGIN DESCRIPTION:
MANSON CREEK 18.0
END DESCRIPTION:
XS GIS Cut Line= 3
      3744244.28     10578231.75      3743732.12     10579108.51
      3744070.62     10580115.34
#Sta/Elev= 30
  4063.5   247.3  4080.9  249.81  4174.4  248.02    4238  249.92  4342.9  245.29
  4438.8  229.26  4460.3     228    4476  222.15  4510.3  218.25  4583.5  213.31
    4606  215.56  4679.4  214.06  4978.6  217.53  4988.2   215.9  4997.1  209.65
  4999.9  209.15  5003.1  209.65  5022.9  211.11  5046.1  217.99  5154.6  215.17
  5293.4   221.2  5464.5  232.01    5566  242.92  5590.6  242.98  5703.1  252.53
  5811.2  263.33  5882.5  275.33  5977.4  285.79  6063.3   289.4  6141.1  285.82
#Mann= 7 ,-1 , 0
  4063.5      .1       0  4174.4     .05       0    4238      .1       0
  4510.3     .12       0  4997.1     .07       0  5003.1     .12       0
  5293.4     .16       0
Bank Sta=4978.6,5046.1
XS Rating Curve= 0 ,0
Exp/Cntr=0.3,0.1

Type RM Length L Ch R = 1 ,23653   ,1086,1086,1086
BEGIN DESCRIPTION:
MANSON CREEK 17.0
END DESCRIPTION:
XS GIS Cut Line= 3
       3743966.5     10577433.14      3743393.58      10578934.9
      3742039.45     10580028.62
#Sta/Elev= 30
  3714.9  269.92  3927.5  248.42  4064.9  232.26  4129.2  226.77  4171.5  226.38
    4228  220.53  4322.5  219.42  4525.2  220.03  4746.9  215.43  4986.7  216.02
  4996.1   208.4  5014.5  207.71  5017.3  207.21  5020.5  207.71  5028.2  215.53
  5507.3  215.46  5513.7  210.91  5520.2  214.27  5542.5  216.25  5969.4  215.26
  6252.9  231.68  6302.3  232.29  6533.9  246.64  6693.9  258.58  6701.8  255.97
  6722.6  259.87  6779.9   261.1  6815.4   267.5  7007.3   281.2  7062.9  288.08
#Mann= 9 ,-1 , 0
  3714.9     .05       0  3927.5      .1       0  4171.5     .12       0
  4322.5     .05       0  4746.9     .12       0  5014.5     .07       0
  5020.5     .12       0  6302.3     .16       0  6533.9      .1       0
Bank Sta=4986.7,5028.2
XS Rating Curve= 0 ,0
Exp/Cntr=0.3,0.1

Type RM Length L Ch R = 1 ,22567   ,698,698,698
BEGIN DESCRIPTION:
MANSON CREEK 16.0
END DESCRIPTION:
XS GIS Cut Line= 3
       3743899.6      10577360.2      3742899.61     10578360.19
      3741899.62     10579360.18
#Sta/Elev= 30
  3587.2  270.36  3700.3  260.83  3798.5  247.62  3813.5  244.44    3870  238.25
  3926.6  236.64  4025.6  217.97    4068  217.51  4082.2  218.99  4152.9   216.2
  4343.8  214.04  4611.1  212.93  4746.8  212.96  4803.4  215.45  4845.8  213.62
    4860  215.27  4888.3  213.15  4944.8  214.71    4959  207.14  4970.1  206.57
  4972.9  206.07  4976.1  206.57  5004.9  206.69  5015.5  215.64  5397.4  212.87
  5552.9  216.15  5624.9  215.45  5821.6  219.73  6047.9  228.05  6415.6   255.4
#Mann= 7 ,-1 , 0
  3587.2     .05       0  3798.5     .12       0  4343.8     .05       0
  4611.1     .12       0  4970.1     .07       0  4976.1     .12       0
  5624.9     .16       0
Bank Sta=4944.8,5015.5
XS Rating Curve= 0 ,0
Exp/Cntr=0.3,0.1

Type RM Length L Ch R = 1 ,21869   ,774,774,774
BEGIN DESCRIPTION:
MANSON CREEK 15.0
END DESCRIPTION:
XS GIS Cut Line= 3
      3743699.62     10577210.18      3742699.61     10577910.19
      3741799.65     10578210.17
#Sta/Elev= 30
  3770.5  257.03  3844.1  246.42  4022.1  222.32  4108.4  214.48    4385  212.48
  4582.6  212.66  4583.7  212.68  4767.1  213.56  4968.9  214.48  4983.8  213.16
  4988.1  210.14  4993.8  210.14  4998.7  205.99  5001.5  205.49  5004.7  205.99
  5022.8  208.95  5033.3  215.15    5116  217.11    5339   217.7  5408.1  221.28
    5476  228.94  5507.7  229.79  5518.2  227.59  5539.3  230.96  5617.7  231.73
  5665.8  231.25  5735.6  226.15  5740.1   226.3  5792.3  228.37  5939.8  245.78
#Mann= 13 ,-1 , 0
  3770.5     .05       0  3844.1     .12       0    4385     .05       0
  4582.6      .1       0  4583.7     .05       0  4767.1     .12       0
  4998.7     .07       0  5004.7     .12       0    5116     .07       0
  5408.1     .12       0  5617.7     .16       0  5735.6     .12       0
  5740.1     .16       0
Bank Sta=4968.9,5033.3
XS Rating Curve= 0 ,0
Exp/Cntr=0.3,0.1

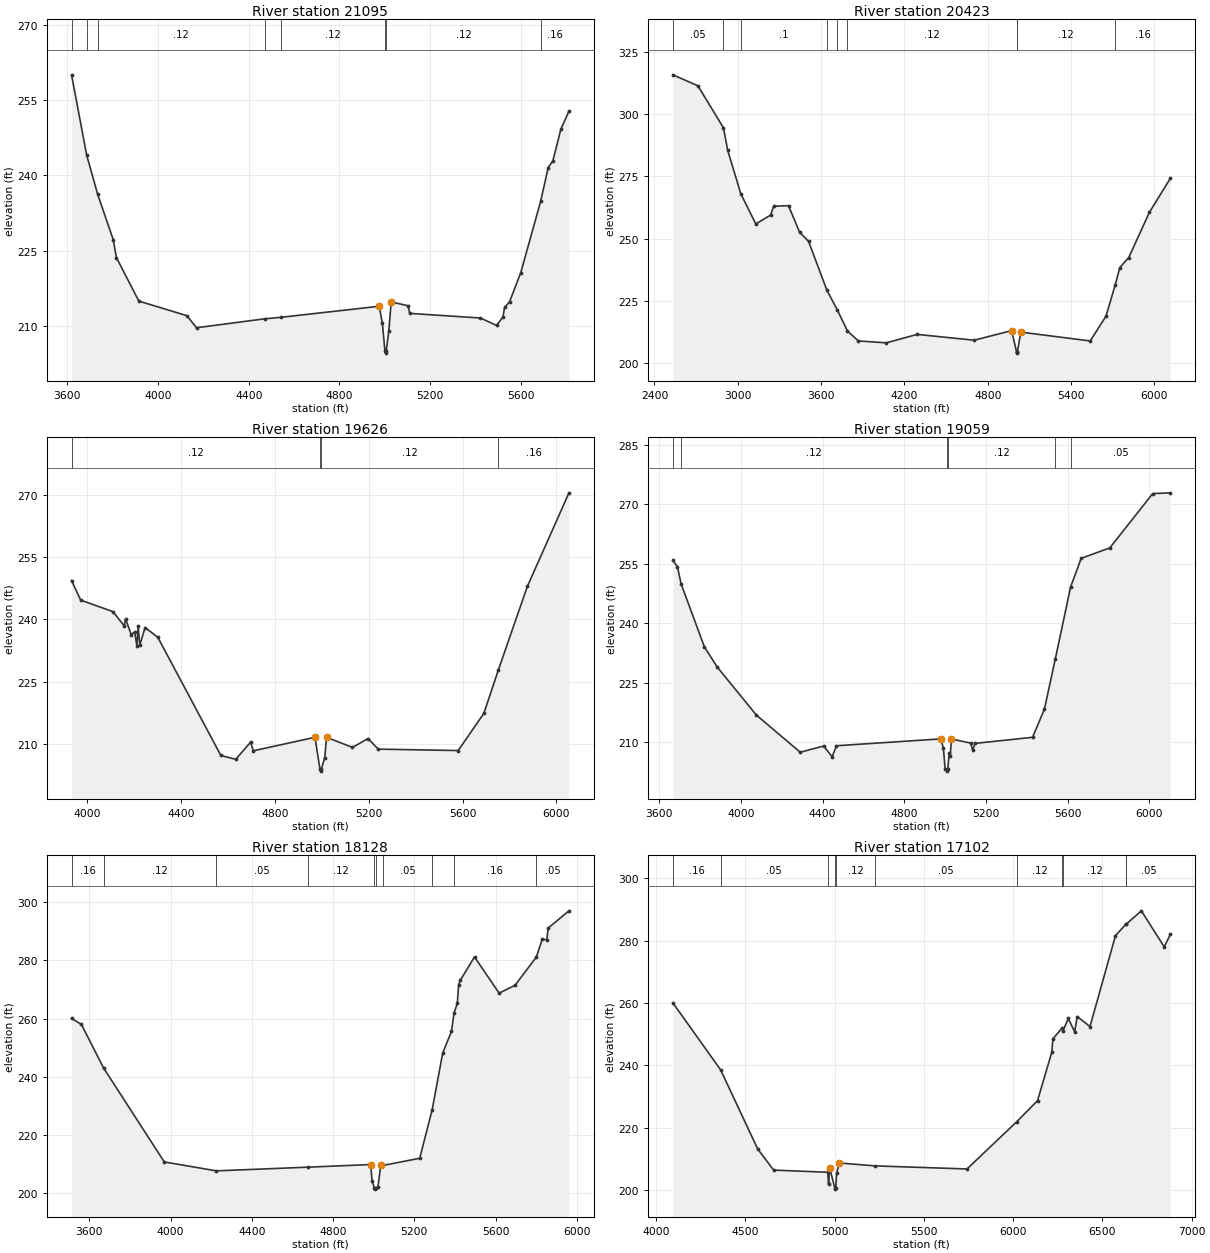
Type RM Length L Ch R = 1 ,21095   ,672,672,672
BEGIN DESCRIPTION:
MANSON CREEK 14.0
END DESCRIPTION:
XS GIS Cut Line= 3
       3743299.6      10576710.2      3742299.61     10577710.19
      3741699.63     10578210.17
#Sta/Elev= 30
  3618.2  260.09  3684.8   244.1  3733.2  236.26    3802   227.2  3816.2   223.6
  3915.2   214.9  4127.3  211.99  4169.7  209.58  4471.8  211.37  4541.5  211.66
  4975.8  213.87    4990  210.45  5001.1  205.01  5003.9  204.51  5007.1  205.01
  5018.3   208.9  5028.9  214.74  5103.3  213.97  5110.5  212.45  5422.9  211.52
  5493.9  210.04  5522.5  211.76    5529  213.63  5551.1  214.74  5600.6  220.58
  5688.3  234.81  5721.7  241.56  5742.5  242.94  5777.6  249.22  5813.4  252.86
#Mann= 8 ,-1 , 0
  3618.2     .12       0  3684.8     .16       0  3733.2     .12       0
  4471.8     .05       0  4541.5     .12       0  5001.1     .07       0
  5007.1     .12       0  5688.3     .16       0
Bank Sta=4975.8,5028.9
XS Rating Curve= 0 ,0
Exp/Cntr=0.3,0.1

Type RM Length L Ch R = 1 ,20423   ,797,797,797
BEGIN DESCRIPTION:
MANSON CREEK 13.0
END DESCRIPTION:
XS GIS Cut Line= 3
      3743949.63     10575960.17      3741949.61     10577360.19
      3741249.62     10578260.17
#Sta/Elev= 30
  2532.8  315.78  2712.9  311.38    2897  294.48  2927.4  285.47    3021  268.16
  3129.6  255.93  3236.9  259.54  3257.8  263.07  3365.1  263.28  3445.3  252.58
  3509.4  248.95  3641.3  229.38  3716.8  221.42  3789.7  212.98  3868.1  208.99
  4070.4  208.25    4291  211.63  4701.7  209.29  4971.1  213.14  5007.3  204.61
  5010.1  204.11  5013.3  204.61  5037.5  212.54    5537     209    5651  218.92
  5717.6  231.52  5750.5  238.44  5814.8  242.47  5964.1  260.67  6114.3  274.23
#Mann= 9 ,-1 , 0
  2532.8     .05       0    2897     .16       0    3021      .1       0
  3641.3     .12       0  3716.8     .16       0  3789.7     .12       0
  5007.3     .07       0  5013.3     .12       0  5717.6     .16       0
Bank Sta=4971.1,5037.5
XS Rating Curve= 0 ,0
Exp/Cntr=0.3,0.1

Type RM Length L Ch R = 1 ,19626   ,567,567,567
BEGIN DESCRIPTION:
MANSON CREEK 12.0
END DESCRIPTION:
XS GIS Cut Line= 3
       3741949.6     10576110.22      3741549.61     10577110.19
      3741249.62     10578110.16
#Sta/Elev= 30
  3932.9  249.35  3971.9  244.63  4109.2  241.87  4157.7  238.43  4163.1  240.15
  4187.3  236.34  4202.1  236.99  4211.5  233.63  4216.9  238.36  4223.7  233.81
  4246.5  238.02  4300.4  235.72  4569.7  207.26  4632.9  206.34  4696.2  210.45
  4708.3  208.39  4970.9  211.64  4992.1     204  4994.8   203.5  4998.1     204
  5012.5  206.74  5020.3  211.64  5130.8   209.2    5197  211.34  5240.5  208.79
  5581.5  208.45  5691.1  217.41  5752.3  227.74  5876.4  247.92  6053.9  270.44
#Mann= 4 ,-1 , 0
  3932.9     .12       0  4992.1     .07       0  4998.1     .12       0
  5752.3     .16       0
Bank Sta=4970.9,5020.3
XS Rating Curve= 0 ,0
Exp/Cntr=0.3,0.1

Type RM Length L Ch R = 1 ,19059   ,931,931,931
BEGIN DESCRIPTION:
MANSON CREEK 11.0
END DESCRIPTION:
XS GIS Cut Line= 3
       3741570.5     10575922.71      3741148.61     10577344.62
      3741169.42     10578296.51
#Sta/Elev= 30
  3667.3  255.81  3689.4  254.18  3707.7  249.84  3821.1  234.03  3883.7  228.94
  4075.7   216.8  4290.7  207.41  4405.3  208.99    4447  206.27  4467.9  209.05
    4979  210.78  4991.7  208.39  4999.8  203.28  5007.3  203.15    5010  202.65
  5013.3  203.15  5019.7  207.19  5024.9  206.44  5031.1  210.76  5124.6  209.72
  5135.4  207.88  5145.6  209.64    5428  211.18  5486.1  218.28  5539.2  230.87
  5614.4   249.1  5666.2  256.31  5806.2  258.95  6016.3  272.64  6102.6  272.84
#Mann= 6 ,-1 , 0
  3667.3     .16       0  3707.7     .12       0  5007.3     .07       0
  5013.3     .12       0  5539.2     .16       0  5614.4     .05       0
Bank Sta=4979,5031.1
XS Rating Curve= 0 ,0
Exp/Cntr=0.3,0.1

Type RM Length L Ch R = 1 ,18128   ,1026,1026,1026
BEGIN DESCRIPTION:
MANSON CREEK 10.0
END DESCRIPTION:
XS GIS Cut Line= 3
      3741518.41     10575881.07      3740695.49     10577011.29
       3740028.8     10577823.81
#Sta/Elev= 30
  3512.1  260.04  3560.5  257.99  3670.3  242.92  3968.7  210.63  4224.9  207.55
  4675.6  208.82  4985.1  209.73  4991.6  204.17    5003  201.76  5005.7  201.26
    5009  201.76  5020.3  201.83  5034.7  209.64  5046.5  209.44  5226.3  211.88
  5287.8  228.65  5339.6  248.15  5382.7  255.54  5394.9  261.81  5411.4  265.18
  5417.9  271.56  5425.7  273.12  5496.1  281.21  5617.4  268.74  5695.6  271.45
  5800.1  281.12  5829.8  287.32    5852  287.12  5858.5  291.14  5961.2  297.09
#Mann= 10 ,-1 , 0
  3512.1     .16       0  3670.3     .12       0  4224.9     .05       0
  4675.6     .12       0    5003     .07       0    5009     .12       0
  5046.5     .05       0  5287.8     .12       0  5394.9     .16       0
  5800.1     .05       0
Bank Sta=4985.1,5034.7
XS Rating Curve= 0 ,0
Exp/Cntr=0.3,0.1

Type RM Length L Ch R = 1 ,17102   ,2190,2190,2190
BEGIN DESCRIPTION:
MANSON CREEK 9.0
END DESCRIPTION:
XS GIS Cut Line= 3
      3741523.59     10575875.88      3740372.57     10576448.79
      3739503.68     10577671.48
#Sta/Elev= 30
  4094.9  260.04    4362  238.58  4569.4  213.21  4658.9   206.4  4961.9   205.7
  4966.8  201.83  4972.4  207.19  5001.1  200.79  5003.9  200.29  5007.1  200.79
  5011.6  205.42  5026.5  208.68  5227.3  207.75  5741.9  206.76    6021  221.95
  6136.7  228.67  6216.6  244.19  6222.8  248.55  6275.2  252.01    6280  251.11
  6308.9  255.06  6344.6   250.8  6359.4  255.66  6430.7  252.46  6573.4  281.63
  6631.3  285.25  6634.4  285.36  6718.5  289.59  6846.4  278.02  6880.6  282.01
#Mann= 11 ,-1 , 0
  4094.9     .16       0    4362     .05       0  4961.9     .12       0
  5001.1     .07       0  5007.1     .12       0  5227.3     .05       0
    6021     .12       0  6275.2     .16       0    6280     .12       0
  6631.3     .16       0  6634.4     .05       0
Bank Sta=4972.4,5026.5
XS Rating Curve= 0 ,0
Exp/Cntr=0.3,0.1

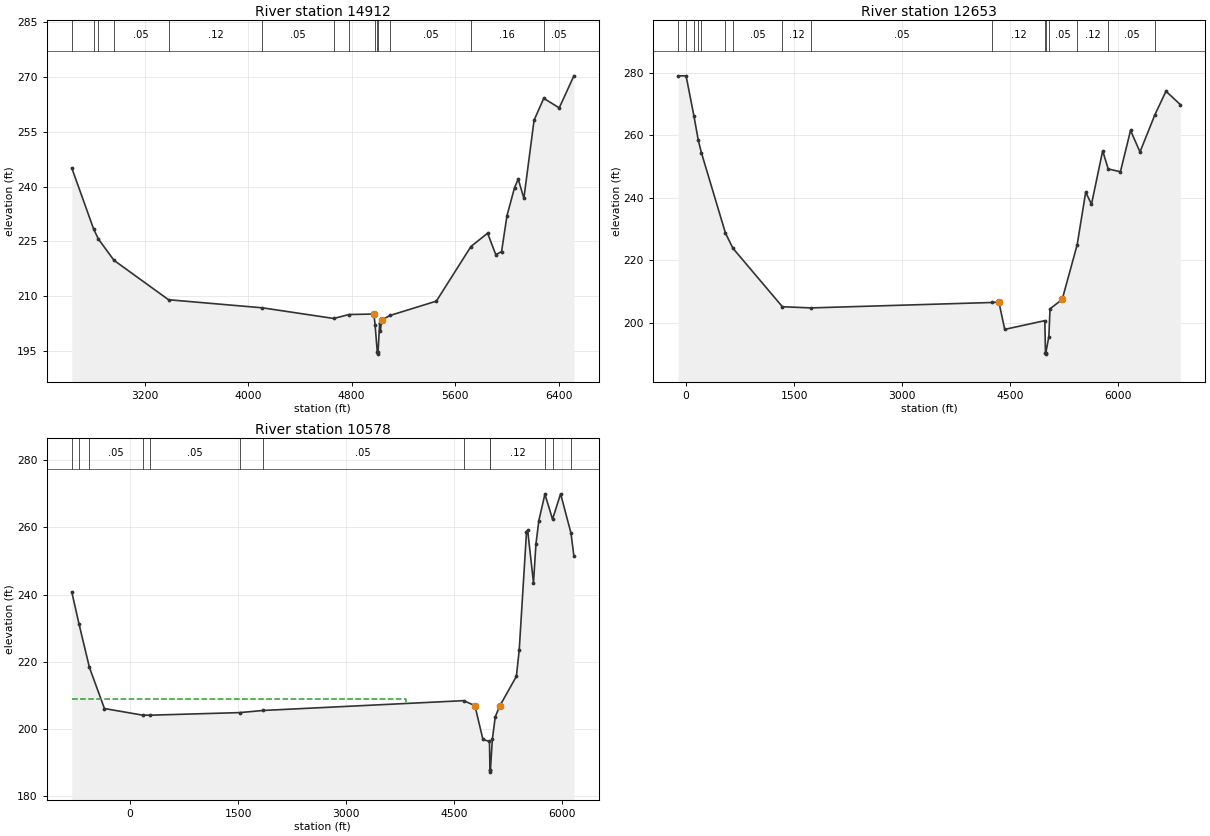
Type RM Length L Ch R = 1 ,14912   ,2259,2259,2259
BEGIN DESCRIPTION:
MANSON CREEK 8.0
END DESCRIPTION:
XS GIS Cut Line= 3
      3741544.47     10575120.65      3739648.61     10575818.58
      3738601.71     10577360.28
#Sta/Elev= 30
  2635.1  245.09  2803.2  228.49  2840.8  225.67  2961.8  219.83  3383.7  209.06
  4109.9  206.85  4661.5  203.94  4779.7  205.02  4971.6  205.15  4981.1  202.25
  4998.2  194.69    5001  194.19  5004.2  194.69  5016.2  202.73  5022.2  200.46
  5031.1   203.5  5096.6  204.76  5455.1  208.68  5722.4  223.61  5851.5  227.26
  5914.5  221.39  5959.3   222.2  6001.3  232.06  6059.5  239.67  6088.1  242.04
    6132  236.81  6210.8  258.14  6285.6  264.13  6405.4  261.52  6518.9  270.28
#Mann= 14 ,-1 , 0
  2635.1     .16       0  2803.2     .05       0  2840.8     .16       0
  2961.8     .05       0  3383.7     .12       0  4109.9     .05       0
  4661.5     .07       0  4779.7     .12       0  4981.1     .07       0
  4998.2     .07       0  5004.2     .07       0  5096.6     .05       0
  5722.4     .16       0  6285.6     .05       0
Bank Sta=4971.6,5031.1
XS Rating Curve= 0 ,0
Exp/Cntr=0.3,0.1

Type RM Length L Ch R = 1 ,12653   ,2075,2075,2075
BEGIN DESCRIPTION:
Mapping XS d7cba651
END DESCRIPTION:
XS GIS Cut Line= 3
      3739572.71     10571570.04       3738123.4     10575110.49
      3737730.12     10578236.03
#Sta/Elev= 30
  -110.2  279.06     -.5  279.07   109.2  266.16   169.3  258.39   213.6  254.35
   546.8  228.66   649.9  223.83  1337.6  205.08  1735.5   204.7  4250.5  206.44
  4345.8  206.55  4426.1  197.82  4983.7  200.62  4992.1  190.39  4994.9  189.89
  4998.1  190.39  5039.5  195.51  5055.6  204.41  5224.8  207.42  5432.4   224.9
  5551.3   241.8  5631.6  237.91  5787.3  255.05  5863.7  249.23  6033.5  248.33
  6174.3  261.58  6305.4  254.67  6513.5  266.64  6666.3  274.13  6865.6  269.87
#Mann= 16 ,-1 , 0
  -110.2     .12       0     -.5     .16       0   109.2     .05       0
   169.3     .16       0   213.6     .05       0   546.8     .16       0
   649.9     .05       0  1337.6     .12       0  1735.5     .05       0
  4250.5     .12       0  4992.1     .07       0  4998.1     .12       0
  5039.5     .05       0  5432.4     .12       0  5863.7     .05       0
  6513.5     .16       0
Bank Sta=4345.8,5224.8
XS Rating Curve= 0 ,0
Exp/Cntr=0.3,0.1

Type RM Length L Ch R = 1 ,10578   ,0,0,0
BEGIN DESCRIPTION:
Mapping XS 2b03eeb8
END DESCRIPTION:
XS GIS Cut Line= 3
      3738413.27     10571259.47      3736839.74     10574510.07
      3736425.65     10577843.42
#Sta/Elev= 30
  -809.1  240.82  -707.4  231.16  -564.1  218.34  -355.7  206.12   173.7  204.15
   282.9  204.14  1524.5  204.91  1845.5  205.54  4628.8  208.46  4786.7     207
  4898.4  196.92  4989.1  196.34  4996.2   187.7    4999   187.2  5002.2   187.7
  5029.3     197  5069.7  203.65  5130.2  206.81  5362.8  215.69  5402.3  223.58
    5503  258.49  5519.5  259.09  5600.4  243.53    5634  254.94  5674.4  261.99
  5758.9   269.9  5864.6  262.43  5976.7  269.99  6121.5  258.22  6161.3  251.43
#Mann= 13 ,-1 , 0
  -809.1     .05       0  -707.4     .16       0  -564.1     .05       0
   173.7     .12       0   282.9     .05       0  1524.5     .12       0
  1845.5     .05       0  4628.8     .12       0  4996.2     .07       0
  5002.2     .12       0  5758.9     .16       0  5864.6     .05       0
  6121.5     .16       0
#XS Ineff= 2 , 0
         3836.36  208.91
Permanent Ineff=
       F       F
Bank Sta=4786.7,5130.2
XS Rating Curve= 0 ,0
Exp/Cntr=0.3,0.1

Chan Stop Cuts=-1
Use User Specified Reach Order=0
Composite Channel Slope=5