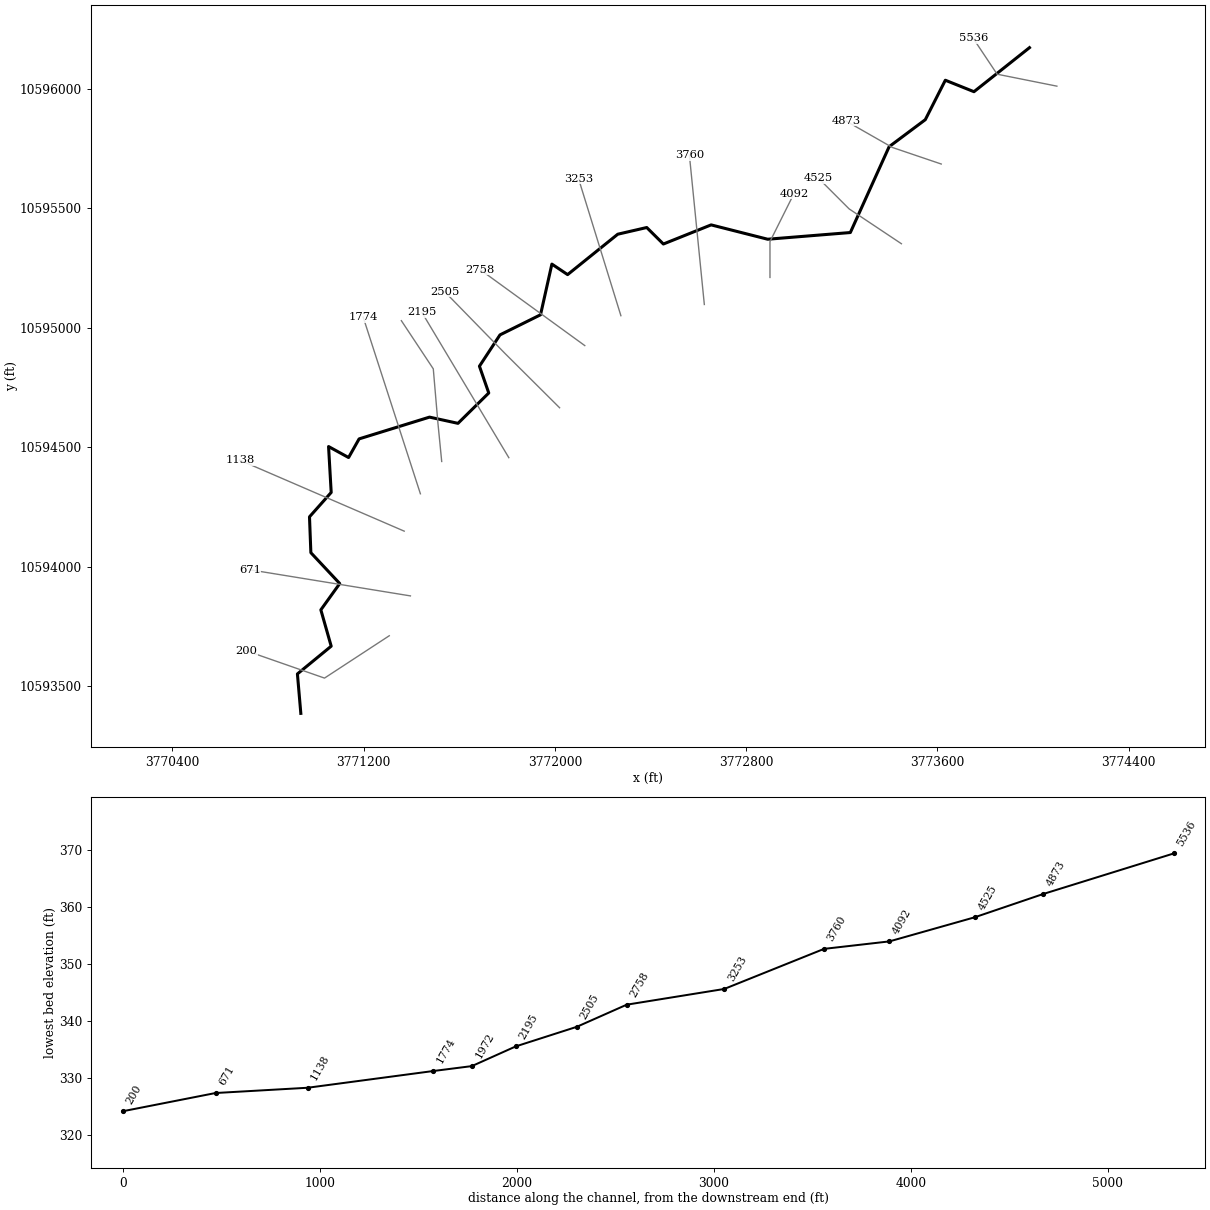
--- PARKER BRANCH.prj (project) ---

Proj Title=PARKER BRANCH Base Level Engineering
Current Plan=p01
Default Exp/Contr=0.3,0.1
English Units
Geom File=g01
Flow File=f01
Plan File=p01
BEGIN DESCRIPTION:
PARKER BRANCH
END DESCRIPTION:

--- PARKER BRANCH.p01 (plan) ---

Plan Title=Multiple Run
Short Identifier=Multiple
Geom File=g01
Flow File=f01
Subcritical Flow
K Sum by GR= 0
Std Step Tol= 0.01
Critical Tol= 0.01
Num of Std Step Trials= 20
Max Error Tol= 0.3
Flow Tol Ratio= 0.001
Split Flow NTrial= 30
Split Flow Tol= 0.02
Split Flow Ratio= 0.02
Log Output Level= 0
Friction Slope Method= 1
Unsteady Friction Slope Method= 2
Unsteady Bridges Friction Slope Method= 1
Parabolic Critical Depth
Global Vel Dist=  1 , 1 , 1
Global Log Level= 0
CheckData=True
Encroach Param= -1, 0, 0, 0
BEGIN DESCRIPTION:
Multiple Run
END DESCRIPTION:

--- PARKER BRANCH.f01 (steady flow) ---

Flow Title=Multiple
Number of Profiles=7
Profile Names=10-year,25-year,50-year,1pct_min,100-year,1pct_plu,500-year
River Rch & RM= PARKER BRANCH,Reach-1,5536
     421     561     675     598     809    1095    1166
Boundary for River Rch & Prof#=PARKER BRANCH,Reach-1,1
Up Type=0
Dn Type=3
Dn Slope=0.005
Boundary for River Rch & Prof#=PARKER BRANCH,Reach-1,2
Up Type=0
Dn Type=3
Dn Slope=0.005
Boundary for River Rch & Prof#=PARKER BRANCH,Reach-1,3
Up Type=0
Dn Type=3
Dn Slope=0.005
Boundary for River Rch & Prof#=PARKER BRANCH,Reach-1,4
Up Type=0
Dn Type=3
Dn Slope=0.005
Boundary for River Rch & Prof#=PARKER BRANCH,Reach-1,5
Up Type=0
Dn Type=3
Dn Slope=0.005
Boundary for River Rch & Prof#=PARKER BRANCH,Reach-1,6
Up Type=0
Dn Type=3
Dn Slope=0.005
Boundary for River Rch & Prof#=PARKER BRANCH,Reach-1,7
Up Type=0
Dn Type=3
Dn Slope=0.005

--- PARKER BRANCH.g01 (geometry) ---

Geom Title=Existing Conditions

River Reach=PARKER BRANCH,Reach-1
Reach XY= 30
      3773984.91     10596171.21      3773752.75     10595987.00
      3773633.00     10596035.00      3773549.25     10595870.00
      3773398.00     10595757.00      3773235.75     10595398.00
      3772890.00     10595370.00      3772653.50     10595430.00
      3772453.75     10595350.00      3772384.25     10595419.00
      3772263.00     10595391.00      3772053.25     10595222.00
      3771987.50     10595266.00      3771940.00     10595054.00
      3771770.50     10594970.00      3771684.50     10594839.00
      3771723.50     10594727.00      3771594.75     10594600.00
      3771475.75     10594626.00      3771181.25     10594535.00
      3771137.25     10594457.00      3771053.50     10594503.00
      3771064.50     10594311.00      3770973.75     10594209.00
      3770979.50     10594059.00      3771100.25     10593930.00
      3771021.25     10593820.00      3771064.50     10593668.00
      3770923.25     10593552.00      3770937.50     10593387.00

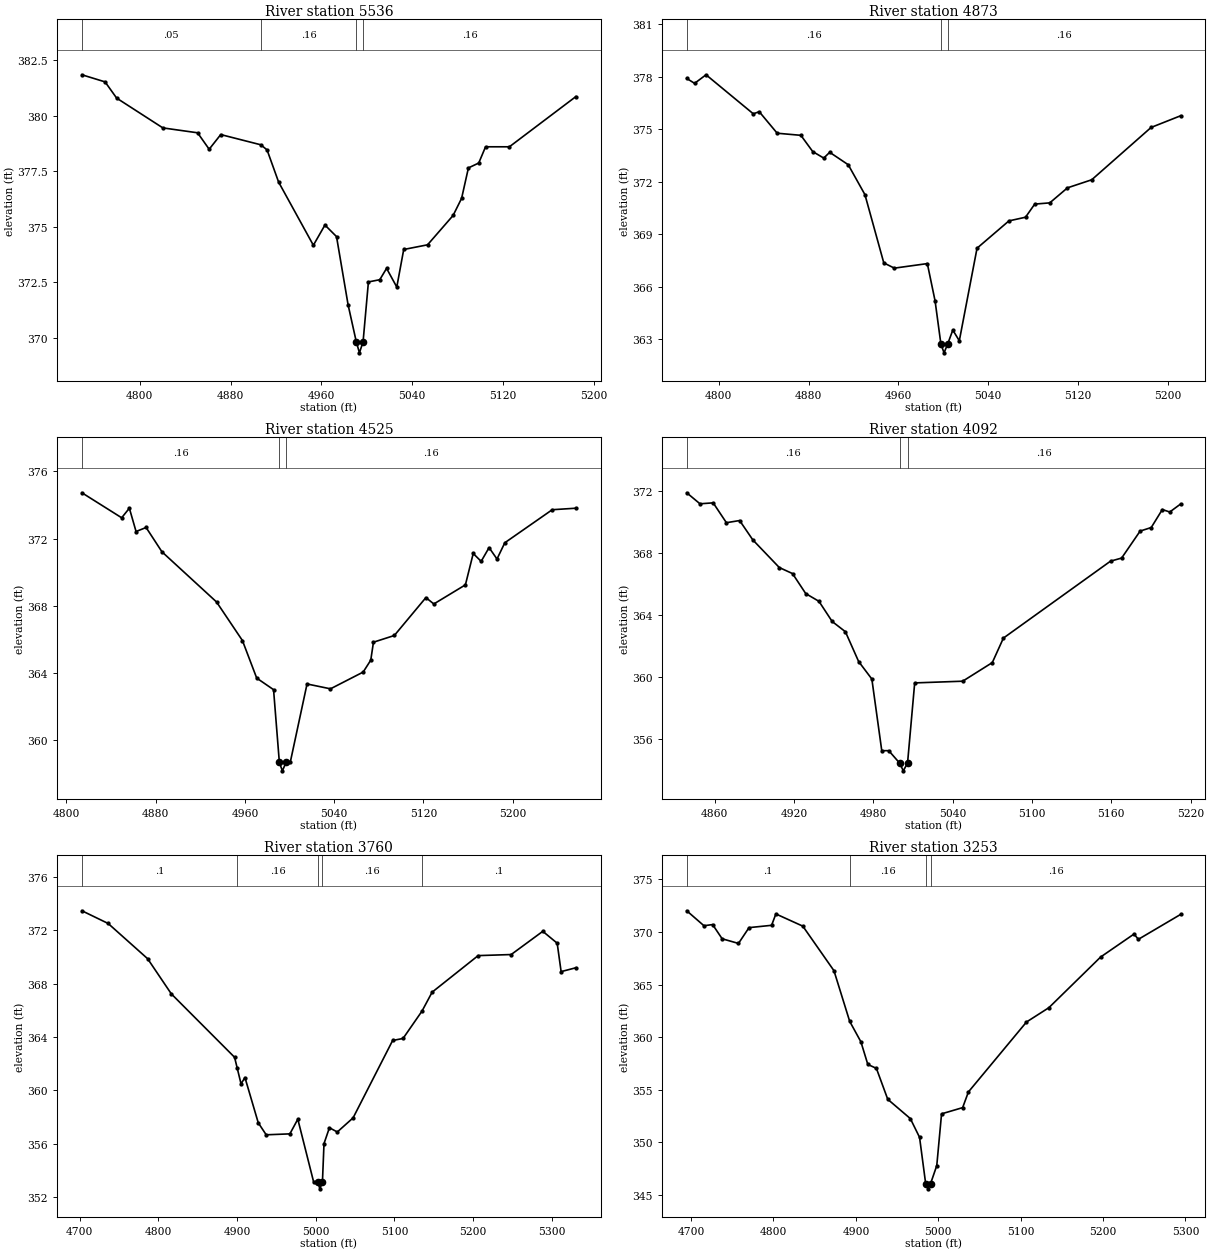
Type RM Length L Ch R = 1,5536,663,663,663
BEGIN DESCRIPTION:
PARKER BRANCH 11.0
END DESCRIPTION:
XS GIS Cut Line= 3
      3774099.57     10596010.20      3773849.61     10596060.19
      3773749.60     10596210.20
#Sta/Elev= 30
  4749.0  381.84  4769.4  381.52  4779.6  380.79  4820.3  379.45  4850.9  379.23
  4861.1  378.49  4871.3  379.15  4906.6  378.69  4912.1  378.46  4922.3  377.01
  4952.9  374.17  4963.1  375.08  4973.3  374.56  4983.5  371.49  4990.7  369.83
  4993.5  369.33  4996.7  369.83  5001.4  372.52  5011.4  372.62  5017.4  373.13
  5026.4  372.29  5032.5  373.98  5053.5  374.19  5076.0  375.51  5083.5  376.28
  5089.5  377.65  5098.6  377.87  5104.6  378.60  5125.6  378.60  5184.2  380.86
#Mann=4,-1,0
  4749.0    0.05       0  4906.6    0.16       0  4990.7    0.07       0
  4996.7    0.16       0
Bank Sta=4990.7,4996.7
Exp/Cntr=0.3,0.1

Type RM Length L Ch R = 1,4873,348,348,348
BEGIN DESCRIPTION:
PARKER BRANCH 10.0
END DESCRIPTION:
XS GIS Cut Line= 3
      3773615.92     10595684.50      3773411.10     10595753.93
      3773216.67     10595865.03
#Sta/Elev= 30
  4771.4  377.91  4778.4  377.63  4788.6  378.12  4830.7  375.89  4836.0  376.01
  4852.0  374.78  4873.1  374.66  4883.7  373.73  4893.5  373.36  4898.8  373.69
  4915.3  372.98  4930.2  371.27  4947.0  367.37  4956.4  367.07  4985.8  367.33
  4992.7  365.20  4997.9  362.73  5000.7  362.23  5003.9  362.73  5008.5  363.53
  5014.3  362.92  5030.1  368.21  5058.5  369.77  5073.3  369.98  5081.5  370.73
  5094.9  370.80  5110.7  371.66  5132.3  372.12  5185.2  375.11  5211.6  375.78
#Mann=3,-1,0
  4771.4    0.16       0  4997.9    0.07       0  5003.9    0.16       0
Bank Sta=4997.9,5003.9
Exp/Cntr=0.3,0.1

Type RM Length L Ch R = 1,4525,433,433,433
BEGIN DESCRIPTION:
PARKER BRANCH 9.0
END DESCRIPTION:
XS GIS Cut Line= 3
      3773449.26     10595351.18      3773230.55     10595496.98
      3773103.45     10595624.08
#Sta/Elev= 30
  4814.0  374.73  4849.6  373.24  4856.5  373.81  4862.5  372.42  4871.5  372.66
  4885.7  371.21  4934.6  368.22  4957.8  365.92  4970.6  363.68  4985.7  362.99
  4990.9  358.65  4993.6  358.15  4996.9  358.65  5000.7  358.67  5015.7  363.33
  5036.7  363.04  5066.0  364.04  5072.8  364.75  5075.2  365.82  5093.9  366.22
  5122.2  368.48  5129.3  368.10  5157.6  369.24  5164.6  371.11  5171.7  370.64
  5178.8  371.46  5185.9  370.78  5192.9  371.75  5235.4  373.72  5256.6  373.81
#Mann=3,-1,0
  4814.0    0.16       0  4990.9    0.07       0  4996.9    0.16       0
Bank Sta=4990.9,4996.9
Exp/Cntr=0.3,0.1

Type RM Length L Ch R = 1,4092,332,332,332
BEGIN DESCRIPTION:
PARKER BRANCH 8.0
END DESCRIPTION:
XS GIS Cut Line= 3
      3772899.61     10595210.16      3772899.61     10595360.19
      3772999.59     10595560.16
#Sta/Elev= 30
  4839.0  371.86  4849.0  371.15  4859.0  371.21  4869.0  369.93  4879.0  370.07
  4889.0  368.82  4909.0  367.04  4919.0  366.65  4929.0  365.36  4939.0  364.86
  4949.0  363.56  4959.0  362.90  4969.0  360.98  4979.0  359.85  4986.5  355.23
  4991.8  355.23  5000.0  354.43  5002.8  353.93  5006.0  354.43  5011.4  359.60
  5047.7  359.71  5070.1  360.91  5078.5  362.49  5159.5  367.45  5167.9  367.65
  5181.9  369.39  5190.3  369.62  5198.7  370.78  5204.3  370.62  5212.6  371.14
#Mann=3,-1,0
  4839.0    0.16       0  5000.0    0.07       0  5006.0    0.16       0
Bank Sta=5000,5006
Exp/Cntr=0.3,0.1

Type RM Length L Ch R = 1,3760,507,507,507
BEGIN DESCRIPTION:
Mapping XS ab5550e7
END DESCRIPTION:
XS GIS Cut Line= 2
      3772625.06     10595097.10      3772562.56     10595722.08
#Sta/Elev= 30
  4702.7  373.46  4736.0  372.51  4786.2  369.87  4816.4  367.23  4896.8  362.48
  4900.1  361.68  4905.0  360.49  4910.0  360.96  4926.9  357.57  4937.0  356.67
  4967.1  356.74  4977.2  357.84  4997.3  353.14  5002.5  353.12  5005.3  352.62
  5008.5  353.12  5010.5  356.01  5017.4  357.20  5027.4  356.88  5047.5  357.94
  5097.8  363.74  5111.0  363.89  5135.1  365.94  5148.0  367.36  5206.5  370.10
  5248.5  370.18  5288.7  371.92  5307.0  371.03  5312.0  368.90  5330.8  369.19
#Mann=5,-1,0
  4702.7     0.1       0  4900.1    0.16       0  5002.5    0.07       0
  5008.5    0.16       0  5135.1     0.1       0
Bank Sta=5002.5,5008.5
Exp/Cntr=0.3,0.1

Type RM Length L Ch R = 1,3253,495,495,495
BEGIN DESCRIPTION:
Mapping XS e3437258
END DESCRIPTION:
XS GIS Cut Line= 2
      3772276.09     10595050.22      3772099.03     10595623.08
#Sta/Elev= 30
  4694.7  372.00  4715.6  370.58  4726.1  370.69  4737.7  369.34  4757.5  368.90
  4770.3  370.40  4797.7  370.62  4802.9  371.70  4835.6  370.54  4873.4  366.31
  4892.5  361.50  4906.1  359.56  4914.5  357.41  4924.9  357.04  4938.7  354.10
  4966.1  352.27  4977.3  350.49  4984.7  346.10  4987.5  345.60  4990.7  346.10
  4998.2  347.81  5004.0  352.72  5029.6  353.31  5036.6  354.80  5107.1  361.44
  5134.3  362.80  5197.1  367.61  5237.6  369.79  5242.9  369.29  5294.3  371.66
#Mann=4,-1,0
  4694.7     0.1       0  4892.5    0.16       0  4984.7    0.07       0
  4990.7    0.16       0
Bank Sta=4984.7,4990.7
Exp/Cntr=0.3,0.1

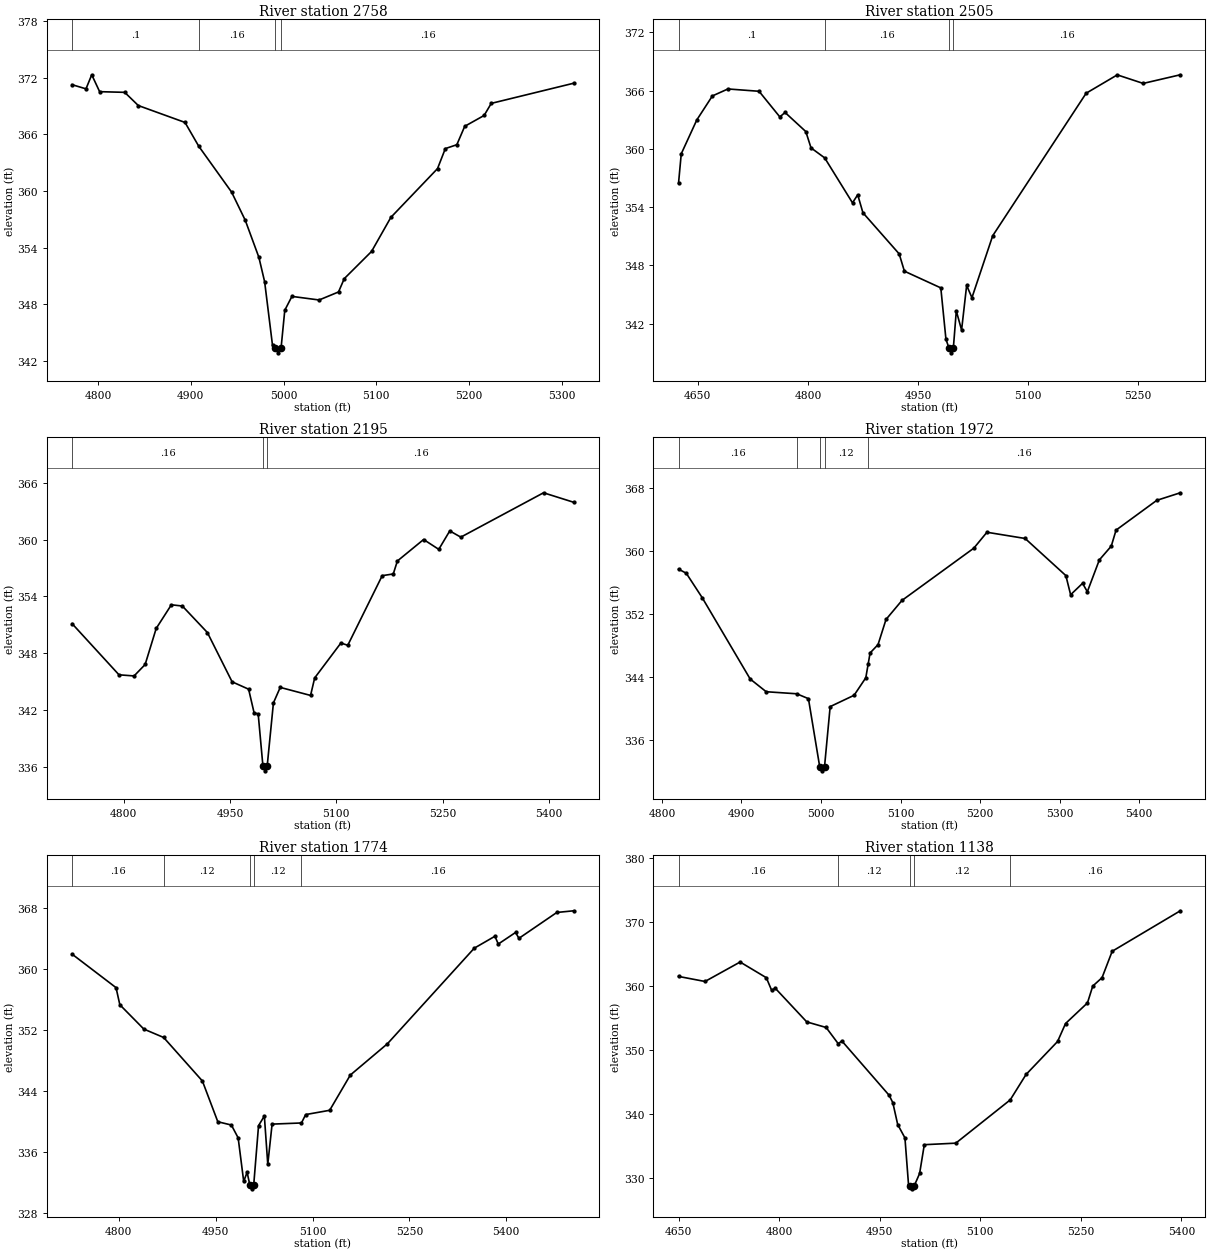
Type RM Length L Ch R = 1,2758,253,253,253
BEGIN DESCRIPTION:
Mapping XS a4e6a232
END DESCRIPTION:
XS GIS Cut Line= 2
      3772125.09     10594925.16      3771687.58     10595242.88
#Sta/Elev= 30
  4772.1  371.26  4787.1  370.82  4793.3  372.31  4801.8  370.52  4828.8  370.45
  4843.5  369.05  4893.8  367.26  4908.6  364.74  4944.0  359.88  4958.7  356.90
  4973.4  352.97  4979.6  350.38  4988.1  343.63  4991.3  343.35  4994.0  342.85
  4997.3  343.35  5001.3  347.36  5009.0  348.83  5038.3  348.45  5059.2  349.30
  5065.4  350.71  5094.8  353.59  5115.6  357.20  5165.9  362.37  5174.3  364.49
  5186.7  364.90  5195.2  366.85  5216.1  368.00  5223.8  369.28  5312.8  371.42
#Mann=4,-1,0
  4772.1     0.1       0  4908.6    0.16       0  4991.3    0.07       0
  4997.3    0.16       0
Bank Sta=4991.3,4997.3
Exp/Cntr=0.3,0.1

Type RM Length L Ch R = 1,2505,310,310,310
BEGIN DESCRIPTION:
Mapping XS 3f136a1f
END DESCRIPTION:
XS GIS Cut Line= 3
      3772019.76     10594665.15      3771791.43     10594892.26
      3771538.83     10595150.94
#Sta/Elev= 30
  4623.7  356.45  4627.4  359.48  4648.6  362.97  4669.8  365.44  4691.0  366.16
  4733.4  365.92  4761.7  363.28  4768.8  363.74  4797.1  361.77  4804.2  360.09
  4822.8  359.06  4860.7  354.43  4867.8  355.26  4874.9  353.41  4924.3  349.17
  4931.4  347.39  4981.0  345.67  4988.0  340.38  4992.1  339.48  4994.9  338.98
  4998.1  339.48  5002.1  343.30  5009.3  341.33  5016.2  345.92  5023.4  344.66
  5051.7  351.04  5179.0  365.72  5221.4  367.61  5256.7  366.73  5307.3  367.62
#Mann=4,-1,0
  4623.7     0.1       0  4822.8    0.16       0  4992.1    0.07       0
  4998.1    0.16       0
Bank Sta=4992.1,4998.1
Exp/Cntr=0.3,0.1

Type RM Length L Ch R = 1,2195,223,223,223
BEGIN DESCRIPTION:
Mapping XS cf7ce0f1
END DESCRIPTION:
XS GIS Cut Line= 2
      3771807.37     10594456.41      3771443.87     10595063.97
#Sta/Elev= 30
  4727.2  351.11  4793.4  345.70  4814.7  345.58  4830.3  346.79  4845.9  350.60
  4867.3  353.10  4882.8  352.97  4918.1  350.17  4953.0  344.96  4976.3  344.18
  4984.0  341.69  4989.8  341.56  4996.5  336.05  4999.3  335.55  5002.5  336.05
  5011.3  342.73  5020.9  344.37  5063.7  343.52  5069.5  345.37  5106.5  349.06
  5116.2  348.82  5164.8  356.18  5180.4  356.36  5186.2  357.73  5223.2  360.00
  5244.6  358.96  5260.1  360.91  5275.7  360.25  5392.4  364.94  5435.2  363.93
#Mann=3,-1,0
  4727.2    0.16       0  4996.5    0.07       0  5002.5    0.16       0
Bank Sta=4996.5,5002.5
Exp/Cntr=0.3,0.1

Type RM Length L Ch R = 1,1972,198,198,198
BEGIN DESCRIPTION:
Mapping XS d6c1e994
END DESCRIPTION:
XS GIS Cut Line= 4
      3771526.71     10594440.49      3771510.92     10594600.82
      3771491.49     10594827.90      3771357.94     10595029.45
#Sta/Elev= 30
  4820.9  357.70  4830.6  357.18  4850.7  354.07  4911.0  343.75  4931.1  342.14
  4969.5  341.88  4984.2  341.26  4998.4  332.60  5001.2  332.10  5004.4  332.60
  5011.5  340.25  5041.6  341.69  5056.3  343.91  5059.4  345.72  5061.7  347.06
  5071.7  348.12  5081.7  351.31  5101.8  353.73  5192.1  360.36  5208.6  362.38
  5256.6  361.59  5307.8  356.88  5313.8  354.45  5328.8  355.90  5334.8  354.83
  5349.9  358.87  5364.9  360.62  5370.9  362.65  5422.1  366.43  5451.7  367.39
#Mann=5,-1,0
  4820.9    0.16       0  4969.5    0.12       0  4998.4    0.07       0
  5004.4    0.12       0  5059.4    0.16       0
Bank Sta=4998.4,5004.4
Exp/Cntr=0.3,0.1

Type RM Length L Ch R = 1,1774,636,636,636
BEGIN DESCRIPTION:
Mapping XS f65dd11c
END DESCRIPTION:
XS GIS Cut Line= 2
      3771437.57     10594305.37      3771198.00     10595044.93
#Sta/Elev= 30
  4727.5  361.98  4795.6  357.59  4801.5  355.35  4838.7  352.16  4869.4  351.06
  4929.4  345.36  4953.3  340.02  4974.3  339.59  4984.8  337.91  4993.4  332.20
  4998.7  333.40  5002.9  331.73  5005.6  331.23  5008.9  331.73  5016.4  339.51
  5025.4  340.77  5030.7  334.45  5037.4  339.71  5082.9  339.86  5089.4  340.96
  5126.6  341.52  5158.6  346.14  5216.1  350.24  5350.6  362.76  5382.6  364.32
  5387.8  363.30  5414.6  364.82  5419.8  364.05  5478.5  367.44  5504.9  367.66
#Mann=5,-1,0
  4727.5    0.16       0  4869.4    0.12       0  5002.9    0.07       0
  5008.9    0.12       0  5082.9    0.16       0
Bank Sta=5002.9,5008.9
Exp/Cntr=0.3,0.1

Type RM Length L Ch R = 1,1138,467,467,467
BEGIN DESCRIPTION:
Mapping XS 9a7b562c
END DESCRIPTION:
XS GIS Cut Line= 2
      3771369.88     10594149.13      3770682.35     10594446.02
#Sta/Elev= 30
  4649.6  361.51  4689.1  360.72  4741.5  363.76  4780.6  361.31  4788.5  359.35
  4794.0  359.66  4841.0  354.40  4869.9  353.53  4887.9  351.00  4893.4  351.42
  4964.0  342.92  4969.4  341.78  4976.7  338.36  4987.5  336.27  4992.9  328.89
  4995.5  328.81  4998.2  328.31  5001.5  328.81  5009.4  330.71  5016.4  335.21
  5063.4  335.45  5144.6  342.21  5168.3  346.19  5215.3  351.34  5227.2  354.15
  5259.9  357.37  5267.8  360.00  5281.7  361.32  5296.8  365.44  5398.5  371.77
#Mann=5,-1,0
  4649.6    0.16       0  4887.9    0.12       0  4995.5    0.07       0
  5001.5    0.12       0  5144.6    0.16       0
Bank Sta=4995.5,5001.5
Exp/Cntr=0.3,0.1

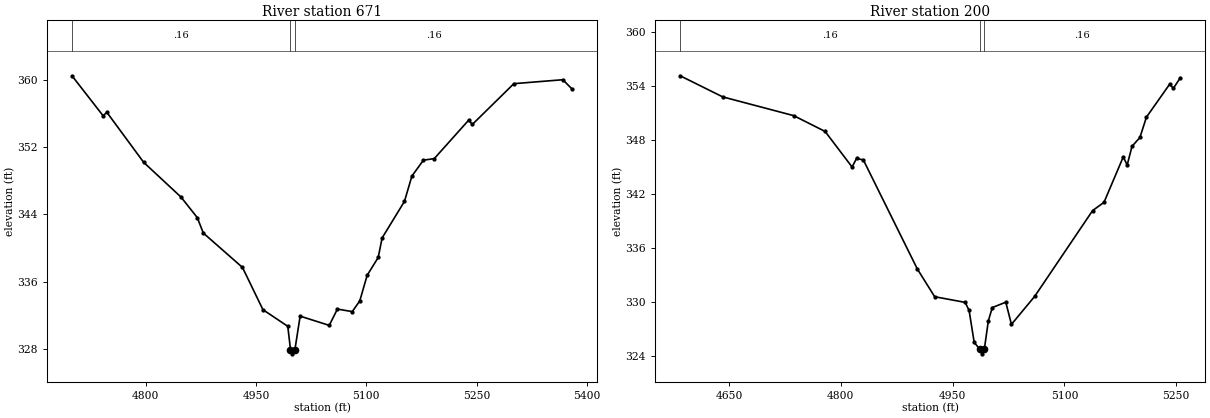
Type RM Length L Ch R = 1,671,471,471,471
BEGIN DESCRIPTION:
Mapping XS 0494a766
END DESCRIPTION:
XS GIS Cut Line= 2
      3771395.89     10593878.31      3770724.33     10593987.63
#Sta/Elev= 30
  4699.6  360.51  4741.9  355.75  4747.0  356.16  4797.1  350.20  4847.8  346.07
  4870.0  343.62  4878.2  341.78  4931.5  337.68  4959.3  332.65  4993.1  330.67
  4996.8  327.89  4999.5  327.39  5002.8  327.89  5009.9  331.88  5049.5  330.78
  5060.6  332.72  5080.8  332.42  5091.0  333.69  5101.1  336.75  5116.1  338.87
  5121.4  341.19  5151.8  345.55  5161.9  348.56  5177.6  350.46  5192.3  350.64
  5239.1  355.22  5244.2  354.72  5300.6  359.57  5367.2  360.04  5380.0  358.91
#Mann=3,-1,0
  4699.6    0.16       0  4996.8    0.07       0  5002.8    0.16       0
Bank Sta=4996.8,5002.8
Exp/Cntr=0.3,0.1

Type RM Length L Ch R = 1,200,0,0,0
BEGIN DESCRIPTION:
PARKER BRANCH 1.0
END DESCRIPTION:
XS GIS Cut Line= 3
      3771307.39     10593711.66      3771036.53     10593534.55
      3770708.38     10593649.14
#Sta/Elev= 30
  4584.4  355.16  4641.5  352.81  4736.8  350.72  4778.9  348.96  4815.1  345.00
  4821.1  345.96  4830.2  345.79  4902.6  333.65  4925.9  330.56  4966.8  329.93
  4972.1  329.03  4978.9  325.48  4986.5  324.70  4989.2  324.20  4992.5  324.70
  4997.9  327.87  5003.2  329.35  5021.3  329.95  5028.9  327.48  5060.0  330.59
  5137.8  340.15  5153.1  341.07  5178.9  346.12  5184.2  345.23  5190.7  347.31
  5201.3  348.29  5210.0  350.55  5241.0  354.20  5246.3  353.78  5255.6  354.95
#Mann=3,-1,0
  4584.4    0.16       0  4986.5    0.07       0  4992.5    0.16       0
Bank Sta=4986.5,4992.5
Exp/Cntr=0.3,0.1

Chan Stop Cuts=-1