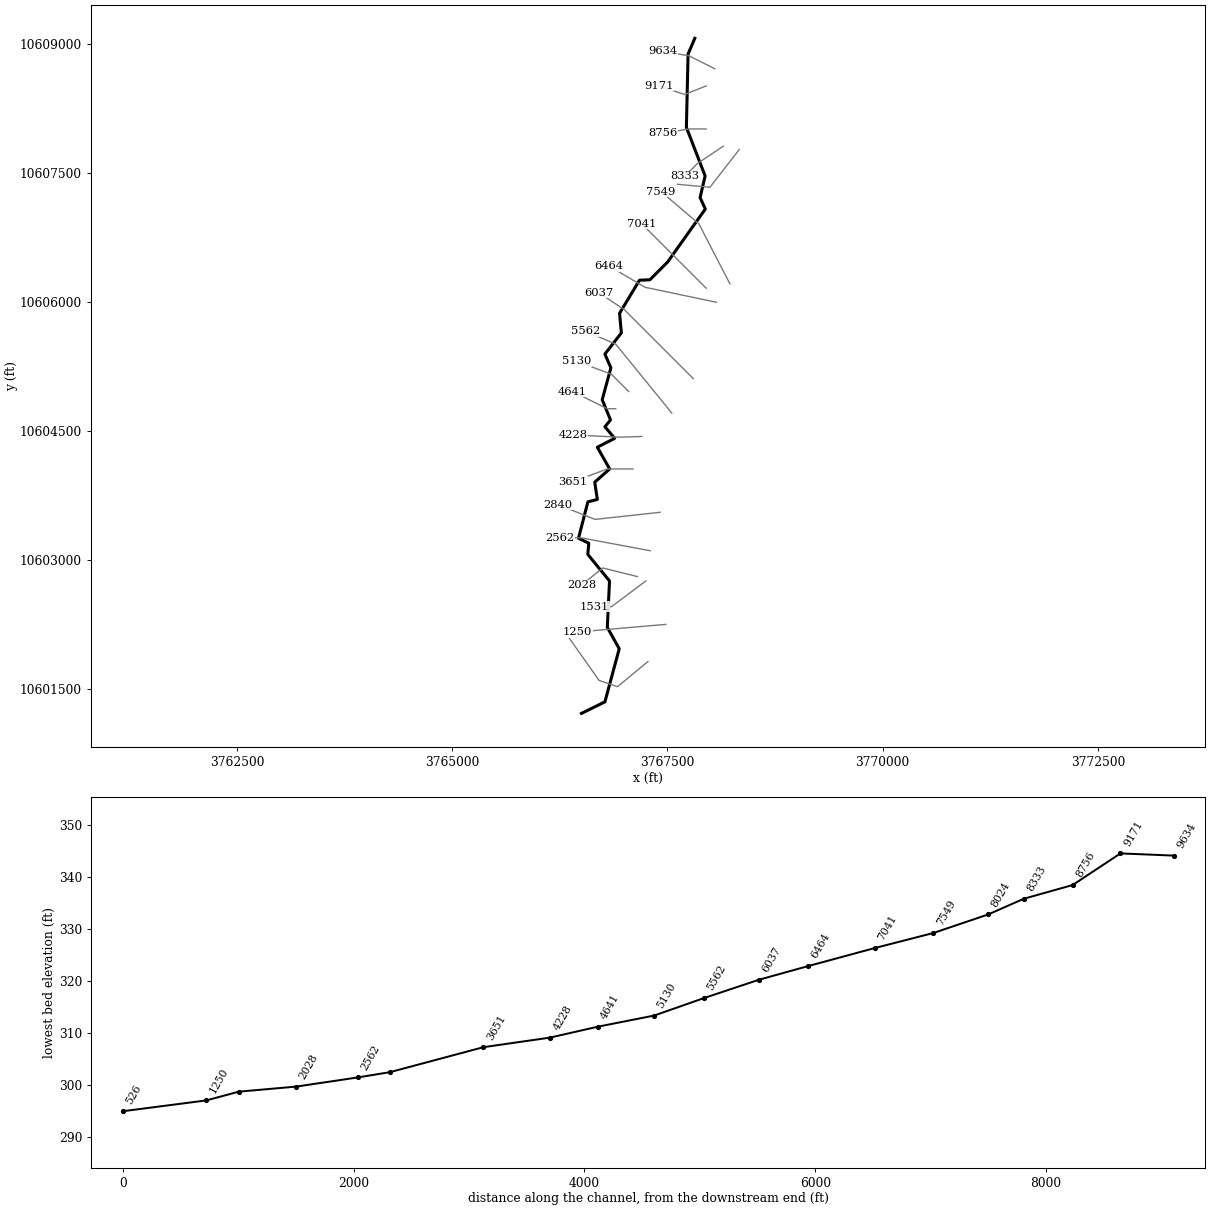
--- SADDLER CREEK.prj (project) ---

Proj Title=SADDLER CREEK Base Level Engineering
Current Plan=p01
Default Exp/Contr=0.3,0.1
English Units
Geom File=g01
Flow File=f01
Plan File=p01
Y Axis Title=Elevation
X Axis Title(PF)=Main Channel Distance
X Axis Title(XS)=Station
BEGIN DESCRIPTION:
SADDLER CREEK
END DESCRIPTION:
DSS Export Rating Curves= 0
DSS Export Rating Curve Sorted= 0
DSS Export Volume Flow Curves= 0
DXF OffsetX= 0
DXF OffsetY= 0
DXF ScaleX= 1
DXF ScaleY= 10

--- SADDLER CREEK.p01 (plan) ---

Plan Title=Multiple Run
Short Identifier=Multiple
Geom File=g01
Flow File=f01
Subcritical Flow
K Sum by GR= 0
Std Step Tol= 0.01
Critical Tol= 0.01
Num of Std Step Trials= 20
Max Error Tol= 0.3
Flow Tol Ratio= 0.001
Split Flow NTrial= 30
Split Flow Tol= 0.02
Split Flow Ratio= 0.02
Log Output Level= 0
Friction Slope Method= 1
Unsteady Friction Slope Method= 2
Unsteady Bridges Friction Slope Method= 1
Parabolic Critical Depth
Global Vel Dist=  1 , 1 , 1
Global Log Level= 0
CheckData=True
Encroach Param= -1, 0, 0, 0
BEGIN DESCRIPTION:
Multiple Run
END DESCRIPTION:

--- SADDLER CREEK.f01 (steady flow) ---

Flow Title=Multiple
Number of Profiles=7
Profile Names=10-year,25-year,50-year,1pct_min,100-year,1pct_plu,500-year
River Rch & RM= SADDLER CREEK,Reach-1,9634
     695     955    1174    1063    1437    1943    2158
River Rch & RM= SADDLER CREEK,Reach-1,7041
    1651    2363    2983    2761    3734    5050    5877
Boundary for River Rch & Prof#=SADDLER CREEK,Reach-1,1
Up Type=0
Dn Type=3
Dn Slope=0.005
Boundary for River Rch & Prof#=SADDLER CREEK,Reach-1,2
Up Type=0
Dn Type=3
Dn Slope=0.005
Boundary for River Rch & Prof#=SADDLER CREEK,Reach-1,3
Up Type=0
Dn Type=3
Dn Slope=0.005
Boundary for River Rch & Prof#=SADDLER CREEK,Reach-1,4
Up Type=0
Dn Type=3
Dn Slope=0.005
Boundary for River Rch & Prof#=SADDLER CREEK,Reach-1,5
Up Type=0
Dn Type=3
Dn Slope=0.005
Boundary for River Rch & Prof#=SADDLER CREEK,Reach-1,6
Up Type=0
Dn Type=3
Dn Slope=0.005
Boundary for River Rch & Prof#=SADDLER CREEK,Reach-1,7
Up Type=0
Dn Type=3
Dn Slope=0.005

--- SADDLER CREEK.g01 (geometry) ---

Geom Title=Existing Conditions
Program Version=4.10

River Reach=SADDLER CREEK   ,Reach-1
Reach XY= 30
      3767817.57     10609062.88       3767739.5       10608880.
        3767720.       10608029.       3767937.5       10607464.
      3767879.25       10607213.        3767940.       10607080.
       3767501.5       10606464.        3767296.       10606258.
      3767175.25       10606253.       3766943.5       10605869.
      3766964.75       10605641.      3766773.25       10605395.
        3766843.       10605235.        3766742.       10604865.
       3766838.5       10604630.      3766773.75       10604551.
        3766887.       10604416.       3766685.5       10604313.
      3766828.75       10604060.      3766655.25       10603907.
      3766685.25       10603706.       3766575.5       10603678.
       3766466.5       10603255.        3766586.       10603198.
      3766574.75       10603068.        3766827.       10602759.
      3766801.25       10602221.      3766939.75       10601971.
       3766773.5       10601355.       3766501.5       10601221.

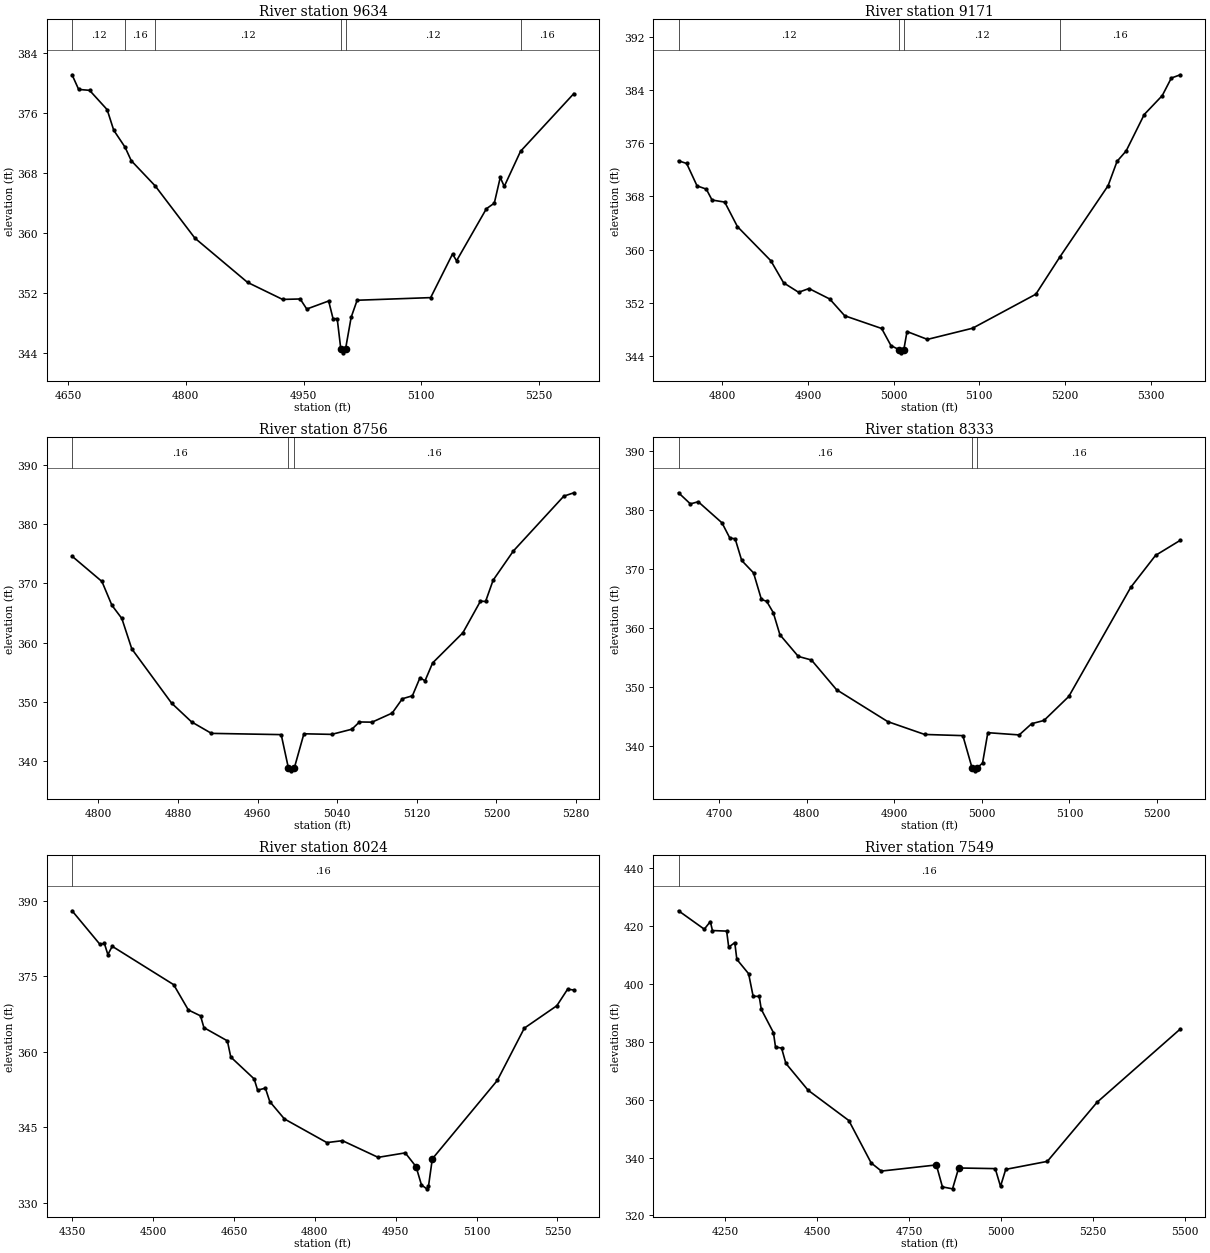
Type RM Length L Ch R = 1 ,9634    ,463,463,463
BEGIN DESCRIPTION:
SADDLER CREEK 19.0
END DESCRIPTION:
XS GIS Cut Line= 3
      3768049.59      10608710.2      3767749.61     10608860.19
      3767449.64     10608910.18
#Sta/Elev= 30
    4655  381.08  4663.4  379.13  4677.3  379.01  4699.7  376.44  4708.1   373.7
  4722.6  371.43  4730.4  369.65  4761.1  366.27  4811.5  359.34  4878.6  353.45
  4923.3  351.18  4945.7  351.24  4954.1   349.9    4982  350.97  4987.6  348.62
  4992.9  348.62  4997.5  344.57  5000.3  344.07  5003.5  344.57  5010.7  348.81
  5018.3  351.07    5112  351.42  5139.9  357.23    5145  356.32    5183  363.25
  5193.1  363.99  5200.7  367.42  5205.8  366.22  5226.5  370.89  5294.5  378.58
#Mann= 6 ,-1 , 0
    4655     .12       0  4722.6     .16       0  4761.1     .12       0
  4997.5     .07       0  5003.5     .12       0  5226.5     .16       0
Bank Sta=4997.5,5003.5
XS Rating Curve= 0 ,0
Exp/Cntr=0.3,0.1

Type RM Length L Ch R = 1 ,9171    ,415,415,415
BEGIN DESCRIPTION:
SADDLER CREEK 18.0
END DESCRIPTION:
XS GIS Cut Line= 3
      3767949.65      10608510.2      3767699.61     10608410.19
      3767399.64     10608510.18
#Sta/Elev= 30
    4749  373.35  4758.5  372.94  4770.6  369.58  4781.4  369.09  4788.1  367.45
  4802.9  367.14  4817.7  363.46  4856.7  358.33  4871.6  355.01  4889.1  353.59
  4901.2  354.15  4925.4  352.58  4942.9  350.06    4986  348.15  4996.8  345.59
  5005.9  344.99  5008.6  344.49  5011.9  344.99  5015.6  347.69  5039.4  346.51
  5092.1  348.19  5165.9   353.3  5193.6  358.83  5250.2   369.6  5260.7  373.27
  5271.3  374.83  5292.4   380.3  5313.4  383.14    5324  385.78  5334.5  386.27
#Mann= 4 ,-1 , 0
    4749     .12       0  5005.9     .07       0  5011.9     .12       0
  5193.6     .16       0
Bank Sta=5005.9,5011.9
XS Rating Curve= 0 ,0
Exp/Cntr=0.3,0.1

Type RM Length L Ch R = 1 ,8756    ,423,423,423
BEGIN DESCRIPTION:
SADDLER CREEK 17.0
END DESCRIPTION:
XS GIS Cut Line= 3
      3767949.59     10608010.19      3767749.61     10608010.19
      3767449.62     10607960.19
#Sta/Elev= 30
  4773.7  374.56  4803.7   370.3  4813.7   366.3  4823.7  364.07  4833.7  358.95
  4873.7  349.81  4893.7  346.66  4913.7  344.72  4983.8  344.51    4991  338.91
  4993.7  338.41    4997  338.91  5006.6  344.65  5034.5  344.55  5054.8  345.42
  5062.4  346.64  5075.1  346.61  5095.3  348.14  5105.5  350.55  5115.6  351.05
  5123.2  354.08  5128.3  353.58  5135.9  356.58  5166.3  361.66    5184     367
  5189.1  366.93  5196.7  370.52    5217  375.43  5267.7  384.67  5277.8  385.24
#Mann= 3 ,-1 , 0
  4773.7     .16       0    4991     .07       0    4997     .16       0
Bank Sta=4991,4997
XS Rating Curve= 0 ,0
Exp/Cntr=0.3,0.1

Type RM Length L Ch R = 1 ,8333    ,309,309,309
BEGIN DESCRIPTION:
SADDLER CREEK 16.0
END DESCRIPTION:
XS GIS Cut Line= 3
      3768149.59     10607810.18      3767849.61     10607610.19
      3767699.59     10607460.16
#Sta/Elev= 30
  4653.9  382.85  4667.4  380.97  4676.4  381.33  4703.5  377.76  4712.5  375.17
  4718.5  375.07    4726  371.39  4739.5  369.29  4748.5  364.79  4754.5  364.48
    4762  362.57  4769.6  358.82  4790.6  355.15  4805.6  354.54  4834.2  349.52
  4892.7  344.11  4934.8  341.94  4978.4  341.74  4988.9  336.28  4991.7  335.78
  4994.9  336.28  5000.9  337.11  5006.9  342.24  5042.7  341.86  5056.9  343.76
    5071  344.31  5099.3  348.37    5170  366.84  5198.3  372.25  5226.6  374.81
#Mann= 3 ,-1 , 0
  4653.9     .16       0  4988.9     .07       0  4994.9     .16       0
Bank Sta=4988.9,4994.9
XS Rating Curve= 0 ,0
Exp/Cntr=0.3,0.1

Type RM Length L Ch R = 1 ,8024    ,475,475,475
BEGIN DESCRIPTION:
SADDLER CREEK 15.0
END DESCRIPTION:
XS GIS Cut Line= 3
      3768333.41     10607770.07       3767993.1     10607332.53
      3767618.11     10607367.25
#Sta/Elev= 30
  4349.7  387.96  4401.6  381.27  4409.7  381.48  4416.1  379.26  4424.2  380.91
  4538.2  373.29  4565.4  368.27    4588   367.1  4594.3  364.76  4637.8  362.14
  4644.1  358.93  4687.5  354.58  4693.9  352.35  4708.3  352.75  4716.5  350.08
  4743.6  346.64  4822.4  341.94  4851.3  342.32  4917.5  339.01  4967.8   339.9
  4987.8  337.17  4997.9  333.53  5007.7  332.76  5010.9  333.26    5018  338.71
  5138.5  354.27  5188.7  364.66    5249  369.11    5269  372.39  5280.6  372.23
#Mann= 1 ,-1 , 0
  4349.7     .16       0
Bank Sta=4987.8,5018
XS Rating Curve= 0 ,0
Exp/Cntr=0.3,0.1

Type RM Length L Ch R = 1 ,7549    ,508,508,508
BEGIN DESCRIPTION:
SADDLER CREEK 14.0
END DESCRIPTION:
XS GIS Cut Line= 3
      3768225.72     10606211.03      3767864.63     10606908.91
      3767424.13     10607283.51
#Sta/Elev= 30
  4123.2  425.18  4193.2  418.83  4209.7  421.46  4215.3  418.36    4254  418.16
  4259.6  412.62  4276.1  414.18  4281.7  408.41  4313.7  403.45    4326  395.66
  4342.5  395.63  4348.1  391.18  4381.2  383.11  4386.8  378.15  4403.3  377.79
    4415   372.5  4475.4  363.24  4586.1  352.78  4646.8  338.14  4674.6  335.33
    4824  337.45  4840.5  329.87    4868   329.2  4884.7   336.4  4984.1  336.18
  4998.4  330.06  5012.6  335.92  5125.7  338.68  5260.8  359.07  5487.2  384.38
#Mann= 1 ,-1 , 0
  4123.2     .16       0
Bank Sta=4824,4884.7
XS Rating Curve= 0 ,0
Exp/Cntr=0.3,0.1

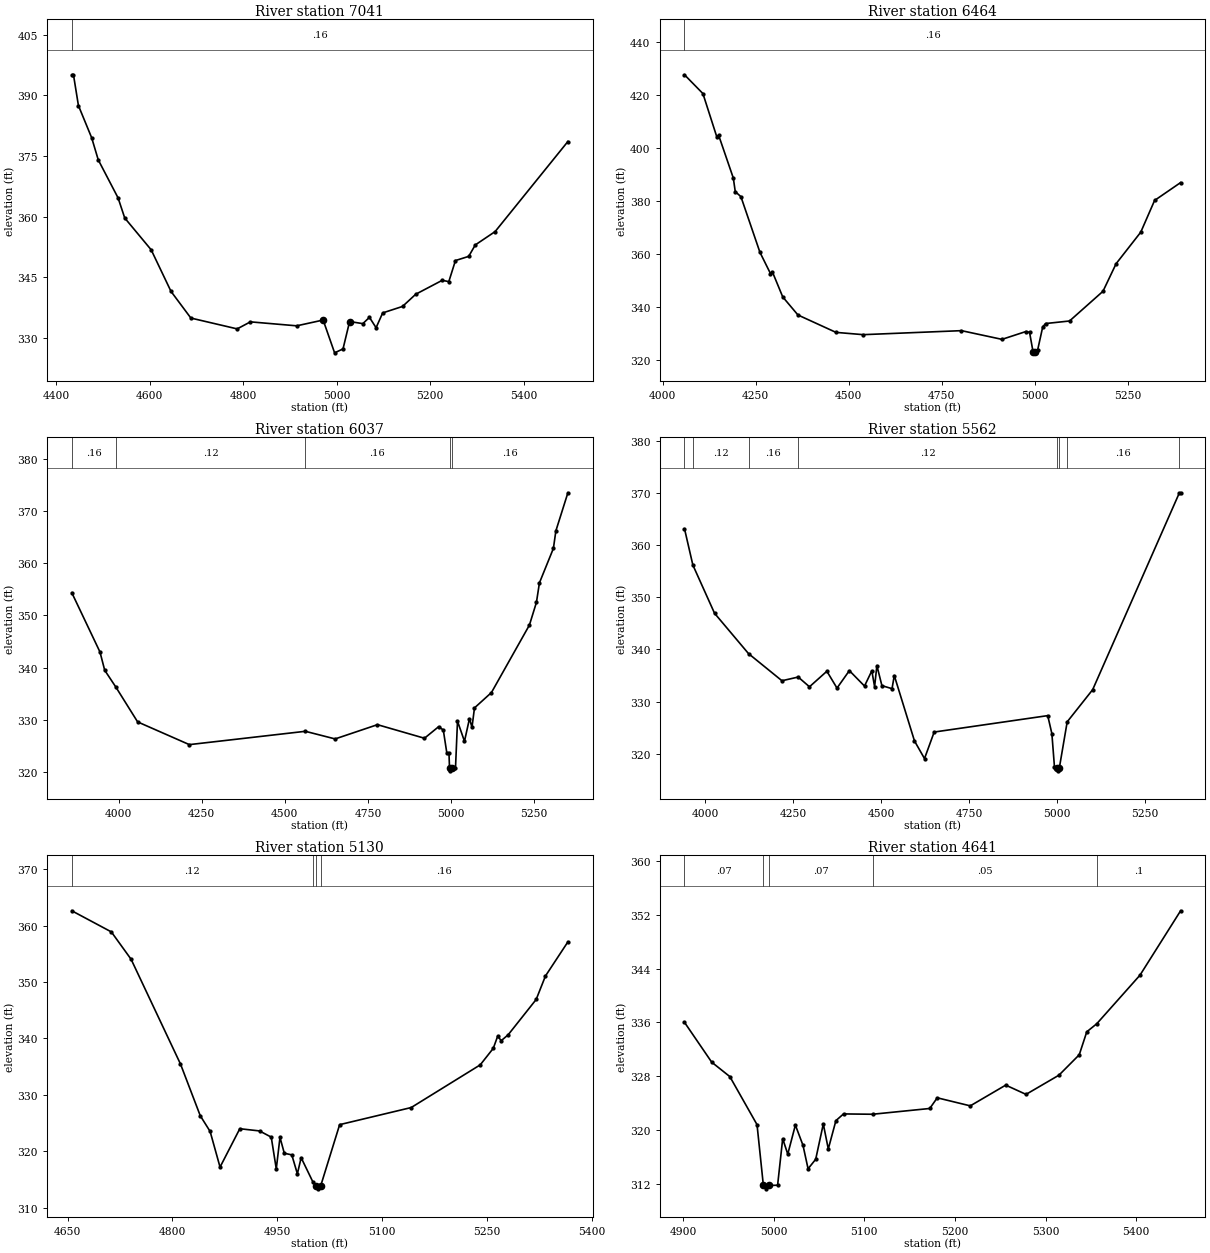
Type RM Length L Ch R = 1 ,7041    ,577,577,577
BEGIN DESCRIPTION:
SADDLER CREEK 13.0
END DESCRIPTION:
XS GIS Cut Line= 3
      3767949.64     10606160.16      3767549.61     10606560.19
      3767199.61     10606910.19
#Sta/Elev= 30
  4433.8  395.06  4437.4  395.06    4448  387.45  4476.3  379.49  4490.4  374.02
  4532.8  364.61    4547  359.65  4603.5  351.79    4646  341.49  4688.4  334.91
  4787.4  332.23  4815.7  333.97  4914.7  332.99  4971.2  334.42  4995.7  326.31
  5013.7  327.28  5027.8  334.05  5056.1  333.53  5070.2  335.09  5084.4  332.52
  5098.5  336.18  5140.9  337.78  5169.2   340.8  5225.8  344.24  5239.9  343.92
  5254.1  349.13  5282.4  350.16  5296.5  352.99  5338.9  356.29  5494.5  378.56
#Mann= 1 ,-1 , 0
  4433.8     .16       0
Bank Sta=4971.2,5027.8
XS Rating Curve= 0 ,0
Exp/Cntr=0.3,0.1

Type RM Length L Ch R = 1 ,6464    ,427,427,427
BEGIN DESCRIPTION:
SADDLER CREEK 12.0
END DESCRIPTION:
XS GIS Cut Line= 3
      3768068.02     10605997.14      3767241.19     10606170.75
      3766820.16     10606418.16
#Sta/Elev= 30
  4058.6  427.63  4108.1  420.54  4145.1  404.37  4150.2   404.9  4189.8  388.71
    4195   383.6  4210.2   381.7  4261.3  360.74  4289.7   352.7  4294.8  353.36
  4322.6  343.92  4363.5  337.11  4465.7  330.56    4539   329.7  4802.9  331.21
  4911.7  327.93  4976.1  330.88  4985.9  330.57  4995.1  323.35  4997.8  322.85
  5001.1  323.35  5007.4  323.79  5021.3  332.65  5028.9  333.89  5093.3  334.85
  5183.2  346.05  5218.5  356.45  5284.7  368.32  5321.9  380.28  5391.8  387.01
#Mann= 1 ,-1 , 0
  4058.6     .16       0
Bank Sta=4995.1,5001.1
XS Rating Curve= 0 ,0
Exp/Cntr=0.3,0.1

Type RM Length L Ch R = 1 ,6037    ,475,475,475
BEGIN DESCRIPTION:
SADDLER CREEK 11.0
END DESCRIPTION:
XS GIS Cut Line= 3
      3767799.59     10605110.21      3766999.61     10605910.19
      3766699.61     10606110.19
#Sta/Elev= 30
  3859.2  354.33    3944  342.97  3958.2  339.48  3991.8  336.25  4057.2  329.59
  4212.7  325.24  4561.5  327.79  4651.1  326.33  4778.4  329.06  4919.8  326.46
  4962.3  328.67  4976.4  328.05    4987  323.65  4993.5  323.65  4995.1  320.72
  4997.8  320.22  5001.1  320.72  5013.1  320.76  5019.1  329.73  5040.1  325.88
  5055.1  330.21  5062.7  328.56  5070.2  332.27  5121.2  335.21  5235.4  348.13
  5256.5  352.48  5265.5  356.21  5307.5  362.81    5315  366.18  5351.1  373.46
#Mann= 5 ,-1 , 0
  3859.2     .16       0  3991.8     .12       0  4561.5     .16       0
  4995.1     .07       0  5001.1     .16       0
Bank Sta=4995.1,5001.1
XS Rating Curve= 0 ,0
Exp/Cntr=0.3,0.1

Type RM Length L Ch R = 1 ,5562    ,432,432,432
BEGIN DESCRIPTION:
SADDLER CREEK 10.0
END DESCRIPTION:
XS GIS Cut Line= 3
      3767549.62     10604710.17      3766899.61     10605510.19
       3766549.6     10605660.19
#Sta/Elev= 30
  3940.8  363.14  3964.6  356.18  4026.3  346.93    4123  339.19  4218.1  333.99
  4264.3   334.7  4296.4  332.83  4345.9  335.81  4374.7  332.58  4409.9  335.93
    4453  332.97  4473.8  335.89  4481.7  332.85  4488.2   336.9  4502.5  333.05
  4531.3  332.47  4537.7  334.99  4595.2  322.44  4623.7  319.06  4651.2  324.15
  4974.3   327.3  4986.1  323.85  4993.4  317.52  5001.2  317.21    5004  316.71
  5007.2  317.21  5029.7  326.11  5102.2  332.28  5348.9  370.03  5352.4  370.04
#Mann= 8 ,-1 , 0
  3940.8     .16       0  3964.6     .12       0    4123     .16       0
  4264.3     .12       0  5001.2     .07       0  5007.2     .12       0
  5029.7     .16       0  5348.9     .12       0
Bank Sta=5001.2,5007.2
XS Rating Curve= 0 ,0
Exp/Cntr=0.3,0.1

Type RM Length L Ch R = 1 ,5130    ,489,489,489
BEGIN DESCRIPTION:
SADDLER CREEK 9.0
END DESCRIPTION:
XS GIS Cut Line= 3
      3767049.64     10604960.16      3766849.61     10605160.19
      3766449.59      10605310.2
#Sta/Elev= 30
  4656.1  362.61  4712.7  358.87    4741  354.02  4811.7  335.46    4840   326.3
  4854.1  323.52  4868.3   317.2  4896.6     324  4924.8  323.61  4941.6  322.51
  4948.8  316.88  4954.1  322.47  4960.3  319.65    4971  319.37    4979  316.01
  4984.4  318.87  5001.4  314.52  5006.3  313.85    5009  313.35  5012.3  313.85
  5039.5  324.72  5141.9  327.75  5240.7  335.31  5259.4  338.24  5265.6  340.36
  5270.9  339.61  5280.7  340.64  5320.8   346.9  5334.1  351.06  5366.2   357.1
#Mann= 4 ,-1 , 0
  4656.1     .12       0  5001.4     .16       0  5006.3     .07       0
  5012.3     .16       0
Bank Sta=5006.3,5012.3
XS Rating Curve= 0 ,0
Exp/Cntr=0.3,0.1

Type RM Length L Ch R = 1 ,4641    ,413,413,413
BEGIN DESCRIPTION:
SADDLER CREEK 8.0
END DESCRIPTION:
XS GIS Cut Line= 3
      3766899.56     10604760.19      3766799.61     10604760.19
      3766399.58      10604960.2
#Sta/Elev= 30
  4901.7  336.01  4931.7  330.08  4951.7  327.93  4981.7  320.77  4988.7  311.71
  4991.4  311.21  4994.7  311.71  5004.4  311.75    5010  318.68  5015.6  316.38
    5024  320.71  5032.4  317.69    5038   314.2  5046.4  315.61  5054.8  320.87
  5060.3  317.15  5068.7  321.37  5077.1  322.37  5109.1  322.32  5172.2  323.18
  5180.5  324.77  5216.9  323.57    5256  326.66  5278.4  325.28  5314.7  328.14
  5337.1  331.18  5345.4   334.6  5356.4   335.8  5404.1  343.04  5448.9  352.63
#Mann= 5 ,-1 , 0
  4901.7     .07       0  4988.7     .07       0  4994.7     .07       0
  5109.1     .05       0  5356.4      .1       0
Bank Sta=4988.7,4994.7
XS Rating Curve= 0 ,0
Exp/Cntr=0.3,0.1

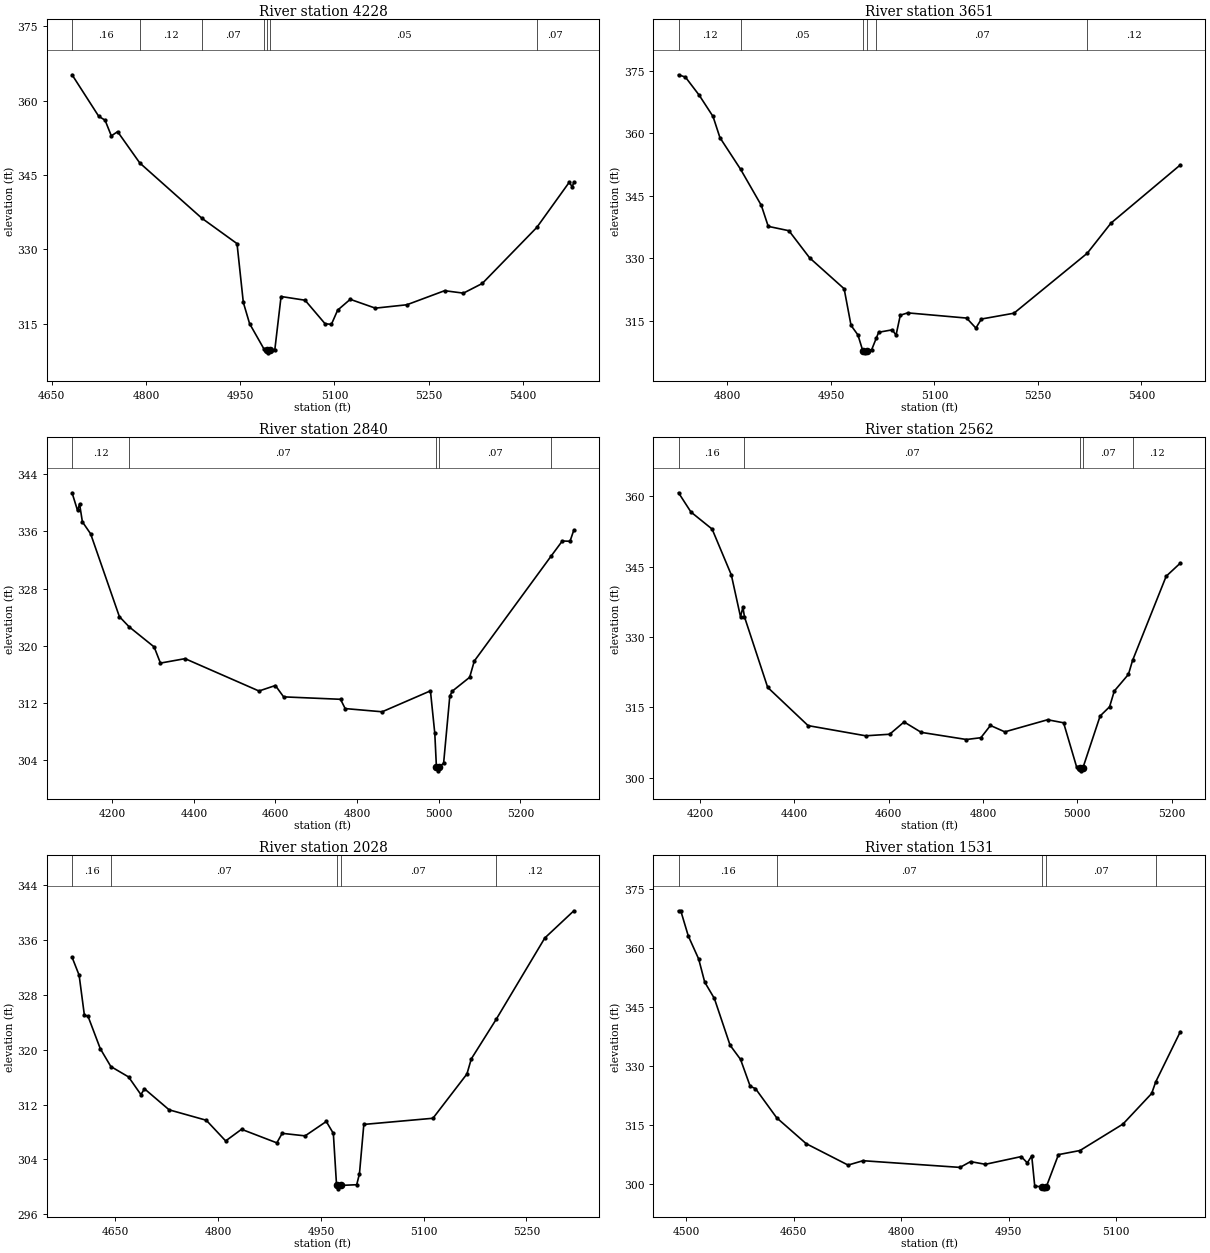
Type RM Length L Ch R = 1 ,4228    ,577,577,577
BEGIN DESCRIPTION:
SADDLER CREEK 7.0
END DESCRIPTION:
XS GIS Cut Line= 3
      3767202.04     10604438.06      3766950.34     10604429.38
      3766404.01     10604455.39
#Sta/Elev= 30
  4682.4  365.24  4724.9  356.85  4734.9  356.08  4744.9  352.91  4754.9  353.76
  4790.2  347.44    4889  336.29    4945  331.16    4955  319.31    4965  315.01
    4988  309.87    4992  309.62  4994.8  309.12    4998  309.62  5005.1  309.68
  5015.1  320.49  5053.3  319.74  5085.1     315  5095.2  314.86  5105.2  317.74
  5125.2  319.92  5165.2  318.14  5215.3  318.82  5275.4  321.66  5305.4  321.17
  5335.4  323.12  5422.2  334.43  5473.7  343.52  5478.7  342.63  5481.2   343.6
#Mann= 7 ,-1 , 0
  4682.4     .16       0  4790.2     .12       0    4889     .07       0
    4988     .05       0    4992    .035       0    4998     .05       0
  5422.2     .07       0
Bank Sta=4992,4998
XS Rating Curve= 0 ,0
Exp/Cntr=0.3,0.1

Type RM Length L Ch R = 1 ,3651    ,811,811,811
BEGIN DESCRIPTION:
SADDLER CREEK 6.0
END DESCRIPTION:
XS GIS Cut Line= 3
      3767099.66     10604060.19      3766799.61     10604060.19
      3766399.65     10603910.21
#Sta/Elev= 30
  4729.1  374.07  4739.1  373.51  4759.1  369.15  4779.1  364.05  4789.1  358.97
    4819  351.38  4849.1  342.69  4859.1  337.66  4889.1  336.61  4919.1  330.09
  4969.1  322.67  4979.1  313.87  4989.1  311.57  4996.1  307.78  4998.9  307.28
  5002.1  307.78  5009.1  308.08  5015.7  310.81  5019.1  312.22  5038.9  312.81
  5044.3  311.52  5050.5  316.32  5061.2  316.88  5146.6  315.63    5160  313.23
    5168   315.4  5215.2   316.8  5321.4   331.2  5355.8  338.44  5456.3  352.42
#Mann= 6 ,-1 , 0
  4729.1     .12       0    4819     .05       0  4996.1    .035       0
  5002.1     .05       0  5015.7     .07       0  5321.4     .12       0
Bank Sta=4996.1,5002.1
XS Rating Curve= 0 ,0
Exp/Cntr=0.3,0.1

Type RM Length L Ch R = 1 ,2840    ,278,278,278
BEGIN DESCRIPTION:
SADDLER CREEK 5.0
END DESCRIPTION:
XS GIS Cut Line= 3
       3767414.8     10603556.99      3766659.54     10603474.52
      3766222.88     10603647.45
#Sta/Elev= 30
  4101.7  341.42  4115.1  338.94  4120.1  339.85    4127  337.35  4147.2  335.67
  4217.6  324.08  4241.3  322.66  4302.8  319.83  4318.2  317.57  4378.5  318.19
  4559.6  313.66  4599.8  314.43    4620  312.84  4759.4   312.5  4770.8   311.2
  4861.4  310.75  4979.7  313.68  4990.4  307.72  4994.4  302.98  4997.2  302.48
  5000.4  302.98    5012  303.55  5027.2  312.97  5033.5  313.65  5075.8  315.58
  5087.2  317.86  5276.1  332.61  5302.8  334.67  5321.7  334.63  5331.1  336.21
#Mann= 5 ,-1 , 0
  4101.7     .12       0  4241.3     .07       0  4994.4     .07       0
  5000.4     .07       0  5276.1     .12       0
Bank Sta=4994.4,5000.4
XS Rating Curve= 0 ,0
Exp/Cntr=0.3,0.1

Type RM Length L Ch R = 1 ,2562    ,534,534,534
BEGIN DESCRIPTION:
SADDLER CREEK 4.0
END DESCRIPTION:
XS GIS Cut Line= 3
      3767299.59     10603110.19      3766499.61     10603260.19
      3766249.63     10603260.19
#Sta/Elev= 30
  4154.4  360.74  4180.7  356.64  4225.6     353  4266.3  343.24  4285.8  334.31
  4290.9  336.34  4294.2  334.29  4343.4  319.26  4429.1  311.11  4551.2  308.94
    4602  309.27  4632.6  311.89    4669  309.67  4764.8  308.15  4795.4  308.53
  4815.7  311.14  4846.2  309.78  4936.9  312.36  4970.8  311.71  4998.3  302.34
  5005.3  301.97  5008.1  301.47  5011.3  301.97  5048.3  313.17  5068.3  315.12
  5078.3  318.48  5108.3  322.04    5117  324.99  5188.3  342.95  5218.3  345.75
#Mann= 5 ,-1 , 0
  4154.4     .16       0  4294.2     .07       0  5005.3     .07       0
  5011.3     .07       0    5117     .12       0
Bank Sta=5005.3,5011.3
XS Rating Curve= 0 ,0
Exp/Cntr=0.3,0.1

Type RM Length L Ch R = 1 ,2028    ,497,497,497
BEGIN DESCRIPTION:
SADDLER CREEK 3.0
END DESCRIPTION:
XS GIS Cut Line= 3
      3767149.61     10602810.19      3766749.61     10602910.19
      3766499.59     10602710.17
#Sta/Elev= 30
  4586.7  333.51    4597  330.89  4604.7  325.03  4609.9  324.92  4627.9  320.16
  4643.3  317.56  4669.2  316.04  4687.2  313.46  4692.4  314.31  4728.4  311.24
  4782.6  309.72  4810.9   306.7  4834.1   308.4  4885.6  306.42  4893.4  307.81
  4926.9  307.44  4957.8  309.54  4968.1   307.8  4972.8  300.21  4975.6  299.71
  4978.8  300.21  5002.2  300.31  5006.2   301.9  5012.6  309.11  5113.5  310.01
  5163.1  316.47  5169.5  318.68  5205.7  324.43  5276.8  336.32  5319.2  340.29
#Mann= 5 ,-1 , 0
  4586.7     .16       0  4643.3     .07       0  4972.8     .07       0
  4978.8     .07       0  5205.7     .12       0
Bank Sta=4972.8,4978.8
XS Rating Curve= 0 ,0
Exp/Cntr=0.3,0.1

Type RM Length L Ch R = 1 ,1531    ,281,281,281
BEGIN DESCRIPTION:
SADDLER CREEK 2.0
END DESCRIPTION:
XS GIS Cut Line= 3
      3767249.62     10602760.19      3766849.61     10602460.19
      3766649.62     10602460.19
#Sta/Elev= 30
  4489.6  369.43  4492.7  369.43  4503.2  363.03  4517.7  357.17  4526.1   351.3
  4539.6  347.13  4561.5  335.25  4576.1  331.65  4589.6  324.79  4596.9  324.23
  4626.6  316.79  4667.7  310.22  4726.1  304.78  4746.9  305.89  4882.3  304.19
  4896.9  305.66  4917.7  304.98  4967.7  306.94  4976.1  305.34  4982.3  307.12
  4986.5  299.44  4996.6  299.24  4999.4  298.74  5002.6  299.24  5019.6  307.44
  5049.6  308.48  5109.6  315.21  5149.6  322.98  5155.3  325.94  5189.6  338.69
#Mann= 5 ,-1 , 0
  4489.6     .16       0  4626.6     .07       0  4996.6     .07       0
  5002.6     .07       0  5155.3     .12       0
Bank Sta=4996.6,5002.6
XS Rating Curve= 0 ,0
Exp/Cntr=0.3,0.1

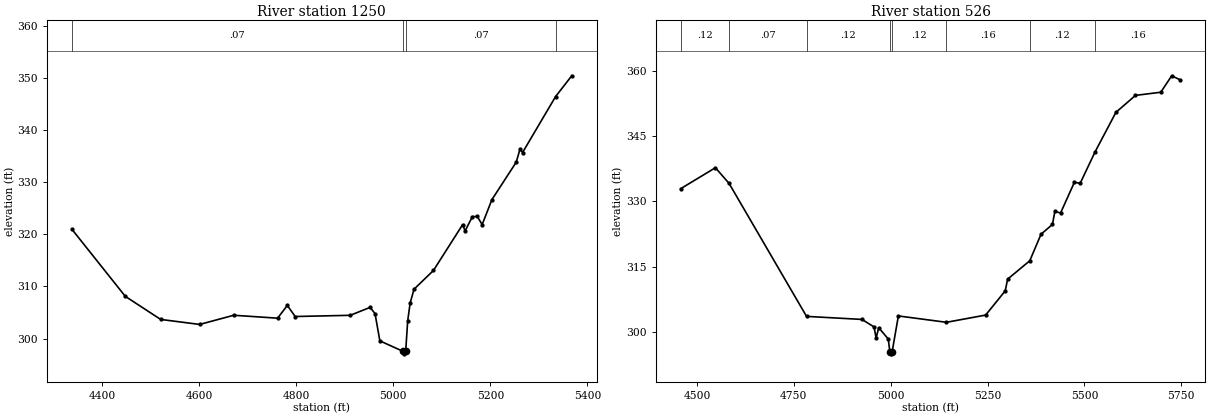
Type RM Length L Ch R = 1 ,1250    ,724,724,724
BEGIN DESCRIPTION:
Mapping XS 91fb2b8b
END DESCRIPTION:
XS GIS Cut Line= 2
      3767481.76     10602254.84      3766455.68     10602166.29
#Sta/Elev= 30
  4337.7  320.94  4447.6  308.09  4520.5  303.66  4600.8   302.7  4671.1  304.46
  4761.4   303.9  4781.5  306.34  4797.7  304.22  4911.1  304.45  4952.1  305.97
  4962.2  304.78  4972.2  299.55  5019.4  297.56  5022.1  297.06  5025.4  297.56
  5029.5  303.34  5034.5  306.75  5042.5  309.45  5082.6  313.05  5142.8  321.85
  5147.8  320.64  5162.9  323.38  5172.9  323.41    5183  321.86  5203.1  326.64
  5253.2  333.83  5261.2   336.4  5266.2  335.67  5334.3  346.41  5367.6   350.4
#Mann= 4 ,-1 , 0
  4337.7     .07       0  5019.4     .07       0  5025.4     .07       0
  5334.3     .16       0
Bank Sta=5019.4,5025.4
XS Rating Curve= 0 ,0
Exp/Cntr=0.3,0.1

Type RM Length L Ch R = 1 ,526     ,0,0,0
BEGIN DESCRIPTION:
SADDLER CREEK 1.0
END DESCRIPTION:
XS GIS Cut Line= 4
      3767273.39     10601822.54      3766919.23     10601530.88
      3766705.69     10601603.79      3766356.74     10602098.57
#Sta/Elev= 30
  4457.8  332.89  4547.5  337.71  4582.7  334.12  4782.7  303.58  4925.7  302.88
    4957  301.16  4962.3  298.59    4969  300.98  4993.6  298.39  4997.7  295.48
  5000.5  294.98  5003.7  295.48  5019.7  303.68  5143.8  302.22    5245  303.88
  5295.5  309.44  5301.7  312.13  5358.9  316.35  5387.9  322.44  5417.4  324.69
  5423.6  327.67  5438.4  327.32  5474.1  334.38  5488.9  334.12  5527.4  341.35
  5581.2  350.42  5631.7  354.32    5697  355.04  5725.2  358.82  5747.7  357.85
#Mann= 8 ,-1 , 0
  4457.8     .12       0  4582.7     .07       0  4782.7     .12       0
  4997.7     .07       0  5003.7     .12       0  5143.8     .16       0
  5358.9     .12       0  5527.4     .16       0
Bank Sta=4997.7,5003.7
XS Rating Curve= 0 ,0
Exp/Cntr=0.3,0.1

Chan Stop Cuts=-1
Use User Specified Reach Order=0
Composite Channel Slope=5