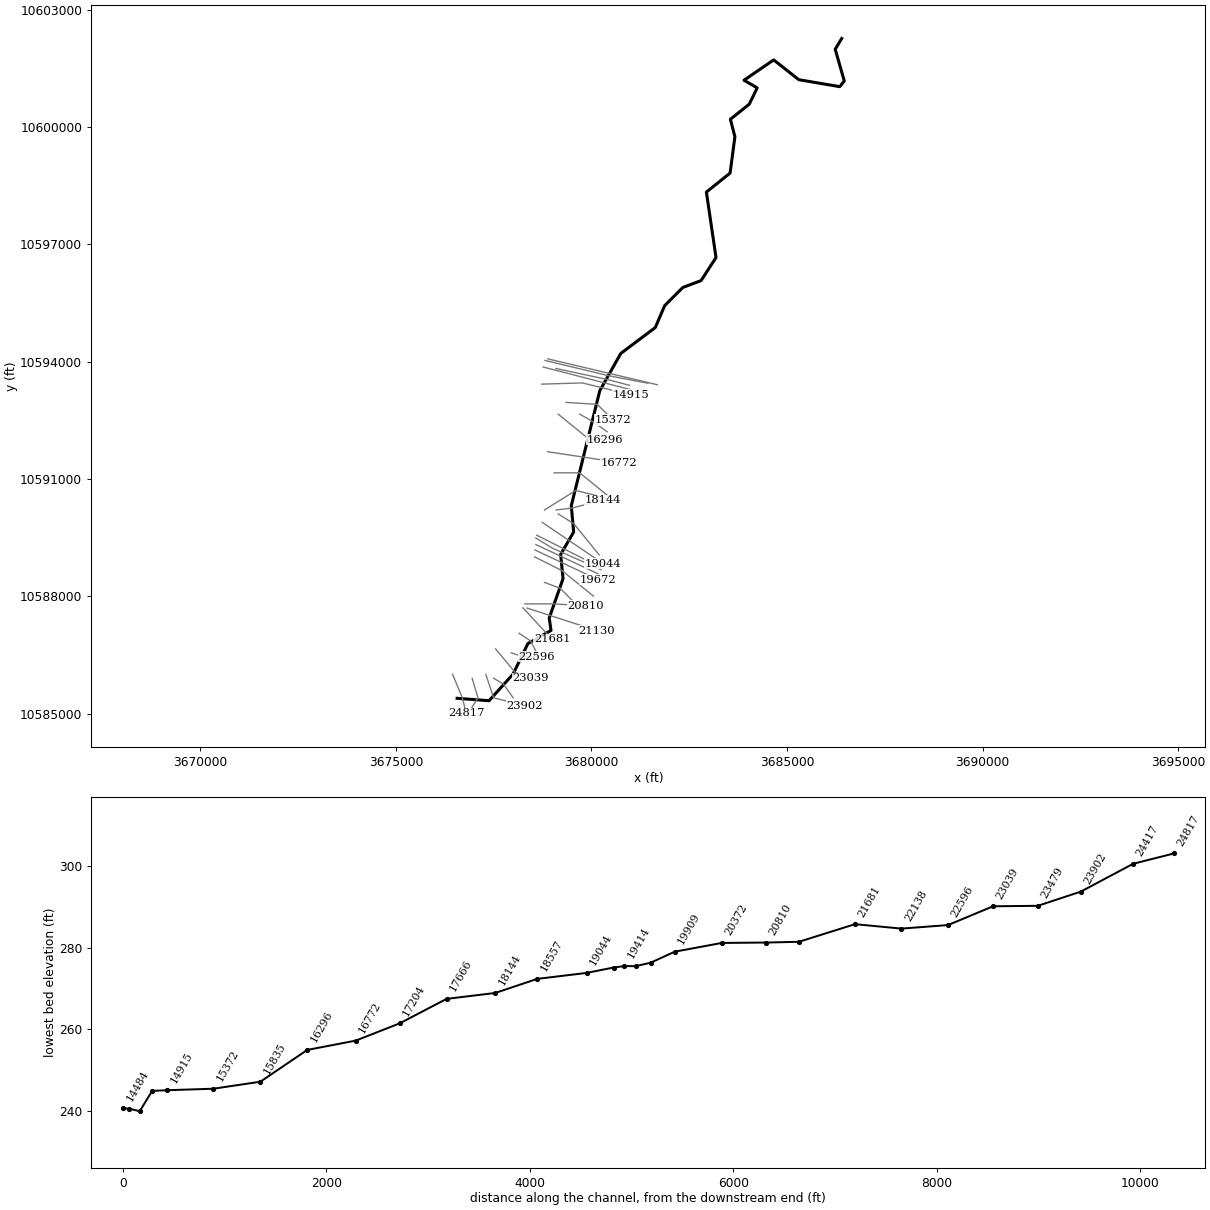
--- SALINE BRANCH.prj (project) ---

Proj Title=SALINE BRANCH Base Level Engineering
Current Plan=p01
Default Exp/Contr=0.3,0.1
English Units
Geom File=g01
Flow File=f01
Plan File=p01
Y Axis Title=Elevation
X Axis Title(PF)=Main Channel Distance
X Axis Title(XS)=Station
BEGIN DESCRIPTION:
SALINE BRANCH
END DESCRIPTION:
DSS Export Rating Curves= 0
DSS Export Rating Curve Sorted= 0
DSS Export Volume Flow Curves= 0
DXF OffsetX= 0
DXF OffsetY= 0
DXF ScaleX= 1
DXF ScaleY= 10

--- SALINE BRANCH.p01 (plan) ---

Plan Title=Multiple Run
Short Identifier=Multiple
Geom File=g01
Flow File=f01
Subcritical Flow
K Sum by GR= 0
Std Step Tol= 0.01
Critical Tol= 0.01
Num of Std Step Trials= 20
Max Error Tol= 0.3
Flow Tol Ratio= 0.001
Split Flow NTrial= 30
Split Flow Tol= 0.02
Split Flow Ratio= 0.02
Log Output Level= 0
Friction Slope Method= 1
Unsteady Friction Slope Method= 2
Unsteady Bridges Friction Slope Method= 1
Parabolic Critical Depth
Global Vel Dist=  1 , 1 , 1
Global Log Level= 0
CheckData=True
Encroach Param= -1, 0, 0, 0
BEGIN DESCRIPTION:
Multiple Run
END DESCRIPTION:

--- SALINE BRANCH.f01 (steady flow) ---

Flow Title=Multiple
Program Version=4.10
Number of Profiles= 7
Profile Names=10-year,25-year,50-year,1pct_min,100-year,1pct_plu,500-year
River Rch & RM=SALINE BRANCH,Reach-1         ,24817
     957    1342    1670    1525    2063    2790    3164
River Rch & RM=SALINE BRANCH,Reach-1         ,23039
    1176    1658    2072    1898    2567    3471    3959
River Rch & RM=SALINE BRANCH,Reach-1         ,17204
    1434    2041    2566    2364    3197    4323    4987
River Rch & RM=SALINE BRANCH,Reach-1         ,14290
    1462    2076    2605    2394    3238    4379    5029
River Rch & RM=SALINE BRANCH,Reach-1         ,10292
    1983    2848    3602    3333    4508    6096    7098
River Rch & RM=SALINE BRANCH,Reach-1         ,9576
    1983    2848    3602    3333    4508    6096    7098
River Rch & RM=SALINE BRANCH,Reach-1         ,5810
    2709    3905    4947    4581    6195    8378    9766
Boundary for River Rch & Prof#=SALINE BRANCH,Reach-1         , 1
Up Type= 0
Dn Type= 3
Dn Slope=0.004
Boundary for River Rch & Prof#=SALINE BRANCH,Reach-1         , 2
Up Type= 0
Dn Type= 3
Dn Slope=0.004
Boundary for River Rch & Prof#=SALINE BRANCH,Reach-1         , 3
Up Type= 0
Dn Type= 3
Dn Slope=0.004
Boundary for River Rch & Prof#=SALINE BRANCH,Reach-1         , 4
Up Type= 0
Dn Type= 3
Dn Slope=0.004
Boundary for River Rch & Prof#=SALINE BRANCH,Reach-1         , 5
Up Type= 0
Dn Type= 3
Dn Slope=0.004
Boundary for River Rch & Prof#=SALINE BRANCH,Reach-1         , 6
Up Type= 0
Dn Type= 3
Dn Slope=0.004
Boundary for River Rch & Prof#=SALINE BRANCH,Reach-1         , 7
Up Type= 0
Dn Type= 3
Dn Slope=0.004
DSS Import GetInterval= 0
DSS Import GetPeak= 0
DSS Import FillOption= 0

--- SALINE BRANCH.g01 (geometry) ---

Geom Title=Existing Conditions
Program Version=4.10

River Reach=SALINE BRANCH   ,Reach-1
Reach XY= 30
        3676566.       10585397.       3677382.5       10585335.
      3677995.25       10586014.        3678377.       10586797.
      3678966.75       10587131.        3678921.       10587450.
        3679274.       10588453.      3679213.75       10589076.
      3679546.25       10589647.       3679485.5       10590320.
       3680213.5       10593257.      3680750.75       10594211.
        3681633.       10594873.      3681873.75       10595434.
      3682336.25       10595897.      3682803.25       10596073.
      3683185.75       10596662.      3682939.75       10598336.
        3683546.       10598822.      3683668.75       10599751.
      3683553.75       10600197.        3684036.       10600582.
      3684238.75       10601000.      3683901.25       10601194.
      3684660.64     10601714.17      3685302.25       10601208.
      3686348.75       10601030.      3686465.25       10601175.
      3686233.41     10601986.56      3686399.22     10602260.56

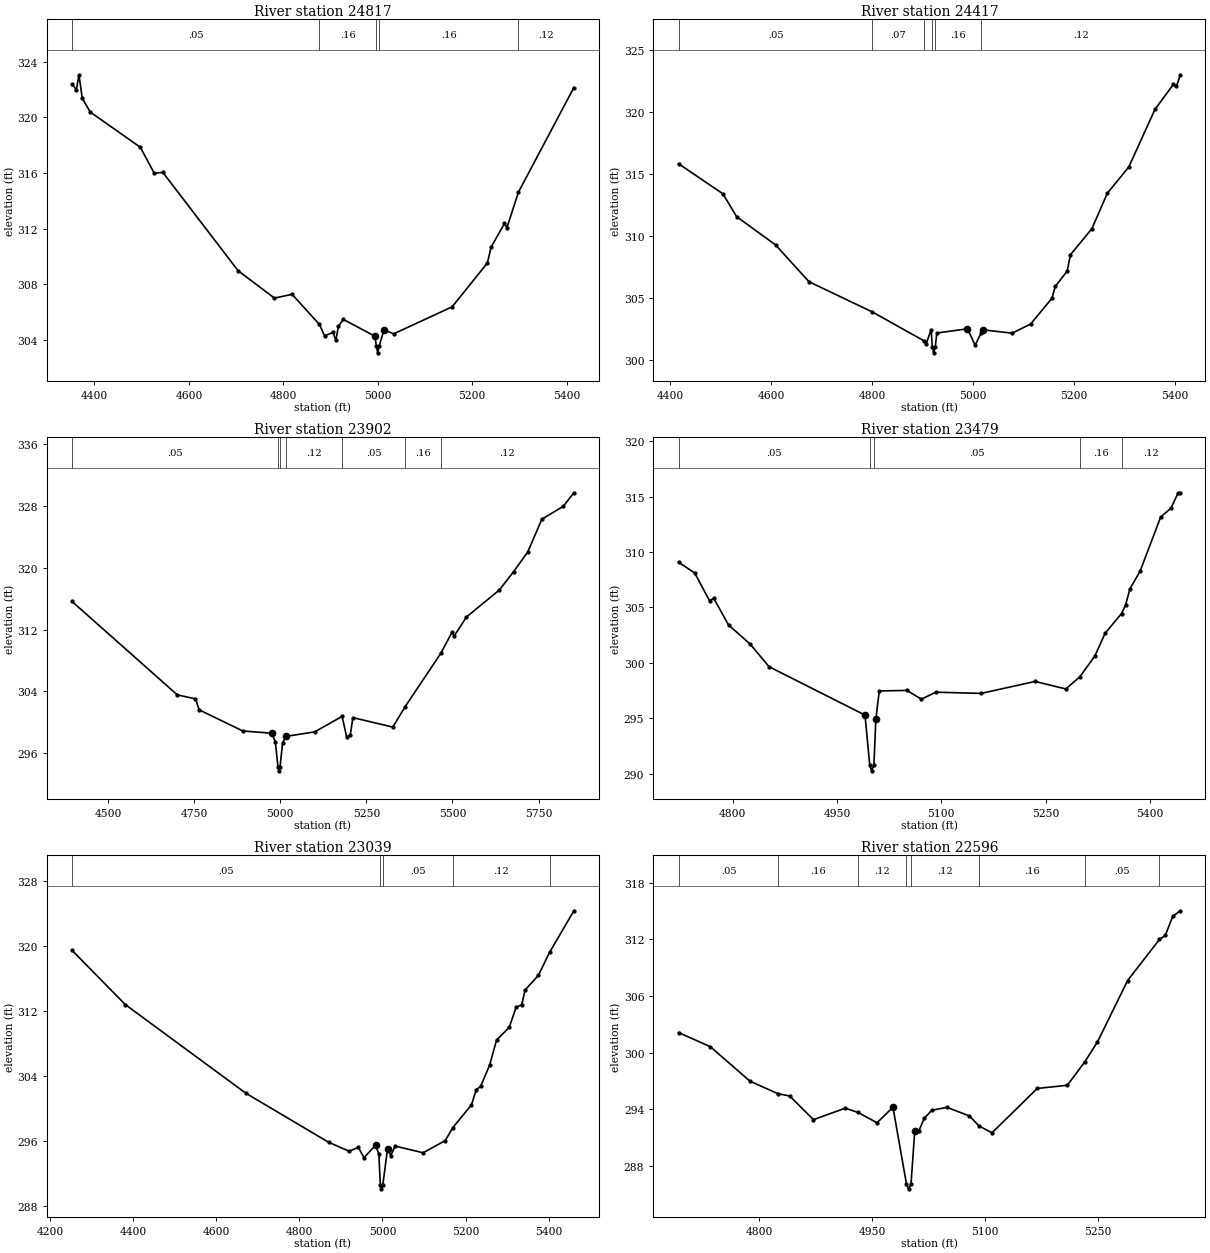
Type RM Length L Ch R = 1 ,24817   ,400,400,400
BEGIN DESCRIPTION:
SALINE BRANCH 45.0
END DESCRIPTION:
XS GIS Cut Line= 3
      3676449.62     10586010.17      3676699.61     10585410.19
      3676799.61     10585010.18
#Sta/Elev= 30
  4352.7  322.38  4361.9     322  4367.3  323.07  4374.3  321.37  4391.1  320.39
  4497.3  317.85  4526.6  315.99    4545  316.04  4704.2  308.97  4781.1     307
  4818.5  307.27  4876.5   305.1  4887.3  304.28  4905.2  304.53  4911.1  303.96
  4916.6  304.97  4926.8  305.47  4993.5  304.26    4997  303.56  4999.7  303.06
    5003  303.56    5013  304.71  5033.6  304.43  5157.3  306.37    5232  309.53
  5239.8  310.67  5268.1  312.37  5273.3  312.06  5297.5  314.61    5415  322.15
#Mann= 5 ,-1 , 0
  4352.7     .05       0  4876.5     .16       0    4997     .07       0
    5003     .16       0  5297.5     .12       0
Bank Sta=4993.5,5013
XS Rating Curve= 0 ,0
Exp/Cntr=0.3,0.1

Type RM Length L Ch R = 1 ,24417   ,515,515,515
BEGIN DESCRIPTION:
SALINE BRANCH 44.0
END DESCRIPTION:
XS GIS Cut Line= 3
       3676949.6     10585910.24      3677099.61     10585410.19
      3676849.59     10585010.16
#Sta/Elev= 30
  4416.2  315.81  4504.1  313.38  4531.1  311.54  4608.5  309.25  4674.6  306.28
  4800.1  303.84  4901.4  301.53  4906.9  301.29  4916.5  302.42  4918.7  301.04
  4921.5  300.54  4924.7  301.04  4927.8  302.14  4988.4  302.48  5003.7  301.16
  5015.6  302.15    5019   302.4  5076.8  302.13  5113.4  302.86  5155.8  304.95
  5162.3   305.9  5185.9  307.14  5192.4  308.46  5234.8  310.56  5265.5  313.43
    5308  315.55  5359.8   320.2  5396.4  322.22  5402.3  322.05    5410  322.99
#Mann= 6 ,-1 , 0
  4416.2     .05       0  4800.1     .07       0  4901.4     .16       0
  4918.7     .07       0  4924.7     .16       0  5015.6     .12       0
Bank Sta=4988.4,5019
XS Rating Curve= 0 ,0
Exp/Cntr=0.3,0.1

Type RM Length L Ch R = 1 ,23902   ,423,423,423
BEGIN DESCRIPTION:
SALINE BRANCH 43.0
END DESCRIPTION:
XS GIS Cut Line= 3
       3677299.6     10586010.22      3677499.61     10585410.19
       3678299.6     10585210.19
#Sta/Elev= 30
  4395.4  315.63  4701.1  303.55  4753.8  303.04  4764.4  301.62  4890.9  298.89
  4975.2  298.59  4985.7  297.47  4993.3  294.23    4996  293.73  4999.3  294.23
  5006.8  297.39  5016.8  298.14  5017.4  298.19    5100  298.77  5179.6  300.77
  5192.8  298.07  5203.1  298.34  5210.9  300.61  5326.8  299.39  5362.9  302.05
  5465.9  308.91  5499.5  311.72  5504.6  311.13  5540.7  313.63    5636  317.11
  5677.3  319.47  5718.5  322.03  5759.7  326.28  5821.6  327.93  5852.5  329.69
#Mann= 7 ,-1 , 0
  4395.4     .05       0  4993.3     .03       0  4999.3     .05       0
  5016.8     .12       0  5179.6     .05       0  5362.9     .16       0
  5465.9     .12       0
Bank Sta=4975.2,5017.4
XS Rating Curve= 0 ,0
Exp/Cntr=0.3,0.1

Type RM Length L Ch R = 1 ,23479   ,440,440,440
BEGIN DESCRIPTION:
SALINE BRANCH 42.0
END DESCRIPTION:
XS GIS Cut Line= 3
      3677499.59      10585910.2      3677749.61     10585760.19
      3677999.62     10585410.17
#Sta/Elev= 30
  4722.2  309.08  4745.5  308.11  4766.9  305.59  4772.8  305.83  4794.1  303.42
  4825.2  301.69  4852.4  299.65  4990.4  295.28  4997.2  290.75  4999.9  290.25
  5003.2  290.75    5006  294.91  5010.9  297.46  5050.6  297.51  5071.5  296.72
  5092.4  297.35  5157.5  297.24    5235  298.32  5279.2  297.64  5299.7  298.76
    5321  300.62  5335.7  302.67  5359.3  304.44  5365.2  305.23  5371.4  306.67
  5386.1  308.28  5415.6  313.16  5430.4  313.96  5440.8  315.35  5443.9  315.35
#Mann= 5 ,-1 , 0
  4722.2     .05       0  4997.2     .03       0  5003.2     .05       0
  5299.7     .16       0  5359.3     .12       0
Bank Sta=4990.4,5006
XS Rating Curve= 0 ,0
Exp/Cntr=0.3,0.1

Type RM Length L Ch R = 1 ,23039   ,443,443,443
BEGIN DESCRIPTION:
SALINE BRANCH 41.0
END DESCRIPTION:
XS GIS Cut Line= 3
      3677549.61     10586660.18      3678049.61     10586060.19
      3678449.59     10585910.19
#Sta/Elev= 30
  4252.7  319.43  4380.9  312.77  4671.2  301.88  4870.4  295.86  4919.8  294.76
  4941.9  295.23  4955.6  293.97  4983.6   295.5  4991.4  294.42  4994.9  290.64
  4997.7  290.14  5000.9  290.64  5012.2  295.01    5020  294.23  5030.5  295.39
  5097.8  294.57  5151.2  296.06  5169.2  297.64  5214.4  300.46    5226  302.33
  5236.6  302.73    5258  305.33  5274.9  308.42  5305.2  309.97  5322.1  312.46
  5335.4  312.74  5343.4  314.56  5375.5  316.36  5402.3  319.17  5460.9  324.29
#Mann= 5 ,-1 , 0
  4252.7     .05       0  4994.9     .03       0  5000.9     .05       0
  5169.2     .12       0  5402.3     .07       0
Bank Sta=4983.6,5012.2
XS Rating Curve= 0 ,0
Exp/Cntr=0.3,0.1

Type RM Length L Ch R = 1 ,22596   ,458,458,458
BEGIN DESCRIPTION:
SALINE BRANCH 40.0
END DESCRIPTION:
XS GIS Cut Line= 3
      3677949.56      10586560.2      3678249.61     10586460.19
      3678599.63     10586460.19
#Sta/Elev= 30
  4692.9  302.12  4735.1  300.62  4787.8  296.96  4825.3  295.62  4840.5  295.39
  4872.1  292.88  4914.3   294.1    4931  293.65  4956.5  292.55  4977.6   294.2
  4995.6  286.04  4998.4  285.54  5001.6  286.04  5006.5  291.63  5011.7  291.63
  5019.2  293.03  5029.2  293.87  5049.2  294.19  5079.2  293.27  5092.2  292.19
  5109.2  291.49  5169.2  296.19  5209.2  296.53  5232.6  299.04  5249.2  301.13
  5289.2  307.64  5331.5     312  5339.2  312.42  5349.2  314.47  5359.2  315.04
#Mann= 8 ,-1 , 0
  4692.9     .05       0  4825.3     .16       0    4931     .12       0
  4995.6     .07       0  5001.6     .12       0  5092.2     .16       0
  5232.6     .05       0  5331.5     .16       0
Bank Sta=4977.6,5006.5
XS Rating Curve= 0 ,0
Exp/Cntr=0.3,0.1

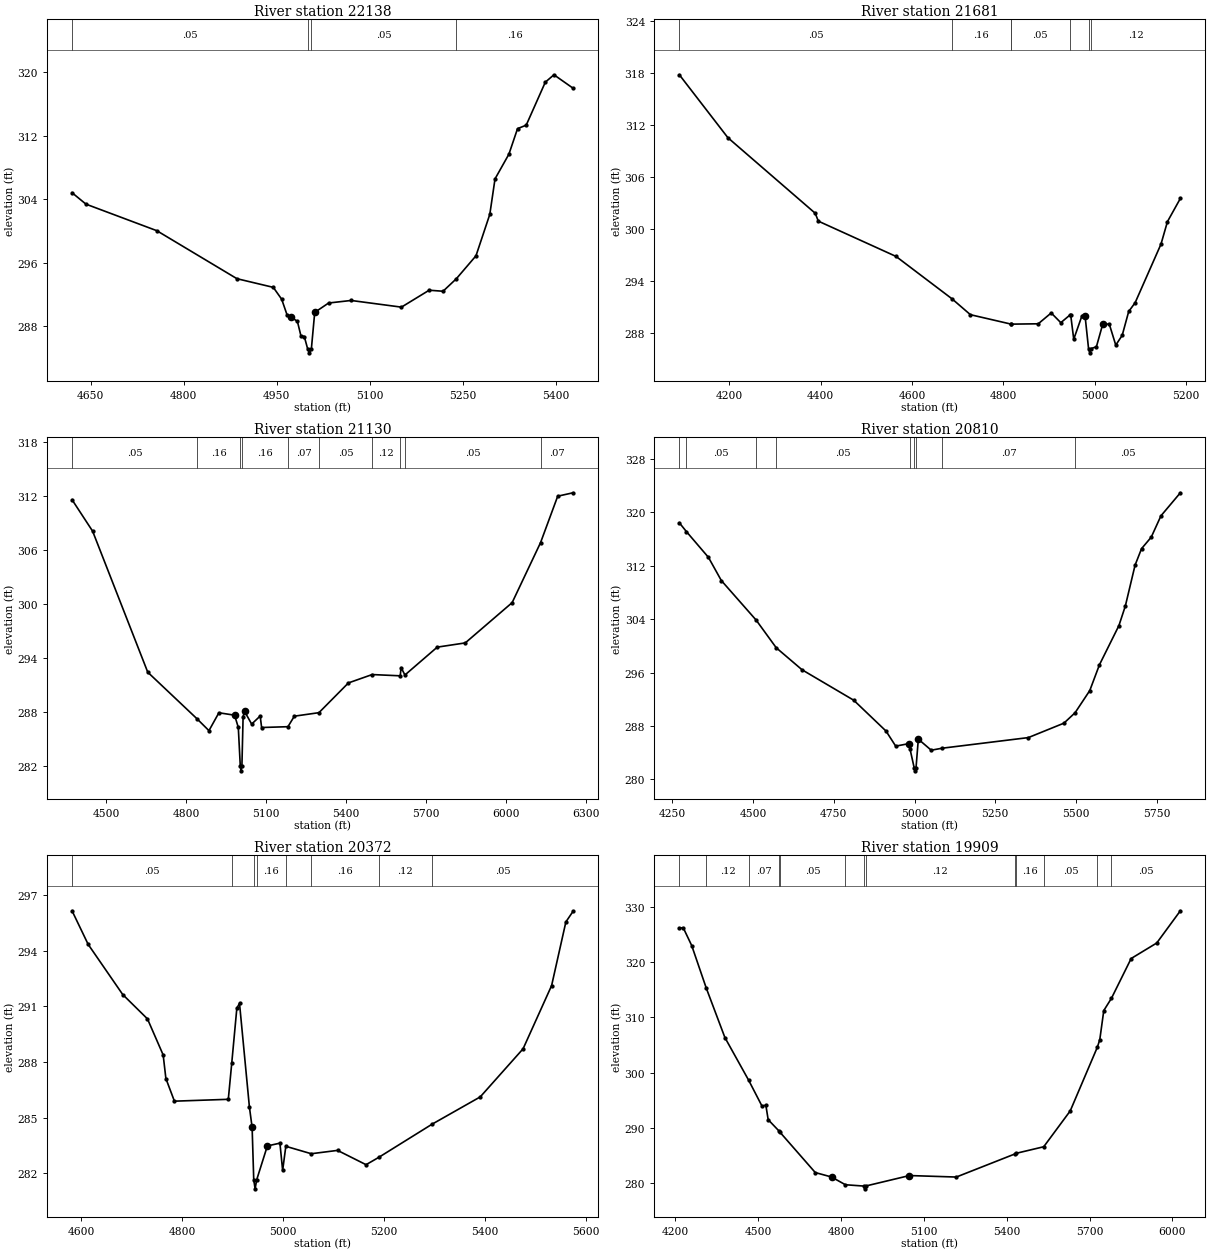
Type RM Length L Ch R = 1 ,22138   ,457,457,457
BEGIN DESCRIPTION:
SALINE BRANCH 39.0
END DESCRIPTION:
XS GIS Cut Line= 3
       3678149.6      10587060.2      3678449.61     10586860.19
      3678649.62     10586460.17
#Sta/Elev= 30
  4620.2  304.83  4642.7  303.39  4756.9  300.05  4886.1  294.01  4944.7  292.92
  4958.2  291.43  4967.2  289.39  4973.3   289.2  4983.6  288.63  4989.2  286.84
  4994.7  286.73  5000.1  285.18  5002.9  284.68  5006.1  285.18  5011.5  289.77
  5033.9  290.95  5070.2  291.27  5151.3  290.43    5196  292.56  5218.4  292.43
  5239.8     294  5271.5  296.89  5293.8  302.11  5302.2  306.57  5324.6  309.68
  5338.5  312.89  5352.5  313.33  5383.3  318.74  5397.2  319.67    5428  317.98
#Mann= 4 ,-1 , 0
  4620.2     .05       0  5000.1     .03       0  5006.1     .05       0
  5239.8     .16       0
Bank Sta=4973.3,5011.5
XS Rating Curve= 0 ,0
Exp/Cntr=0.3,0.1

Type RM Length L Ch R = 1 ,21681   ,551,551,551
BEGIN DESCRIPTION:
SALINE BRANCH 38.0
END DESCRIPTION:
XS GIS Cut Line= 3
      3678249.61     10587710.18      3678849.61     10587060.19
       3678999.6      10586910.2
#Sta/Elev= 30
  4090.8  317.83  4197.1  310.57  4388.2  301.86    4395  300.95  4565.1  296.88
  4687.4     292  4727.9  290.16  4816.3  289.08  4816.7  289.07  4876.4  289.11
  4904.8  290.36  4925.8  289.24  4945.1  290.09  4947.3  290.18  4954.1  287.33
    4972  290.02  4978.9  290.02  4986.5  286.26  4989.3  285.76  4992.5  286.26
  5003.7  286.46  5017.8  289.11    5032  289.06  5046.1  286.65  5060.2  287.78
  5074.4  290.53  5088.5  291.54  5145.1   298.3  5159.2  300.89  5187.5  303.57
#Mann= 7 ,-1 , 0
  4090.8     .05       0  4687.4     .16       0  4816.3     .12       0
  4816.7     .05       0  4945.1     .12       0  4986.5     .07       0
  4992.5     .12       0
Bank Sta=4978.9,5017.8
XS Rating Curve= 0 ,0
Exp/Cntr=0.3,0.1

Type RM Length L Ch R = 1 ,21130   ,320,320,320
BEGIN DESCRIPTION:
SALINE BRANCH 37.0
END DESCRIPTION:
XS GIS Cut Line= 2
      3678356.16     10587703.01       3680144.3     10587125.77
#Sta/Elev= 30
  4372.3  311.61  4449.5  308.11  4656.3  292.42  4840.3  287.26  4885.8  285.92
  4923.1  287.91  4981.9  287.64  4995.9  286.28  5003.4  281.95  5006.2  281.45
  5009.4  281.95  5013.9  287.48  5019.2  288.07    5046  286.65    5078  287.55
  5083.3  286.27  5182.1  286.36  5206.1  287.53  5298.3  287.92  5408.9  291.23
  5497.9  292.16  5603.2  292.02  5606.4  292.94  5620.8  292.11    5742  295.21
  5847.1  295.68  6022.9  300.16  6129.4  306.83  6193.8     312  6251.3  312.38
#Mann= 10 ,-1 , 0
  4372.3     .05       0  4840.3     .16       0  5003.4     .07       0
  5009.4     .16       0  5182.1     .07       0  5298.3     .05       0
  5497.9     .12       0  5603.2     .07       0  5620.8     .05       0
  6129.4     .07       0
Bank Sta=4981.9,5019.2
XS Rating Curve= 0 ,0
Exp/Cntr=0.3,0.1

Type RM Length L Ch R = 1 ,20810   ,438,438,438
BEGIN DESCRIPTION:
SALINE BRANCH 36.0
END DESCRIPTION:
XS GIS Cut Line= 3
      3678299.65     10587810.19      3679049.61     10587810.19
      3679849.59     10587760.19
#Sta/Elev= 30
  4271.6  318.43  4293.7   317.1  4361.6  313.26  4401.6  309.78  4509.5  303.85
  4571.6  299.71  4651.6  296.41  4811.6  291.85  4911.6  287.23  4941.6  284.97
  4981.6  285.34  4986.1   284.5  4998.6  281.77  5001.3  281.27  5004.6  281.77
  5011.6  286.02  5051.6  284.36  5085.3  284.66  5352.2  286.25  5462.4  288.41
    5497  289.97  5542.6   293.3  5572.6  297.17  5632.8  303.03  5652.8  305.98
  5682.8  312.08  5702.9  314.56  5732.9  316.28    5763  319.48  5823.1  322.93
#Mann= 9 ,-1 , 0
  4271.6     .12       0  4293.7     .05       0  4509.5     .16       0
  4571.6     .05       0  4986.1     .16       0  4998.6     .07       0
  5004.6     .16       0  5085.3     .07       0    5497     .05       0
Bank Sta=4981.6,5011.6
XS Rating Curve= 0 ,0
Exp/Cntr=0.3,0.1

Type RM Length L Ch R = 1 ,20372   ,463,463,463
BEGIN DESCRIPTION:
SALINE BRANCH 35.0
END DESCRIPTION:
XS GIS Cut Line= 3
      3678799.64     10588360.18      3679199.61     10588210.19
      3679599.64     10587810.15
#Sta/Elev= 30
  4581.6  296.14  4613.6  294.33  4682.1  291.63  4731.1  290.32  4762.2  288.38
  4767.6  287.11  4784.5  285.89  4891.3  285.99  4898.1  287.93  4908.2  290.89
  4913.5  291.16  4933.1  285.58  4938.5  284.48  4941.7  281.67  4944.4  281.17
  4947.7  281.67  4968.7  283.48  4993.6  283.63    4999  282.16  5005.3  283.46
  5055.7  283.06  5107.8  283.24  5164.3  282.47  5189.2  282.86  5295.1  284.65
  5390.6  286.12  5475.5  288.71    5532  292.11  5560.3  295.54  5574.5  296.11
#Mann= 8 ,-1 , 0
  4581.6     .05       0  4898.1     .16       0  4941.7     .07       0
  4947.7     .16       0  5005.3     .12       0  5055.7     .16       0
  5189.2     .12       0  5295.1     .05       0
Bank Sta=4938.5,4968.7
XS Rating Curve= 0 ,0
Exp/Cntr=0.3,0.1

Type RM Length L Ch R = 1 ,19909   ,237,237,237
BEGIN DESCRIPTION:
SALINE BRANCH 34.0
END DESCRIPTION:
XS GIS Cut Line= 3
      3678549.59      10589010.2      3679249.61     10588660.19
      3680049.59      10588010.2
#Sta/Elev= 30
  4215.1  326.11  4229.1  326.19  4259.8  322.97  4312.7  315.26    4380  306.35
  4466.1  298.63  4514.2  293.98  4528.2  294.13  4536.6  291.52  4574.4  289.55
  4578.9  289.28  4707.1  281.97  4765.8  281.17  4816.1  279.77  4882.9  279.53
  4885.7  279.03  4888.9  279.53    5048  281.43  5217.5  281.16  5430.1  285.34
    5432  285.42  5533.9  286.63  5629.8   293.1  5728.2  304.63  5736.9  305.99
  5751.3  311.23    5779  313.44  5850.4  320.63    5943  323.43  6028.5  329.25
#Mann= 13 ,-1 , 0
  4215.1     .16       0  4312.7     .12       0  4466.1     .07       0
  4574.4     .16       0  4578.9     .05       0  4816.1     .12       0
  4882.9     .07       0  4888.9     .12       0  5430.1     .05       0
    5432     .16       0  5533.9     .05       0  5728.2     .16       0
    5779     .05       0
Bank Sta=4765.8,5048
XS Rating Curve= 0 ,0
Exp/Cntr=0.3,0.1

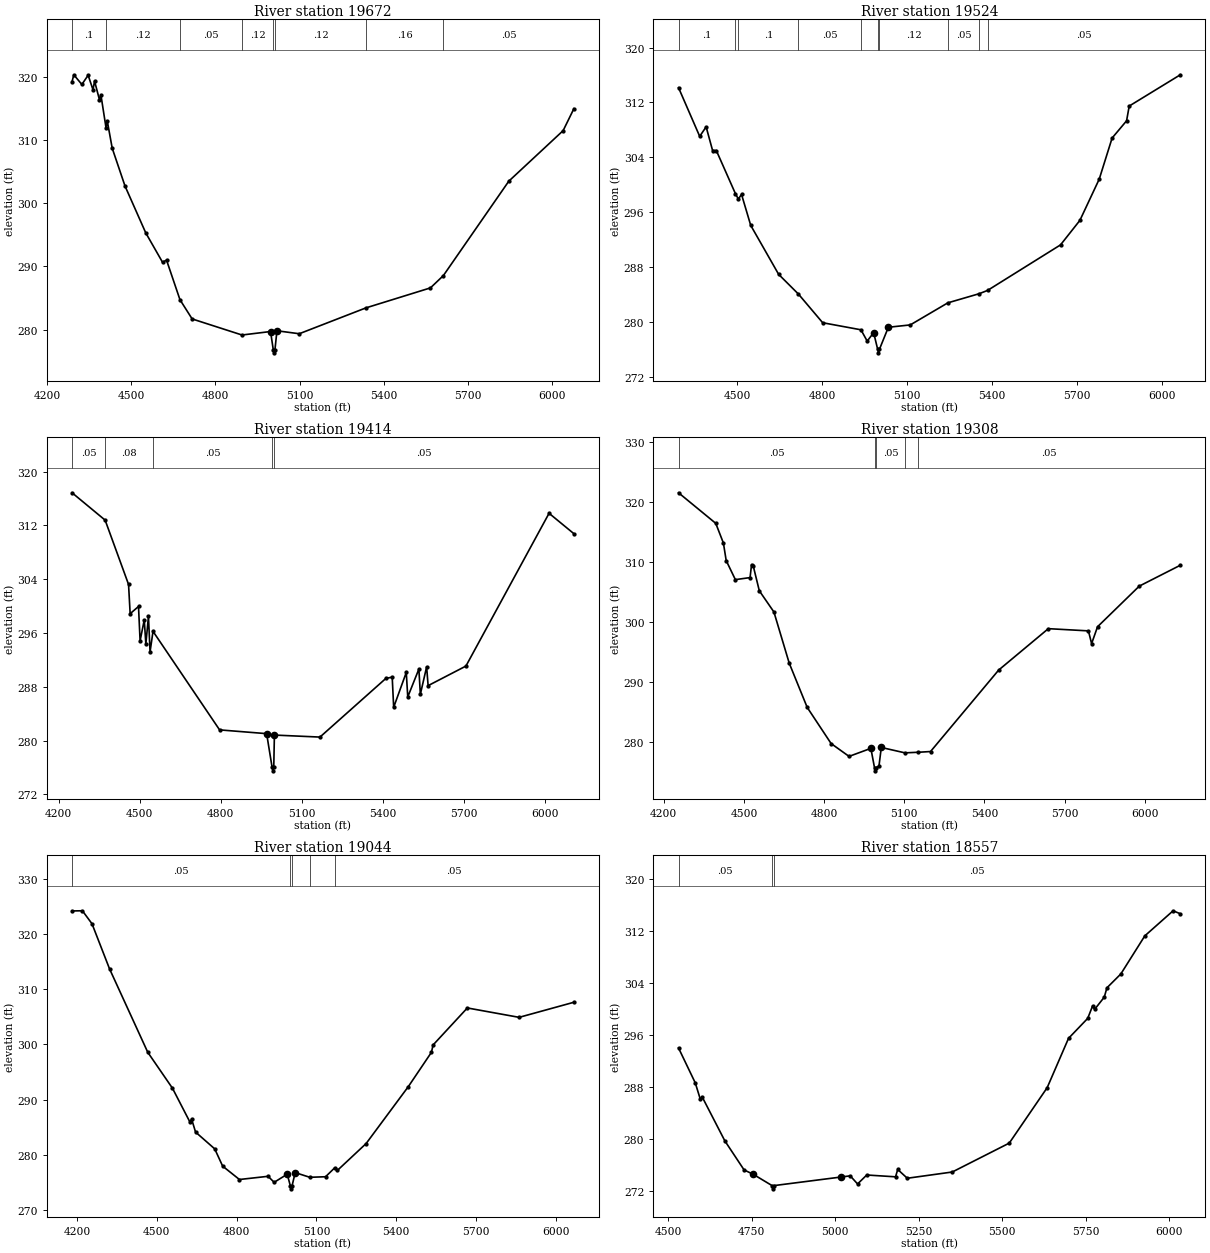
Type RM Length L Ch R = 1 ,19672   ,148,148,148
BEGIN DESCRIPTION:
Mapping XS c187dea9
END DESCRIPTION:
XS GIS Cut Line= 2
      3678557.99     10589187.29      3680176.24     10588427.59
#Sta/Elev= 30
  4289.3  319.22  4295.4   320.3  4324.2  318.77  4346.6  320.23  4363.9  317.92
  4369.4  319.31  4386.7  316.38  4392.2  317.08  4410.3  311.91    4415  312.93
  4432.3  308.69  4477.9  302.71  4551.9  295.29  4611.5  290.66  4625.9  290.99
  4673.7  284.73  4717.1  281.69  4894.7  279.15  4996.4   279.7  5006.1  276.83
  5008.9  276.33  5012.1  276.83  5019.2  279.82  5098.7  279.35  5336.3  283.44
    5566   286.6    5612  288.54  5845.3  303.48  6038.8  311.47    6077  314.93
#Mann= 8 ,-1 , 0
  4289.3      .1       0  4410.3     .12       0  4673.7     .05       0
  4894.7     .12       0  5006.1     .07       0  5012.1     .12       0
  5336.3     .16       0    5612     .05       0
Bank Sta=4996.4,5019.2
XS Rating Curve= 0 ,0
Exp/Cntr=0.3,0.1

Type RM Length L Ch R = 1 ,19524   ,110,110,110
BEGIN DESCRIPTION:
SALINE BRANCH 33.0
END DESCRIPTION:
XS GIS Cut Line= 2
      3678578.84     10589327.91      3680182.96     10588572.72
#Sta/Elev= 30
  4292.2  314.15    4367  307.05  4389.7  308.44  4412.5  304.99  4425.7  304.99
  4493.3  298.69  4503.5  297.91  4514.8  298.59  4547.3  294.07    4646  286.93
    4716  284.05  4801.5  279.88  4936.7  278.85  4958.8   277.2  4981.6  278.43
  4995.9  275.99  4998.7  275.49  5001.9  275.99  5033.6  279.22    5111  279.56
  5243.8  282.78  5354.4  284.11  5384.1  284.59  5641.9  291.23  5710.3   294.8
  5778.7  300.82  5824.2  306.81  5875.3  309.32  5884.6  311.47  6065.2  316.03
#Mann= 10 ,-1 , 0
  4292.2      .1       0  4493.3     .05       0  4503.5      .1       0
    4716     .05       0  4936.7     .12       0  4995.9     .07       0
  5001.9     .12       0  5243.8     .05       0  5354.4     .16       0
  5384.1     .05       0
Bank Sta=4981.6,5033.6
XS Rating Curve= 0 ,0
Exp/Cntr=0.3,0.1

Type RM Length L Ch R = 1 ,19414   ,106,106,106
BEGIN DESCRIPTION:
Mapping XS 04059eb3
END DESCRIPTION:
XS GIS Cut Line= 3
      3678576.79     10589494.32      3679003.89     10589233.89
      3680243.47     10588685.28
#Sta/Elev= 30
  4250.1  316.86  4372.4  312.79    4459  303.23  4464.9  298.88  4495.8  299.95
  4501.7  294.84  4517.1  297.96    4523  294.37  4532.6  298.48  4538.5  293.21
  4549.5  296.25  4795.7   281.6  4969.7  281.04    4990  276.01  4992.7  275.51
    4996  276.01  4998.4  280.83  5166.9  280.53  5410.8  289.26  5434.1  289.44
  5439.5  284.96  5486.1  290.14  5491.6   286.5  5532.7  290.64  5538.2   286.9
  5561.4  290.97  5566.9  288.18  5706.7  291.09  6014.2  313.81  6105.9  310.78
#Mann= 5 ,-1 , 0
  4250.1     .05       0  4372.4     .08       0  4549.5     .05       0
    4990     .04       0    4996     .05       0
Bank Sta=4969.7,4998.4
XS Rating Curve= 0 ,0
Exp/Cntr=0.3,0.1

Type RM Length L Ch R = 1 ,19308   ,264,264,264
BEGIN DESCRIPTION:
SALINE BRANCH 32.0
END DESCRIPTION:
XS GIS Cut Line= 2
      3678599.65      10589567.5      3680276.76     10588723.74
#Sta/Elev= 30
  4255.4  321.55  4394.7  316.45  4423.3  313.16  4433.7  310.24    4468  307.06
    4523   307.4  4528.6  309.57  4535.2  309.29  4557.6   305.2  4612.3  301.66
  4669.5  293.13  4736.7  285.75  4826.3  279.71  4893.4  277.57    4975  278.91
  4988.7  275.66  4991.4  275.16  4994.7  275.66  5005.4  275.99    5014  279.06
  5102.5  278.16  5152.4  278.26  5198.2  278.38  5453.1  291.97    5639  298.88
    5789  298.51  5800.8  296.38  5823.1   299.2  5979.3  305.98  6132.8  309.46
#Mann= 5 ,-1 , 0
  4255.4     .05       0  4988.7     .03       0  4994.7     .05       0
  5102.5      .1       0  5152.4     .05       0
Bank Sta=4975,5014
XS Rating Curve= 0 ,0
Exp/Cntr=0.3,0.1

Type RM Length L Ch R = 1 ,19044   ,487,487,487
BEGIN DESCRIPTION:
Mapping XS 6a0a085f
END DESCRIPTION:
XS GIS Cut Line= 2
      3678740.31     10589895.61       3680302.8     10588838.32
#Sta/Elev= 30
  4181.4  324.17  4220.3   324.2  4256.3  321.85  4322.2  313.69    4466  298.57
  4558.9  292.06  4624.8  285.91  4630.8  286.48  4645.7  284.12  4717.7  281.08
  4747.6  277.95  4810.6  275.53  4918.4  276.11  4941.2  275.02  4990.3  276.49
  5002.3  274.34  5005.1  273.84  5008.3  274.34  5020.3  276.78  5075.3  275.93
  5134.4  276.03  5168.1  277.61    5179  277.18  5286.9  282.04  5445.7  292.36
  5532.6  298.57  5538.6  299.89  5667.5   306.6  5862.2   304.9    6068  307.63
#Mann= 5 ,-1 , 0
  4181.4     .05       0  5002.3     .03       0  5008.3     .05       0
  5075.3      .1       0  5168.1     .05       0
Bank Sta=4990.3,5020.3
XS Rating Curve= 0 ,0
Exp/Cntr=0.3,0.1

Type RM Length L Ch R = 1 ,18557   ,413,413,413
BEGIN DESCRIPTION:
SALINE BRANCH 31.0
END DESCRIPTION:
XS GIS Cut Line= 3
      3679149.62     10590110.18      3679549.61     10589860.19
      3680199.63     10589060.16
#Sta/Elev= 30
  4531.4  294.06  4581.5  288.69  4596.8  286.14  4602.7  286.48    4670  279.77
  4727.7  275.29  4755.4  274.61  4811.4  272.88  4814.2  272.38  4817.4  272.88
  5016.7  274.19  5045.5  274.38  5067.5  273.13    5095  274.51  5181.2  274.23
  5187.7  275.36  5216.4  274.01    5351  274.97  5521.7  279.42  5635.2  287.95
  5699.1  295.54  5756.6  298.62    5771  300.51  5777.4  300.01  5806.2  301.89
  5814.1  303.32  5855.7  305.45  5927.6  311.32  6012.3  315.18  6033.9  314.72
#Mann= 3 ,-1 , 0
  4531.4     .05       0  4811.4     .03       0  4817.4     .05       0
Bank Sta=4755.4,5016.7
XS Rating Curve= 0 ,0
Exp/Cntr=0.3,0.1

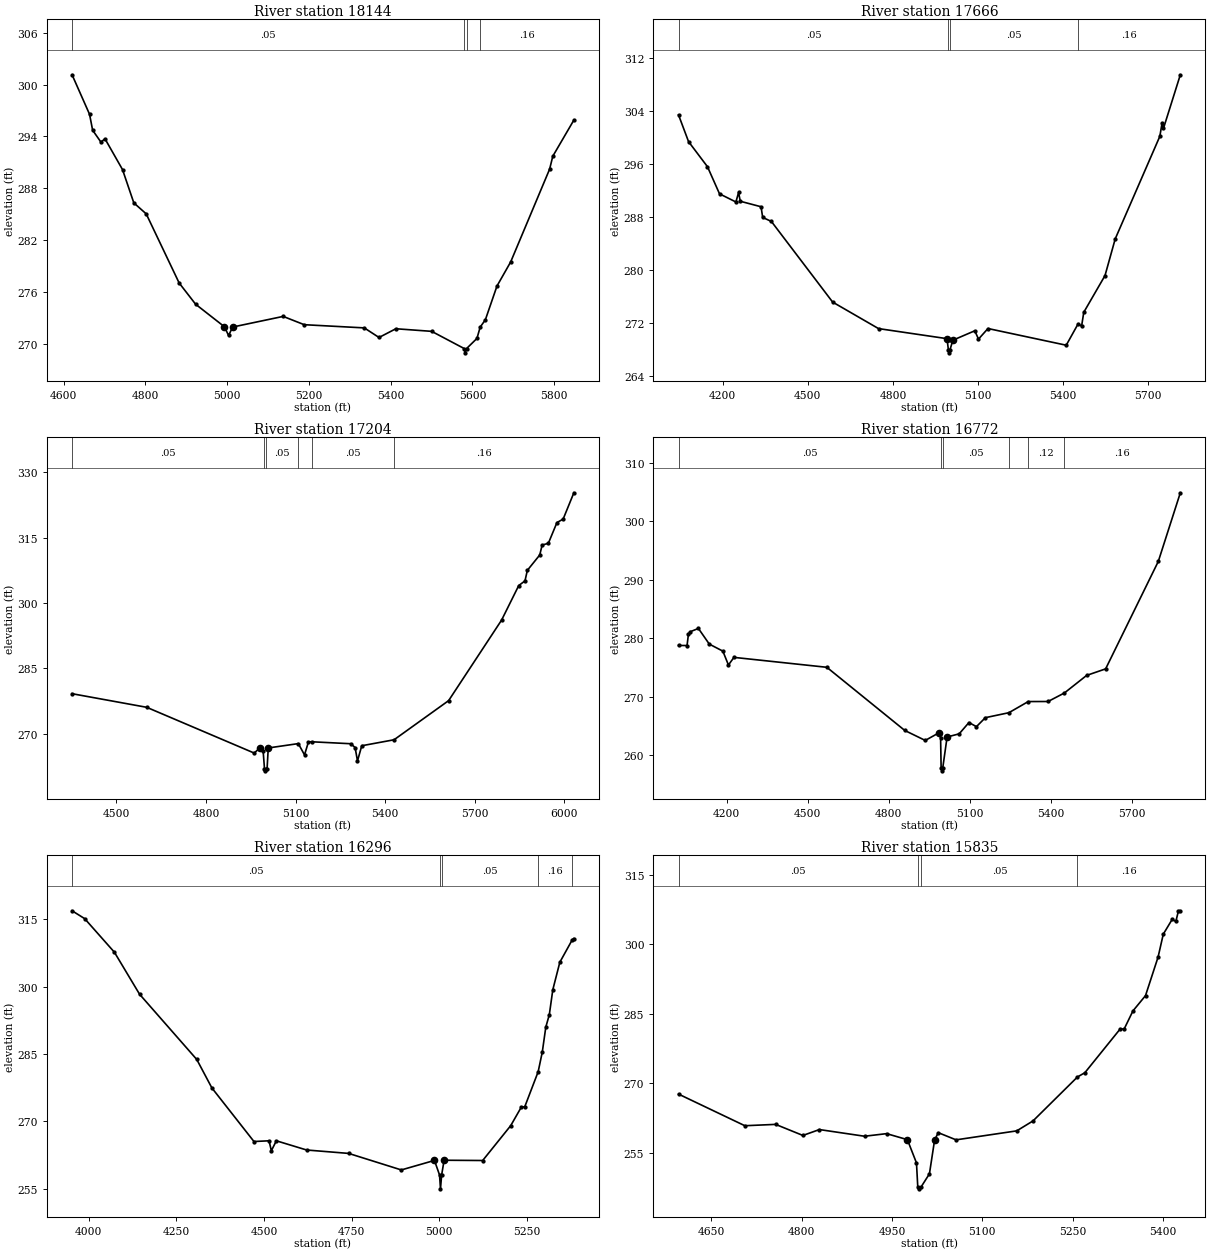
Type RM Length L Ch R = 1 ,18144   ,478,478,478
BEGIN DESCRIPTION:
SALINE BRANCH 30.0
END DESCRIPTION:
XS GIS Cut Line= 3
      3679099.65     10590210.19      3679499.61     10590260.19
      3680299.62     10590460.19
#Sta/Elev= 30
  4620.4  301.14  4663.2  296.56  4670.7  294.72  4690.9  293.35    4701  293.72
  4743.8  290.16  4771.5   286.3  4801.8  285.03  4882.4  277.02  4922.7  274.56
  4993.2  271.95  5003.3  270.94  5013.4  271.92  5136.9  273.15  5188.4  272.19
  5335.3  271.82  5371.4  270.71  5412.6  271.72  5500.2  271.42  5579.7  269.43
  5582.4  268.93  5585.7  269.43    5611   270.6  5618.9  271.91  5631.6  272.76
    5660  276.67  5693.5  279.46  5788.8  290.21  5796.6  291.71  5848.1  295.89
#Mann= 4 ,-1 , 0
  4620.4     .05       0  5579.7     .03       0  5585.7     .05       0
  5618.9     .16       0
Bank Sta=4993.2,5013.4
XS Rating Curve= 0 ,0
Exp/Cntr=0.3,0.1

Type RM Length L Ch R = 1 ,17666   ,462,462,462
BEGIN DESCRIPTION:
SALINE BRANCH 29.0
END DESCRIPTION:
XS GIS Cut Line= 3
      3678799.64     10590210.21      3679599.61     10590710.19
      3680399.62     10590510.19
#Sta/Elev= 30
  4044.8   303.4  4080.1  299.37  4146.8  295.58  4189.2  291.49    4247  290.26
  4256.4   291.7  4262.3  290.37  4335.5  289.54  4341.3  287.93    4372  287.32
  4587.8  275.15  4749.4  271.15  4990.7  269.63  4995.5  267.99  4998.2  267.49
  5001.5  267.99  5011.4   269.4  5088.7  270.82  5101.6  269.56  5135.1  271.16
  5410.8  268.64    5453  271.89  5464.9  271.51  5472.6  273.61  5547.4  279.15
  5583.4  284.69  5740.6  300.17  5748.4  302.15  5753.5  301.38  5812.8  309.46
#Mann= 4 ,-1 , 0
  4044.8     .05       0  4995.5     .03       0  5001.5     .05       0
    5453     .16       0
Bank Sta=4990.7,5011.4
XS Rating Curve= 0 ,0
Exp/Cntr=0.3,0.1

Type RM Length L Ch R = 1 ,17204   ,432,432,432
BEGIN DESCRIPTION:
SALINE BRANCH 28.0
END DESCRIPTION:
XS GIS Cut Line= 3
      3679049.65     10591160.19      3679699.61     10591160.19
      3680499.58     10590510.21
#Sta/Elev= 30
  4351.6  279.19  4601.6  276.07  4961.6  265.57  4981.6  266.82  4991.6     266
  4996.1  261.99  4998.8  261.49  5002.1  261.99  5004.8  261.99  5008.7  266.74
  5109.4  267.74  5130.2  265.14  5143.3  268.13    5154  268.16  5285.3  267.71
  5299.6  266.83  5307.6  263.76  5321.9  267.25  5430.1  268.62  5612.8   277.6
  5790.3  296.09  5847.7  304.01  5868.6  305.08  5876.5   307.5  5918.1  311.03
    5926   313.3  5946.9  313.71  5975.6  318.46  5996.4  319.26  6032.3   325.3
#Mann= 6 ,-1 , 0
  4351.6     .05       0  4996.1     .03       0  5002.1     .05       0
  5109.4     .16       0    5154     .05       0  5430.1     .16       0
Bank Sta=4981.6,5008.7
XS Rating Curve= 0 ,0
Exp/Cntr=0.3,0.1

Type RM Length L Ch R = 1 ,16772   ,476,476,476
BEGIN DESCRIPTION:
SALINE BRANCH 27.0
END DESCRIPTION:
XS GIS Cut Line= 2
      3678876.96     10591700.42      3680712.87     10591422.64
#Sta/Elev= 30
    4022  278.75  4053.5  278.74  4058.5  280.63  4065.1   281.1  4095.5  281.67
  4135.9  278.98    4186  277.78  4206.7   275.4    4227  276.71  4570.8  275.01
  4859.1  264.19  4934.9  262.48  4985.5  263.78  4991.7  262.91  4993.7  257.77
  4996.5  257.27  4999.7  257.77  5015.8  263.07  5060.5  263.61  5096.7  265.55
  5124.3  264.84  5157.4  266.38  5244.4  267.23  5316.1  269.14  5389.4  269.15
  5449.8  270.61  5532.1  273.62  5602.4  274.74  5797.3  293.15  5878.8  304.91
#Mann= 6 ,-1 , 0
    4022     .05       0  4993.7     .03       0  4999.7     .05       0
  5244.4     .16       0  5316.1     .12       0  5449.8     .16       0
Bank Sta=4985.5,5015.8
XS Rating Curve= 0 ,0
Exp/Cntr=0.3,0.1

Type RM Length L Ch R = 1 ,16296   ,461,461,461
BEGIN DESCRIPTION:
SALINE BRANCH 26.0
END DESCRIPTION:
XS GIS Cut Line= 3
      3679149.62     10592660.18      3679949.61     10592010.19
      3680349.64     10592010.19
#Sta/Elev= 30
  3952.8  316.93  3988.7  315.18  4073.5   307.7  4145.3  298.34  4308.4  283.81
  4351.5  277.47  4471.4  265.54  4514.5   265.7    4521  263.48  4535.3   265.7
  4621.6  263.65  4741.5  262.89  4891.6  259.21  4986.1  261.33  5000.6  258.08
  5003.3     255  5006.6  258.08  5013.6  261.37  5123.6  261.31  5203.6  269.08
  5233.6  273.18  5243.6  273.28  5281.8  281.08  5293.6  285.47  5303.6  291.02
  5313.6  293.78  5323.6  299.35  5343.6  305.47  5378.9  310.45  5383.6  310.74
#Mann= 5 ,-1 , 0
  3952.8     .05       0  5000.6     .03       0  5006.6     .05       0
  5281.8     .16       0  5378.9     .05       0
Bank Sta=4986.1,5013.6
XS Rating Curve= 0 ,0
Exp/Cntr=0.3,0.1

Type RM Length L Ch R = 1 ,15835   ,463,463,463
BEGIN DESCRIPTION:
SALINE BRANCH 25.0
END DESCRIPTION:
XS GIS Cut Line= 3
      3679699.65     10592660.16      3680049.61     10592460.19
      3680399.63     10592210.18
#Sta/Elev= 30
  4595.7  267.68  4705.8  260.85  4756.9  261.14  4802.2  258.75  4829.6  260.02
  4904.5  258.58  4941.2  259.14  4975.7  257.84  4990.8  252.81  4992.9  247.72
  4995.6  247.22  4998.9  247.72  5012.3  250.46  5020.9  257.78    5027  259.35
  5056.5   257.8  5157.3  259.74  5184.3  261.89  5258.1  271.38  5270.4   272.3
  5329.3  281.79  5335.5   281.7  5350.2  285.64  5371.1  288.95    5392  297.29
  5400.6  302.22  5415.4  305.42  5421.5  304.97  5425.8  307.27  5428.9  307.27
#Mann= 4 ,-1 , 0
  4595.7     .05       0  4992.9     .03       0  4998.9     .05       0
  5258.1     .16       0
Bank Sta=4975.7,5020.9
XS Rating Curve= 0 ,0
Exp/Cntr=0.3,0.1

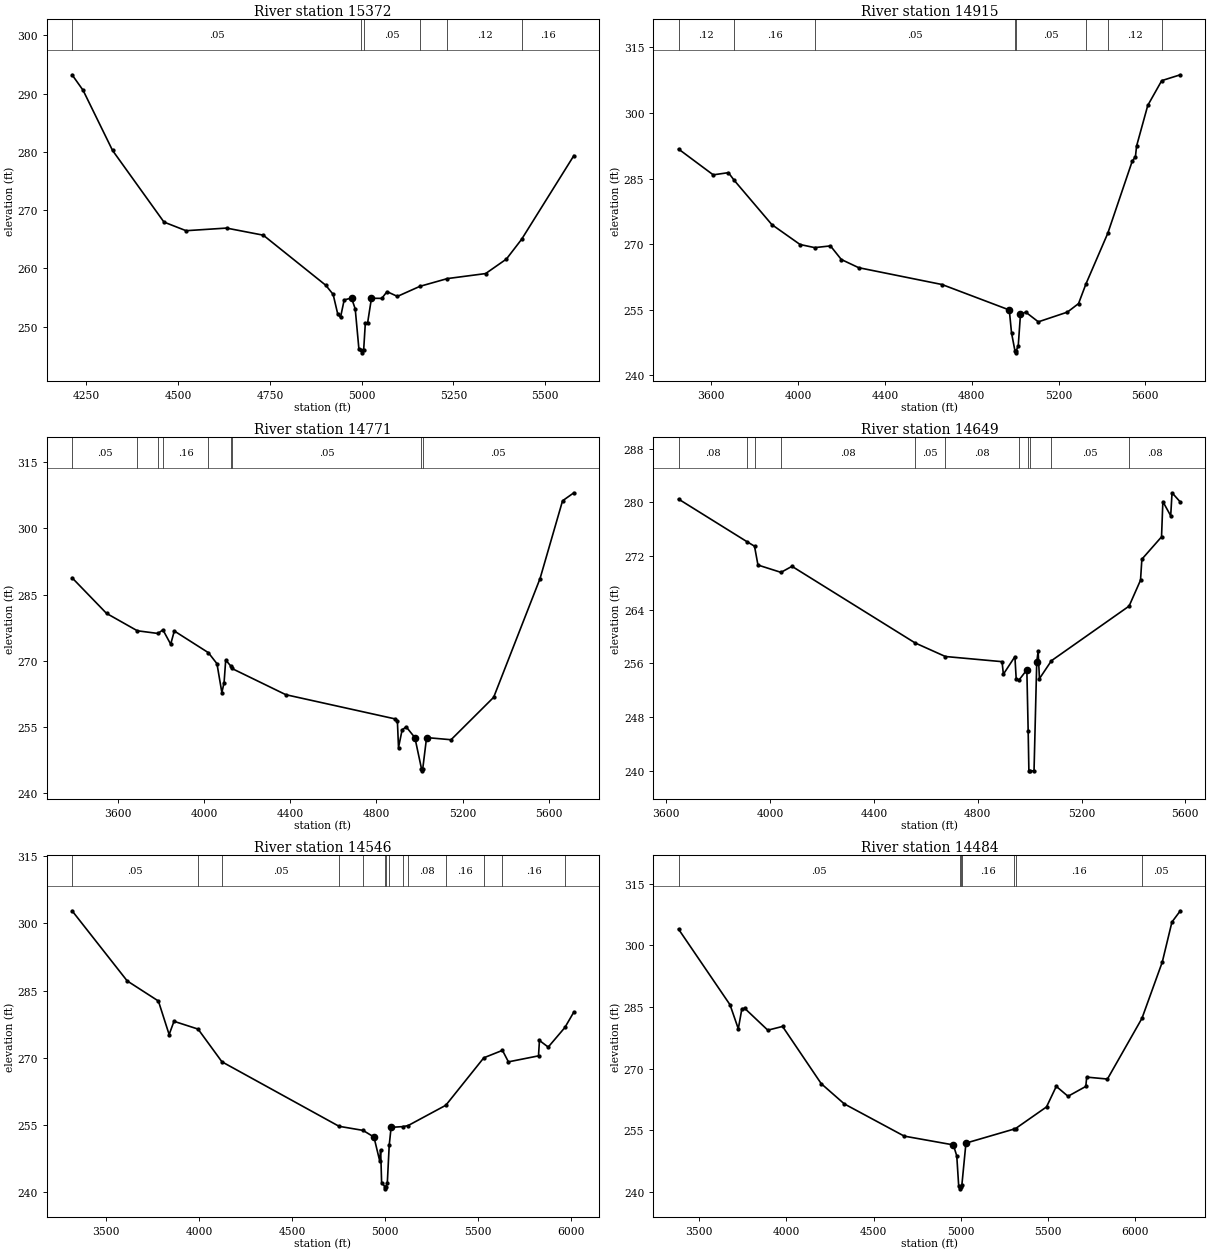
Type RM Length L Ch R = 1 ,15372   ,457,457,457
BEGIN DESCRIPTION:
SALINE BRANCH 24.0
END DESCRIPTION:
XS GIS Cut Line= 3
      3679349.65     10592960.19      3680149.61     10592910.19
      3680549.61     10592510.19
#Sta/Elev= 30
    4211  293.25    4241  290.59  4321.2  280.27  4461.4  267.96  4521.6  266.48
  4631.8  266.93    4732  265.71  4902.3  257.11  4922.3  255.55  4934.9  252.16
  4942.4   251.6  4952.4  254.59  4972.4  254.93  4982.5  253.04  4992.5   246.2
  4999.5  246.01  5002.3  245.51  5005.5  246.01    5010  250.59  5016.1  250.59
  5026.7  254.88  5054.9  254.86  5069.1  256.02  5097.4   255.2  5158.8  256.93
  5233.7  258.26  5337.8  259.12  5394.4  261.61  5435.7  264.99  5578.2  279.37
#Mann= 6 ,-1 , 0
    4211     .05       0  4999.5     .03       0  5005.5     .05       0
  5158.8     .16       0  5233.7     .12       0  5435.7     .16       0
Bank Sta=4972.4,5026.7
XS Rating Curve= 0 ,0
Exp/Cntr=0.3,0.1

Type RM Length L Ch R = 1 ,14915   ,144,144,144
BEGIN DESCRIPTION:
Mapping XS 30e70272
END DESCRIPTION:
XS GIS Cut Line= 3
      3678729.84     10593426.86      3679766.34     10593458.11
      3681005.31     10593156.18
#Sta/Elev= 30
  3449.1  291.74  3608.9  285.84    3679  286.34  3705.7  284.58  3879.1  274.46
  4009.1  269.91  4076.4   269.2  4149.2  269.59  4199.2  266.48  4279.2  264.61
  4663.3  260.76  4973.2  254.94  4983.5   249.7  4999.1  245.64  5001.8  245.14
  5005.1  245.64  5014.4  246.73  5024.7  253.94  5048.9  254.45    5107  252.23
  5240.8  254.45  5292.3   256.4  5326.7  260.93  5427.1  272.49  5539.3  288.91
  5554.5  290.02  5559.9  292.46  5611.3  301.72  5675.6  307.38  5761.3  308.72
#Mann= 8 ,-1 , 0
  3449.1     .12       0  3705.7     .16       0  4076.4     .05       0
  4999.1     .03       0  5005.1     .05       0  5326.7     .16       0
  5427.1     .12       0  5675.6     .05       0
Bank Sta=4973.2,5024.7
XS Rating Curve= 0 ,0
Exp/Cntr=0.3,0.1

Type RM Length L Ch R = 1 ,14771   ,122,122,122
BEGIN DESCRIPTION:
SALINE BRANCH 23.0
END DESCRIPTION:
XS GIS Cut Line= 2
      3678766.35     10593864.36      3681021.53     10593281.03
#Sta/Elev= 30
  3386.9   288.8  3546.8  280.72  3689.9  276.77  3785.7  276.16  3808.6  276.99
  3844.7  273.72  3861.5  276.72  4019.6   271.8  4059.5   269.3  4082.3  262.74
  4092.6  265.02  4100.1  270.13  4122.8  268.82  4128.7  268.22  4379.3  262.26
    4888  256.75  4897.1  256.28  4902.3  250.27    4919  254.26  4937.7  254.98
  4978.3  252.52  5008.9  245.48  5011.7  244.98  5014.9  245.48  5032.6  252.53
  5146.2  252.04    5344  261.67  5559.4  288.63  5663.8  306.27  5716.3  308.09
#Mann= 9 ,-1 , 0
  3386.9     .05       0  3689.9     .08       0  3785.7     .12       0
  3808.6     .16       0  4019.6     .05       0  4122.8     .08       0
  4128.7     .05       0  5008.9     .03       0  5014.9     .05       0
Bank Sta=4978.3,5032.6
XS Rating Curve= 0 ,0
Exp/Cntr=0.3,0.1

Type RM Length L Ch R = 1 ,14649   ,103,103,103
BEGIN DESCRIPTION:
Mapping XS d48eb078
END DESCRIPTION:
XS GIS Cut Line= 3
      3679090.27     10593827.46      3680402.79     10593546.21
      3680975.15     10593397.05
#Sta/Elev= 30
    3647   280.5  3911.2  274.14  3939.8  273.48  3953.1  270.67  4041.8  269.58
  4084.2  270.48  4558.8  259.06  4675.3  257.04  4893.8  256.27  4898.9   254.4
  4943.3  257.02  4948.4  253.62  4959.8  253.57  4989.3  255.05  4994.4  245.99
  4997.2     240  5000.4     240    5017     240  5027.4  256.16  5032.8  257.86
  5037.9  253.74    5084  256.41  5383.3  264.55  5427.4  268.41  5432.6  271.54
  5508.4  274.87  5513.5  280.13  5543.7  278.01  5548.9  281.44  5580.8  280.06
#Mann= 11 ,-1 , 0
    3647     .08       0  3911.2     .16       0  3939.8     .05       0
  4041.8     .08       0  4558.8     .05       0  4675.3     .08       0
  4959.8      .1       0  4994.4     .07       0  5000.4      .1       0
    5084     .05       0  5383.3     .08       0
Bank Sta=4989.3,5027.4
XS Rating Curve= 0 ,0
Exp/Cntr=0.3,0.1

Type RM Length L Ch R = 1 ,14546   ,62,62,62
BEGIN DESCRIPTION:
Mapping XS 1e4e35f8
END DESCRIPTION:
XS GIS Cut Line= 3
      3678812.52     10594033.59      3680440.98     10593641.23
      3681444.41     10593450.27
#Sta/Elev= 30
  3318.1  302.84  3614.3  287.15    3782  282.65  3839.7  275.15  3865.8  278.11
  3995.2  276.37  4123.5  269.05  4752.9  254.62  4881.4  253.71  4940.3  252.22
  4971.2  246.89  4976.3  249.38  4981.5  242.03  4998.9  241.13  5001.7  240.63
  5004.9  241.13  5012.1  241.89  5022.3  250.34  5032.5  254.39  5094.9  254.55
  5123.7  254.78  5326.6  259.33  5530.7  269.95  5630.9  271.61  5662.9  269.04
  5824.6  270.38  5829.7  273.83  5876.8  272.34  5966.4  276.73  6014.6  280.19
#Mann= 14 ,-1 , 0
  3318.1     .05       0  3995.2     .08       0  4123.5     .05       0
  4752.9     .08       0  4881.4     .05       0  4998.9     .03       0
  5004.9     .05       0  5022.3     .16       0  5094.9      .1       0
  5123.7     .08       0  5326.6     .16       0  5530.7     .08       0
  5630.9     .16       0  5966.4     .08       0
Bank Sta=4940.3,5032.5
XS Rating Curve= 0 ,0
Exp/Cntr=0.3,0.1

Type RM Length L Ch R = 1 ,14484   ,194,194,194
BEGIN DESCRIPTION:
SALINE BRANCH 22.0
END DESCRIPTION:
XS GIS Cut Line= 2
      3678886.09     10594072.71      3681686.42     10593411.66
#Sta/Elev= 30
  3381.4  303.96  3676.6  285.54  3724.1  279.69  3744.6  284.56  3761.2  284.66
  3893.3  279.35  3977.9  280.26  4199.7  266.32  4331.8   261.4  4675.5  253.55
  4957.1  251.41  4976.8  248.73  4987.9  241.38  4995.2  241.21  4997.9  240.71
  5001.2  241.21  5005.9  241.56  5029.4  251.85  5305.5  255.27  5313.6  255.38
  5491.4  260.66  5547.4  265.67  5614.7  263.25  5716.7  265.65  5721.8  267.92
  5840.7  267.45  6038.7  282.24  6155.2  295.94  6210.6  305.69  6258.7  308.43
#Mann= 7 ,-1 , 0
  3381.4     .05       0  4995.2     .03       0  5001.2     .05       0
  5005.9     .16       0  5305.5     .08       0  5313.6     .16       0
  6038.7     .05       0
Bank Sta=4957.1,5029.4
XS Rating Curve= 0 ,0
Exp/Cntr=0.3,0.1