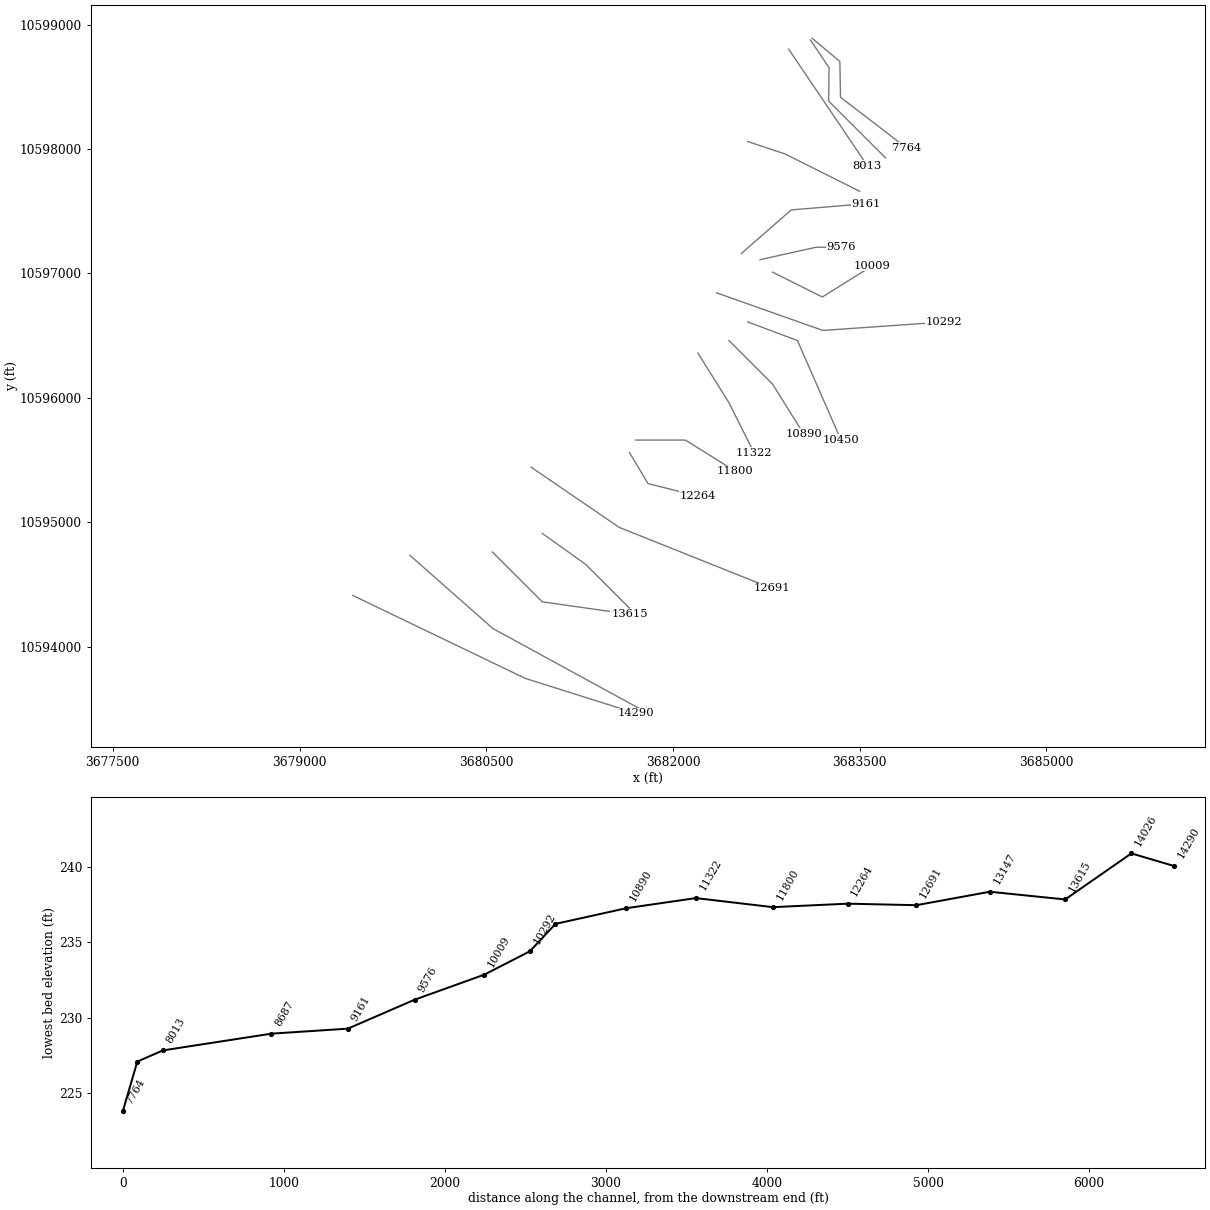
HEC-RAS study SALINE BRANCH.prj: SALINE BRANCH Base Level Engineering

--- SALINE BRANCH.g01 (geometry) --- (continued)

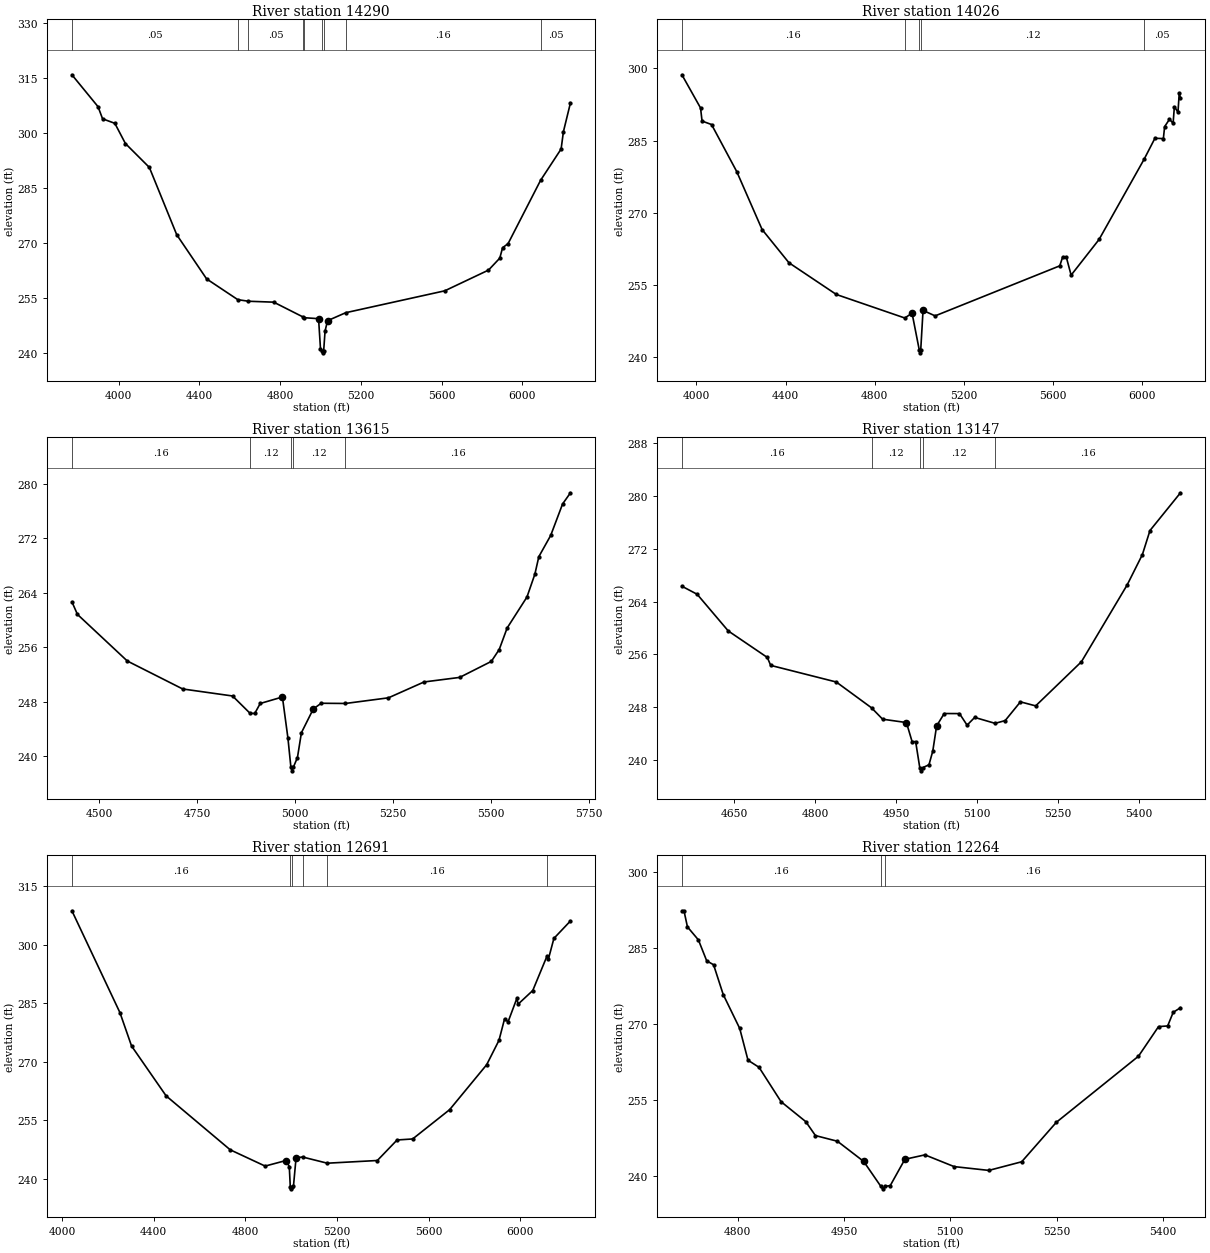
Type RM Length L Ch R = 1 ,14290   ,264,264,264
BEGIN DESCRIPTION:
Mapping XS 1d5281fb
END DESCRIPTION:
XS GIS Cut Line= 3
      3679427.83     10594411.22      3680813.21     10593744.57
      3681703.83     10593463.33
#Sta/Elev= 30
  3767.7  315.78  3897.1   307.1  3919.7  303.79  3980.5  302.56  4032.9  297.06
  4151.6  290.55  4287.3  272.22  4435.5  260.19    4590  254.54    4643  254.11
  4768.1  253.86  4911.8  249.87  4915.8  249.64  4990.4  249.36  4999.9  241.15
  5009.6  240.56  5012.3  240.06  5015.6  240.56  5022.6  245.99  5034.8  248.81
  5125.1  250.99    5616  256.95  5832.7  262.59  5888.6  265.84  5902.6  268.69
  5929.7  269.79  6090.9  287.04  6192.7  295.57  6204.1  300.29  6239.1  308.16
#Mann= 9 ,-1 , 0
  3767.7     .05       0    4590     .16       0    4643     .05       0
  4911.8     .16       0  4915.8     .05       0  5009.6     .03       0
  5015.6     .05       0  5125.1     .16       0  6090.9     .05       0
Bank Sta=4990.4,5034.8
XS Rating Curve= 0 ,0
Exp/Cntr=0.3,0.1

Type RM Length L Ch R = 1 ,14026   ,411,411,411
BEGIN DESCRIPTION:
SALINE BRANCH 21.0
END DESCRIPTION:
XS GIS Cut Line= 3
       3679886.1     10594734.18       3680552.8     10594145.61
      3681734.82     10593499.93
#Sta/Elev= 30
  3934.8  298.68  4018.4  291.78  4025.1  289.06  4067.7  288.34  4180.6  278.57
  4294.4  266.52  4414.9  259.61  4627.4  253.02  4934.5  248.13    4967  249.14
  4999.8  241.39  5002.6  240.89  5005.8  241.39  5016.3  249.71  5070.4  248.57
  5629.5  258.97  5642.6  260.82  5658.7  260.81  5680.5  257.04  5805.8  264.45
  6008.5  281.18  6056.3  285.48  6094.2  285.42  6099.9  287.91  6121.7  289.43
  6137.9   288.6  6143.6  292.05  6159.7   290.9  6165.4  294.83    6171  293.86
#Mann= 5 ,-1 , 0
  3934.8     .16       0  4934.5     .12       0  4999.8     .07       0
  5005.8     .12       0  6008.5     .05       0
Bank Sta=4967,5016.3
XS Rating Curve= 0 ,0
Exp/Cntr=0.3,0.1

Type RM Length L Ch R = 1 ,13615   ,468,468,468
BEGIN DESCRIPTION:
SALINE BRANCH 20.0
END DESCRIPTION:
XS GIS Cut Line= 3
      3680549.63     10594760.17      3680949.61     10594360.19
      3681649.64     10594260.18
#Sta/Elev= 30
  4430.6  262.68  4444.7  260.83    4572  253.98  4713.4  249.87  4840.7  248.84
  4885.5  246.29  4897.3  246.27  4911.4  247.74    4968  248.69  4982.1  242.64
  4989.7  238.34  4992.5  237.84  4995.7  238.34  5006.4   239.8  5016.5  243.44
  5046.8  246.93    5067  247.77    5129  247.74  5238.7  248.57  5329.6   250.9
  5420.5  251.57  5501.3  253.92  5521.5  255.67  5541.7  258.83  5592.3  263.38
  5612.5  266.74  5622.6  269.31  5652.9  272.43  5683.2  277.05  5703.4   278.7
#Mann= 5 ,-1 , 0
  4430.6     .16       0  4885.5     .12       0  4989.7     .07       0
  4995.7     .12       0    5129     .16       0
Bank Sta=4968,5046.8
XS Rating Curve= 0 ,0
Exp/Cntr=0.3,0.1

Type RM Length L Ch R = 1 ,13147   ,456,456,456
BEGIN DESCRIPTION:
SALINE BRANCH 19.0
END DESCRIPTION:
XS GIS Cut Line= 3
      3680949.59      10594910.2      3681299.61     10594660.19
       3681649.6     10594310.19
#Sta/Elev= 30
  4552.8  266.34  4581.1  265.12  4638.8  259.56  4711.3  255.54  4717.5  254.34
  4839.2  251.82  4904.7   247.9  4925.2  246.18  4969.4  245.67  4979.9  242.78
  4986.5  242.78  4994.1  238.85  4996.8  238.35  5000.1  238.85  5011.2  239.27
  5018.3  241.35  5025.4  245.16  5039.5  247.04  5067.8  247.03  5081.9  245.28
  5096.1  246.45  5133.9  245.55  5152.6  245.97  5180.9  248.81  5209.2   248.2
  5294.1  254.89  5378.9  266.53  5407.2  271.14  5421.3  274.79  5477.9  280.51
#Mann= 5 ,-1 , 0
  4552.8     .16       0  4904.7     .12       0  4994.1     .07       0
  5000.1     .12       0  5133.9     .16       0
Bank Sta=4969.4,5025.4
XS Rating Curve= 0 ,0
Exp/Cntr=0.3,0.1

Type RM Length L Ch R = 1 ,12691   ,427,427,427
BEGIN DESCRIPTION:
SALINE BRANCH 18.0
END DESCRIPTION:
XS GIS Cut Line= 3
      3680860.08     10595442.49      3681568.42     10594958.11
      3682792.42     10594468.51
#Sta/Elev= 30
  4043.2  308.71  4252.8  282.62  4303.6  274.06  4454.5  261.28  4734.3  247.46
  4886.7  243.29    4978  244.72  4992.1  243.18  4996.5  237.96  4999.3  237.46
  5002.5  237.96  5010.3  238.11  5021.7   245.4  5049.8  245.62    5158  244.03
  5376.5  244.72  5462.7  249.98  5530.6  250.24  5692.1  257.75  5853.7  269.26
  5907.5  275.51  5931.8     281  5947.3  280.27  5985.6  286.27    5991  284.78
    6055  288.28  6116.9  297.07  6122.9  296.25  6147.2  301.63  6219.6  306.11
#Mann= 6 ,-1 , 0
  4043.2     .16       0  4996.5     .07       0  5002.5     .16       0
  5049.8     .12       0    5158     .16       0  6116.9     .05       0
Bank Sta=4978,5021.7
XS Rating Curve= 0 ,0
Exp/Cntr=0.3,0.1

Type RM Length L Ch R = 1 ,12264   ,464,464,464
BEGIN DESCRIPTION:
SALINE BRANCH 17.0
END DESCRIPTION:
XS GIS Cut Line= 3
       3681649.6      10595560.2      3681799.61     10595310.19
      3682199.64     10595210.18
#Sta/Elev= 30
  4721.1  292.32    4724  292.32  4728.9  289.15  4744.4  286.58  4756.1  282.46
  4765.8  281.69  4779.4  275.83  4802.7  269.15  4814.4  262.89    4830  261.49
  4861.1  254.72    4896  250.79  4909.6  248.05  4940.7  246.93  4977.7  242.96
  5001.9  238.06  5004.6  237.56  5007.9  238.06  5015.2  238.19  5035.9  243.38
  5064.2  244.25  5105.4  241.94  5154.4  241.19  5200.8  242.89  5249.7  250.66
  5365.7  263.68    5394  269.51  5406.9  269.64  5414.7  272.32    5425  273.23
#Mann= 3 ,-1 , 0
  4721.1     .16       0  5001.9     .07       0  5007.9     .16       0
Bank Sta=4977.7,5035.9
XS Rating Curve= 0 ,0
Exp/Cntr=0.3,0.1

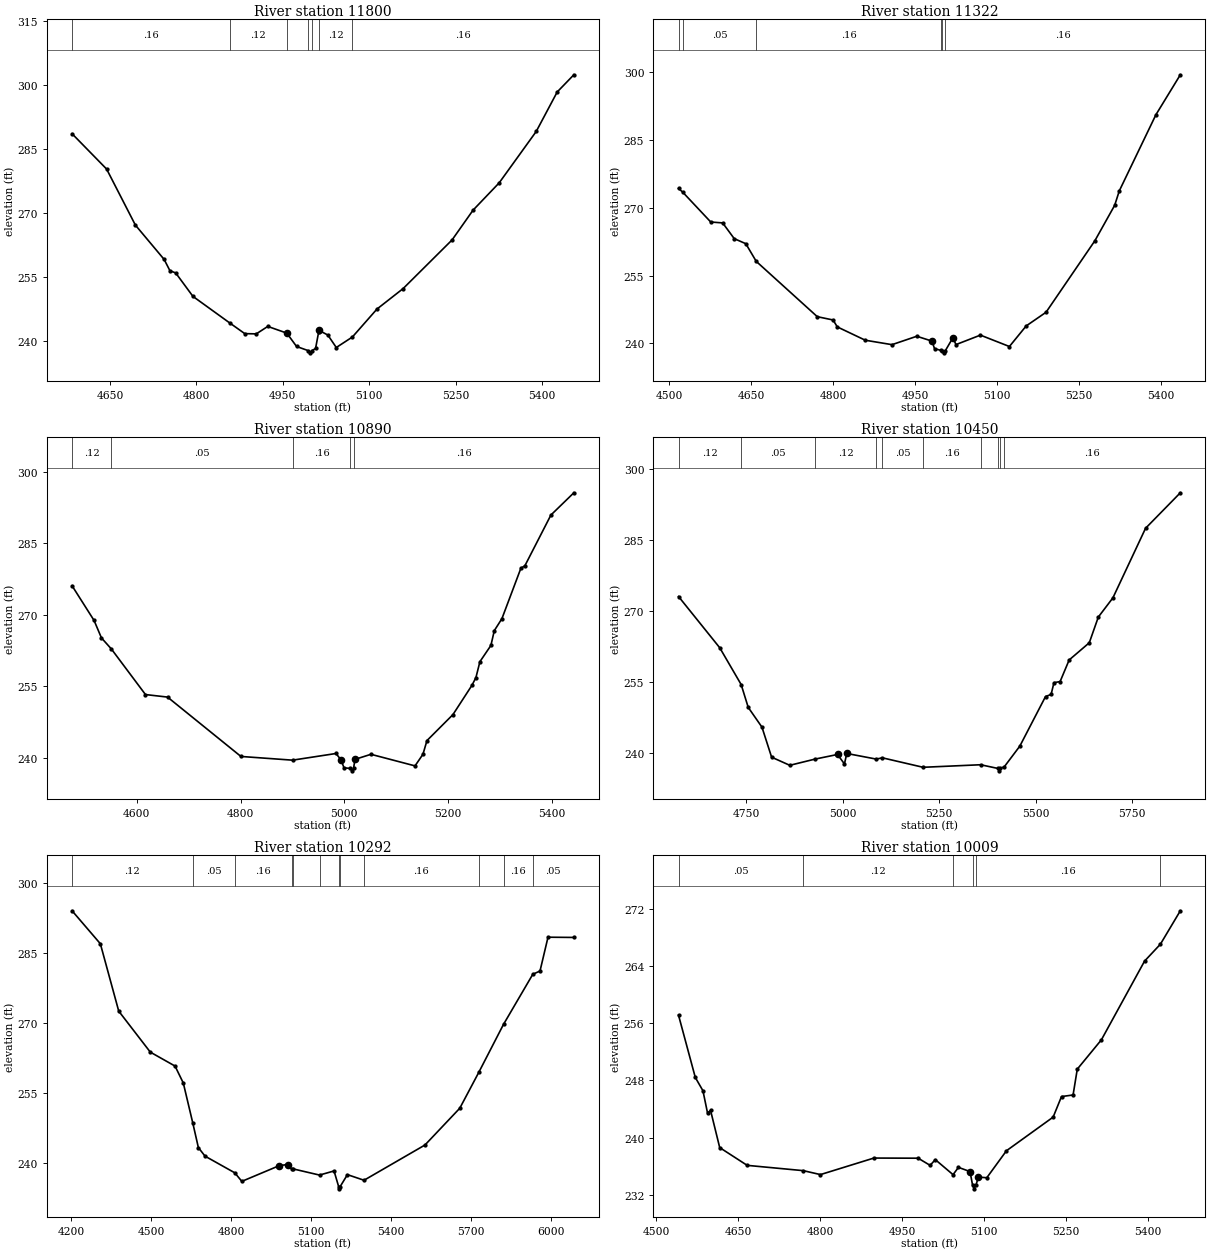
Type RM Length L Ch R = 1 ,11800   ,478,478,478
BEGIN DESCRIPTION:
SALINE BRANCH 16.0
END DESCRIPTION:
XS GIS Cut Line= 3
      3681699.58     10595660.19      3682099.61     10595660.19
      3682499.58      10595410.2
#Sta/Elev= 30
  4583.9  288.65  4643.9  280.38  4693.9  267.25  4743.9   259.2  4753.9  256.56
  4763.9  256.05  4793.9  250.55    4858  244.31  4883.9  241.83  4903.9  241.77
  4923.9  243.52  4956.9  241.95  4973.9  238.82  4994.5  237.83  4997.2  237.33
  5000.5  237.83  5006.9  238.36  5012.2  242.17  5012.8   242.6  5028.2   241.5
  5042.9  238.58  5070.8  241.03  5113.6  247.59    5159  252.38    5244  263.77
  5280.5  270.75  5325.9  277.15  5390.2  289.18  5426.7  298.44  5455.6  302.46
#Mann= 7 ,-1 , 0
  4583.9     .16       0    4858     .12       0  4956.9     .16       0
  4994.5     .07       0  5000.5     .16       0  5012.2     .12       0
  5070.8     .16       0
Bank Sta=4956.9,5012.8
XS Rating Curve= 0 ,0
Exp/Cntr=0.3,0.1

Type RM Length L Ch R = 1 ,11322   ,432,432,432
BEGIN DESCRIPTION:
SALINE BRANCH 15.0
END DESCRIPTION:
XS GIS Cut Line= 3
       3682199.6      10596360.2      3682449.61     10595960.19
       3682649.6     10595560.21
#Sta/Elev= 30
  4516.9  274.31  4524.2  273.53  4575.9  266.88  4597.7  266.68  4618.9   263.2
  4640.1  262.08  4659.2  258.17    4771  245.93  4799.9   245.2  4807.6  243.67
  4858.9  240.72  4907.8  239.74  4953.2   241.6  4980.9  240.53  4985.7  238.86
  4997.5  238.47  4999.6  238.43  5002.3  237.93  5005.6  238.43  5019.4  241.29
  5024.9  239.75  5069.7  241.85  5122.8  239.33  5153.5  243.88  5189.9  246.91
  5279.3  262.73  5315.6  270.58    5324  273.76  5391.1  290.62  5435.8  299.46
#Mann= 6 ,-1 , 0
  4516.9     .12       0  4524.2     .05       0  4659.2     .16       0
  4997.5     .12       0  4999.6     .07       0  5005.6     .16       0
Bank Sta=4980.9,5019.4
XS Rating Curve= 0 ,0
Exp/Cntr=0.3,0.1

Type RM Length L Ch R = 1 ,10890   ,440,440,440
BEGIN DESCRIPTION:
SALINE BRANCH 14.0
END DESCRIPTION:
XS GIS Cut Line= 3
       3682449.6     10596460.19      3682799.61     10596110.19
      3683049.62     10595710.17
#Sta/Elev= 30
  4475.5   276.1  4517.9  268.82  4532.1  265.16  4551.2  262.84  4616.9  253.27
  4659.4  252.74  4800.8  240.28  4900.2   239.5    4984   240.9  4993.5  239.58
  4999.4   237.9  5011.7  237.76  5014.5  237.26  5017.7  237.76  5020.6  239.67
  5051.3  240.73  5136.2   238.3  5151.5  240.74  5159.2  243.61  5209.3  249.07
  5245.8   255.2  5253.5  256.82  5261.2  260.17  5282.4  263.58  5288.9  266.68
  5303.6   269.2  5340.2   279.8  5347.8  280.29    5398  290.95  5442.2  295.62
#Mann= 5 ,-1 , 0
  4475.5     .12       0  4551.2     .05       0  4900.2     .16       0
  5011.7     .07       0  5017.7     .16       0
Bank Sta=4993.5,5020.6
XS Rating Curve= 0 ,0
Exp/Cntr=0.3,0.1

Type RM Length L Ch R = 1 ,10450   ,158,158,158
BEGIN DESCRIPTION:
SALINE BRANCH 13.0
END DESCRIPTION:
XS GIS Cut Line= 3
      3682599.64     10596610.18      3682999.61     10596460.19
      3683349.62     10595660.17
#Sta/Elev= 30
  4574.7  273.09  4681.5  262.25    4737  254.47  4755.3  249.64  4790.9  245.46
  4815.9  239.11    4863  237.39  4928.3   238.7  4986.7  239.68  5004.6  237.68
  5010.8  239.89  5086.8  238.71  5103.2  238.97  5208.5  236.97  5357.6  237.51
  5402.7  236.72  5405.5  236.22  5408.7  236.72    5419  237.09  5459.1  241.44
  5525.8  251.94  5540.2  252.38  5547.6  254.86  5563.6  255.11    5587  259.67
  5639.2  263.31  5662.6  268.75  5700.4  272.81    5785  287.52  5875.1  295.03
#Mann= 10 ,-1 , 0
  4574.7     .12       0    4737     .05       0  4928.3     .12       0
  5086.8     .16       0  5103.2     .05       0  5208.5     .16       0
  5357.6     .05       0  5402.7     .07       0  5408.7     .05       0
    5419     .16       0
Bank Sta=4986.7,5010.8
XS Rating Curve= 0 ,0
Exp/Cntr=0.3,0.1

Type RM Length L Ch R = 1 ,10292   ,283,283,283
BEGIN DESCRIPTION:
Mapping XS 66adac9f
END DESCRIPTION:
XS GIS Cut Line= 3
      3682349.72     10596843.51      3683203.84     10596541.45
      3684176.23     10596609.05
#Sta/Elev= 30
  4203.6  293.96  4309.6   286.9  4378.5  272.47  4496.8  263.69  4589.6   260.7
  4620.5  257.07  4655.8  248.57    4677  243.24    4702  241.41  4813.5  237.84
  4839.9  236.01  4980.7  239.39  5011.6  239.62  5026.3  238.66  5032.8  238.67
    5131  237.36  5185.5  238.24  5202.6  234.91  5205.3  234.41  5208.6  234.91
  5235.6  237.45  5297.9  236.25  5526.3   243.8  5656.7  251.67    5728  259.36
  5820.6  269.63  5930.4  280.36  5957.4  281.06  5987.4   288.3  6084.3  288.25
#Mann= 12 ,-1 , 0
  4203.6     .12       0  4655.8     .05       0  4813.5     .16       0
  5026.3     .12       0  5032.8     .16       0    5131     .12       0
  5202.6     .07       0  5208.6     .12       0  5297.9     .16       0
    5728     .05       0  5820.6     .16       0  5930.4     .05       0
Bank Sta=4980.7,5011.6
XS Rating Curve= 0 ,0
Exp/Cntr=0.3,0.1

Type RM Length L Ch R = 1 ,10009   ,433,433,433
BEGIN DESCRIPTION:
SALINE BRANCH 12.0
END DESCRIPTION:
XS GIS Cut Line= 3
      3682799.65     10597010.17      3683199.61     10596810.19
      3683599.64     10597060.21
#Sta/Elev= 30
  4540.9  257.11  4571.6  248.42  4585.6  246.56    4594  243.45  4599.5  243.83
  4616.3  238.62  4666.6  236.14  4769.4   235.4  4800.8  234.85  4898.6  237.16
  4979.7  237.14  5001.6  236.14  5011.1  236.94  5043.6  234.84  5053.5  235.86
  5074.7  235.27  5079.4  233.36  5082.2  232.86  5085.4  233.36  5090.1   234.5
  5105.4  234.41  5141.4  238.18  5226.9  242.88  5242.2  245.75  5263.4  245.97
  5271.1  249.58  5315.3  253.68  5394.3  264.67  5423.3  267.03  5459.8   271.7
#Mann= 6 ,-1 , 0
  4540.9     .05       0  4769.4     .12       0  5043.6     .16       0
  5079.4     .07       0  5085.4     .16       0  5423.3     .05       0
Bank Sta=5074.7,5090.1
XS Rating Curve= 0 ,0
Exp/Cntr=0.3,0.1

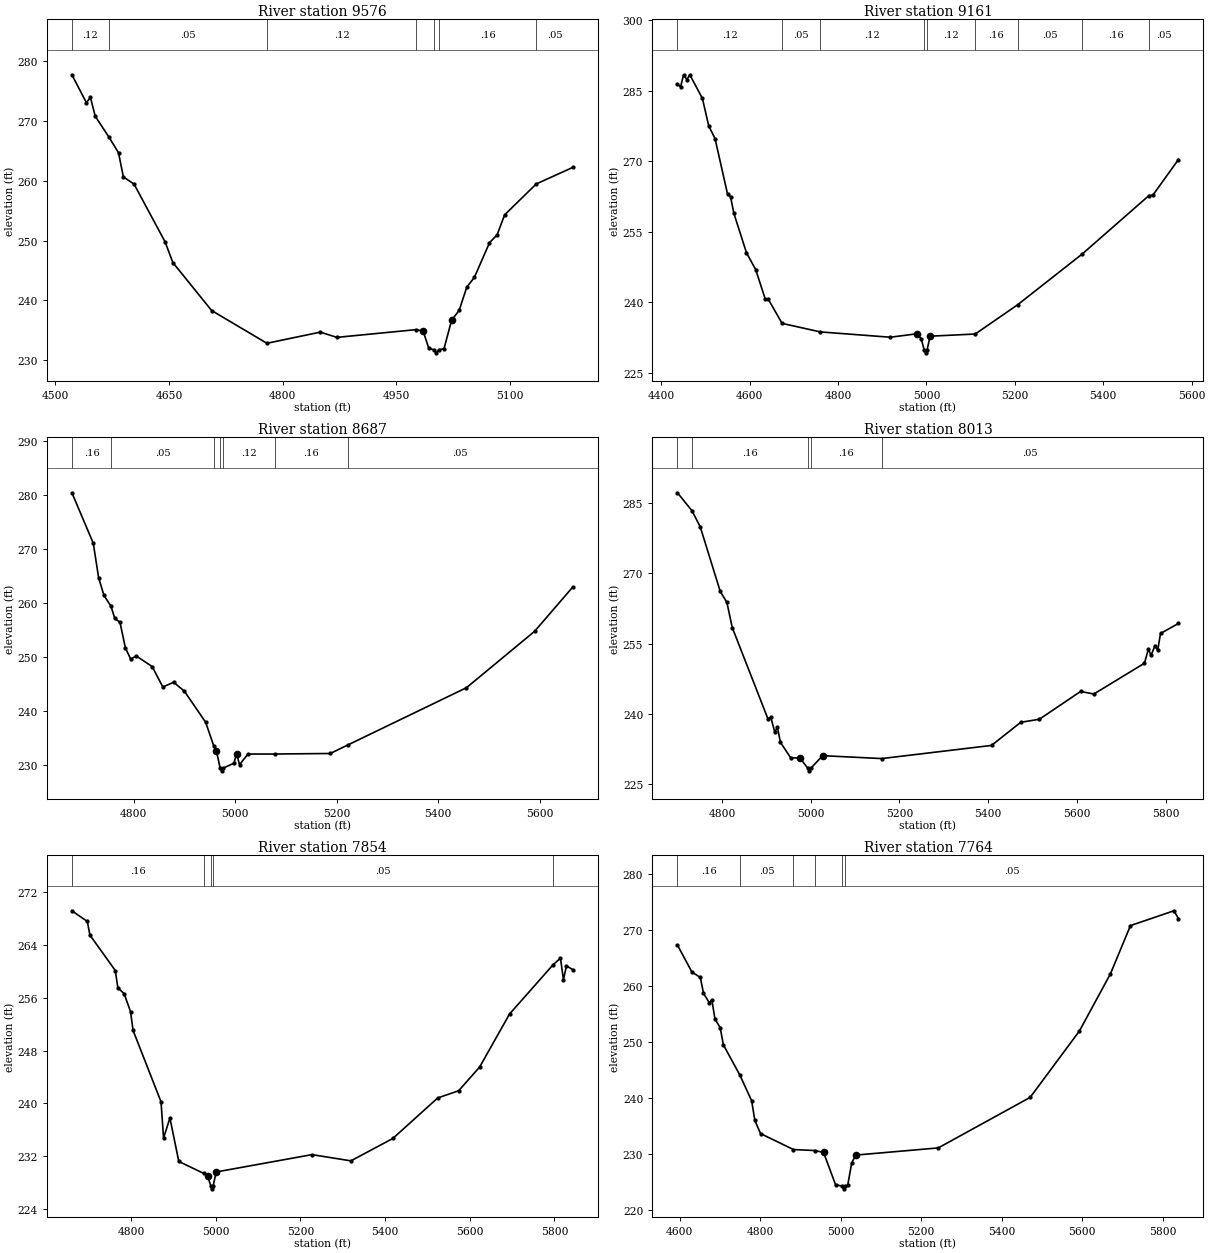
Type RM Length L Ch R = 1 ,9576    ,415,415,415
BEGIN DESCRIPTION:
SALINE BRANCH 11.0
END DESCRIPTION:
XS GIS Cut Line= 3
      3682699.57     10597110.18      3683149.61     10597210.19
      3683349.59     10597210.19
#Sta/Elev= 30
  4521.9  277.76  4541.1  273.07  4546.3     274  4552.7  270.81  4570.6  267.36
  4583.4   264.7  4589.8  260.66  4603.9  259.46  4644.9  249.77  4655.1  246.32
  4706.3  238.28  4779.2   232.8  4849.7  234.67  4871.5  233.79  4976.5  235.09
  4985.4  234.82  4992.9  231.93  4999.9   231.7  5002.7   231.2  5005.9   231.7
  5012.9   231.9  5022.9  236.66  5032.9  238.32  5042.9  242.19  5052.9  243.82
  5072.9  249.64  5082.9  250.95  5092.9  254.31  5134.6  259.48  5182.9  262.26
#Mann= 7 ,-1 , 0
  4521.9     .12       0  4570.6     .05       0  4779.2     .12       0
  4976.5     .16       0  4999.9     .07       0  5005.9     .16       0
  5134.6     .05       0
Bank Sta=4985.4,5022.9
XS Rating Curve= 0 ,0
Exp/Cntr=0.3,0.1

Type RM Length L Ch R = 1 ,9161    ,474,474,474
BEGIN DESCRIPTION:
SALINE BRANCH 10.0
END DESCRIPTION:
XS GIS Cut Line= 3
       3682549.6     10597160.18      3682949.61     10597510.19
      3683549.62     10597560.19
#Sta/Elev= 30
  4436.5  286.35  4443.6  285.88  4450.3  288.37  4457.9   287.4  4464.5  288.41
    4493  283.37  4507.2  277.56  4521.5  274.84  4549.9  263.02  4556.6  262.49
  4564.2  258.93  4592.6  250.58  4613.5  246.98  4635.3  240.69    4642  240.68
  4673.3  235.54  4759.8  233.73  4918.2   232.6    4978  233.33  4988.1  232.26
  4995.1  229.78  4997.9  229.28  5001.1  229.78  5008.2  232.82  5110.3  233.28
  5206.2   239.5  5351.9  250.26  5503.5  262.73  5512.4  262.83  5570.1  270.38
#Mann= 9 ,-1 , 0
  4436.5     .12       0  4673.3     .05       0  4759.8     .12       0
  4995.1     .07       0  5001.1     .12       0  5110.3     .16       0
  5206.2     .05       0  5351.9     .16       0  5503.5     .05       0
Bank Sta=4978,5008.2
XS Rating Curve= 0 ,0
Exp/Cntr=0.3,0.1

Type RM Length L Ch R = 1 ,8687    ,674,674,674
BEGIN DESCRIPTION:
SALINE BRANCH 9.0
END DESCRIPTION:
XS GIS Cut Line= 3
      3682599.63     10598060.18      3682899.61     10597960.19
      3683499.58      10597660.2
#Sta/Elev= 30
  4678.5  280.39  4720.6  271.06  4731.2  264.64  4741.7   261.4  4755.6  259.39
  4762.8   257.2  4773.3   256.4  4783.9   251.7  4794.4   249.6    4805  250.21
  4836.6  248.25  4857.7  244.46  4878.8  245.33  4899.8  243.72    4942  237.94
  4958.1  233.53  4963.1  232.68  4970.6  229.45  4973.4  228.95  4976.6  229.45
  4997.5  230.35  5003.1  232.13  5008.7  230.09  5025.5  232.06  5077.8  232.06
  5187.6  232.16  5221.6  233.71  5455.9  244.33  5590.1  254.76  5665.5  262.97
#Mann= 7 ,-1 , 0
  4678.5     .16       0  4755.6     .05       0  4958.1     .12       0
  4970.6     .07       0  4976.6     .12       0  5077.8     .16       0
  5221.6     .05       0
Bank Sta=4963.1,5003.1
XS Rating Curve= 0 ,0
Exp/Cntr=0.3,0.1

Type RM Length L Ch R = 1 ,8013    ,159,159,159
BEGIN DESCRIPTION:
Mapping XS b44d068b
END DESCRIPTION:
XS GIS Cut Line= 2
      3682928.92     10598802.51      3683560.89     10597866.72
#Sta/Elev= 30
  4699.8  287.24  4732.7  283.38  4751.3  279.92  4796.2  266.18  4811.2  263.83
  4823.3  258.45  4904.1  238.86  4910.1  239.36  4919.1  236.09  4925.1  237.18
  4931.9  233.93    4955  230.62    4976  230.58    4994  228.34  4996.8  227.84
    5000  228.34    5027  231.08  5160.3  230.46  5407.7  233.27  5473.6  238.21
  5515.6  238.86  5608.5   244.8  5638.4  244.25  5752.4  250.83  5761.3  253.84
  5767.3  252.51  5776.3  254.61  5782.3  253.59  5788.6  257.18    5829  259.32
#Mann= 5 ,-1 , 0
  4699.8     .05       0  4732.7     .16       0    4994     .07       0
    5000     .16       0  5160.3     .05       0
Bank Sta=4976,5027
XS Rating Curve= 0 ,0
Exp/Cntr=0.3,0.1

Type RM Length L Ch R = 1 ,7854    ,90,90,90
BEGIN DESCRIPTION:
SALINE BRANCH 8.0
END DESCRIPTION:
XS GIS Cut Line= 4
      3683104.24     10598875.48      3683253.57     10598653.21
       3683250.1     10598385.85      3683708.41     10597927.54
#Sta/Elev= 30
  4660.1  269.13  4696.6  267.51  4702.6  265.46  4762.6   260.1  4768.6  257.51
  4783.6  256.58  4798.6  253.88  4804.6  251.04  4870.6  240.26  4876.6  234.77
  4891.6  237.81  4912.6  231.24  4971.9  229.42  4980.9  228.99  4987.9   227.6
  4990.7   227.1  4993.9   227.6  5000.9  229.65  5227.2  232.27  5319.1  231.33
  5418.1  234.71  5524.2  240.84  5573.7  241.93  5623.2  245.51  5693.9  253.53
  5795.8  260.91  5814.1  261.98  5821.2  258.71  5828.2   260.8  5843.4  260.23
#Mann= 5 ,-1 , 0
  4660.1     .16       0  4971.9     .05       0  4987.9     .04       0
  4993.9     .05       0  5795.8     .08       0
Bank Sta=4980.9,5000.9
XS Rating Curve= 0 ,0
Exp/Cntr=0.3,0.1

Type RM Length L Ch R = 1 ,7764    ,155,155,155
BEGIN DESCRIPTION:
SALINE BRANCH 7.0
END DESCRIPTION:
XS GIS Cut Line= 4
      3683118.17     10598889.31      3683340.38     10598703.56
      3683345.59     10598415.37      3683874.82     10598009.33
#Sta/Elev= 30
  4594.4  267.35  4630.4  262.53  4651.3  261.57  4659.1  258.75  4673.4  257.05
  4679.9  257.54  4687.5  254.18  4700.7  252.57  4708.5  249.53  4749.2  244.17
  4778.8  239.54  4786.6  236.05  4800.9  233.68  4882.6  230.83  4936.1  230.65
  4957.4  230.32  4987.4  224.52  5004.4  224.31  5007.2  223.81  5010.4  224.31
  5017.4  224.43  5027.4  228.43  5037.4  229.84  5242.5  231.12  5470.9  240.15
  5593.3  252.01  5670.3  262.21  5720.1  270.83  5828.1  273.48  5839.3   272.1
#Mann= 6 ,-1 , 0
  4594.4     .16       0  4749.2     .05       0  4882.6     .16       0
  4936.1     .05       0  5004.4     .04       0  5010.4     .05       0
Bank Sta=4957.4,5037.4
XS Rating Curve= 0 ,0
Exp/Cntr=0.3,0.1