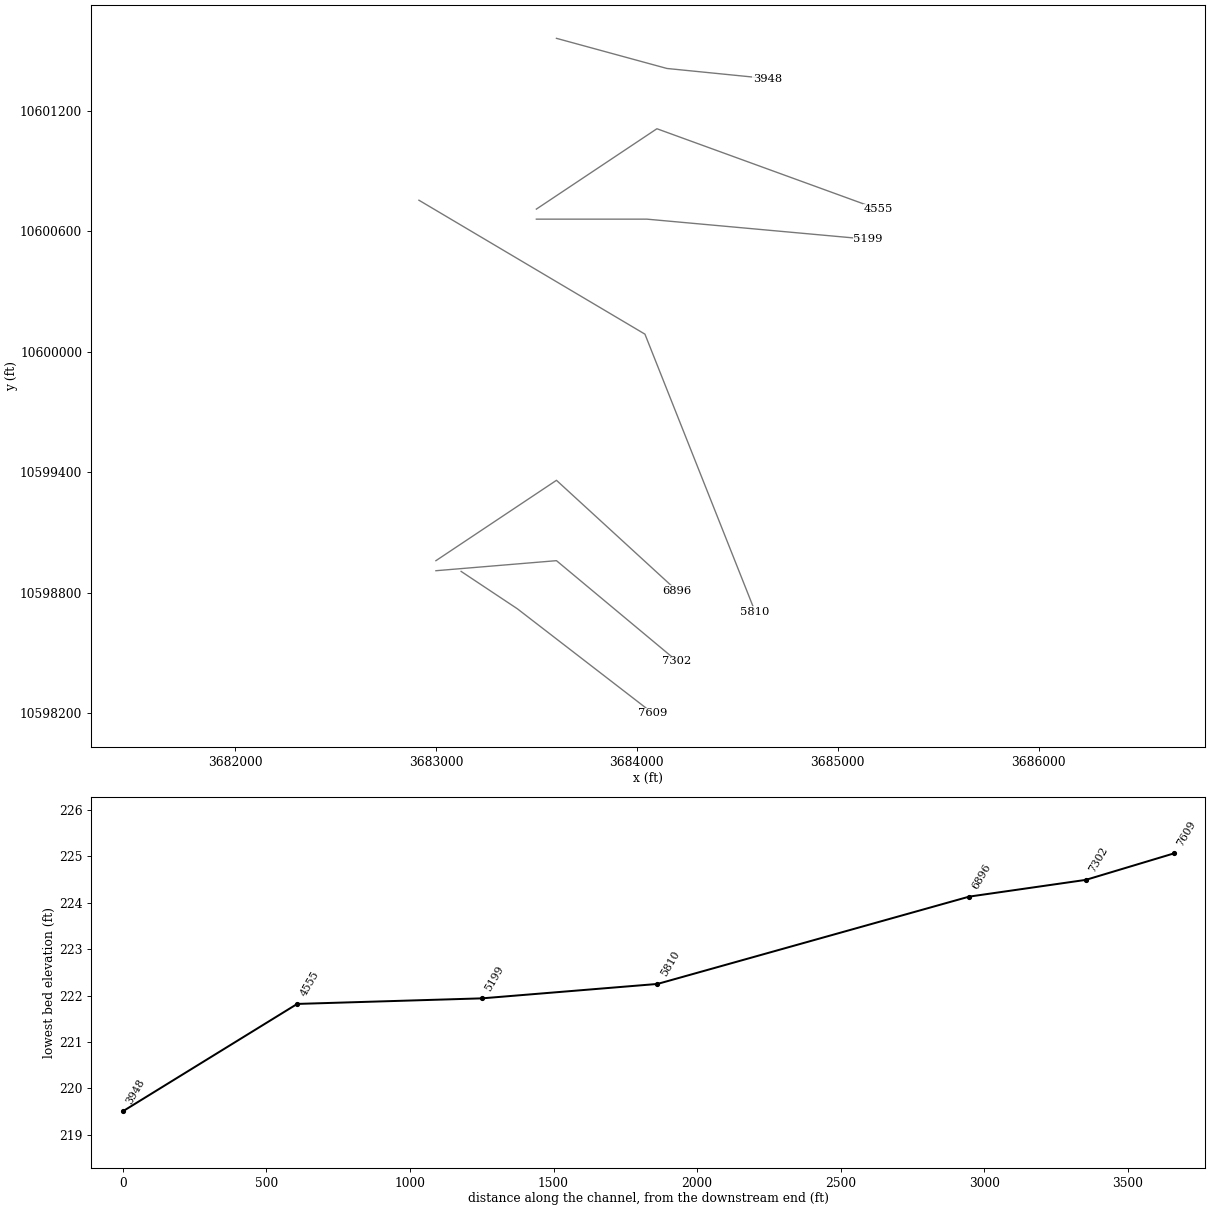
HEC-RAS study SALINE BRANCH.prj: SALINE BRANCH Base Level Engineering

--- SALINE BRANCH.g01 (geometry) --- (continued)

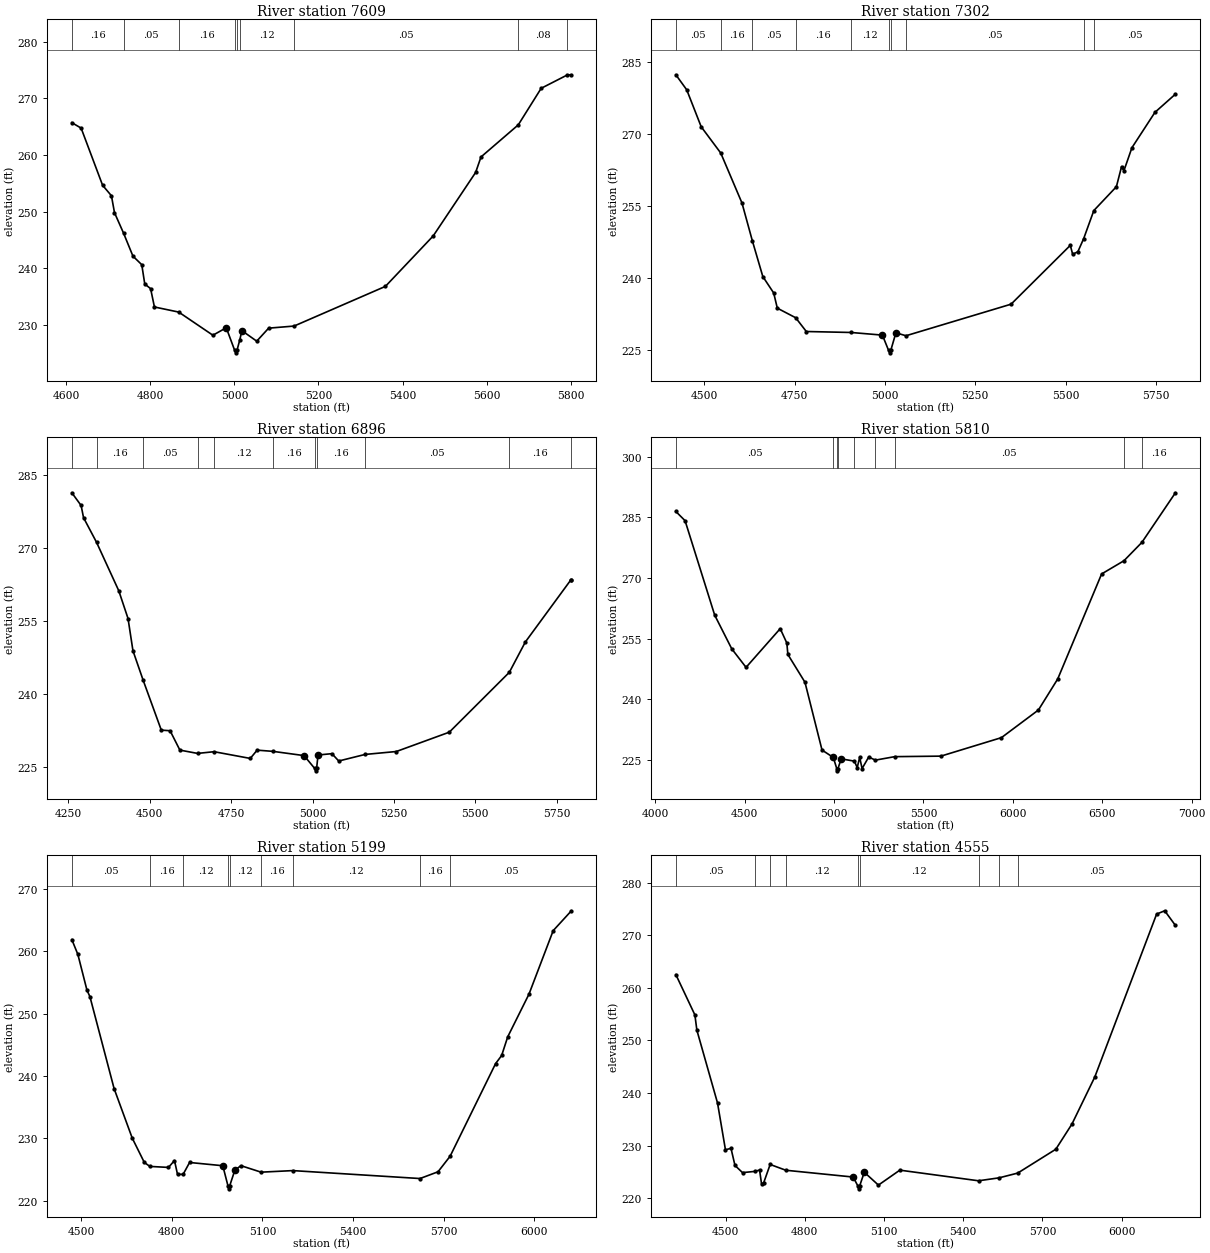
Type RM Length L Ch R = 1 ,7609    ,307,307,307
BEGIN DESCRIPTION:
Mapping XS 64666c6e
END DESCRIPTION:
XS GIS Cut Line= 3
      3683125.11     10598906.68      3683404.61     10598720.92
        3684080.     10598200.06
#Sta/Elev= 30
  4613.2  265.72  4635.3  264.76  4686.4  254.66  4707.4  252.81  4714.7  249.82
  4736.5  246.16  4758.6  242.14  4779.6  240.63  4786.7  237.22  4800.6   236.4
  4809.7  233.16  4867.5  232.26  4948.8  228.17  4980.6  229.49  5000.3  225.56
  5003.1  225.06  5006.3  225.56  5012.7  227.32  5017.8  228.98  5053.1  227.12
  5081.4  229.42  5141.9  229.79  5359.2   236.8  5472.9  245.71  5573.9  256.93
  5586.6  259.66  5675.3  265.33  5729.8  271.79  5791.7  274.14  5801.7  274.18
#Mann= 9 ,-1 , 0
  4613.2     .16       0  4736.5     .05       0  4867.5     .16       0
  5000.3     .07       0  5006.3     .16       0  5012.7     .12       0
  5141.9     .05       0  5675.3     .08       0  5791.7     .05       0
Bank Sta=4980.6,5017.8
XS Rating Curve= 0 ,0
Exp/Cntr=0.3,0.1

Type RM Length L Ch R = 1 ,7302    ,406,406,406
BEGIN DESCRIPTION:
SALINE BRANCH 6.0
END DESCRIPTION:
XS GIS Cut Line= 3
      3682999.64     10598910.19      3683599.61     10598960.19
      3684199.63     10598460.17
#Sta/Elev= 30
  4421.2  282.38  4451.3  279.25  4491.4  271.55  4545.5  266.09  4604.3  255.68
  4633.2  247.76    4662  240.37  4692.1  236.95  4702.1  233.79  4752.9   231.8
  4782.4  228.93  4906.1  228.73  4993.1  228.18  5010.2  224.99    5013  224.49
  5016.2  224.99  5030.4  228.66  5058.4  228.05  5349.3  234.62  5513.3  246.87
  5519.8  245.02  5534.2  245.54  5550.4  248.29  5578.4  254.11  5640.9  259.08
  5655.2  263.27  5661.7   262.4  5683.9   267.2  5747.6  274.56  5804.3  278.35
#Mann= 10 ,-1 , 0
  4421.2     .05       0  4545.5     .16       0  4633.2     .05       0
  4752.9     .16       0  4906.1     .12       0  5010.2     .07       0
  5016.2     .12       0  5058.4     .05       0  5550.4     .16       0
  5578.4     .05       0
Bank Sta=4993.1,5030.4
XS Rating Curve= 0 ,0
Exp/Cntr=0.3,0.1

Type RM Length L Ch R = 1 ,6896    ,1086,1086,1086
BEGIN DESCRIPTION:
SALINE BRANCH 5.0
END DESCRIPTION:
XS GIS Cut Line= 3
      3682999.63      10598960.2      3683599.61     10599360.19
      3684199.59     10598810.21
#Sta/Elev= 30
  4260.5  281.25    4289  278.64  4296.5  276.13  4336.4  271.08  4404.7  261.13
  4433.2  255.42  4448.3   248.8  4479.5  242.77  4535.4  232.49  4562.4  232.37
  4592.5  228.39  4646.8  227.71  4697.6  228.06  4808.8  226.68  4829.9  228.38
  4878.6  228.13  4974.1  227.26  5006.6  224.63  5009.4  224.13  5012.6  224.63
    5017  227.38  5059.6  227.66  5080.6  226.15  5161.7   227.5  5257.5   228.1
  5420.3  232.07  5604.8  244.37    5654   250.6  5793.6  263.33  5795.5  263.33
#Mann= 11 ,-1 , 0
  4260.5     .05       0  4336.4     .16       0  4479.5     .05       0
  4646.8     .16       0  4697.6     .12       0  4878.6     .16       0
  5006.6     .07       0  5012.6     .16       0  5161.7     .05       0
  5604.8     .16       0  5793.6     .05       0
Bank Sta=4974.1,5017
XS Rating Curve= 0 ,0
Exp/Cntr=0.3,0.1

Type RM Length L Ch R = 1 ,5810    ,611,611,611
BEGIN DESCRIPTION:
SALINE BRANCH 4.0
END DESCRIPTION:
XS GIS Cut Line= 3
      3682915.05     10600754.37      3684040.02     10600087.73
      3684588.62      10598705.8
#Sta/Elev= 30
  4114.7  286.44  4166.3  284.16    4332  260.78  4427.5  252.44  4507.4  247.86
  4698.5  257.44  4735.5  253.88  4741.3  251.05  4836.9  244.18  4932.4  227.39
  4995.6  225.56  5015.1  222.75  5017.9  222.25  5021.1  222.75  5039.6  225.22
  5113.2  224.65  5129.3  223.05  5142.9  225.59  5156.5  222.82  5193.6  225.67
  5230.9   224.9  5338.9  225.76  5597.3  225.89  5936.1  230.47  6142.7   237.3
  6250.7  244.98  6496.4  270.98  6621.4  274.25  6721.6  278.79  6909.2  291.07
#Mann= 9 ,-1 , 0
  4114.7     .05       0  4995.6     .16       0  5015.1     .07       0
  5021.1     .16       0  5113.2     .12       0  5230.9     .16       0
  5338.9     .05       0  6621.4     .08       0  6721.6     .16       0
Bank Sta=4995.6,5039.6
XS Rating Curve= 0 ,0
Exp/Cntr=0.3,0.1

Type RM Length L Ch R = 1 ,5199    ,644,644,644
BEGIN DESCRIPTION:
SALINE BRANCH 3.0
END DESCRIPTION:
XS GIS Cut Line= 3
      3683499.57     10600660.19      3684049.61     10600660.19
      3685149.64     10600560.19
#Sta/Elev= 30
  4468.8  261.85  4488.8  259.47  4518.8  253.77  4528.8   252.7  4608.8  237.99
  4668.8  230.07  4708.8  226.17  4727.2  225.53  4788.8  225.37  4808.8  226.47
  4818.8  224.26  4837.4  224.26  4858.8  226.16  4968.8  225.64  4985.8  222.44
  4988.6  221.94  4991.8  222.44  5008.8  224.94  5028.9  225.65  5095.6  224.61
  5200.7  224.86    5622  223.59  5681.6  224.67  5721.7  227.16  5872.3  241.99
  5892.4  243.29  5912.5  246.28  5982.8   253.1  6063.1  263.28  6123.4  266.46
#Mann= 9 ,-1 , 0
  4468.8     .05       0  4727.2     .16       0  4837.4     .12       0
  4985.8     .07       0  4991.8     .12       0  5095.6     .16       0
  5200.7     .12       0    5622     .16       0  5721.7     .05       0
Bank Sta=4968.8,5008.8
XS Rating Curve= 0 ,0
Exp/Cntr=0.3,0.1

Type RM Length L Ch R = 1 ,4555    ,607,607,607
BEGIN DESCRIPTION:
SALINE BRANCH 2.0
END DESCRIPTION:
XS GIS Cut Line= 3
       3683499.6     10600710.18      3684099.61     10601110.19
      3685199.61     10600710.19
#Sta/Elev= 30
  4311.9  262.51    4384  254.85  4391.5  251.95  4469.7  238.12  4499.7  229.24
  4520.7  229.51  4535.8  226.26  4564.3   224.9  4612.4  225.14  4628.9   225.4
  4636.4  222.76  4643.9  222.89    4669  226.45  4728.3  225.35  4983.4  224.06
  5001.5  222.32  5004.2  221.82  5007.5  222.32  5025.5  224.97  5078.9  222.53
    5160  225.37    5458  223.35  5535.9  223.91  5606.3  224.81  5750.6  229.34
  5811.8  234.13  5898.2  243.06  6132.3     274  6162.9  274.63  6203.5  271.85
#Mann= 9 ,-1 , 0
  4311.9     .05       0  4612.4     .16       0    4669     .05       0
  4728.3     .12       0  5001.5     .07       0  5007.5     .12       0
    5458     .05       0  5535.9     .16       0  5606.3     .05       0
Bank Sta=4983.4,5025.5
XS Rating Curve= 0 ,0
Exp/Cntr=0.3,0.1

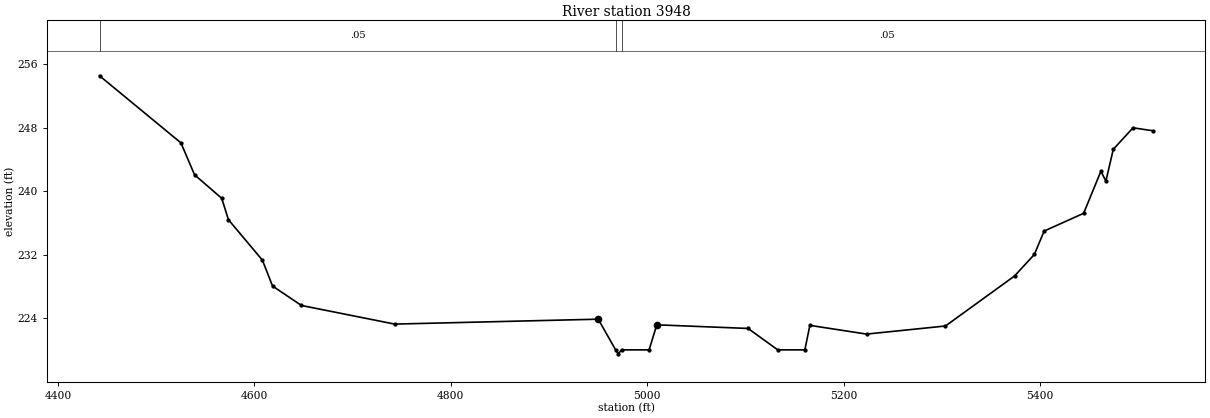
Type RM Length L Ch R = 1 ,3948    ,0,0,0
BEGIN DESCRIPTION:
SALINE BRANCH 1.0
END DESCRIPTION:
XS GIS Cut Line= 3
       3683599.6     10601560.19      3684149.61     10601410.19
      3684649.62     10601360.19
#Sta/Elev= 30
  4442.2  254.57  4525.1  246.11    4539  242.08  4566.6  239.13  4573.5  236.42
  4608.1  231.32  4618.4  228.06  4647.8  225.61  4742.8  223.26  4950.1  223.88
  4967.8  220.01  4970.6  219.51  4973.8  220.01  5001.9  220.01  5009.7  223.17
  5102.7  222.71  5132.9  220.01  5160.5  220.01  5165.6   223.1  5223.3     222
  5303.7  223.02  5374.1  229.33  5394.2  232.04  5404.2  234.99  5444.4  237.23
    5462  242.53  5467.1  241.29  5474.6   245.3  5494.7  248.01  5514.8  247.64
#Mann= 3 ,-1 , 0
  4442.2     .05       0  4967.8     .03       0  4973.8     .05       0
Bank Sta=4950.1,5009.7
XS Rating Curve= 0 ,0
Exp/Cntr=0.3,0.1

Chan Stop Cuts=-1
Use User Specified Reach Order=0
Composite Channel Slope=5