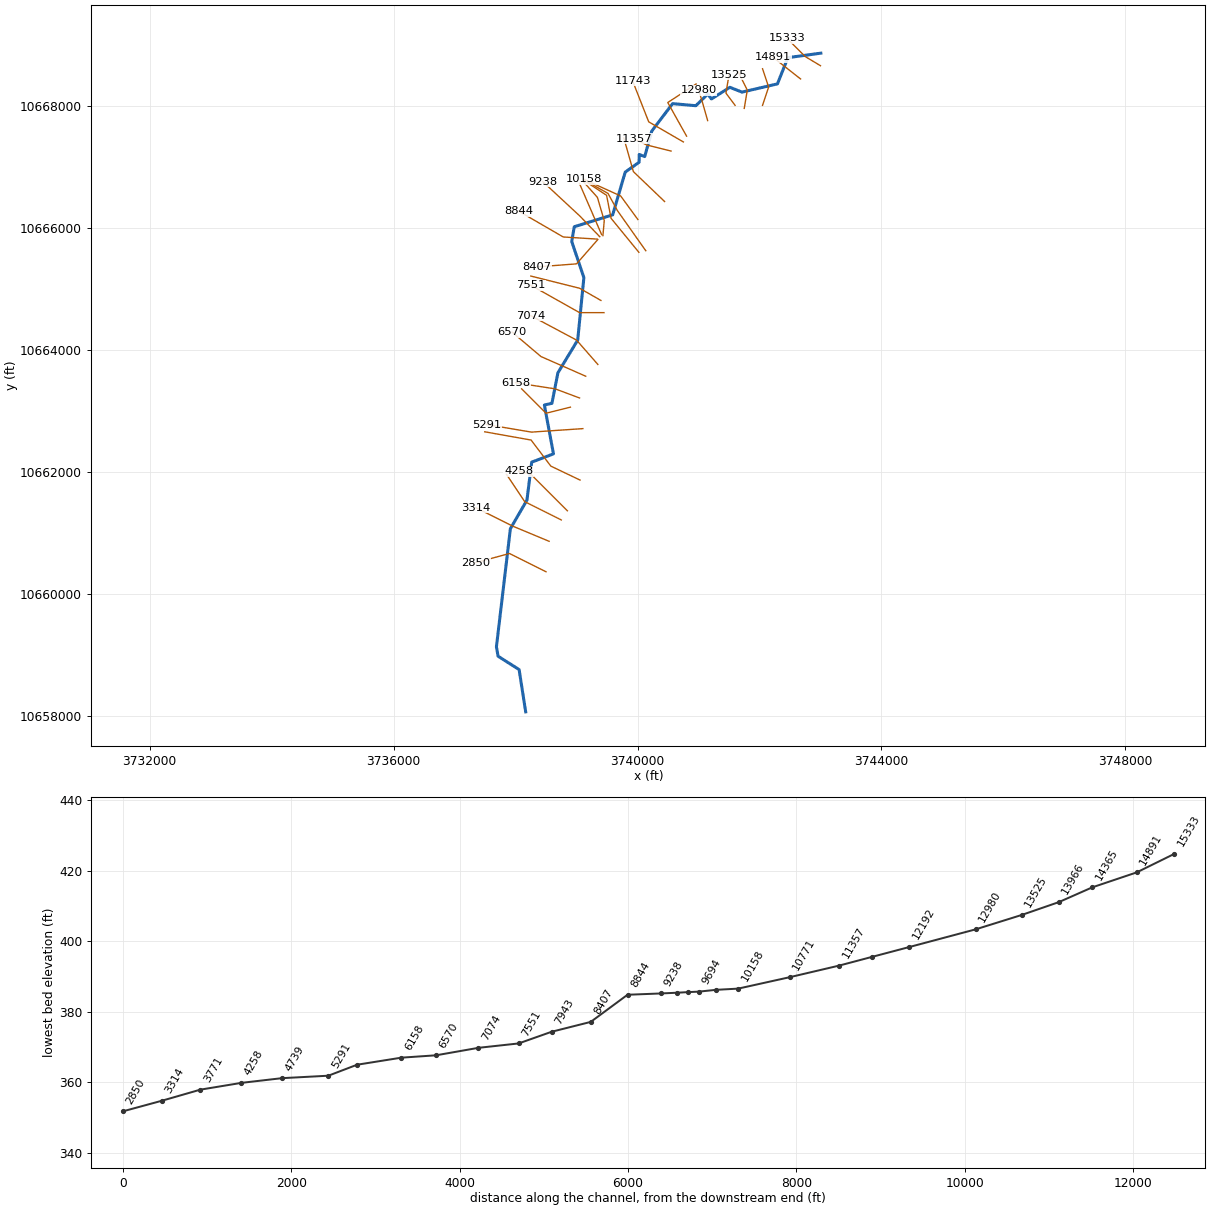
--- SIXMILE BRANCH.prj (project) ---

Proj Title=SIXMILE BRANCH Base Level Engineering
Current Plan=p01
Default Exp/Contr=0.3,0.1
English Units
Geom File=g01
Flow File=f01
Plan File=p01
Y Axis Title=Elevation
X Axis Title(PF)=Main Channel Distance
X Axis Title(XS)=Station
BEGIN DESCRIPTION:
SIXMILE BRANCH
END DESCRIPTION:
DSS Export Rating Curves= 0
DSS Export Rating Curve Sorted= 0
DSS Export Volume Flow Curves= 0
DXF OffsetX= 0
DXF OffsetY= 0
DXF ScaleX= 1
DXF ScaleY= 10

--- SIXMILE BRANCH.p01 (plan) ---

Plan Title=Multiple Run
Short Identifier=Multiple
Geom File=g01
Flow File=f01
Subcritical Flow
K Sum by GR= 0
Std Step Tol= 0.01
Critical Tol= 0.01
Num of Std Step Trials= 20
Max Error Tol= 0.3
Flow Tol Ratio= 0.001
Split Flow NTrial= 30
Split Flow Tol= 0.02
Split Flow Ratio= 0.02
Log Output Level= 0
Friction Slope Method= 1
Unsteady Friction Slope Method= 2
Unsteady Bridges Friction Slope Method= 1
Parabolic Critical Depth
Global Vel Dist=  1 , 1 , 1
Global Log Level= 0
CheckData=True
Encroach Param= -1, 0, 0, 0
BEGIN DESCRIPTION:
Multiple Run
END DESCRIPTION:

--- SIXMILE BRANCH.f01 (steady flow) ---

Flow Title=Multiple
Program Version=4.10
Number of Profiles= 7
Profile Names=10-year,25-year,50-year,1pct_min,100-year,1pct_plu,500-year
River Rch & RM=SIXMILE BRANCH,Reach-1         ,15333
     949    1338    1674    1538    2081    2814    3228
River Rch & RM=SIXMILE BRANCH,Reach-1         ,11743
    1422    2046    2594    2413    3264    4414    5191
River Rch & RM=SIXMILE BRANCH,Reach-1         ,10158
    1947    2831    3613    3381    4572    6183    7352
River Rch & RM=SIXMILE BRANCH,Reach-1         ,5291
    2223    3249    4160    3904    5280    7141    8543
River Rch & RM=SIXMILE BRANCH,Reach-1         ,4258
    2223    3249    4160    3904    5280    7141    8543
River Rch & RM=SIXMILE BRANCH,Reach-1         ,2850
    2237    3263    4172    3909    5287    7149    8526
Boundary for River Rch & Prof#=SIXMILE BRANCH,Reach-1         , 1
Up Type= 0
Dn Type= 3
Dn Slope=0.005
Boundary for River Rch & Prof#=SIXMILE BRANCH,Reach-1         , 2
Up Type= 0
Dn Type= 3
Dn Slope=0.005
Boundary for River Rch & Prof#=SIXMILE BRANCH,Reach-1         , 3
Up Type= 0
Dn Type= 3
Dn Slope=0.005
Boundary for River Rch & Prof#=SIXMILE BRANCH,Reach-1         , 4
Up Type= 0
Dn Type= 3
Dn Slope=0.005
Boundary for River Rch & Prof#=SIXMILE BRANCH,Reach-1         , 5
Up Type= 0
Dn Type= 3
Dn Slope=0.005
Boundary for River Rch & Prof#=SIXMILE BRANCH,Reach-1         , 6
Up Type= 0
Dn Type= 3
Dn Slope=0.005
Boundary for River Rch & Prof#=SIXMILE BRANCH,Reach-1         , 7
Up Type= 0
Dn Type= 3
Dn Slope=0.005
DSS Import GetInterval= 0
DSS Import GetPeak= 0
DSS Import FillOption= 0

--- SIXMILE BRANCH.g01 (geometry) ---

Geom Title=Existing Conditions
Program Version=4.10

River Reach=SIXMILE BRANCH  ,Reach-1
Reach XY= 30
      3743005.03     10668865.76      3742464.75       10668792.
      3742294.25       10668362.      3741712.75       10668227.
      3741513.75       10668306.       3741211.5       10668115.
       3741152.5       10668196.       3740955.5       10668004.
        3740575.       10668038.      3740233.25       10667588.
      3740117.25       10667170.       3740027.5       10667204.
      3740025.75       10667077.        3739798.       10666915.
        3739592.       10666214.      3738962.25       10666019.
        3738921.       10665776.        3739120.       10665185.
      3739018.75       10664160.        3738694.       10663623.
        3738596.       10663123.      3738472.25       10663095.
       3738621.5       10662294.      3738264.25       10662158.
      3738186.25       10661535.      3737914.75       10661066.
        3737686.       10659129.      3737713.25       10658975.
        3738058.       10658756.      3738165.75       10658063.

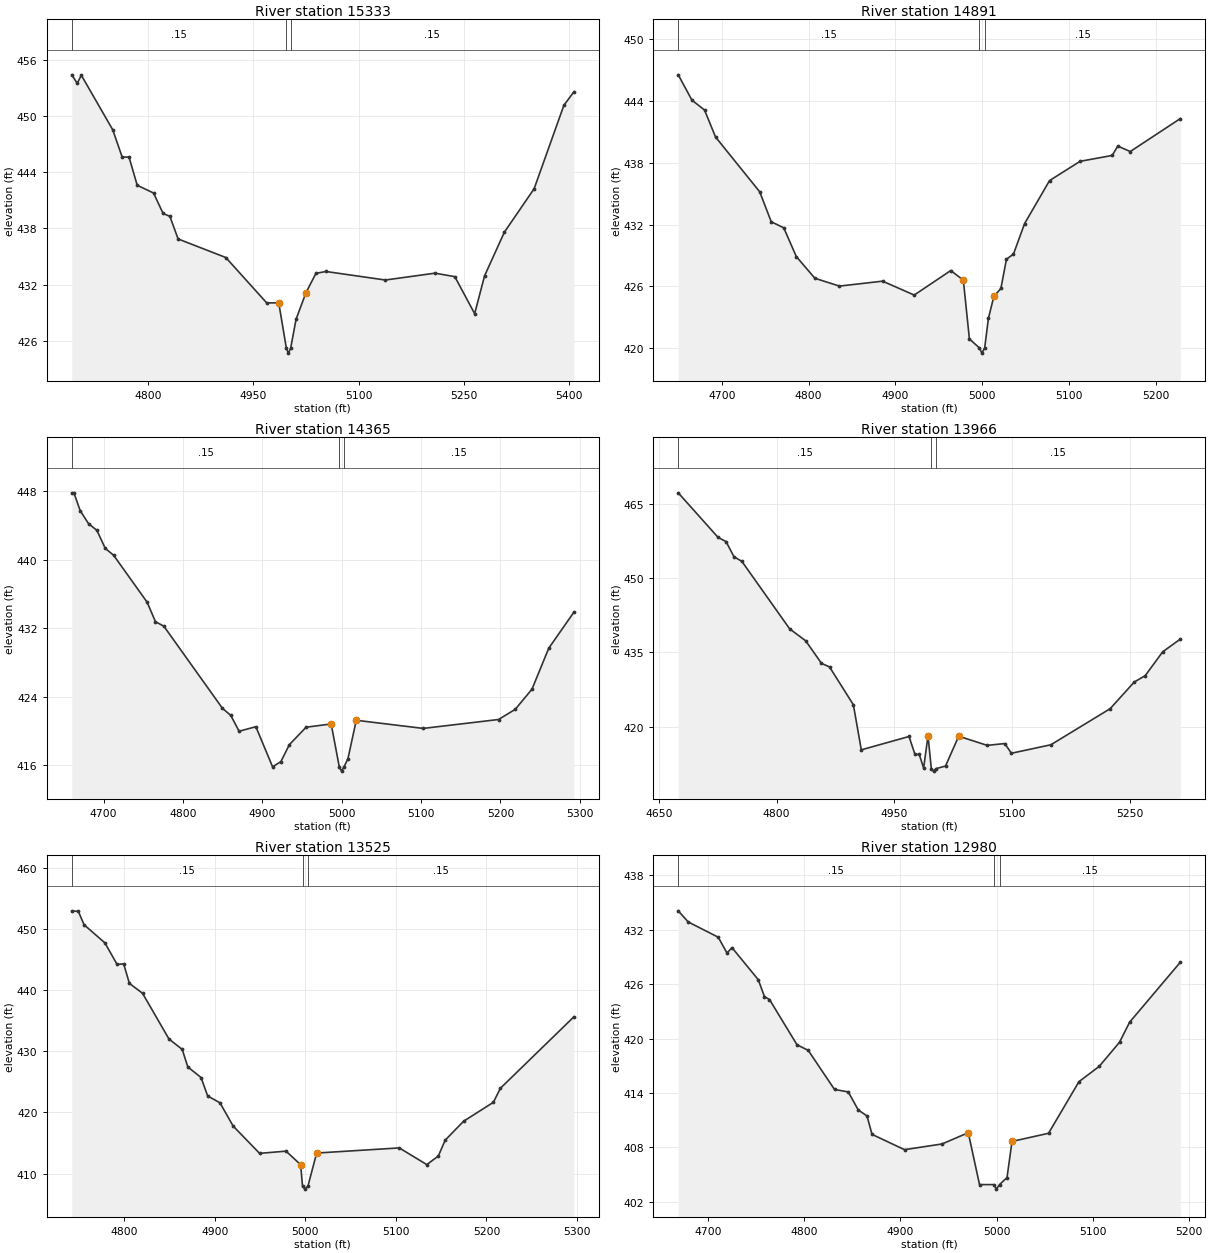
Type RM Length L Ch R = 1 ,15333   ,442,442,442
BEGIN DESCRIPTION:
SIXMILE BRANCH 32.0
END DESCRIPTION:
XS GIS Cut Line= 3
      3742999.59      10668660.2      3742749.61     10668810.19
       3742449.6      10669110.2
#Sta/Elev= 30
    4691  454.39  4698.8  453.48  4704.6  454.35  4749.3  448.54  4762.9  445.61
  4772.6  445.62  4784.3  442.61  4807.6  441.78  4821.2   439.6  4830.9  439.29
  4842.6  436.88  4910.6   434.9  4968.9  430.06  4986.1  430.06    4997   425.2
  4999.8   424.7    5003   425.2  5010.8  428.32  5024.9  431.15  5039.1  433.21
  5053.2  433.41  5138.1   432.5  5208.8  433.23  5237.1  432.86  5265.4  428.91
  5279.5  432.94  5307.8  437.61  5350.2  442.24  5392.6  451.14  5406.8  452.57
#Mann= 3 ,-1 , 0
    4691     .15       0    4997     .05       0    5003     .15       0
Bank Sta=4986.1,5024.9
XS Rating Curve= 0 ,0
Exp/Cntr=0.3,0.1

Type RM Length L Ch R = 1 ,14891   ,526,526,526
BEGIN DESCRIPTION:
SIXMILE BRANCH 31.0
END DESCRIPTION:
XS GIS Cut Line= 2
      3742673.41     10668442.52      3742218.48      10668800.2
#Sta/Elev= 30
  4649.8  446.54  4665.6  444.08  4680.1  443.12  4692.8   440.5  4743.7  435.18
    4757  432.27  4771.4  431.68  4785.9  428.89  4807.3  426.78  4835.6  426.02
  4885.3   426.5  4921.8  425.15  4963.9  427.53  4978.4   426.6  4985.4  420.89
    4997  420.01  4999.8  419.51    5003  420.01  5007.3  422.88  5013.6  425.02
  5021.7  425.79  5028.1  428.63  5036.2  429.13    5049  432.09  5077.8  436.27
    5113  438.14    5150  438.71  5156.4  439.62  5170.8  439.09  5228.5  442.29
#Mann= 3 ,-1 , 0
  4649.8     .15       0    4997     .05       0    5003     .15       0
Bank Sta=4978.4,5013.6
XS Rating Curve= 0 ,0
Exp/Cntr=0.3,0.1

Type RM Length L Ch R = 1 ,14365   ,399,399,399
BEGIN DESCRIPTION:
SIXMILE BRANCH 30.0
END DESCRIPTION:
XS GIS Cut Line= 3
       3742049.6     10668010.17      3742149.61     10668310.19
       3742049.6     10668610.21
#Sta/Elev= 30
    4660   447.8  4662.7   447.8  4670.6  445.72  4681.1   444.2  4691.6  443.42
  4702.2  441.31  4712.7  440.51  4754.9  435.03  4765.4  432.75    4776  432.22
  4849.8  422.63  4860.3   421.8  4870.8  419.95  4891.9  420.48    4913  415.79
  4923.5  416.41  4934.1  418.38  4955.2  420.42  4986.8   420.8    4997  415.79
  4999.8  415.29    5003  415.79  5007.9  416.74  5018.4  421.23  5102.7  420.28
  5197.6  421.32  5218.7  422.51  5239.8  424.87  5260.9  429.65  5292.5  433.85
#Mann= 3 ,-1 , 0
    4660     .15       0    4997     .05       0    5003     .15       0
Bank Sta=4986.8,5018.4
XS Rating Curve= 0 ,0
Exp/Cntr=0.3,0.1

Type RM Length L Ch R = 1 ,13966   ,441,441,441
BEGIN DESCRIPTION:
SIXMILE BRANCH 29.0
END DESCRIPTION:
XS GIS Cut Line= 3
       3741749.6     10667960.14      3741799.61     10668260.19
      3741649.61     10668560.19
#Sta/Elev= 30
  4674.6  467.17  4725.3   458.2  4735.5  457.34  4745.6   454.3  4755.7  453.35
  4816.6  439.75  4836.9  437.36  4857.1  432.81  4867.3  432.09  4897.7  424.47
  4907.8  415.38  4968.6  418.07  4976.2  414.45  4981.6  414.45  4987.2  411.73
  4992.8   418.2    4997  411.59  4999.8  411.09    5003  411.59  5015.1  412.12
  5031.9  418.13  5068.2  416.28  5090.6  416.65    5099  414.69  5149.3   416.4
  5224.8  423.67  5255.5  429.04  5269.5  430.33  5291.8  435.14  5314.2  437.69
#Mann= 3 ,-1 , 0
  4674.6     .15       0    4997     .05       0    5003     .15       0
Bank Sta=4992.8,5031.9
XS Rating Curve= 0 ,0
Exp/Cntr=0.3,0.1

Type RM Length L Ch R = 1 ,13525   ,545,545,545
BEGIN DESCRIPTION:
SIXMILE BRANCH 28.0
END DESCRIPTION:
XS GIS Cut Line= 3
      3741599.62     10668010.17      3741449.61     10668210.19
      3741499.62     10668510.23
#Sta/Elev= 30
  4742.3  452.96  4749.6  452.86  4755.9  450.68  4778.8  447.73  4792.3  444.21
  4799.6  444.28  4805.9   441.1  4820.4  439.48  4849.6     432  4864.2   430.3
  4870.4  427.43    4885   425.7  4892.3  422.69  4905.9  421.56  4920.4  417.77
  4949.6   413.3  4978.8  413.66  4994.9  411.45    4997  407.95  4999.8  407.45
    5003  407.95  5012.6  413.35  5103.8  414.19  5134.2  411.46  5146.9  412.86
  5154.5  415.46  5174.8  418.55  5207.7  421.65  5215.4  423.94  5296.5  435.62
#Mann= 3 ,-1 , 0
  4742.3     .15       0    4997     .05       0    5003     .15       0
Bank Sta=4994.9,5012.6
XS Rating Curve= 0 ,0
Exp/Cntr=0.3,0.1

Type RM Length L Ch R = 1 ,12980   ,788,788,788
BEGIN DESCRIPTION:
SIXMILE BRANCH 27.0
END DESCRIPTION:
XS GIS Cut Line= 3
       3741149.6      10667760.2      3741049.61     10668110.19
      3740999.61     10668260.18
#Sta/Elev= 30
  4668.9  434.08  4679.3  432.85  4710.5  431.17  4719.6  429.43  4724.8  430.02
  4752.1  426.49  4758.6  424.61  4763.8   424.3  4792.4  419.31  4804.1  418.69
  4831.4  414.38  4845.7  414.11  4856.1  412.12  4865.2  411.46  4870.4  409.43
  4904.2  407.74  4943.2  408.37  4970.5  409.61  4982.2  403.89    4997  403.89
  4999.8  403.39    5003  403.89  5010.8  404.67    5016  408.65    5054  409.55
  5085.6  415.24  5106.7  416.93  5127.8  419.59  5138.3   421.8    5191  428.41
#Mann= 3 ,-1 , 0
  4668.9     .15       0    4997     .05       0    5003     .15       0
Bank Sta=4970.5,5016
XS Rating Curve= 0 ,0
Exp/Cntr=0.3,0.1

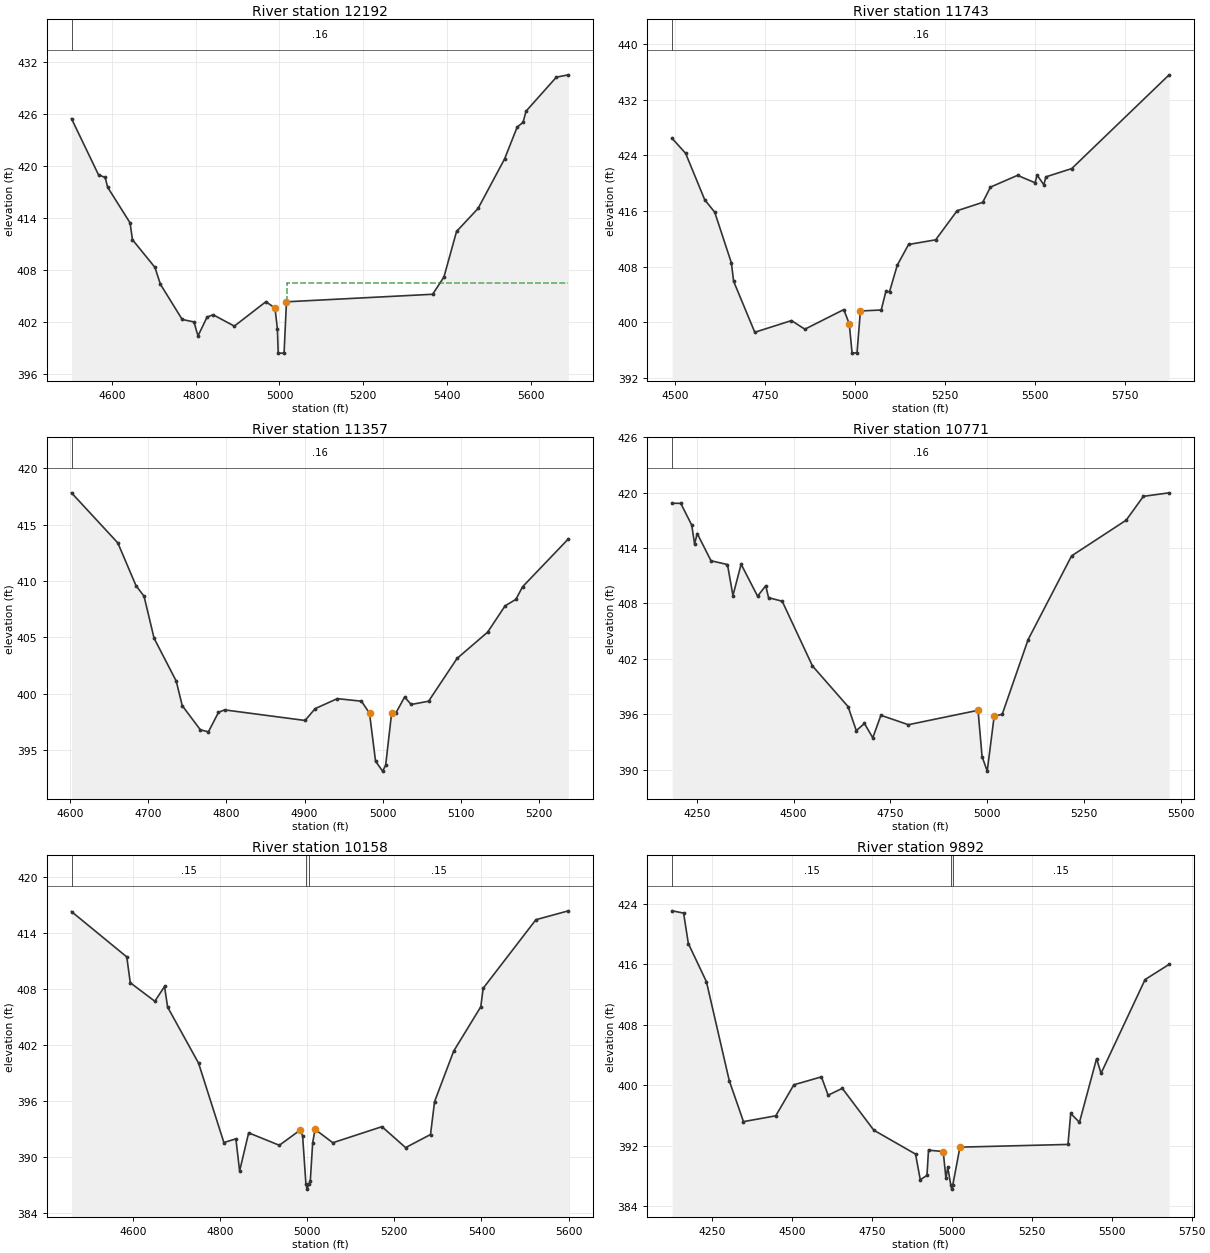
Type RM Length L Ch R = 1 ,12192   ,449,449,449
BEGIN DESCRIPTION:
SIXMILE BRANCH 26.0
END DESCRIPTION:
XS GIS Cut Line= 3
      3740803.84     10667504.91      3740495.69     10668056.12
      3740960.13     10668359.96
#Sta/Elev= 30
  4503.4  425.47  4567.9  418.98  4583.9  418.67  4589.6  417.55  4643.2  413.43
    4649  411.48  4702.6  408.29  4715.7  406.34  4767.7  402.27  4795.9  401.98
  4805.4  400.36  4827.1  402.55  4841.7  402.81  4892.2   401.5  4967.6  404.32
  4989.3  403.59    4995  401.21    4997  398.38    5011  398.38  5016.7  404.31
  5365.7  405.18  5392.7  407.17  5422.9  412.44  5474.2  415.09  5537.5  420.81
  5567.7   424.5  5581.7  425.04  5588.8  426.33  5661.2  430.26  5689.9  430.53
#Mann= 1 ,-1 , 0
  4503.4     .16       0
#XS Ineff= 2 , 0
                         5018.86          406.51
Permanent Ineff=
       F       F
Bank Sta=4989.3,5016.7
XS Rating Curve= 0 ,0
Exp/Cntr=0.3,0.1

Type RM Length L Ch R = 1 ,11743   ,386,386,386
BEGIN DESCRIPTION:
SIXMILE BRANCH 25.0
END DESCRIPTION:
XS GIS Cut Line= 3
      3740751.77     10667409.41      3740183.19     10667739.28
      3739918.43     10668412.02
#Sta/Elev= 30
  4492.4  426.41  4529.6  424.27  4582.6   417.6  4610.5   415.8  4656.7  408.52
  4662.9  405.88  4721.7  398.55  4823.6  400.23  4860.8  398.99  4968.9  401.81
  4984.2  399.76    4992  395.55  5005.7  395.59  5015.1  401.61  5072.9  401.75
    5086  404.44    5096  404.38  5117.5  408.19  5148.9  411.17  5224.2  411.84
  5283.7  416.02  5354.9  417.23  5376.4  419.42  5451.6  421.11  5500.4  420.04
  5505.8  421.16  5524.8  419.74  5530.2  420.89  5602.1  422.08  5872.7  435.56
#Mann= 1 ,-1 , 0
  4492.4     .16       0
Bank Sta=4984.2,5015.1
XS Rating Curve= 0 ,0
Exp/Cntr=0.3,0.1

Type RM Length L Ch R = 1 ,11357   ,586,586,586
BEGIN DESCRIPTION:
SIXMILE BRANCH 24.0
END DESCRIPTION:
XS GIS Cut Line= 3
      3740549.61     10667260.19      3740149.61     10667360.19
      3739949.63     10667460.18
#Sta/Elev= 30
  4601.7  417.83    4661  413.38  4684.2  409.59  4694.5  408.65  4707.4  404.91
  4735.7  401.11  4743.4  398.93  4766.6  396.78  4776.9   396.6  4789.8  398.33
  4797.6  398.55  4900.6  397.61  4913.5  398.66  4941.9  399.55  4972.8  399.32
  4983.1  398.25  4990.8     394  4999.8  393.11  5003.7  393.61  5011.4  398.27
  5016.8  398.27    5028  399.69  5036.4  399.03  5058.7  399.32  5095.1  403.12
  5134.2  405.45  5156.6  407.79  5170.5  408.37  5178.9  409.48  5237.6  413.74
#Mann= 1 ,-1 , 0
  4601.7     .16       0
Bank Sta=4983.1,5011.4
XS Rating Curve= 0 ,0
Exp/Cntr=0.3,0.1

Type RM Length L Ch R = 1 ,10771   ,613,613,613
BEGIN DESCRIPTION:
SIXMILE BRANCH 23.0
END DESCRIPTION:
XS GIS Cut Line= 3
      3740443.58     10666432.87      3739931.45     10666923.31
       3739775.2      10667474.5
#Sta/Elev= 30
  4187.1  418.85  4209.1  418.84  4237.4  416.48  4244.7  414.45  4251.6  415.57
  4287.1  412.62  4329.6  412.21  4343.7  408.85  4364.8  412.25  4407.3  408.78
  4428.3  409.92  4435.6  408.62  4470.8  408.24  4548.8  401.23  4640.6  396.83
    4662  394.22  4683.1  394.99  4704.5  393.44  4725.5  395.88  4796.3  394.86
  4976.1  396.42  4986.5  391.41  4999.8  389.83  5017.7  395.78  5038.5  395.99
  5105.3  404.08  5217.5  413.15  5358.4  417.02  5402.7   419.6  5469.1  419.98
#Mann= 1 ,-1 , 0
  4187.1     .16       0
Bank Sta=4976.1,5017.7
XS Rating Curve= 0 ,0
Exp/Cntr=0.3,0.1

Type RM Length L Ch R = 1 ,10158   ,266,266,266
BEGIN DESCRIPTION:
SIXMILE BRANCH 22.0
END DESCRIPTION:
XS GIS Cut Line= 3
      3740005.23     10666137.72      3739723.12       10666524.
      3739119.82     10666797.44
#Sta/Elev= 30
  4458.8  416.27  4585.7  411.42  4593.7  408.66  4650.1  406.68  4672.4  408.26
  4679.4  406.06  4750.5  400.06  4808.6  391.57  4836.2  391.97  4844.7  388.53
  4865.5  392.61  4935.9  391.28  4983.9  392.91  4989.4  392.28    4997  387.09
  4999.8  386.59    5003  387.09  5006.9  387.41  5012.5  391.57    5018  392.98
  5058.7  391.55  5171.5  393.27  5225.8  391.03    5283  392.43  5292.3  395.95
  5336.2  401.35  5398.4  406.09  5403.9  408.07  5524.9   415.4  5599.5  416.35
#Mann= 3 ,-1 , 0
  4458.8     .15       0    4997     .05       0    5003     .15       0
Bank Sta=4983.9,5018
XS Rating Curve= 0 ,0
Exp/Cntr=0.3,0.1

Type RM Length L Ch R = 1 ,9892    ,198,198,198
BEGIN DESCRIPTION:
Mapping XS 4c60f821
END DESCRIPTION:
XS GIS Cut Line= 4
      3740134.69      10665625.6      3739670.31     10666283.12
      3739516.23     10666565.23      3739144.23     10666775.02
#Sta/Elev= 30
    4126   423.1  4161.5   422.8  4176.3  418.77  4232.9  413.71  4304.3   400.6
  4348.7  395.18  4449.6  395.95  4506.3  400.06  4592.4  401.11  4613.4  398.68
  4657.7  399.59  4756.1  394.05  4886.7  390.88  4901.5  387.48  4922.4  388.06
  4927.2   391.4  4973.2  391.22  4981.7  387.66  4987.4  389.15    4997  386.74
  4999.8  386.24    5003  386.74  5025.4   391.8  5363.3  392.16  5371.8  396.26
  5399.2  395.09  5452.7  403.52  5466.7  401.58  5604.4     414  5679.5  416.01
#Mann= 3 ,-1 , 0
    4126     .15       0    4997     .05       0    5003     .15       0
Bank Sta=4973.2,5025.4
XS Rating Curve= 0 ,0
Exp/Cntr=0.3,0.1

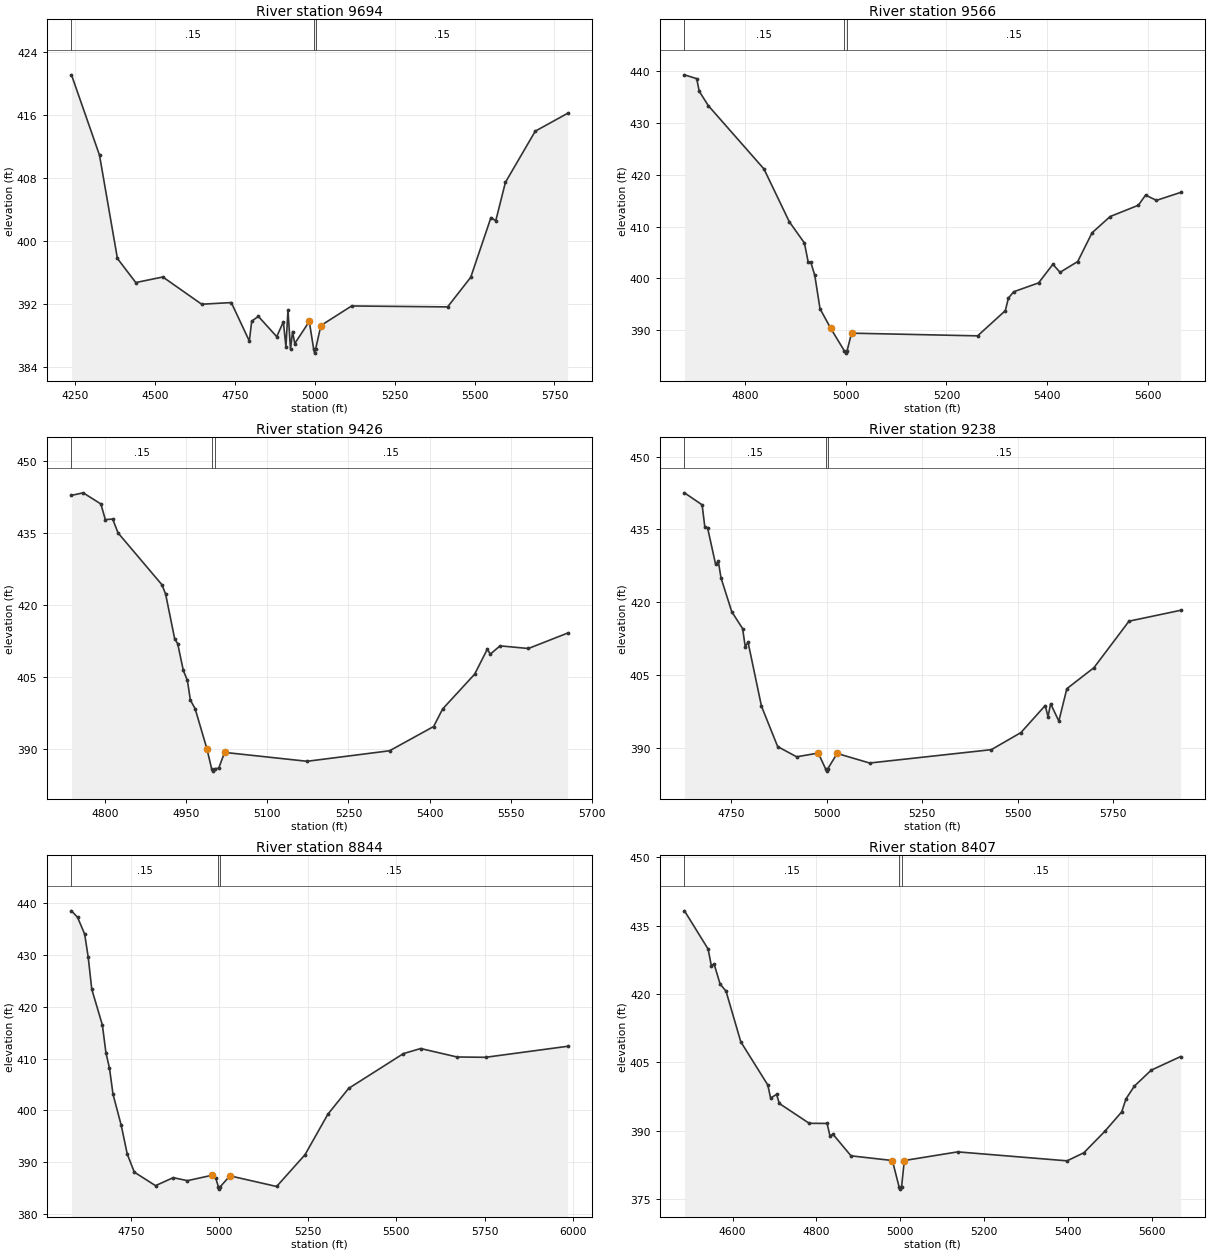
Type RM Length L Ch R = 1 ,9694    ,128,128,128
BEGIN DESCRIPTION:
Mapping XS c317b770
END DESCRIPTION:
XS GIS Cut Line= 4
       3740021.9     10665599.49      3739566.14     10666157.25
      3739492.36     10666534.85      3739119.13     10666780.06
#Sta/Elev= 30
  4239.5  421.08  4327.2  410.87  4383.2  397.76  4440.6   394.7  4525.3  395.41
  4646.7  391.95  4739.3  392.16  4795.7  387.28  4803.2   389.8    4824  390.41
  4881.4  387.83  4902.2  389.72  4910.1  386.56  4916.6  391.19  4924.5  386.24
  4930.9  388.48  4937.8  386.96  4983.2  389.76    4997  386.24  4999.8  385.74
    5003  386.24  5019.4  389.24  5115.6  391.73  5415.8  391.61  5488.1  395.37
  5551.3  402.95  5566.4  402.55  5596.6  407.43    5690  413.93  5791.1  416.19
#Mann= 3 ,-1 , 0
  4239.5     .15       0    4997     .05       0    5003     .15       0
Bank Sta=4983.2,5019.4
XS Rating Curve= 0 ,0
Exp/Cntr=0.3,0.1

Type RM Length L Ch R = 1 ,9566    ,140,140,140
BEGIN DESCRIPTION:
SIXMILE BRANCH 21.0
END DESCRIPTION:
XS GIS Cut Line= 4
      3739432.32     10665872.98      3739454.02     10666120.35
      3739341.17      10666502.3      3739115.47     10666754.04
#Sta/Elev= 30
  4680.1  439.25  4704.4  438.51  4709.4  436.08  4727.5   433.3  4837.9   421.1
  4888.1  410.94  4918.2  406.83  4925.8  403.08  4930.9  403.08  4938.7  400.61
  4949.1  394.17    4970  390.44    4997   386.1  4999.8   385.6    5003   386.1
  5011.7  389.45  5261.9  388.93  5316.9  393.79    5323  396.21  5333.5  397.43
  5382.9  399.14  5411.3  402.73  5425.5  401.18  5460.6  403.26    5489  408.79
  5524.9  411.93    5581  414.11  5595.2  416.06  5616.9  415.05  5664.8  416.58
#Mann= 3 ,-1 , 0
  4680.1     .15       0    4997     .05       0    5003     .15       0
Bank Sta=4970,5011.7
XS Rating Curve= 0 ,0
Exp/Cntr=0.3,0.1

Type RM Length L Ch R = 1 ,9426    ,188,188,188
BEGIN DESCRIPTION:
Mapping XS 5031f967
END DESCRIPTION:
XS GIS Cut Line= 2
      3739410.62      10665890.3      3739046.02     10666732.35
#Sta/Elev= 30
  4737.8  442.85  4759.5  443.38  4792.2  441.06  4800.4   437.8    4814  437.92
  4823.9  435.04  4905.3  424.21    4912  422.26  4928.7  412.97  4934.2  411.97
  4944.7  406.38  4952.2  404.31  4957.7  400.21  4966.5  398.42  4988.3  390.07
    4997  385.92  4999.8  385.42    5003  385.92  5010.1  386.03    5021  389.32
  5173.6  387.47  5326.1  389.66  5407.6  394.71  5424.2  398.36  5483.5  405.62
  5506.9  410.82  5512.4  409.78  5530.4  411.51  5582.8  410.96  5655.4  414.17
#Mann= 3 ,-1 , 0
  4737.8     .15       0    4997     .05       0    5003     .15       0
Bank Sta=4988.3,5021
XS Rating Curve= 0 ,0
Exp/Cntr=0.3,0.1

Type RM Length L Ch R = 1 ,9238    ,394,394,394
BEGIN DESCRIPTION:
SIXMILE BRANCH 20.0
END DESCRIPTION:
XS GIS Cut Line= 3
      3739380.23      10665855.6      3739054.71     10666194.14
      3738447.05      10666758.4
#Sta/Elev= 30
  4627.7  442.53  4673.9  440.06  4680.9  435.57  4688.1  435.36  4709.2  427.82
  4716.4   428.4  4723.3  425.03  4751.6  418.03  4779.9  414.58  4786.8  410.84
  4794.1  411.79  4829.3  398.59  4871.7  390.27  4921.4  388.17    4978  388.94
    4997  385.72  4999.8  385.22    5003  385.72  5027.4  388.86  5112.4  386.89
    5431  389.64  5508.6  393.16  5572.1  398.73  5579.5  396.43  5586.3   399.1
  5607.8  395.53  5628.8   402.2  5699.7  406.52  5791.5   416.1  5926.6  418.34
#Mann= 3 ,-1 , 0
  4627.7     .15       0    4997     .05       0    5003     .15       0
Bank Sta=4978,5027.4
XS Rating Curve= 0 ,0
Exp/Cntr=0.3,0.1

Type RM Length L Ch R = 1 ,8844    ,437,437,437
BEGIN DESCRIPTION:
SIXMILE BRANCH 19.0
END DESCRIPTION:
XS GIS Cut Line= 3
      3739336.87     10665816.53      3738781.28     10665851.26
      3738048.97     10666275.91
#Sta/Elev= 30
  4581.7  438.47    4599  437.21    4619  433.99  4629.1  429.51  4639.1  423.37
  4669.1  416.47  4679.2  411.11  4689.2  408.15  4699.2  403.13  4722.4  397.15
  4739.3  391.65  4759.3  388.13  4819.4  385.52  4869.5  387.06  4909.6  386.48
  4979.7  387.53  4989.8  386.96    4997  385.35  4999.8  384.85    5003  385.35
  5029.8  387.41  5161.9  385.36  5242.2  391.48  5306.8  399.28  5365.6  404.26
  5520.5  410.96  5569.3  411.94  5672.1  410.31    5753  410.25  5984.9  412.37
#Mann= 3 ,-1 , 0
  4581.7     .15       0    4997     .05       0    5003     .15       0
Bank Sta=4979.7,5029.8
XS Rating Curve= 0 ,0
Exp/Cntr=0.3,0.1

Type RM Length L Ch R = 1 ,8407    ,464,464,464
BEGIN DESCRIPTION:
SIXMILE BRANCH 18.0
END DESCRIPTION:
XS GIS Cut Line= 3
      3739349.58     10665810.16      3738999.61     10665410.19
       3738349.6     10665360.19
#Sta/Elev= 30
  4485.1  438.25  4541.5  429.86  4549.1  426.24  4555.8  426.58    4570   422.2
  4584.2  420.62  4619.4  409.51  4683.9  400.01  4690.5  397.16  4704.8  397.95
  4711.4  395.96  4782.6  391.61  4825.3  391.58    4832   388.9  4839.6  389.18
  4882.3  384.47    4981  383.44    4997  377.66  4999.8  377.16    5003  377.66
  5009.4  383.44  5136.9  385.34  5397.7  383.37  5437.8  385.15    5488  389.88
  5528.1  394.13  5538.1  396.96  5558.2  399.77  5598.3  403.27  5668.5  406.26
#Mann= 3 ,-1 , 0
  4485.1     .15       0    4997     .05       0    5003     .15       0
Bank Sta=4981,5009.4
XS Rating Curve= 0 ,0
Exp/Cntr=0.3,0.1

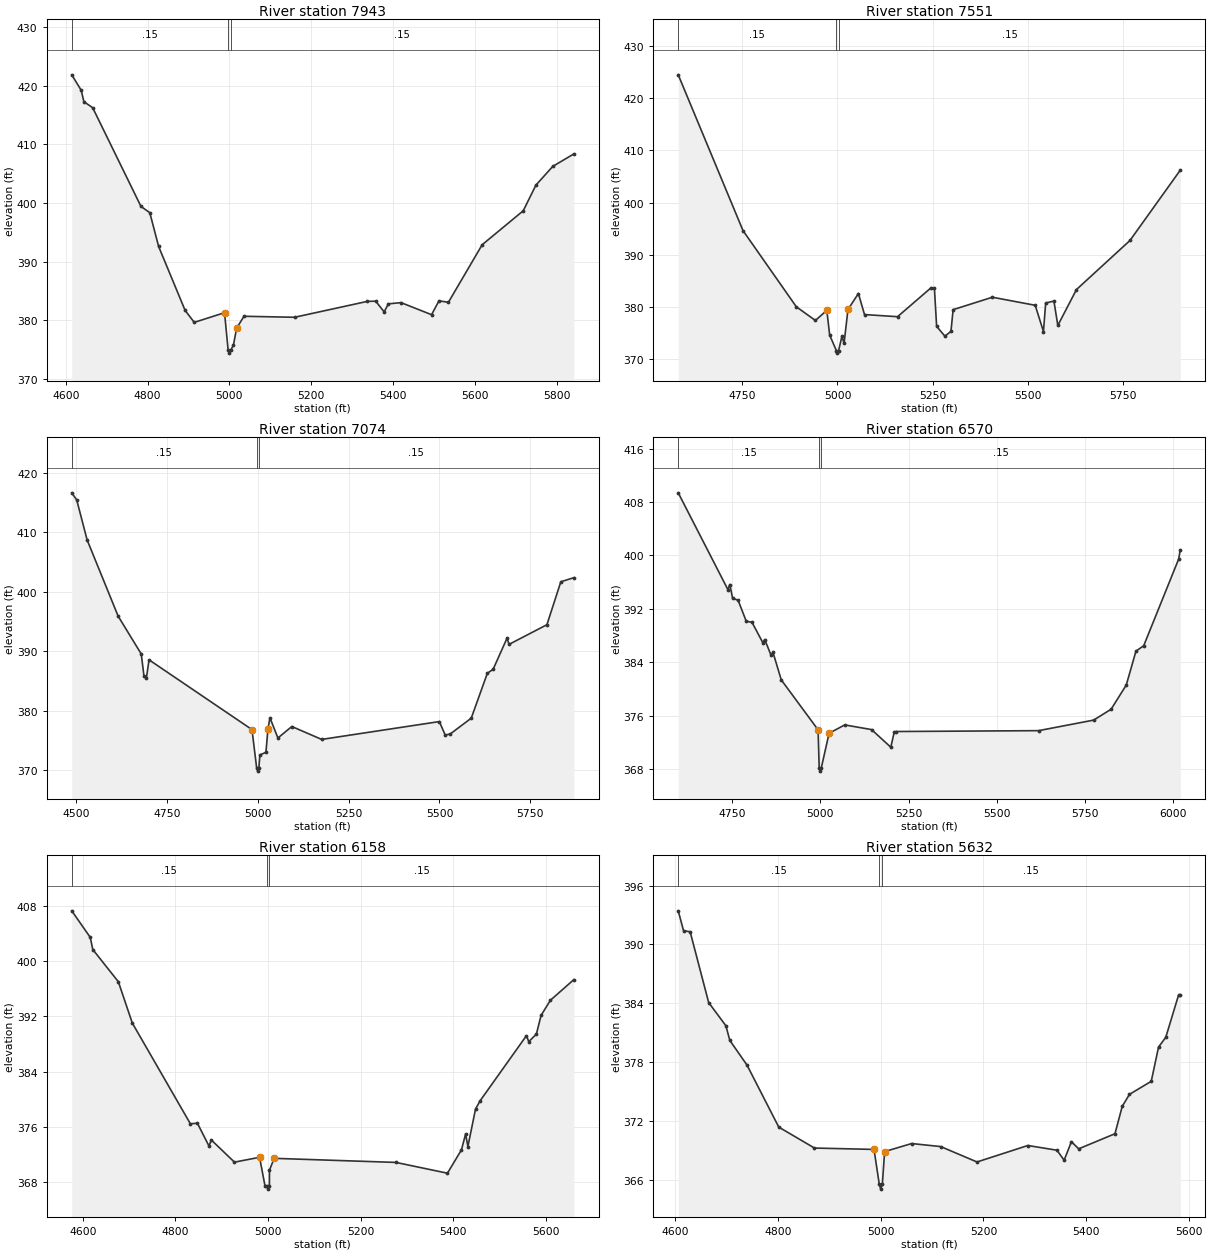
Type RM Length L Ch R = 1 ,7943    ,392,392,392
BEGIN DESCRIPTION:
SIXMILE BRANCH 17.0
END DESCRIPTION:
XS GIS Cut Line= 3
      3739399.65     10664810.17      3739049.61     10665010.19
      3738249.59     10665210.19
#Sta/Elev= 30
  4614.6  421.87  4637.7  419.23  4644.2  417.29  4665.8  416.25  4783.8  399.41
  4805.4  398.34    4827  392.57  4891.8  381.66  4914.1  379.62  4988.2  381.27
    4997  374.87  4999.8  374.37    5003  374.87  5009.8  375.69  5017.8  378.64
  5035.8  380.66  5159.5  380.49  5337.3   383.2  5357.9  383.24  5378.5  381.41
  5388.8  382.78  5419.8  382.99  5494.5  380.93  5512.5  383.29  5535.7  383.05
  5618.2  392.87  5718.7  398.67  5749.6  403.04  5790.8  406.24  5842.4  408.37
#Mann= 3 ,-1 , 0
  4614.6     .15       0    4997     .05       0    5003     .15       0
Bank Sta=4988.2,5017.8
XS Rating Curve= 0 ,0
Exp/Cntr=0.3,0.1

Type RM Length L Ch R = 1 ,7551    ,477,477,477
BEGIN DESCRIPTION:
SIXMILE BRANCH 16.0
END DESCRIPTION:
XS GIS Cut Line= 3
      3739449.56     10664610.19      3739049.61     10664610.19
      3738249.63     10665060.17
#Sta/Elev= 30
    4582  424.53    4752   394.6    4892  379.96    4942  377.34    4972  379.28
  4979.5  374.52    4997  371.56  4999.8  371.06    5003  371.56  5011.6   374.3
  5017.3  372.95  5027.5  379.45  5054.9  382.51  5070.9  378.47  5157.6  378.06
  5245.8  383.63  5254.4  383.53  5260.2  376.21  5281.9  374.32  5297.8  375.24
  5303.5  379.41  5406.5   381.8    5519  380.25  5540.6   375.2  5546.4  380.69
  5568.1  381.06  5578.3  376.38  5627.3  383.28  5767.6   392.7  5899.8  406.22
#Mann= 3 ,-1 , 0
    4582     .15       0    4997     .05       0    5003     .15       0
Bank Sta=4972,5027.5
XS Rating Curve= 0 ,0
Exp/Cntr=0.3,0.1

Type RM Length L Ch R = 1 ,7074    ,504,504,504
BEGIN DESCRIPTION:
SIXMILE BRANCH 15.0
END DESCRIPTION:
XS GIS Cut Line= 3
      3739349.58     10663760.23      3738999.61     10664160.19
      3738249.57     10664560.21
#Sta/Elev= 30
  4488.2   416.6  4501.9  415.39  4530.4  408.69  4615.8  395.87  4679.4  389.51
    4687  385.75  4693.6  385.48  4700.8  388.53  4984.1   376.8    4997  370.32
  4999.8  369.82    5003  370.32  5005.9  372.55  5022.5  372.98  5027.8  376.82
  5033.5  378.79  5055.4  375.39  5093.7  377.32  5175.8  375.15  5499.6  378.15
  5515.8  375.88  5529.7  376.07  5587.4  378.72  5631.7  386.27  5647.6  386.94
  5685.8  392.16  5691.5  391.13  5795.6  394.43  5833.9  401.65  5869.7  402.34
#Mann= 3 ,-1 , 0
  4488.2     .15       0    4997     .05       0    5003     .15       0
Bank Sta=4984.1,5027.8
XS Rating Curve= 0 ,0
Exp/Cntr=0.3,0.1

Type RM Length L Ch R = 1 ,6570    ,412,412,412
BEGIN DESCRIPTION:
SIXMILE BRANCH 14.0
END DESCRIPTION:
XS GIS Cut Line= 3
      3739150.58     10663567.42      3738416.23     10663890.32
      3737943.47     10664290.35
#Sta/Elev= 30
  4597.9  409.37  4738.5  394.88  4743.9  395.64  4751.9  393.57  4767.3   393.3
  4790.6  390.12  4806.5  390.01  4837.3  386.94  4842.8   387.4  4860.7  385.05
  4866.1   385.5  4889.5  381.37  4993.8  373.89    4997   368.2  4999.8   367.7
    5003   368.2    5025  373.37  5069.3  374.62  5145.2  373.92  5199.8  371.28
  5209.3  373.52  5214.8  373.63  5618.1  373.76  5774.1  375.34  5823.5  376.97
  5866.4  380.59  5893.8  385.66  5915.8  386.48  6014.7  399.45  6019.4  400.84
#Mann= 3 ,-1 , 0
  4597.9     .15       0    4997     .05       0    5003     .15       0
Bank Sta=4993.8,5025
XS Rating Curve= 0 ,0
Exp/Cntr=0.3,0.1

Type RM Length L Ch R = 1 ,6158    ,526,526,526
BEGIN DESCRIPTION:
SIXMILE BRANCH 13.0
END DESCRIPTION:
XS GIS Cut Line= 3
       3739049.6     10663210.19      3738649.61     10663360.19
      3737999.64     10663460.18
#Sta/Elev= 30
    4576  407.25    4616  403.41  4621.4  401.66  4676.6  397.01  4706.8  391.03
  4832.3  376.47  4847.4  376.56  4872.4  373.27  4877.7  374.12  4927.5  370.93
  4981.8  371.63  4993.4  367.53    4997  367.53  4999.8  367.03    5003  367.53
  5003.2  369.78  5013.3  371.48  5276.4  370.89  5387.7  369.33    5418  372.71
  5426.9  374.99  5431.9  373.19  5448.4  378.61  5458.5  379.82  5558.4  389.21
  5563.4  388.34  5579.9  389.44    5590  392.14  5610.2  394.33  5660.8  397.31
#Mann= 3 ,-1 , 0
    4576     .15       0    4997     .05       0    5003     .15       0
Bank Sta=4981.8,5013.3
XS Rating Curve= 0 ,0
Exp/Cntr=0.3,0.1

Type RM Length L Ch R = 1 ,5632    ,341,341,341
BEGIN DESCRIPTION:
SIXMILE BRANCH 12.0
END DESCRIPTION:
XS GIS Cut Line= 3
      3738899.61     10663060.19      3738499.61     10662960.19
      3738099.61     10663360.19
#Sta/Elev= 30
  4605.4  393.42  4615.7   391.4  4628.6  391.28  4664.7  384.06  4698.2   381.7
  4705.9   380.2  4739.4  377.68  4801.2  371.36  4870.8  369.22  4986.8  369.08
    4997  365.53  4999.8  365.03    5003  365.53  5007.4  368.86  5060.1  369.68
  5116.7  369.37  5187.4   367.8  5286.4  369.48    5343     369  5357.1  367.98
  5371.3  369.87  5385.4  369.14  5456.1  370.68  5470.3  373.48  5484.4   374.7
  5526.8  376.03    5541  379.52  5555.1  380.52  5579.9  384.81  5583.4  384.81
#Mann= 3 ,-1 , 0
  4605.4     .15       0    4997     .05       0    5003     .15       0
Bank Sta=4986.8,5007.4
XS Rating Curve= 0 ,0
Exp/Cntr=0.3,0.1

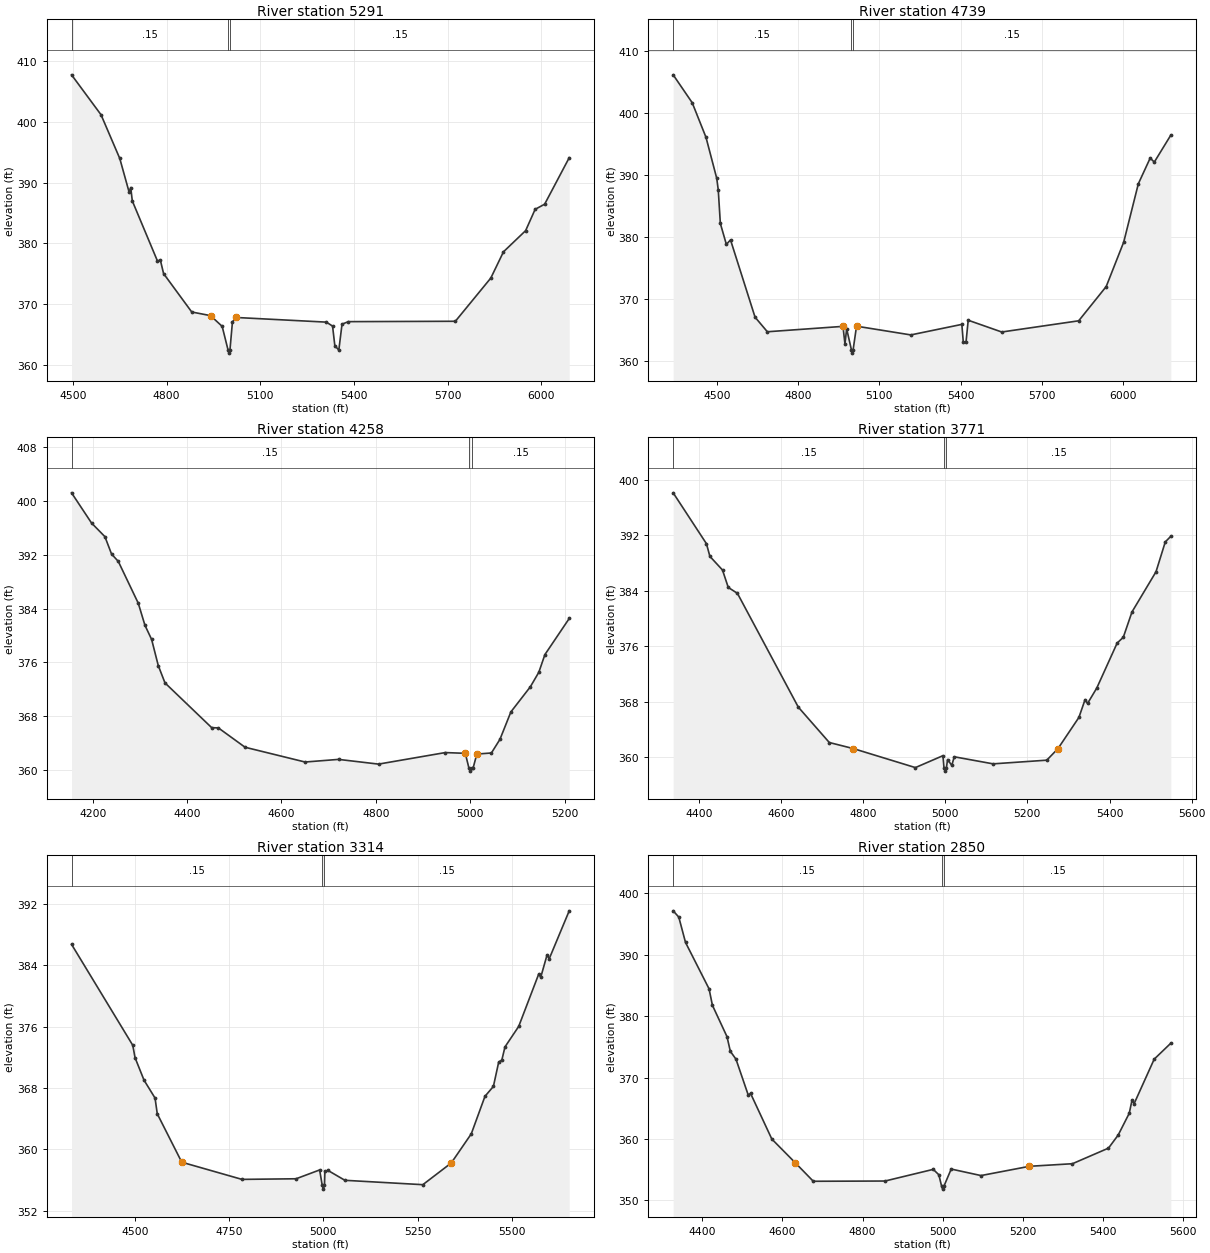
Type RM Length L Ch R = 1 ,5291    ,552,552,552
BEGIN DESCRIPTION:
SIXMILE BRANCH 11.0
END DESCRIPTION:
XS GIS Cut Line= 3
      3739103.77     10662708.03      3738259.98     10662650.74
      3737521.98     10662775.47
#Sta/Elev= 30
  4495.6  407.79    4590  401.21  4650.1     394  4680.2  388.42  4685.2  389.21
  4690.2  387.01  4770.4  377.15  4780.4  377.19  4790.4  375.03  4880.6   368.7
  4940.8   368.1  4978.1  366.33    4997  362.42  4999.8  361.92    5003  362.42
  5010.9  367.01    5021   367.8  5311.6  367.03  5331.7  366.38    5339  363.15
  5351.8  362.42    5362  366.69  5382.3  367.11  5725.1  367.17  5838.7   374.3
  5879.2  378.62  5950.2  382.11  5980.6  385.62  6011.1  386.47  6089.8  394.13
#Mann= 3 ,-1 , 0
  4495.6     .15       0    4997     .05       0    5003     .15       0
Bank Sta=4940.8,5021
XS Rating Curve= 0 ,0
Exp/Cntr=0.3,0.1

Type RM Length L Ch R = 1 ,4739    ,481,481,481
BEGIN DESCRIPTION:
SIXMILE BRANCH 10.0
END DESCRIPTION:
XS GIS Cut Line= 4
      3739056.87     10661864.27      3738577.69     10662093.44
      3738254.77     10662520.53      3737494.52     10662655.92
#Sta/Elev= 30
  4338.2  406.15  4408.5  401.65  4459.4  396.07  4499.2  389.44  4504.8  387.57
  4512.5  382.16  4534.7  378.78  4550.1   379.5  4640.8  367.02  4686.2  364.67
  4965.6  365.54  4972.9  362.71  4979.2  365.15    4997  361.72  4999.8  361.22
    5003  361.72  5015.7  365.57  5216.3  364.16  5404.8  365.86    5410  363.06
  5420.2  362.97  5428.3  366.53  5552.2  364.63  5836.6  366.44  5938.2  371.97
    6003  379.16  6056.9  388.56  6100.7  392.71  6115.9  392.06    6177  396.42
#Mann= 3 ,-1 , 0
  4338.2     .15       0    4997     .05       0    5003     .15       0
Bank Sta=4965.6,5015.7
XS Rating Curve= 0 ,0
Exp/Cntr=0.3,0.1

Type RM Length L Ch R = 1 ,4258    ,487,487,487
BEGIN DESCRIPTION:
SIXMILE BRANCH 9.0
END DESCRIPTION:
XS GIS Cut Line= 3
      3738849.59     10661360.21      3738249.61     10661960.19
      3738049.66     10662010.18
#Sta/Elev= 30
  4155.1  401.15  4197.5  396.67  4225.8  394.65  4239.9  392.07  4254.1  390.99
  4296.5  384.78  4310.6  381.52  4324.8  379.41  4338.9  375.53  4353.1  372.97
  4452.1  366.33  4466.2   366.3  4522.8  363.43    4650  361.24  4720.8  361.63
  4805.6  360.93    4947  362.64  4989.5  362.53    4997  360.39  4999.8  359.89
    5003  360.39  5006.2  360.39  5013.9  362.42  5044.8  362.58  5062.9   364.6
  5086.1  368.67  5127.3  372.39  5145.3  374.55  5158.2  377.17  5209.7  382.52
#Mann= 3 ,-1 , 0
  4155.1     .15       0    4997     .05       0    5003     .15       0
Bank Sta=4989.5,5013.9
XS Rating Curve= 0 ,0
Exp/Cntr=0.3,0.1

Type RM Length L Ch R = 1 ,3771    ,457,457,457
BEGIN DESCRIPTION:
SIXMILE BRANCH 8.0
END DESCRIPTION:
XS GIS Cut Line= 3
      3738749.56     10661210.21      3738149.61     10661510.19
      3737849.61     10661960.19
#Sta/Elev= 30
  4337.7  398.13  4418.7  390.79  4427.1  388.96  4457.8  386.99  4471.8  384.48
  4494.2  383.62  4642.3  367.21  4717.8   362.1  4776.5  361.22  4927.4  358.48
  4994.5   360.2    4997  358.47  4999.8  357.97    5003  358.47  5005.7  359.64
    5016   358.8    5022  360.04  5116.6  359.02  5247.3  359.55  5274.4  361.21
  5325.5  365.72  5340.5  368.29  5346.5  367.73    5369  369.96  5418.6  376.45
  5433.6  377.29  5454.7  380.94  5513.2  386.74  5535.8  391.05  5549.3  391.86
#Mann= 3 ,-1 , 0
  4337.7     .15       0    4997     .05       0    5003     .15       0
Bank Sta=4776.5,5274.4
XS Rating Curve= 0 ,0
Exp/Cntr=0.3,0.1

Type RM Length L Ch R = 1 ,3314    ,464,464,464
BEGIN DESCRIPTION:
SIXMILE BRANCH 7.0
END DESCRIPTION:
XS GIS Cut Line= 3
      3738549.63     10660860.18      3737949.61     10661110.19
      3737349.64     10661410.17
#Sta/Elev= 30
  4331.7  386.74  4494.2  373.58  4500.2  371.97    4524  369.04  4553.3   366.7
  4559.2  364.65  4624.2  358.34    4784   356.1  4927.6  356.18  4990.1  357.33
    4997  355.33  4999.8  354.83    5003  355.33  5004.1  357.14  5012.5  357.26
  5057.2  355.98    5264  355.41  5339.5  358.24  5392.6  362.04  5428.9  366.93
  5451.3  368.22  5465.3  371.39  5473.7  371.66    5482  373.37  5518.4  376.04
  5571.5  382.86  5577.1  382.48  5593.8  385.38  5599.4  384.86  5652.5  391.11
#Mann= 3 ,-1 , 0
  4331.7     .15       0    4997     .05       0    5003     .15       0
Bank Sta=4624.2,5339.5
XS Rating Curve= 0 ,0
Exp/Cntr=0.3,0.1

Type RM Length L Ch R = 1 ,2850    ,463,463,463
BEGIN DESCRIPTION:
SIXMILE BRANCH 6.0
END DESCRIPTION:
XS GIS Cut Line= 3
      3738499.65     10660360.17      3737899.61     10660660.19
      3737349.57     10660510.18
#Sta/Elev= 30
  4327.7  397.17  4341.7  396.15  4358.5  392.02  4417.2  384.46  4425.6  381.77
  4461.9  376.67  4470.3  374.27  4484.3     373    4515  367.13  4520.6  367.43
  4573.7  359.98  4632.4   356.1  4677.1   353.1    4856  353.14  4976.2  355.04
  4990.2  354.16    4997  352.32  4999.8  351.82    5003  352.32    5021  355.09
  5095.3  354.03  5216.2  355.54  5323.3  355.96  5413.2   358.5  5437.4  360.63
    5465  364.18  5471.9  366.32  5477.1  365.74  5527.2     373  5568.7   375.6
#Mann= 3 ,-1 , 0
  4327.7     .15       0    4997     .05       0    5003     .15       0
Bank Sta=4632.4,5216.2
XS Rating Curve= 0 ,0
Exp/Cntr=0.3,0.1