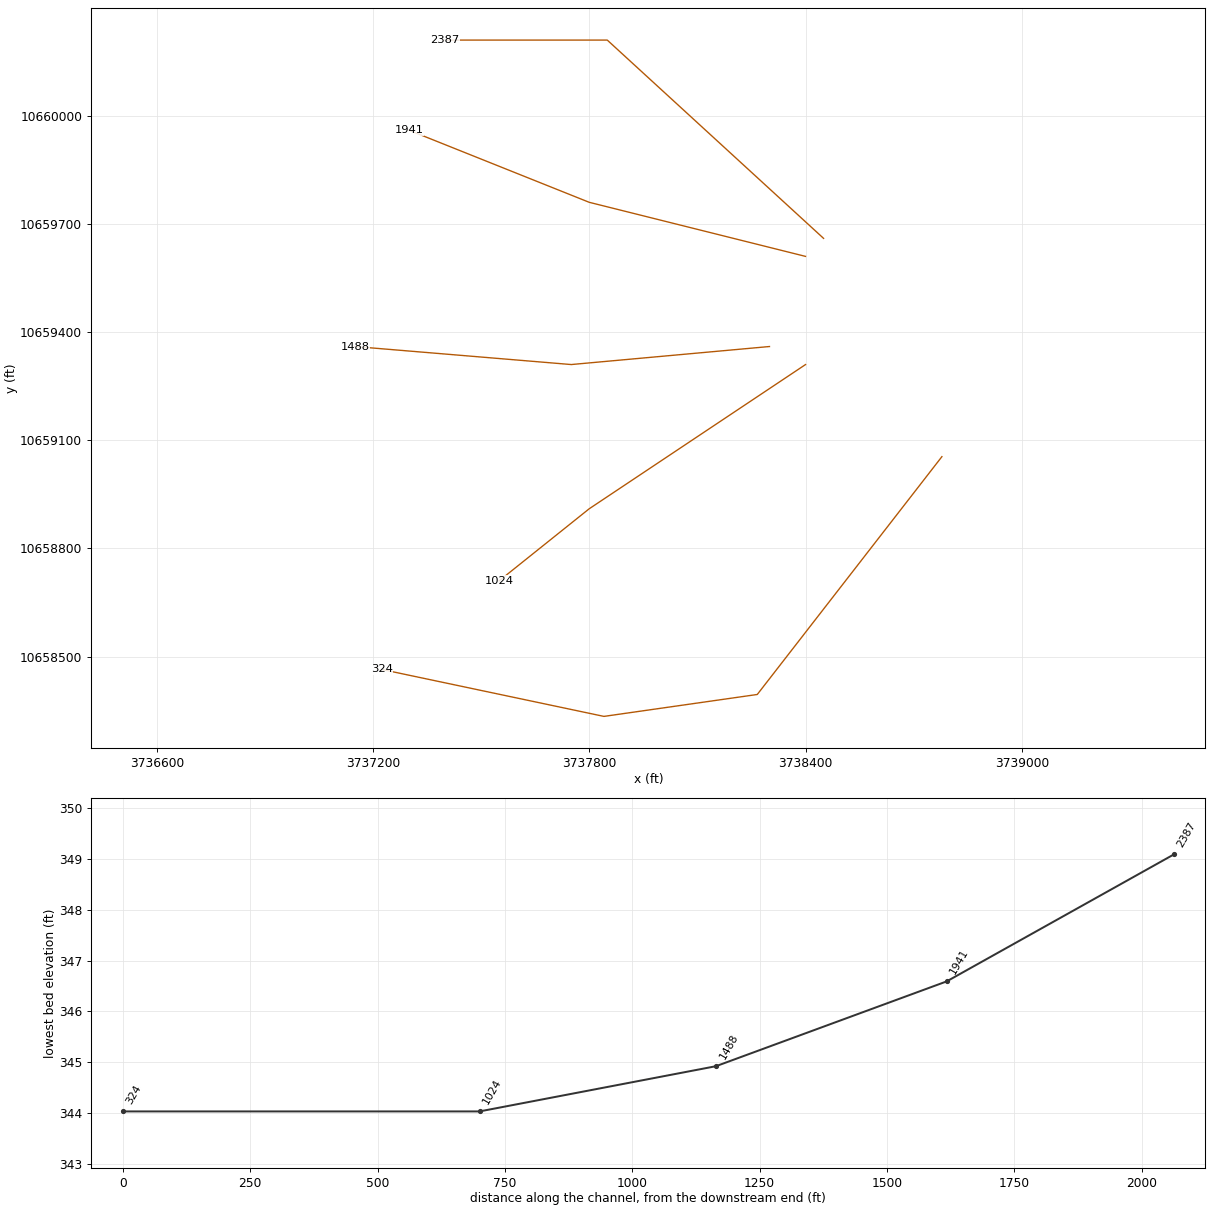
HEC-RAS study SIXMILE BRANCH.prj: SIXMILE BRANCH Base Level Engineering

--- SIXMILE BRANCH.g01 (geometry) --- (continued)

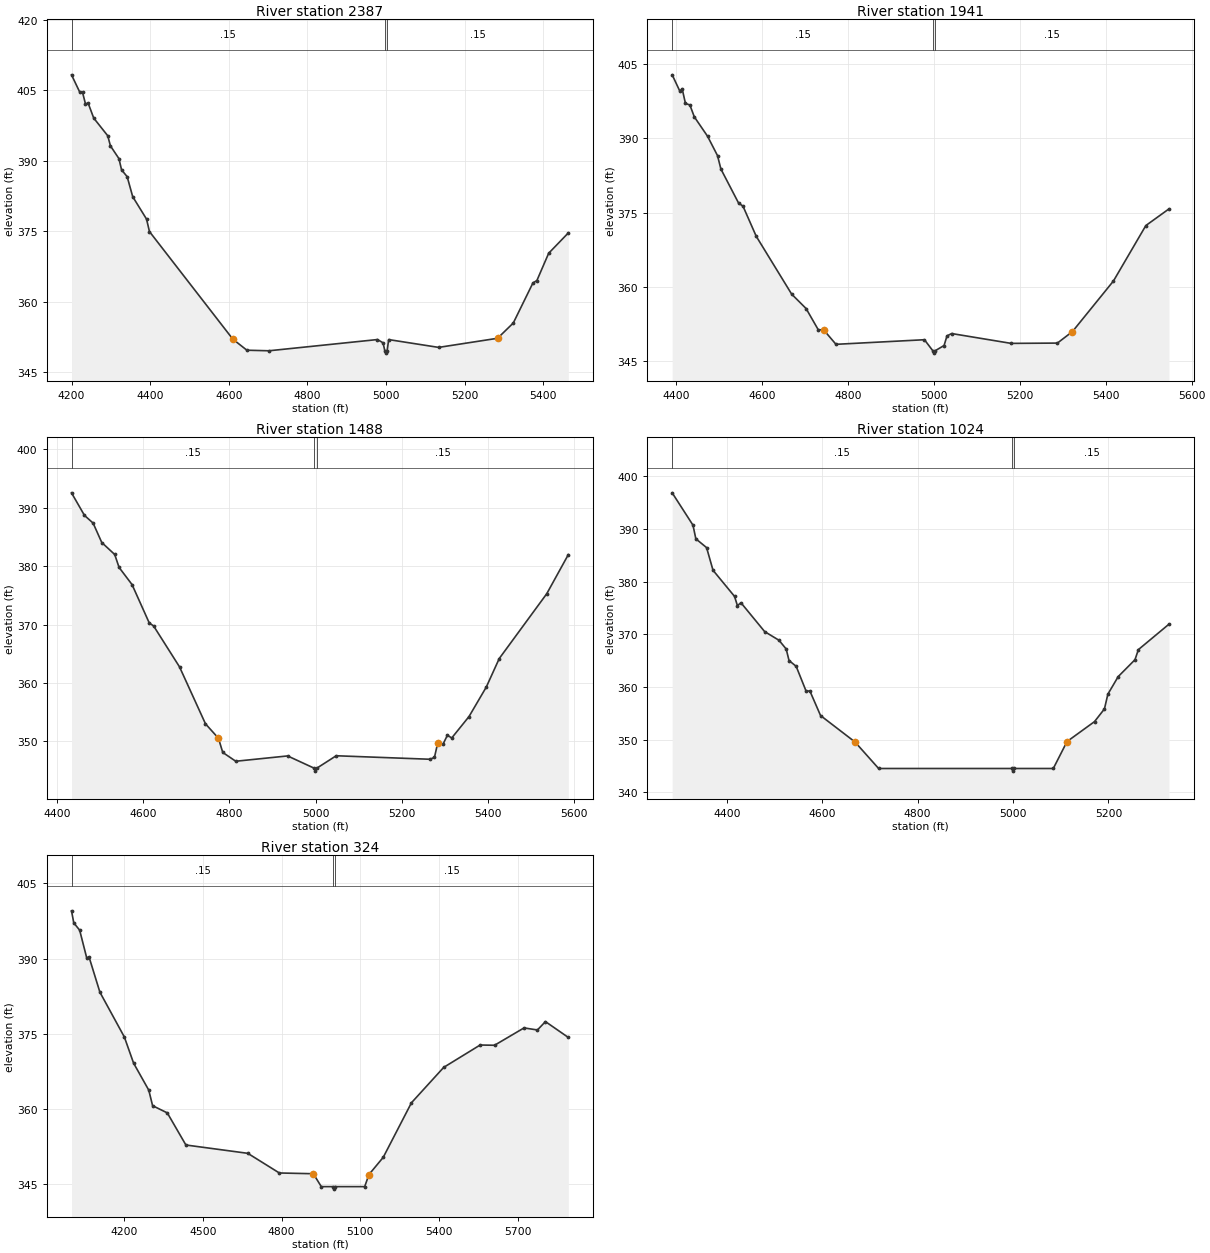
Type RM Length L Ch R = 1 ,2387    ,446,446,446
BEGIN DESCRIPTION:
SIXMILE BRANCH 5.0
END DESCRIPTION:
XS GIS Cut Line= 3
      3738449.64     10659660.16      3737849.61     10660210.19
      3737399.59     10660210.19
#Sta/Elev= 30
  4199.9  408.31  4221.2  404.57    4228  404.55  4235.4  402.15  4242.2  402.29
  4256.4  399.11  4292.1  395.34  4298.9   393.2  4320.5  390.49  4327.3  388.08
  4341.5  386.64  4355.6  382.38  4390.8  377.61  4398.2  374.96  4610.3  352.07
  4646.1  349.71  4702.2  349.59  4978.4  351.98  4992.6  351.28    4997  349.59
  4999.8  349.09    5003  349.59  5006.8  351.97  5133.9  350.31  5283.9  352.25
  5323.9   355.5  5373.9  364.03  5383.9  364.53  5413.9  370.34  5463.9  374.67
#Mann= 3 ,-1 , 0
  4199.9     .15       0    4997     .05       0    5003     .15       0
Bank Sta=4610.3,5283.9
XS Rating Curve= 0 ,0
Exp/Cntr=0.3,0.1

Type RM Length L Ch R = 1 ,1941    ,453,453,453
BEGIN DESCRIPTION:
SIXMILE BRANCH 4.0
END DESCRIPTION:
XS GIS Cut Line= 3
      3738399.58     10659610.19      3737799.61     10659760.19
      3737299.57      10659960.2
#Sta/Elev= 30
  4390.2  402.85  4408.2  399.52  4413.4  400.05  4421.1  397.06  4431.4  396.76
  4441.7  394.36  4472.6  390.43  4495.8  386.51  4503.6  383.82  4544.8  376.93
  4555.1   376.3    4586   370.2  4668.5  358.51    4702  355.61  4730.3  351.33
  4743.2  351.27  4771.6  348.37  4977.7   349.3    4997  347.09  4999.8  346.59
    5003  347.09  5023.4  348.13  5030.2  350.07    5041  350.55  5179.6  348.56
  5287.3  348.62  5322.3  350.94  5417.9  361.18  5493.3  372.38  5547.2  375.75
#Mann= 3 ,-1 , 0
  4390.2     .15       0    4997     .05       0    5003     .15       0
Bank Sta=4743.2,5322.3
XS Rating Curve= 0 ,0
Exp/Cntr=0.3,0.1

Type RM Length L Ch R = 1 ,1488    ,464,464,464
BEGIN DESCRIPTION:
SIXMILE BRANCH 3.0
END DESCRIPTION:
XS GIS Cut Line= 3
      3738299.61     10659360.19      3737749.61     10659310.19
      3737149.66     10659360.18
#Sta/Elev= 30
  4433.1  392.53  4463.2  388.67  4483.3  387.35  4503.4  384.03  4533.5  381.98
  4543.6  379.77  4573.7  376.84  4613.8  370.26  4623.9  369.75  4684.1  362.75
  4744.4  353.01  4774.5  350.55  4784.5  348.12  4814.7  346.61  4935.2  347.52
    4997  345.42  4999.8  344.92    5003  345.42  5048.1  347.55  5266.3  346.95
  5276.4  347.28  5283.9  349.71  5296.4  349.54  5306.5  351.07  5316.5  350.59
  5356.7  354.26  5396.8   359.3  5426.9  364.18  5537.3  375.27  5587.4  381.96
#Mann= 3 ,-1 , 0
  4433.1     .15       0    4997     .05       0    5003     .15       0
Bank Sta=4774.5,5283.9
XS Rating Curve= 0 ,0
Exp/Cntr=0.3,0.1

Type RM Length L Ch R = 1 ,1024    ,700,700,700
BEGIN DESCRIPTION:
SIXMILE BRANCH 2.0
END DESCRIPTION:
XS GIS Cut Line= 3
      3738399.61     10659310.19      3737799.61     10658910.19
      3737549.59     10658710.17
#Sta/Elev= 30
  4285.6  396.86  4329.2  390.72  4335.2  388.13  4357.7  386.46  4371.2  382.16
  4416.3   377.2  4422.3  375.46  4429.8  375.99  4479.4  370.52  4509.5  368.87
  4524.5  367.22  4530.5  365.03  4545.5  363.92  4566.5  359.17  4574.1  359.27
  4596.6  354.58  4668.7  349.57  4718.3  344.53    4997  344.53  4999.8  344.03
    5003  344.53  5084.4  344.53  5113.2  349.65  5170.8  353.43  5191.6  355.84
  5198.8  358.64  5220.4  361.97  5255.6  365.18  5262.8   367.1  5326.9  371.93
#Mann= 3 ,-1 , 0
  4285.6     .15       0    4997     .05       0    5003     .15       0
Bank Sta=4668.7,5113.2
XS Rating Curve= 0 ,0
Exp/Cntr=0.3,0.1

Type RM Length L Ch R = 1 ,324     ,0,0,0
BEGIN DESCRIPTION:
SIXMILE BRANCH 1.0
END DESCRIPTION:
XS GIS Cut Line= 4
      3738777.87     10659054.74      3738265.71     10658395.01
      3737840.36     10658334.24      3737224.32     10658464.39
#Sta/Elev= 30
  3998.9  399.53  4007.6  397.12    4030  395.67  4057.4  390.04  4065.5  390.37
  4107.2   383.3  4200.4  374.37  4235.7  369.15  4293.6  363.76  4308.1  360.67
  4364.2  359.23  4435.1  352.83  4671.1  351.17  4791.4  347.25  4921.1   347.1
  4951.4  344.53    4997  344.53  4999.8  344.03    5003  344.53  5116.9  344.53
  5133.2  346.94  5187.6  350.37  5295.2  361.25  5418.2  368.31  5557.2  372.77
  5612.1  372.72  5724.5  376.18  5775.6  375.77  5806.2  377.44  5893.4  374.28
#Mann= 3 ,-1 , 0
  3998.9     .15       0    4997     .05       0    5003     .15       0
Bank Sta=4921.1,5133.2
XS Rating Curve= 0 ,0
Exp/Cntr=0.3,0.1

Chan Stop Cuts=-1
Use User Specified Reach Order=0
Composite Channel Slope=5