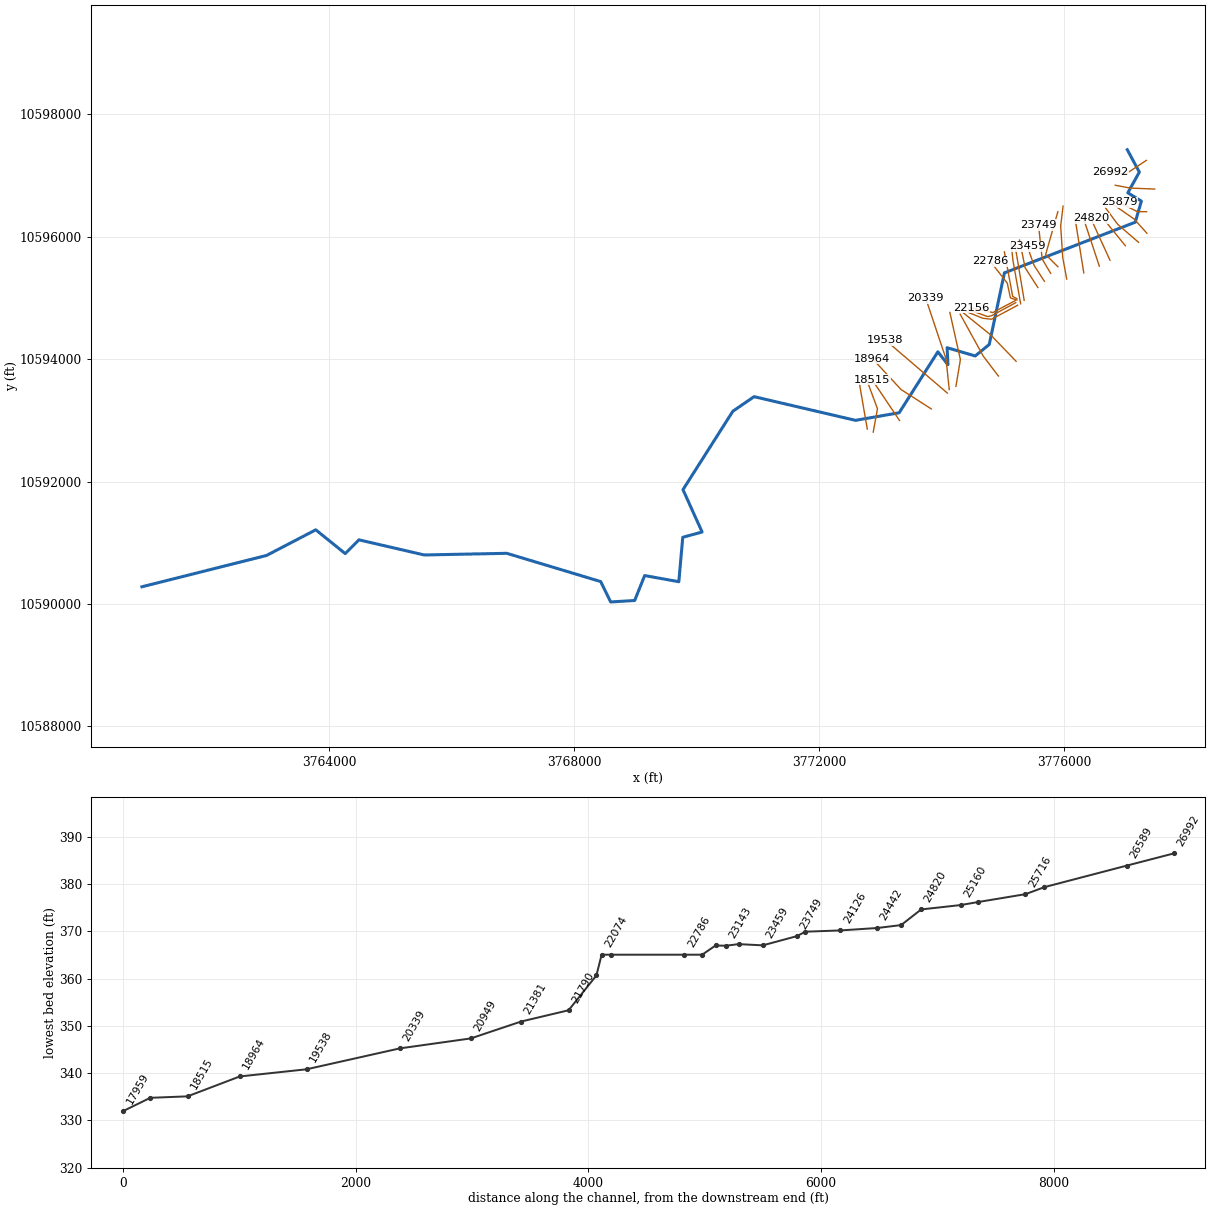
--- SPRING BRANCH.prj (project) ---

Proj Title=SPRING BRANCH Base Level Engineering
Current Plan=p01
Default Exp/Contr=0.3,0.1
English Units
Geom File=g01
Flow File=f01
Plan File=p01
Y Axis Title=Elevation
X Axis Title(PF)=Main Channel Distance
X Axis Title(XS)=Station
BEGIN DESCRIPTION:
SPRING BRANCH
END DESCRIPTION:
DSS Export Rating Curves= 0
DSS Export Rating Curve Sorted= 0
DSS Export Volume Flow Curves= 0
DXF OffsetX= 0
DXF OffsetY= 0
DXF ScaleX= 1
DXF ScaleY= 10

--- SPRING BRANCH.p01 (plan) ---

Plan Title=Multiple Run
Short Identifier=Multiple
Geom File=g01
Flow File=f01
Subcritical Flow
K Sum by GR= 0
Std Step Tol= 0.01
Critical Tol= 0.01
Num of Std Step Trials= 20
Max Error Tol= 0.3
Flow Tol Ratio= 0.001
Split Flow NTrial= 30
Split Flow Tol= 0.02
Split Flow Ratio= 0.02
Log Output Level= 0
Friction Slope Method= 1
Unsteady Friction Slope Method= 2
Unsteady Bridges Friction Slope Method= 1
Parabolic Critical Depth
Global Vel Dist=  1 , 1 , 1
Global Log Level= 0
CheckData=True
Encroach Param= -1, 0, 0, 0
BEGIN DESCRIPTION:
Multiple Run
END DESCRIPTION:

--- SPRING BRANCH.f01 (steady flow) ---

Flow Title=Multiple
Program Version=4.10
Number of Profiles= 7
Profile Names=10-year,25-year,50-year,1pct_min,100-year,1pct_plu,500-year
River Rch & RM=SPRING BRANCH,Reach-1         ,26992
     710     979    1207    1096    1482    2004    2237
River Rch & RM=SPRING BRANCH,Reach-1         ,24126
     939    1308    1623    1479    2001    2706    3050
River Rch & RM=SPRING BRANCH,Reach-1         ,15710
    1222    1723    2153    1974    2669    3610    4120
River Rch & RM=SPRING BRANCH,Reach-1         ,9515
    1699    2434    3074    2847    3850    5207    6063
River Rch & RM=SPRING BRANCH,Reach-1         ,7823
    1949    2802    3548    3290    4449    6017    7031
Boundary for River Rch & Prof#=SPRING BRANCH,Reach-1         , 1
Up Type= 0
Dn Type= 3
Dn Slope=0.005
Boundary for River Rch & Prof#=SPRING BRANCH,Reach-1         , 2
Up Type= 0
Dn Type= 3
Dn Slope=0.005
Boundary for River Rch & Prof#=SPRING BRANCH,Reach-1         , 3
Up Type= 0
Dn Type= 3
Dn Slope=0.005
Boundary for River Rch & Prof#=SPRING BRANCH,Reach-1         , 4
Up Type= 0
Dn Type= 3
Dn Slope=0.005
Boundary for River Rch & Prof#=SPRING BRANCH,Reach-1         , 5
Up Type= 0
Dn Type= 3
Dn Slope=0.005
Boundary for River Rch & Prof#=SPRING BRANCH,Reach-1         , 6
Up Type= 0
Dn Type= 3
Dn Slope=0.005
Boundary for River Rch & Prof#=SPRING BRANCH,Reach-1         , 7
Up Type= 0
Dn Type= 3
Dn Slope=0.005
DSS Import GetInterval= 0
DSS Import GetPeak= 0
DSS Import FillOption= 0

--- SPRING BRANCH.g01 (geometry) ---

Geom Title=Existing Conditions
Program Version=4.10

River Reach=SPRING BRANCH   ,Reach-1
Reach XY= 30
      3777033.83     10597422.09      3777230.25       10597057.
      3777042.25       10596718.       3777263.5       10596583.
      3777163.25       10596238.       3775026.5       10595410.
      3774778.75       10594240.       3774549.5       10594052.
       3774090.5       10594187.        3774104.       10593910.
      3773939.25       10594120.      3773307.25       10593124.
       3772594.5       10593000.       3770937.5       10593387.
      3770590.75       10593149.        3769776.       10591867.
      3770088.75       10591175.       3769772.5       10591089.
      3769708.25       10590363.      3769150.25       10590463.
      3768986.75       10590056.        3768595.       10590032.
      3768432.25       10590365.      3766898.25       10590827.
      3765549.75       10590800.       3764483.5       10591047.
       3764259.5       10590822.      3763778.25       10591211.
      3762974.25       10590792.      3760938.75       10590280.

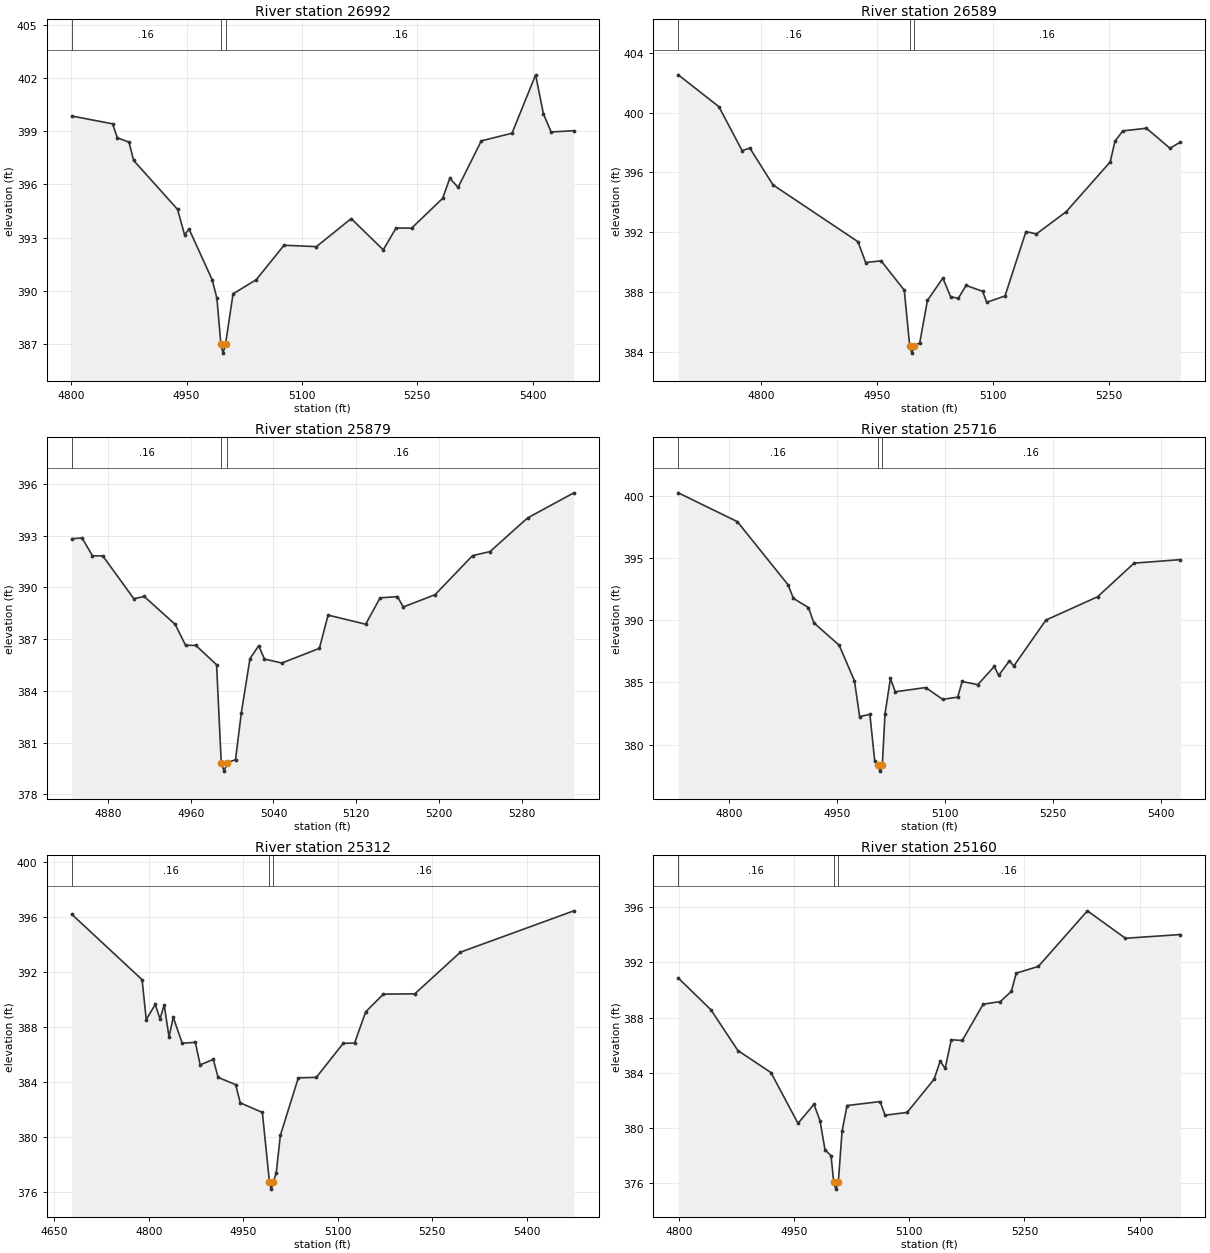
Type RM Length L Ch R = 1 ,26992   ,403,403,403
BEGIN DESCRIPTION:
SPRING BRANCH 52.0
END DESCRIPTION:
XS GIS Cut Line= 3
      3777343.81     10597248.09      3777005.28     10597024.14
      3776760.26     10597054.52
#Sta/Elev= 30
  4800.7  399.85  4853.7  399.41    4860  398.62  4875.1  398.38  4881.1  397.35
  4938.2  394.59  4947.3  393.17  4953.3  393.47  4983.4  390.61  4989.4  389.58
  4994.6  386.99  4997.3  386.49  5000.6  386.99  5010.4  389.83  5040.6  390.63
  5076.7  392.57  5118.8  392.49    5164  394.07  5205.7  392.31  5222.4  393.54
  5242.5  393.53  5282.9  395.21  5292.2  396.34    5303  395.83  5333.2  398.45
  5373.1  398.88  5403.8  402.17  5413.9  399.98  5423.9  398.95  5453.5  399.02
#Mann= 3 ,-1 , 0
  4800.7     .16       0  4994.6     .07       0  5000.6     .16       0
Bank Sta=4994.6,5000.6
XS Rating Curve= 0 ,0
Exp/Cntr=0.3,0.1

Type RM Length L Ch R = 1 ,26589   ,710,710,710
BEGIN DESCRIPTION:
SPRING BRANCH 51.0
END DESCRIPTION:
XS GIS Cut Line= 3
       3777482.3     10596779.97      3777081.24     10596795.59
      3776836.45     10596842.47
#Sta/Elev= 30
  4692.4  402.53  4745.1   400.4  4775.2  397.46  4785.2  397.63  4815.2  395.17
  4925.3  391.37  4935.3  389.98  4955.3  390.09  4985.3  388.13  4992.3  384.42
  4995.1  383.92  4998.3  384.42  5005.3   384.6  5015.3  387.44  5035.3  388.94
  5045.4  387.69  5055.4  387.59  5065.4  388.45  5086.9  388.05  5092.1  387.32
  5115.8  387.74    5143  392.05  5156.5  391.89    5195  393.37  5252.2  396.71
  5258.3  398.09  5268.5  398.78  5299.1  398.96  5329.6  397.62    5343  398.03
#Mann= 3 ,-1 , 0
  4692.4     .16       0  4992.3     .07       0  4998.3     .16       0
Bank Sta=4992.3,4998.3
XS Rating Curve= 0 ,0
Exp/Cntr=0.3,0.1

Type RM Length L Ch R = 1 ,25879   ,163,163,163
BEGIN DESCRIPTION:
SPRING BRANCH 50.0
END DESCRIPTION:
XS GIS Cut Line= 3
      3777349.56     10596410.19      3777199.61     10596410.19
      3776899.58      10596560.2
#Sta/Elev= 30
    4845  392.83    4855  392.87    4865  391.84    4875  391.83    4905  389.35
    4915  389.48    4945  387.86    4955  386.65    4965  386.64    4985  385.52
  4989.5  379.85  4992.2  379.35  4995.5  379.85  5003.3  380.01  5008.9  382.72
  5017.3  385.88  5025.7  386.62  5031.3  385.85  5048.1  385.62  5084.4  386.47
  5092.8   388.4  5129.1  387.87  5143.1   389.4  5159.9  389.47  5165.5  388.87
  5196.2  389.58  5232.5  391.85  5249.3  392.08  5285.6  394.03  5330.4  395.49
#Mann= 3 ,-1 , 0
    4845     .16       0  4989.5     .07       0  4995.5     .16       0
Bank Sta=4989.5,4995.5
XS Rating Curve= 0 ,0
Exp/Cntr=0.3,0.1

Type RM Length L Ch R = 1 ,25716   ,404,404,404
BEGIN DESCRIPTION:
Mapping XS 575f7e9e
END DESCRIPTION:
XS GIS Cut Line= 3
      3777352.89     10596058.03      3777144.55     10596290.68
      3776828.58     10596509.43
#Sta/Elev= 30
  4729.9  400.27  4811.9  397.95  4882.2  392.87  4889.7  391.77  4910.6  391.03
  4918.1   389.8  4953.2     388  4974.4  385.13  4981.6  382.25  4995.8  382.43
  5002.6  378.64  5007.1  378.36  5009.8  377.86  5013.1  378.36  5016.8  382.49
  5024.3  385.32    5031  384.25  5073.2  384.59  5096.8  383.64  5117.7  383.82
  5123.8  385.08  5145.5  384.82  5168.4  386.29  5174.5  385.57  5189.4  386.74
  5195.5  386.33    5240  390.02  5311.7   391.9  5362.4  394.61  5426.5  394.89
#Mann= 3 ,-1 , 0
  4729.9     .16       0  5007.1     .07       0  5013.1     .16       0
Bank Sta=5007.1,5013.1
XS Rating Curve= 0 ,0
Exp/Cntr=0.3,0.1

Type RM Length L Ch R = 1 ,25312   ,152,152,152
BEGIN DESCRIPTION:
SPRING BRANCH 49.0
END DESCRIPTION:
XS GIS Cut Line= 3
      3777216.66     10595910.17      3776878.12     10596201.84
      3776669.76     10596483.12
#Sta/Elev= 30
  4677.9  396.21  4789.5  391.45  4796.1  388.55  4810.4  389.65    4818  388.59
  4824.6  389.62  4832.3  387.27  4838.9  388.72  4853.2  386.83    4874  386.89
  4881.7  385.25  4902.5  385.65  4910.2  384.34    4938  383.81  4945.3  382.49
  4980.4  381.79  4991.7  376.71  4994.4  376.21  4997.7  376.71  5002.4  377.39
    5009  380.13  5037.5  384.31    5066  384.34  5108.8  386.82  5126.8  386.84
  5144.4  389.11  5172.5   390.4  5222.3  390.42  5294.7  393.45  5474.8  396.46
#Mann= 3 ,-1 , 0
  4677.9     .16       0  4991.7     .07       0  4997.7     .16       0
Bank Sta=4991.7,4997.7
XS Rating Curve= 0 ,0
Exp/Cntr=0.3,0.1

Type RM Length L Ch R = 1 ,25160   ,340,340,340
BEGIN DESCRIPTION:
Mapping XS 5584072f
END DESCRIPTION:
XS GIS Cut Line= 2
      3777002.21     10595853.15      3776589.02     10596360.09
#Sta/Elev= 30
    4799  390.87  4841.5  388.57  4876.7  385.61  4919.8  384.01    4955  380.33
  4975.8  381.71  4983.7  380.52  4990.1  378.43  4998.1  377.97  5001.5  376.06
  5004.3  375.56  5007.5  376.06  5012.4  379.75  5018.9  381.62    5062  381.91
  5068.4  380.92  5097.1  381.12  5132.3  383.53  5140.2  384.84  5146.7  384.31
  5154.6  386.39    5169  386.34  5196.2  388.97  5218.5  389.16  5232.9   389.9
  5239.3  391.22  5268.1  391.71    5332  395.74  5381.5  393.75    5453  394.02
#Mann= 3 ,-1 , 0
    4799     .16       0  5001.5     .07       0  5007.5     .16       0
Bank Sta=5001.5,5007.5
XS Rating Curve= 0 ,0
Exp/Cntr=0.3,0.1

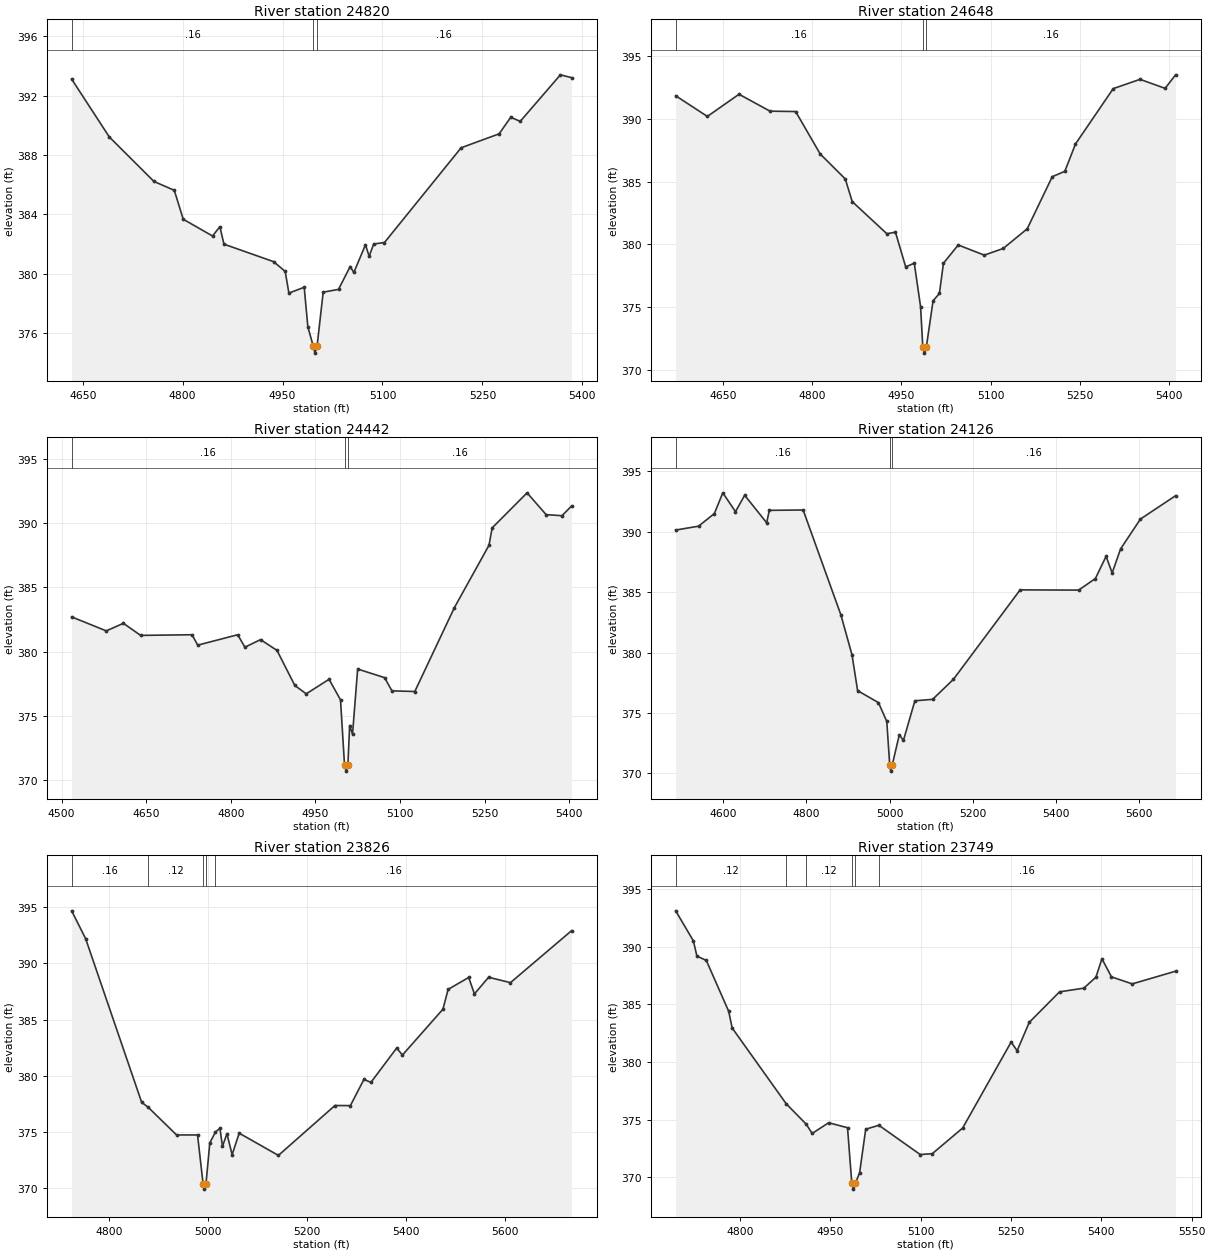
Type RM Length L Ch R = 1 ,24820   ,172,172,172
BEGIN DESCRIPTION:
Mapping XS 46888089
END DESCRIPTION:
XS GIS Cut Line= 2
      3776750.05     10595617.93      3776437.57     10596300.17
#Sta/Elev= 30
  4633.4  393.11  4689.9  389.21  4756.9  386.21  4787.5  385.61  4800.9  383.66
  4844.9  382.53  4855.9  383.16    4862  381.98  4936.5   380.8    4954  380.14
  4959.5  378.68  4982.5  379.07    4988   376.4  4995.9  375.13  4998.6  374.63
  5001.9  375.13    5011  378.74    5034  378.93  5051.5  380.47    5057  380.07
  5074.5  381.94    5080  381.16  5086.8  381.99    5103  382.09  5218.1  388.48
  5275.1  389.42  5292.6  390.54  5306.8  390.26  5367.1   393.4  5383.8  393.21
#Mann= 3 ,-1 , 0
  4633.4     .16       0  4995.9     .07       0  5001.9     .16       0
Bank Sta=4995.9,5001.9
XS Rating Curve= 0 ,0
Exp/Cntr=0.3,0.1

Type RM Length L Ch R = 1 ,24648   ,206,206,206
BEGIN DESCRIPTION:
Mapping XS 87efb70d
END DESCRIPTION:
XS GIS Cut Line= 2
      3776576.63     10595519.72      3776312.39     10596316.77
#Sta/Elev= 30
  4570.8  391.86    4624  390.21  4677.2  391.98  4729.3  390.63  4772.3   390.6
  4813.6  387.21  4855.7  385.22  4867.4  383.41  4925.5  380.85    4940  380.97
  4957.2   378.2  4971.6   378.5  4982.2  375.02  4985.9  371.82  4988.6  371.32
  4991.9  371.82  5003.2   375.5  5013.8  376.08  5020.6  378.49  5045.4  379.95
  5089.2  379.14  5120.9  379.67  5161.3  381.24  5203.4   385.4  5224.5  385.83
  5242.4  388.01  5305.8  392.43  5350.9  393.17    5393  392.45  5410.5  393.53
#Mann= 3 ,-1 , 0
  4570.8     .16       0  4985.9     .07       0  4991.9     .16       0
Bank Sta=4985.9,4991.9
XS Rating Curve= 0 ,0
Exp/Cntr=0.3,0.1

Type RM Length L Ch R = 1 ,24442   ,316,316,316
BEGIN DESCRIPTION:
Mapping XS ef48f12d
END DESCRIPTION:
XS GIS Cut Line= 2
      3776322.99     10595409.52      3776182.35     10596284.59
#Sta/Elev= 30
  4517.8  382.71  4579.2  381.62  4609.6  382.21    4640  381.27  4731.2  381.32
  4741.3  380.51  4812.2  381.32    4825  380.35  4852.7  380.94  4881.9   380.1
  4913.5  377.37  4933.7  376.72  4974.2  377.85  4994.5  376.25  5001.6   371.2
  5004.4   370.7  5007.6   371.2  5010.7  374.25  5015.8  373.58  5024.9  378.65
  5072.6  377.98  5085.7  376.95  5126.2   376.9  5196.4  383.43  5257.8  388.29
  5263.4  389.64  5325.3  392.37  5359.1  390.67  5387.2  390.59  5404.1  391.34
#Mann= 3 ,-1 , 0
  4517.8     .16       0  5001.6     .07       0  5007.6     .16       0
Bank Sta=5001.6,5007.6
XS Rating Curve= 0 ,0
Exp/Cntr=0.3,0.1

Type RM Length L Ch R = 1 ,24126   ,300,300,300
BEGIN DESCRIPTION:
Mapping XS 760e024f
END DESCRIPTION:
XS GIS Cut Line= 4
      3776044.21     10595308.82       3775979.1     10595660.41
      3775945.24     10596173.43       3775984.3     10596501.51
#Sta/Elev= 30
  4485.5  390.14  4540.5  390.46  4578.4   391.5  4598.8  393.22  4629.3  391.66
  4651.4  393.02  4704.3  390.74  4710.6  391.77    4792   391.8  4882.9  383.11
  4909.6   379.8    4923  376.85  4973.1  375.86  4993.2   374.3  5000.2  370.69
  5002.9  370.19  5006.2  370.69  5023.2  373.19  5033.3  372.74  5060.7  376.01
  5103.4  376.13  5153.5  377.79  5313.9  385.19  5454.6  385.17  5494.9  386.13
  5520.6  387.97  5535.2  386.59  5555.4  388.58  5603.2  391.05  5687.6  392.98
#Mann= 3 ,-1 , 0
  4485.5     .16       0  5000.2     .07       0  5006.2     .16       0
Bank Sta=5000.2,5006.2
XS Rating Curve= 0 ,0
Exp/Cntr=0.3,0.1

Type RM Length L Ch R = 1 ,23826   ,77,77,77
BEGIN DESCRIPTION:
SPRING BRANCH 46.0
END DESCRIPTION:
XS GIS Cut Line= 3
      3775899.64     10595510.15      3775699.61     10595710.19
      3775899.61     10596410.19
#Sta/Elev= 30
  4724.2  394.68  4752.5   392.2  4865.7  377.65    4879   377.2  4936.4  374.74
  4978.8  374.74  4989.9  370.42  4992.7  369.92  4995.9  370.42  5003.6  374.04
    5015     375    5024  375.33  5029.2  373.73  5038.3  374.85  5048.7  372.98
    5063   374.9  5142.3  372.92  5256.7  377.36  5287.9  377.35  5315.2  379.68
  5329.5  379.42  5381.5  382.47  5393.2  381.85  5475.1  385.93  5485.5  387.69
  5527.1  388.75  5538.8  387.29  5567.4  388.77  5611.6  388.29  5735.1  392.91
#Mann= 5 ,-1 , 0
  4724.2     .16       0    4879     .12       0  4989.9     .07       0
  4995.9     .12       0    5015     .16       0
Bank Sta=4989.9,4995.9
XS Rating Curve= 0 ,0
Exp/Cntr=0.3,0.1

Type RM Length L Ch R = 1 ,23749   ,290,290,290
BEGIN DESCRIPTION:
Mapping XS 46fe0a2f
END DESCRIPTION:
XS GIS Cut Line= 3
      3775781.18     10595402.59      3775643.16     10595636.97
      3775583.26     10596191.64
#Sta/Elev= 30
  4693.4  393.11  4722.8   390.5  4728.6  389.19  4744.3   388.8  4781.4  384.39
  4787.2  382.94    4877  376.36  4910.2  374.59    4920  373.79  4947.3  374.72
  4978.7  374.29  4985.8  369.46  4988.5  368.96  4991.8  369.46  4998.8   370.4
  5008.9  374.16  5030.8   374.5  5099.4  371.96  5119.5  372.04  5169.8  374.26
  5250.3  381.72  5260.3  380.97  5280.4  383.43  5330.7  386.08    5371   386.4
  5391.1  387.35  5401.1  388.95  5416.9  387.38  5451.4  386.77  5523.3  387.87
#Mann= 6 ,-1 , 0
  4693.4     .12       0    4877     .16       0  4910.2     .12       0
  4985.8     .07       0  4991.8     .12       0  5030.8     .16       0
Bank Sta=4985.8,4991.8
XS Rating Curve= 0 ,0
Exp/Cntr=0.3,0.1

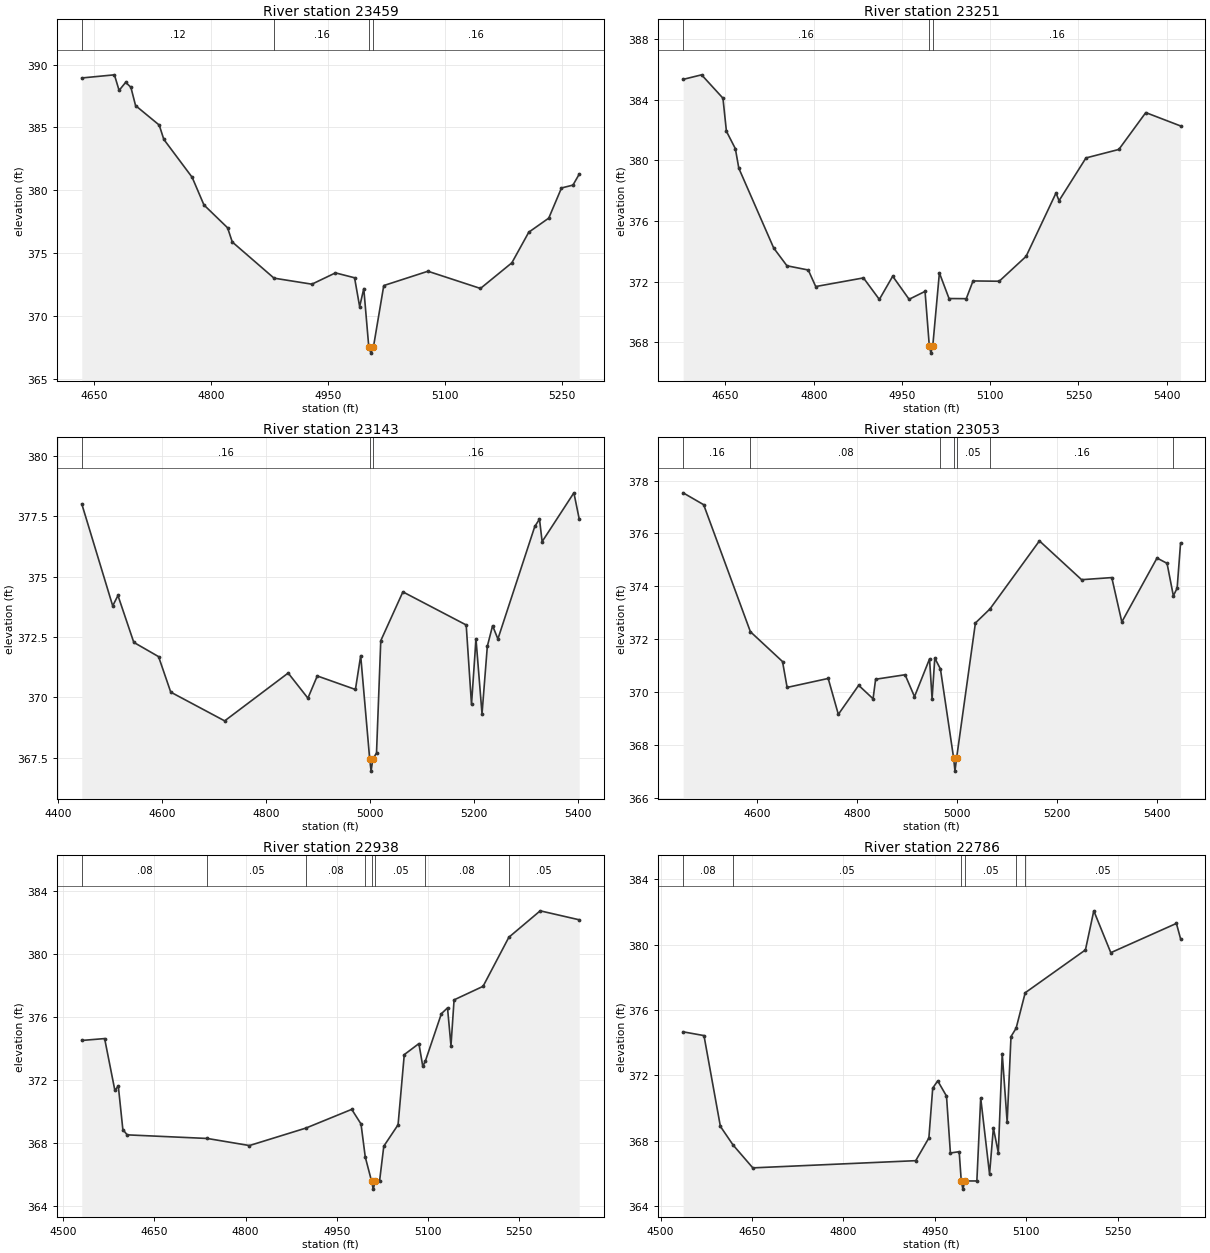
Type RM Length L Ch R = 1 ,23459   ,208,208,208
BEGIN DESCRIPTION:
SPRING BRANCH 45.0
END DESCRIPTION:
XS GIS Cut Line= 3
      3775679.32     10595273.04      3775510.06     10595533.44
      3775401.55     10595841.62
#Sta/Elev= 30
  4634.6  388.94  4676.4  389.19  4682.4  387.95  4690.8  388.59  4697.5   388.2
  4703.5  386.74  4733.8  385.19  4739.7  384.05    4776  381.03  4791.1  378.83
  4821.4  377.01  4827.4  375.88  4880.9     373  4929.4  372.52  4959.6  373.42
  4984.1  373.03  4990.6  370.73  4995.9  372.17  5002.3  367.53  5005.1  367.03
  5008.3  367.53  5021.5  372.41  5078.1  373.55  5145.4  372.18  5185.6  374.22
  5207.3  376.66  5232.9  377.78  5249.2  380.18  5263.9  380.41  5271.9  381.28
#Mann= 4 ,-1 , 0
  4634.6     .12       0  4880.9     .16       0  5002.3     .07       0
  5008.3     .16       0
Bank Sta=5002.3,5008.3
XS Rating Curve= 0 ,0
Exp/Cntr=0.3,0.1

Type RM Length L Ch R = 1 ,23251   ,108,108,108
BEGIN DESCRIPTION:
Mapping XS a2c15135
END DESCRIPTION:
XS GIS Cut Line= 3
      3775572.87     10595170.79      3775364.51     10595493.74
      3775273.53     10595946.05
#Sta/Elev= 30
    4578  385.34  4609.4  385.64  4645.7   384.1  4651.6  381.92  4666.8  380.77
  4672.7  379.48    4732  374.22  4754.5  373.05  4790.8  372.77  4803.4  371.68
  4884.6  372.25  4911.6  370.83  4934.3  372.36  4962.2  370.84  4989.3  371.36
  4996.5  367.79  4999.3  367.29  5002.5  367.79  5013.7  372.58  5030.1  370.89
  5059.4  370.88  5070.9  372.05  5115.4  372.03  5161.1  373.67    5212  377.85
  5217.1  377.34  5262.9  380.16  5318.8  380.72  5364.6  383.15  5423.7  382.27
#Mann= 3 ,-1 , 0
    4578     .16       0  4996.5     .07       0  5002.5     .16       0
Bank Sta=4996.5,5002.5
XS Rating Curve= 0 ,0
Exp/Cntr=0.3,0.1

Type RM Length L Ch R = 1 ,23143   ,90,90,90
BEGIN DESCRIPTION:
Mapping XS f1788cbf
END DESCRIPTION:
XS GIS Cut Line= 2
      3775349.03     10594961.59      3775192.78     10595904.33
#Sta/Elev= 30
  4445.9  378.01  4505.3  373.79  4515.4  374.22  4545.8  372.28  4593.4  371.69
  4616.8  370.22  4720.4  369.03  4842.4  371.01  4880.3  369.97  4898.3  370.89
  4971.6  370.33  4981.7  371.73    4999  367.45  5001.7  366.95    5005  367.45
  5012.1   367.7  5020.3  372.35  5062.8  374.37  5184.4     373  5194.6  369.71
  5203.2  372.42  5214.8  369.32    5225  372.12  5235.1  372.97  5245.3  372.42
  5316.2  377.08  5325.2  377.38  5330.3  376.45  5391.3  378.47  5401.5  377.39
#Mann= 3 ,-1 , 0
  4445.9     .16       0    4999     .07       0    5005     .16       0
Bank Sta=4999,5005
XS Rating Curve= 0 ,0
Exp/Cntr=0.3,0.1

Type RM Length L Ch R = 1 ,23053   ,115,115,115
BEGIN DESCRIPTION:
Mapping XS be0384aa
END DESCRIPTION:
XS GIS Cut Line= 3
      3775291.74     10594904.34      3775166.73     10595607.47
      3775135.68     10595886.99
#Sta/Elev= 30
  4452.6  377.54  4493.7  377.09  4587.2  372.28  4651.5  371.15  4660.7  370.17
  4742.9  370.51  4763.2  369.15  4803.9  370.25  4832.7  369.74  4837.8  370.48
  4896.8  370.65  4915.6  369.82  4945.7  371.25  4950.8  369.74  4956.2  371.28
  4967.5  370.87  4993.9   367.5  4996.6     367  4999.9   367.5  5037.5  372.61
  5066.5  373.14  5165.6  375.72    5250  374.25  5310.4  374.33  5330.5  372.65
  5400.9  375.07    5421  374.87  5433.6  373.64  5441.2  373.93    5448  375.63
#Mann= 7 ,-1 , 0
  4452.6     .16       0  4587.2     .08       0  4967.5     .05       0
  4993.9     .03       0  4999.9     .05       0  5066.5     .16       0
  5433.6     .08       0
Bank Sta=4993.9,4999.9
XS Rating Curve= 0 ,0
Exp/Cntr=0.3,0.1

Type RM Length L Ch R = 1 ,22938   ,152,152,152
BEGIN DESCRIPTION:
SPRING BRANCH 44.0
END DESCRIPTION:
XS GIS Cut Line= 3
      3775230.39     10594989.69      3775161.96     10595023.08
      3775026.11     10595753.31
#Sta/Elev= 30
  4530.3   374.5  4567.9  374.62  4584.8  371.32  4590.4  371.61  4597.9  368.84
    4605   368.5    4737  368.27  4806.3  367.82  4899.2  368.93  4974.7  370.12
    4990  369.19    4997  367.09  5007.4  365.55  5010.1  365.05  5013.4  365.55
  5020.5  365.55  5027.5  367.78    5051  369.14  5061.2   373.6  5085.3   374.3
  5091.7  372.85  5096.1  373.21  5122.3   376.2  5132.4  376.57  5138.1  374.17
  5143.2  377.08  5190.9  377.94  5233.4  381.06    5285  382.74  5349.2  382.17
#Mann= 8 ,-1 , 0
  4530.3     .08       0    4737     .05       0  4899.2     .08       0
    4997     .05       0  5007.4     .04       0  5013.4     .05       0
  5096.1     .08       0  5233.4     .05       0
Bank Sta=5007.4,5013.4
XS Rating Curve= 0 ,0
Exp/Cntr=0.3,0.1

Type RM Length L Ch R = 1 ,22786   ,630,630,630
BEGIN DESCRIPTION:
Mapping XS 573afe14
END DESCRIPTION:
XS GIS Cut Line= 4
      3775230.41     10594965.81      3775124.88      10594999.6
      3775072.98     10595242.89      3774791.74     10595602.25
#Sta/Elev= 30
    4537  374.67  4571.2  374.44  4598.1  368.89  4618.9  367.75  4651.3  366.35
  4918.5  366.79  4940.1  368.18  4946.4  371.23  4954.6  371.67    4969  370.74
  4975.4  367.26  4989.8  367.34  4993.2  365.55  4995.9  365.05  4999.2  365.55
  5018.8  365.55  5025.1  370.63  5039.6  365.97  5045.9  368.79    5054  367.28
  5060.4  373.34  5068.5  369.15  5074.8  374.38  5083.2  374.89  5098.1  377.06
  5196.9  379.68  5210.6  382.07  5238.5  379.51  5346.1   381.3  5352.9  380.37
#Mann= 6 ,-1 , 0
    4537     .08       0  4618.9     .05       0  4993.2     .03       0
  4999.2     .05       0  5083.2     .08       0  5098.1     .05       0
Bank Sta=4993.2,4999.2
XS Rating Curve= 0 ,0
Exp/Cntr=0.3,0.1

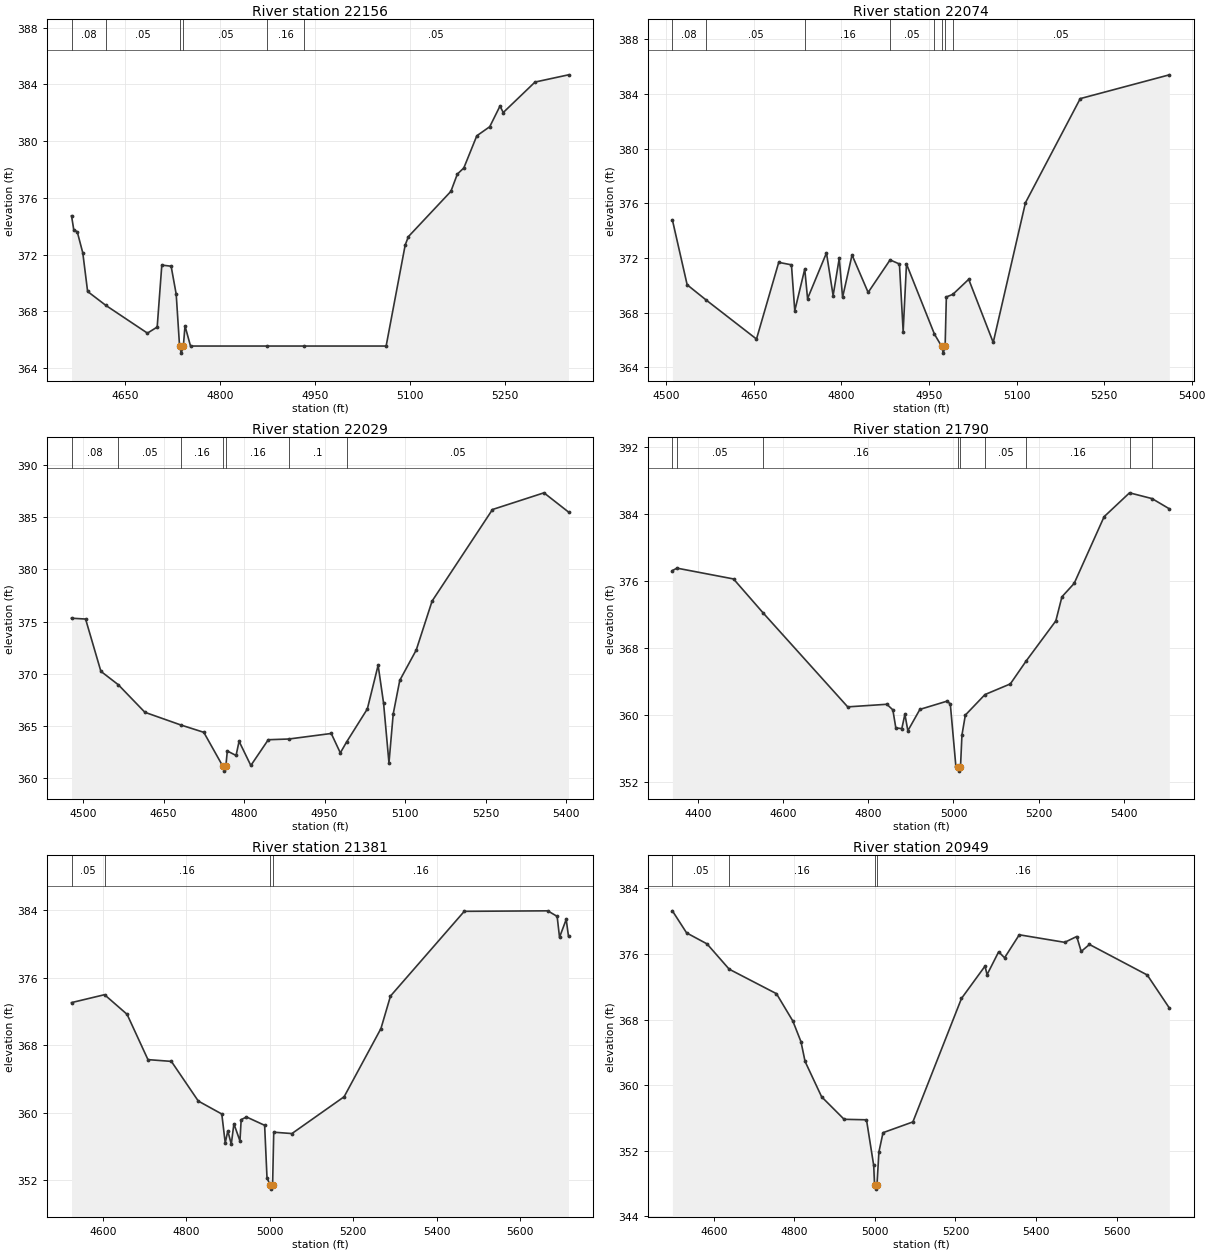
Type RM Length L Ch R = 1 ,22156   ,82,82,82
BEGIN DESCRIPTION:
Mapping XS dd507758
END DESCRIPTION:
XS GIS Cut Line= 3
      3775205.35     10594958.05      3774837.32     10594761.74
      3774477.98     10594837.25
#Sta/Elev= 30
  4565.6  374.74  4569.1  373.77  4574.7   373.6  4583.4  372.12    4591   369.4
  4619.7  368.42  4685.4  366.46  4700.8  366.89  4708.1  371.26  4722.8  371.18
  4730.8  369.21  4736.1  365.55  4738.8  365.05  4742.1  365.55  4744.7  366.97
  4753.4  365.55  4874.8  365.55  4931.9  365.55  5062.1  365.55  5092.2  372.68
  5097.3  373.27  5164.3  376.46  5174.5  377.68  5184.7  378.11  5205.2  380.38
  5225.6  381.02  5241.8  382.48  5246.9  382.02  5297.1  384.17  5349.9  384.68
#Mann= 6 ,-1 , 0
  4565.6     .08       0  4619.7     .05       0  4736.1    .033       0
  4742.1     .05       0  4874.8     .16       0  4931.9     .05       0
Bank Sta=4736.1,4742.1
XS Rating Curve= 0 ,0
Exp/Cntr=0.3,0.1

Type RM Length L Ch R = 1 ,22074   ,45,45,45
BEGIN DESCRIPTION:
Mapping XS b00e42cd
END DESCRIPTION:
XS GIS Cut Line= 4
       3775211.9     10594923.35      3774811.28     10594707.05
      3774748.78     10594696.64      3774436.27     10594811.22
#Sta/Elev= 30
  4510.3   374.8  4535.6  370.05  4568.3  368.93  4654.4  366.08  4692.5  371.69
  4714.3  371.51    4720  368.15  4737.1   371.2  4741.9  369.04  4774.3  372.38
  4785.7  369.26  4796.2  371.99  4801.9  369.13  4818.1  372.23  4845.7  369.49
  4883.3  371.87  4899.3  371.57  4905.7  366.63  4911.4  371.57  4959.3  366.44
  4971.6  365.55  4974.4  365.05  4977.6  365.55  4979.7  369.16  4990.8  369.35
    5018  370.45    5060  365.83  5115.2  376.05  5209.1  383.67  5361.8  385.41
#Mann= 8 ,-1 , 0
  4510.3     .08       0  4568.3     .05       0  4737.1     .16       0
  4883.3     .05       0  4959.3      .1       0  4971.6     .03       0
  4977.6      .1       0  4990.8     .05       0
Bank Sta=4971.6,4977.6
XS Rating Curve= 0 ,0
Exp/Cntr=0.3,0.1

Type RM Length L Ch R = 1 ,22029   ,239,239,239
BEGIN DESCRIPTION:
SPRING BRANCH 43.0
END DESCRIPTION:
XS GIS Cut Line= 4
      3775242.73     10594881.13      3774816.49     10594652.36
      3774673.26     10594667.99      3774397.23     10594779.96
#Sta/Elev= 30
  4478.6  375.32  4504.8  375.24  4533.3  370.23  4565.8  368.94  4615.3   366.3
  4681.9  365.09    4725  364.38  4760.1  361.16  4762.9  360.66  4766.1  361.16
  4768.8  362.59  4785.1  362.16  4790.7  363.52  4812.6   361.2  4845.1  363.67
  4883.6  363.74  4962.4  364.27  4979.3  362.41  4990.8  363.44  5029.6  366.62
  5049.7  370.81  5059.8   367.2  5069.9  361.45  5077.8  366.14    5090  369.36
  5120.7  372.27  5150.2  376.96  5262.7  385.74  5358.6  387.34  5404.3   385.5
#Mann= 7 ,-1 , 0
  4478.6     .08       0  4565.8     .05       0  4681.9     .16       0
  4760.1     .03       0  4766.1     .16       0  4883.6      .1       0
  4990.8     .05       0
Bank Sta=4760.1,4766.1
XS Rating Curve= 0 ,0
Exp/Cntr=0.3,0.1

Type RM Length L Ch R = 1 ,21790   ,409,409,409
BEGIN DESCRIPTION:
Mapping XS 979e0bae
END DESCRIPTION:
XS GIS Cut Line= 3
      3775217.51     10593964.88      3774798.26     10594399.76
      3774358.14     10594753.94
#Sta/Elev= 30
  4338.8  377.23  4349.6  377.52  4482.6  376.23  4552.7  372.15  4751.2  360.96
  4843.3  361.27  4857.4   360.6  4864.4  358.44  4878.5  358.37  4885.7  360.08
  4892.7  358.11    4921  360.66  4984.7  361.64  4992.5  361.32  5005.6  353.88
  5010.5  353.79  5013.3  353.29  5016.5  353.79  5019.9  357.59  5027.9  359.98
  5074.1  362.43  5133.7   363.7  5170.7  366.42  5240.7  371.22  5255.1   374.1
  5283.9   375.7  5354.3  383.66  5414.1  386.51  5467.1  385.82  5507.8   384.6
#Mann= 9 ,-1 , 0
  4338.8     .08       0  4349.6     .05       0  4552.7     .16       0
  5010.5     .07       0  5016.5     .16       0  5074.1     .05       0
  5170.7     .16       0  5414.1     .05       0  5467.1     .16       0
Bank Sta=5010.5,5016.5
XS Rating Curve= 0 ,0
Exp/Cntr=0.3,0.1

Type RM Length L Ch R = 1 ,21381   ,432,432,432
BEGIN DESCRIPTION:
Mapping XS 9d328b4b
END DESCRIPTION:
XS GIS Cut Line= 3
      3774928.48     10593723.53      3774681.07     10594049.07
      3774304.06     10594733.75
#Sta/Elev= 30
  4525.2  373.05  4604.3  373.99  4658.3  371.66  4708.3  366.28  4764.4  366.07
  4828.9  361.36  4885.2  359.82  4893.4  356.38  4899.6  357.82  4907.9  356.23
  4914.2  358.66  4928.7  356.62  4931.6  359.15  4944.3  359.47  4987.8  358.48
  4993.5  352.23  5000.9   351.4  5003.6   350.9  5006.9   351.4  5009.6  357.66
  5053.2   357.5  5178.2  361.87  5266.4  369.97  5289.3  373.83    5466  383.89
    5666  383.95  5688.5  383.29  5694.2  380.81  5710.2  382.93  5715.7  380.92
#Mann= 4 ,-1 , 0
  4525.2     .05       0  4604.3     .16       0  5000.9     .07       0
  5006.9     .16       0
Bank Sta=5000.9,5006.9
XS Rating Curve= 0 ,0
Exp/Cntr=0.3,0.1

Type RM Length L Ch R = 1 ,20949   ,610,610,610
BEGIN DESCRIPTION:
Mapping XS 24fa6ca6
END DESCRIPTION:
XS GIS Cut Line= 3
      3774234.44      10593555.4      3774307.36     10593992.89
      3774135.48     10594763.73
#Sta/Elev= 30
  4497.5  381.25  4532.8  378.56  4583.5  377.22  4638.4  374.14  4755.8  371.15
  4796.4  367.82  4816.6   365.3  4826.8  362.89  4867.9  358.58  4923.7  355.84
  4979.2  355.78  4997.1  350.22  4999.2  347.83    5002  347.33  5005.2  347.83
    5010  351.86  5020.2  354.21  5094.3  355.52  5214.9  370.57  5273.3  374.51
  5278.4  373.47  5307.1  376.25  5321.9  375.53  5358.3  378.33    5471  377.41
  5500.9  378.12    5512   376.3  5532.5  377.15  5675.9  373.43  5730.8   369.4
#Mann= 4 ,-1 , 0
  4497.5     .05       0  4638.4     .16       0  4999.2     .07       0
  5005.2     .16       0
Bank Sta=4999.2,5005.2
XS Rating Curve= 0 ,0
Exp/Cntr=0.3,0.1

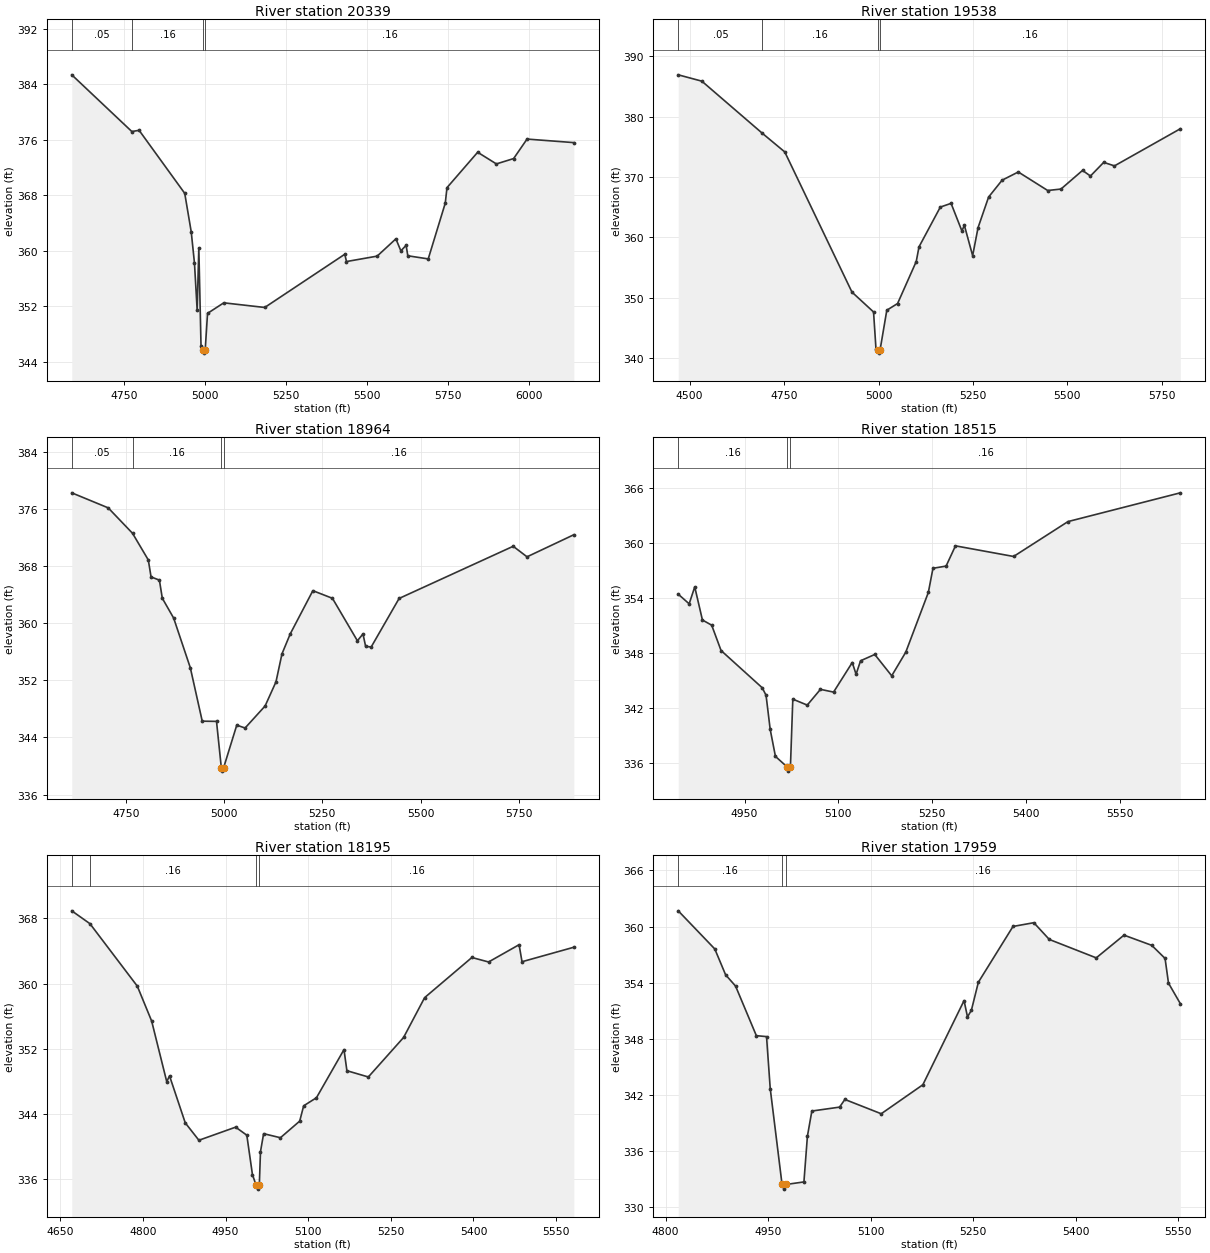
Type RM Length L Ch R = 1 ,20339   ,801,801,801
BEGIN DESCRIPTION:
Mapping XS 4a26a6e4
END DESCRIPTION:
XS GIS Cut Line= 3
      3774125.07     10593503.28      3774072.98      10594003.3
      3773740.15      10594996.6
#Sta/Elev= 30
  4589.1  385.33  4774.5  377.16  4797.1  377.33  4937.9  368.25    4958  362.69
    4968  358.19  4976.3   351.4  4981.4  360.39  4988.2  346.24  4995.2  345.72
    4998  345.22  5001.2  345.72  5008.3  350.95  5058.5  352.47  5184.9   351.8
  5432.1  359.47  5437.4  358.42  5532.1   359.2  5589.9  361.69  5605.3  359.96
  5621.5  360.76  5626.7  359.25  5689.8   358.8  5742.4  366.84  5747.7  369.07
  5842.4  374.17  5900.2  372.49  5953.4  373.26  5994.9  376.07  6139.4  375.56
#Mann= 4 ,-1 , 0
  4589.1     .05       0  4774.5     .16       0  4995.2     .07       0
  5001.2     .16       0
Bank Sta=4995.2,5001.2
XS Rating Curve= 0 ,0
Exp/Cntr=0.3,0.1

Type RM Length L Ch R = 1 ,19538   ,574,574,574
BEGIN DESCRIPTION:
Mapping XS a477513b
END DESCRIPTION:
XS GIS Cut Line= 2
      3774093.82     10593446.01      3773084.03     10594310.06
#Sta/Elev= 30
  4469.8  386.92  4532.3  385.87  4692.8  377.21  4751.8  374.14  4929.7  350.91
  4986.8  347.62  4993.3  341.44    4998   341.3  5000.8   340.8    5004   341.3
  5021.9  347.91  5050.4  349.02  5099.8  355.98  5107.1  358.41  5163.5     365
    5192  365.62  5220.6  361.06  5227.2  361.98  5249.1  356.95  5263.4  361.59
  5291.3  366.66  5327.1  369.46  5369.9  370.82  5447.8  367.75  5482.9  367.99
    5540  371.08  5560.9  370.15    5596  372.41  5624.5  371.83  5798.8  377.98
#Mann= 4 ,-1 , 0
  4469.8     .05       0  4692.8     .16       0    4998     .07       0
    5004     .16       0
Bank Sta=4998,5004
XS Rating Curve= 0 ,0
Exp/Cntr=0.3,0.1

Type RM Length L Ch R = 1 ,18964   ,449,449,449
BEGIN DESCRIPTION:
Mapping XS 40abaa46
END DESCRIPTION:
XS GIS Cut Line= 3
      3773833.42     10593185.58      3773338.61      10593503.3
      3772869.87      10594008.5
#Sta/Elev= 30
  4612.8  378.33  4705.5  376.22  4767.4  372.65  4807.5  368.91  4814.5  366.53
  4835.7  366.08  4843.1  363.54    4872  360.75  4914.4  353.78  4944.7  346.29
    4981  346.26  4993.2  339.78    4996  339.28  4999.2  339.78  5032.5  345.73
  5053.7  345.33  5104.6  348.42  5132.3  351.81  5147.5  355.73  5168.6  358.54
  5226.1   364.6  5275.9  363.53  5339.4  357.57  5353.6  358.53  5360.4  356.77
  5374.6  356.71  5445.5  363.51  5735.7  370.83  5770.9  369.35    5890  372.45
#Mann= 4 ,-1 , 0
  4612.8     .05       0  4767.4     .16       0  4993.2     .07       0
  4999.2     .16       0
Bank Sta=4993.2,4999.2
XS Rating Curve= 0 ,0
Exp/Cntr=0.3,0.1

Type RM Length L Ch R = 1 ,18515   ,320,320,320
BEGIN DESCRIPTION:
Mapping XS af842e66
END DESCRIPTION:
XS GIS Cut Line= 2
      3773312.59     10592998.07      3772864.65     10593664.76
#Sta/Elev= 30
  4843.8  354.39  4861.3  353.34  4870.2  355.19  4882.5  351.57  4897.3  351.01
  4912.3  348.24  4978.2  344.17  4984.3  343.35  4990.9  339.63  4999.3  336.68
  5017.3  335.57    5020  335.07  5023.3  335.57  5027.1  342.93  5050.2  342.28
  5071.3     344  5092.3   343.7  5122.2  346.93  5128.3  345.65  5135.5  347.12
  5158.2  347.81  5185.3  345.48  5207.8  348.06  5243.9  354.58  5251.3  357.22
  5272.3  357.46  5287.3  359.67  5380.3  358.51  5467.3  362.32    5647  365.46
#Mann= 3 ,-1 , 0
  4843.8     .16       0  5017.3     .07       0  5023.3     .16       0
Bank Sta=5017.3,5023.3
XS Rating Curve= 0 ,0
Exp/Cntr=0.3,0.1

Type RM Length L Ch R = 1 ,18195   ,236,236,236
BEGIN DESCRIPTION:
Mapping XS 42b883df
END DESCRIPTION:
XS GIS Cut Line= 3
      3772883.43     10592807.49      3772952.88     10593189.45
      3772770.57     10593679.95
#Sta/Elev= 30
  4670.7  368.93  4703.7  367.35  4789.7  359.68  4815.7   355.4  4843.1  347.96
  4848.2  348.66  4876.7   342.9  4901.5  340.76  4968.2  342.37  4988.5  341.38
  4998.7  336.55  5005.2  335.26    5008  334.76  5011.2  335.26  5013.3  339.36
    5019  341.57  5049.5  341.07  5084.5  343.11  5091.7  344.99  5114.9  345.98
  5164.9  351.89  5170.2   349.3  5209.1  348.53  5273.1  353.38  5311.3  358.27
  5397.1   363.2  5427.4  362.65  5482.8  364.77  5488.1  362.68  5582.2  364.46
#Mann= 4 ,-1 , 0
  4670.7     .05       0  4703.7     .16       0  5005.2     .07       0
  5011.2     .16       0
Bank Sta=5005.2,5011.2
XS Rating Curve= 0 ,0
Exp/Cntr=0.3,0.1

Type RM Length L Ch R = 1 ,17959   ,293,293,293
BEGIN DESCRIPTION:
Mapping XS 131fc056
END DESCRIPTION:
XS GIS Cut Line= 2
      3772786.52     10592857.51      3772661.53      10593581.4
#Sta/Elev= 30
  4818.6  361.68  4872.1   357.6  4887.9  354.84  4902.5  353.63  4932.9  348.33
  4947.8  348.23  4953.2  342.67  4970.5  332.42  4973.3  331.92  4976.5  332.42
  5002.5  332.69  5007.6  337.58  5014.1  340.27  5054.7  340.69  5062.4  341.51
  5115.6  339.98  5176.5  343.08  5236.8  352.08  5241.8  350.34  5247.5  351.04
  5257.7  354.04  5308.4  360.01  5338.9  360.41  5361.5  358.62  5430.2  356.65
  5470.8  359.08  5511.4  357.99  5530.9  356.59  5535.9  353.95  5553.2  351.76
#Mann= 3 ,-1 , 0
  4818.6     .16       0  4970.5     .07       0  4976.5     .16       0
Bank Sta=4970.5,4976.5
XS Rating Curve= 0 ,0
Exp/Cntr=0.3,0.1