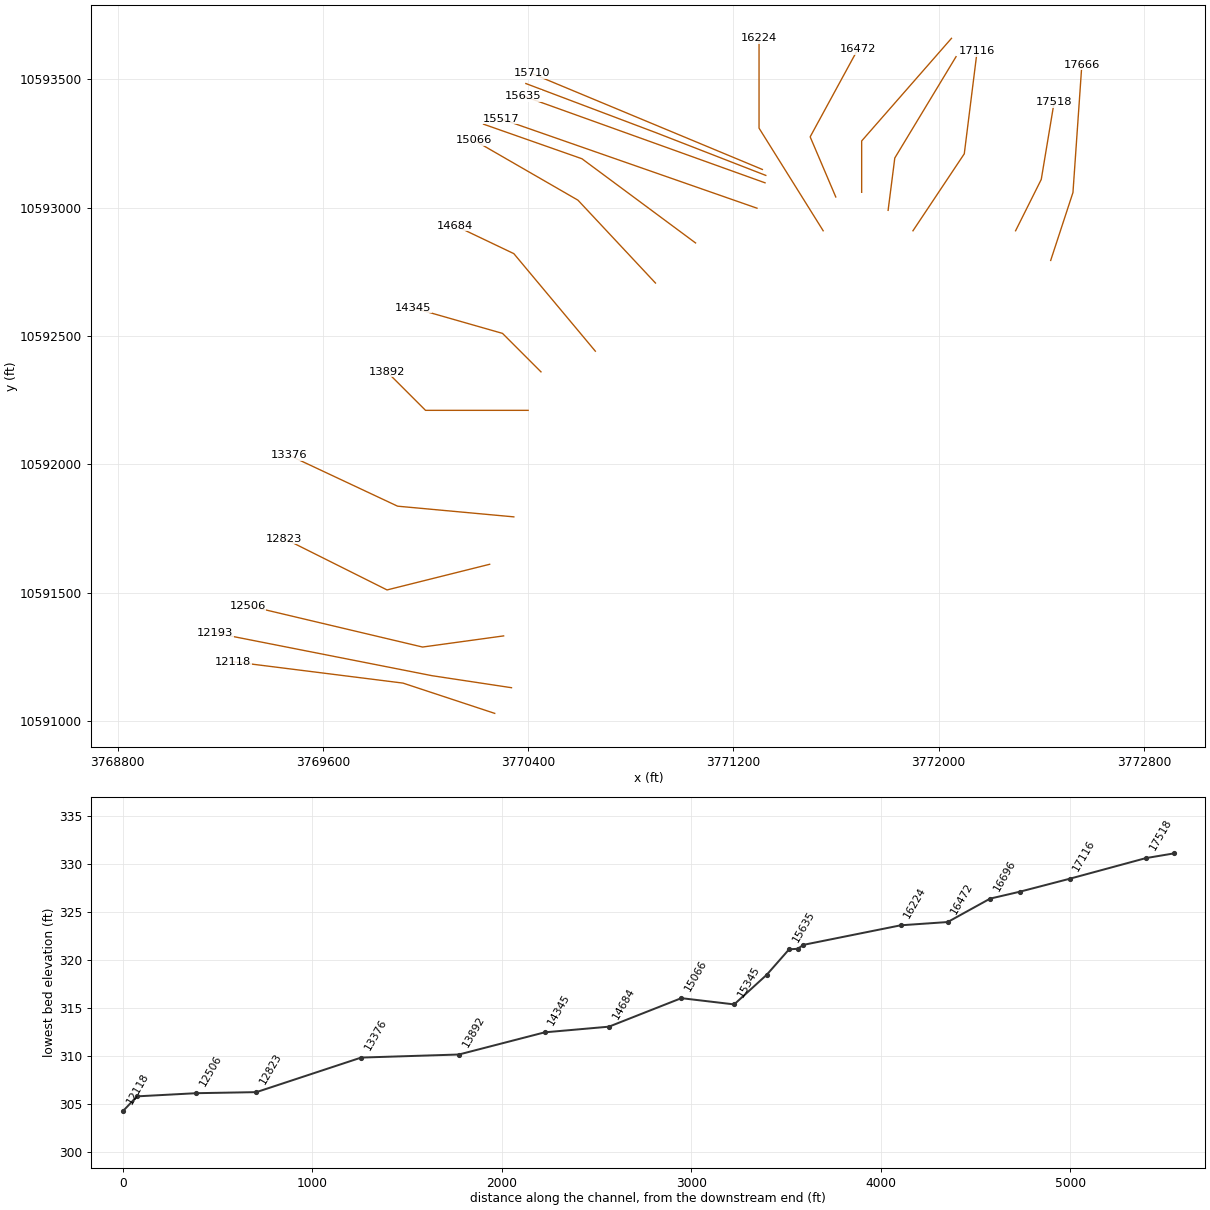
HEC-RAS study SPRING BRANCH.prj: SPRING BRANCH Base Level Engineering

--- SPRING BRANCH.g01 (geometry) --- (continued)

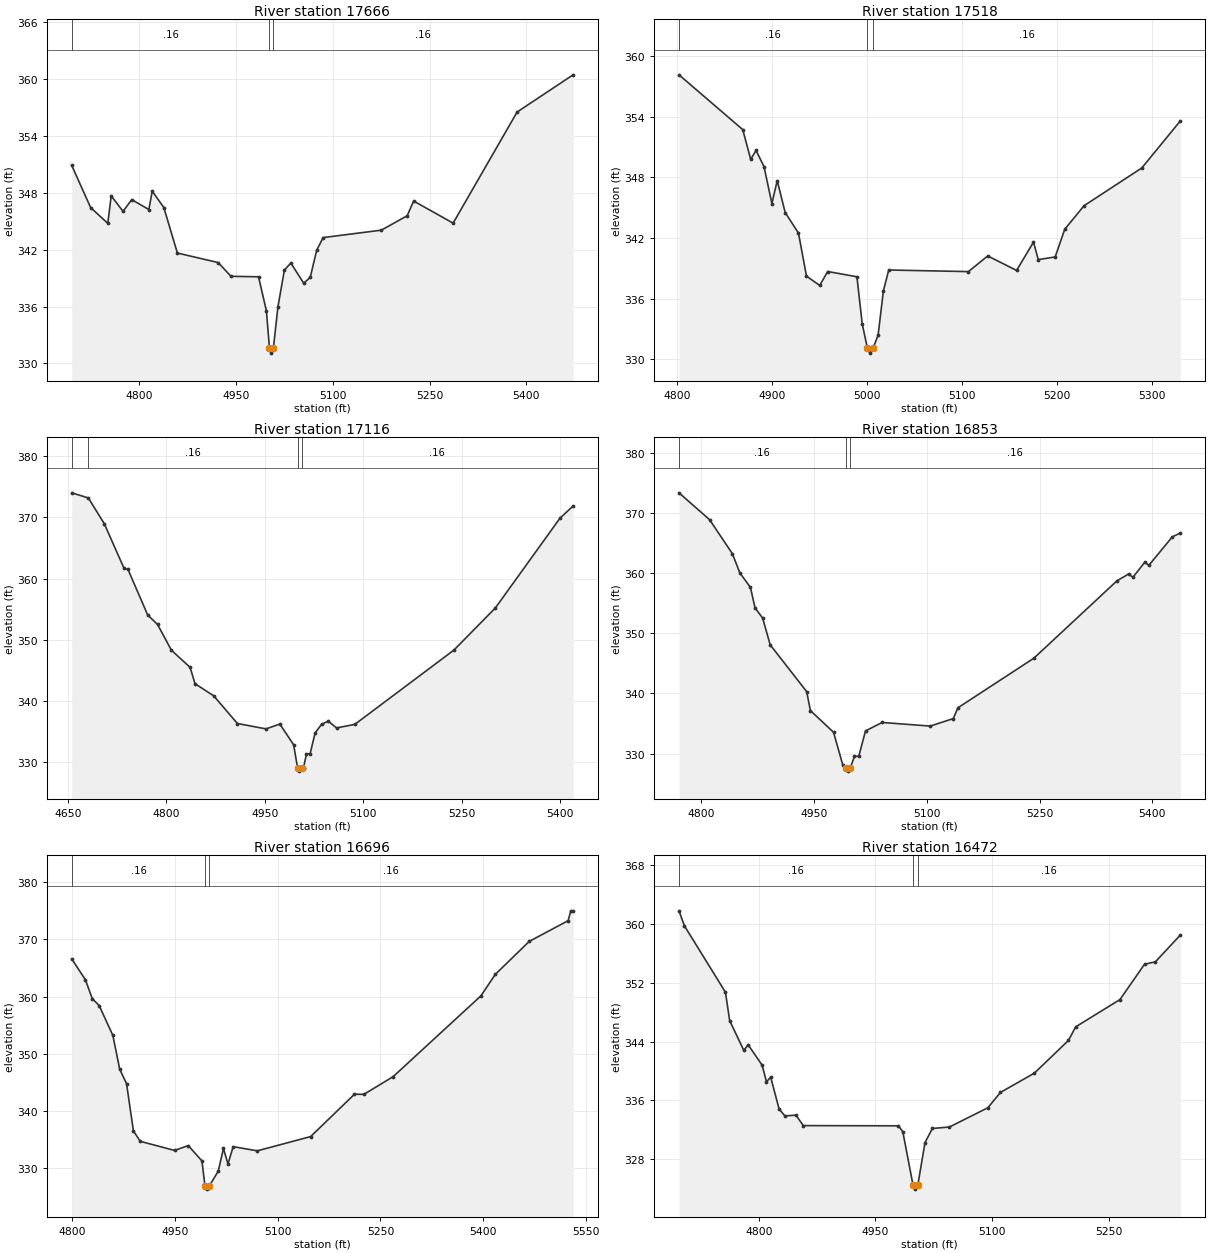
Type RM Length L Ch R = 1 ,17666   ,148,148,148
BEGIN DESCRIPTION:
Mapping XS 8cbc70e8
END DESCRIPTION:
XS GIS Cut Line= 3
      3772436.39     10592794.52      3772523.19     10593059.25
       3772557.8     10593556.75
#Sta/Elev= 30
  4695.2  350.86  4724.5  346.42  4751.1  344.76  4756.4  347.65  4774.8  346.02
  4788.2  347.26  4814.8  346.21    4820  348.15    4838  346.42    4859  341.63
  4922.2  340.63  4942.1  339.18  4984.8  339.13    4997  335.55  5001.8  331.59
  5004.6  331.09  5007.8  331.59  5014.8  335.92  5024.9  339.84  5034.9  340.58
  5054.9  338.45    5065  339.07    5075  341.93    5085  343.26  5175.2  344.04
  5215.3  345.56  5225.3  347.11  5286.5  344.78  5385.7  356.48  5472.5   360.4
#Mann= 3 ,-1 , 0
  4695.2     .16       0  5001.8     .07       0  5007.8     .16       0
Bank Sta=5001.8,5007.8
XS Rating Curve= 0 ,0
Exp/Cntr=0.3,0.1

Type RM Length L Ch R = 1 ,17518   ,402,402,402
BEGIN DESCRIPTION:
SPRING BRANCH 33.0
END DESCRIPTION:
XS GIS Cut Line= 3
       3772299.6     10592910.17      3772399.61     10593110.19
      3772449.62     10593410.23
#Sta/Elev= 30
  4801.9  358.15    4869  352.73  4877.4  349.78    4883  350.67  4891.4  349.06
  4899.7  345.41  4905.3  347.68  4913.7  344.52  4927.7  342.48  4936.1  338.22
  4950.1   337.3  4958.4  338.68  4989.2  338.16  4994.8   333.5  5000.2   331.1
  5002.9   330.6  5006.2   331.1  5011.5  332.37  5017.1  336.77  5022.7  338.83
  5106.6  338.67  5126.9  340.22  5157.3  338.79  5175.1  341.59  5180.1  339.86
  5197.9  340.12    5208  342.86  5228.3  345.19  5289.1  348.93  5329.7  353.59
#Mann= 3 ,-1 , 0
  4801.9     .16       0  5000.2     .07       0  5006.2     .16       0
Bank Sta=5000.2,5006.2
XS Rating Curve= 0 ,0
Exp/Cntr=0.3,0.1

Type RM Length L Ch R = 1 ,17116   ,263,263,263
BEGIN DESCRIPTION:
SPRING BRANCH 32.0
END DESCRIPTION:
XS GIS Cut Line= 3
       3771899.6     10592910.17      3772099.61     10593210.19
      3772149.61      10593610.2
#Sta/Elev= 30
  4655.7  374.04    4681   373.2  4705.3  368.98  4735.3  361.69  4741.4  361.48
  4771.4  354.03  4786.4  352.48  4807.5  348.26    4836  345.45  4843.5  342.78
  4872.1  340.77  4908.1  336.25  4951.7  335.37  4972.7  336.16  4993.7  332.77
  4999.8  328.95  5002.5  328.45  5005.8  328.95  5008.8     329  5013.3  331.29
  5018.8  331.29  5026.4   334.7  5036.4  336.13  5046.5  336.63  5059.1  335.53
  5086.8   336.1    5238  348.29    5301  355.18  5399.2  369.85  5419.4  371.89
#Mann= 4 ,-1 , 0
  4655.7     .05       0    4681     .16       0  4999.8     .07       0
  5005.8     .16       0
Bank Sta=4999.8,5005.8
XS Rating Curve= 0 ,0
Exp/Cntr=0.3,0.1

Type RM Length L Ch R = 1 ,16853   ,157,157,157
BEGIN DESCRIPTION:
Mapping XS 1a535a56
END DESCRIPTION:
XS GIS Cut Line= 3
       3771802.7     10592989.79      3771828.75     10593193.79
      3772067.48     10593588.79
#Sta/Elev= 30
  4770.1  373.32  4810.8  368.86  4841.1  363.22  4851.1  360.02  4865.2  357.61
  4871.3  354.21  4881.4  352.52  4891.5  348.07    4940  340.31    4945  337.15
  4975.8  333.55  4988.1  328.11  4991.9   327.6  4994.7   327.1  4997.9   327.6
  5003.6  329.54  5009.4  329.59  5018.3  333.78  5040.5  335.18  5104.5  334.58
  5135.1  335.83  5141.4  337.63  5242.3  345.85  5352.9   358.7  5368.4  359.84
  5374.2   359.3  5389.7  361.75  5395.6  361.31  5426.6  366.01  5437.3  366.65
#Mann= 3 ,-1 , 0
  4770.1     .16       0  4991.9     .07       0  4997.9     .16       0
Bank Sta=4991.9,4997.9
XS Rating Curve= 0 ,0
Exp/Cntr=0.3,0.1

Type RM Length L Ch R = 1 ,16696   ,224,224,224
BEGIN DESCRIPTION:
SPRING BRANCH 31.0
END DESCRIPTION:
XS GIS Cut Line= 3
      3771699.61     10593060.14      3771699.61     10593260.19
      3772049.64     10593660.22
#Sta/Elev= 30
  4799.6   366.6  4819.6  362.95  4829.6  359.64  4839.6  358.46  4859.6  353.24
  4869.6  347.33  4879.6   344.8  4889.6  336.56  4899.6  334.73  4949.6  333.14
  4969.6  333.98  4989.6  331.32  4994.1  326.88  4996.9  326.38  5000.1  326.88
  5013.4  329.52    5021  333.48  5027.6  330.78  5035.2   333.8  5070.4  333.07
  5148.2  335.56  5212.2  342.96    5226  342.94  5268.7  346.04  5396.9  360.17
  5417.7   363.9  5467.1  369.65    5524  373.28  5527.8     375  5531.2     375
#Mann= 3 ,-1 , 0
  4799.6     .16       0  4994.1     .07       0  5000.1     .16       0
Bank Sta=4994.1,5000.1
XS Rating Curve= 0 ,0
Exp/Cntr=0.3,0.1

Type RM Length L Ch R = 1 ,16472   ,248,248,248
BEGIN DESCRIPTION:
Mapping XS 9acefbf4
END DESCRIPTION:
XS GIS Cut Line= 3
       3771598.7      10593041.9      3771498.88     10593276.26
      3771685.08     10593618.34
#Sta/Elev= 30
  4697.6  361.79  4704.6  359.74  4757.3  350.72  4762.7  346.86  4780.9   342.8
  4786.4  343.58  4804.4   340.8    4810  338.53  4815.4  339.17  4826.2  334.85
  4833.6   333.9  4847.9     334  4857.3  332.58  4979.5  332.55  4985.2  331.74
  4998.4  324.44  5001.1  323.94  5004.4  324.44  5013.7  330.27  5023.2  332.19
  5045.1  332.39  5094.5  335.01  5110.6  337.09  5154.3  339.72    5198  344.16
  5207.3  346.01  5264.2  349.72  5295.8  354.53  5309.7  354.85  5341.8   358.5
#Mann= 3 ,-1 , 0
  4697.6     .16       0  4998.4     .07       0  5004.4     .16       0
Bank Sta=4998.4,5004.4
XS Rating Curve= 0 ,0
Exp/Cntr=0.3,0.1

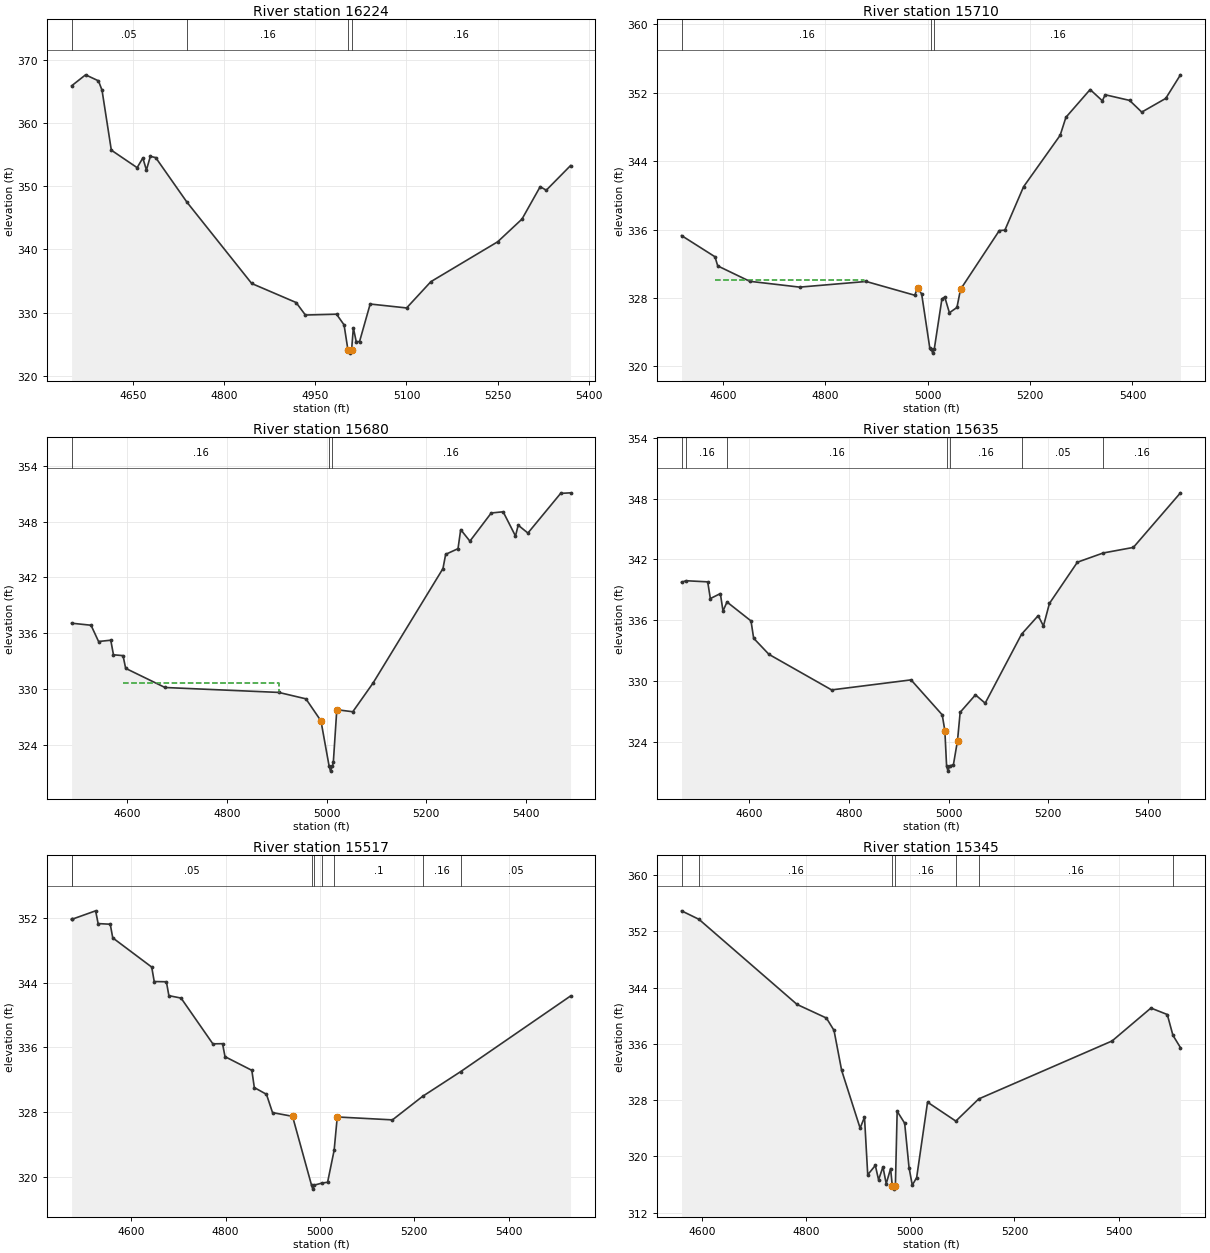
Type RM Length L Ch R = 1 ,16224   ,514,514,514
BEGIN DESCRIPTION:
SPRING BRANCH 30.0
END DESCRIPTION:
XS GIS Cut Line= 3
      3771549.59     10592910.21      3771299.61     10593310.19
      3771299.61     10593660.22
#Sta/Elev= 30
  4548.5   365.9  4571.5  367.64  4592.7  366.69  4598.6   365.2  4613.9  355.72
  4656.4  352.95  4665.8  354.48  4671.7  352.58  4678.2  354.74    4687  354.54
  4738.5  347.48  4845.1  334.62  4918.2  331.61  4933.5  329.63  4984.8  329.76
  4997.2  328.07  5003.6   324.1  5006.4   323.6  5009.6   324.1  5012.5  327.61
  5017.2  325.43  5022.7  325.43  5040.2  331.37  5100.2  330.75  5140.2  334.91
  5250.2  341.22  5290.2  344.81  5320.2  349.94  5330.2  349.38  5370.2  353.28
#Mann= 4 ,-1 , 0
  4548.5     .05       0  4738.5     .16       0  5003.6     .07       0
  5009.6     .16       0
Bank Sta=5003.6,5009.6
XS Rating Curve= 0 ,0
Exp/Cntr=0.3,0.1

Type RM Length L Ch R = 1 ,15710   ,30,30,30
BEGIN DESCRIPTION:
Mapping XS 98fdbad0
END DESCRIPTION:
XS GIS Cut Line= 2
      3771312.56     10593149.14      3770413.05      10593523.5
#Sta/Elev= 30
  4519.4  335.31  4584.7  332.83  4590.1  331.76  4652.6  329.96  4750.1  329.28
    4880  329.94  4974.8  328.33  4980.3  329.18  4988.3  328.48  5004.1  322.19
    5007  322.06  5009.8  321.56    5013  322.06  5027.9  327.91  5033.4  328.12
  5042.5  326.28  5057.2   326.9  5064.2  329.02    5140   335.9  5150.8  335.94
  5187.3  341.02  5258.8  347.04    5270  349.14  5317.3  352.39  5341.2  351.07
  5346.6  351.78  5394.3  351.12  5418.1  349.75  5464.9  351.35  5493.7  354.11
#Mann= 3 ,-1 , 0
  4519.4     .16       0    5007      .1       0    5013     .16       0
#XS Ineff= 1 ,-1
 4584.13    4875   330.1
Permanent Ineff=
       T
Bank Sta=4980.3,5064.2
XS Rating Curve= 0 ,0
Exp/Cntr=0.3,0.1

Type RM Length L Ch R = 1 ,15680   ,45,45,45
BEGIN DESCRIPTION:
Mapping XS d6a9afc9
END DESCRIPTION:
XS GIS Cut Line= 3
      3771325.98     10593125.94      3770896.32     10593293.03
      3770390.68       10593484.
#Sta/Elev= 30
    4488  337.07    4527  336.85  4542.1   335.1  4566.6  335.24    4572  333.67
  4591.2  333.58  4596.5  332.21  4675.5  330.15  4903.8  329.62  4958.3  328.93
  4988.5  326.56    5005  321.65  5007.7  321.15    5011  321.65  5013.3  322.08
  5020.3  327.76  5052.4  327.54  5093.2  330.64  5233.4  342.95  5238.8  344.48
  5263.6  345.09    5269  347.14  5287.5   345.9  5330.3  348.93  5354.2  349.06
    5379  346.45  5384.4  347.62  5403.9  346.77  5469.6  351.04  5489.5   351.1
#Mann= 3 ,-1 , 0
    4488     .16       0    5005      .1       0    5011     .16       0
#XS Ineff= 1 ,-1
 4591.83    4905  330.65
Permanent Ineff=
       T
Bank Sta=4988.5,5020.3
XS Rating Curve= 0 ,0
Exp/Cntr=0.3,0.1

Type RM Length L Ch R = 1 ,15635   ,118,118,118
BEGIN DESCRIPTION:
SPRING BRANCH 29.0
END DESCRIPTION:
XS GIS Cut Line= 2
      3771322.97     10593097.06      3770380.88     10593435.38
#Sta/Elev= 30
  4464.2  339.74    4473   339.9  4516.7  339.79    4522  338.14  4542.1  338.63
  4547.4  336.91  4555.4   337.8  4603.6  335.93  4608.9  334.22  4639.6  332.63
  4765.3  329.12  4924.7  330.11  4987.2  326.66  4992.5   325.1    4996   321.6
  4998.8   321.1    5002   321.6  5009.7  321.74  5017.9  324.12  5023.2  326.91
  5053.9  328.63  5073.4  327.81  5146.4  334.62  5179.7  336.45  5190.3  335.43
  5202.3  337.66  5258.4  341.73  5310.2  342.64  5370.7  343.19  5465.2  348.58
#Mann= 7 ,-1 , 0
  4464.2     .16       0    4473     .16       0  4555.4     .16       0
    4996     .08       0    5002     .16       0  5146.4     .05       0
  5310.2     .16       0
#XS Ineff= 1 ,-1
 4627.54 4911.08  329.42
Permanent Ineff=
       T
Bank Sta=4992.5,5017.9
XS Rating Curve= 0 ,0
Exp/Cntr=0.3,0.1

Type RM Length L Ch R = 1 ,15517   ,172,172,172
BEGIN DESCRIPTION:
Mapping XS a67fc3d5
END DESCRIPTION:
XS GIS Cut Line= 2
      3771291.72      10592998.1      3770293.17     10593346.55
#Sta/Elev= 30
  4473.5  351.88  4474.1  351.88  4524.4  352.93  4529.7  351.35  4555.4  351.27
  4560.7  349.58  4643.3  345.96  4648.6  344.17  4674.4  344.14  4679.7  342.42
  4705.5  342.12  4772.9  336.45  4793.4  336.47  4798.7  334.86  4855.5  333.17
  4860.8  331.03  4886.5   330.2  4899.4  327.93  4941.8  327.47    4982  318.95
  4984.8  318.45    4988  318.95    5005  319.21  5016.1   319.3    5030  323.27
  5036.6  327.39  5153.6  327.03  5217.4  329.94  5298.2  333.01  5531.1  342.38
#Mann= 8 ,-1 , 0
  4473.5     .16       0  4474.1     .05       0    4982     .04       0
    4988     .05       0    5005     .16       0    5030      .1       0
  5217.4     .16       0  5298.2     .05       0
Bank Sta=4941.8,5036.6
XS Rating Curve= 0 ,0
Exp/Cntr=0.3,0.1

Type RM Length L Ch R = 1 ,15345   ,279,279,279
BEGIN DESCRIPTION:
Mapping XS 09ec9c07
END DESCRIPTION:
XS GIS Cut Line= 3
      3771052.15     10592862.68      3770609.44      10593190.8
      3770225.78      10593325.6
#Sta/Elev= 30
  4561.1  354.92  4594.6  353.71  4782.9  341.61  4839.2  339.68  4853.8  337.92
  4868.4  332.25  4903.9  324.03  4912.3  325.59  4918.5   317.4  4933.1  318.73
  4939.3  316.68  4947.7  318.52    4954  316.13  4962.4  318.28  4965.6  315.86
  4968.3  315.36  4971.6  315.86    4975  326.43  4989.4  324.73  4997.8  318.42
    5004  315.93  5012.4  316.99  5033.3  327.72  5087.6  325.03  5131.5  328.18
  5387.5  336.42  5462.1   341.1  5493.5  340.18  5504.3  337.23  5518.8  335.47
#Mann= 7 ,-1 , 0
  4561.1     .05       0  4594.6     .16       0  4965.6     .07       0
  4971.6     .16       0  5087.6     .05       0  5131.5     .16       0
  5504.3     .05       0
Bank Sta=4965.6,4971.6
XS Rating Curve= 0 ,0
Exp/Cntr=0.3,0.1

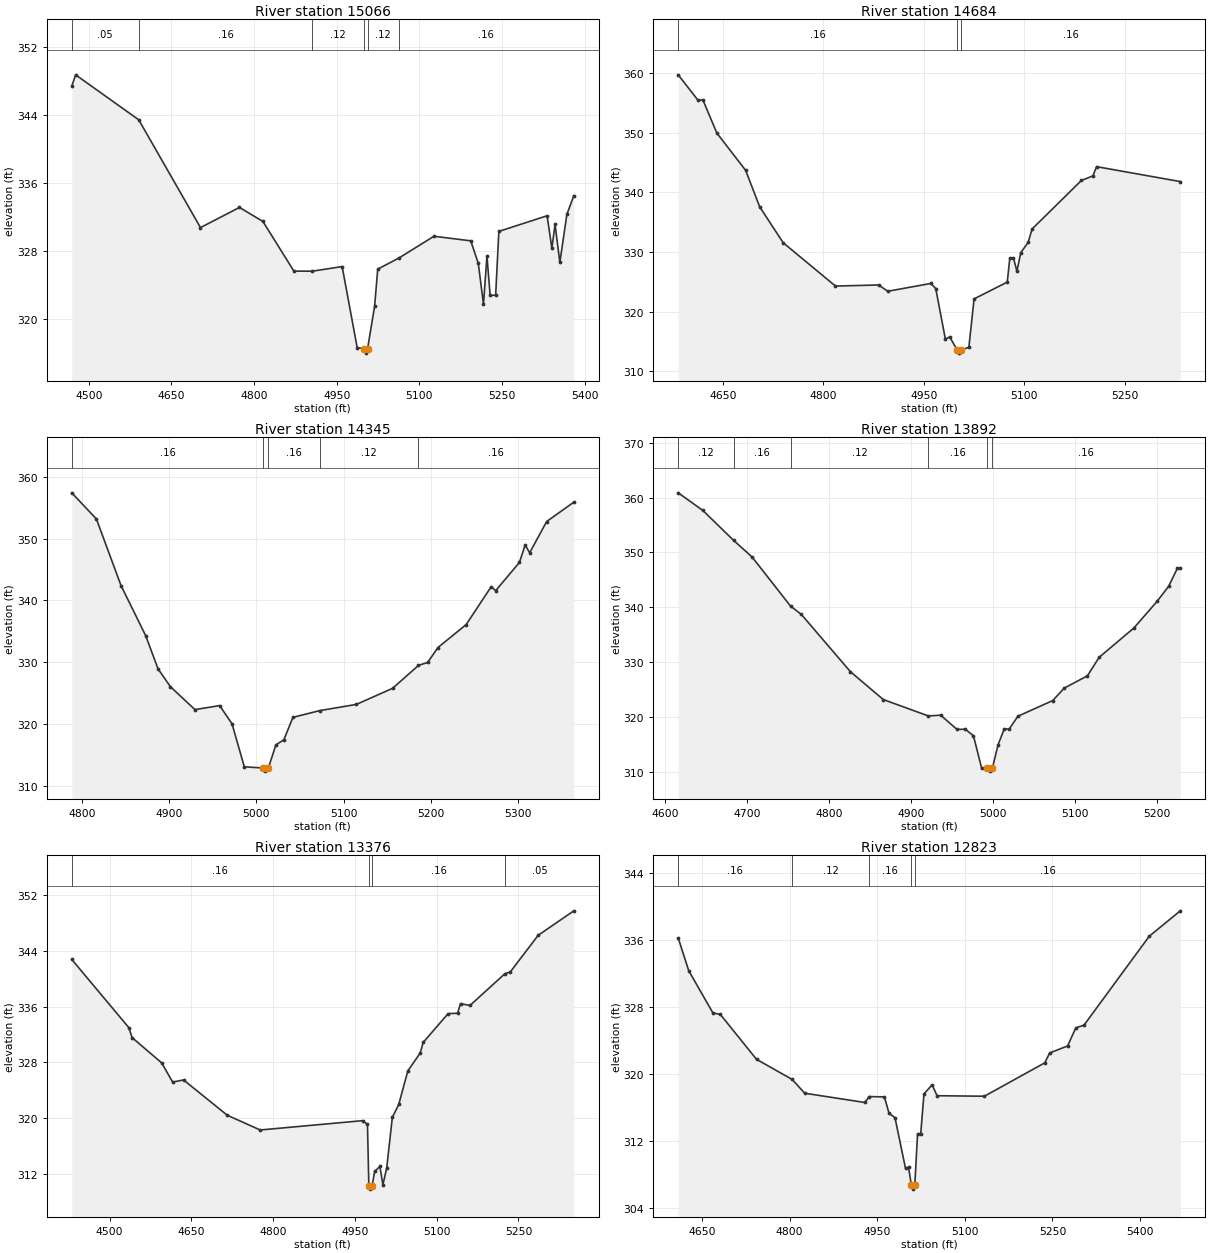
Type RM Length L Ch R = 1 ,15066   ,382,382,382
BEGIN DESCRIPTION:
SPRING BRANCH 28.0
END DESCRIPTION:
XS GIS Cut Line= 3
      3770895.91     10592706.42      3770593.82     10593029.35
      3770187.58     10593263.71
#Sta/Elev= 30
  4469.1   347.4  4476.1  348.75  4590.6  343.46  4702.7  330.78  4773.5  333.15
    4816   331.5  4872.2  325.66  4905.5  325.65  4959.8  326.19  4987.1  316.66
  4999.9  316.51  5002.6  316.01  5005.9  316.51  5018.7  321.51  5024.4  325.89
  5062.6  327.19  5126.4  329.76  5193.2  329.22  5206.9  326.56  5216.3  321.76
  5222.6  327.42  5228.4   322.8  5238.4  322.83  5244.2  330.33  5331.8  332.17
  5340.4  328.34  5346.2  331.15  5354.9  326.69  5367.7  332.34  5380.3  334.54
#Mann= 6 ,-1 , 0
  4469.1     .05       0  4590.6     .16       0  4905.5     .12       0
  4999.9     .07       0  5005.9     .12       0  5062.6     .16       0
Bank Sta=4999.9,5005.9
XS Rating Curve= 0 ,0
Exp/Cntr=0.3,0.1

Type RM Length L Ch R = 1 ,14684   ,339,339,339
BEGIN DESCRIPTION:
SPRING BRANCH 27.0
END DESCRIPTION:
XS GIS Cut Line= 3
      3770661.55     10592440.77      3770343.82     10592821.01
      3770114.69     10592930.37
#Sta/Elev= 30
  4583.3  359.68  4612.4  355.48  4620.2  355.45    4641  349.91    4684  343.66
  4704.8  337.57    4740  331.53    4818  324.28  4882.3  324.46  4896.1  323.41
  4960.5  324.72  4967.7  323.85    4982   315.4  4988.5  315.75  4999.8  313.54
  5002.6  313.04  5005.8  313.54  5017.1  314.03  5024.9  322.13  5074.4  324.94
  5078.2  328.96  5083.7  328.96  5088.8  326.77  5094.6  329.89  5105.6  331.59
  5111.5  333.85  5185.1  341.98  5202.2  342.74  5207.7  344.29  5332.7  341.79
#Mann= 3 ,-1 , 0
  4583.3     .16       0  4999.8     .07       0  5005.8     .16       0
Bank Sta=4999.8,5005.8
XS Rating Curve= 0 ,0
Exp/Cntr=0.3,0.1

Type RM Length L Ch R = 1 ,14345   ,453,453,453
BEGIN DESCRIPTION:
SPRING BRANCH 26.0
END DESCRIPTION:
XS GIS Cut Line= 3
      3770449.63     10592360.17      3770299.61     10592510.19
      3769949.57      10592610.2
#Sta/Elev= 30
  4788.1  357.38  4816.4  353.15  4844.7  342.38    4873   334.3  4887.1  328.96
  4901.3  326.08  4929.5  322.38  4957.8  323.03    4972  320.09  4986.1  313.15
  5007.7  312.95  5010.4  312.45  5013.7  312.95  5022.4   316.7  5031.5  317.51
  5041.9  321.13    5073  322.23  5114.7  323.22  5156.3  325.82    5186  329.52
  5196.6     330  5208.3   332.4  5240.8  336.12  5269.4  342.22  5274.6  341.59
  5301.9  346.15  5308.4  348.96  5313.6   347.7  5333.1  352.75  5364.3  355.87
#Mann= 5 ,-1 , 0
  4788.1     .16       0  5007.7     .07       0  5013.7     .16       0
    5073     .12       0    5186     .16       0
Bank Sta=5007.7,5013.7
XS Rating Curve= 0 ,0
Exp/Cntr=0.3,0.1

Type RM Length L Ch R = 1 ,13892   ,516,516,516
BEGIN DESCRIPTION:
SPRING BRANCH 25.0
END DESCRIPTION:
XS GIS Cut Line= 3
      3770399.65     10592210.19      3769999.61     10592210.19
      3769849.59     10592360.21
#Sta/Elev= 30
  4615.8  360.87  4645.8  357.66  4683.2  352.22  4705.8  349.18  4752.7  340.23
  4765.8  338.72  4825.8  328.26  4865.8  323.19  4920.8   320.2  4935.8  320.34
  4955.8  317.73  4965.8  317.79  4975.8  316.57  4985.8  310.65  4992.8  310.64
  4995.6  310.14  4998.8  310.64  5005.8  314.95  5013.3  317.82  5019.4  317.82
    5030  320.15  5072.4     323  5086.5  325.27  5114.8  327.52    5129  330.88
  5171.4  336.23  5199.7  341.09  5213.8  343.84  5224.4  347.11    5228  347.11
#Mann= 6 ,-1 , 0
  4615.8     .12       0  4683.2     .16       0  4752.7     .12       0
  4920.8     .16       0  4992.8     .07       0  4998.8     .16       0
Bank Sta=4992.8,4998.8
XS Rating Curve= 0 ,0
Exp/Cntr=0.3,0.1

Type RM Length L Ch R = 1 ,13376   ,553,553,553
BEGIN DESCRIPTION:
SPRING BRANCH 24.0
END DESCRIPTION:
XS GIS Cut Line= 3
      3770343.85     10591794.97      3769890.69     10591836.64
      3769468.79     10592034.57
#Sta/Elev= 30
  4430.5  342.79  4535.2     333  4541.2  331.57  4595.4  327.95  4615.5  325.19
  4635.6  325.49  4715.9  320.42  4776.2  318.31  4964.1  319.65    4973  319.11
  4975.5  310.32  4978.3  309.82  4981.5  310.32  4986.2  312.36  4995.8  313.08
  5001.3  310.45  5008.3  312.86  5018.6  320.12  5030.4  321.98    5047  326.79
  5069.8  329.36  5075.3  330.89  5120.9  335.01  5138.2  335.07  5143.8  336.45
    5161  336.18  5224.9  340.73    5235     341  5286.2  346.26  5351.6  349.77
#Mann= 4 ,-1 , 0
  4430.5     .16       0  4975.5     .07       0  4981.5     .16       0
  5224.9     .05       0
Bank Sta=4975.5,4981.5
XS Rating Curve= 0 ,0
Exp/Cntr=0.3,0.1

Type RM Length L Ch R = 1 ,12823   ,317,317,317
BEGIN DESCRIPTION:
SPRING BRANCH 23.0
END DESCRIPTION:
XS GIS Cut Line= 3
      3770249.59     10591610.18      3769849.61     10591510.19
      3769449.62     10591710.18
#Sta/Elev= 30
  4609.4  336.22  4627.4  332.31  4668.7  327.28  4681.5  327.09  4743.4  321.73
  4804.5  319.32  4825.8  317.68  4928.9  316.57  4936.1  317.28  4962.4  317.24
  4970.2  315.29  4980.5  314.75  4998.5  308.69  5003.7  308.85  5008.4  306.72
  5011.1  306.22  5014.4  306.72  5019.1  312.84  5024.5  312.84  5030.1   317.6
  5044.1  318.69  5052.4  317.38  5133.5  317.32  5236.9  321.31  5245.3  322.49
    5276  323.33    5290  325.49    5304  325.81  5415.8  336.44  5468.9  339.47
#Mann= 5 ,-1 , 0
  4609.4     .16       0  4804.5     .12       0  4936.1     .16       0
  5008.4     .07       0  5014.4     .16       0
Bank Sta=5008.4,5014.4
XS Rating Curve= 0 ,0
Exp/Cntr=0.3,0.1

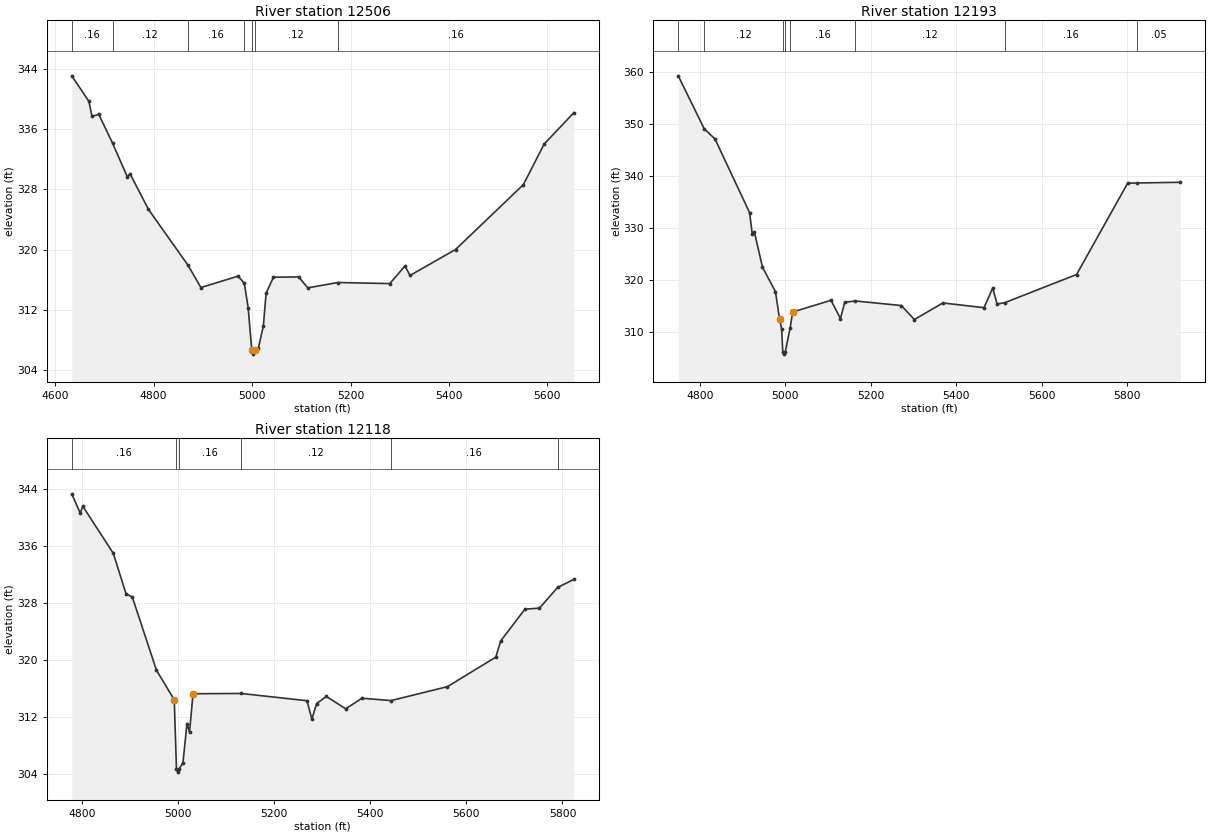
Type RM Length L Ch R = 1 ,12506   ,313,313,313
BEGIN DESCRIPTION:
SPRING BRANCH 22.0
END DESCRIPTION:
XS GIS Cut Line= 3
      3770303.96     10591330.98      3769988.03     10591287.58
      3769305.77     10591449.04
#Sta/Elev= 30
  4633.7  343.11  4668.4  339.73  4674.8  337.74  4688.6  337.97  4716.7  334.14
  4746.9  329.63    4752   330.1  4789.5  325.35  4869.4  317.97  4896.1  314.96
  4971.5  316.48  4984.3  315.53  4992.1  312.25  4999.4  306.61  5002.1  306.11
  5005.4  306.61  5012.6  306.86  5022.9  309.85  5028.5  314.21  5043.5  316.34
  5094.8  316.37  5113.1  314.92  5174.3  315.63  5279.8  315.49  5310.6  317.83
  5320.9  316.57  5413.4  320.02  5551.1  328.64  5593.4  334.04  5653.7  338.21
#Mann= 7 ,-1 , 0
  4633.7     .16       0  4716.7     .12       0  4869.4     .16       0
  4984.3     .12       0  4999.4     .07       0  5005.4     .12       0
  5174.3     .16       0
Bank Sta=4999.4,5005.4
XS Rating Curve= 0 ,0
Exp/Cntr=0.3,0.1

Type RM Length L Ch R = 1 ,12193   ,75,75,75
BEGIN DESCRIPTION:
Mapping XS c8be5bfb
END DESCRIPTION:
XS GIS Cut Line= 3
      3770334.73     10591129.06      3770024.88     10591175.92
      3769178.51     10591342.59
#Sta/Elev= 30
    4749  359.29    4810  349.08  4835.1  347.15    4916     333  4922.4   328.9
  4927.4  329.25  4946.3   322.5  4976.7   317.8  4986.2   312.6  4991.2  310.61
  4993.9  306.28  4996.7  305.78  4999.9  306.28  5011.2  310.87  5017.1  313.88
  5106.9  316.13  5128.9  312.62  5139.1  315.75  5164.1     316  5271.6  315.12
  5302.2  312.43  5368.8  315.62  5465.2  314.71  5485.6   318.5  5495.8  315.42
  5513.8  315.67    5682  321.09  5801.6  338.64  5823.3  338.69    5925  338.82
#Mann= 8 ,-1 , 0
    4749     .16       0    4810     .12       0  4993.9     .07       0
  4999.9     .12       0  5011.2     .16       0  5164.1     .12       0
  5513.8     .16       0  5823.3     .05       0
Bank Sta=4986.2,5017.1
XS Rating Curve= 0 ,0
Exp/Cntr=0.3,0.1

Type RM Length L Ch R = 1 ,12118   ,443,443,443
BEGIN DESCRIPTION:
Mapping XS b5830df3
END DESCRIPTION:
XS GIS Cut Line= 3
      3770269.33     10591029.02      3769911.72     10591147.06
      3769248.52      10591230.4
#Sta/Elev= 30
  4778.7  343.36  4796.3  340.65  4801.6  341.62  4865.1     335  4891.5  329.34
  4904.8  328.82    4955  318.56    4992   314.4  4996.6  304.73  4999.3  304.23
  5002.6  304.73  5010.1  305.57  5018.5  311.04  5023.8  309.88  5031.1  315.25
  5131.5  315.29  5268.3  314.27  5278.4  311.68  5288.4  313.87  5308.6  314.87
  5348.9  313.13  5382.5  314.62  5443.1  314.29  5560.6  316.25  5661.3   320.4
  5671.4  322.67  5721.8  327.14  5752.1  327.29  5789.9   330.2  5823.7  331.33
#Mann= 6 ,-1 , 0
  4778.7     .16       0  4996.6     .07       0  5002.6     .16       0
  5131.5     .12       0  5443.1     .16       0  5789.9     .05       0
Bank Sta=4992,5031.1
XS Rating Curve= 0 ,0
Exp/Cntr=0.3,0.1