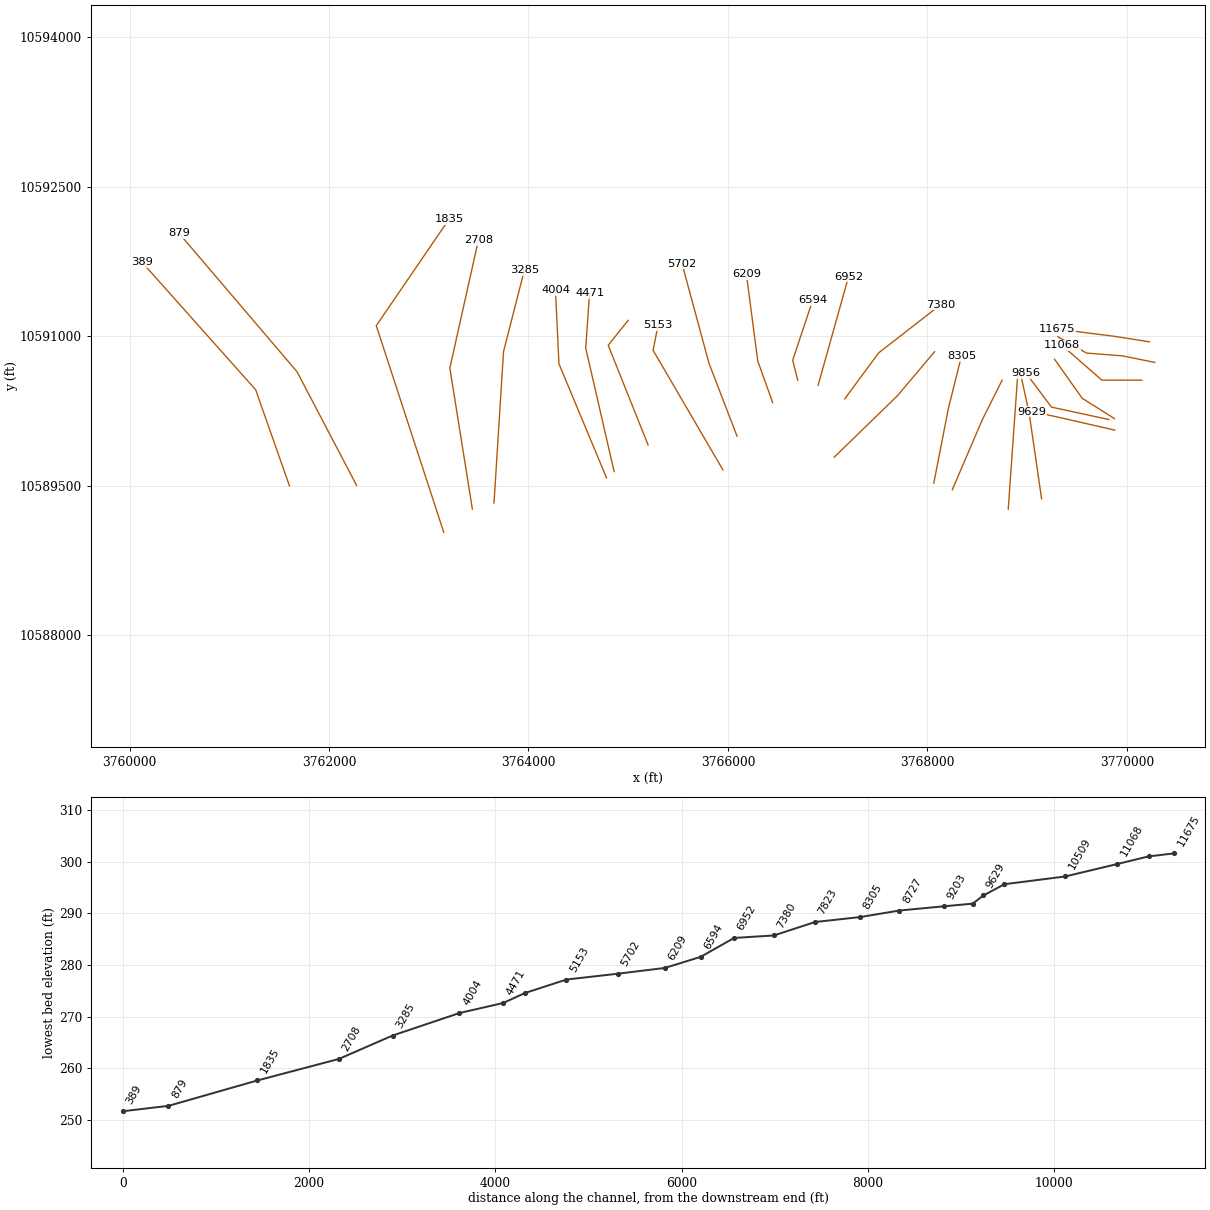
HEC-RAS study SPRING BRANCH.prj: SPRING BRANCH Base Level Engineering

--- SPRING BRANCH.g01 (geometry) --- (continued)

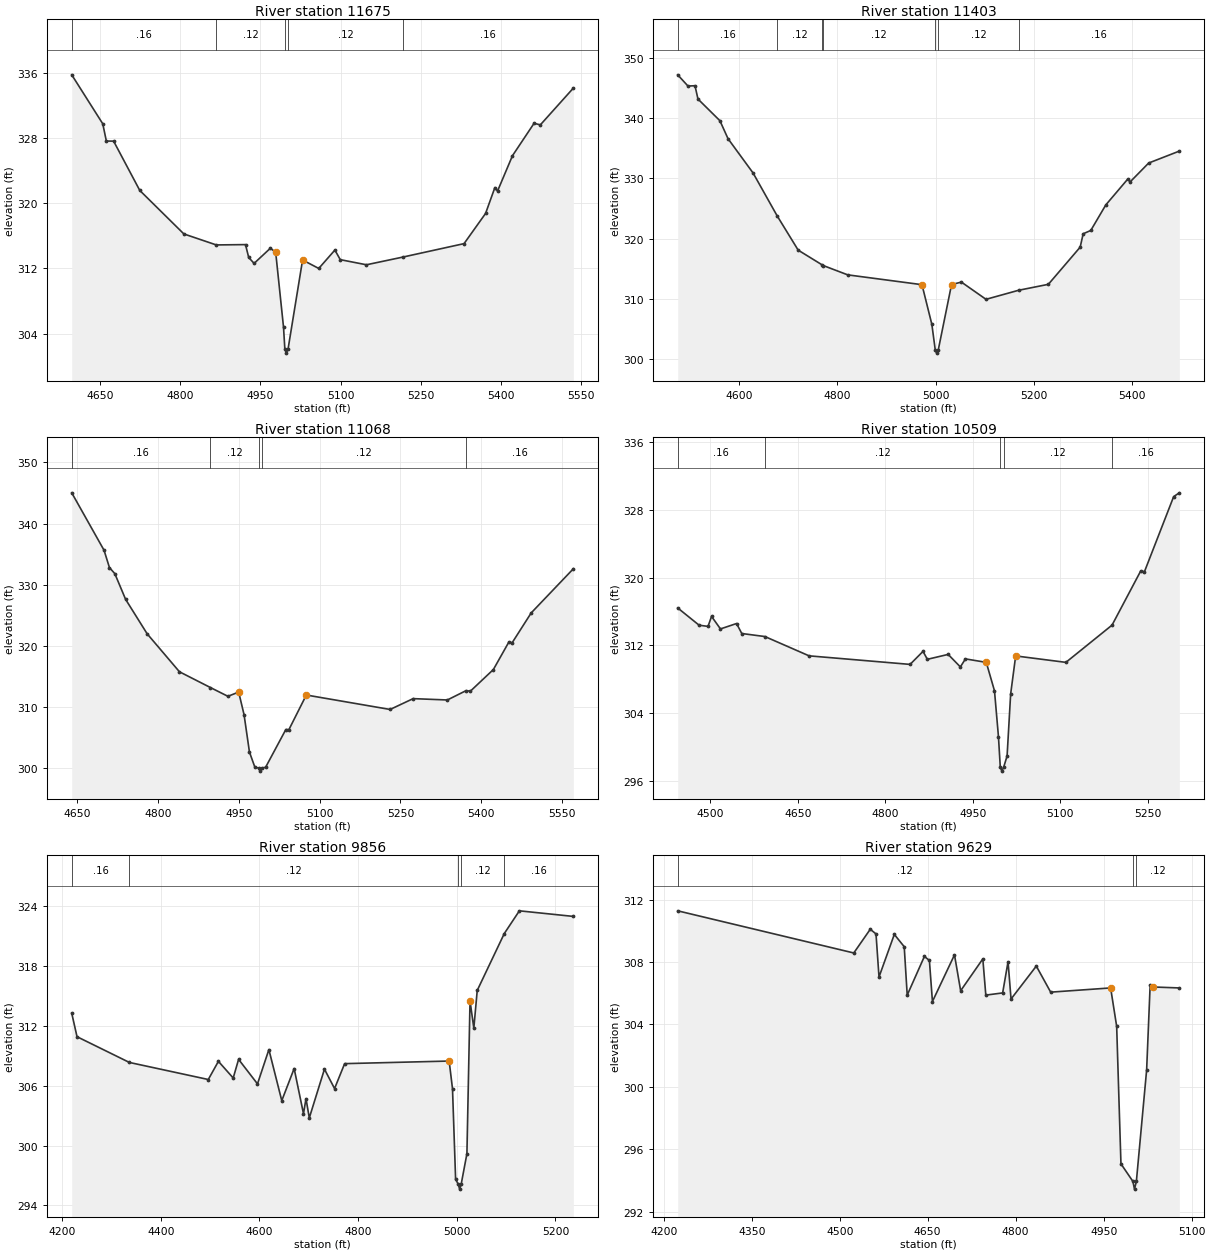
Type RM Length L Ch R = 1 ,11675   ,272,272,272
BEGIN DESCRIPTION:
SPRING BRANCH 21.0
END DESCRIPTION:
XS GIS Cut Line= 3
      3770227.03     10590944.91      3769872.91     10591000.45
      3769296.55     10591073.37
#Sta/Elev= 30
  4596.6   335.8  4654.7  329.78  4661.4  327.66    4675  327.65    4724  321.59
  4806.6  316.24  4867.3  314.89    4922  314.93    4928  313.35  4938.1  312.62
  4968.5  314.48  4978.5     314  4993.2  304.78  4995.7  302.09  4998.4  301.59
  5001.7  302.09  5028.9  313.04  5059.2     312  5089.4  314.26  5099.5  313.08
  5148.5  312.45  5216.9   313.4  5331.3  315.05  5371.6  318.76    5389  321.94
    5394  321.51    5422  325.86  5462.4  329.84  5474.2  329.65    5536  334.17
#Mann= 5 ,-1 , 0
  4596.6     .16       0  4867.3     .12       0  4995.7     .07       0
  5001.7     .12       0  5216.9     .16       0
Bank Sta=4978.5,5028.9
XS Rating Curve= 0 ,0
Exp/Cntr=0.3,0.1

Type RM Length L Ch R = 1 ,11403   ,335,335,335
BEGIN DESCRIPTION:
Mapping XS b44de5c8
END DESCRIPTION:
XS GIS Cut Line= 4
      3770280.13     10590738.42      3769957.18     10590803.53
       3769595.2     10590832.17      3769309.67      10590995.7
#Sta/Elev= 30
  4474.6   347.2  4495.5  345.34  4509.8  345.39  4515.9  343.18  4560.6  339.58
  4577.1   336.6  4628.1  330.91  4677.3  323.77    4720   318.1  4769.3  315.63
  4770.9  315.55  4820.9     314  4972.1  312.37  4992.2  305.79  4999.2  301.51
    5002  301.01  5005.2  301.51  5032.3  312.39  5052.4   312.8  5102.5  309.94
  5168.8  311.44  5229.5  312.43  5294.3   318.6  5300.4  320.82  5315.9  321.37
  5346.5  325.61  5390.7  329.85  5396.4  329.46  5433.8  332.56  5496.2  334.54
#Mann= 7 ,-1 , 0
  4474.6     .16       0  4677.3     .12       0  4769.3     .16       0
  4770.9     .12       0  4999.2     .07       0  5005.2     .12       0
  5168.8     .16       0
Bank Sta=4972.1,5032.3
XS Rating Curve= 0 ,0
Exp/Cntr=0.3,0.1

Type RM Length L Ch R = 1 ,11068   ,559,559,559
BEGIN DESCRIPTION:
SPRING BRANCH 20.0
END DESCRIPTION:
XS GIS Cut Line= 3
       3770149.6     10590560.19      3769749.61     10590560.19
      3769349.61     10590910.19
#Sta/Elev= 30
  4639.6  345.03  4699.6  335.64  4709.6  332.81  4719.6  331.82  4739.6  327.62
  4779.6  321.99  4839.6  315.78  4897.2   313.2  4929.6  311.77  4949.6  312.46
  4959.6  308.76  4969.6  302.66  4979.6   300.2  4986.6  300.04  4989.3  299.54
  4992.6  300.04  4999.6  300.17  5037.1  306.33  5042.9  306.33  5075.2  311.98
  5230.8  309.62  5273.6  311.39  5337.1  311.17  5371.7  312.69  5379.9  312.61
  5422.6  316.15    5451  320.59  5457.7  320.56  5492.8   325.4  5571.1  332.62
#Mann= 5 ,-1 , 0
  4639.6     .16       0  4897.2     .12       0  4986.6     .07       0
  4992.6     .12       0  5371.7     .16       0
Bank Sta=4949.6,5075.2
XS Rating Curve= 0 ,0
Exp/Cntr=0.3,0.1

Type RM Length L Ch R = 1 ,10509   ,653,653,653
BEGIN DESCRIPTION:
SPRING BRANCH 19.0
END DESCRIPTION:
XS GIS Cut Line= 3
      3769875.04      10590175.2      3769552.15      10590378.3
      3769276.09     10590768.95
#Sta/Elev= 30
  4444.1  316.41  4480.8  314.37  4496.1  314.23  4502.1  315.41  4517.4  313.93
    4545  314.57  4553.9  313.39  4593.6  313.03  4669.3  310.75  4842.4  309.74
  4864.6  311.28    4872  310.34  4907.7  310.92  4928.6  309.44  4937.3  310.39
    4973  309.98  4987.1  306.62  4993.9   301.2    4997  297.63  4999.7  297.13
    5003  297.63  5008.7  298.92  5014.8  306.24  5023.4  310.74  5109.5  309.98
  5188.6  314.38  5237.6  320.76  5244.2   320.7  5294.2  329.56  5303.9  330.01
#Mann= 5 ,-1 , 0
  4444.1     .16       0  4593.6     .12       0    4997     .07       0
    5003     .12       0  5188.6     .16       0
Bank Sta=4973,5023.4
XS Rating Curve= 0 ,0
Exp/Cntr=0.3,0.1

Type RM Length L Ch R = 1 ,9856    ,227,227,227
BEGIN DESCRIPTION:
Mapping XS f674c4ac
END DESCRIPTION:
XS GIS Cut Line= 3
      3769820.07      10590164.9      3769243.66     10590289.91
      3768988.48     10590631.88
#Sta/Elev= 30
  4219.7  313.26  4230.4  310.91  4336.5  308.33  4496.4  306.62  4516.9  308.44
  4546.9  306.77  4557.8  308.64  4596.1  306.18  4619.2  309.62  4645.3   304.5
  4670.4  307.72  4689.3  303.19  4694.4   304.7  4701.1  302.77  4731.8  307.66
  4752.3  305.71  4772.7  308.21  4984.5  308.47  4991.3  305.69  4997.6  296.61
  5002.9  296.13  5005.7  295.63  5008.9  296.13  5020.5  299.18  5026.8   314.5
  5034.5  311.77  5041.4  315.55  5096.2  321.25  5126.8  323.53  5236.2  322.97
#Mann= 5 ,-1 , 0
  4219.7     .16       0  4336.5     .12       0  5002.9     .07       0
  5008.9     .12       0  5096.2     .16       0
Bank Sta=4984.5,5026.8
XS Rating Curve= 0 ,0
Exp/Cntr=0.3,0.1

Type RM Length L Ch R = 1 ,9629    ,114,114,114
BEGIN DESCRIPTION:
SPRING BRANCH 18.0
END DESCRIPTION:
XS GIS Cut Line= 3
      3769879.68     10590058.88      3769287.12     10590194.22
      3769045.06     10590245.27
#Sta/Elev= 30
  4223.8  311.28    4524  308.58  4552.1   310.1  4561.9   309.8    4567  307.04
  4593.1  309.77    4610  308.98  4615.1  305.88  4644.4  308.36  4652.9   308.1
  4658.1  305.47  4695.7  308.46  4706.2  306.16    4744   308.2  4749.1  305.88
  4777.8  306.02    4787  308.02  4792.1  305.63  4835.2  307.74  4859.7  306.07
  4961.9  306.34  4972.2  303.88  4979.5  295.07  4999.8  293.95  5002.6  293.45
  5005.8  293.95  5023.3  301.09  5029.3  306.54  5034.4   306.4    5079  306.34
#Mann= 3 ,-1 , 0
  4223.8     .12       0  4999.8     .07       0  5005.8     .12       0
Bank Sta=4961.9,5034.4
XS Rating Curve= 0 ,0
Exp/Cntr=0.3,0.1

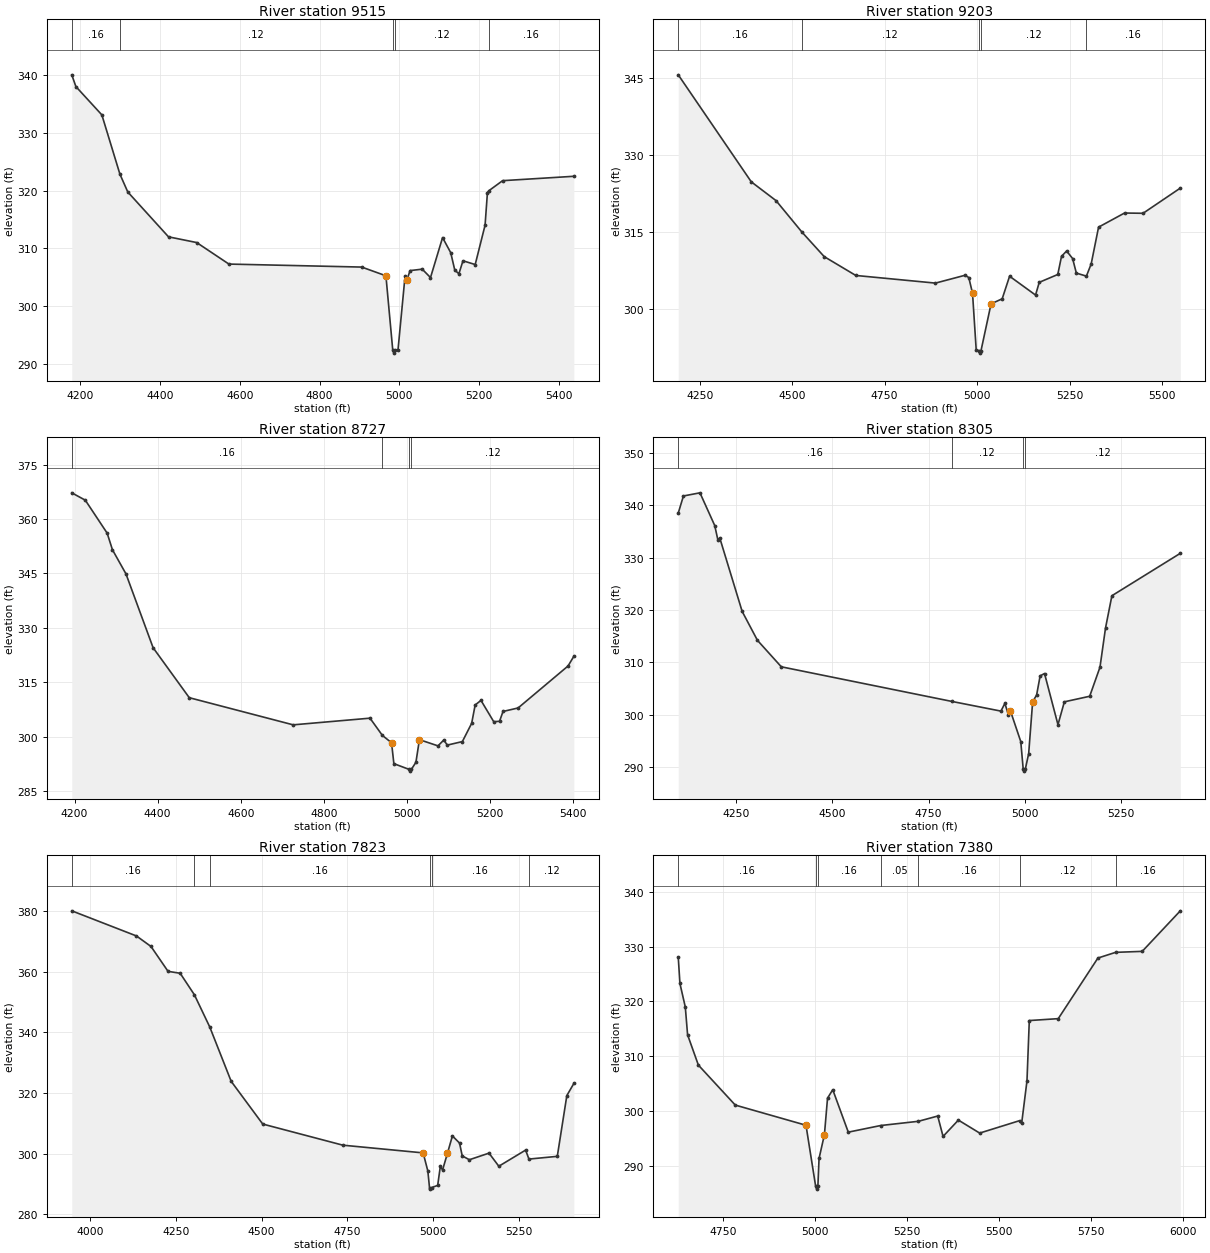
Type RM Length L Ch R = 1 ,9515    ,312,312,312
BEGIN DESCRIPTION:
SPRING BRANCH 17.0
END DESCRIPTION:
XS GIS Cut Line= 3
       3769145.4     10589369.92      3769020.39     10590229.32
      3768937.06     10590612.11
#Sta/Elev= 30
  4178.1  340.09  4188.5  338.05  4253.6  333.15    4299  322.87  4318.7  319.79
  4420.9  312.02  4491.6  311.03  4572.5   307.3  4905.9  306.78  4966.6  305.27
  4983.8  292.37  4986.5  291.87  4989.8  292.37  4996.9   292.4  5014.6  305.18
  5019.7  304.62  5027.2  306.17  5057.7  306.42  5078.5  304.96  5108.8  311.89
  5129.3  309.27  5139.5  306.24  5149.8  305.62    5160  307.87  5190.7  307.22
  5215.5  314.04  5221.4  319.69    5225  320.01  5259.5  321.75  5438.3  322.51
#Mann= 5 ,-1 , 0
  4178.1     .16       0    4299     .12       0  4983.8     .07       0
  4989.8     .12       0    5225     .16       0
Bank Sta=4966.6,5019.7
XS Rating Curve= 0 ,0
Exp/Cntr=0.3,0.1

Type RM Length L Ch R = 1 ,9203    ,476,476,476
BEGIN DESCRIPTION:
SPRING BRANCH 16.0
END DESCRIPTION:
XS GIS Cut Line= 2
      3768810.83     10589266.48      3768906.31     10590620.62
#Sta/Elev= 30
  4191.9   345.6  4389.4  324.74  4456.3  321.08  4526.3  314.95  4586.6  310.16
    4672  306.49  4887.3     305  4967.5  306.53  4977.5  306.08  4987.6  303.03
  4997.6  291.92  5004.6  291.85  5007.4  291.35  5010.6  291.85  5037.7  300.96
  5067.8  301.94  5087.8  306.34    5158  302.67    5168  305.15  5218.1  306.68
  5228.2  310.22    5242  311.26  5258.2  309.79  5268.3  306.95  5295.5  306.36
  5308.4  308.73  5328.4  315.91  5398.6  318.66  5448.7  318.61  5549.4  323.52
#Mann= 5 ,-1 , 0
  4191.9     .16       0  4526.3     .12       0  5004.6     .07       0
  5010.6     .12       0  5295.5     .16       0
Bank Sta=4987.6,5037.7
XS Rating Curve= 0 ,0
Exp/Cntr=0.3,0.1

Type RM Length L Ch R = 1 ,8727    ,422,422,422
BEGIN DESCRIPTION:
SPRING BRANCH 15.0
END DESCRIPTION:
XS GIS Cut Line= 3
      3768249.62     10589460.21      3768549.61     10590160.19
      3768749.62     10590560.21
#Sta/Elev= 30
  4193.3  367.21  4225.9  365.18  4278.5   356.1  4291.2  351.53  4323.8  344.88
  4389.1  324.54  4476.2  310.77  4726.4  303.29  4911.3  305.13  4941.2  300.37
  4963.2  298.36  4968.8   292.6    5005  291.04  5007.7  290.54    5011  291.04
  5021.9  292.98  5030.3  299.21    5075   297.5    5089  299.11  5097.4  297.71
  5133.7  298.68  5156.1  303.71  5164.5  308.76  5178.5  310.03  5209.2  304.16
  5223.2  304.27  5231.6  306.98  5267.9  307.94  5388.1   319.5  5402.1  322.17
#Mann= 4 ,-1 , 0
  4193.3     .16       0  4941.2     .12       0    5005     .07       0
    5011     .12       0
Bank Sta=4963.2,5030.3
XS Rating Curve= 0 ,0
Exp/Cntr=0.3,0.1

Type RM Length L Ch R = 1 ,8305    ,482,482,482
BEGIN DESCRIPTION:
SPRING BRANCH 14.0
END DESCRIPTION:
XS GIS Cut Line= 3
      3768064.31     10589526.93      3768211.87     10590282.12
      3768342.07     10590802.92
#Sta/Elev= 30
  4098.7  338.48  4112.2  341.76  4155.2  342.36  4193.7  336.11  4201.7  333.42
  4206.8  333.74    4265  319.74  4304.8  314.22  4366.9  309.17  4809.7  302.58
  4938.3  300.72  4948.6   302.2  4957.9  299.99    4963  300.76  4989.9  294.91
  4996.1  289.77  4998.8  289.27  5002.1  289.77  5010.5  292.63  5020.8   302.5
  5031.1  303.78  5040.3  307.44  5051.7  307.89  5086.7  298.13  5103.3  302.49
  5169.2  303.55    5196   309.1  5210.4  316.57    5227  322.73    5405  330.82
#Mann= 4 ,-1 , 0
  4098.7     .16       0  4809.7     .12       0  4996.1     .07       0
  5002.1     .12       0
Bank Sta=4963,5020.8
XS Rating Curve= 0 ,0
Exp/Cntr=0.3,0.1

Type RM Length L Ch R = 1 ,7823    ,443,443,443
BEGIN DESCRIPTION:
SPRING BRANCH 13.0
END DESCRIPTION:
XS GIS Cut Line= 3
      3767066.01      10589787.3      3767699.72     10590403.65
      3768072.48     10590845.76
#Sta/Elev= 30
  3947.2  380.01  4135.6  371.73    4178  368.26  4227.6  360.07  4262.9  359.44
  4304.4  352.34  4349.1  341.74  4411.5  323.83  4503.4  309.76  4736.7   302.8
  4970.6  300.26  4984.3  294.27  4989.1  288.82  4991.8  288.32  4995.1  288.82
  5012.9  289.55  5020.7  295.84  5027.2  294.64  5041.5  300.18  5055.8  305.85
  5076.6  303.49  5084.4  299.27  5105.2     298  5162.4  300.18    5191  295.86
    5269  301.18  5278.7  298.22  5361.3  299.12  5389.1  319.14  5409.5  323.14
#Mann= 6 ,-1 , 0
  3947.2     .16       0  4304.4     .05       0  4349.1     .16       0
  4989.1     .07       0  4995.1     .16       0  5278.7     .12       0
Bank Sta=4970.6,5041.5
XS Rating Curve= 0 ,0
Exp/Cntr=0.3,0.1

Type RM Length L Ch R = 1 ,7380    ,428,428,428
BEGIN DESCRIPTION:
SPRING BRANCH 12.0
END DESCRIPTION:
XS GIS Cut Line= 3
      3767171.37     10590372.19      3767511.64     10590833.99
       3768135.6      10591319.3
#Sta/Elev= 30
  4628.4   328.1    4633  323.26  4647.6  318.96  4653.8  313.89  4683.1  308.36
  4783.4  301.06  4975.5  297.38  5001.8  286.22  5004.5  285.72  5007.8  286.22
    5011  291.33  5025.6  295.67    5034  302.32  5048.2  303.87  5090.4  296.12
  5178.4  297.33  5280.8   298.1  5333.4  299.06  5347.9  295.34  5389.5  298.32
  5447.4  295.95  5555.9  298.22  5561.4   297.7  5575.9  305.48  5582.2  316.49
  5660.9  316.84  5768.6   327.9  5816.7  328.94    5889  329.12  5992.5  336.52
#Mann= 7 ,-1 , 0
  4628.4     .16       0  5001.8     .07       0  5007.8     .16       0
  5178.4     .05       0  5280.8     .16       0  5555.9     .12       0
  5816.7     .16       0
Bank Sta=4975.5,5025.6
XS Rating Curve= 0 ,0
Exp/Cntr=0.3,0.1

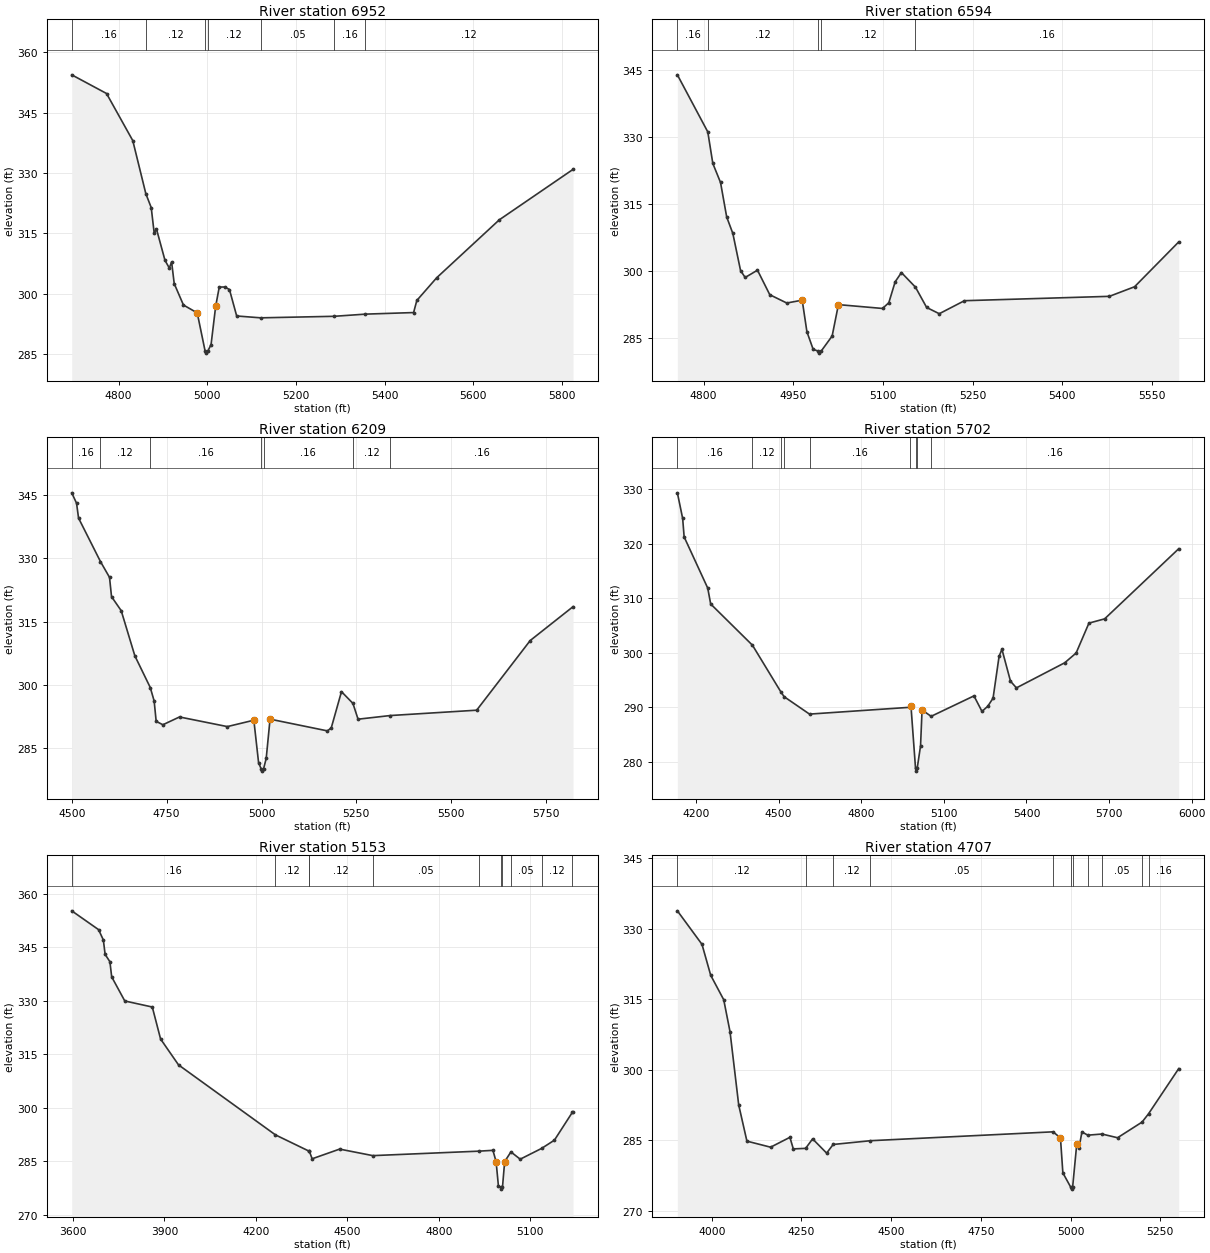
Type RM Length L Ch R = 1 ,6952    ,358,358,358
BEGIN DESCRIPTION:
SPRING BRANCH 11.0
END DESCRIPTION:
XS GIS Cut Line= 2
      3766903.99     10590507.57      3767209.17     10591596.51
#Sta/Elev= 30
  4694.4  354.38  4772.9  349.74  4832.1  338.04  4861.6  324.83  4873.7   321.4
  4880.4  315.06  4885.6  316.06  4904.8  308.27  4914.5  306.38  4919.7  307.89
  4925.6   302.5  4946.4  297.18  4977.5  295.23  4995.3  285.73  4998.1  285.23
  5001.3  285.73  5008.7  287.35  5019.1  296.87  5027.2  301.65  5039.8  301.66
  5050.2  301.03  5066.5  294.46  5120.7     294  5286.5  294.38    5357  294.92
  5465.6  295.31  5472.9  298.32  5517.6  303.95    5659  318.36  5825.3  330.89
#Mann= 7 ,-1 , 0
  4694.4     .16       0  4861.6     .12       0  4995.3     .07       0
  5001.3     .12       0  5120.7     .05       0  5286.5     .16       0
    5357     .12       0
Bank Sta=4977.5,5019.1
XS Rating Curve= 0 ,0
Exp/Cntr=0.3,0.1

Type RM Length L Ch R = 1 ,6594    ,385,385,385
BEGIN DESCRIPTION:
SPRING BRANCH 10.0
END DESCRIPTION:
XS GIS Cut Line= 3
      3766699.61     10590560.19      3766649.61     10590760.19
      3766849.61     10591360.18
#Sta/Elev= 30
    4756  344.01  4806.9   331.2  4815.3  324.13  4828.2  319.86  4838.5  312.12
  4848.8  308.42  4861.7   300.1  4869.4  298.55    4890  300.19  4910.6  294.68
    4939  292.82  4964.8  293.46  4972.7  286.37  4983.2  282.41  4990.8  282.08
  4993.5  281.58  4996.8  282.08  5014.9  285.42  5025.4  292.46  5099.2   291.6
  5109.7  292.89  5120.3  297.58  5130.8  299.65  5154.3  296.37    5173  291.82
  5194.1  290.42  5236.2  293.34  5478.7  294.32  5520.8  296.47  5594.6  306.52
#Mann= 5 ,-1 , 0
    4756     .16       0  4806.9     .12       0  4990.8     .07       0
  4996.8     .12       0  5154.3     .16       0
Bank Sta=4964.8,5025.4
XS Rating Curve= 0 ,0
Exp/Cntr=0.3,0.1

Type RM Length L Ch R = 1 ,6209    ,507,507,507
BEGIN DESCRIPTION:
SPRING BRANCH 9.0
END DESCRIPTION:
XS GIS Cut Line= 3
      3766449.14       10590334.      3766299.83     10590750.66
      3766185.25     10591622.16
#Sta/Elev= 30
  4499.7  345.61  4512.4  343.14  4517.7   339.6  4575.4  329.27  4599.3  325.51
  4604.6  320.92  4630.1  317.59  4666.1  306.85  4706.8   299.3    4717   296.1
  4722.3  291.27    4740  290.46  4783.8  292.31  4909.9  290.02  4979.8  291.54
  4992.3  281.43  4999.3  279.93  5002.1  279.43  5005.3  279.93  5012.4  282.47
  5022.5  291.79  5173.8     289  5183.9  289.72  5210.8  298.33    5241  295.54
  5254.5  291.78  5339.5  292.65  5567.2  293.92  5708.4  310.49  5821.3  318.54
#Mann= 7 ,-1 , 0
  4499.7     .16       0  4575.4     .12       0  4706.8     .16       0
  4999.3     .07       0  5005.3     .16       0    5241     .12       0
  5339.5     .16       0
Bank Sta=4979.8,5022.5
XS Rating Curve= 0 ,0
Exp/Cntr=0.3,0.1

Type RM Length L Ch R = 1 ,5702    ,549,549,549
BEGIN DESCRIPTION:
SPRING BRANCH 8.0
END DESCRIPTION:
XS GIS Cut Line= 3
      3766091.49     10589997.22      3765810.25     10590729.82
      3765539.41     10591729.86
#Sta/Elev= 30
  4132.2  329.36  4151.4  324.67  4156.8  321.27  4242.5  311.88  4253.2  308.97
    4405   301.4  4508.6   292.8    4520  291.96  4612.1  288.77  4977.5  290.02
  4980.7  290.19  4997.2  278.81  4999.9  278.31  5003.2  278.81  5015.4  282.94
  5020.9  289.53  5053.8  288.36  5209.4  292.11  5238.5  289.27  5259.2  290.19
  5278.8  291.69  5300.6  299.35    5311  300.66  5342.1  294.81  5363.6  293.58
  5538.9  298.18  5580.4  299.97    5627  305.46    5684  306.24    5953   319.1
#Mann= 9 ,-1 , 0
  4132.2     .16       0    4405     .12       0  4508.6     .16       0
    4520     .12       0  4612.1     .16       0  4977.5     .12       0
  4997.2     .07       0  5003.2     .12       0  5053.8     .16       0
Bank Sta=4980.7,5020.9
XS Rating Curve= 0 ,0
Exp/Cntr=0.3,0.1

Type RM Length L Ch R = 1 ,5153    ,446,446,446
BEGIN DESCRIPTION:
SPRING BRANCH 7.0
END DESCRIPTION:
XS GIS Cut Line= 3
      3765949.58     10589660.23      3765249.61     10590860.19
       3765299.6     10591110.14
#Sta/Elev= 30
  3595.8  355.27  3683.8  349.99  3699.5  347.09  3705.3  343.05    3721  340.99
  3726.8  336.75  3769.8  329.98    3860  328.28  3887.2  319.31    3946  312.05
  4263.9  292.41    4373  287.89  4374.9  287.87  4384.2   285.7  4474.4  288.42
  4583.1  286.59  4930.2  287.84  4977.1  288.07  4987.5  284.92  4995.2  278.01
  5002.4  277.69  5005.1  277.19  5008.4  277.69  5015.6  284.91  5036.1  287.63
  5066.6  285.59  5136.9  288.62  5178.8  290.93  5237.7  298.75  5239.9  298.75
#Mann= 11 ,-1 , 0
  3595.8     .16       0  4263.9     .12       0    4373     .16       0
  4374.9     .12       0  4583.1     .05       0  4930.2     .16       0
  5002.4     .07       0  5008.4     .16       0  5036.1     .05       0
  5136.9     .12       0  5237.7     .16       0
Bank Sta=4987.5,5015.6
XS Rating Curve= 0 ,0
Exp/Cntr=0.3,0.1

Type RM Length L Ch R = 1 ,4707    ,236,236,236
BEGIN DESCRIPTION:
SPRING BRANCH 6.0
END DESCRIPTION:
XS GIS Cut Line= 3
      3765199.59     10589910.23      3764799.61     10590910.19
      3764999.58     10591160.15
#Sta/Elev= 30
  3904.1  333.78  3972.7  326.65    3997  320.07  4033.3  314.86  4050.8  308.08
    4075  292.49  4097.9  284.79  4163.9   283.5  4217.7   285.6  4227.2  283.14
  4261.5  283.25    4281  285.27  4320.1  282.24  4338.2  284.08  4442.3  284.88
  4951.2  286.77  4971.7  285.46  4978.4  278.04  4999.7  275.08  5002.5  274.58
  5005.7  275.08  5017.1  284.16  5023.5  283.37  5031.5  286.74    5048  286.06
  5087.5   286.3  5130.8  285.51  5199.1  288.84  5217.1   290.6  5301.2  300.21
#Mann= 11 ,-1 , 0
  3904.1     .12       0  4261.5     .16       0  4338.2     .12       0
  4442.3     .05       0  4951.2     .12       0  4999.7     .07       0
  5005.7     .12       0    5048     .16       0  5087.5     .05       0
  5199.1     .12       0  5217.1     .16       0
Bank Sta=4971.7,5017.1
XS Rating Curve= 0 ,0
Exp/Cntr=0.3,0.1

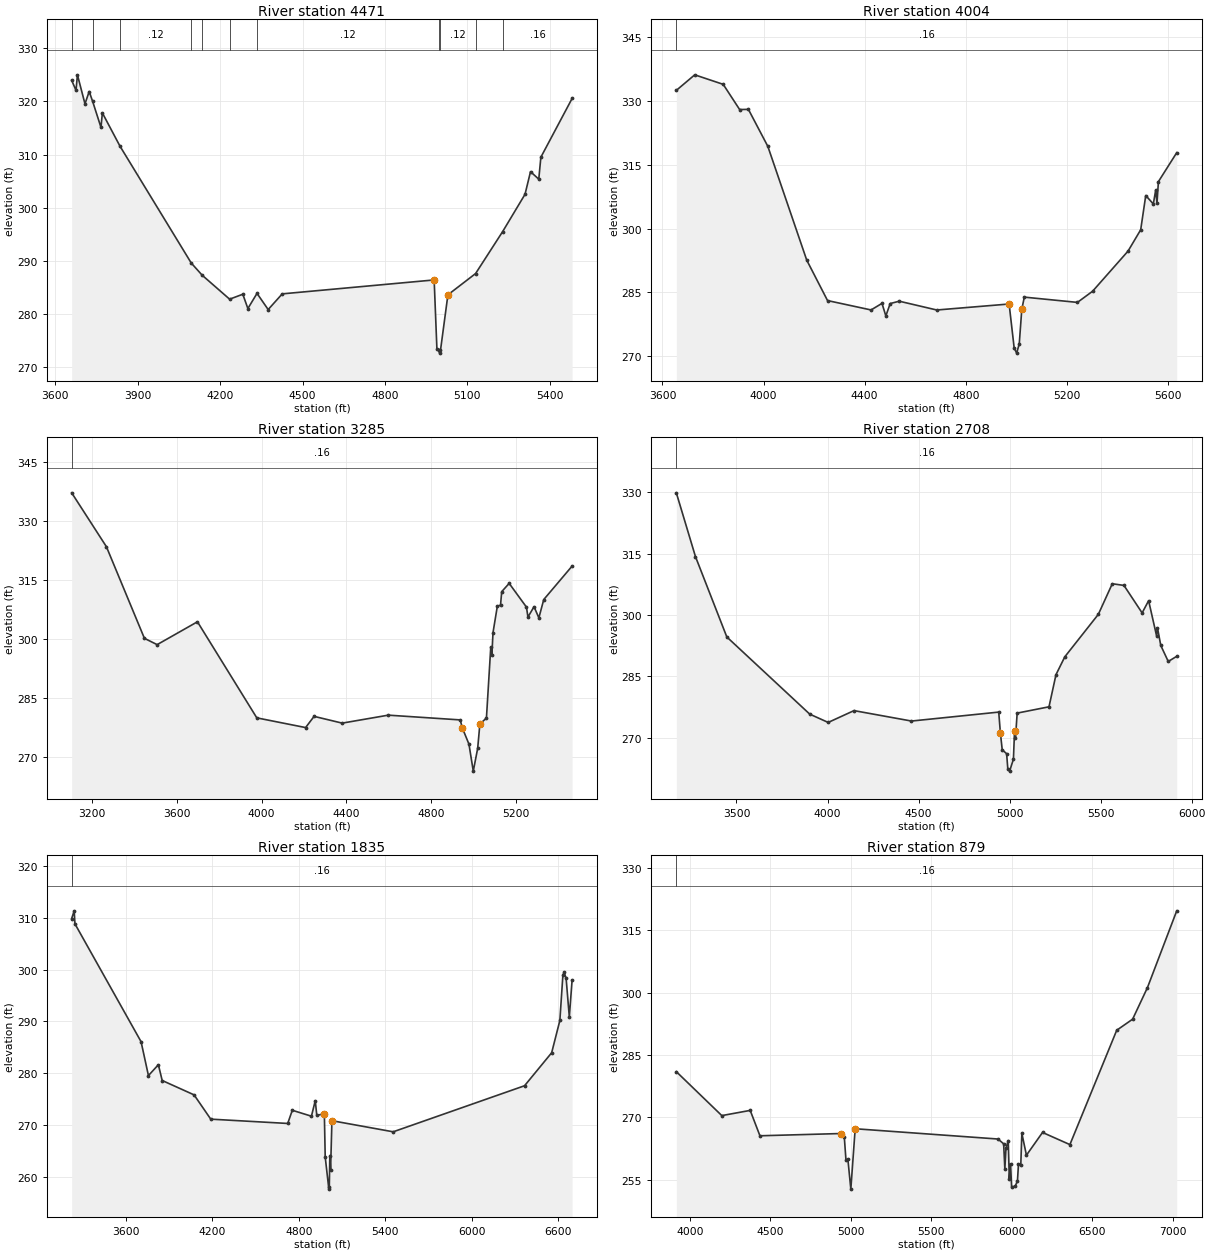
Type RM Length L Ch R = 1 ,4471    ,467,467,467
BEGIN DESCRIPTION:
SPRING BRANCH 5.0
END DESCRIPTION:
XS GIS Cut Line= 3
      3764858.87       10589643.      3764574.14      10590882.6
      3764612.33     10591431.19
#Sta/Elev= 30
  3659.3  323.96  3675.1  322.07  3680.2     325  3707.7  319.54    3723  321.86
  3735.5  320.02  3765.9  315.11    3771  317.83  3835.3  311.56  4094.6  289.59
  4134.5  287.29  4234.3  282.79  4282.3  283.72  4300.7  281.03    4334  283.88
  4374.6  280.84  4425.9  283.79  4978.9  286.41  4988.9  273.48  4995.9  273.14
  4998.7  272.64  5001.9  273.14    5029  283.61  5129.7  287.61  5228.3  295.51
  5309.7  302.52  5329.7  306.78  5359.8  305.37  5367.4   309.5  5481.1  320.55
#Mann= 11 ,-1 , 0
  3659.3     .07       0  3735.5     .16       0  3835.3     .12       0
  4094.6     .16       0  4134.5     .05       0  4234.3     .16       0
    4334     .12       0  4995.9     .07       0  5001.9     .12       0
  5129.7     .05       0  5228.3     .16       0
Bank Sta=4978.9,5029
XS Rating Curve= 0 ,0
Exp/Cntr=0.3,0.1

Type RM Length L Ch R = 1 ,4004    ,719,719,719
BEGIN DESCRIPTION:
SPRING BRANCH 4.0
END DESCRIPTION:
XS GIS Cut Line= 3
      3764783.07     10589578.96      3764305.62     10590724.83
       3764270.9     10591462.65
#Sta/Elev= 30
  3654.8  332.55  3727.7  336.21  3840.3  333.97  3905.3  328.04    3940  328.08
  4016.9  319.37  4170.8   292.6  4253.1  283.08  4425.3  280.87  4468.6  282.42
  4483.8  279.47  4501.1  282.38  4536.9  282.93  4685.3  280.86  4971.6  282.27
  4991.6  271.91  5001.4  270.71  5011.7  272.88  5021.7     281  5031.7  283.89
  5241.9  282.65    5302  285.28  5442.1  294.72  5492.2  299.74  5512.2   307.8
  5542.2  305.82  5551.6  309.09  5556.6  305.96  5562.3  311.07  5634.8  317.89
#Mann= 1 ,-1 , 0
  3654.8     .16       0
Bank Sta=4971.6,5021.7
XS Rating Curve= 0 ,0
Exp/Cntr=0.3,0.1

Type RM Length L Ch R = 1 ,3285    ,577,577,577
BEGIN DESCRIPTION:
SPRING BRANCH 3.0
END DESCRIPTION:
XS GIS Cut Line= 3
      3763654.58     10589327.29      3763750.07     10590846.36
       3763958.4     10591662.32
#Sta/Elev= 30
  3102.9   337.2  3266.9  323.49  3446.5  300.16  3506.6  298.55    3697  304.37
  3977.5  279.91    4208  277.44  4248.1  280.29  4380.9  278.57  4598.7   280.6
  4938.5  279.39  4948.9  277.29  4979.8  273.22  5000.2  266.35  5021.1  272.17
  5031.4  278.34  5062.4  279.86  5082.9  297.96  5088.1   295.9  5093.4   301.6
    5114  308.37  5128.9  308.58  5134.6  312.04  5169.8  314.15  5251.5   308.1
  5258.5  305.57  5287.2  308.21  5310.1  305.37  5333.2  310.03  5467.1  318.55
#Mann= 1 ,-1 , 0
  3102.9     .16       0
Bank Sta=4948.9,5031.4
XS Rating Curve= 0 ,0
Exp/Cntr=0.3,0.1

Type RM Length L Ch R = 1 ,2708    ,873,873,873
BEGIN DESCRIPTION:
SPRING BRANCH 2.0
END DESCRIPTION:
XS GIS Cut Line= 3
      3763437.56     10589266.54      3763211.87     10590681.43
      3763498.23     10591965.71
#Sta/Elev= 30
  3169.5  329.84  3274.5  314.27  3446.9  294.61  3902.3  275.75  4003.6  273.72
  4145.5  276.61  4461.1  274.06  4940.4  276.25  4949.4  271.19  4959.6  267.03
  4983.8  266.08  4990.3  262.36  5000.3  261.82  5021.1  264.76  5027.3  271.71
  5032.4  269.88  5041.6     276  5216.5  277.54  5254.9   285.4  5303.5  289.77
  5487.6  300.15  5564.1  307.62  5628.2  307.21    5728  300.49  5763.7  303.48
  5807.2  294.92  5812.3  296.85  5830.5  292.53  5871.5  288.62  5918.1  289.88
#Mann= 1 ,-1 , 0
  3169.5     .16       0
Bank Sta=4949.4,5027.3
XS Rating Curve= 0 ,0
Exp/Cntr=0.3,0.1

Type RM Length L Ch R = 1 ,1835    ,956,956,956
BEGIN DESCRIPTION:
SPRING BRANCH 1.0
END DESCRIPTION:
XS GIS Cut Line= 3
      3763151.12     10589032.09      3762474.03     10591106.78
      3763203.18     10592174.47
#Sta/Elev= 30
    3223  309.84  3240.4  311.32  3245.6  308.81  3704.9  286.09    3756  279.56
    3825  281.65  3851.6  278.61    4073  275.84  4188.8  271.16  4723.3  270.33
  4755.2  272.87    4888  271.73  4914.6  274.72  4925.2  271.89  4977.7   272.2
  4983.7  263.87    5009  257.67  5012.2  258.17  5015.6  264.14  5020.9   261.3
  5030.3  270.86  5455.8  268.72  6368.1   277.6  6556.4  283.96  6613.3  290.18
  6634.3   298.9  6643.1  299.47  6656.8   298.3    6679  290.86  6698.3  297.97
#Mann= 1 ,-1 , 0
    3223     .16       0
Bank Sta=4977.7,5030.3
XS Rating Curve= 0 ,0
Exp/Cntr=0.3,0.1

Type RM Length L Ch R = 1 ,879     ,490,490,490
BEGIN DESCRIPTION:
Mapping XS f92bc710
END DESCRIPTION:
XS GIS Cut Line= 3
      3762276.09     10589505.43       3761679.3     10590644.76
      3760496.58     10592033.64
#Sta/Elev= 30
  3915.1  280.98  4197.8  270.42  4374.3  271.67  4434.8  265.57  4936.7  266.11
    4959  265.35  4969.5  259.79  4981.6  259.88  4999.8  252.75  5026.8  267.26
  5914.6  264.79  5949.7  263.64  5957.1   257.6    5964  262.52  5978.2  264.42
  5984.8  255.27  5992.5  258.85  5999.1  253.25  6021.1  253.46  6035.4  254.68
  6041.9   258.8  6056.2  258.54  6062.8  266.15  6091.3   260.9  6191.3  266.37
  6361.5  263.45  6652.5  290.93  6751.3  293.59  6843.6  301.19  7025.5  319.63
#Mann= 1 ,-1 , 0
  3915.1     .16       0
Bank Sta=4936.7,5026.8
XS Rating Curve= 0 ,0
Exp/Cntr=0.3,0.1

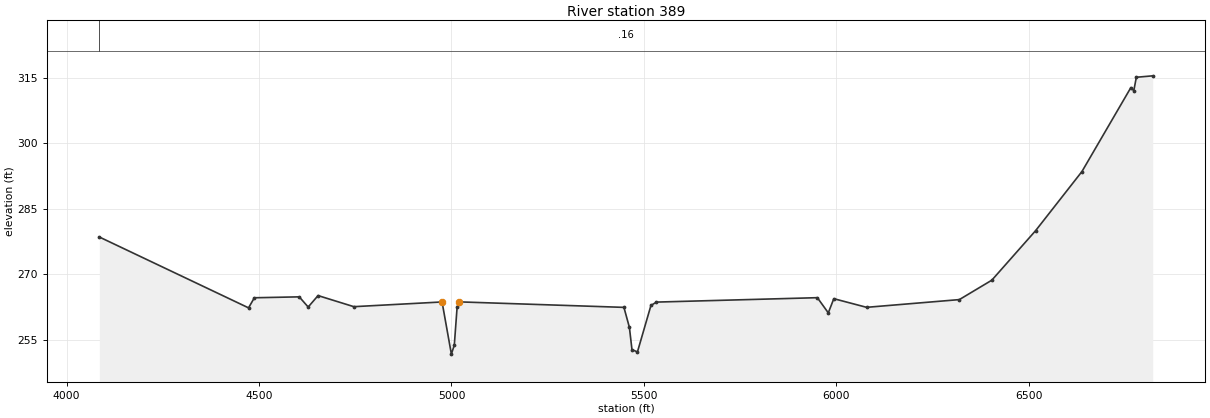
Type RM Length L Ch R = 1 ,389     ,0,0,0
BEGIN DESCRIPTION:
Mapping XS f92bc711
END DESCRIPTION:
XS GIS Cut Line= 3
      3761603.35     10589500.23      3761264.81     10590463.77
      3760124.38      10591744.8
#Sta/Elev= 30
  4085.3  278.54  4472.9  262.31    4488  264.62  4604.6  264.83  4627.8   262.5
  4653.5  265.12  4746.4  262.58  4975.6  263.66  4999.8  251.71  5007.4  253.78
  5014.7   262.5    5020  263.68    5448  262.42  5462.2  257.85  5468.9  252.75
  5483.1  252.21  5518.2  262.86  5532.5  263.63  5950.5  264.64  5978.9  261.16
  5993.2  264.41  6078.4  262.43  6319.3   264.2  6403.7  268.65  6517.4  279.99
  6637.8  293.54  6764.9  312.77  6772.5  312.06  6779.1  315.13  6821.7  315.46
#Mann= 1 ,-1 , 0
  4085.3     .16       0
Bank Sta=4975.6,5020
XS Rating Curve= 0 ,0
Exp/Cntr=0.3,0.1

Chan Stop Cuts=-1
Use User Specified Reach Order=0
Composite Channel Slope=5