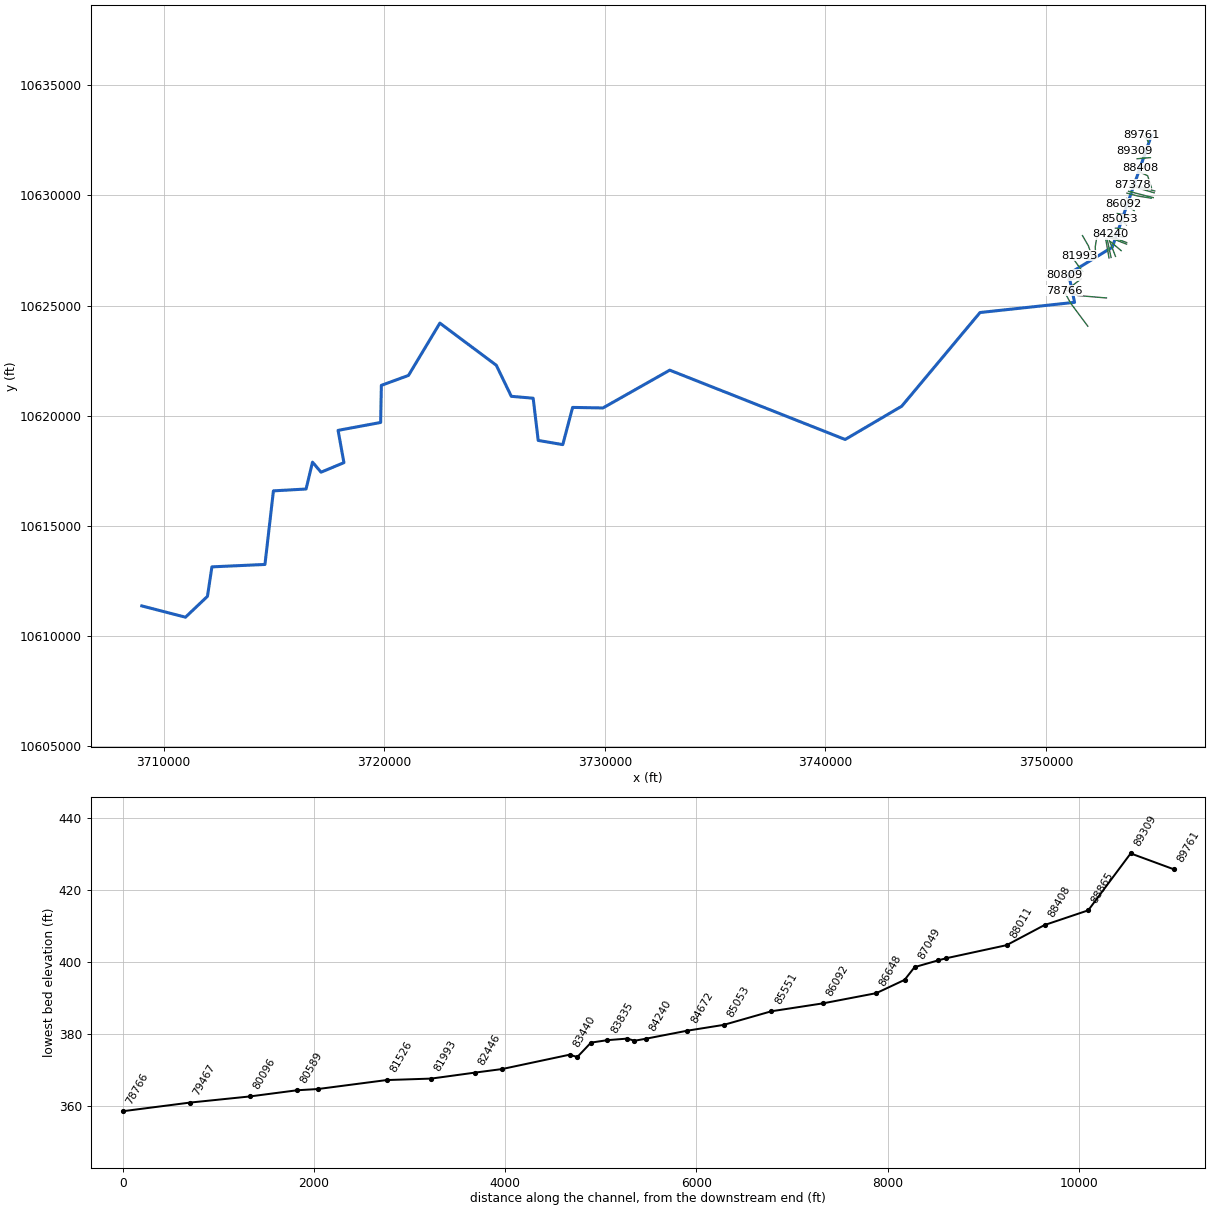
--- TOWN CREEK.prj (project) ---

Proj Title=TOWN CREEK Base Level Engineering
Current Plan=p01
Default Exp/Contr=0.3,0.1
English Units
Geom File=g01
Flow File=f01
Plan File=p01
Y Axis Title=Elevation
X Axis Title(PF)=Main Channel Distance
X Axis Title(XS)=Station
BEGIN DESCRIPTION:
TOWN CREEK
END DESCRIPTION:
DSS Export Rating Curves= 0
DSS Export Rating Curve Sorted= 0
DSS Export Volume Flow Curves= 0
DXF OffsetX= 0
DXF OffsetY= 0
DXF ScaleX= 1
DXF ScaleY= 10

--- TOWN CREEK.p01 (plan) ---

Plan Title=Multiple Run
Short Identifier=Multiple
Geom File=g01
Flow File=f01
Subcritical Flow
K Sum by GR= 0
Std Step Tol= 0.01
Critical Tol= 0.01
Num of Std Step Trials= 20
Max Error Tol= 0.3
Flow Tol Ratio= 0.001
Split Flow NTrial= 30
Split Flow Tol= 0.02
Split Flow Ratio= 0.02
Log Output Level= 0
Friction Slope Method= 1
Unsteady Friction Slope Method= 2
Unsteady Bridges Friction Slope Method= 1
Parabolic Critical Depth
Global Vel Dist=  1 , 1 , 1
Global Log Level= 0
CheckData=True
Encroach Param= -1, 0, 0, 0
BEGIN DESCRIPTION:
Multiple Run
END DESCRIPTION:

--- TOWN CREEK.f01 (steady flow) ---

Flow Title=Multiple
Program Version=4.10
Number of Profiles= 7
Profile Names=10-year,25-year,50-year,1pct_min,100-year,1pct_plu,500-year
River Rch & RM=TOWN CREEK,Reach-1         ,89761
     390     513     611     537     726     982    1026
River Rch & RM=TOWN CREEK,Reach-1         ,88011
     849    1166    1432    1290    1745    2360    2602
River Rch & RM=TOWN CREEK,Reach-1         ,87378
     849    1166    1432    1290    1745    2360    2602
River Rch & RM=TOWN CREEK,Reach-1         ,82446
    1157    1614    2002    1822    2463    3331    3744
River Rch & RM=TOWN CREEK,Reach-1         ,78495
    1246    1740    2161    1967    2660    3597    4046
River Rch & RM=TOWN CREEK,Reach-1         ,74773
    1466    2059    2566    2342    3167    4283    4846
River Rch & RM=TOWN CREEK,Reach-1         ,67607
    1697    2392    2988    2731    3694    4995    5670
River Rch & RM=TOWN CREEK,Reach-1         ,66970
    1697    2392    2988    2731    3694    4995    5670
River Rch & RM=TOWN CREEK,Reach-1         ,58282
    1769    2496    3120    2854    3860    5220    5934
River Rch & RM=TOWN CREEK,Reach-1         ,53641
    2974    4279    5418    5015    6782    9172   10671
River Rch & RM=TOWN CREEK,Reach-1         ,47173
    3802    5507    7005    6509    8802   11904   13955
River Rch & RM=TOWN CREEK,Reach-1         ,46632
    3802    5507    7005    6509    8802   11904   13955
River Rch & RM=TOWN CREEK,Reach-1         ,42687
    4015    5813    7393    6865    9284   12556   14704
River Rch & RM=TOWN CREEK,Reach-1         ,32483
    6055    8868   11369   10634   14381   19449   23098
River Rch & RM=TOWN CREEK,Reach-1         ,31933
    6055    8868   11369   10634   14381   19449   23098
River Rch & RM=TOWN CREEK,Reach-1         ,30950
    6252    9172   11773   11025   14910   20165   24005
River Rch & RM=TOWN CREEK,Reach-1         ,30406
    6154    9001   11527   10771   14566   19699   23342
River Rch & RM=TOWN CREEK,Reach-1         ,29800
    6154    9001   11527   10771   14566   19699   23342
River Rch & RM=TOWN CREEK,Reach-1         ,21840
    6092    8893   11375   10613   14353   19411   22938
River Rch & RM=TOWN CREEK,Reach-1         ,21408
    6047    8812   11258   10491   14188   19188   22618
River Rch & RM=TOWN CREEK,Reach-1         ,13762
    5974    8688   11083   10312   13946   18860   22162
River Rch & RM=TOWN CREEK,Reach-1         ,9281
    5981    8691   11081   10305   13936   18847   22123
Boundary for River Rch & Prof#=TOWN CREEK,Reach-1         , 1
Up Type= 0
Dn Type= 3
Dn Slope=0.003
Boundary for River Rch & Prof#=TOWN CREEK,Reach-1         , 2
Up Type= 0
Dn Type= 3
Dn Slope=0.003
Boundary for River Rch & Prof#=TOWN CREEK,Reach-1         , 3
Up Type= 0
Dn Type= 3
Dn Slope=0.003
Boundary for River Rch & Prof#=TOWN CREEK,Reach-1         , 4
Up Type= 0
Dn Type= 3
Dn Slope=0.003
Boundary for River Rch & Prof#=TOWN CREEK,Reach-1         , 5
Up Type= 0
Dn Type= 3
Dn Slope=0.003
Boundary for River Rch & Prof#=TOWN CREEK,Reach-1         , 6
Up Type= 0
Dn Type= 3
Dn Slope=0.003
Boundary for River Rch & Prof#=TOWN CREEK,Reach-1         , 7
Up Type= 0
Dn Type= 3
Dn Slope=0.003
DSS Import GetInterval= 0
DSS Import GetPeak= 0
DSS Import FillOption= 0

--- TOWN CREEK.g01 (geometry) ---

Geom Title=Existing Conditions
Program Version=4.10

River Reach=TOWN CREEK      ,Reach-1
Reach XY= 30
      3754786.65     10632738.36        3753007.       10627647.
       3751027.5       10626437.      3751296.25       10625146.
       3747010.5       10624684.      3743461.75       10620434.
      3740897.25       10618924.      3732943.75       10622069.
        3729915.       10620354.      3728540.25       10620379.
      3728094.25       10618690.       3726980.5       10618881.
       3726751.5       10620796.       3725760.5       10620882.
      3725080.25       10622291.       3722521.5       10624203.
        3721099.       10621830.       3719869.5       10621380.
       3719836.5       10619696.        3717907.       10619337.
        3718172.       10617873.        3717135.       10617440.
        3716747.       10617895.      3716456.25       10616677.
       3714975.5       10616593.      3714591.75       10613254.
      3712187.25       10613145.       3711984.5       10611808.
      3710988.75       10610861.      3709008.75       10611373.

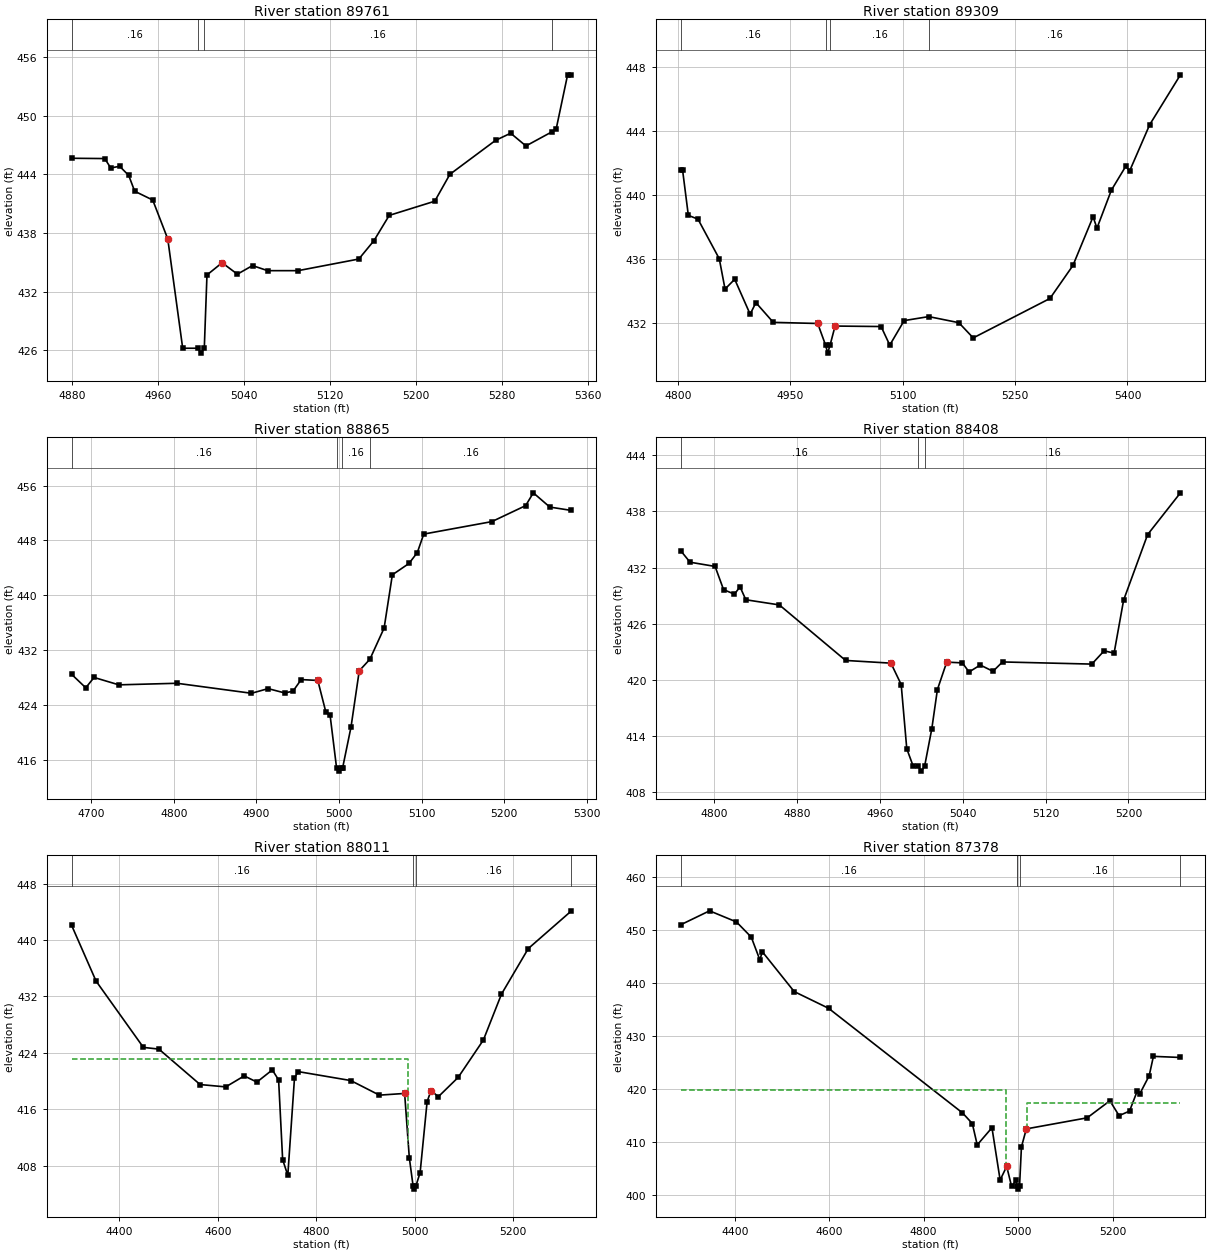
Type RM Length L Ch R = 1 ,89761   ,452,452,452
BEGIN DESCRIPTION:
TOWN CREEK 149.0
END DESCRIPTION:
XS GIS Cut Line= 3
      3754649.62     10632410.17      3754599.61     10632510.19
      3754349.59      10632760.2
#Sta/Elev= 30
  4879.5  445.63  4910.3   445.6  4915.9  444.64  4924.2  444.81  4932.6  443.88
  4938.2  442.26    4955  441.36    4969  437.38  4982.9  426.21    4997  426.21
  4999.8  425.71    5003  426.21  5005.5   433.7  5019.6  434.95  5033.8  433.78
  5047.9  434.66    5062  434.14  5090.3  434.14  5146.9  435.33    5161  437.21
  5175.2  439.79  5217.6  441.24  5231.7  443.99  5274.2  447.46  5288.3  448.19
  5302.5  446.89    5327  448.35  5330.7  448.64  5341.3  454.16  5344.9  454.16
#Mann= 4 ,-1 , 0
  4879.5     .16       0    4997     .16       0    5003     .16       0
    5327     .16       0
Bank Sta=4969,5019.6
XS Rating Curve= 0 ,0
Exp/Cntr=0.3,0.1

Type RM Length L Ch R = 1 ,89309   ,444,444,444
BEGIN DESCRIPTION:
TOWN CREEK 148.0
END DESCRIPTION:
XS GIS Cut Line= 3
      3754649.63     10632160.19      3754449.61     10632110.19
      3753999.56     10632010.18
#Sta/Elev= 30
  4803.5  441.55  4806.1  441.55  4813.8  438.72  4826.7  438.48  4855.1  436.01
  4862.8  434.12  4875.7  434.73  4896.3  432.55    4904  433.27  4927.2  432.04
  4986.5  431.97    4997  430.62  4999.8  430.12    5003  430.62  5009.7  431.81
  5071.1  431.78  5082.7  430.62  5101.9  432.15  5134.7   432.4  5174.9  432.02
  5194.1  431.07  5296.5  433.53  5327.2  435.59  5354.1  438.63  5359.3  437.92
  5378.5  440.29  5397.7  441.78  5402.8  441.48  5429.7  444.38  5470.7  447.49
#Mann= 4 ,-1 , 0
  4803.5     .16       0    4997     .16       0    5003     .16       0
  5134.7     .16       0
Bank Sta=4986.5,5009.7
XS Rating Curve= 0 ,0
Exp/Cntr=0.3,0.1

Type RM Length L Ch R = 1 ,88865   ,457,457,457
BEGIN DESCRIPTION:
TOWN CREEK 147.0
END DESCRIPTION:
XS GIS Cut Line= 2
      3754736.61     10631712.05      3754133.55     10631660.06
#Sta/Elev= 30
  4676.2  428.46  4693.3   426.5  4703.3  428.01  4733.4  426.93  4803.7  427.16
    4894   425.7  4914.1  426.38  4934.2  425.75  4944.2     426  4954.2   427.7
  4974.3  427.57  4984.1  422.93  4989.1  422.57    4997  414.84  4999.8  414.34
    5003  414.84  5004.4  414.84  5014.5  420.76  5024.5  428.98  5037.4  430.67
  5054.6  435.22  5064.6  442.99  5084.7  444.64  5094.8  446.23  5102.6  448.93
  5185.1  450.75    5226  453.08  5235.3  454.95  5255.3  452.87  5281.5  452.38
#Mann= 4 ,-1 , 0
  4676.2     .16       0    4997     .16       0    5003     .16       0
  5037.4     .16       0
Bank Sta=4974.3,5024.5
XS Rating Curve= 0 ,0
Exp/Cntr=0.3,0.1

Type RM Length L Ch R = 1 ,88408   ,397,397,397
BEGIN DESCRIPTION:
TOWN CREEK 146.0
END DESCRIPTION:
XS GIS Cut Line= 2
      3754718.08     10631406.58      3754270.19     10631226.04
#Sta/Elev= 30
  4767.3  433.81  4776.4  432.57  4800.6  432.12  4808.8  429.64  4819.3  429.16
  4824.7  429.94  4830.3  428.56  4862.7  428.01  4926.7  422.08  4970.5  421.79
  4980.4  419.51  4985.8  412.65  4992.1  410.76    4997  410.76  4999.8  410.26
    5003  410.76    5010  414.79  5015.4  418.97  5024.4   421.9  5039.5  421.82
    5046  420.85  5056.8  421.59  5069.1  420.92  5078.3  421.92  5164.6  421.69
  5176.5  423.11  5186.1  422.86  5195.3  428.52  5218.5  435.52  5250.2  439.98
#Mann= 3 ,-1 , 0
  4767.3     .16       0    4997     .16       0    5003     .16       0
Bank Sta=4970.5,5024.4
XS Rating Curve= 0 ,0
Exp/Cntr=0.3,0.1

Type RM Length L Ch R = 1 ,88011   ,633,633,633
BEGIN DESCRIPTION:
TOWN CREEK 145.0
END DESCRIPTION:
XS GIS Cut Line= 3
      3754780.56     10630351.06      3754610.43     10630889.22
      3754200.67     10631080.21
#Sta/Elev= 30
  4302.7  442.08  4352.3  434.19  4448.6  424.78  4480.1  424.54    4564  419.51
  4616.1  419.18  4653.7  420.74  4679.4  419.86  4710.8  421.59  4723.6  420.16
  4731.8  408.87  4742.3  406.63  4755.9  420.44  4763.3  421.35  4870.3  420.08
  4928.6  418.01  4979.9  418.25  4989.4  409.15    4997  405.18  4999.8  404.68
    5003  405.18  5011.4  407.02  5025.6  417.07  5033.5  418.66  5048.5  417.79
  5088.7  420.52    5140  425.82  5176.9  432.34  5231.4   438.8  5319.2  444.15
#Mann= 4 ,-1 , 0
  4302.7     .16       0    4997     .16       0    5003     .16       0
  5319.2     .16       0
#XS Ineff= 2 , 0
          4987.5  423.09
Permanent Ineff=
       F       F
Bank Sta=4979.9,5033.5
XS Rating Curve= 0 ,0
Exp/Cntr=0.3,0.1

Type RM Length L Ch R = 1 ,87378   ,80,80,80
BEGIN DESCRIPTION:
Mapping XS 36b29bd6
END DESCRIPTION:
XS GIS Cut Line= 2
      3754933.38     10630198.24      3753915.96     10630489.92
#Sta/Elev= 30
  4285.3  450.94  4346.6  453.58  4403.6  451.48  4434.9  448.62  4453.1  444.32
  4458.3  445.86  4525.8  438.34  4598.5  435.19  4882.2  415.44    4903  413.43
  4913.4   409.4  4944.6  412.64  4961.9  402.77  4975.8  405.34  4986.2  401.55
  4995.7  402.76    4997  401.55  4999.8  401.05    5003  401.55    5007     409
  5017.4  412.42  5146.3  414.51  5194.3  417.73  5213.8  414.92  5235.9  415.78
  5252.7  419.66  5257.9  419.08  5277.5  422.45  5286.5  426.11  5343.7   425.9
#Mann= 5 ,-1 , 0
  4285.3     .16       0    4997     .16       0    4997     .16       0
    5003     .16       0  5343.7     .16       0
#XS Ineff= 2 , 0
         4975.23  419.75 5018.18          417.27
Permanent Ineff=
       F       F
Bank Sta=4975.8,5017.4
XS Rating Curve= 0 ,0
Exp/Cntr=0.3,0.1

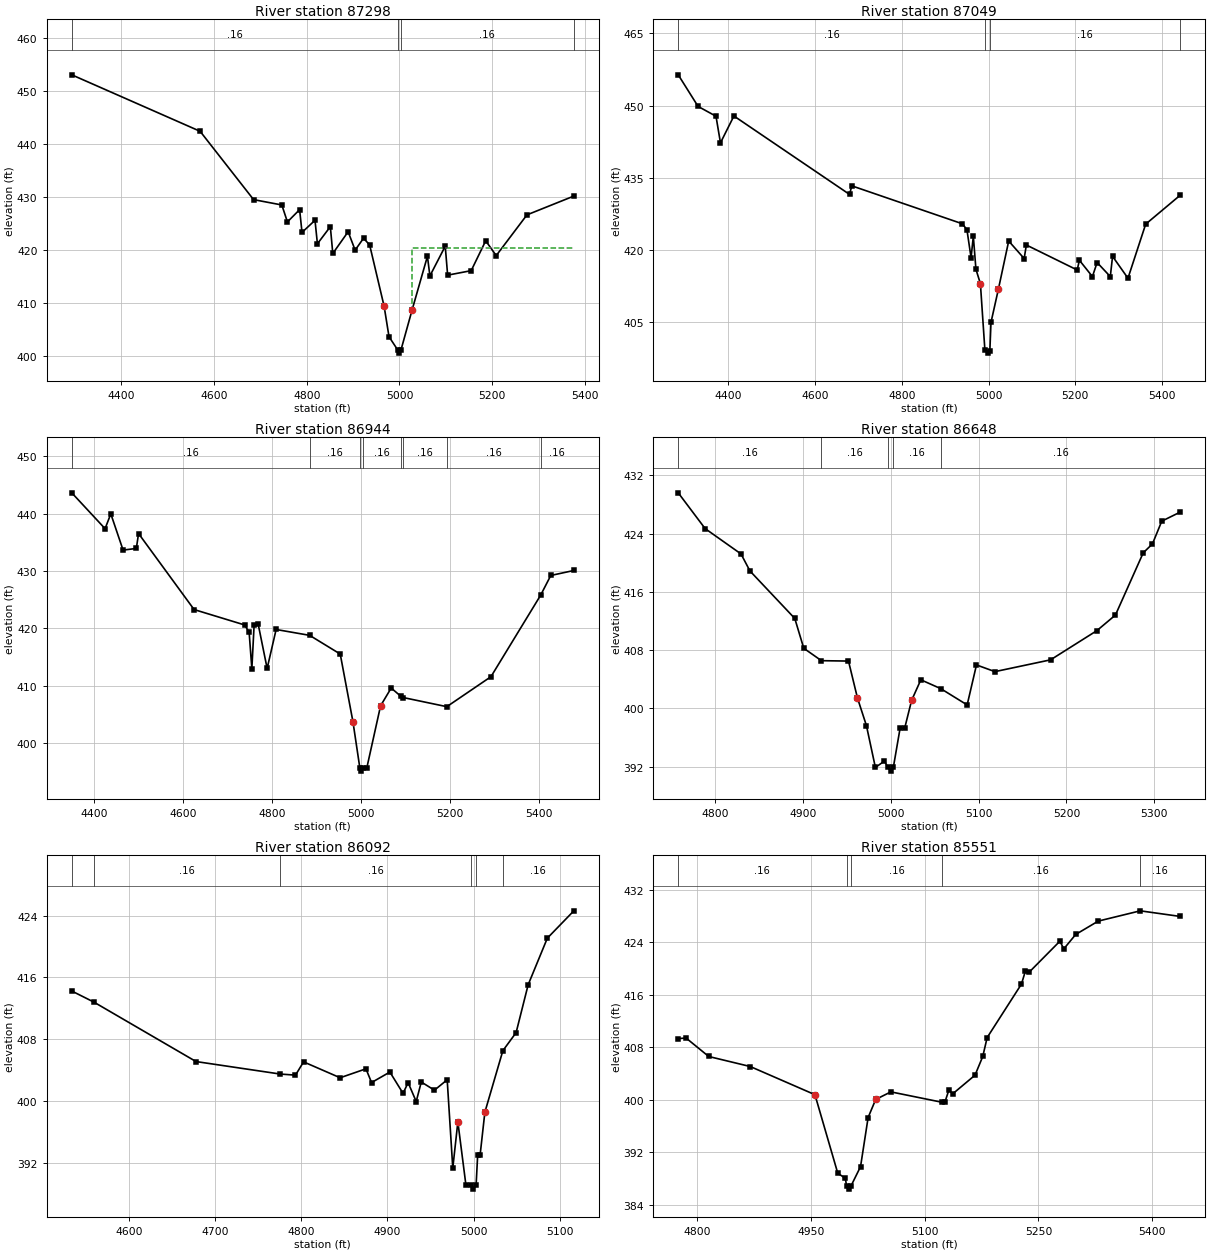
Type RM Length L Ch R = 1 ,87298   ,249,249,249
BEGIN DESCRIPTION:
TOWN CREEK 144.0
END DESCRIPTION:
XS GIS Cut Line= 2
      3754905.62      10630114.9      3753867.34     10630423.95
#Sta/Elev= 30
    4293  453.03  4569.9  442.37  4685.3  429.47  4746.2  428.46  4758.3  425.26
  4784.6  427.58  4789.8  423.28  4817.8  425.57    4823  421.13  4850.9  424.37
  4856.2   419.3  4889.3  423.41  4904.4  419.93  4922.5  422.18  4935.7  420.92
    4967  409.31  4977.5  403.59    4997  400.99  4999.8  400.49    5003  400.99
  5027.3  408.64  5060.4  418.77  5065.7  415.06  5098.8  420.68    5104  415.21
  5154.8  416.06  5186.1   421.7  5208.8   418.9  5275.1  426.59  5376.3  430.14
#Mann= 4 ,-1 , 0
    4293     .16       0    4997     .16       0    5003     .16       0
  5376.3     .16       0
#XS Ineff= 2 , 0
                         5026.36          420.35
Permanent Ineff=
       F       F
Bank Sta=4967,5027.3
XS Rating Curve= 0 ,0
Exp/Cntr=0.3,0.1

Type RM Length L Ch R = 1 ,87049   ,105,105,105
BEGIN DESCRIPTION:
TOWN CREEK 143.0
END DESCRIPTION:
XS GIS Cut Line= 2
      3754863.88     10629896.17      3753743.48     10630184.07
#Sta/Elev= 30
    4285  456.41  4330.7  449.85    4372  447.81  4382.3  442.28  4413.3  447.86
  4679.7  431.57  4684.9  433.35  4939.9  425.46  4950.2  424.22  4959.7  418.42
  4964.9  422.87  4970.9  416.02  4981.2  413.03  4991.5   399.3  4999.8   398.6
    5003   399.1  5005.6  404.99  5022.5  411.82  5046.4  421.89    5082  418.25
  5087.1  421.06  5204.2  415.87  5209.3  417.89  5239.3   414.5  5250.1  417.42
  5280.5   414.5  5285.7   418.7  5321.2  414.16    5362  425.39  5441.8  431.42
#Mann= 4 ,-1 , 0
    4285     .16       0  4991.5     .16       0    5003     .16       0
  5441.8     .16       0
Bank Sta=4981.2,5022.5
XS Rating Curve= 0 ,0
Exp/Cntr=0.3,0.1

Type RM Length L Ch R = 1 ,86944   ,296,296,296
BEGIN DESCRIPTION:
Mapping XS 2078859b
END DESCRIPTION:
XS GIS Cut Line= 3
      3754773.62     10629871.86      3754179.88     10629965.61
      3753669.43     10630101.03
#Sta/Elev= 30
    4349  443.65  4423.9  437.39  4436.8  439.98  4464.4  433.65  4494.2  433.94
  4499.2  436.54  4624.1  423.27  4737.8  420.58  4747.9  419.31    4754  412.94
  4759.1  420.55  4768.1  420.78  4788.4  412.99  4808.6  419.79    4884418.7672
  4952.8   415.5  4981.4  403.68    4997  395.56  4999.8  395.06    5003  395.56
  5012.5   395.6  5043.5  406.46  5067.4  409.57  5089.2408.1205  5094.2407.9117
  5192.5406.3125  5291.8  411.55  5403.5425.7743  5426.3  429.22  5478.2  430.09
#Mann= 8 ,-1 , 0
    4349     .16       0    4884     .16       0    4997     .16       0
    5003     .16       0  5089.2     .16       0  5094.2     .16       0
  5192.5     .16       0  5403.5     .16       0
Bank Sta=4981.4,5043.5
XS Rating Curve= 0 ,0
Exp/Cntr=0.3,0.1

Type RM Length L Ch R = 1 ,86648   ,556,556,556
BEGIN DESCRIPTION:
TOWN CREEK 142.0
END DESCRIPTION:
XS GIS Cut Line= 3
      3754199.59     10629710.19      3753949.61     10629760.19
      3753649.57      10629860.2
#Sta/Elev= 30
  4758.3  429.59  4788.9  424.68  4829.7   421.2  4839.9  418.86  4890.9  412.34
  4901.1  408.25  4921.2406.5447    4952  406.49  4962.2  401.42  4972.4  397.63
  4982.6  391.88  4992.8  392.76    4997  391.88  4999.8  391.38    5003  391.88
  5010.7  397.27  5015.9  397.27  5023.8  401.09  5034.3  403.92    5057402.7038
    5087  400.47  5097.6  405.96  5118.6  405.04  5181.9  406.66  5234.6  410.67
  5255.7  412.81  5287.3  421.35  5297.8  422.58  5308.4   425.7  5329.5  426.95
#Mann= 5 ,-1 , 0
  4758.3     .16       0  4921.2     .16       0    4997     .16       0
    5003     .16       0    5057     .16       0
Bank Sta=4962.2,5023.8
XS Rating Curve= 0 ,0
Exp/Cntr=0.3,0.1

Type RM Length L Ch R = 1 ,86092   ,541,541,541
BEGIN DESCRIPTION:
TOWN CREEK 141.0
END DESCRIPTION:
XS GIS Cut Line= 3
      3753999.58     10629310.21      3753599.61     10629560.19
      3753499.58      10629610.2
#Sta/Elev= 30
  4533.1  414.23  4558.9412.7875  4677.5  405.09  4775.4403.4705  4793.1  403.33
  4802.5  405.05    4845  402.99    4875  404.15  4881.5  402.37  4902.8  403.73
  4918.1  400.97    4924  402.36  4933.4  399.91  4939.3  402.44  4954.6  401.38
  4969.4  402.73  4975.9  391.29  4981.8  397.27  4991.2  389.06    4997  389.06
  4999.8  388.56    5003  389.06  5004.8  392.92  5007.6  392.92  5013.2  398.53
  5034.1406.4984  5049.5  408.84  5063.5  415.04  5085.8  421.08  5116.6  424.62
#Mann= 6 ,-1 , 0
  4533.1     .16       0  4558.9     .16       0  4775.4     .16       0
    4997     .16       0    5003     .16       0  5034.1     .16       0
Bank Sta=4981.8,5013.2
XS Rating Curve= 0 ,0
Exp/Cntr=0.3,0.1

Type RM Length L Ch R = 1 ,85551   ,498,498,498
BEGIN DESCRIPTION:
TOWN CREEK 140.0
END DESCRIPTION:
XS GIS Cut Line= 3
      3753889.76     10629102.24      3753542.56     10629113.09
      3753234.49       10629176.
#Sta/Elev= 30
  4775.2  409.32  4785.4  409.43  4815.4   406.6  4870.1  405.07  4955.4  400.77
  4985.5  388.78  4995.5  388.02    4997  386.86  4999.8  386.36    5003  386.86
  5015.5  389.79  5025.5  397.29  5035.5  400.05  5055.5   401.2  5123.5   399.6
  5126.6   399.6  5131.9  401.47    5137   400.9  5166.4  403.75  5176.6   406.6
  5182.4  409.49  5227.6  417.65  5232.9  419.68    5238  419.49  5278.3   424.2
  5283.4  423.02  5299.1  425.22  5328.8  427.26  5384.2428.8283    5437  427.97
#Mann= 5 ,-1 , 0
  4775.2     .16       0    4997     .16       0    5003     .16       0
  5123.5     .16       0  5384.2     .16       0
Bank Sta=4955.4,5035.5
XS Rating Curve= 0 ,0
Exp/Cntr=0.3,0.1

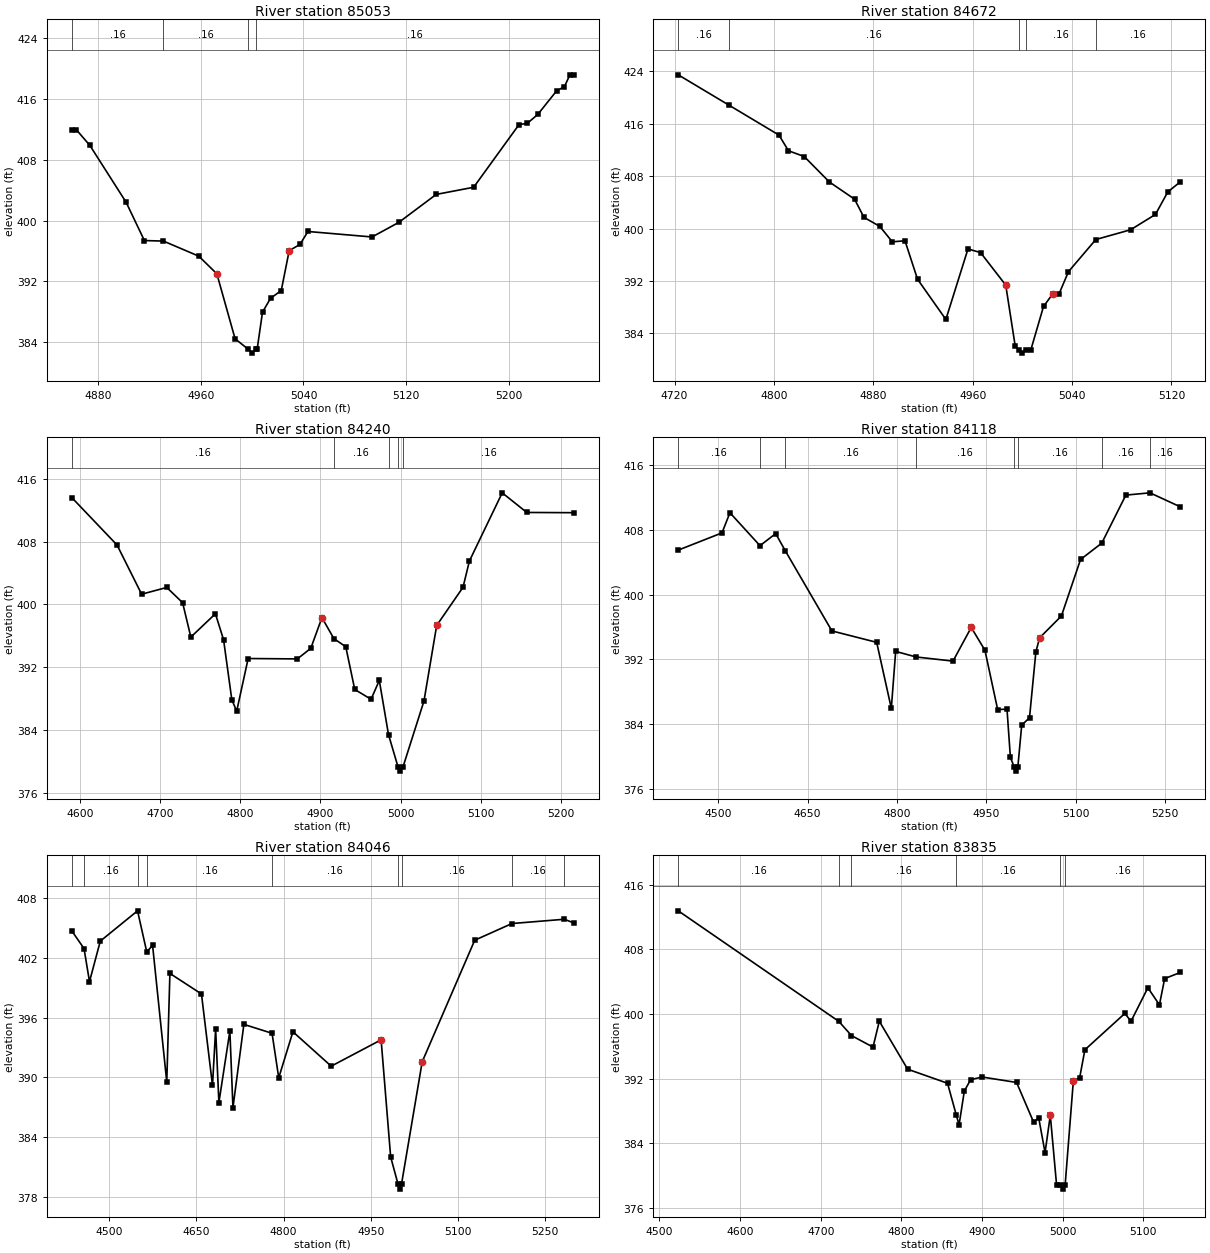
Type RM Length L Ch R = 1 ,85053   ,381,381,381
BEGIN DESCRIPTION:
TOWN CREEK 139.0
END DESCRIPTION:
XS GIS Cut Line= 3
      3753649.61     10628660.19      3753549.61     10628760.19
      3753349.62     10628910.18
#Sta/Elev= 30
  4859.4  411.95  4862.9  411.95  4873.5  409.88  4901.8   402.4    4916  397.38
  4930.9397.3072  4958.4  395.33  4972.5  393.01  4986.7  384.48    4997  383.09
  4999.8  382.59    5003  383.09  5003.9  383.09  5008.1  387.98  5014.4   389.8
  5022.7  390.81  5028.9  396.05  5037.3  396.87  5043.5  398.57  5093.5  397.85
  5114.4  399.77  5143.5  403.44  5172.7  404.38  5208.1  412.62  5214.4  412.76
  5222.7  413.95  5237.3  417.03  5243.5   417.6  5247.7  419.15  5250.8  419.15
#Mann= 4 ,-1 , 0
  4859.4     .16       0  4930.9     .16       0    4997     .16       0
    5003     .16       0
Bank Sta=4972.5,5028.9
XS Rating Curve= 0 ,0
Exp/Cntr=0.3,0.1

Type RM Length L Ch R = 1 ,84672   ,432,432,432
BEGIN DESCRIPTION:
TOWN CREEK 138.0
END DESCRIPTION:
XS GIS Cut Line= 3
      3753549.59     10628460.19      3753249.61     10628510.19
      3753149.63     10628510.19
#Sta/Elev= 30
    4723  423.46  4763.6418.8564  4804.1  414.26  4811.7  411.87  4824.4  410.99
  4844.6  407.11  4864.9  404.48  4872.5   401.7  4885.2  400.33  4895.3  397.97
  4905.5  398.13  4915.6  392.26  4938.4  386.12  4956.2  396.88  4966.3  396.33
  4986.6  391.36  4994.2  382.07    4997  381.48  4999.8  380.98    5003  381.48
  5006.8  381.48    5017   388.1  5024.6  390.07  5029.6  390.07  5037.1  393.42
  5059.1  398.32  5087.1  399.81  5107.1  402.15  5117.1  405.61  5127.1  407.12
#Mann= 5 ,-1 , 0
    4723     .16       0  4763.6     .16       0    4997     .16       0
    5003     .16       0  5059.1     .16       0
Bank Sta=4986.6,5024.6
XS Rating Curve= 0 ,0
Exp/Cntr=0.3,0.1

Type RM Length L Ch R = 1 ,84240   ,122,122,122
BEGIN DESCRIPTION:
TOWN CREEK 137.0
END DESCRIPTION:
XS GIS Cut Line= 2
      3753554.89      10628090.6      3752942.18     10628225.61
#Sta/Elev= 30
  4589.2   413.6  4645.8  407.55  4676.5  401.29  4707.9  402.15  4727.7  400.21
    4738  395.83  4768.7   398.8  4778.9  395.49  4789.2  387.85  4795.3   386.4
  4809.6   393.1  4871.1  393.05  4887.9   394.4  4901.8  398.31  4916.7395.6395
  4931.6   394.6  4942.8  389.16  4963.2  387.91  4973.5  390.31    4985383.4089
    4997  379.26  4999.8  378.76    5003  379.26  5029.3  387.68  5045.2  397.31
  5078.1  402.17  5086.1  405.52  5127.1   414.2  5157.8   411.7  5216.6  411.67
#Mann= 5 ,-1 , 0
  4589.2     .16       0  4916.7     .16       0    4985     .16       0
    4997     .16       0    5003     .16       0
Bank Sta=4901.8,5045.2
XS Rating Curve= 0 ,0
Exp/Cntr=0.3,0.1

Type RM Length L Ch R = 1 ,84118   ,72,72,72
BEGIN DESCRIPTION:
Mapping XS 313a9650
END DESCRIPTION:
XS GIS Cut Line= 2
      3753660.63     10627857.87      3752873.07     10628159.38
#Sta/Elev= 30
  4432.6   405.5  4506.1  407.63  4519.4  410.12  4569.9406.0507  4596.3  407.54
  4612.3405.4317  4690.7  395.51  4765.9   394.1  4790.5  385.94  4797.8  392.98
  4832.1392.2908  4894.1  391.78  4924.7  395.94  4947.7  393.13  4969.1  385.79
  4984.8  385.84  4990.5  379.88    4997  378.68  4999.8  378.18    5003  378.68
  5009.5  383.86  5022.6  384.78  5033.3  392.93  5039.6  394.66  5076.2  397.36
  5108.3  404.34    5144406.3656  5184.4   412.3  5224.9412.5816  5275.9  410.85
#Mann= 8 ,-1 , 0
  4432.6     .16       0  4569.9     .16       0  4612.3     .16       0
  4832.1     .16       0    4997     .16       0    5003     .16       0
    5144     .16       0  5224.9     .16       0
Bank Sta=4924.7,5039.6
XS Rating Curve= 0 ,0
Exp/Cntr=0.3,0.1

Type RM Length L Ch R = 1 ,84046   ,211,211,211
BEGIN DESCRIPTION:
TOWN CREEK 136.0
END DESCRIPTION:
XS GIS Cut Line= 2
      3753655.37     10627784.98      3752850.76     10628100.05
#Sta/Elev= 30
  4435.5  404.69  4456.6402.9155    4466   399.6  4484.6  403.66  4548.7406.6967
  4564.5  402.59  4574.6  403.22    4599  389.53  4604.4  400.42  4658.7  398.36
  4677.7  389.19  4683.1  394.83  4688.7  387.47  4707.6  394.64  4712.9  386.96
  4731.7  395.31  4780.2394.4184  4791.7  389.95  4816.1  394.57    4882  391.12
  4967.9  393.76  4984.3  382.03    4997  379.29  4999.8  378.79    5003  379.29
  5038.6  391.56    5129  403.75  5193.2 405.424  5283.3405.8512  5299.6  405.48
#Mann= 9 ,-1 , 0
  4435.5     .16       0  4456.6     .16       0  4548.7     .16       0
  4564.5     .16       0  4780.2     .16       0    4997     .16       0
    5003     .16       0  5193.2     .16       0  5283.3     .16       0
Bank Sta=4967.9,5038.6
XS Rating Curve= 0 ,0
Exp/Cntr=0.3,0.1

Type RM Length L Ch R = 1 ,83835   ,171,171,171
BEGIN DESCRIPTION:
Mapping XS e760f386
END DESCRIPTION:
XS GIS Cut Line= 2
      3753410.61      10627490.7      3752934.32     10627891.51
#Sta/Elev= 30
  4523.3  412.76  4722.4399.0903  4738.1 397.334  4764.8  395.91  4772.6  399.11
  4807.7  393.18  4857.2  391.44    4868387.5225  4871.5   386.3    4878  390.47
  4885.8  391.88  4900.1  392.21  4942.8  391.54  4963.8  386.65  4970.3  387.13
  4978.1  382.86  4984.6  387.48  4992.4  378.85    4997  378.85  4999.8  378.35
    5003  378.85  5013.2  391.76    5021  392.12  5027.5  395.58    5077  400.07
  5084.7  399.11  5105.6  403.25  5119.9  401.13  5126.4  404.38  5145.8  405.14
#Mann= 6 ,-1 , 0
  4523.3     .16       0  4722.4     .16       0  4738.1     .16       0
    4868     .16       0    4997     .16       0    5003     .16       0
Bank Sta=4984.6,5013.2
XS Rating Curve= 0 ,0
Exp/Cntr=0.3,0.1

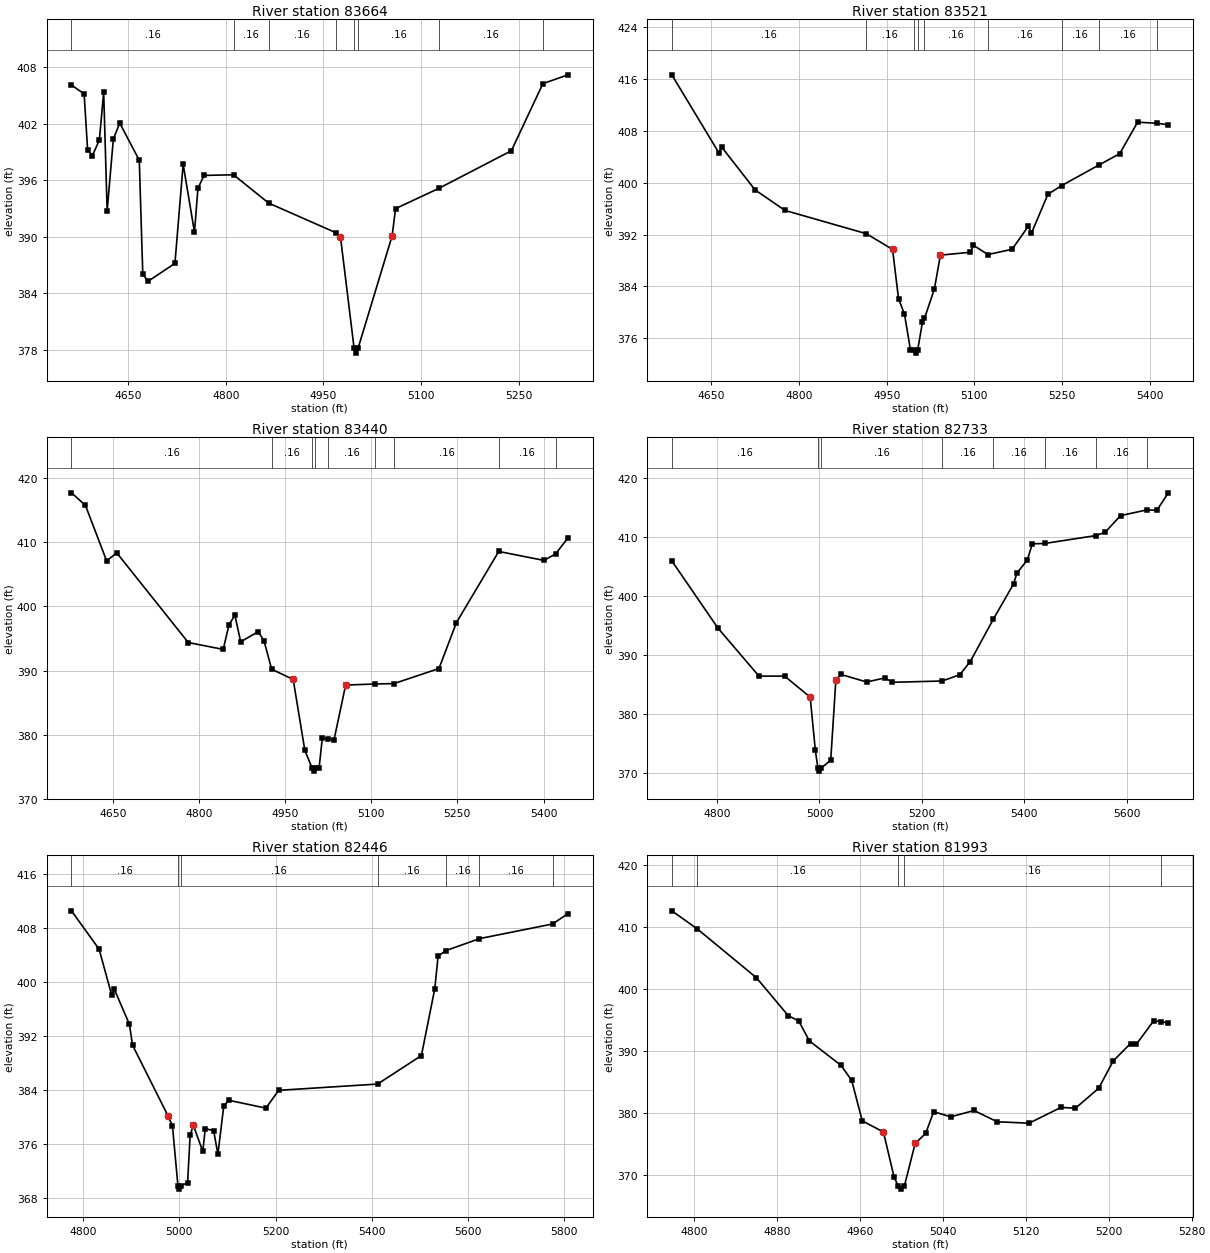
Type RM Length L Ch R = 1 ,83664   ,143,143,143
BEGIN DESCRIPTION:
Mapping XS 762241db
END DESCRIPTION:
XS GIS Cut Line= 2
       3753152.8      10627230.3      3752879.36     10627941.23
#Sta/Elev= 30
  4563.4   406.1  4582.8  405.17  4588.1  399.26  4595.4  398.61  4606.1  400.26
  4612.8  405.33  4618.1  392.75  4627.6  400.37  4637.4  402.07  4667.4  398.13
  4672.8  386.02  4681.1   385.3  4722.1  387.19  4734.7  397.71  4752.1   390.5
  4757.4  395.17  4766.9  396.52    4812396.5867  4865.8393.5878  4969.4390.4315
    4976  390.04    4997  378.17  4999.8  377.67    5003  378.17  5055.3   390.1
  5060.6     393    5127395.1476  5238.3  399.14  5286.6406.2539  5325.1  407.19
#Mann= 8 ,-1 , 0
  4563.4     .16       0    4812     .16       0  4865.8     .16       0
  4969.4     .16       0    4997     .16       0    5003     .16       0
    5127     .16       0  5286.6     .16       0
Bank Sta=4976,5055.3
XS Rating Curve= 0 ,0
Exp/Cntr=0.3,0.1

Type RM Length L Ch R = 1 ,83521   ,81,81,81
BEGIN DESCRIPTION:
TOWN CREEK 135.0
END DESCRIPTION:
XS GIS Cut Line= 2
      3752952.28     10627180.82       3752775.2     10628011.56
#Sta/Elev= 30
  4582.3  416.68  4662.7  404.65  4667.8   405.5  4724.8   398.9  4775.9  395.73
  4915.2392.1324    4960   389.7  4970.2  382.08  4980.4   379.7  4990.6  374.18
    4997  374.18  4999.8  373.68    5003  374.18  5011.1  378.47  5014.6379.0568
  5031.5  383.57  5041.8  388.82  5092.9  389.26  5098.4  390.33  5123.3 388.912
  5164.5  389.73  5192.4   393.3  5197.5  392.19  5225.8  398.23  5249.4 399.571
    5313402.7459  5348.5  404.49  5379.2  409.36  5412.4409.2012  5431.7  408.96
#Mann= 9 ,-1 , 0
  4582.3     .16       0  4915.2     .16       0    4997     .16       0
    5003     .16       0  5014.6     .16       0  5123.3     .16       0
  5249.4     .16       0    5313     .16       0  5412.4     .16       0
Bank Sta=4960,5041.8
XS Rating Curve= 0 ,0
Exp/Cntr=0.3,0.1

Type RM Length L Ch R = 1 ,83440   ,707,707,707
BEGIN DESCRIPTION:
Mapping XS e9f58283
END DESCRIPTION:
XS GIS Cut Line= 2
      3752858.54     10627159.93       3752710.1     10628011.49
#Sta/Elev= 30
  4578.2  417.69  4602.5  415.73  4639.4  407.08    4657  408.34  4781.5  394.36
  4842.4  393.29  4852.5  397.17  4862.7   398.6  4872.8  394.47  4903.3  396.06
  4913.4  394.63  4926.6390.2107  4964.2   388.6  4984.5  377.55    4997  374.82
  4999.8  374.32    5003  374.82  5009.3  374.82  5014.9  379.46  5025.5379.3905
  5035.2  379.16  5055.5  387.73  5106.1387.8994  5139.8387.9657    5218  390.31
  5248.4  397.47  5322.1408.5518  5400.7  407.16    5421408.1616  5442.6  410.67
#Mann= 9 ,-1 , 0
  4578.2     .16       0  4926.6     .16       0    4997     .16       0
    5003     .16       0  5025.5     .16       0  5106.1     .16       0
  5139.8     .16       0  5322.1     .16       0    5421     .16       0
Bank Sta=4964.2,5055.5
XS Rating Curve= 0 ,0
Exp/Cntr=0.3,0.1

Type RM Length L Ch R = 1 ,82733   ,287,287,287
BEGIN DESCRIPTION:
TOWN CREEK 134.0
END DESCRIPTION:
XS GIS Cut Line= 3
       3752252.8     10627250.28      3752235.43       10627667.
      3752322.24     10628212.15
#Sta/Elev= 30
  4711.8  405.97  4801.8  394.58  4881.9  386.44  4931.9  386.44  4981.9  382.88
    4992  373.85    4997  370.84  4999.8  370.34    5003  370.84    5022  372.18
    5032  385.73    5042  386.72    5092  385.44    5128  386.13  5142.2  385.39
  5239.6385.6093  5273.9  386.67  5294.1  388.87  5339.5396.0984  5379.1  402.08
  5385.3  403.88  5405.5  406.07  5415.6  408.85  5439.4408.9085  5539.3410.2434
  5557.4  410.79  5587.8  413.63  5639.3414.6025  5658.7  414.53  5680.9  417.49
#Mann= 8 ,-1 , 0
  4711.8     .16       0    4997     .16       0    5003     .16       0
  5239.6     .16       0  5339.5     .16       0  5439.4     .16       0
  5539.3     .16       0  5639.3     .16       0
Bank Sta=4981.9,5032
XS Rating Curve= 0 ,0
Exp/Cntr=0.3,0.1

Type RM Length L Ch R = 1 ,82446   ,453,453,453
BEGIN DESCRIPTION:
TOWN CREEK 133.0
END DESCRIPTION:
XS GIS Cut Line= 3
      3752082.65     10627239.93       3751926.4     10627705.19
      3751655.55     10628173.97
#Sta/Elev= 30
  4775.7  410.61  4833.2  404.91  4859.4  398.07  4864.7  398.98  4896.2  393.78
  4902.6  390.69  4976.4   380.2  4985.6  378.71    4997  369.84  4999.8  369.34
    5003  369.84  5017.1  370.29  5022.4  377.38  5029.1  378.79  5048.6  374.94
  5053.9  378.33  5071.3  377.99  5080.1  374.51  5092.4  381.74    5103  382.51
    5180  381.35  5206.3  383.99  5412.1384.9214  5503.2  389.15    5531  399.07
  5537.9  403.91  5554.3404.7166  5623.9406.4876  5775.9408.6571  5807.9   410.2
#Mann= 7 ,-1 , 0
  4775.7     .16       0    4997     .16       0    5003     .16       0
  5412.1     .16       0  5554.3     .16       0  5623.9     .16       0
  5775.9     .16       0
Bank Sta=4976.4,5029.1
XS Rating Curve= 0 ,0
Exp/Cntr=0.3,0.1

Type RM Length L Ch R = 1 ,81993   ,467,467,467
BEGIN DESCRIPTION:
TOWN CREEK 132.0
END DESCRIPTION:
XS GIS Cut Line= 3
      3751949.63     10627110.18      3751699.61     10627160.19
      3751499.59      10627260.2
#Sta/Elev= 30
  4778.8  412.61  4802.9409.7515  4860.4  401.81    4891   395.7  4901.2  394.83
  4911.4  391.62    4942  387.66  4952.2  385.24  4962.4  378.72  4982.8  376.92
    4993  369.69    4997   368.2  4999.8   367.7    5003   368.2  5013.4  375.08
  5023.6   376.7  5031.2  380.19  5047.8  379.37  5070.1  380.39  5092.5  378.57
  5123.2  378.34    5154  380.89  5167.9  380.75  5190.3  383.98  5204.3  388.38
    5221   391.2  5226.6  391.08  5243.4  394.88  5250.8  394.71  5257.4  394.52
#Mann= 5 ,-1 , 0
  4778.8     .16       0  4802.9     .16       0    4997     .16       0
    5003     .16       0  5250.8     .16       0
Bank Sta=4982.8,5013.4
XS Rating Curve= 0 ,0
Exp/Cntr=0.3,0.1

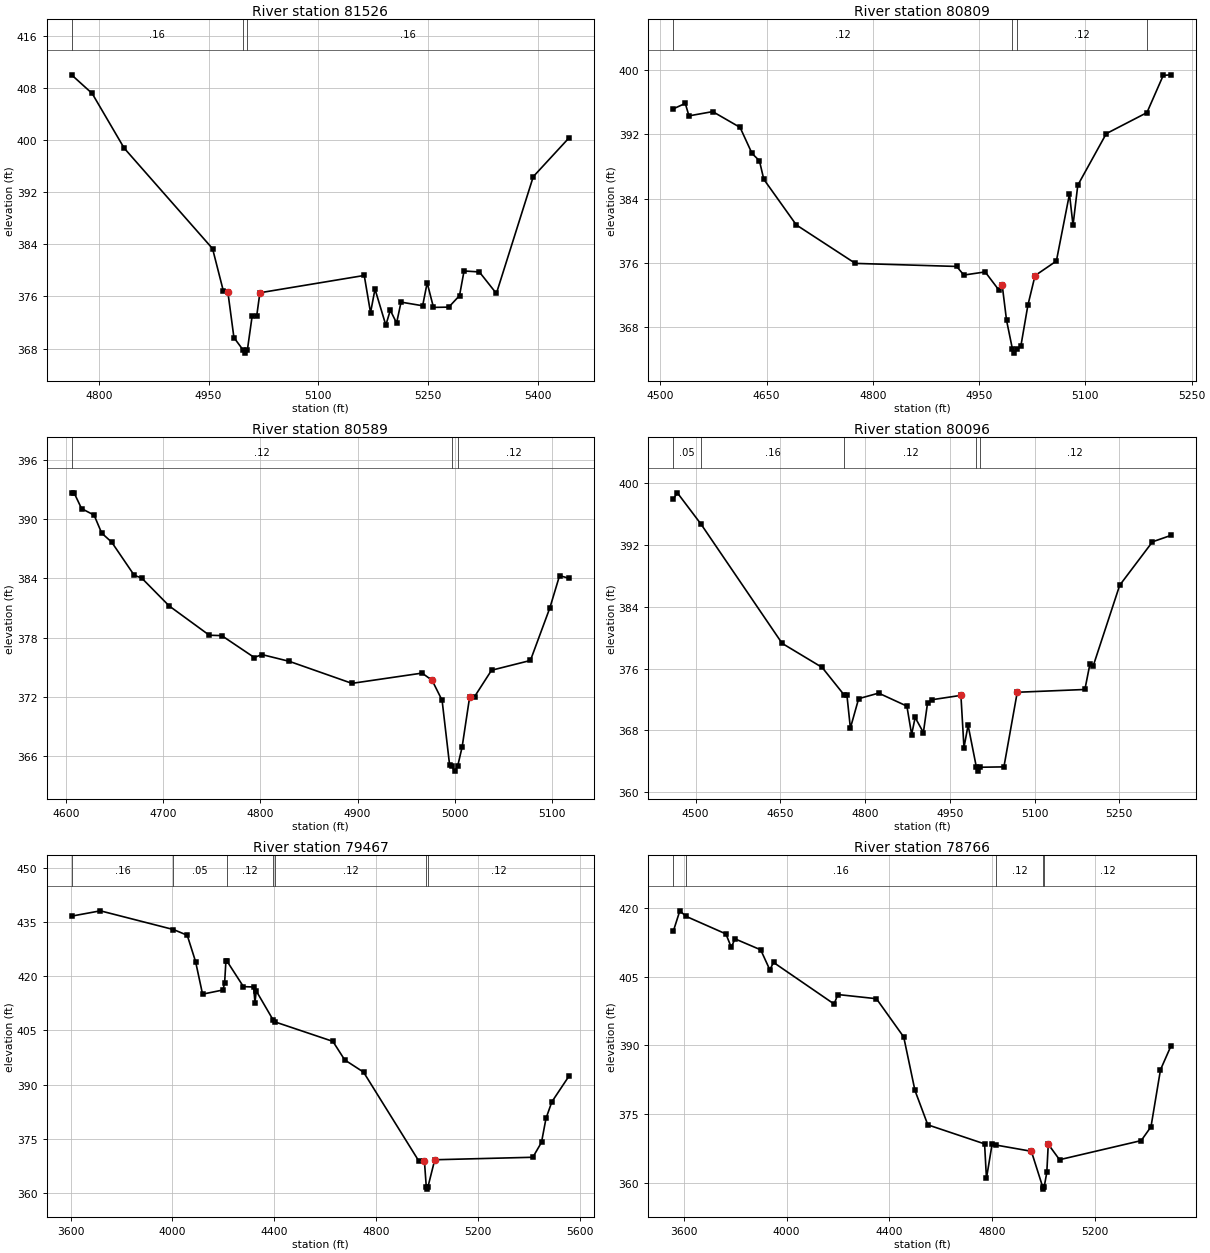
Type RM Length L Ch R = 1 ,81526   ,717,717,717
BEGIN DESCRIPTION:
TOWN CREEK 131.0
END DESCRIPTION:
XS GIS Cut Line= 3
      3751649.63     10626560.16      3751499.61     10626760.19
      3751249.58     10627110.23
#Sta/Elev= 30
  4762.7  410.07  4790.9   407.2  4834.6   398.8  4955.4  383.35    4970  376.91
  4976.3   376.7  4984.6  369.68    4997  367.79  4999.8  367.29    5003  367.79
  5009.6  373.06  5015.8  373.06  5020.1  376.57  5162.7  379.23  5171.3   373.5
  5177.4  377.13  5192.2  371.59  5198.3  373.88  5206.9  371.92    5213  375.13
  5242.5  374.57  5248.7   378.1  5257.3  374.32  5278.2  374.36  5292.9  376.13
  5299.1  379.92    5320  379.77  5343.3  376.46  5393.7  394.42  5442.9  400.42
#Mann= 3 ,-1 , 0
  4762.7     .16       0    4997     .16       0    5003     .16       0
Bank Sta=4976.3,5020.1
XS Rating Curve= 0 ,0
Exp/Cntr=0.3,0.1

Type RM Length L Ch R = 1 ,80809   ,220,220,220
BEGIN DESCRIPTION:
TOWN CREEK 130.0
END DESCRIPTION:
XS GIS Cut Line= 3
       3751506.3     10626441.31      3751197.24     10626351.02
      3750818.74     10626389.22
#Sta/Elev= 30
  4518.3  395.16  4535.3  395.84  4540.5  394.29    4574  394.82  4612.6  392.86
  4629.5  389.62  4639.9  388.72  4646.1  386.41    4692  380.74  4775.3  375.96
  4918.3  375.58  4928.4  374.51  4958.5   374.9  4977.5  372.69  4982.5  373.29
  4988.7  368.88    4997  365.31  4999.8  364.81    5003  365.31  5008.8  365.64
  5018.8  370.76  5028.9  374.44    5059  376.25  5077.5  384.58  5082.5   380.7
  5089.2  385.67  5129.4  392.08  5186.8394.6935  5209.8  399.32  5220.7  399.39
#Mann= 4 ,-1 , 0
  4518.3     .12       0    4997     .07       0    5003     .12       0
  5186.8     .07       0
Bank Sta=4982.5,5028.9
XS Rating Curve= 0 ,0
Exp/Cntr=0.3,0.1

Type RM Length L Ch R = 1 ,80589   ,493,493,493
BEGIN DESCRIPTION:
TOWN CREEK 129.0
END DESCRIPTION:
XS GIS Cut Line= 3
      3751499.64      10626260.2      3751099.61     10626160.19
      3750999.65     10626160.19
#Sta/Elev= 30
  4605.6  392.68  4608.2  392.68  4615.9  391.08  4628.8  390.42  4636.6   388.6
  4646.9  387.68  4670.1  384.32  4677.8  384.04  4706.1  381.21  4747.4  378.24
  4760.2   378.2  4793.7  375.98  4801.5  376.28  4829.8  375.59  4894.2  373.36
  4966.4   374.4  4976.7  373.67    4987  371.64  4994.7   365.1    4997  364.96
  4999.8  364.46    5003  364.96  5007.6   366.9  5015.4  372.01  5020.4  372.01
  5037.9  374.69  5077.9  375.68  5097.9  381.01  5107.9  384.28  5117.9  384.01
#Mann= 3 ,-1 , 0
  4605.6     .12       0    4997     .07       0    5003     .12       0
Bank Sta=4976.7,5015.4
XS Rating Curve= 0 ,0
Exp/Cntr=0.3,0.1

Type RM Length L Ch R = 1 ,80096   ,629,629,629
BEGIN DESCRIPTION:
TOWN CREEK 128.0
END DESCRIPTION:
XS GIS Cut Line= 3
      3751599.61     10626210.19      3751199.61     10625910.19
      3750849.59     10625760.18
#Sta/Elev= 30
  4460.5   397.9  4467.8  398.71  4509.8  394.65  4653.2  379.26    4724  376.15
  4763.5372.5434  4767.8  372.62    4774  368.31  4788.6  372.11    4824  372.83
    4874  371.15  4882.4  367.48  4888.6  369.68  4903.2  367.74  4910.5  371.53
  4917.8  371.97  4969.6  372.54    4975  365.79  4982.3  368.68    4997  363.25
  4999.8  362.75    5003  363.25  5045.7   363.3  5069.3  372.94    5189   373.3
    5198  376.63  5203.5  376.29  5250.6  386.77  5308.6  392.38  5341.3  393.21
#Mann= 5 ,-1 , 0
  4460.5     .05       0  4509.8     .16       0  4763.5     .12       0
    4997     .07       0    5003     .12       0
Bank Sta=4969.6,5069.3
XS Rating Curve= 0 ,0
Exp/Cntr=0.3,0.1

Type RM Length L Ch R = 1 ,79467   ,701,701,701
BEGIN DESCRIPTION:
TOWN CREEK 127.0
END DESCRIPTION:
XS GIS Cut Line= 3
      3752742.38     10625344.08      3751436.82     10625455.19
      3750850.04     10625722.54
#Sta/Elev= 30
  3603.5  436.61  3716.7  438.08  4003.8432.8968  4057.9  431.32  4090.7  424.02
  4118.1  415.01  4198.4  416.17  4204.8  418.18  4209.8  424.14  4214.3424.1193
  4278.7  417.09  4318.8     417    4324  412.68    4329   415.9  4395.3407.8744
  4402.3407.3372    4630  401.94  4676.5  396.81  4750.4  393.43  4966.6  368.93
  4989.6  368.79    4997  361.54  4999.8  361.04    5003  361.54  5030.2  369.17
  5415.5  369.86  5449.5  373.99  5467.1   380.6  5490.1   385.2  5558.6  392.45
#Mann= 7 ,-1 , 0
  3603.5     .16       0  4003.8     .05       0  4214.3     .12       0
  4395.3     .07       0  4402.3     .12       0    4997     .07       0
    5003     .12       0
Bank Sta=4989.6,5030.2
XS Rating Curve= 0 ,0
Exp/Cntr=0.3,0.1

Type RM Length L Ch R = 1 ,78766   ,271,271,271
BEGIN DESCRIPTION:
TOWN CREEK 126.0
END DESCRIPTION:
XS GIS Cut Line= 3
      3751898.65      10624062.8       3751113.9     10625114.91
      3750819.26     10625666.06
#Sta/Elev= 30
  3558.9  414.88  3584.6  419.39  3608.2418.2022  3763.9  414.35  3784.8  411.44
  3799.4  413.27  3899.4  410.88  3934.9  406.52  3949.5  408.12  4185.1  399.05
  4199.7  401.12  4349.8  400.21  4456.1  391.86  4499.9  380.18  4549.9  372.68
  4770.9  368.52  4778.2  360.99  4800.1  368.45  4817.1  368.25    4953  366.91
    4997  359.15  4999.8  358.65    5003  359.15  5013.1  362.29  5018.8  368.45
  5062.7  365.07  5380.5  369.24  5418.7  372.26  5455.7  384.71  5496.4  389.89
#Mann= 5 ,-1 , 0
  3558.9     .05       0  3608.2     .16       0  4817.1     .12       0
    4997     .07       0    5003     .12       0
Bank Sta=4953,5018.8
XS Rating Curve= 0 ,0
Exp/Cntr=0.3,0.1