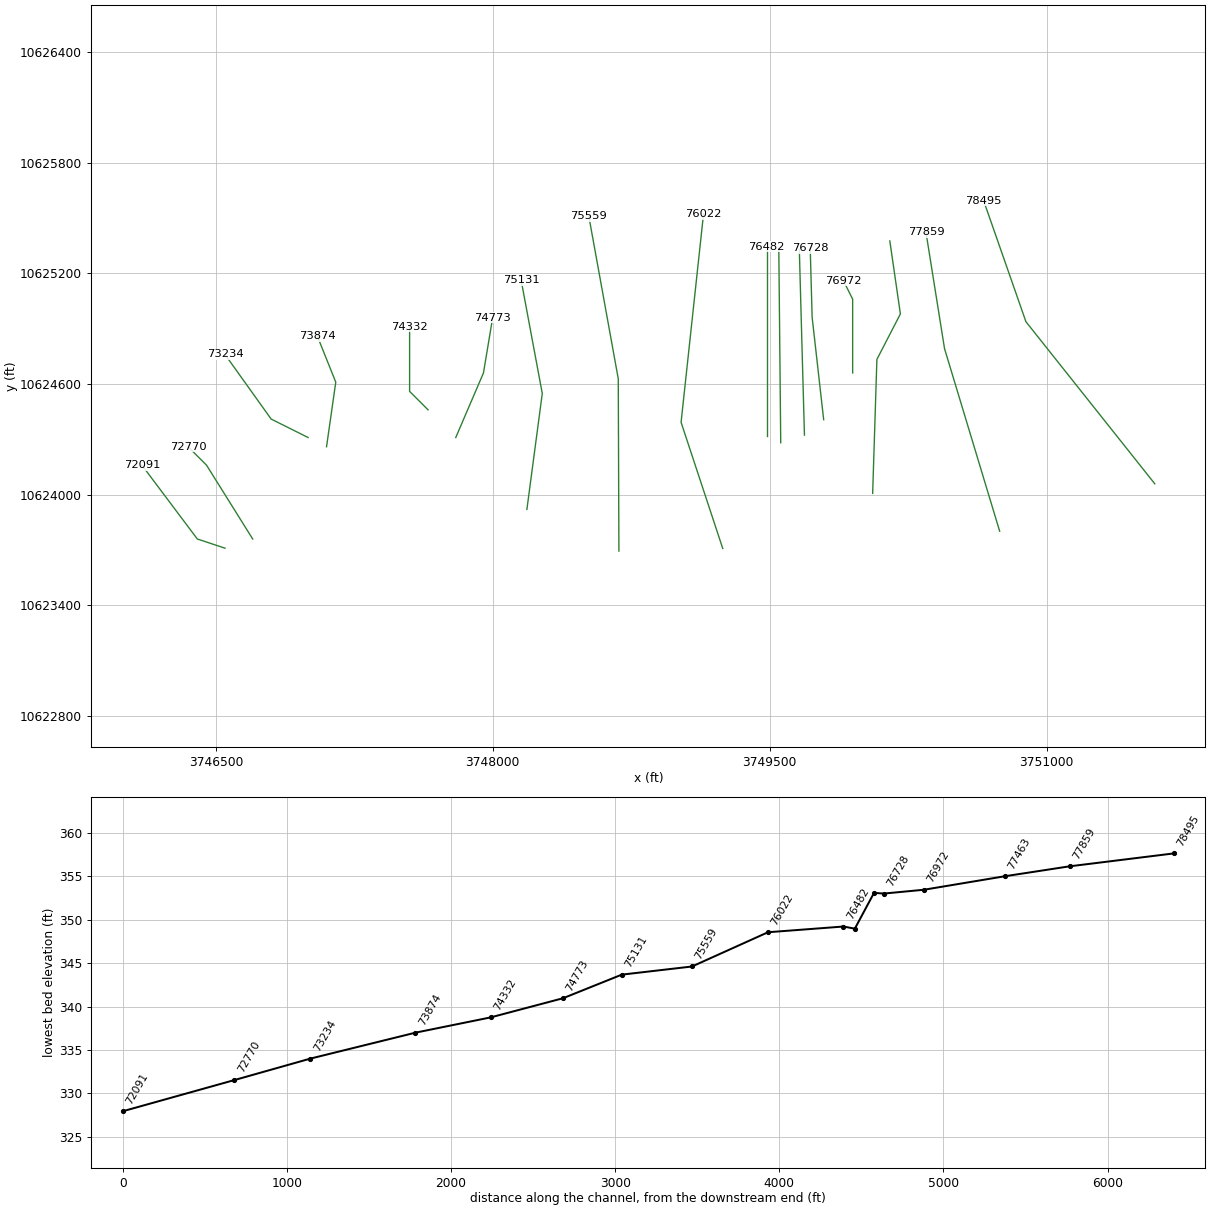
HEC-RAS study TOWN CREEK.prj: TOWN CREEK Base Level Engineering

--- TOWN CREEK.g01 (geometry) --- (continued)

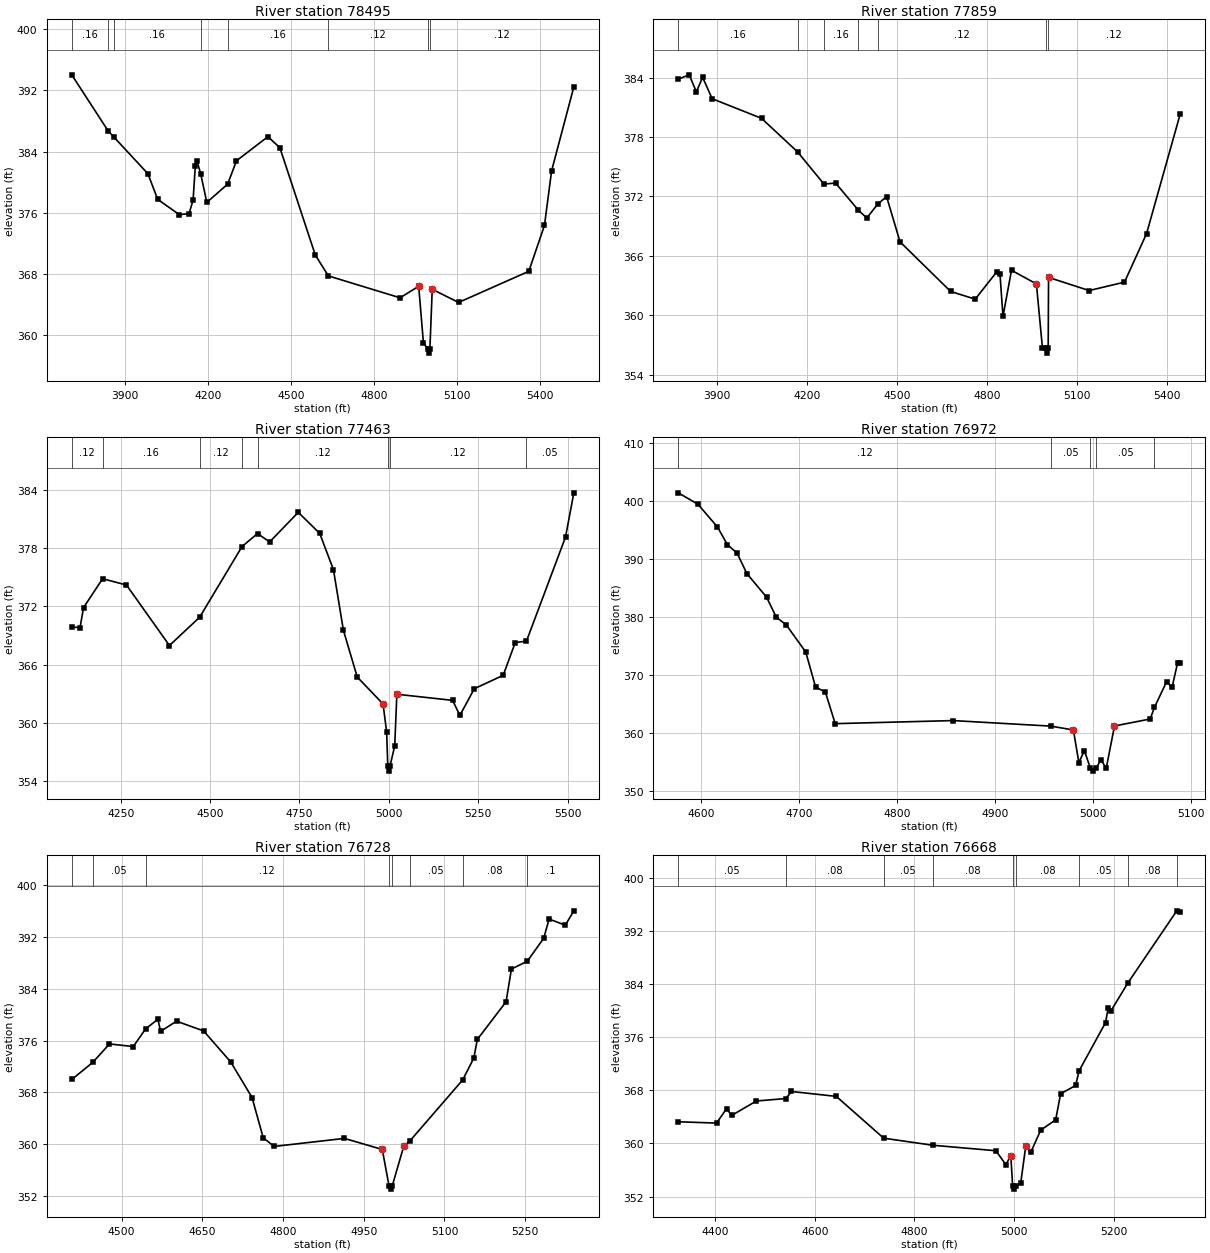
Type RM Length L Ch R = 1 ,78495   ,636,636,636
BEGIN DESCRIPTION:
TOWN CREEK 125.0
END DESCRIPTION:
XS GIS Cut Line= 3
      3751586.11     10624059.38      3750888.21     10624937.83
      3750659.06     10625594.03
#Sta/Elev= 30
    3707  394.02    3839386.6692  3859.3385.8953  3982.7  381.09  4017.9  377.75
  4096.4  375.75  4131.6  375.89  4146.1  377.68  4154.1   382.1  4160.5  382.72
  4173.6381.0842  4195.7  377.35    4271 379.735  4303.1  382.79  4416.8  385.94
  4460.1   384.5  4588.2  370.49  4635.6367.7477    4895  364.89  4962.5  366.39
  4979.7  358.98    4997  358.16  4999.8  357.66    5003  358.16  5011.5     366
  5106.8  364.28    5361  368.35  5417.7  374.35  5443.5  381.48    5524  392.45
#Mann= 8 ,-1 , 0
    3707     .16       0    3839     .12       0  3859.3     .16       0
  4173.6     .12       0    4271     .16       0  4635.6     .12       0
    4997     .07       0    5003     .12       0
Bank Sta=4962.5,5011.5
XS Rating Curve= 0 ,0
Exp/Cntr=0.3,0.1

Type RM Length L Ch R = 1 ,77859   ,396,396,396
BEGIN DESCRIPTION:
TOWN CREEK 124.0
END DESCRIPTION:
XS GIS Cut Line= 3
      3750745.86     10623802.38      3750447.24       10624792.
      3750346.55     10625423.93
#Sta/Elev= 30
  3769.8  383.84  3806.4  384.28  3830.2  382.56  3851.1  384.03  3882.8  381.87
  4047.7  379.88  4167.9376.4867  4255.6373.2425  4294.2  373.35  4370.4370.6037
  4398.3  369.82  4435.1371.2346  4464.3  371.98  4509.1  367.41  4677.8   362.4
  4759.8  361.62    4832   364.4  4842.2  364.19  4852.3  359.88  4880.7  364.54
  4963.7  363.16  4983.9  356.67    4997  356.67  4999.8  356.17    5003  356.67
  5004.2  363.82  5139.4  362.49  5257.3  363.34  5330.9  368.24  5443.4  380.36
#Mann= 7 ,-1 , 0
  3769.8     .16       0  4167.9     .12       0  4255.6     .16       0
  4370.4     .05       0  4435.1     .12       0    4997     .07       0
    5003     .12       0
Bank Sta=4963.7,5004.2
XS Rating Curve= 0 ,0
Exp/Cntr=0.3,0.1

Type RM Length L Ch R = 1 ,77463   ,491,491,491
BEGIN DESCRIPTION:
TOWN CREEK 123.0
END DESCRIPTION:
XS GIS Cut Line= 4
      3750057.91     10624007.23      3750080.85     10624733.56
      3750208.13     10624980.16      3750150.89     10625375.64
#Sta/Elev= 30
  4113.4  369.88  4136.4  369.79  4146.4  371.87  4199.6 374.842  4266.4  374.19
  4386.5  367.96    4471370.8765  4589.5 378.159  4632.8379.4962  4666.6  378.63
  4746.7  381.68  4806.7  379.51  4845.1  375.76  4872.9  369.53  4911.6  364.71
  4983.7  361.94  4993.8  359.05    4997  355.52  4999.8  355.02    5003  355.52
  5016.4  357.62  5022.3  362.94  5178.3  362.31  5198.5  360.76  5238.9  363.51
  5319.7  364.89  5353.4  368.27  5384.7368.4091  5493.9  379.13  5517.2  383.69
#Mann= 8 ,-1 , 0
  4113.4     .12       0  4199.6     .16       0    4471     .12       0
  4589.5     .08       0  4632.8     .12       0    4997     .07       0
    5003     .12       0  5384.7     .05       0
Bank Sta=4983.7,5022.3
XS Rating Curve= 0 ,0
Exp/Cntr=0.3,0.1

Type RM Length L Ch R = 1 ,76972   ,244,244,244
BEGIN DESCRIPTION:
TOWN CREEK 122.0
END DESCRIPTION:
XS GIS Cut Line= 3
      3749949.61     10624660.18      3749949.61     10625060.19
      3749899.62     10625160.17
#Sta/Elev= 30
  4576.9  401.37  4596.9  399.42  4616.9  395.49  4626.9  392.47  4636.9  390.99
  4646.9  387.46  4666.9  383.42  4676.9  379.95  4686.9  378.67  4706.9  373.96
  4716.9  367.95  4726.9  367.07  4736.9  361.64  4856.9  362.17  4956.7361.2174
  4979.7  360.55  4985.3  354.93  4990.9  357.01    4997  353.97  4999.8  353.47
    5003  353.97  5007.7  355.44  5013.2  353.97  5021.6  361.24    5058  362.44
  5062.3364.4312  5074.7  368.86  5080.3  367.91  5085.9  372.07  5088.7  372.07
#Mann= 5 ,-1 , 0
  4576.9     .12       0  4956.7     .05       0    4997     .04       0
    5003     .05       0  5062.3     .08       0
Bank Sta=4979.7,5021.6
XS Rating Curve= 0 ,0
Exp/Cntr=0.3,0.1

Type RM Length L Ch R = 1 ,76728   ,60,60,60
BEGIN DESCRIPTION:
Mapping XS 06a6a46c
END DESCRIPTION:
XS GIS Cut Line= 3
      3749792.56     10624406.58      3749730.06      10624962.1
      3749719.67     10625336.13
#Sta/Elev= 30
  4407.3  369.98  4446.3372.6174  4477.4  375.47  4521.6  375.07  4544.5377.7964
  4567.4  379.29  4572.4  377.42  4602.1  378.99  4652.4  377.48  4702.8  372.68
  4742.4  367.19  4763.1  360.97  4783.3  359.63  4914.1  360.87  4984.4  359.16
    4997  353.53  4999.8  353.03    5003  353.53  5024.4  359.68  5035.7360.4765
  5133.7369.8884  5154.5  373.27  5161.1  376.17  5214.5  381.99  5224.5  387.06
  5253.8388.2413  5284.5  391.81  5294.5  394.78  5324.6  393.83  5340.5  396.05
#Mann= 8 ,-1 , 0
  4407.3     .16       0  4446.3     .05       0  4544.5     .12       0
    4997     .07       0    5003     .12       0  5035.7     .05       0
  5133.7     .08       0  5253.8      .1       0
Bank Sta=4984.4,5024.4
XS Rating Curve= 0 ,0
Exp/Cntr=0.3,0.1

Type RM Length L Ch R = 1 ,76668   ,117,117,117
BEGIN DESCRIPTION:
Mapping XS 91c78343
END DESCRIPTION:
XS GIS Cut Line= 2
       3749688.4     10624323.23      3749660.62     10625330.15
#Sta/Elev= 30
  4326.1  363.25  4403.1  363.05  4423.1  365.24  4433.1   364.2  4483.1  366.38
  4542.3366.7464  4553.1  367.81  4643.2  367.07  4738.3360.7788  4836.3359.7193
  4963.3  358.89  4983.3  356.81  4993.3  358.13    4997  353.61  4999.8  353.11
    5003  353.61  5013.3  354.07  5023.3  359.57  5033.3  358.63  5053.3  361.99
  5083.3  363.54  5093.3  367.47  5123.4  368.71  5130.3 370.918  5183.4  378.18
  5188.6  380.35  5193.6  379.86  5228.3384.1601  5326.3395.0027  5333.4  394.88
#Mann= 9 ,-1 , 0
  4326.1     .05       0  4542.3     .08       0  4738.3     .05       0
  4836.3     .08       0    4997     .07       0    5003     .08       0
  5130.3     .05       0  5228.3     .08       0  5326.3     .05       0
Bank Sta=4993.3,5023.3
XS Rating Curve= 0 ,0
Exp/Cntr=0.3,0.1

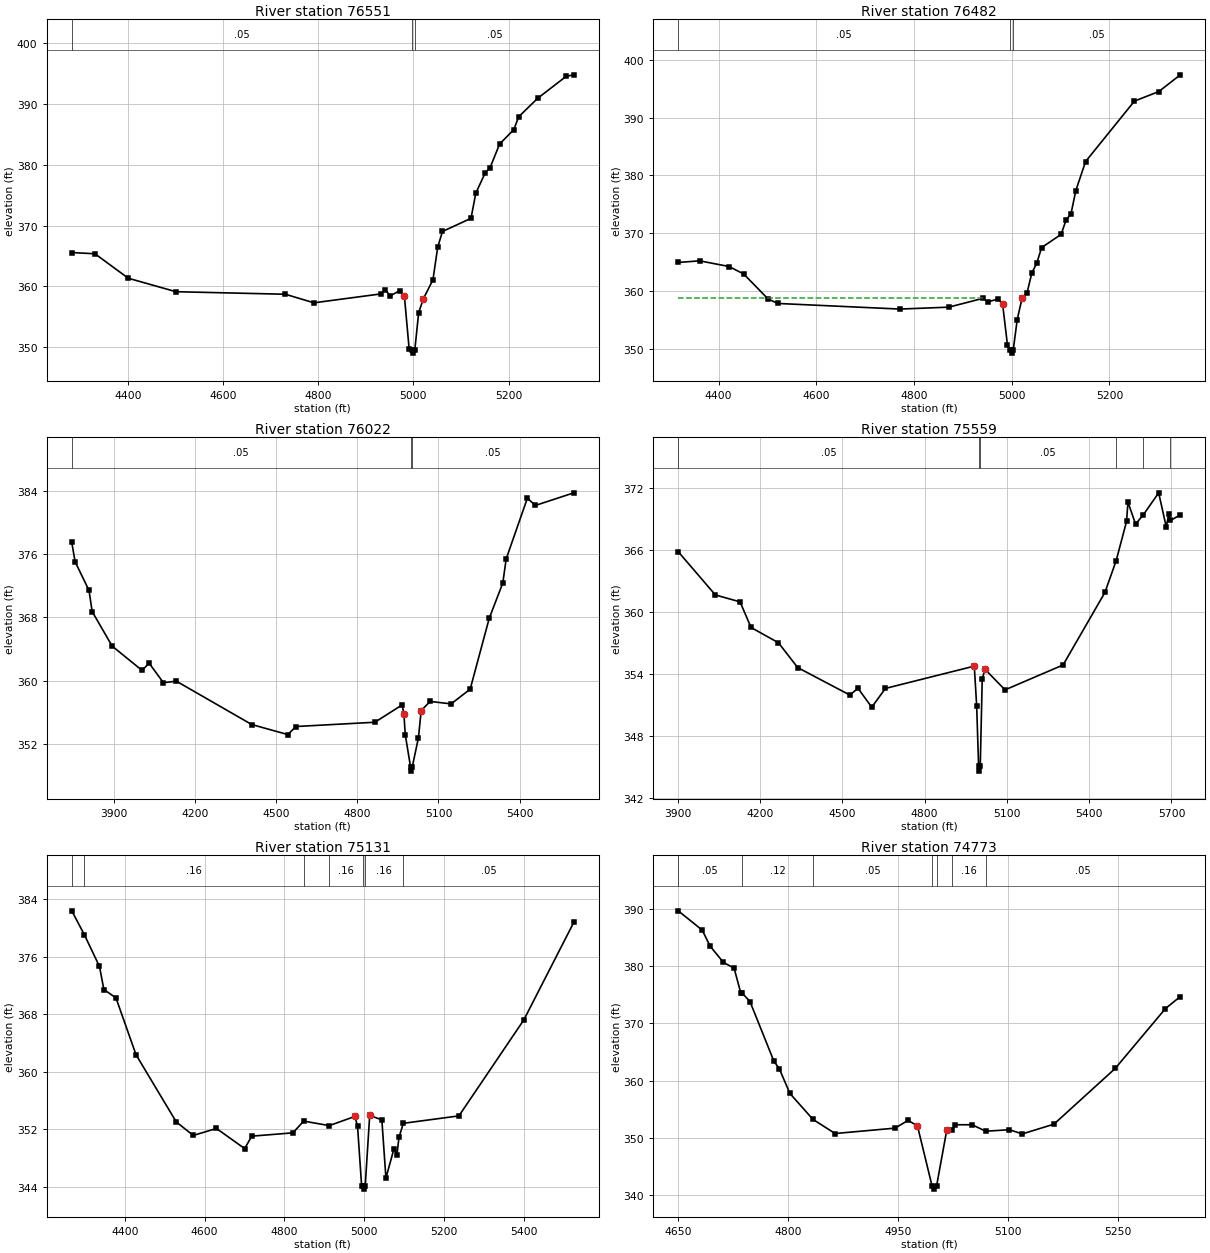
Type RM Length L Ch R = 1 ,76551   ,69,69,69
BEGIN DESCRIPTION:
TOWN CREEK 121.0
END DESCRIPTION:
XS GIS Cut Line= 2
      3749559.93     10624281.51      3749549.52     10625336.16
#Sta/Elev= 30
  4282.4  365.55  4331.1  365.35  4401.1  361.32  4501.1   359.1  4731.1  358.68
  4791.1  357.27  4931.1  358.73  4941.1  359.46  4951.1   358.4  4971.1  359.27
  4981.1   358.4  4991.1  349.68    4997  349.48  4999.8  348.98    5003  349.48
  5011.1  355.64  5021.1  357.96  5041.1  361.05  5051.1  366.43  5061.1  369.02
  5121.1  371.19  5131.1  375.32  5151.1  378.72  5161.1  379.53  5181.1  383.42
  5211.1  385.82  5221.1  387.91  5261.1  390.96  5321.1  394.59  5337.1  394.83
#Mann= 3 ,-1 , 0
  4282.4     .05       0    4997     .03       0    5003     .05       0
Bank Sta=4981.1,5021.1
XS Rating Curve= 0 ,0
Exp/Cntr=0.3,0.1

Type RM Length L Ch R = 1 ,76482   ,460,460,460
BEGIN DESCRIPTION:
Mapping XS c1ddb908
END DESCRIPTION:
XS GIS Cut Line= 2
      3749483.54     10624316.25      3749483.54     10625344.05
#Sta/Elev= 30
  4317.3  364.93  4361.2  365.21  4421.2  364.23  4451.2  362.94  4501.2  358.61
  4521.2  357.83  4771.2  356.86  4871.2  357.19  4941.2  358.72  4951.2  358.09
  4971.2   358.6  4981.2  357.82  4991.2  350.67    4997  349.73  4999.8  349.23
    5003  349.73  5011.2  355.01  5021.2  358.79  5031.2  359.61  5041.2  363.13
  5051.2   364.8  5061.2  367.51  5101.2   369.8  5111.2  372.29  5121.2  373.32
  5131.2  377.38  5151.2  382.41  5251.2  392.87  5301.2  394.53  5345.1  397.42
#Mann= 3 ,-1 , 0
  4317.3     .05       0    4997     .03       0    5003     .05       0
#XS Ineff= 2 , 0
         4942.57  358.81
Permanent Ineff=
       F       F
Bank Sta=4981.2,5021.2
XS Rating Curve= 0 ,0
Exp/Cntr=0.3,0.1

Type RM Length L Ch R = 1 ,76022   ,463,463,463
BEGIN DESCRIPTION:
TOWN CREEK 120.0
END DESCRIPTION:
XS GIS Cut Line= 3
      3749245.86     10623708.63      3749020.15     10624392.69
      3749141.68     10625521.13
#Sta/Elev= 30
    3745  377.48  3757.2  375.05  3808.7  371.41  3820.4  368.74  3894.1  364.38
  4004.5  361.31    4031  362.21  4083.6  359.75  4131.5  359.94    4410  354.46
  4543.3  353.19  4573.5  354.21  4865.1  354.75  4965.7  356.94  4972.3  355.82
  4977.3   353.2    4997  349.07  4999.8  348.57    5003  349.07  5026.1   352.8
  5036.1  356.22  5069.3  357.38  5146.8  357.07  5217.2  358.93  5287.6  367.89
  5337.8  372.35  5350.2  375.39  5428.4  383.06  5458.5  382.16  5600.3  383.75
#Mann= 3 ,-1 , 0
    3745     .05       0    4997     .03       0    5003     .05       0
Bank Sta=4972.3,5036.1
XS Rating Curve= 0 ,0
Exp/Cntr=0.3,0.1

Type RM Length L Ch R = 1 ,75559   ,428,428,428
BEGIN DESCRIPTION:
TOWN CREEK 119.0
END DESCRIPTION:
XS GIS Cut Line= 3
      3748683.35     10623694.76      3748679.88      10624628.8
      3748520.16     10625510.71
#Sta/Elev= 30
    3902  365.87  4037.4  361.68  4127.4  361.01  4167.4  358.53  4267.4  357.05
  4337.4  354.65  4527.4  351.99  4557.4  352.64  4607.4  350.81  4657.4  352.63
  4981.3  354.79  4989.9  350.94    4997  345.12  4999.8  344.62    5003  345.12
  5010.2  353.57  5020.4  354.48  5093.3  352.49  5304.9   354.9  5457.4  361.92
  5498.6365.0153  5536.3   368.8  5541.4  370.67  5569.2  368.54  5597.5  369.44
  5653.4  371.57    5681  368.28  5691.1  369.56  5696.5368.8982  5732.3  369.43
#Mann= 6 ,-1 , 0
    3902     .05       0    4997     .03       0    5003     .05       0
  5498.6     .08       0  5597.5      .1       0  5696.5     .05       0
Bank Sta=4981.3,5020.4
XS Rating Curve= 0 ,0
Exp/Cntr=0.3,0.1

Type RM Length L Ch R = 1 ,75131   ,358,358,358
BEGIN DESCRIPTION:
TOWN CREEK 118.0
END DESCRIPTION:
XS GIS Cut Line= 3
      3748184.92      10623920.4      3748268.26     10624548.91
      3748153.67     10625163.51
#Sta/Elev= 30
    4267   382.4  4298.5 379.083  4336.5  374.66  4347.5  371.45  4377.8  370.29
  4428.2  362.37  4529.1  353.03  4571.7  351.15  4629.9  352.12  4700.6  349.32
  4718.4  351.05  4821.6  351.51  4848.6353.1446  4912.7352.5166    4977  353.79
  4983.7  352.44  4993.9  344.18    4997  344.18  4999.8  343.68    5003  344.18
  5014.2  353.93  5044.7  353.32  5054.9  345.21  5075.2  349.33  5082.5  348.44
  5087.6  350.88  5098.6352.8376    5238  353.87  5400.8  367.23  5526.2  380.81
#Mann= 7 ,-1 , 0
    4267     .05       0  4298.5     .16       0  4848.6     .05       0
  4912.7     .16       0    4997     .07       0    5003     .16       0
  5098.6     .05       0
Bank Sta=4977,5014.2
XS Rating Curve= 0 ,0
Exp/Cntr=0.3,0.1

Type RM Length L Ch R = 1 ,74773   ,441,441,441
BEGIN DESCRIPTION:
TOWN CREEK 117.0
END DESCRIPTION:
XS GIS Cut Line= 3
       3747799.6     10624310.17      3747949.61     10624660.19
      3747999.62     10624960.24
#Sta/Elev= 30
  4650.6  389.75  4683.3  386.37  4694.1  383.56  4712.3   380.7  4726.8   379.7
  4735.8  375.42    4738   375.3  4748.5  373.84  4781.2  363.36  4788.4   362.1
  4802.9  357.74  4834.4353.1856  4864.6  350.71  4946.2  351.65  4964.3  353.01
    4977  352.03    4997  341.46  4999.8  340.96    5003  341.46  5016.9  351.27
    5024351.3614  5028.7  352.25  5051.7  352.24  5070.1351.1125  5102.4  351.37
  5120.1  350.64  5163.2  352.35  5246.8  362.12  5315.3  372.61  5335.6  374.72
#Mann= 7 ,-1 , 0
  4650.6     .05       0    4738     .12       0  4834.4     .05       0
    4997     .03       0    5003     .05       0    5024     .16       0
  5070.1     .05       0
Bank Sta=4977,5016.9
XS Rating Curve= 0 ,0
Exp/Cntr=0.3,0.1

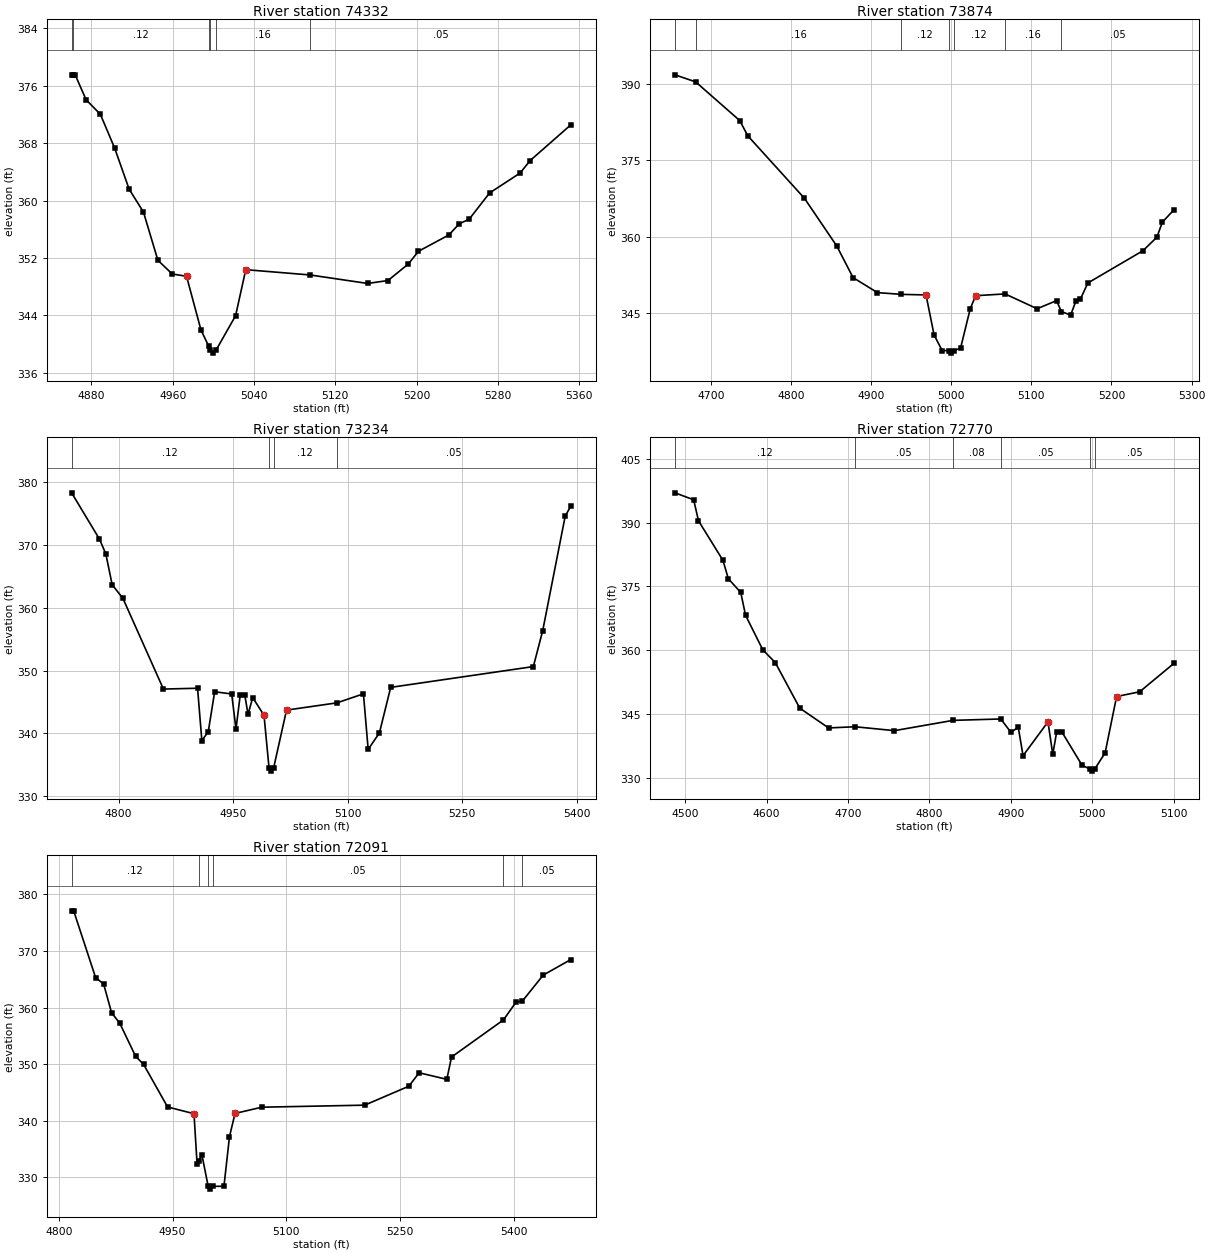
Type RM Length L Ch R = 1 ,74332   ,458,458,458
BEGIN DESCRIPTION:
TOWN CREEK 116.0
END DESCRIPTION:
XS GIS Cut Line= 3
      3747649.62     10624460.18      3747549.61     10624560.19
      3747549.61     10624910.16
#Sta/Elev= 30
  4860.5   377.5  4861.7   377.5    4864   377.5  4874.7  374.04  4888.8     372
  4902.9  367.28  4917.1  361.58  4931.2  358.39  4945.4  351.68  4959.5  349.77
  4973.6  349.45  4987.8  341.98  4995.3339.7545    4997  339.25  4999.8  338.75
    5003  339.25  5021.9  343.96  5031.9  350.37  5095.1349.6356  5151.9  348.45
  5171.9  348.86  5191.9  351.16  5201.9  352.93  5231.9  355.21  5241.9  356.74
  5251.9  357.41  5271.9  361.05  5301.9  363.82  5311.9  365.57  5351.9  370.54
#Mann= 6 ,-1 , 0
  4860.5     .16       0  4861.7     .12       0  4995.3     .16       0
    4997     .07       0    5003     .16       0  5095.1     .05       0
Bank Sta=4973.6,5031.9
XS Rating Curve= 0 ,0
Exp/Cntr=0.3,0.1

Type RM Length L Ch R = 1 ,73874   ,640,640,640
BEGIN DESCRIPTION:
TOWN CREEK 115.0
END DESCRIPTION:
XS GIS Cut Line= 3
      3747099.61     10624260.17      3747149.61     10624610.19
      3747049.62     10624860.16
#Sta/Elev= 30
  4655.4   391.9  4681.2390.5112  4736.2  382.88  4746.3  379.86    4817  367.53
  4857.4  358.09  4877.6  351.89    4908  348.93  4937.6348.5858  4968.6  348.47
  4978.7  340.57  4988.8  337.49    4997  337.49  4999.8  336.99    5003  337.49
  5011.7  337.97  5023.8  345.76  5030.5  348.32  5067.2 348.673  5107.2  345.75
  5131.5  347.35  5137.4345.2014    5149  344.49  5155.7   347.3  5161.1   347.6
  5170.5  350.83  5239.2  357.19  5256.7  359.87  5263.4  362.83  5278.2  365.31
#Mann= 7 ,-1 , 0
  4655.4     .12       0  4681.2     .16       0  4937.6     .12       0
    4997     .07       0    5003     .12       0  5067.2     .16       0
  5137.4     .05       0
Bank Sta=4968.6,5030.5
XS Rating Curve= 0 ,0
Exp/Cntr=0.3,0.1

Type RM Length L Ch R = 1 ,73234   ,464,464,464
BEGIN DESCRIPTION:
TOWN CREEK 114.0
END DESCRIPTION:
XS GIS Cut Line= 3
       3746999.6     10624310.19      3746799.61     10624410.19
      3746549.62     10624760.17
#Sta/Elev= 30
  4738.5  378.29  4774.8  370.95  4783.2  368.62  4791.6  363.66  4805.6  361.51
  4858.7  347.06  4903.4  347.19    4909  338.87  4917.4  340.26  4925.8  346.63
  4948.1  346.28  4953.7  340.67  4959.3  346.15  4965.2  346.15  4969.5  343.03
  4975.6   345.7  4990.4   342.9    4997   334.5  4999.8     334    5003   334.5
  5019.9  343.71  5085.9344.8658  5120.6   346.3  5126.8  337.46  5141.5  340.07
  5156.3  347.33  5343.1  350.64  5355.3  356.32  5384.8  374.58  5392.2  376.19
#Mann= 4 ,-1 , 0
  4738.5     .12       0    4997     .07       0    5003     .12       0
  5085.9     .05       0
Bank Sta=4990.4,5019.9
XS Rating Curve= 0 ,0
Exp/Cntr=0.3,0.1

Type RM Length L Ch R = 1 ,72770   ,679,679,679
BEGIN DESCRIPTION:
TOWN CREEK 113.0
END DESCRIPTION:
XS GIS Cut Line= 3
      3746699.61     10623760.19      3746449.61     10624160.19
      3746349.63     10624260.17
#Sta/Elev= 30
  4487.4  396.98  4510.4  395.34  4516.3   390.4  4546.4  381.08  4552.9  376.79
  4568.2  373.55  4574.1  368.18  4595.3  360.05  4610.6  357.05  4640.7  346.33
  4676.1  341.68  4708.6341.9579  4756.9  341.04    4829343.4594  4887.6 343.789
  4900.1  340.62    4909  341.87  4914.9  335.15  4945.5  343.11  4951.4  335.48
  4956.2  340.73  4962.6  340.73  4987.4  332.89    4997  332.02  4999.8  331.52
    5003  332.02  5015.7  335.83  5029.8  349.07  5058.1  350.18  5100.5  356.91
#Mann= 6 ,-1 , 0
  4487.4     .12       0  4708.6     .05       0    4829     .08       0
  4887.6     .05       0    4997     .04       0    5003     .05       0
Bank Sta=4945.5,5029.8
XS Rating Curve= 0 ,0
Exp/Cntr=0.3,0.1

Type RM Length L Ch R = 1 ,72091   ,416,416,416
BEGIN DESCRIPTION:
TOWN CREEK 112.0
END DESCRIPTION:
XS GIS Cut Line= 3
      3746549.63     10623710.18      3746399.61     10623760.19
      3746099.63     10624160.16
#Sta/Elev= 30
    4817  377.08  4819.7  377.08  4848.6  365.29  4859.2  364.15  4869.7  359.06
  4880.3  357.27  4901.3   351.4  4911.9  349.95  4943.5  342.44  4978.3  341.25
  4982.4  332.34  4984.3332.8466  4988.7  334.02    4997  328.43  4999.8  327.93
    5003  328.43  5017.8  328.43  5025.1   337.2  5032.4   341.3  5067.8   342.4
  5203.3  342.76  5261.6  346.11  5275.1  348.48  5311.6  347.32  5317.8  351.26
  5386.3357.8219  5403.3  361.04  5410.8361.0761  5438.7  365.73  5475.1  368.48
#Mann= 6 ,-1 , 0
    4817     .12       0  4984.3     .05       0    4997     .04       0
    5003     .05       0  5386.3     .16       0  5410.8     .05       0
Bank Sta=4978.3,5032.4
XS Rating Curve= 0 ,0
Exp/Cntr=0.3,0.1