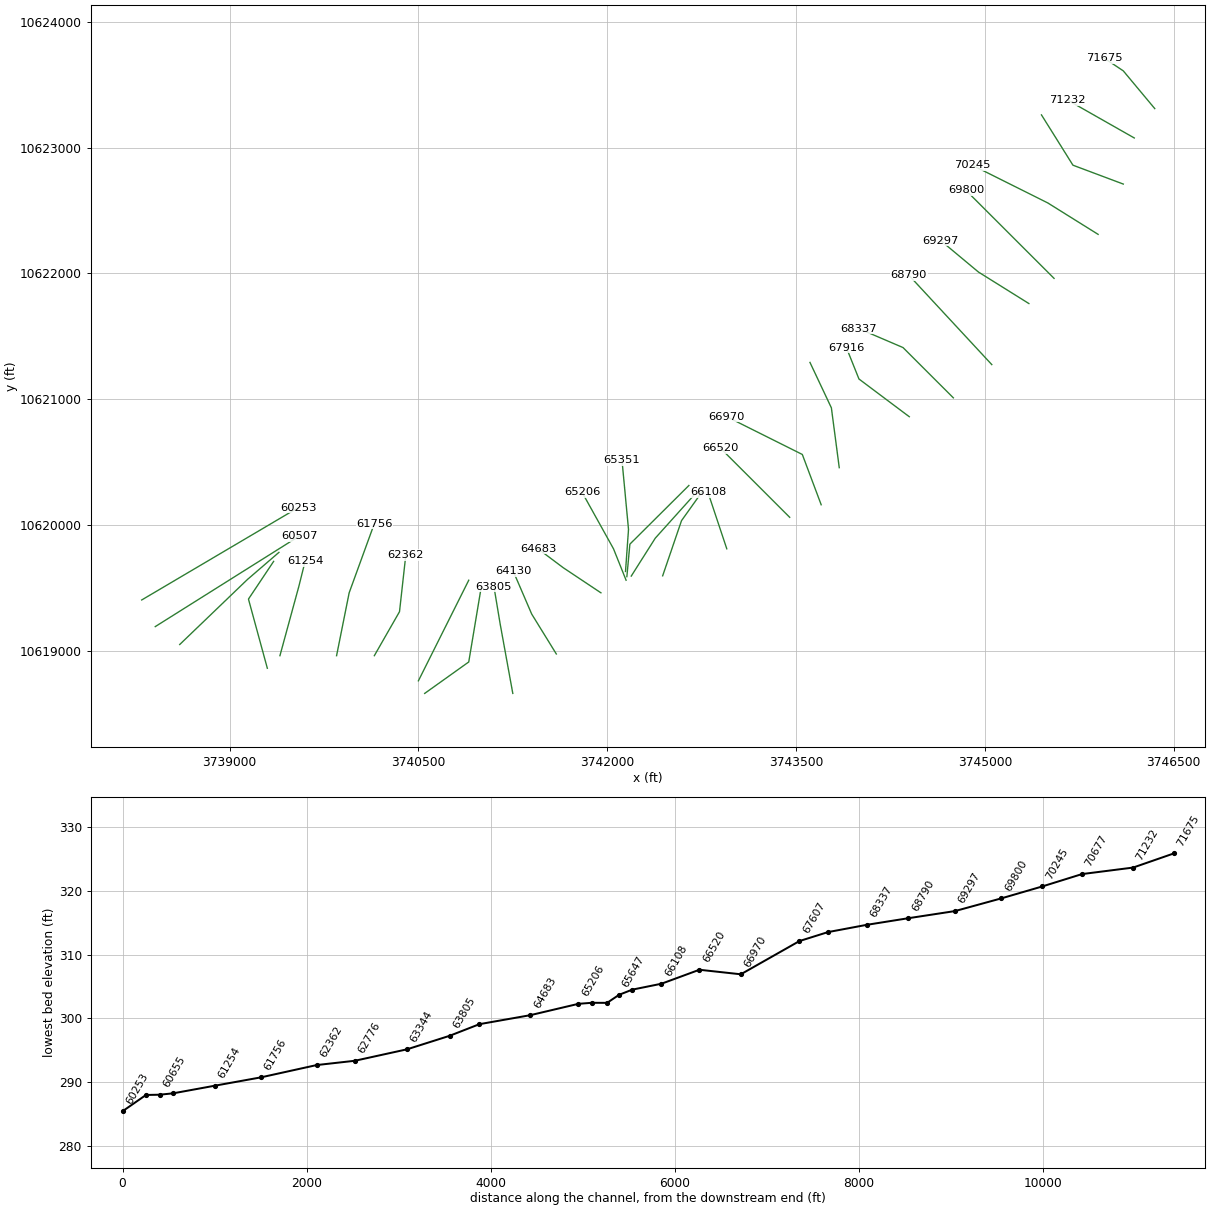
HEC-RAS study TOWN CREEK.prj: TOWN CREEK Base Level Engineering

--- TOWN CREEK.g01 (geometry) --- (continued)

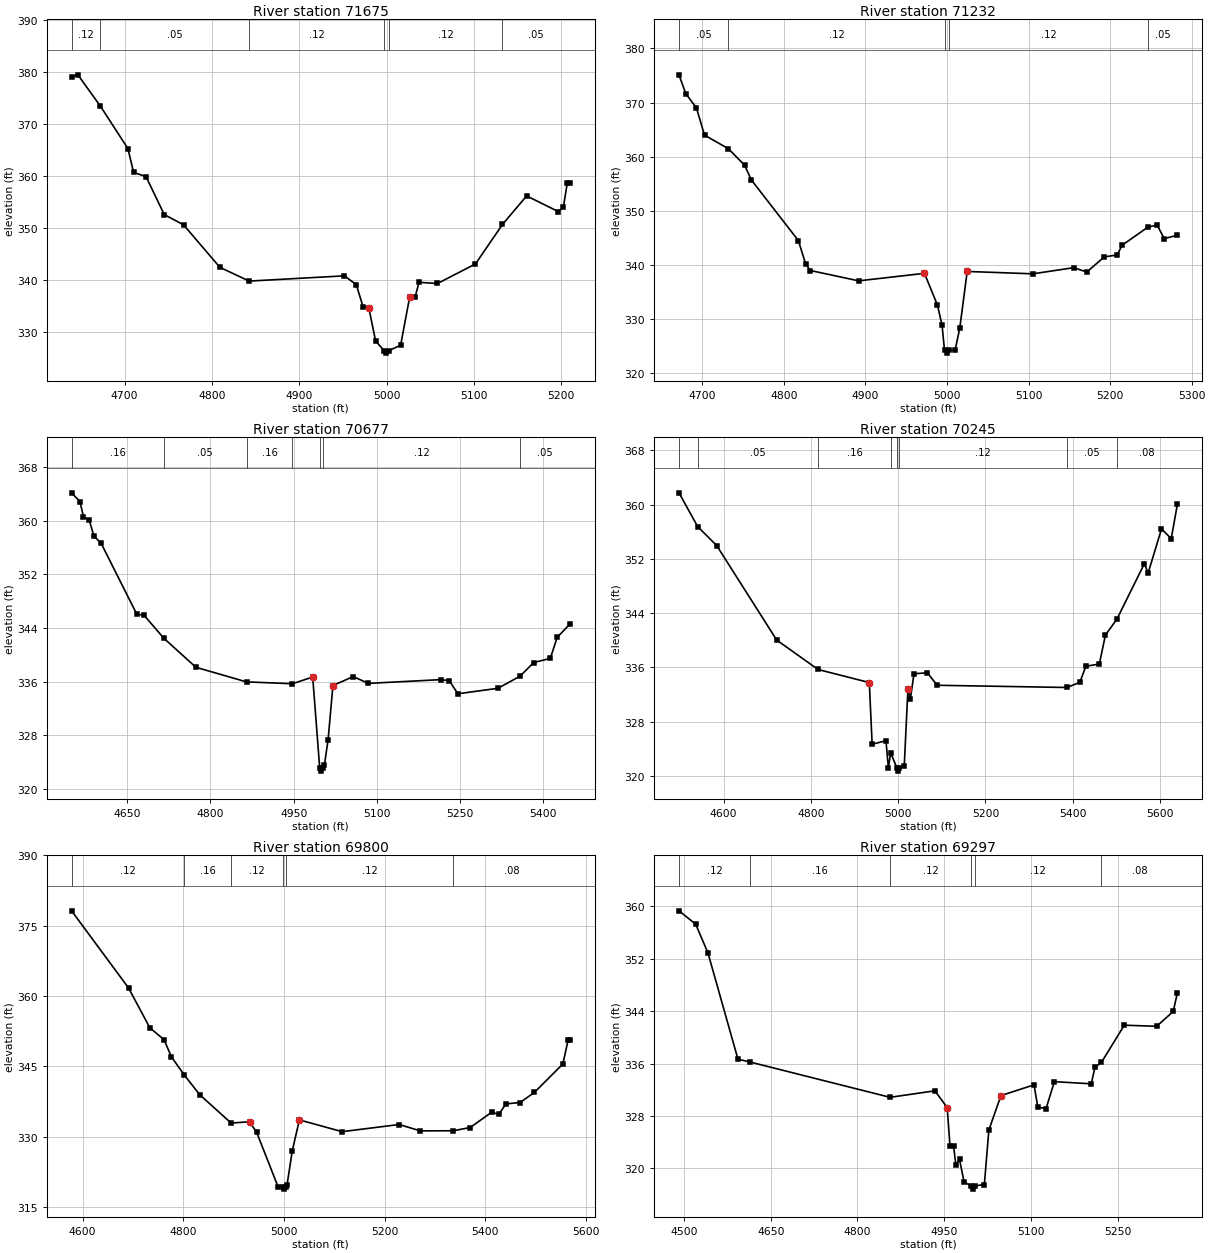
Type RM Length L Ch R = 1 ,71675   ,443,443,443
BEGIN DESCRIPTION:
TOWN CREEK 111.0
END DESCRIPTION:
XS GIS Cut Line= 3
      3746349.62     10623310.17      3746099.61     10623610.19
      3745949.62     10623710.18
#Sta/Elev= 30
  4639.2  379.04  4646.4  379.38  4672.3373.3373  4703.7   365.2  4710.2  360.64
  4724.5   359.8  4745.3  352.52  4767.4  350.54  4809.1  342.36  4842.6339.7215
  4951.6  340.73  4965.3  339.05  4973.1  334.72  4979.6  334.59  4987.4  328.21
    4997  326.37  4999.8  325.87    5003  326.37  5016.1  327.41  5026.5  336.71
  5032.7  336.71  5037.2  339.48  5058.3  339.26  5101.8  343.02  5132.7350.6078
  5160.4   356.1  5196.5   353.1  5202.5  353.93    5207  358.64    5210  358.64
#Mann= 6 ,-1 , 0
  4639.2     .12       0  4672.3     .05       0  4842.6     .12       0
    4997     .07       0    5003     .12       0  5132.7     .05       0
Bank Sta=4979.6,5026.5
XS Rating Curve= 0 ,0
Exp/Cntr=0.3,0.1

Type RM Length L Ch R = 1 ,71232   ,555,555,555
BEGIN DESCRIPTION:
TOWN CREEK 110.0
END DESCRIPTION:
XS GIS Cut Line= 2
      3746186.83     10623076.71      3745655.61     10623378.78
#Sta/Elev= 30
  4671.4  375.13  4679.7  371.65  4692.8  369.01  4702.7  363.98    4732361.4563
  4751.9   358.4  4760.2  355.67  4817.8  344.47  4826.8  340.09  4832.6  338.93
  4891.7  337.02  4972.4  338.41  4988.3  332.54    4994   328.8    4997  324.15
  4999.8  323.65    5003  324.15  5009.9  324.15  5015.7  328.29  5024.8  338.76
  5105.3  338.32  5155.5  339.46  5171.4  338.65    5193  341.46  5208.8   341.8
  5214.6  343.59  5246.8347.0027  5257.8  347.32  5266.4  344.84  5282.5  345.45
#Mann= 5 ,-1 , 0
  4671.4     .05       0    4732     .12       0    4997     .07       0
    5003     .12       0  5246.8     .05       0
Bank Sta=4972.4,5024.8
XS Rating Curve= 0 ,0
Exp/Cntr=0.3,0.1

Type RM Length L Ch R = 1 ,70677   ,432,432,432
BEGIN DESCRIPTION:
TOWN CREEK 109.0
END DESCRIPTION:
XS GIS Cut Line= 3
      3746099.62     10622710.19      3745699.61     10622860.19
      3745449.61     10623260.18
#Sta/Elev= 30
  4549.5  364.15  4564.6  362.83  4570.9   360.6  4581.5  360.03  4589.6  357.74
  4602.9   356.6    4667  346.06  4680.3  345.88  4715.9342.4515  4773.8  338.12
    4865335.9436  4947.9335.6708  4984.4  336.67    4997  323.13  4999.8  322.63
    5003  323.13  5005.6   323.6  5012.1  327.25  5020.9   335.4  5057.5  336.74
  5084.6  335.72  5215.5  336.28  5230.8  336.12  5246.2  334.17  5318.7  334.99
  5358.4336.7992    5383  338.83    5413  339.45  5425.4  342.59  5448.4  344.58
#Mann= 7 ,-1 , 0
  4549.5     .16       0  4715.9     .05       0    4865     .16       0
  4947.9     .12       0    4997     .07       0    5003     .12       0
  5358.4     .05       0
Bank Sta=4984.4,5020.9
XS Rating Curve= 0 ,0
Exp/Cntr=0.3,0.1

Type RM Length L Ch R = 1 ,70245   ,445,445,445
BEGIN DESCRIPTION:
TOWN CREEK 108.0
END DESCRIPTION:
XS GIS Cut Line= 3
      3745899.58     10622310.21      3745499.61     10622560.19
      3744899.59      10622860.2
#Sta/Elev= 30
  4497.6  361.73  4540.4356.7537  4584.2  353.94  4721.6  340.02  4816.4335.6782
  4933.9  333.75  4940.4  324.66  4972.1  325.17  4977.6  321.21    4983323.3699
    4997  321.19  4999.8  320.69    5003  321.19    5014  321.44  5022.4  332.76
    5028  331.31  5036.3  335.05  5067.1  335.19  5089.4  333.35  5387.2333.0239
  5416.5  333.79  5430.4  336.16  5461.2  336.48  5475.2  340.76  5501.6343.1115
  5564.6   351.3    5573  349.88  5603.7   356.4  5626.1  354.98  5640.1  360.02
#Mann= 8 ,-1 , 0
  4497.6     .12       0  4540.4     .05       0  4816.4     .16       0
    4983     .12       0    4997     .07       0    5003     .12       0
  5387.2     .05       0  5501.6     .08       0
Bank Sta=4933.9,5022.4
XS Rating Curve= 0 ,0
Exp/Cntr=0.3,0.1

Type RM Length L Ch R = 1 ,69800   ,503,503,503
BEGIN DESCRIPTION:
TOWN CREEK 107.0
END DESCRIPTION:
XS GIS Cut Line= 3
       3745549.6      10621960.2      3745249.61     10622260.19
      3744849.63     10622660.16
#Sta/Elev= 30
    4578  378.16  4691.1  361.72  4733.5  353.21  4761.8  350.67    4776  347.08
  4801.7343.1743  4832.5  338.95  4894.9332.9081  4931.5  333.18  4945.7  330.91
  4988.1  319.32    4997  319.32  4999.8  318.82    5003  319.32  5005.8  319.61
  5016.4  327.01  5030.5  333.58  5115.4  331.07  5228.5   332.6  5270.9  331.24
  5336.2331.2701  5369.9  331.96  5412.4  335.22  5426.5  334.76  5440.7  336.99
  5468.9  337.29  5497.2  339.43  5553.8   345.5  5564.4  350.67  5567.9  350.67
#Mann= 6 ,-1 , 0
    4578     .12       0  4801.7     .16       0  4894.9     .12       0
    4997     .07       0    5003     .12       0  5336.2     .08       0
Bank Sta=4931.5,5030.5
XS Rating Curve= 0 ,0
Exp/Cntr=0.3,0.1

Type RM Length L Ch R = 1 ,69297   ,507,507,507
BEGIN DESCRIPTION:
TOWN CREEK 106.0
END DESCRIPTION:
XS GIS Cut Line= 3
      3745349.62     10621760.18      3744949.61     10622010.19
      3744649.62     10622260.18
#Sta/Elev= 30
  4491.3  359.32  4520.2  357.28  4541.4   352.9  4593.3  336.67  4614.5  336.23
  4856.5330.8473  4934.1  331.84  4955.3  329.28  4960.1  323.48  4966.3  323.48
  4970.2  320.56  4976.7  321.36  4984.5  317.91    4997  317.33  4999.8  316.83
    5003  317.33  5019.6  317.53  5027.4  325.85  5048.3  331.11  5105.5  332.75
  5112.1  329.35  5126.4  329.13  5140.7  333.24  5204.5  332.91    5211  335.43
  5222.1336.1679  5261.7  341.86  5317.7  341.69  5346.4  343.96  5353.5  346.77
#Mann= 6 ,-1 , 0
  4491.3     .12       0  4614.5     .16       0  4856.5     .12       0
    4997     .07       0    5003     .12       0  5222.1     .08       0
Bank Sta=4955.3,5048.3
XS Rating Curve= 0 ,0
Exp/Cntr=0.3,0.1

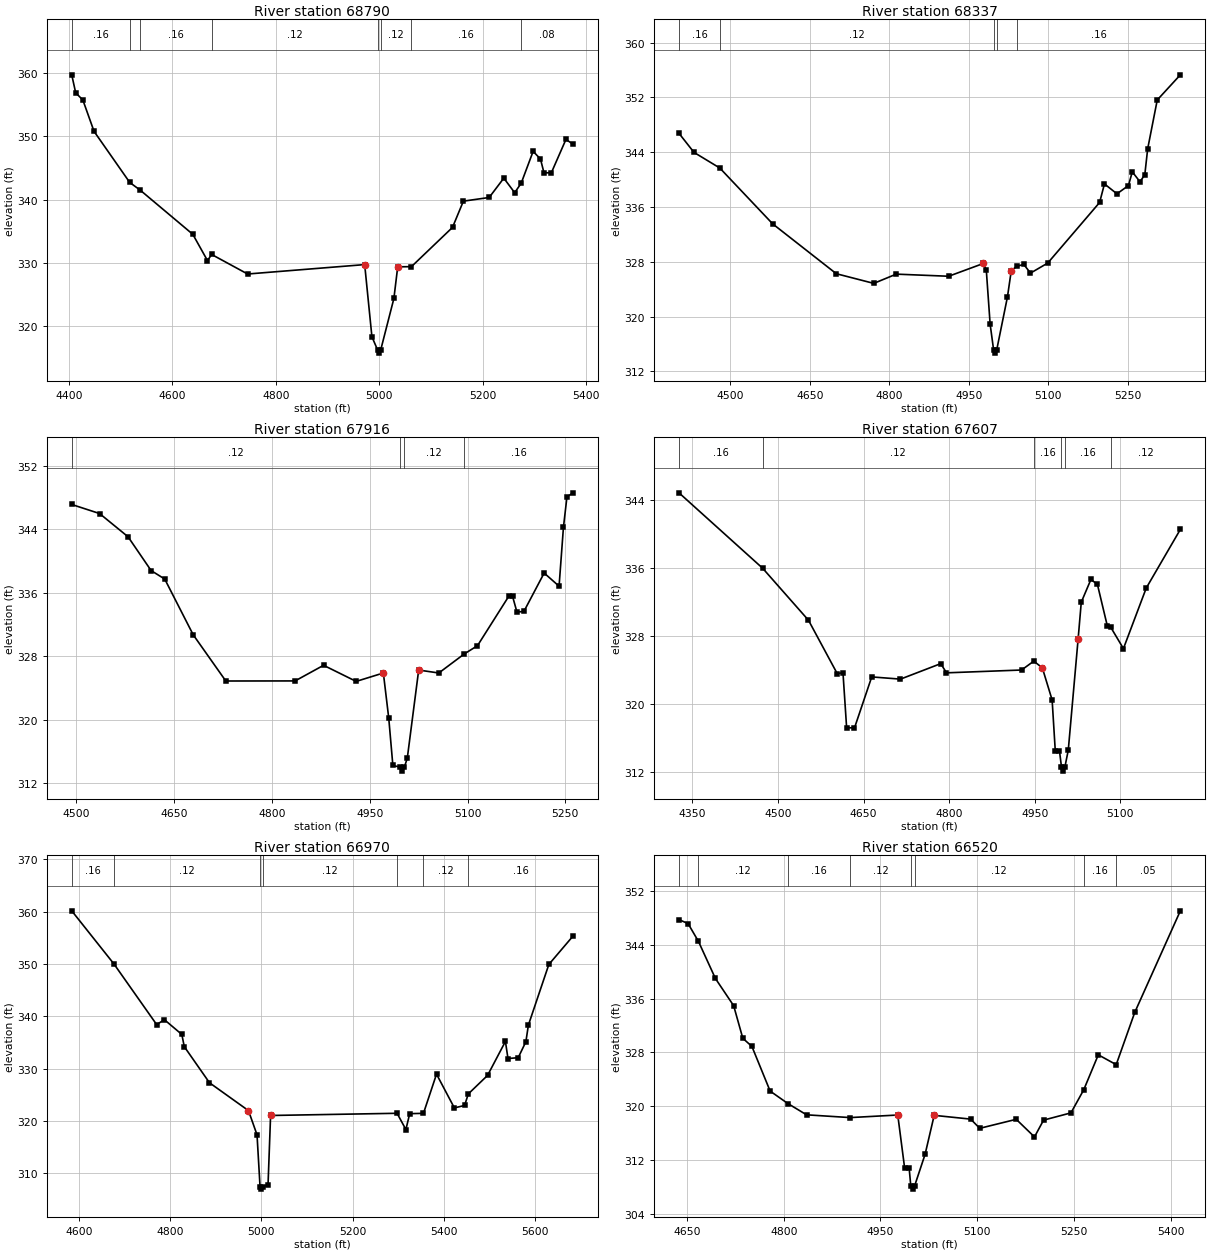
Type RM Length L Ch R = 1 ,68790   ,453,453,453
BEGIN DESCRIPTION:
TOWN CREEK 105.0
END DESCRIPTION:
XS GIS Cut Line= 2
       3745054.9     10621274.61      3744395.73     10621985.82
#Sta/Elev= 30
  4405.4  359.75    4413  356.92    4427  355.75  4448.5  350.81  4517.6342.7181
  4537.9341.4972  4639.6  334.51  4667.9  330.36  4676.1331.3183  4745.6  328.23
    4972  329.72    4986   318.3    4997  316.21  4999.8  315.71    5003  316.21
  5028.5  324.36  5035.9  329.37  5062.4329.3923  5141.9  335.61  5162.9  339.76
  5212.8  340.34  5241.1   343.4  5262.1   341.1  5274.7342.5936  5297.8  347.64
    5312  346.43  5318.8  344.25    5333  344.24  5361.3  349.53  5375.1  348.76
#Mann= 8 ,-1 , 0
  4405.4     .16       0  4517.6     .12       0  4537.9     .16       0
  4676.1     .12       0    4997     .07       0    5003     .12       0
  5062.4     .16       0  5274.7     .08       0
Bank Sta=4972,5035.9
XS Rating Curve= 0 ,0
Exp/Cntr=0.3,0.1

Type RM Length L Ch R = 1 ,68337   ,421,421,421
BEGIN DESCRIPTION:
TOWN CREEK 104.0
END DESCRIPTION:
XS GIS Cut Line= 3
       3744749.6      10621010.2      3744349.61     10621410.19
      3743999.58      10621560.2
#Sta/Elev= 30
  4403.1  346.75  4431.4  343.97  4480.1341.6902  4579.9  333.54  4700.1  326.26
  4770.8  324.85  4813.2   326.2  4912.2  325.89  4977.8  327.76  4983.3  326.75
  4990.5   318.9    4997  315.17  4999.8  314.67    5003  315.17  5023.2  322.88
  5030.4  326.71  5040.8 327.342    5054  327.62  5066.7  326.35  5099.3  327.82
  5197.2  336.66  5206.3  339.37  5229.9  337.92  5251.6  339.13  5258.9  341.13
  5273.4  339.68  5282.5  340.71  5287.9  344.48    5306  351.62  5349.6  355.29
#Mann= 5 ,-1 , 0
  4403.1     .16       0  4480.1     .12       0    4997     .07       0
    5003     .12       0  5040.8     .16       0
Bank Sta=4977.8,5030.4
XS Rating Curve= 0 ,0
Exp/Cntr=0.3,0.1

Type RM Length L Ch R = 1 ,67916   ,309,309,309
BEGIN DESCRIPTION:
TOWN CREEK 103.0
END DESCRIPTION:
XS GIS Cut Line= 3
      3744399.58     10620860.21      3743999.61     10621160.19
      3743899.62     10621410.17
#Sta/Elev= 30
  4492.7  347.14  4535.4     346  4579.1  343.07  4614.5  338.81  4635.4  337.74
  4679.1  330.71  4729.1  324.89  4835.4   324.9  4879.1  326.87  4929.1  324.84
  4970.8   325.9  4979.1  320.19  4985.4  314.24    4997  314.03  4999.8  313.53
    5003  314.03  5007.5  315.15    5025  326.27  5055.9   325.9    5095328.3048
  5115.2  329.34  5163.6  335.62    5169  335.57  5175.8  333.57  5186.5  333.67
  5217.5   338.5  5240.4  336.84  5247.1  344.27  5252.5  348.11  5261.9  348.61
#Mann= 4 ,-1 , 0
  4492.7     .12       0    4997     .07       0    5003     .12       0
    5095     .16       0
Bank Sta=4970.8,5025
XS Rating Curve= 0 ,0
Exp/Cntr=0.3,0.1

Type RM Length L Ch R = 1 ,67607   ,637,637,637
BEGIN DESCRIPTION:
TOWN CREEK 102.0
END DESCRIPTION:
XS GIS Cut Line= 3
      3743843.08     10620455.16      3743780.57     10620930.88
      3743610.43       10621292.
#Sta/Elev= 30
  4326.4  344.83  4473.1335.9669  4553.4  329.86  4603.8  323.59  4613.9   323.7
  4620.3  317.23  4634.1  317.21  4664.3   323.2  4714.7  322.94  4785.3  324.76
  4795.4  323.68    4927  324.01  4948.4325.0509  4963.4  324.27  4980.6  320.49
  4986.1  314.53  4993.4  314.53    4997  312.63  4999.8  312.13    5003  312.63
  5008.9  314.59  5026.2  327.68  5031.7  331.98  5048.6  334.65    5060  334.07
  5077.3  329.21  5083.5329.0188  5105.6  326.53  5145.6  333.64  5205.4  340.53
#Mann= 6 ,-1 , 0
  4326.4     .16       0  4473.1     .12       0  4948.4     .16       0
    4997     .07       0    5003     .16       0  5083.5     .12       0
Bank Sta=4963.4,5026.2
XS Rating Curve= 0 ,0
Exp/Cntr=0.3,0.1

Type RM Length L Ch R = 1 ,66970   ,450,450,450
BEGIN DESCRIPTION:
TOWN CREEK 101.0
END DESCRIPTION:
XS GIS Cut Line= 3
      3743699.59     10620160.23      3743549.61     10620560.19
      3742949.59      10620860.2
#Sta/Elev= 30
  4584.6  360.17  4677.3 349.975  4770.6   338.4  4787.5  339.34  4825.7  336.52
  4831.1  334.18  4886.3  327.27  4971.7  321.94  4990.4  317.31    4997  307.42
  4999.8  306.92    5003  307.42  5014.5  307.72  5020.1  321.01  5297.1321.4319
  5316.4  318.32  5324.8  321.36  5354.9 321.422  5383.5  328.92  5422.6  322.46
    5445  322.93  5453.1325.1364  5495.3  328.68  5534.4  335.18    5540  331.91
  5562.4  332.07  5579.2  335.12  5584.7   338.3  5629.5  349.91  5682.6  355.36
#Mann= 7 ,-1 , 0
  4584.6     .16       0  4677.3     .12       0    4997     .07       0
    5003     .12       0  5297.1     .16       0  5354.9     .12       0
  5453.1     .16       0
Bank Sta=4971.7,5020.1
XS Rating Curve= 0 ,0
Exp/Cntr=0.3,0.1

Type RM Length L Ch R = 1 ,66520   ,412,412,412
BEGIN DESCRIPTION:
TOWN CREEK 100.0
END DESCRIPTION:
XS GIS Cut Line= 3
      3743449.58     10620060.22      3743199.61     10620310.19
      3742899.59     10620610.21
#Sta/Elev= 30
  4637.4  347.74  4651.5  347.15  4667.6344.4956  4693.9  338.98  4722.2  334.93
  4736.4  330.08  4750.5  328.87  4778.8  322.22  4806.3320.3696  4835.3  318.69
    4903318.2777  4976.8  318.66  4987.4  310.81  4994.4  310.81    4997  308.13
  4999.8  307.63    5003  308.13  5019.2  312.81  5033.3  318.61  5089.9  318.05
    5104  316.68  5160.6  318.02  5188.9   315.4    5203   317.9  5245.5  318.98
  5265.4322.4313  5287.9  327.62  5315.7326.1569  5344.5  333.94  5415.2  349.05
#Mann= 8 ,-1 , 0
  4637.4     .16       0  4667.6     .12       0  4806.3     .16       0
    4903     .12       0    4997     .07       0    5003     .12       0
  5265.4     .16       0  5315.7     .05       0
Bank Sta=4976.8,5033.3
XS Rating Curve= 0 ,0
Exp/Cntr=0.3,0.1

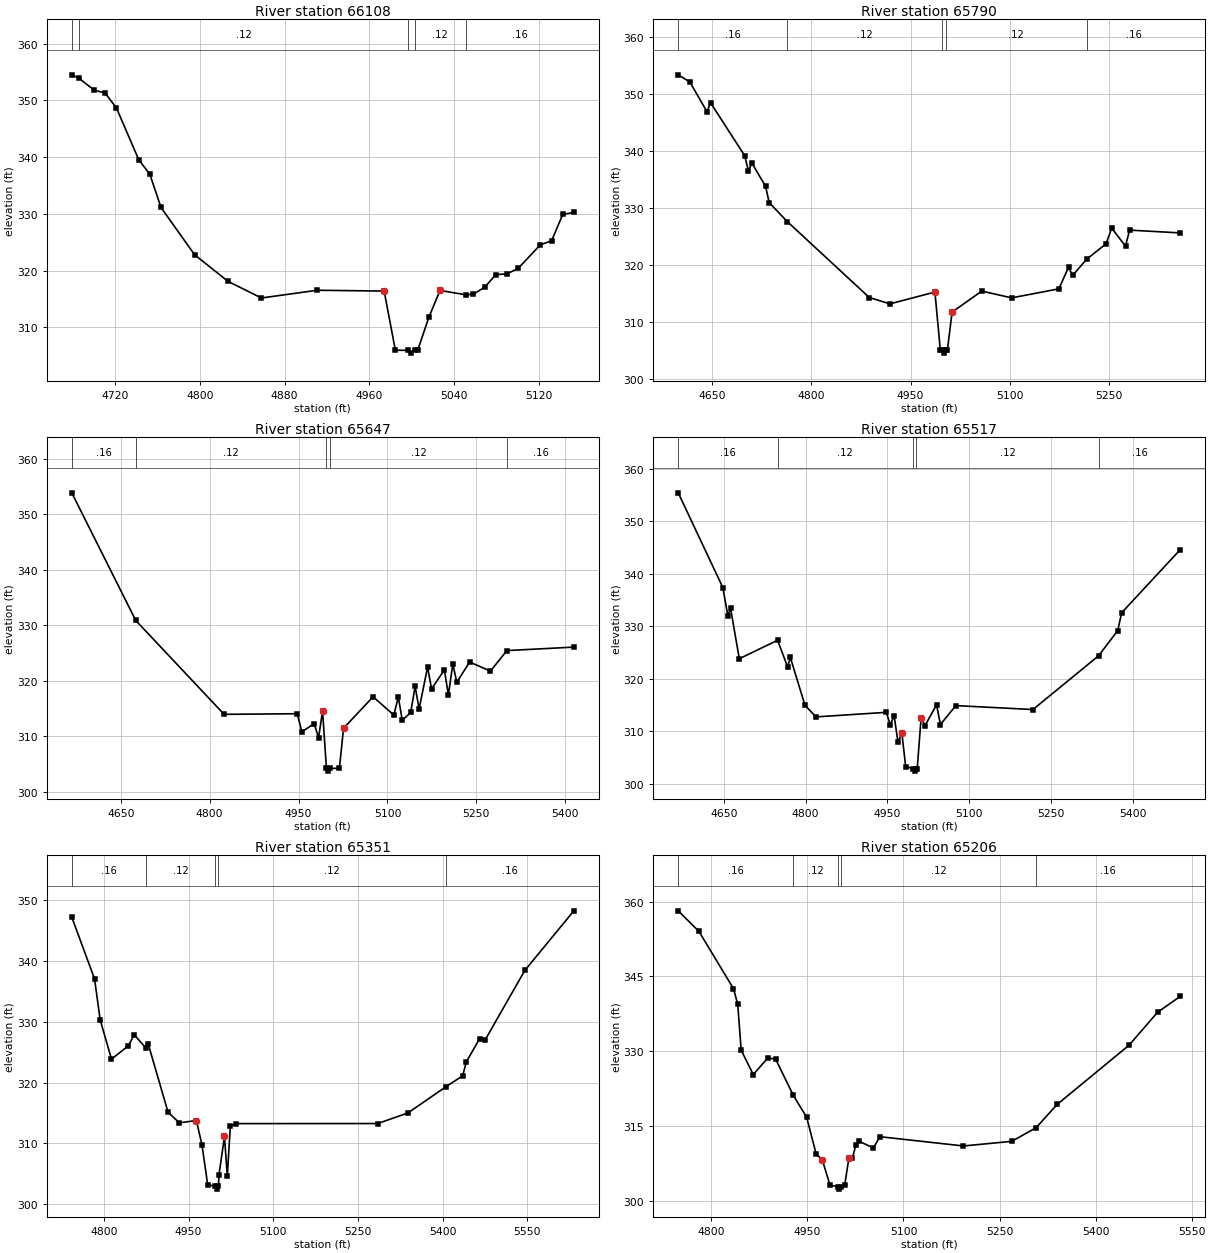
Type RM Length L Ch R = 1 ,66108   ,318,318,318
BEGIN DESCRIPTION:
TOWN CREEK 99.0
END DESCRIPTION:
XS GIS Cut Line= 3
      3742949.61     10619810.19      3742849.61     10620110.19
      3742799.62     10620260.15
#Sta/Elev= 30
    4679  354.49  4685.9353.8641  4700.1  351.81  4710.6  351.26  4721.2  348.64
  4742.2  339.56  4752.8  336.94  4763.3  331.11    4795  322.79  4826.6  318.09
  4858.2  315.16  4910.9  316.52  4974.1  316.38  4984.7  305.94    4997  305.94
  4999.8  305.44    5003  305.94  5005.8  305.94  5016.3  311.75  5026.9  316.49
  5051.4 315.716  5058.5  315.85    5069  317.04  5079.6  319.28  5090.1  319.41
  5100.6  320.36  5121.7  324.54  5132.3  325.24  5142.8  329.88  5153.3  330.25
#Mann= 5 ,-1 , 0
    4679     .16       0  4685.9     .12       0    4997     .07       0
    5003     .12       0  5051.4     .16       0
Bank Sta=4974.1,5026.9
XS Rating Curve= 0 ,0
Exp/Cntr=0.3,0.1

Type RM Length L Ch R = 1 ,65790   ,143,143,143
BEGIN DESCRIPTION:
Mapping XS 70628544
END DESCRIPTION:
XS GIS Cut Line= 3
      3742440.14     10619595.22      3742589.87     10620033.57
      3742761.32     10620274.47
#Sta/Elev= 30
  4598.8  353.31  4616.3  352.06  4642.3  346.84  4647.6  348.42  4699.2  339.14
  4704.9  336.49  4710.2  337.84  4730.9  333.73  4736.3   330.9  4763.8327.5594
  4887.6  314.26  4918.9  313.15  4986.8  315.22    4995  305.01    4997  305.01
  4999.8  304.51    5003  305.01  5005.6  305.04  5012.8  311.71  5057.6  315.39
  5102.8   314.2  5174.1  315.78  5188.8  319.56    5195  318.13  5216.2320.9877
  5245.4  323.66    5254  326.43  5274.9  323.26    5281  326.08  5357.7  325.59
#Mann= 5 ,-1 , 0
  4598.8     .16       0  4763.8     .12       0    4997     .07       0
    5003     .12       0  5216.2     .16       0
Bank Sta=4986.8,5012.8
XS Rating Curve= 0 ,0
Exp/Cntr=0.3,0.1

Type RM Length L Ch R = 1 ,65647   ,130,130,130
BEGIN DESCRIPTION:
Mapping XS d4b7ed18
END DESCRIPTION:
XS GIS Cut Line= 3
      3742190.56     10619593.03      3742381.54     10619894.68
      3742709.21     10620259.24
#Sta/Elev= 30
  4567.3  353.83  4675.3  330.84  4824.3  313.93  4947.9  314.04  4955.4  310.78
  4976.3  312.24  4983.8  309.73  4990.5  314.53    4997   304.2  4999.8   303.7
    5003   304.2  5018.9   304.2  5025.9  311.42  5075.7  317.09  5110.8   313.8
  5118.3  317.06    5125  312.85  5139.2  314.27  5146.7  318.95  5153.4  314.89
  5167.7  322.44  5174.4  318.52  5196.1  321.94  5202.8  317.42  5210.3  322.99
    5217  319.71  5238.7  323.35  5273.8  321.72  5301.6325.4154  5414.5  326.04
#Mann= 5 ,-1 , 0
  4567.3     .16       0  4675.3     .12       0    4997     .07       0
    5003     .12       0  5301.6     .16       0
Bank Sta=4990.5,5025.9
XS Rating Curve= 0 ,0
Exp/Cntr=0.3,0.1

Type RM Length L Ch R = 1 ,65517   ,166,166,166
BEGIN DESCRIPTION:
TOWN CREEK 98.0
END DESCRIPTION:
XS GIS Cut Line= 3
      3742155.85      10619588.7      3742179.72     10619846.94
      3742648.45     10620313.51
#Sta/Elev= 30
  4566.4   355.4  4648.2  337.37  4657.4  332.01  4662.4  333.41  4678.4  323.83
  4748.6327.3434    4767  322.28    4772  324.07  4798.9  314.95    4819  312.76
  4948.2  313.63  4955.2  311.19  4962.3  313.01  4969.4  307.91  4976.5   309.7
  4983.5  303.28    4997  302.94  4999.8  302.44    5003  302.94  5004.7  302.94
  5011.8  312.59  5018.9  311.09  5040.1  315.07  5047.2  311.31  5075.5  314.91
  5216.9  314.16  5337.2324.3876  5372.4  329.18  5379.5  332.57  5487.1   344.6
#Mann= 5 ,-1 , 0
  4566.4     .16       0  4748.6     .12       0    4997     .07       0
    5003     .12       0  5337.2     .16       0
Bank Sta=4976.5,5011.8
XS Rating Curve= 0 ,0
Exp/Cntr=0.3,0.1

Type RM Length L Ch R = 1 ,65351   ,145,145,145
BEGIN DESCRIPTION:
Mapping XS 18a648d3
END DESCRIPTION:
XS GIS Cut Line= 3
        3742145.     10619629.93      3742168.87     10619964.13
      3742116.89     10620516.34
#Sta/Elev= 30
    4743  347.24  4783.4  337.06  4793.4  330.29  4813.4  323.86  4843.5  326.07
  4853.5   327.9  4874.8 325.626  4878.3  326.41  4913.7  315.09  4933.7  313.37
  4963.8  313.75  4973.8   309.7  4983.9  303.14    4997  302.95  4999.8  302.45
    5003  302.95  5003.9  304.82  5013.6  311.12  5018.6  304.58    5024   312.8
    5034  313.24    5285  313.25  5338.6  314.99    5406319.3073  5435.7  321.11
  5442.2  323.41  5465.8  327.23  5475.9  327.08  5545.8  338.46  5632.7  348.28
#Mann= 5 ,-1 , 0
    4743     .16       0  4874.8     .12       0    4997     .07       0
    5003     .12       0    5406     .16       0
Bank Sta=4963.8,5013.6
XS Rating Curve= 0 ,0
Exp/Cntr=0.3,0.1

Type RM Length L Ch R = 1 ,65206   ,523,523,523
BEGIN DESCRIPTION:
TOWN CREEK 97.0
END DESCRIPTION:
XS GIS Cut Line= 3
      3742149.62     10619560.16      3742049.61     10619810.19
      3741799.59     10620260.22
#Sta/Elev= 30
  4748.2  358.19  4780.5  354.07  4834.4  342.58  4841.1  339.47  4846.5   330.2
  4865.4   325.3  4888.2  328.66  4900.4  328.38  4927.9321.1364  4948.8  316.72
  4963.6  309.33  4973.1  308.22  4985.2  303.09    4997  302.79  4999.8  302.29
    5003  302.79  5008.1  303.03  5014.8  308.58  5020.3  308.58  5025.5  311.08
  5031.2  311.87    5053  310.56  5063.2  312.82  5193.7  310.96  5269.2  311.89
  5307.1314.6284  5340.1  319.32  5452.2  331.19  5496.8  337.81  5532.3  341.01
#Mann= 5 ,-1 , 0
  4748.2     .16       0  4927.9     .12       0    4997     .07       0
    5003     .12       0  5307.1     .16       0
Bank Sta=4973.1,5014.8
XS Rating Curve= 0 ,0
Exp/Cntr=0.3,0.1

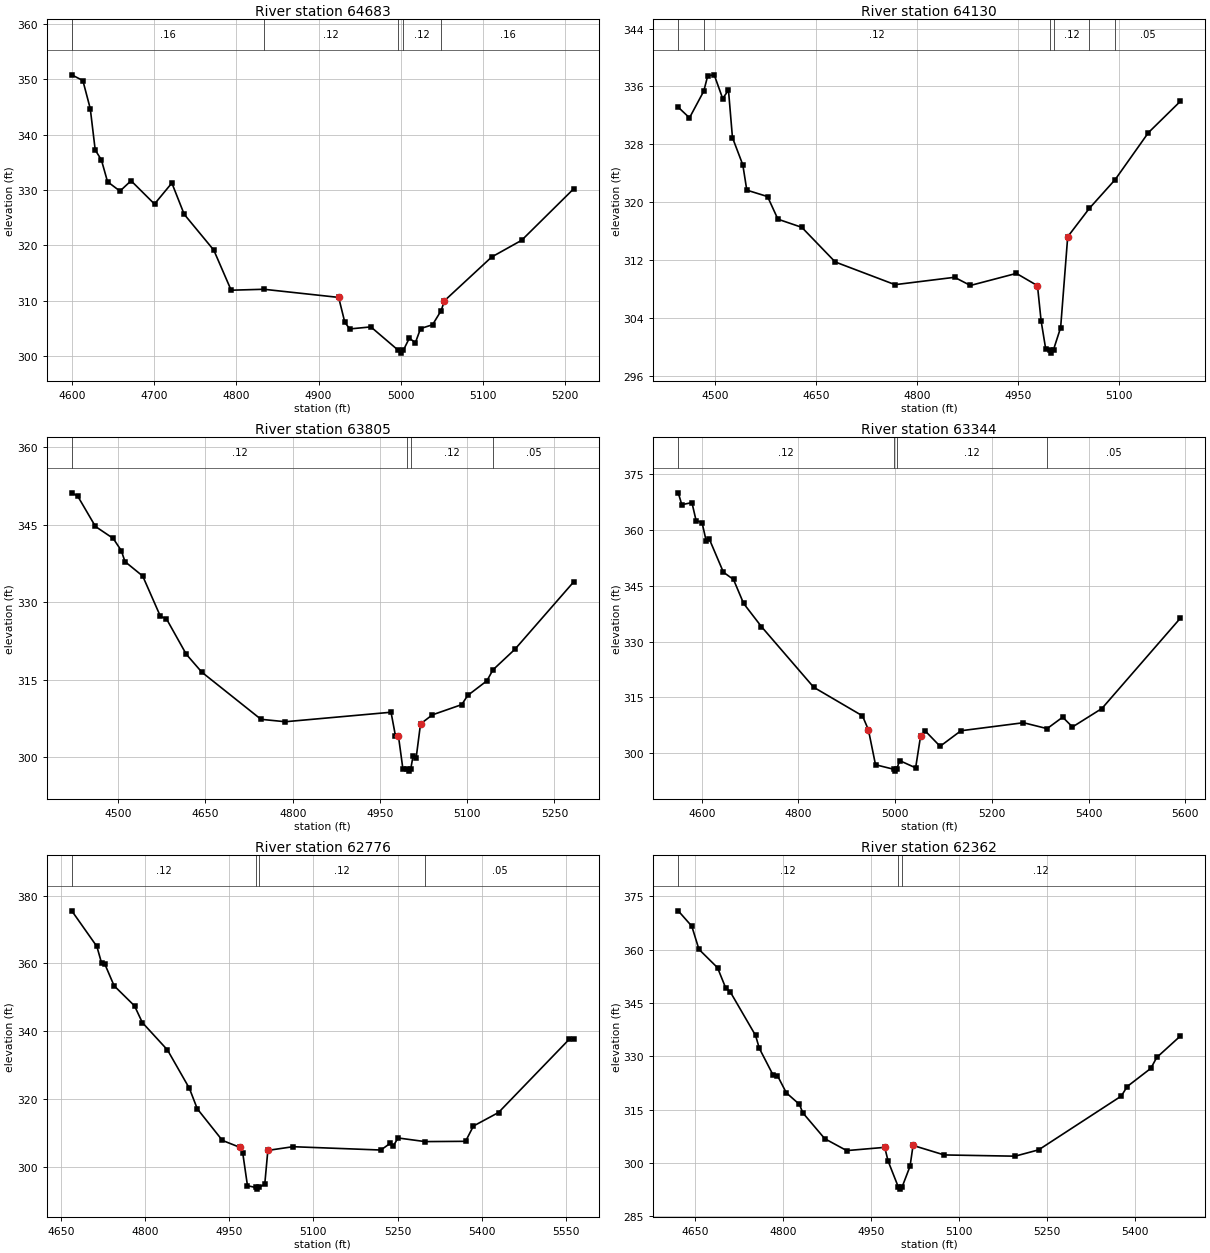
Type RM Length L Ch R = 1 ,64683   ,553,553,553
BEGIN DESCRIPTION:
TOWN CREEK 96.0
END DESCRIPTION:
XS GIS Cut Line= 3
      3741949.59      10619460.2      3741649.61     10619660.19
      3741449.64     10619810.17
#Sta/Elev= 30
  4599.9   350.8  4613.4  349.76  4622.4  344.68  4628.4  337.22  4635.9  335.43
  4643.4  331.48  4658.5  329.79    4672  331.66  4700.5  327.45  4721.6  331.25
  4736.6   325.6  4772.6  319.12  4793.7  311.88  4833.5312.0489  4924.4  310.58
  4931.9  306.08  4937.9  304.88  4963.6  305.25    4997  301.01  4999.8  300.51
    5003  301.01  5010.4  303.22  5017.7  302.38    5024  304.95  5038.6  305.64
    5049308.1813  5053.1  309.98  5110.4  317.87  5146.9   320.9  5210.4  330.23
#Mann= 5 ,-1 , 0
  4599.9     .16       0  4833.5     .12       0    4997     .07       0
    5003     .12       0    5049     .16       0
Bank Sta=4924.4,5053.1
XS Rating Curve= 0 ,0
Exp/Cntr=0.3,0.1

Type RM Length L Ch R = 1 ,64130   ,325,325,325
BEGIN DESCRIPTION:
TOWN CREEK 95.0
END DESCRIPTION:
XS GIS Cut Line= 3
      3741595.23       10618974.      3741399.91     10619290.84
      3741252.34     10619633.73
#Sta/Elev= 30
  4445.7  333.12  4462.4  331.65  4483.6335.3401  4489.5  337.48  4499.1   337.6
  4511.7  334.32  4520.3  335.48  4526.2  328.92  4541.6  325.14  4547.5  321.65
  4578.3  320.76  4593.7  317.63  4629.2   316.5  4678.8  311.71  4767.6  308.57
    4856  309.59  4879.5  308.46  4947.8  310.13  4979.1  308.43  4984.5  303.57
  4991.4  299.64    4997   299.6  4999.8   299.1    5003   299.6  5013.5  302.63
    5024   315.2    5056319.1109  5094.4323.0996  5143.8   329.6  5191.2  333.93
#Mann= 6 ,-1 , 0
  4445.7     .16       0  4483.6     .12       0    4997     .07       0
    5003     .12       0    5056     .16       0  5094.4     .05       0
Bank Sta=4979.1,5024
XS Rating Curve= 0 ,0
Exp/Cntr=0.3,0.1

Type RM Length L Ch R = 1 ,63805   ,461,461,461
BEGIN DESCRIPTION:
TOWN CREEK 94.0
END DESCRIPTION:
XS GIS Cut Line= 3
      3741249.61     10618660.18      3741149.61     10619210.19
       3741099.6     10619510.22
#Sta/Elev= 30
  4420.1  351.19  4430.3  350.55  4460.8  344.67  4491.3  342.36  4505.2     340
  4511.6  337.86  4542.1  335.06  4572.6  327.23  4582.7  326.81    4617  319.91
  4643.7  316.44  4745.4  307.31  4787.3  306.84    4969  308.68  4976.6   304.1
  4981.7   304.1  4989.3  297.77    4997  297.77  4999.8  297.27    5003  297.77
    5007  300.27  5012.1  299.76  5019.7  306.42    5040  308.17  5090.6  310.16
  5100.8  311.93  5133.7  314.76  5144.3   316.9  5181.9  320.87  5283.3  333.97
#Mann= 4 ,-1 , 0
  4420.1     .12       0    4997     .07       0    5003     .12       0
  5144.3     .05       0
Bank Sta=4981.7,5019.7
XS Rating Curve= 0 ,0
Exp/Cntr=0.3,0.1

Type RM Length L Ch R = 1 ,63344   ,568,568,568
BEGIN DESCRIPTION:
TOWN CREEK 93.0
END DESCRIPTION:
XS GIS Cut Line= 3
       3740549.6     10618660.18      3740899.61     10618910.19
      3740999.61     10619510.19
#Sta/Elev= 30
  4551.3  370.01  4558.7  366.82  4579.6  367.38  4588.2  362.56  4600.5     362
  4609.1   357.1  4615.2  357.69  4644.7  348.66  4665.6   346.7  4686.5  340.26
  4723.4  334.02  4831.5  317.71  4932.3  310.03  4944.6  306.29  4959.3  296.88
    4997  295.66  4999.8  295.16    5003  295.66  5009.3  297.99  5042.3  296.04
  5052.4  304.48  5062.5  305.92  5092.9  301.84    5136  306.02  5265.3  308.18
  5314.2306.5922  5346.4  309.67  5366.7  307.04  5427.5     312  5589.7  336.28
#Mann= 4 ,-1 , 0
  4551.3     .12       0    4997     .07       0    5003     .12       0
  5314.2     .05       0
Bank Sta=4944.6,5052.4
XS Rating Curve= 0 ,0
Exp/Cntr=0.3,0.1

Type RM Length L Ch R = 1 ,62776   ,414,414,414
BEGIN DESCRIPTION:
TOWN CREEK 92.0
END DESCRIPTION:
XS GIS Cut Line= 3
      3740499.63     10618760.23      3740649.61     10619060.19
      3740899.62      10619560.2
#Sta/Elev= 30
  4669.5   375.5  4714.2  364.99  4722.6  360.08  4728.2  359.86  4744.9  353.38
  4781.3  347.45  4795.2  342.52    4840  334.43  4879.1  323.08  4893.1  317.06
  4937.8  307.74  4968.5  305.72  4974.1  303.99  4982.5  294.36    4997  293.86
  4999.8  293.36    5003  293.86  5013.3  294.83  5018.8  304.79  5063.6  305.88
  5220.1   304.9  5236.9  306.89  5242.4  306.16  5250.8  308.46    5299307.3874
    5371  307.47    5385  311.98  5429.7  315.97  5555.5  337.56  5563.9  337.79
#Mann= 4 ,-1 , 0
  4669.5     .12       0    4997     .07       0    5003     .12       0
    5299     .05       0
Bank Sta=4968.5,5018.8
XS Rating Curve= 0 ,0
Exp/Cntr=0.3,0.1

Type RM Length L Ch R = 1 ,62362   ,606,606,606
BEGIN DESCRIPTION:
TOWN CREEK 91.0
END DESCRIPTION:
XS GIS Cut Line= 3
       3740149.6     10618960.16      3740349.61     10619310.19
      3740399.61     10619760.18
#Sta/Elev= 30
  4621.6  370.91  4644.7  366.59  4656.9  360.09  4688.6  354.92  4702.2  349.36
  4710.2  348.15  4753.4  335.89  4759.8  332.27  4782.9  324.88  4790.8  324.57
  4805.9  319.75  4828.2  316.51    4834  314.13  4871.4  306.86  4908.8  303.52
  4973.6  304.43  4979.4  300.56    4997  293.19  4999.8  292.69    5003  293.19
  5016.8  299.14  5021.9  304.97    5075   302.3  5195.8  301.95    5236  303.73
  5376.9  318.85    5387  321.53  5427.2  326.63  5437.3  329.69  5477.5  335.71
#Mann= 3 ,-1 , 0
  4621.6     .12       0    4997     .07       0    5003     .12       0
Bank Sta=4973.6,5021.9
XS Rating Curve= 0 ,0
Exp/Cntr=0.3,0.1

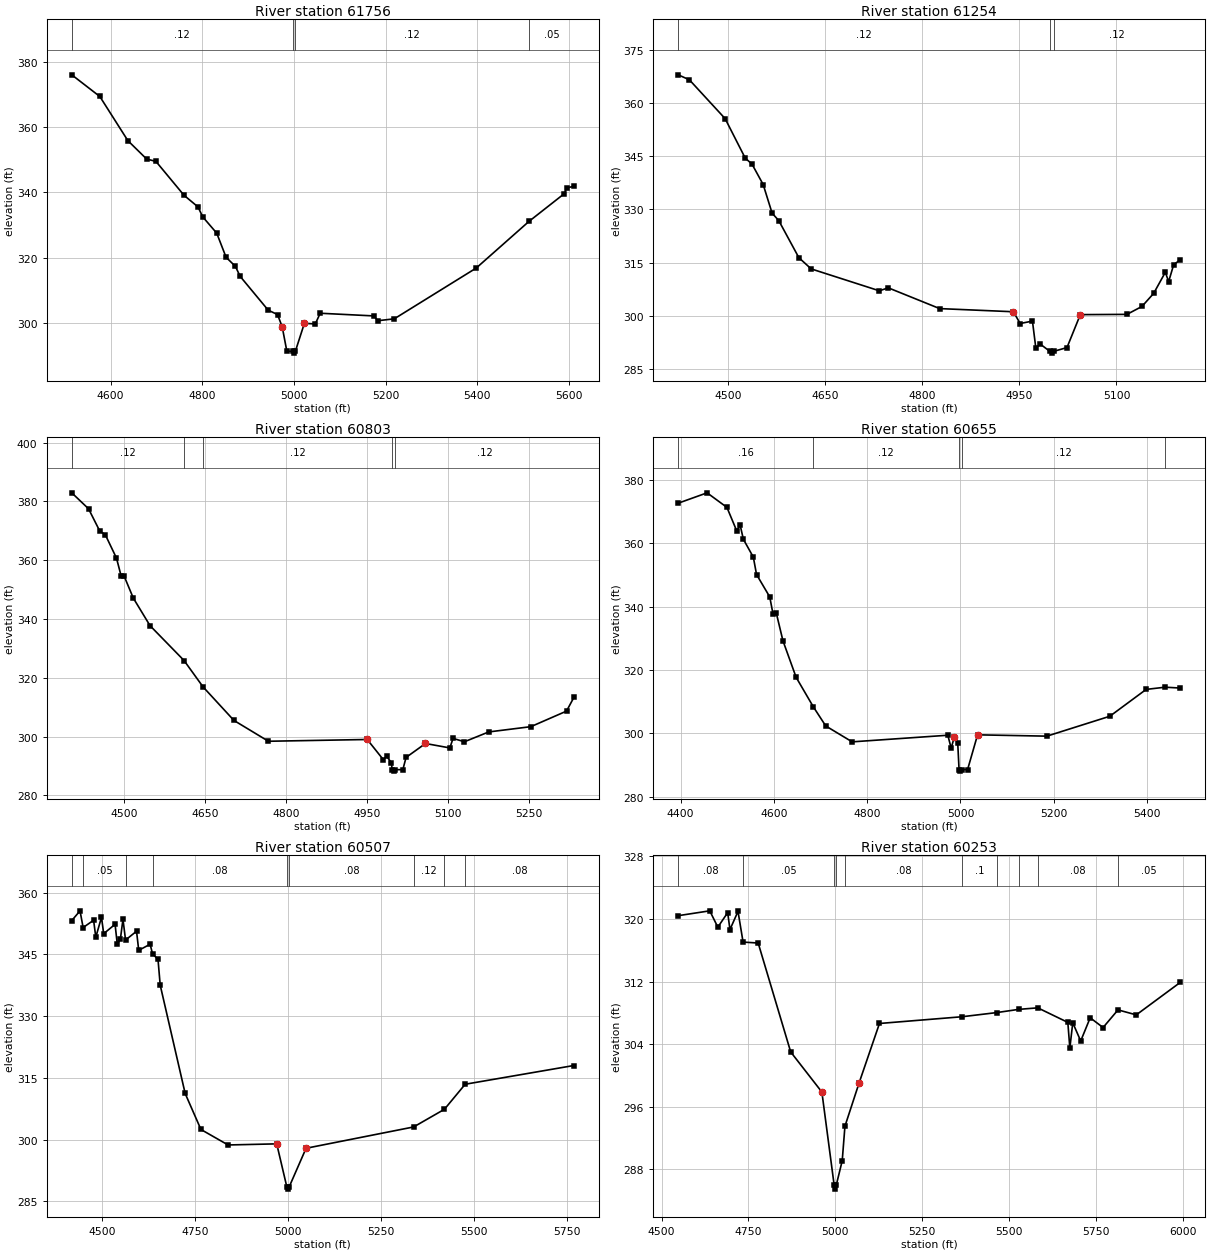
Type RM Length L Ch R = 1 ,61756   ,502,502,502
BEGIN DESCRIPTION:
TOWN CREEK 90.0
END DESCRIPTION:
XS GIS Cut Line= 3
       3739849.6     10618960.15      3739949.61     10619460.19
      3740149.62     10620010.21
#Sta/Elev= 30
  4515.4  376.03  4576.6  369.39  4637.8  355.86  4678.6  350.24    4699   349.5
  4760.2  339.13  4790.8  335.55    4801  332.52  4831.6  327.52    4852  320.13
  4872.4  317.33  4882.6   314.3  4943.8  303.93  4964.2  302.58  4974.4  298.84
  4984.5  291.38    4997  291.26  4999.8  290.76    5003  291.26  5022.8  299.89
  5046.6  299.71  5057.3  302.98  5174.3  302.16    5183  300.69  5218.9  301.27
  5397.8  316.84  5512.9 331.142  5589.3  339.57  5595.3  341.34  5610.6  341.93
#Mann= 4 ,-1 , 0
  4515.4     .12       0    4997     .07       0    5003     .12       0
  5512.9     .05       0
Bank Sta=4974.4,5022.8
XS Rating Curve= 0 ,0
Exp/Cntr=0.3,0.1

Type RM Length L Ch R = 1 ,61254   ,451,451,451
BEGIN DESCRIPTION:
TOWN CREEK 89.0
END DESCRIPTION:
XS GIS Cut Line= 3
      3739399.62     10618960.22      3739549.61     10619510.19
      3739599.61     10619710.18
#Sta/Elev= 30
  4422.5  367.95  4439.7  366.55    4495  355.59  4526.1  344.45  4536.5  342.78
  4553.8  337.01  4567.6  328.94  4577.9  326.84    4609  316.37    4628  313.21
  4733.4  307.03  4747.2  307.87  4826.7  302.01  4940.7  301.12  4951.1   297.8
  4970.1  298.49  4975.3  290.94  4982.2     292    4997  289.95  4999.8  289.45
    5003  289.95  5023.5  291.02  5044.1  300.31  5116.2  300.38  5139.4  302.62
  5157.5   306.3  5175.5  312.24  5180.7  309.64  5188.4  314.38  5198.7   315.8
#Mann= 3 ,-1 , 0
  4422.5     .12       0    4997     .07       0    5003     .12       0
Bank Sta=4940.7,5044.1
XS Rating Curve= 0 ,0
Exp/Cntr=0.3,0.1

Type RM Length L Ch R = 1 ,60803   ,148,148,148
BEGIN DESCRIPTION:
TOWN CREEK 88.0
END DESCRIPTION:
XS GIS Cut Line= 3
      3739299.62     10618860.17      3739149.61     10619410.19
      3739349.63     10619710.22
#Sta/Elev= 30
  4403.2  382.91  4434.3  377.48    4455  369.94  4465.4  368.65  4486.1   360.7
  4494.8  354.57    4500  354.71  4517.2  347.13  4548.3  337.73  4611.3325.8841
  4646.6316.9052  4703.8   305.5  4767.7  298.42  4950.9  299.02  4980.8  292.14
  4986.8  293.38  4995.8  291.05    4997  288.76  4999.8  288.26    5003  288.76
  5016.9  288.76  5022.9  292.92  5058.9  297.66    5104  296.15    5110  299.39
  5131.1  298.25  5176.1  301.59  5254.2  303.38  5320.3  308.67  5333.9  313.31
#Mann= 5 ,-1 , 0
  4403.2     .12       0  4611.3     .16       0  4646.6     .12       0
    4997     .07       0    5003     .12       0
Bank Sta=4950.9,5058.9
XS Rating Curve= 0 ,0
Exp/Cntr=0.3,0.1

Type RM Length L Ch R = 1 ,60655   ,148,148,148
BEGIN DESCRIPTION:
Mapping XS b2a92bd8
END DESCRIPTION:
XS GIS Cut Line= 3
      3738603.47     10619048.92      3739141.68      10619566.3
       3739391.7     10619781.59
#Sta/Elev= 30
  4394.9   372.7  4456.8  375.97  4499.3  371.37  4520.3  363.95  4527.6  365.81
  4534.5  361.31  4555.9  355.65  4562.8  350.16  4591.1  343.09    4598  337.77
  4605.3  337.89  4619.4  329.23  4647.7  317.67  4684.7308.3217  4711.2  302.31
  4767.8  297.29  4972.9  299.38  4980.1  295.31    4987  298.87  4994.2  296.84
    4997  288.54  4999.8  288.04    5003  288.54  5015.3  288.54  5036.7  299.51
  5185.3  299.09  5320.3  305.38  5398.2  313.86  5438.7314.5572  5471.4  314.29
#Mann= 5 ,-1 , 0
  4394.9     .16       0  4684.7     .12       0    4997     .07       0
    5003     .12       0  5438.7     .08       0
Bank Sta=4987,5036.7
XS Rating Curve= 0 ,0
Exp/Cntr=0.3,0.1

Type RM Length L Ch R = 1 ,60507   ,254,254,254
BEGIN DESCRIPTION:
Mapping XS 93773baf
END DESCRIPTION:
XS GIS Cut Line= 2
      3738409.08     10619191.32      3739551.39     10619910.04
#Sta/Elev= 30
  4418.8   353.2    4441  355.56  4449.3 351.503  4477.5  353.27  4483.4  349.16
  4498.7     354  4504.6  350.01  4535.2  352.29  4541.1  347.49  4549.4  348.64
  4556.4   353.5  4563.4348.4704  4592.9  350.61  4598.8  345.97  4629.4  347.45
  4635.9345.1167  4650.6  343.78  4656.5  337.53  4723.6  311.22    4766  302.48
    4839  298.72  4969.7  298.99    4997   288.5  4999.8     288    5003   288.5
  5048.6  297.92  5337.8 303.094  5420.5307.3807  5476.3313.4614  5768.4  318.01
#Mann= 9 ,-1 , 0
  4418.8     .08       0  4449.3     .05       0  4563.4     .16       0
  4635.9     .08       0    4997     .07       0    5003     .08       0
  5337.8     .12       0  5420.5      .1       0  5476.3     .08       0
Bank Sta=4969.7,5048.6
XS Rating Curve= 0 ,0
Exp/Cntr=0.3,0.1

Type RM Length L Ch R = 1 ,60253   ,55,55,55
BEGIN DESCRIPTION:
TOWN CREEK 87.0
END DESCRIPTION:
XS GIS Cut Line= 2
      3738301.41     10619403.11      3739546.26     10620138.23
#Sta/Elev= 30
    4548  320.43  4638.8  321.05    4662  318.96  4690.4  320.82  4696.9  318.65
  4720.1  320.98  4734.7317.0529  4778.2  316.93  4871.8     303  4961.6  297.87
    4997  285.95  4999.8  285.45    5003  285.95  5020.2  289.09    5028293.4919
  5068.9  299.05  5127.4  306.64    5365307.5005  5465.6308.0364  5528.4308.4442
  5583.3  308.64  5669.8  306.78  5675.6  303.49    5684  306.73  5706.9   304.4
  5734.2  307.37  5771.3  306.12  5814.3308.3792  5866.9  307.74  5993.7   311.9
#Mann= 10 ,-1 , 0
    4548     .08       0  4734.7     .05       0    4997     .04       0
    5003     .05       0    5028     .08       0    5365      .1       0
  5465.6     .15       0  5528.4      .1       0  5583.3     .08       0
  5814.3     .05       0
Bank Sta=4961.6,5068.9
XS Rating Curve= 0 ,0
Exp/Cntr=0.3,0.1