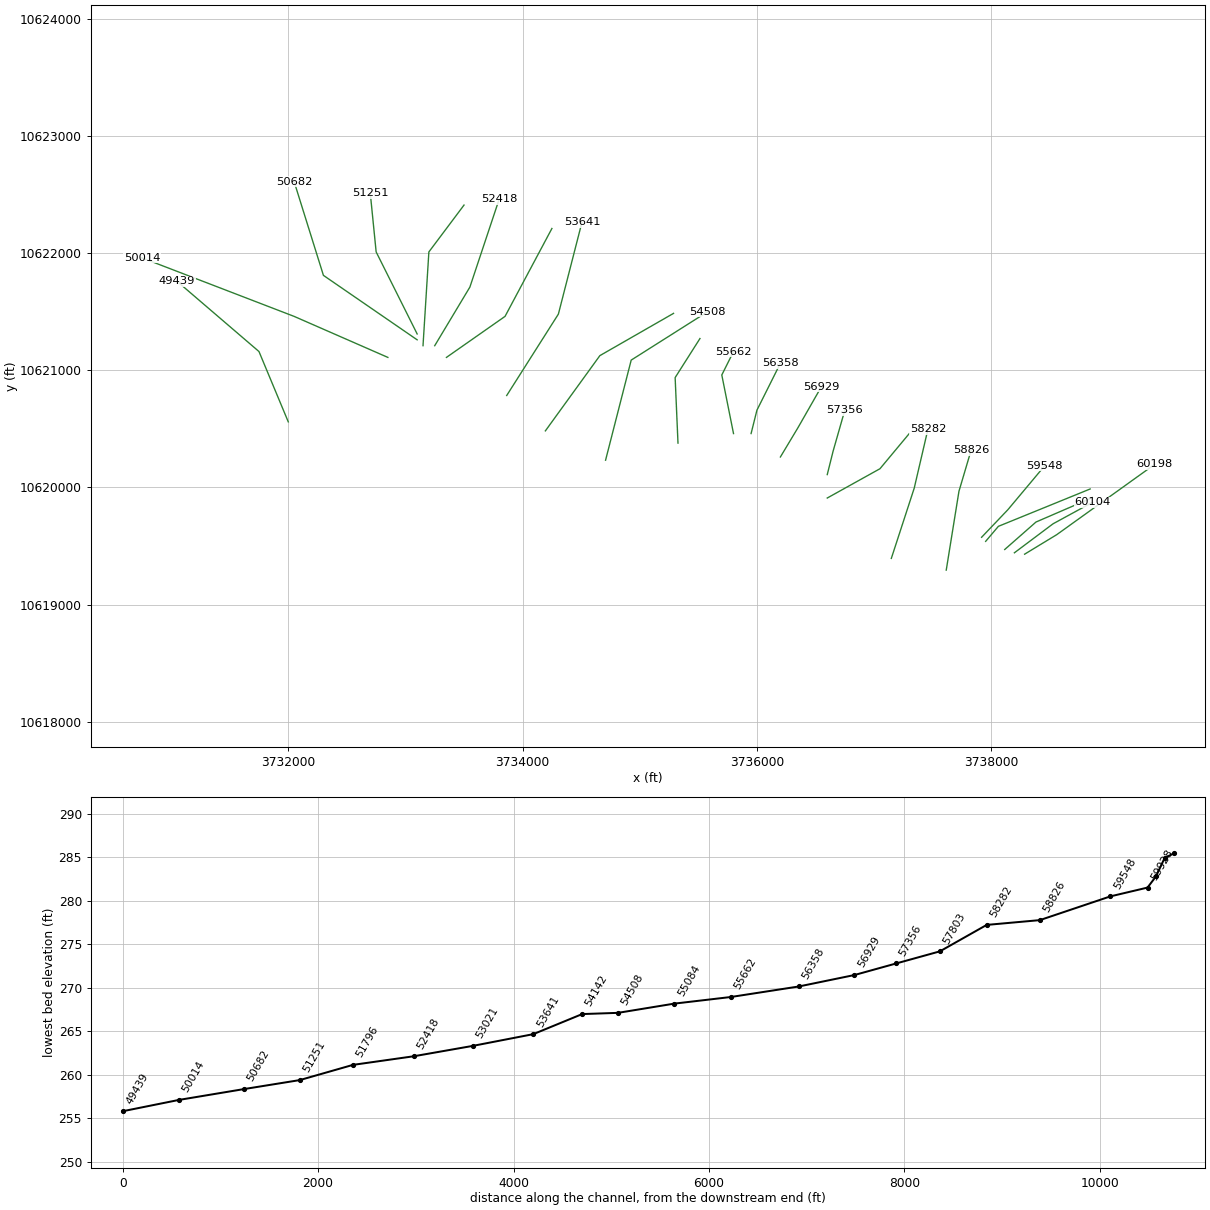
HEC-RAS study TOWN CREEK.prj: TOWN CREEK Base Level Engineering

--- TOWN CREEK.g01 (geometry) --- (continued)

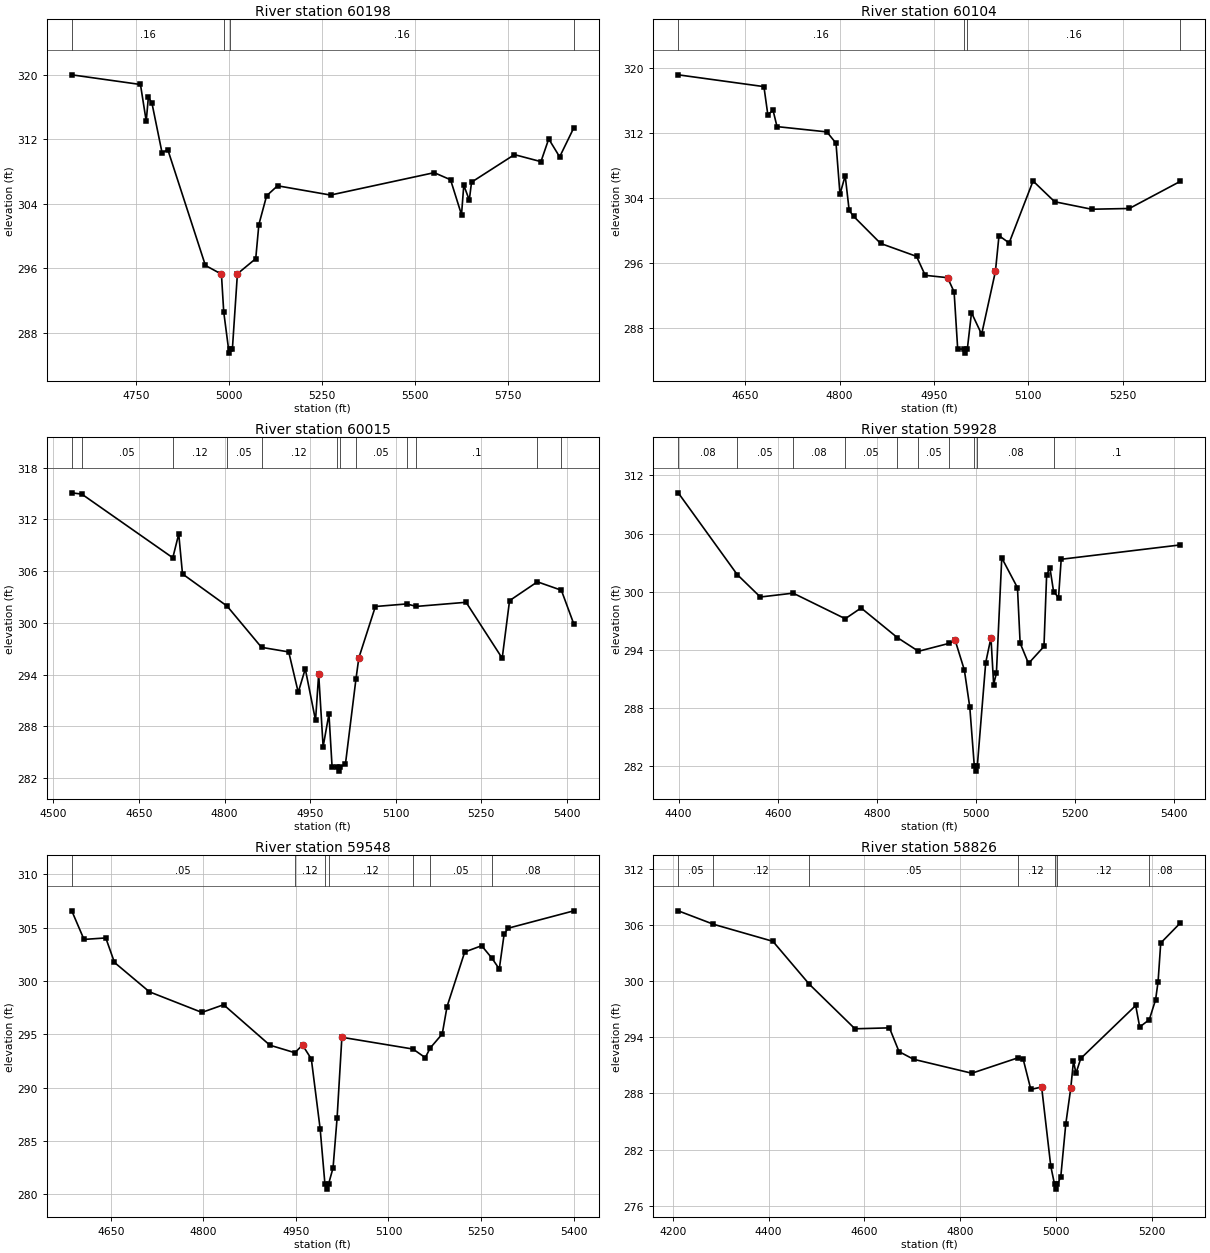
Type RM Length L Ch R = 1 ,60198   ,94,94,94
BEGIN DESCRIPTION:
Mapping XS 62e8a5fa
END DESCRIPTION:
XS GIS Cut Line= 3
      3738284.02     10619430.87      3738558.35     10619597.55
      3739394.84     10620198.02
#Sta/Elev= 30
  4576.6     320  4761.4   318.8  4776.9  314.25  4782.7  317.23  4792.3  316.48
  4819.5  310.32    4835   310.7  4936.1  296.33  4979.2  295.25  4985.4  290.56
  4999.8  285.44    5003  285.94  5008.7  285.96  5022.2  295.29  5071.5  297.17
  5079.9   301.4  5100.8  304.98  5130.2  306.22  5272.7  305.07  5551.6  307.85
  5595.6  306.97  5625.1  302.63  5631.2   306.3    5646  304.44  5652.1  306.67
  5767.5  310.09  5838.8  309.22  5859.7  312.04  5889.1  309.81  5927.3  313.43
#Mann= 4 ,-1 , 0
  4576.6     .16       0  4985.4     .07       0    5003     .16       0
  5927.3     .05       0
Bank Sta=4979.2,5022.2
XS Rating Curve= 0 ,0
Exp/Cntr=0.3,0.1

Type RM Length L Ch R = 1 ,60104   ,89,89,89
BEGIN DESCRIPTION:
Mapping XS affd7096
END DESCRIPTION:
XS GIS Cut Line= 3
      3738196.81     10619442.77      3738526.65     10619690.15
       3738864.9     10619874.45
#Sta/Elev= 30
  4543.8  319.16  4679.9  317.71  4686.1  314.26  4694.4   314.8  4700.7  312.79
  4779.9  312.14  4794.4  310.75  4800.7  304.48    4809  306.75  4815.3  302.49
  4822.3  301.76  4865.3  298.42  4922.3  296.83  4936.1   294.5  4971.6  294.21
    4982  292.46  4987.7  285.43    4997  285.43  4999.8  284.93    5003  285.43
  5009.6   289.9  5025.7  287.25  5047.6  294.97  5053.3  299.38  5069.4  298.48
  5107.4   306.1  5141.7  303.55  5200.4  302.63  5260.3  302.72  5341.3  306.06
#Mann= 4 ,-1 , 0
  4543.8     .16       0    4997     .07       0    5003     .16       0
  5341.3     .08       0
Bank Sta=4971.6,5047.6
XS Rating Curve= 0 ,0
Exp/Cntr=0.3,0.1

Type RM Length L Ch R = 1 ,60015   ,87,87,87
BEGIN DESCRIPTION:
TOWN CREEK 86.0
END DESCRIPTION:
XS GIS Cut Line= 3
      3738114.34     10619470.98      3738381.25     10619705.34
      3738863.03     10619913.68
#Sta/Elev= 30
  4532.1  315.09  4549.7  314.94  4709.2307.5524  4719.6  310.32  4726.2  305.68
  4804.4 301.945  4864.7297.1621  4912.4  296.63  4929.1  291.94  4941.4  294.67
  4959.4  288.69  4964.9  294.06  4972.7  285.63  4982.9  289.43  4988.4   283.3
    4997   283.3  4999.8   282.8    5003   283.3  5011.8  283.61  5030.3 293.507
  5035.3  295.94  5064.3   301.9    5119 302.198  5136.3301.9122  5223.3  302.39
  5286.6   295.9  5299.5  302.58  5348.3 304.764  5390.3303.7889  5412.2  299.86
#Mann= 12 ,-1 , 0
  4532.1     .08       0  4549.7     .05       0  4709.2     .12       0
  4804.4     .05       0  4864.7     .12       0    4997     .07       0
    5003     .12       0  5030.3     .05       0    5119     .08       0
  5136.3      .1       0  5348.3     .08       0  5390.3      .1       0
Bank Sta=4964.9,5035.3
XS Rating Curve= 0 ,0
Exp/Cntr=0.3,0.1

Type RM Length L Ch R = 1 ,59928   ,380,380,380
BEGIN DESCRIPTION:
TOWN CREEK 85.0
END DESCRIPTION:
XS GIS Cut Line= 3
      3737951.55     10619540.39      3738060.07     10619668.45
      3738843.45     10619987.44
#Sta/Elev= 30
  4399.2   310.2  4518.2301.7797  4564.9  299.46  4631.2299.8578  4736.4297.2202
  4768.4  298.33  4841.5  295.28  4884.2293.8656  4946.7294.6901  4958.4  294.98
  4976.9  291.93  4987.9  288.08    4997  282.01  4999.8  281.51    5003  282.01
    5020   292.7  5030.6  295.26    5036  290.44  5041.6  291.61  5052.4  303.49
  5084.1  300.42  5089.5  294.71  5106.4  292.61  5137.6  294.36    5143  301.73
  5149.6  302.48    5157 300.027    5167  299.39  5172.4  303.35  5412.9  304.83
#Mann= 10 ,-1 , 0
  4399.2     .08       0  4518.2     .05       0  4631.2     .08       0
  4736.4     .05       0  4841.5     .12       0  4884.2     .05       0
  4946.7     .08       0    4997     .07       0    5003     .08       0
    5157      .1       0
Bank Sta=4958.4,5030.6
XS Rating Curve= 0 ,0
Exp/Cntr=0.3,0.1

Type RM Length L Ch R = 1 ,59548   ,722,722,722
BEGIN DESCRIPTION:
Mapping XS a7333cae
END DESCRIPTION:
XS GIS Cut Line= 3
      3737916.82     10619575.11      3738140.37     10619809.51
       3738454.8     10620184.66
#Sta/Elev= 30
  4586.9  306.58  4606.7   303.9    4642  304.04  4656.1  301.74  4712.7  298.99
  4797.7  297.06  4832.9  297.78  4907.8  293.99  4948.3293.2831  4960.7     294
    4975   292.7  4989.3  286.15    4997     281  4999.8   280.5    5003     281
  5010.2  282.49  5016.7  287.14  5024.5  294.73  5139.7293.6269  5159.6  292.82
  5167.5293.7183  5187.1  295.04  5194.9  297.61  5223.5  302.72  5250.9  303.31
  5267.5302.1483  5279.5  301.13  5287.3  304.37  5293.8  304.95  5400.3  306.58
#Mann= 7 ,-1 , 0
  4586.9     .05       0  4948.3     .12       0    4997     .07       0
    5003     .12       0  5139.7     .07       0  5167.5     .05       0
  5267.5     .08       0
Bank Sta=4960.7,5024.5
XS Rating Curve= 0 ,0
Exp/Cntr=0.3,0.1

Type RM Length L Ch R = 1 ,58826   ,544,544,544
BEGIN DESCRIPTION:
TOWN CREEK 84.0
END DESCRIPTION:
XS GIS Cut Line= 3
      3737615.19     10619295.15       3737723.7     10619967.93
      3737827.85     10620319.45
#Sta/Elev= 30
  4211.4  307.52    4285306.0816    4409  304.26  4484.9299.6788  4580.3  294.91
  4652.3  295.01  4672.3  292.47  4702.7  291.65  4824.3  290.16  4920.8291.8095
  4931.5  291.66  4947.4  288.43    4970  288.68  4989.1  280.22    4997  278.27
  4999.8  277.77    5003  278.27    5010   279.1  5020.4  284.73  5030.8  288.56
  5036.5  291.47  5041.7  290.15  5051.7  291.74  5166.4   297.4  5174.7   295.1
  5194.8295.8907  5207.9  298.02  5213.1  299.95  5218.6  304.08  5259.5  306.22
#Mann= 7 ,-1 , 0
  4211.4     .05       0    4285     .12       0  4484.9     .05       0
  4920.8     .12       0    4997     .07       0    5003     .12       0
  5194.8     .08       0
Bank Sta=4970,5030.8
XS Rating Curve= 0 ,0
Exp/Cntr=0.3,0.1

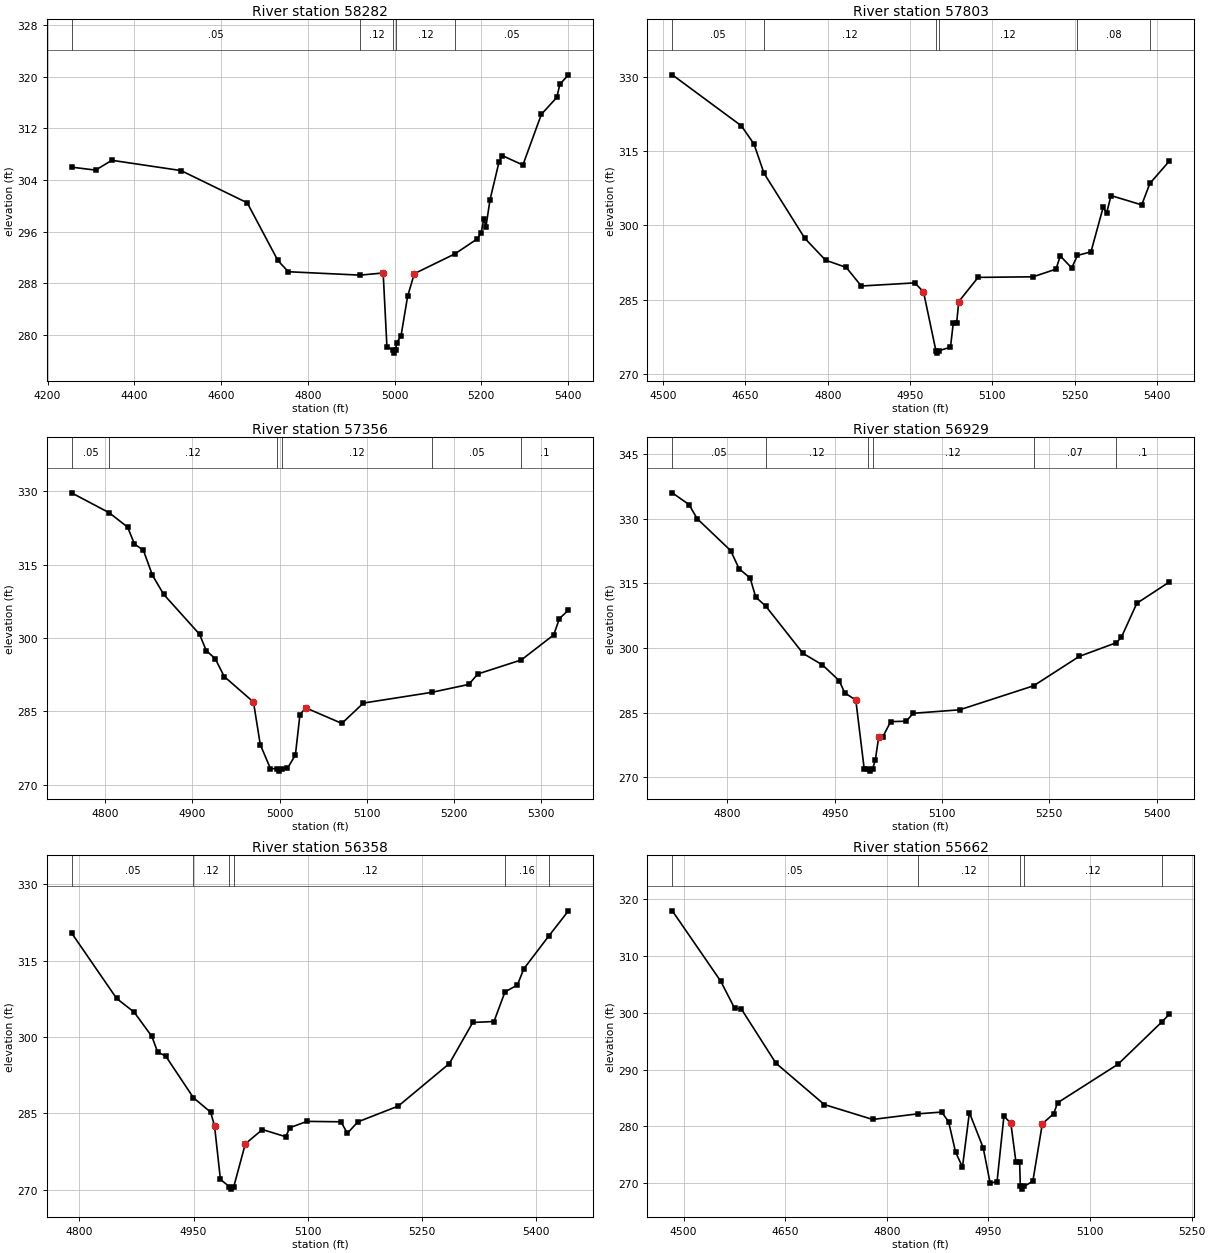
Type RM Length L Ch R = 1 ,58282   ,479,479,479
BEGIN DESCRIPTION:
TOWN CREEK 83.0
END DESCRIPTION:
XS GIS Cut Line= 3
      3737146.43     10619394.96      3737341.75     10619993.97
      3737458.67     10620496.29
#Sta/Elev= 30
  4255.2  305.99  4310.9  305.53  4348.1  307.05  4507.6  305.46  4660.4  300.47
    4731  291.55  4755.1  289.81  4920.8289.2843  4973.8  289.62  4982.5  278.18
    4997  277.72  4999.8  277.22    5003  277.72  5004.6  278.82  5014.8  279.82
  5030.2  286.01  5045.6  289.51  5139.5292.5818  5189.4  294.83  5199.7  295.76
  5205.7  298.03  5210.8  296.78  5220.2  300.95  5240.7  306.72  5248.3  307.78
    5296  306.32  5338.6  314.16  5374.2  316.78  5381.2   318.8    5401  320.27
#Mann= 5 ,-1 , 0
  4255.2     .05       0  4920.8     .12       0    4997     .07       0
    5003     .12       0  5139.5     .05       0
Bank Sta=4973.8,5045.6
XS Rating Curve= 0 ,0
Exp/Cntr=0.3,0.1

Type RM Length L Ch R = 1 ,57803   ,447,447,447
BEGIN DESCRIPTION:
TOWN CREEK 82.0
END DESCRIPTION:
XS GIS Cut Line= 3
      3736599.62      10619910.2      3737049.61     10620160.19
      3737299.62      10620460.2
#Sta/Elev= 30
  4516.8  330.44  4642.6  320.13  4665.5  316.47  4683.9310.5299  4758.2  297.39
  4795.9  292.98  4833.7   291.5  4861.1  287.75  4958.4  288.38  4974.4  286.58
    4997  274.68  4999.8  274.18    5003  274.68  5023.6  275.39  5028.7  280.31
  5034.8  280.31  5038.7  284.61  5073.9  289.49  5174.1  289.61  5215.8  291.16
  5223.6  293.83  5244.4  291.39  5254.9293.9366  5279.5  294.65  5301.7  303.64
  5308.2  302.56    5316  306.03    5372  304.15  5386.8 308.481  5422.1  312.98
#Mann= 6 ,-1 , 0
  4516.8     .05       0  4683.9     .12       0    4997     .07       0
    5003     .12       0  5254.9     .08       0  5386.8     .12       0
Bank Sta=4974.4,5038.7
XS Rating Curve= 0 ,0
Exp/Cntr=0.3,0.1

Type RM Length L Ch R = 1 ,57356   ,427,427,427
BEGIN DESCRIPTION:
TOWN CREEK 81.0
END DESCRIPTION:
XS GIS Cut Line= 3
      3736599.61     10620110.18      3736649.61     10620310.19
      3736749.62     10620660.21
#Sta/Elev= 30
  4761.2  329.71  4804.5325.6341  4825.6  322.69  4833.4  319.25  4843.7  317.95
    4854  312.87  4866.9  308.96  4908.1  300.79  4915.8  297.44  4926.1  295.79
  4936.4  292.14    4970  286.92  4977.8  278.22  4989.5  273.29    4997  273.29
  4999.8  272.79    5003  273.29    5009  273.37  5018.1   276.1  5023.3  284.31
  5029.8  285.75  5071.4  282.55  5096.1  286.71  5174.3288.8949    5217  290.52
  5227.4  292.66  5277.4295.5385  5314.5  300.65    5321  303.98  5331.4  305.72
#Mann= 6 ,-1 , 0
  4761.2     .05       0  4804.5     .12       0    4997     .07       0
    5003     .12       0  5174.3     .05       0  5277.4      .1       0
Bank Sta=4970,5029.8
XS Rating Curve= 0 ,0
Exp/Cntr=0.3,0.1

Type RM Length L Ch R = 1 ,56929   ,571,571,571
BEGIN DESCRIPTION:
TOWN CREEK 80.0
END DESCRIPTION:
XS GIS Cut Line= 3
      3736199.63     10620260.22      3736349.61     10620510.19
       3736549.6     10620860.17
#Sta/Elev= 30
  4723.1  335.96  4746.4  333.24    4758  329.94  4804.7  322.56  4816.4  318.38
  4831.9   316.2  4839.7  311.79  4853.8309.6841  4905.8  298.75    4933  296.07
  4956.3  292.44  4964.1   289.6  4979.6  287.92  4991.3  272.01    4997  271.96
  4999.8  271.46    5003  271.96  5006.8  273.97  5011.7  279.47  5017.5  279.47
  5028.3  282.93  5049.9  283.03    5060  284.87  5124.7  285.67  5228.2291.2413
  5291.8  298.04  5343.7301.2209  5350.8  302.48  5372.4  310.36  5417.7  315.28
#Mann= 6 ,-1 , 0
  4723.1     .05       0  4853.8     .12       0    4997     .07       0
    5003     .12       0  5228.2     .07       0  5343.7      .1       0
Bank Sta=4979.6,5011.7
XS Rating Curve= 0 ,0
Exp/Cntr=0.3,0.1

Type RM Length L Ch R = 1 ,56358   ,696,696,696
BEGIN DESCRIPTION:
TOWN CREEK 79.0
END DESCRIPTION:
XS GIS Cut Line= 3
      3735949.61      10620460.2      3735999.61     10620660.19
      3736199.63     10621060.23
#Sta/Elev= 30
  4789.6  320.45  4848.9  307.58    4872  304.88  4895.2  300.13    4903  297.01
  4913.3   296.3  4949.9288.0872  4972.6  285.24  4977.7   282.5  4985.4  272.05
    4997  270.64  4999.8  270.14    5003  270.64  5018.1  279.01  5040.5  281.84
  5071.2  280.43  5076.8  282.21  5099.2  283.44  5143.9  283.36  5152.3  281.11
  5166.2  283.35  5219.3  286.45  5286.4  294.79  5317.2  302.86  5345.1  303.05
  5359.6308.8707  5375.9  310.21  5384.3  313.39  5417.5319.8983    5443  324.78
#Mann= 6 ,-1 , 0
  4789.6     .05       0  4949.9     .12       0    4997     .07       0
    5003     .12       0  5359.6     .16       0  5417.5     .07       0
Bank Sta=4977.7,5018.1
XS Rating Curve= 0 ,0
Exp/Cntr=0.3,0.1

Type RM Length L Ch R = 1 ,55662   ,578,578,578
BEGIN DESCRIPTION:
TOWN CREEK 78.0
END DESCRIPTION:
XS GIS Cut Line= 3
       3735799.6     10620460.22      3735699.61     10620960.19
      3735799.62     10621160.21
#Sta/Elev= 30
  4483.3  317.98  4554.7  305.59  4575.1  300.84  4585.3  300.66  4636.2  291.13
  4707.6  283.84    4779  281.21  4845.4282.1984    4881  282.51  4891.2  280.78
  4901.4  275.46  4911.6  272.82  4921.8  282.42  4942.2  276.22  4952.4  270.02
  4962.6  270.22  4972.8   281.8    4983  280.54  4990.6  273.65    4996  273.65
    4997  269.43  4999.8  268.93    5003  269.43  5015.5  270.34  5029.5  280.46
  5046.3  282.22  5051.9  284.14  5141.3  290.95  5206.3298.4487  5216.8  299.74
#Mann= 5 ,-1 , 0
  4483.3     .05       0  4845.4     .12       0    4997     .07       0
    5003     .12       0  5206.3     .16       0
Bank Sta=4983,5029.5
XS Rating Curve= 0 ,0
Exp/Cntr=0.3,0.1

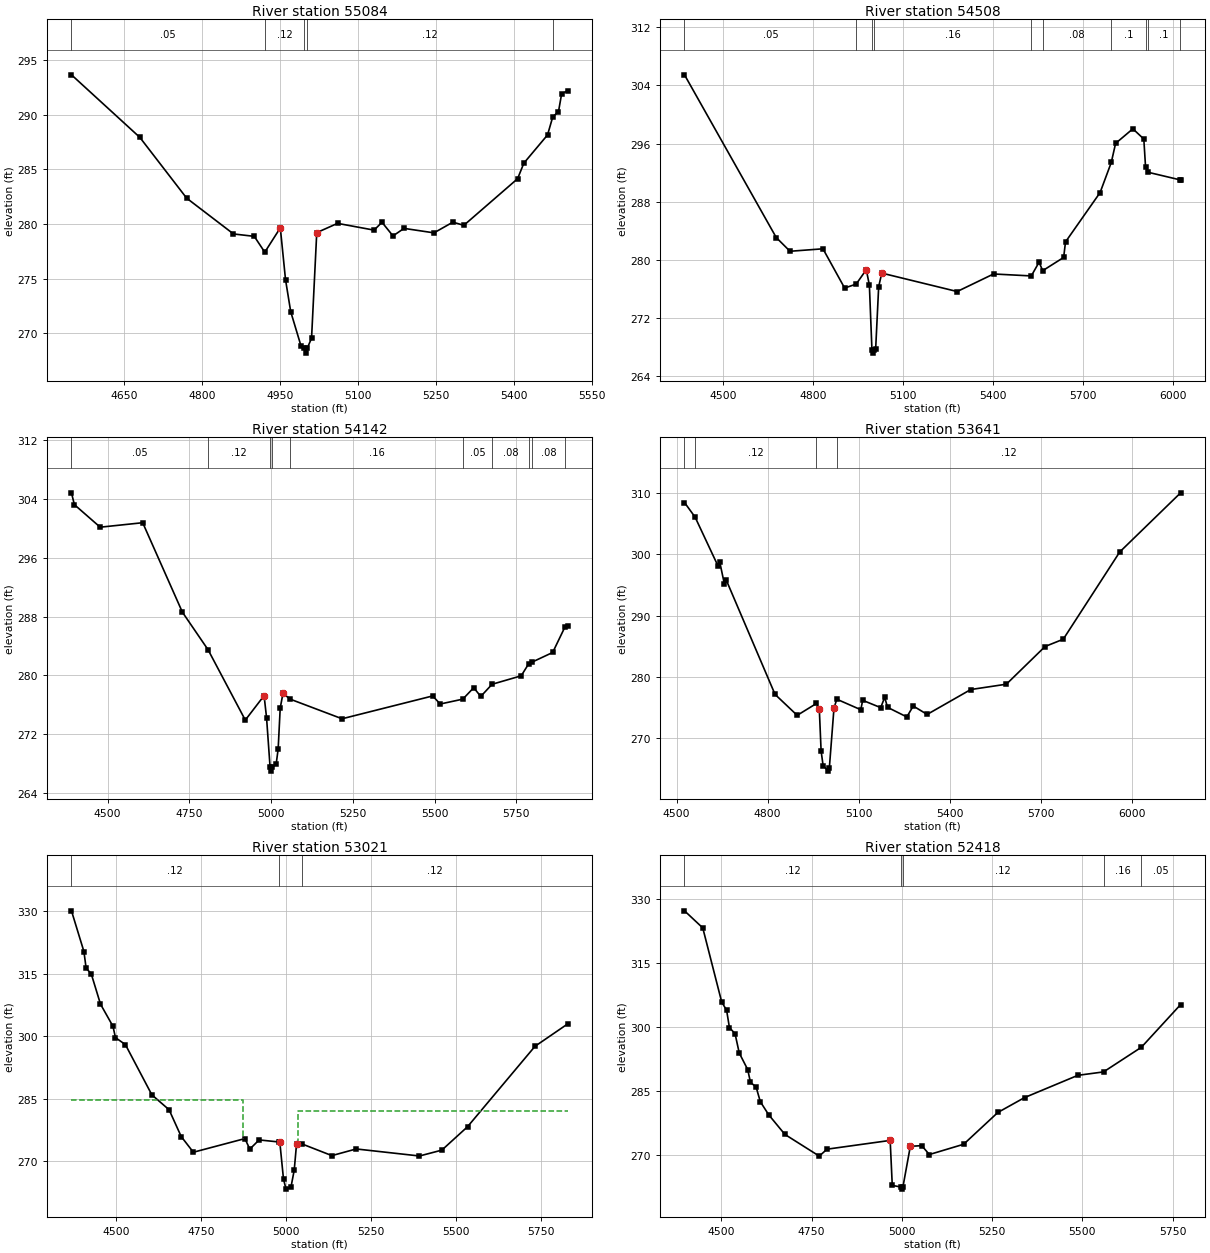
Type RM Length L Ch R = 1 ,55084   ,576,576,576
BEGIN DESCRIPTION:
TOWN CREEK 77.0
END DESCRIPTION:
XS GIS Cut Line= 3
      3735325.71     10620378.77       3735301.4     10620937.83
       3735513.2     10621271.15
#Sta/Elev= 30
    4549  293.67  4680.5  287.94  4770.6  282.37  4860.7  279.09  4900.7  278.87
  4920.9277.4167  4950.8  279.65  4960.8  274.91  4970.8  271.97  4990.8   268.8
    4997  268.67  4999.8  268.17    5003  268.67  5010.9  269.53  5020.9  279.21
  5060.9  280.06  5131.2  279.44  5146.4  280.16  5167.6  278.91  5188.8   279.6
  5246.4  279.19  5282.8  280.17  5303.9  279.88  5407.3  284.15  5419.4  285.58
  5464.9  288.16    5475289.8221    5486   290.3    5492  291.92  5503.5  292.22
#Mann= 5 ,-1 , 0
    4549     .05       0  4920.9     .12       0    4997     .07       0
    5003     .12       0    5475     .05       0
Bank Sta=4950.8,5020.9
XS Rating Curve= 0 ,0
Exp/Cntr=0.3,0.1

Type RM Length L Ch R = 1 ,54508   ,366,366,366
BEGIN DESCRIPTION:
TOWN CREEK 76.0
END DESCRIPTION:
XS GIS Cut Line= 3
      3734707.64     10620232.92       3734926.4     10621087.13
      3735579.15     10621500.31
#Sta/Elev= 30
    4372  305.47    4678  283.04  4723.9  281.15  4833.7  281.49    4906  276.08
  4944.5276.6266  4978.2  278.61  4988.5  276.48    4997  267.61  4999.8  267.11
    5003  267.61  5009.5  267.73  5019.5  276.27  5029.8  278.14  5281.2   275.6
  5402.6  278.02  5528.4277.7504  5554.3  279.64  5566.5278.4756  5636.3   280.3
  5642.5  282.44  5757.8  289.24  5795.1293.3915  5809.5  296.02  5867.1  298.03
  5903.6  296.62  5909.4292.7665  5918.9292.0281  6023.7     291  6026.3     291
#Mann= 10 ,-1 , 0
    4372     .05       0  4944.5     .16       0    4997     .07       0
    5003     .16       0  5528.4     .05       0  5566.5     .08       0
  5795.1      .1       0  5909.4     .08       0  5918.9      .1       0
  6023.7     .16       0
Bank Sta=4978.2,5029.8
XS Rating Curve= 0 ,0
Exp/Cntr=0.3,0.1

Type RM Length L Ch R = 1 ,54142   ,501,501,501
BEGIN DESCRIPTION:
TOWN CREEK 75.0
END DESCRIPTION:
XS GIS Cut Line= 3
      3734193.76     10620482.97      3734659.04     10621125.33
      3735287.63     10621485.84
#Sta/Elev= 30
  4389.3  304.87  4398.2  303.26  4477.2  300.19  4607.2   300.8  4728.6  288.62
    4807283.5135  4921.1  273.92  4978.6  277.25  4986.1  274.26    4997  267.47
  4999.8  266.97    5003  267.47  5015.5  267.92  5021.6  269.97  5027.9  275.55
  5036.3  277.55  5059.2276.7583  5217.2   274.1  5494.4  277.21  5517.4  276.11
  5586.5276.7727  5619.9  278.33  5641.5  277.14  5676.1 278.799  5765.2  279.95
  5787.7281.5622  5797.8281.8027  5861.5  283.13  5899.3286.6256  5907.1  286.79
#Mann= 10 ,-1 , 0
  4389.3     .05       0    4807     .12       0    4997     .07       0
    5003     .12       0  5059.2     .16       0  5586.5     .05       0
  5676.1     .08       0  5787.7      .1       0  5797.8     .08       0
  5899.3      .1       0
Bank Sta=4978.6,5036.3
XS Rating Curve= 0 ,0
Exp/Cntr=0.3,0.1

Type RM Length L Ch R = 1 ,53641   ,620,620,620
BEGIN DESCRIPTION:
TOWN CREEK 74.0
END DESCRIPTION:
XS GIS Cut Line= 3
      3733863.92     10620785.07      3734304.88      10621479.5
      3734506.28     10622264.26
#Sta/Elev= 30
  4526.3  308.48  4561.3306.0862  4636.3  298.16  4642.2  298.81  4657.5   295.2
  4663.4  295.87  4824.3  277.18  4897.2  273.76  4960.7   275.7    4970  274.77
  4975.9  267.95  4982.5  265.56  4999.8  264.66    5003  265.16  5018.3  274.95
  5027.6  276.39  5106.4  274.68  5112.8  276.21    5172  275.02  5185.2  276.69
  5194.5  275.07    5258   273.5  5279.2  275.28  5324.9  273.91  5468.4  277.97
  5585.6  278.84    5713  284.99  5772.9  286.18  5958.7  300.41  6159.1  310.06
#Mann= 4 ,-1 , 0
  4526.3     .05       0  4561.3     .12       0  4960.7     .13       0
  5027.6     .12       0
Bank Sta=4970,5018.3
XS Rating Curve= 0 ,0
Exp/Cntr=0.3,0.1

Type RM Length L Ch R = 1 ,53021   ,603,603,603
BEGIN DESCRIPTION:
TOWN CREEK 73.0
END DESCRIPTION:
XS GIS Cut Line= 3
      3733349.61     10621110.19      3733849.61     10621460.19
      3734249.59     10622210.16
#Sta/Elev= 30
  4368.2  330.16  4404.8  320.39  4411.4  316.35  4426.2  315.08  4453.6  307.75
  4490.3  302.43  4497.7   299.7  4526.9  298.03  4604.9  285.95  4655.5  282.38
  4691.2  275.94    4727  272.17  4878.7  275.45  4893.1  272.92  4920.5  275.13
  4978.5  274.64  4981.4  274.64  4992.3  265.71  4999.8  263.31  5014.3  263.81
  5023.9  267.89  5030.6  274.06  5046.5  274.17  5134.7  271.36  5206.3  272.96
  5392.6  271.27  5458.4  272.68  5533.9  278.29  5732.6  297.62  5828.5  302.98
#Mann= 3 ,-1 , 0
  4368.2     .12       0  4978.5     .13       0  5046.5     .12       0
#XS Ineff= 2 , 0
         4872.95  284.73 5035.57          282.13
Permanent Ineff=
       F       F
Bank Sta=4981.4,5030.6
XS Rating Curve= 0 ,0
Exp/Cntr=0.3,0.1

Type RM Length L Ch R = 1 ,52418   ,622,622,622
BEGIN DESCRIPTION:
TOWN CREEK 72.0
END DESCRIPTION:
XS GIS Cut Line= 3
       3733249.6     10621210.17      3733549.61     10621710.19
      3733799.61      10622460.2
#Sta/Elev= 30
  4398.2  327.13  4448.8  323.14  4501.2  305.83  4514.8  303.91  4522.6  299.87
  4538.2  298.42  4549.8  293.92  4573.2  290.05  4580.9  287.05  4596.5  285.98
  4608.1  282.55  4631.5  279.47  4676.2   274.9  4771.4  269.83  4792.8  271.45
  4967.7   273.5  4973.5  262.99    4997  262.62  4999.8  262.12    5003  262.62
  5023.5  272.12  5055.1  272.28  5076.2   270.2  5171.1   272.6  5265.9  280.03
  5339.7   283.5  5487.3   288.7  5558.5289.5016  5663.3 295.263  5771.9  305.23
#Mann= 5 ,-1 , 0
  4398.2     .12       0    4997     .07       0    5003     .12       0
  5558.5     .16       0  5663.3     .05       0
Bank Sta=4967.7,5023.5
XS Rating Curve= 0 ,0
Exp/Cntr=0.3,0.1

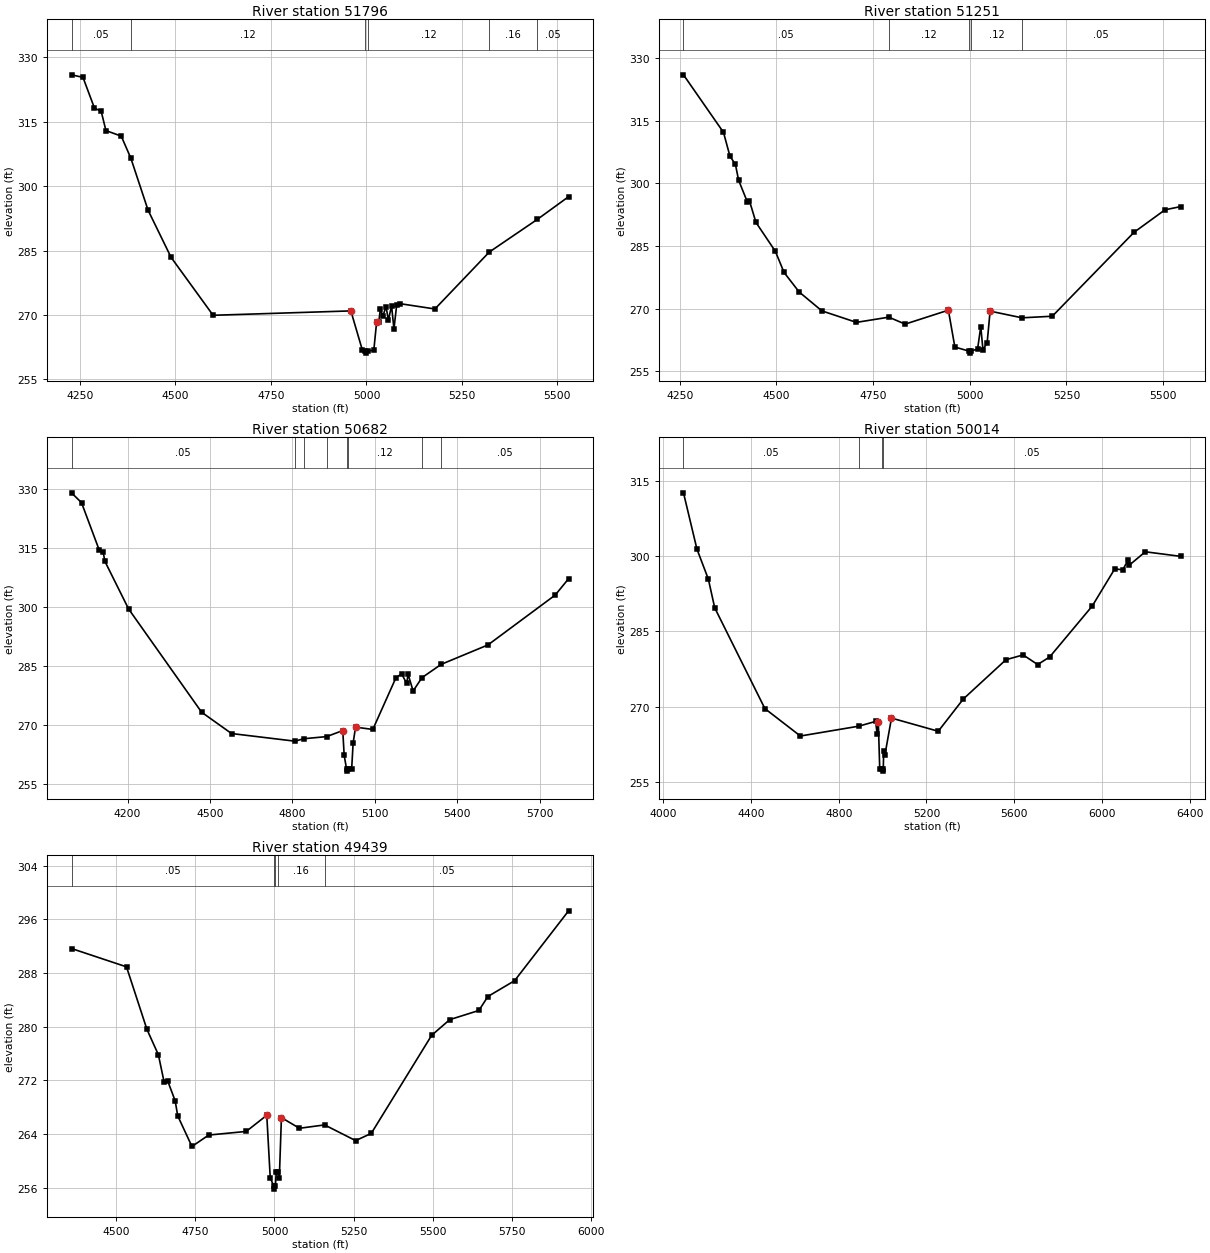
Type RM Length L Ch R = 1 ,51796   ,545,545,545
BEGIN DESCRIPTION:
TOWN CREEK 71.0
END DESCRIPTION:
XS GIS Cut Line= 3
      3733149.61     10621210.22      3733199.61     10622010.19
      3733499.59     10622410.17
#Sta/Elev= 30
  4227.8  325.92  4257.8  325.33  4287.9  318.16  4305.4  317.45  4317.9  312.94
    4358  311.65  4383.2306.4975  4428.2  294.41  4488.3  283.45  4598.5  269.94
  4959.2  270.96  4989.3  261.84    4997  261.63  4999.8  261.13    5003  261.63
  5019.3  261.81  5026.8  268.49  5032.5  268.49  5036.6  271.48  5042.9  269.72
  5051.2  271.96  5057.5  268.86  5065.8  272.14    5072  266.75  5079.3  272.43
  5086.6  272.66  5179.3  271.41  5321.6284.6584  5447.8292.2879  5529.3  297.55
#Mann= 6 ,-1 , 0
  4227.8     .05       0  4383.2     .12       0    4997     .07       0
    5003     .12       0  5321.6     .16       0  5447.8     .05       0
Bank Sta=4959.2,5026.8
XS Rating Curve= 0 ,0
Exp/Cntr=0.3,0.1

Type RM Length L Ch R = 1 ,51251   ,569,569,569
BEGIN DESCRIPTION:
TOWN CREEK 70.0
END DESCRIPTION:
XS GIS Cut Line= 3
       3733099.6      10621310.2      3732749.61     10622010.19
      3732699.61     10622510.18
#Sta/Elev= 30
  4259.8  325.98  4363.2  312.21    4380  306.48    4394  304.57  4402.3  300.76
  4424.7   295.6  4430.3  295.84  4447.1  290.67  4497.4  283.73  4519.7   278.7
  4558.9  274.01  4617.6  269.49    4707  266.74  4790.7267.9866  4832.8  266.32
  4944.6  269.66  4961.4  260.84    4997  259.88  4999.8  259.38    5003  259.88
  5020.1  260.35  5028.4  265.73    5034  260.18  5044.9  261.89  5052.5  269.43
  5134.9 267.832  5213.3  268.21  5424.3  288.27  5504.7  293.68  5544.9  294.44
#Mann= 5 ,-1 , 0
  4259.8     .05       0  4790.7     .12       0    4997     .07       0
    5003     .12       0  5134.9     .05       0
Bank Sta=4944.6,5052.5
XS Rating Curve= 0 ,0
Exp/Cntr=0.3,0.1

Type RM Length L Ch R = 1 ,50682   ,668,668,668
BEGIN DESCRIPTION:
TOWN CREEK 69.0
END DESCRIPTION:
XS GIS Cut Line= 3
      3733099.61     10621260.19      3732299.61     10621810.19
       3732049.6     10622610.21
#Sta/Elev= 30
  3995.9  329.07  4032.3  326.57    4096  314.66  4110.9  314.06  4117.3  311.67
  4203.6  299.56  4469.5  273.31  4578.4   267.9  4808.6 265.964  4842.3266.5888
  4924.3 267.123    4983  268.66  4988.2  262.33    4997  258.85  4999.8  258.35
    5003  258.85  5015.4  258.85  5020.7  265.48  5029.6  269.53  5092.4  268.94
  5176.3  282.04  5197.2   283.1  5215.5  280.64  5220.8  282.94  5239.1  278.72
  5271.4282.1113  5341.4285.4876  5511.5  290.42  5756.2  303.09  5804.9  307.25
#Mann= 8 ,-1 , 0
  3995.9     .05       0  4808.6     .16       0  4842.3     .05       0
  4924.3     .12       0    4997     .07       0    5003     .12       0
  5271.4     .16       0  5341.4     .05       0
Bank Sta=4983,5029.6
XS Rating Curve= 0 ,0
Exp/Cntr=0.3,0.1

Type RM Length L Ch R = 1 ,50014   ,575,575,575
BEGIN DESCRIPTION:
TOWN CREEK 68.0
END DESCRIPTION:
XS GIS Cut Line= 3
       3732849.6     10621110.19      3732049.61     10621460.19
      3730749.65     10621960.17
#Sta/Elev= 30
  4092.3  312.66  4153.5  301.44  4205.7  295.42  4234.6  289.71  4463.4  269.58
  4625.2  264.11  4891.6266.0754  4968.2  267.03  4975.1   264.5  4980.5  266.83
  4986.9   257.6    4997   257.6  4999.8   257.1    5003   257.6  5005.1  261.15
  5010.5  260.33  5040.5  267.69  5253.7  265.06  5368.4  271.52  5562.3  279.34
  5640.5   280.3  5706.9  278.38  5761.6  279.89  5955.5  290.05  6058.3  297.48
  6094.8  297.29  6119.4  299.26  6124.8  298.23  6197.6  300.89  6358.3  299.98
#Mann= 4 ,-1 , 0
  4092.3     .05       0  4891.6     .12       0    4997     .07       0
    5003     .05       0
Bank Sta=4980.5,5040.5
XS Rating Curve= 0 ,0
Exp/Cntr=0.3,0.1

Type RM Length L Ch R = 1 ,49439   ,543,543,543
BEGIN DESCRIPTION:
TOWN CREEK 67.0
END DESCRIPTION:
XS GIS Cut Line= 3
      3731999.62     10620560.16      3731749.61     10621160.19
       3731049.6     10621760.19
#Sta/Elev= 30
  4358.1  291.66    4532  288.93  4596.5  279.62  4632.8  275.83  4650.6  271.83
    4662  271.96  4685.8  268.97    4694  266.72  4738.9  262.16    4792  263.86
  4910.6   264.4  4975.6  266.81  4986.5  257.52    4997   256.3  4999.8   255.8
    5003   256.3  5005.4  258.35  5009.9  258.35  5015.3   257.5  5021.9  266.46
  5078.9  264.87  5158.5265.3705  5256.7  263.03  5306.1  264.11  5497.1  278.73
  5554.2  281.06  5646.4  282.43  5674.9  284.51  5759.4  286.87  5930.1  297.28
#Mann= 5 ,-1 , 0
  4358.1     .05       0    4997     .03       0    5003     .05       0
  5009.9     .16       0  5158.5     .05       0
Bank Sta=4975.6,5021.9
XS Rating Curve= 0 ,0
Exp/Cntr=0.3,0.1