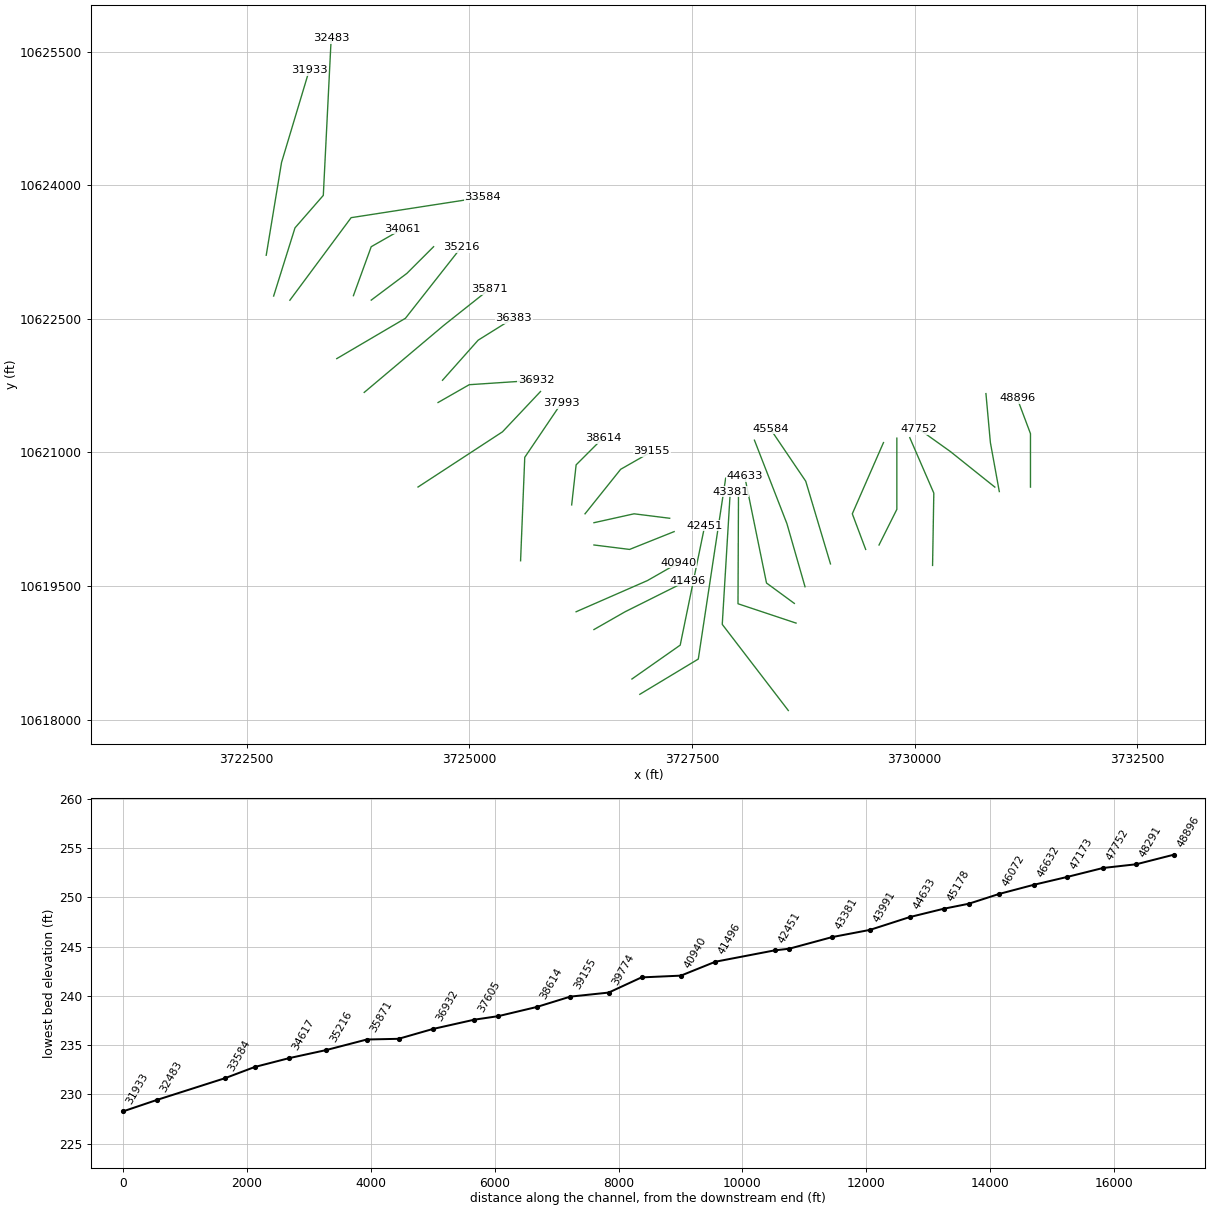
HEC-RAS study TOWN CREEK.prj: TOWN CREEK Base Level Engineering

--- TOWN CREEK.g01 (geometry) --- (continued)

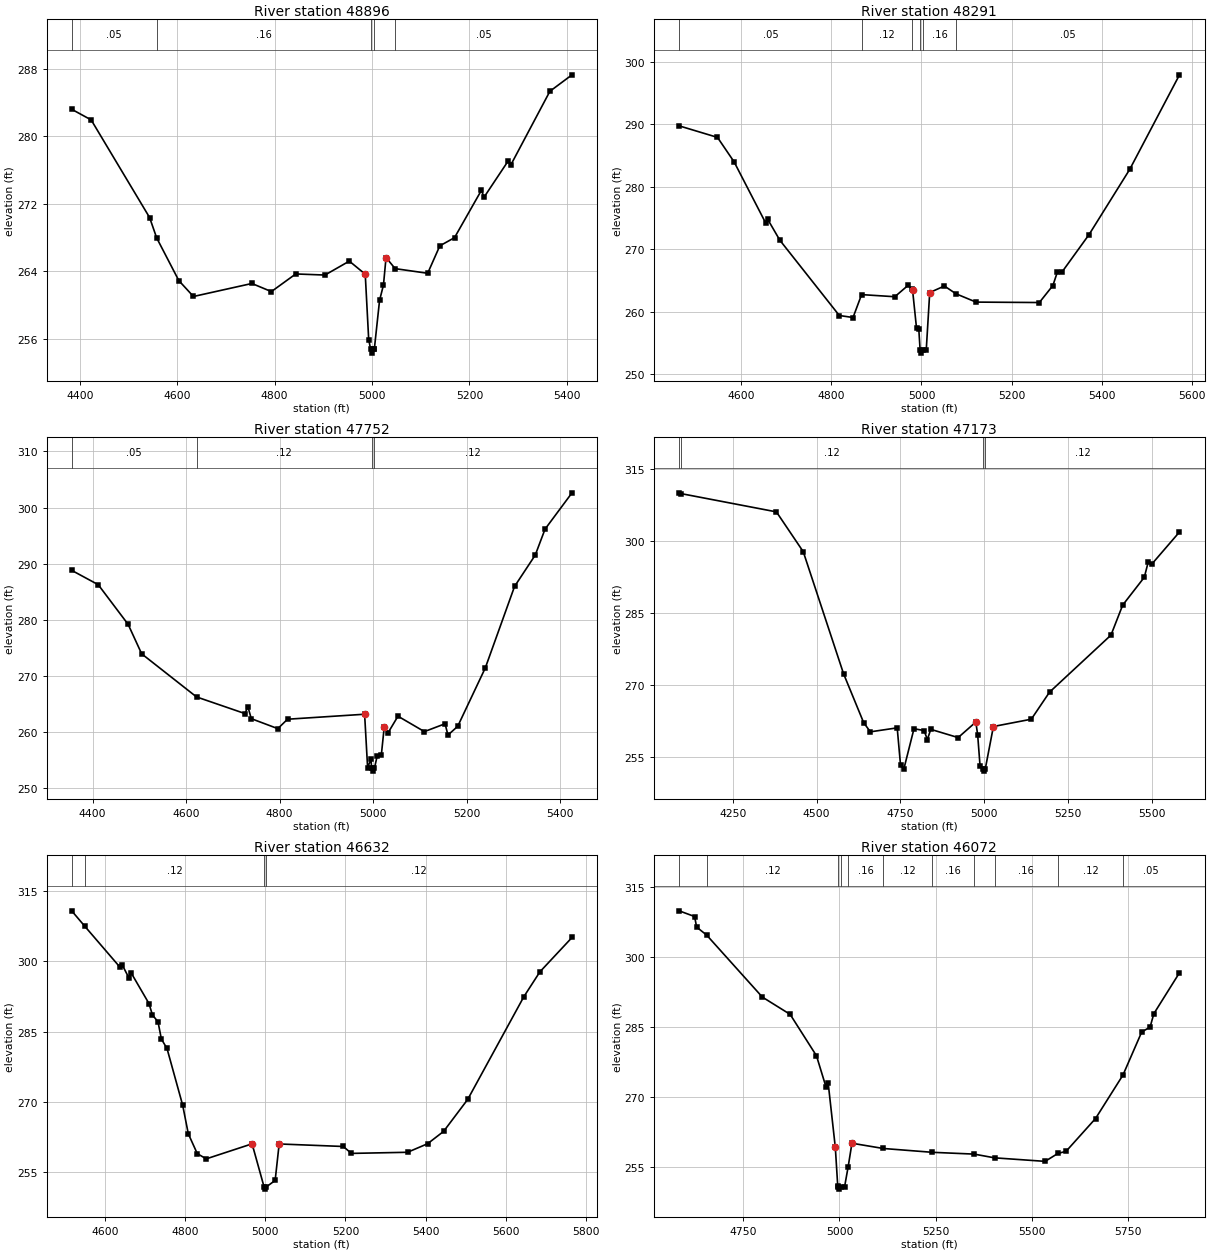
Type RM Length L Ch R = 1 ,48896   ,605,605,605
BEGIN DESCRIPTION:
TOWN CREEK 66.0
END DESCRIPTION:
XS GIS Cut Line= 3
      3731299.61     10620610.16      3731299.61     10621210.19
      3731149.62     10621610.17
#Sta/Elev= 30
  4383.3  283.21  4423.3  281.95  4543.3  270.38  4557.8 267.969  4603.3  262.91
  4633.3  261.03  4753.3  262.57  4793.3  261.61  4843.3   263.7  4903.3  263.57
  4953.3  265.22    4986  263.67  4993.1  255.91    4997  254.82  4999.8  254.32
    5003  254.82  5004.7  254.82  5015.4  260.57  5023.4  262.39  5028.7  265.64
  5047.4  264.33  5114.2  263.78  5139.1  267.03  5169.3     268  5224.5  273.61
  5229.9  272.79  5279.7  277.11    5285  276.63  5365.1  285.34  5410.5  287.29
#Mann= 5 ,-1 , 0
  4383.3     .05       0  4557.8     .16       0    4997     .07       0
    5003     .16       0  5047.4     .05       0
Bank Sta=4986,5028.7
XS Rating Curve= 0 ,0
Exp/Cntr=0.3,0.1

Type RM Length L Ch R = 1 ,48291   ,539,539,539
BEGIN DESCRIPTION:
TOWN CREEK 65.0
END DESCRIPTION:
XS GIS Cut Line= 3
      3730949.61      10620560.2      3730849.61     10621110.19
      3730799.61     10621660.22
#Sta/Elev= 30
  4461.8  289.78  4546.9  287.93  4583.8  284.01  4653.6  274.26  4658.7  274.77
  4685.4  271.45  4817.5  259.38    4848  259.06    4867262.7308  4940.8  262.39
    4970   264.2  4978.1263.6707  4980.1  263.54    4989  257.35  4994.1  257.15
    4997  253.85  4999.8  253.35    5003  253.85  5010.6  253.85  5018.3  263.06
  5050.9  264.11  5076.6262.8628  5121.2  261.53  5261.8  261.46  5291.9  264.19
    5302  266.38    5312  266.34  5372.2  272.35  5462.6  282.81  5573.1  297.96
#Mann= 6 ,-1 , 0
  4461.8     .05       0    4867     .12       0  4978.1     .16       0
    4997     .07       0    5003     .16       0  5076.6     .05       0
Bank Sta=4980.1,5018.3
XS Rating Curve= 0 ,0
Exp/Cntr=0.3,0.1

Type RM Length L Ch R = 1 ,47752   ,579,579,579
BEGIN DESCRIPTION:
TOWN CREEK 64.0
END DESCRIPTION:
XS GIS Cut Line= 3
       3730899.6      10620610.2      3730399.61     10621010.19
      3730049.62     10621260.18
#Sta/Elev= 30
  4355.3  288.79  4412.1  286.23  4476.1  279.15    4505   273.9  4622.4266.2069
  4725.9  263.24  4732.3  264.46  4739.5  262.33  4796.3  260.55  4817.1  262.23
    4982  263.12  4988.4   253.6  4995.6   255.1    4997  253.47  4999.8  252.97
    5003  253.47  5009.1  255.75  5017.7   255.8  5023.9  260.78  5032.5  259.86
  5053.4  262.77  5109.9  260.02  5154.1  261.42  5160.3   259.4  5181.2  260.97
  5240.2  271.38  5302.8  285.92  5347.1  291.52    5368  296.14  5425.7  302.62
#Mann= 4 ,-1 , 0
  4355.3     .05       0  4622.4     .12       0    4997     .07       0
    5003     .12       0
Bank Sta=4982,5023.9
XS Rating Curve= 0 ,0
Exp/Cntr=0.3,0.1

Type RM Length L Ch R = 1 ,47173   ,541,541,541
BEGIN DESCRIPTION:
TOWN CREEK 63.0
END DESCRIPTION:
XS GIS Cut Line= 3
      3730200.63     10619730.47      3730214.52     10620542.95
      3729944.74     10621165.52
#Sta/Elev= 30
  4090.6  310.06  4094.9309.9141  4380.4  306.09  4460.4  297.79  4580.4  272.38
  4640.4  262.17  4660.4  260.25  4740.4  261.08  4750.4  253.24  4760.4  252.56
  4790.4   260.9  4820.4  260.52  4830.4  258.65  4840.4  260.77    4922  259.05
  4974.7  262.29  4980.2  259.62  4987.4  253.07    4997  252.56  4999.8  252.06
    5003  252.56  5027.1  261.36    5140  262.88  5194.4  268.52  5377.5  280.41
  5412.4  286.66  5476.9  292.47  5488.7   295.7  5499.6  295.24  5581.7   301.9
#Mann= 4 ,-1 , 0
  4090.6     .05       0  4094.9     .12       0    4997     .07       0
    5003     .12       0
Bank Sta=4974.7,5027.1
XS Rating Curve= 0 ,0
Exp/Cntr=0.3,0.1

Type RM Length L Ch R = 1 ,46632   ,560,560,560
BEGIN DESCRIPTION:
TOWN CREEK 62.0
END DESCRIPTION:
XS GIS Cut Line= 3
      3729599.62      10619960.2      3729799.61     10620360.19
      3729799.61     10621160.19
#Sta/Elev= 30
  4517.5  310.85  4550.2307.5421  4637.7   298.8  4643.3  299.31    4660   296.5
  4665.6  297.58  4710.3  290.98  4718.7  288.58  4732.7  287.08  4741.1  283.39
  4755.1  281.38  4794.2  269.22  4808.2  263.11  4830.5  258.87  4852.9  257.74
  4967.2  260.96    4997  251.76  4999.8  251.26    5003  251.76  5024.7  253.12
  5034.7  260.93  5194.7  260.39  5214.7  258.91  5354.7  259.15  5404.7  260.98
  5444.7  263.63  5504.7  270.47  5644.7  292.47  5684.7  297.79  5764.7  305.14
#Mann= 4 ,-1 , 0
  4517.5     .05       0  4550.2     .12       0    4997     .07       0
    5003     .12       0
Bank Sta=4967.2,5034.7
XS Rating Curve= 0 ,0
Exp/Cntr=0.3,0.1

Type RM Length L Ch R = 1 ,46072   ,488,488,488
BEGIN DESCRIPTION:
TOWN CREEK 61.0
END DESCRIPTION:
XS GIS Cut Line= 3
      3729449.63     10619910.15      3729299.61     10620310.19
      3729649.63     10621110.23
#Sta/Elev= 30
  4583.3  309.87  4623.4  308.65  4628.7  306.39  4654.7304.6851  4799.6  291.41
  4871.7  287.72  4940.2  278.86  4965.2  272.12  4970.5  273.11  4989.2  259.24
  4995.4  251.08    4997  250.83  4999.8  250.33    5003  250.83  5013.3  250.85
  5022.6  255.14  5032.4  260.15  5113.5259.0296    5241258.2082  5349.9257.8227
    5403257.0246  5534.5  256.27  5567.6257.9578    5589  258.42  5665.5  265.43
  5736.9274.7421  5785.5  283.93  5807.4  285.01  5817.1  287.86  5883.8  296.63
#Mann= 11 ,-1 , 0
  4583.3     .05       0  4654.7     .12       0    4997     .07       0
    5003     .12       0  5022.6     .16       0  5113.5     .12       0
    5241     .16       0  5349.9     .12       0    5403     .16       0
  5567.6     .12       0  5736.9     .05       0
Bank Sta=4989.2,5032.4
XS Rating Curve= 0 ,0
Exp/Cntr=0.3,0.1

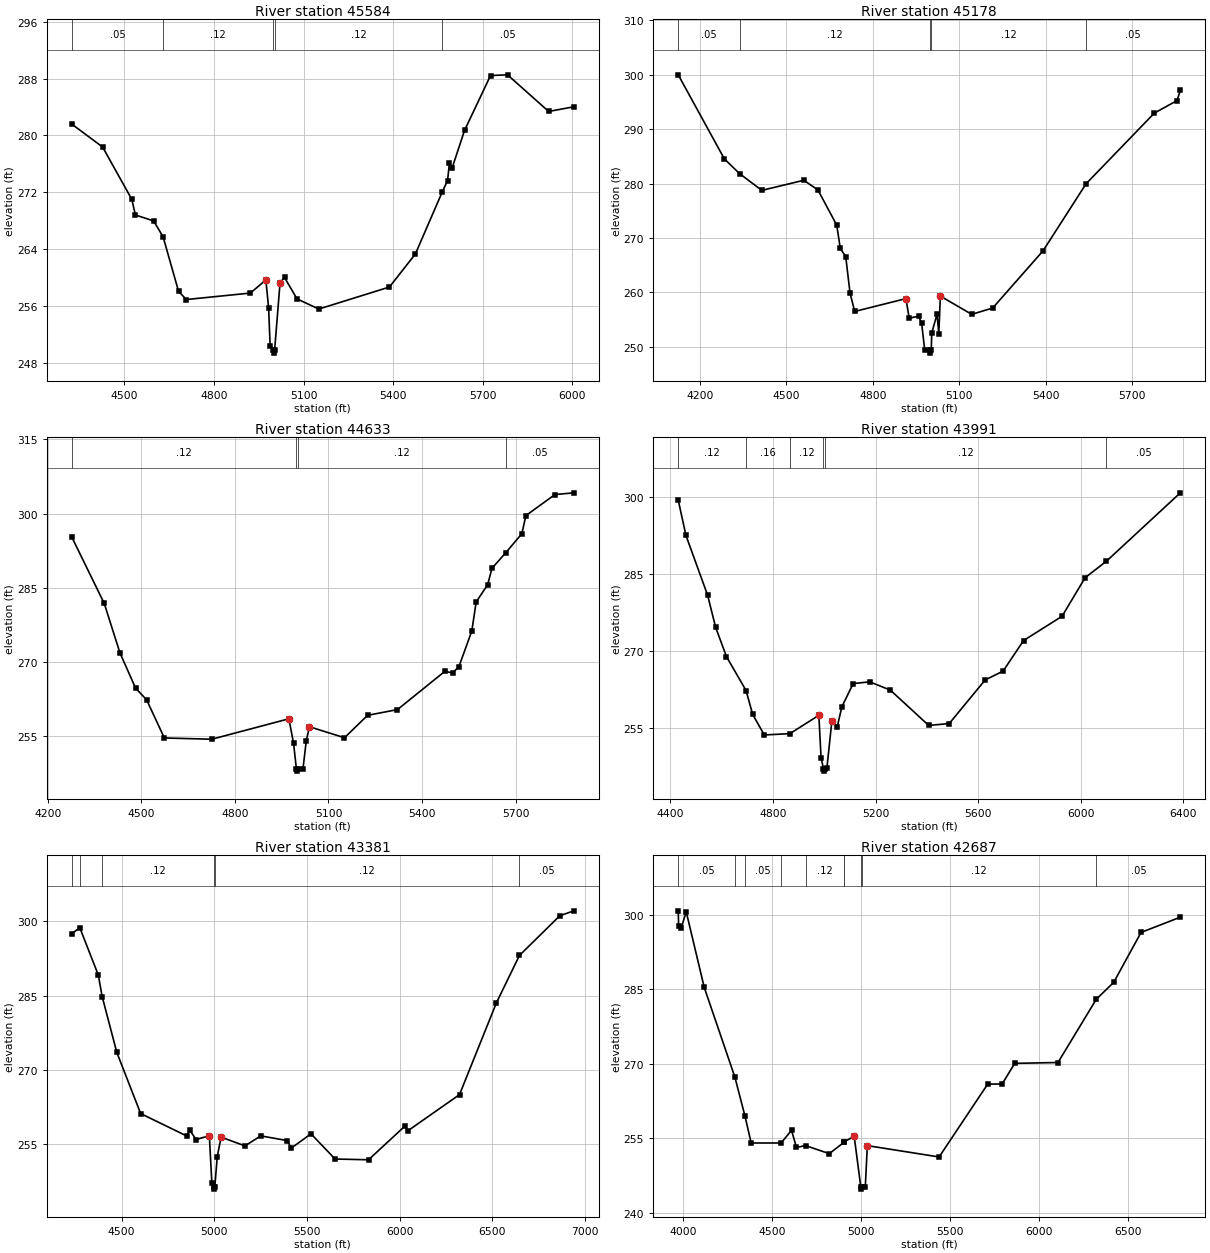
Type RM Length L Ch R = 1 ,45584   ,406,406,406
BEGIN DESCRIPTION:
TOWN CREEK 60.0
END DESCRIPTION:
XS GIS Cut Line= 3
      3729054.63     10619747.62      3728776.86     10620676.43
      3728378.06     10621265.96
#Sta/Elev= 30
  4323.6   281.6  4426.9  278.37  4524.6     271  4536.7   268.8  4597.7  267.96
  4629.4265.7263  4681.2  258.04  4707.4  256.89  4921.7   257.8  4973.4  259.65
  4982.7  255.76  4987.9  250.29    4997  249.84  4999.8  249.34    5003  249.84
    5021  259.24    5036     260  5077.8  256.98  5150.9  255.55  5387.2  258.65
  5474.1   263.3  5563.9  272.02    5582  273.65    5588  276.09  5596.9  275.38
  5638.9  280.72  5725.8  288.44  5782.7  288.54  5920.5  283.38  6004.8  284.04
#Mann= 5 ,-1 , 0
  4323.6     .05       0  4629.4     .12       0    4997     .07       0
    5003     .12       0  5563.9     .05       0
Bank Sta=4973.4,5021
XS Rating Curve= 0 ,0
Exp/Cntr=0.3,0.1

Type RM Length L Ch R = 1 ,45178   ,545,545,545
BEGIN DESCRIPTION:
Mapping XS 86662fb9
END DESCRIPTION:
XS GIS Cut Line= 3
      3728768.77     10619491.32      3728565.63     10620199.69
      3728201.05     10621137.18
#Sta/Elev= 30
  4124.8  299.98  4284.9  284.53  4337.5 281.834  4414.9  278.74  4560.5   280.6
  4609.4  278.84    4675  272.36  4687.3  268.08  4706.2  266.57  4721.1  259.88
  4737.4  256.49  4915.1  258.85  4926.6  255.24  4958.8  255.63  4969.5  254.39
  4980.3  249.46    4997  249.33  4999.8  248.83    5003  249.33  5004.8  252.51
  5023.2  256.01  5029.3  252.34  5034.7  259.31  5143.5  255.96  5216.3  257.12
  5391.1  267.63  5540.4 279.948  5777.3  292.94  5856.3  295.25  5867.6  297.14
#Mann= 5 ,-1 , 0
  4124.8     .05       0  4337.5     .12       0    4997     .07       0
    5003     .12       0  5540.4     .05       0
Bank Sta=4915.1,5034.7
XS Rating Curve= 0 ,0
Exp/Cntr=0.3,0.1

Type RM Length L Ch R = 1 ,44633   ,642,642,642
BEGIN DESCRIPTION:
Mapping XS 3523af8f
END DESCRIPTION:
XS GIS Cut Line= 3
        3728649.     10619303.83      3728336.47     10619533.02
      3728091.68     10620730.91
#Sta/Elev= 30
  4276.7  295.28  4380.9  281.85  4431.1  271.89  4481.2  264.77  4516.7  262.39
  4573.6  254.69  4725.6  254.43  4972.9  258.56    4988  253.64    4997  248.49
  4999.8  247.99    5003  248.49  5018.3  248.49  5028.8  254.15    5039  256.95
  5151.3  254.73  5225.4  259.26  5321.3  260.42  5472.7  268.12  5498.3  267.85
  5518.1  269.06  5559.6  276.28  5573.7  282.16  5610.6  285.65  5624.2  288.95
  5668.9 292.134  5720.1  295.94  5733.1   299.6  5826.2  303.85  5886.9   304.2
#Mann= 4 ,-1 , 0
  4276.7     .12       0    4997     .07       0    5003     .12       0
  5668.9     .05       0
Bank Sta=4972.9,5039
XS Rating Curve= 0 ,0
Exp/Cntr=0.3,0.1

Type RM Length L Ch R = 1 ,43991   ,610,610,610
BEGIN DESCRIPTION:
Mapping XS 619b8410
END DESCRIPTION:
XS GIS Cut Line= 3
      3728668.11      10619082.8      3728016.49     10619300.01
      3728022.28     10620571.52
#Sta/Elev= 30
  4430.5  299.32  4460.5  292.47  4544.9  280.87  4576.5   274.6  4618.7  268.92
  4695.2262.3287  4720.7  257.72  4766.2  253.71  4866.2 253.972    4979  257.53
  4987.6  249.31    4997  247.19  4999.8  246.69    5003  247.19  5010.6  247.39
  5029.8  256.46  5050.8  255.31  5068.6  259.17  5113.1   263.7  5177.6  264.02
  5257.6  262.43  5407.6  255.56  5487.6  255.93  5627.6  264.39  5697.6  266.11
  5777.6  272.05  5927.6  276.76  6017.6  284.25  6100.7287.4532  6388.9  300.73
#Mann= 6 ,-1 , 0
  4430.5     .12       0  4695.2     .16       0  4866.2     .12       0
    4997     .07       0    5003     .12       0  6100.7     .05       0
Bank Sta=4979,5029.8
XS Rating Curve= 0 ,0
Exp/Cntr=0.3,0.1

Type RM Length L Ch R = 1 ,43381   ,694,694,694
BEGIN DESCRIPTION:
TOWN CREEK 59.0
END DESCRIPTION:
XS GIS Cut Line= 3
      3728581.27     10618100.93      3727839.81      10619068.3
      3727929.54     10620556.06
#Sta/Elev= 30
    4231  297.48  4274.4298.6776  4374.2  289.14  4394.9284.8041  4473.9  273.55
  4602.7   261.2    4852  256.67  4866.5  257.91  4901.8  255.96  4973.4  256.73
    4987  247.12    4997  246.46  4999.8  245.96    5003  246.46    5016  252.52
  5036.9  256.45  5165.6  254.68  5250.8   256.7  5394.1  255.75  5414.9  254.22
  5521.9  257.11  5652.1  252.03  5832.4  251.88  6027.8  258.64  6042.8  257.68
  6323.3  265.02  6522.4  283.53  6646.7  293.09  6864.3  301.09  6940.3  302.09
#Mann= 6 ,-1 , 0
    4231     .12       0  4274.4     .16       0  4394.9     .12       0
    4997     .07       0    5003     .12       0  6646.7     .05       0
Bank Sta=4973.4,5036.9
XS Rating Curve= 0 ,0
Exp/Cntr=0.3,0.1

Type RM Length L Ch R = 1 ,42687   ,236,236,236
BEGIN DESCRIPTION:
TOWN CREEK 58.0
END DESCRIPTION:
XS GIS Cut Line= 3
       3726914.6     10618283.03      3727570.84     10618678.86
      3727878.13     10620710.07
#Sta/Elev= 30
  3971.5  300.76  3973.6  297.74    3989  297.38  4016.3  300.58  4117.5  285.36
  4289.9267.2988  4346.5259.4637  4381.3  254.06  4549.4  254.06    4608  256.61
  4635.6  253.16  4686.7253.5431  4820.1  251.91  4903.1254.2127  4904.3254.3204
  4960.1  255.38    4997  245.28  4999.8  244.78    5003  245.28  5022.4  245.28
    5034  253.53  5437.1  251.25  5710.1  265.91  5791.1  265.92  5861.9  270.08
  6104.9  270.25  6320.4282.9837  6418.1  286.37  6571.5  296.41  6792.2  299.48
#Mann= 10 ,-1 , 0
  3971.5     .05       0  4289.9     .16       0  4346.5     .05       0
  4549.4     .16       0  4686.7     .12       0  4903.1     .16       0
  4904.3     .12       0    4997     .07       0    5003     .12       0
  6320.4     .05       0
Bank Sta=4960.1,5034
XS Rating Curve= 0 ,0
Exp/Cntr=0.3,0.1

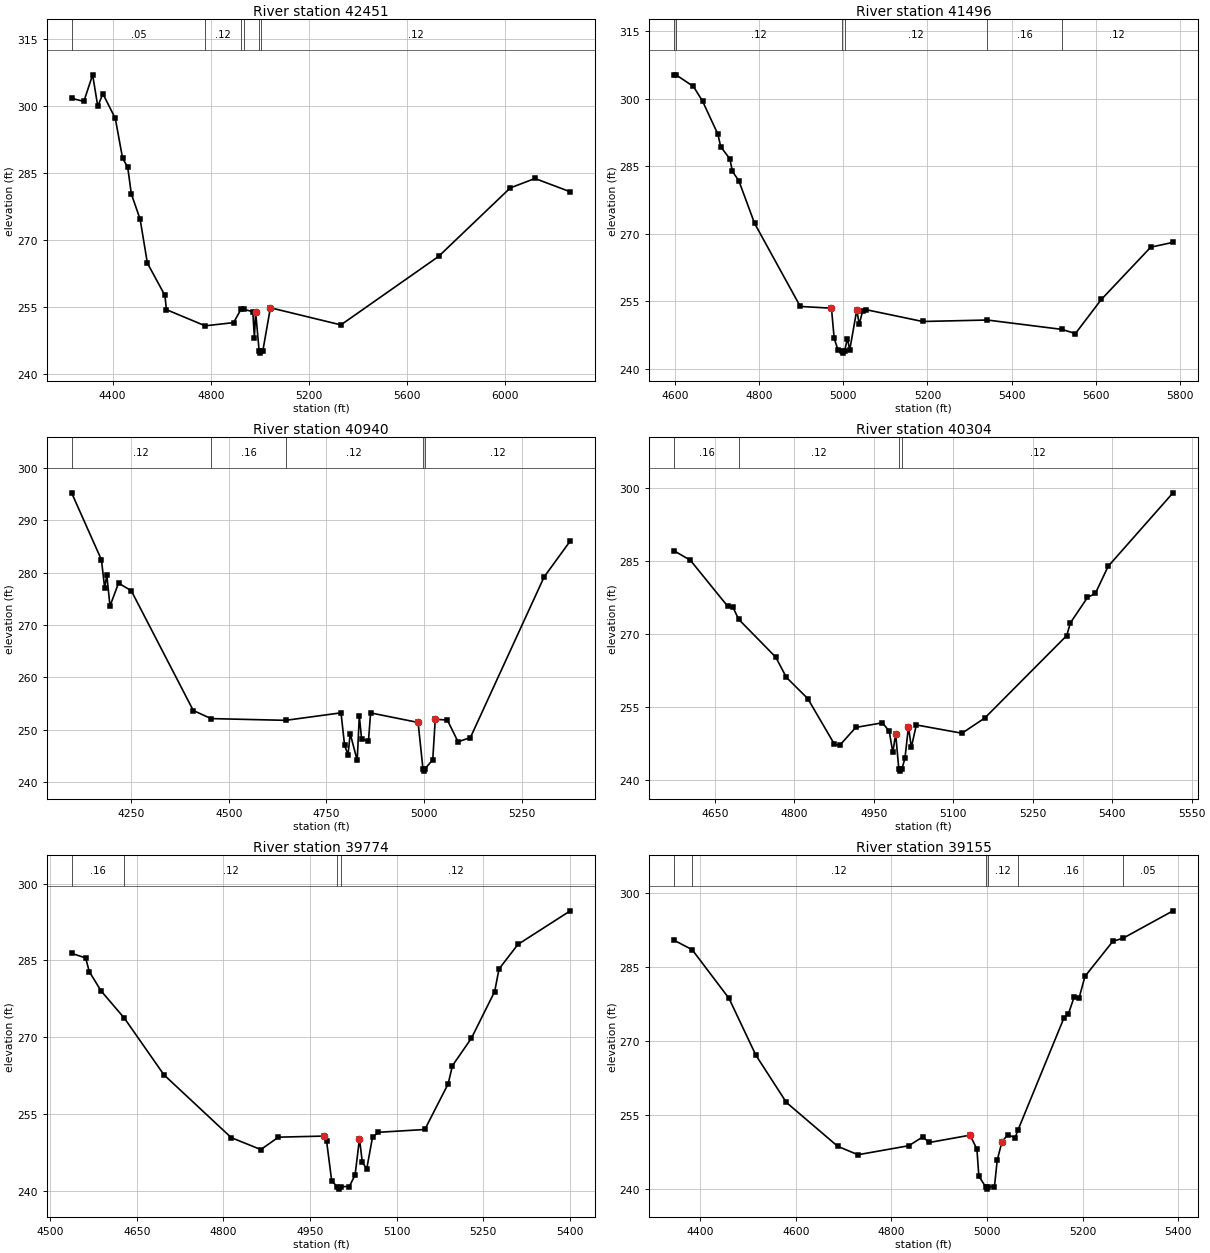
Type RM Length L Ch R = 1 ,42451   ,955,955,955
BEGIN DESCRIPTION:
TOWN CREEK 57.0
END DESCRIPTION:
XS GIS Cut Line= 3
      3726826.04     10618454.89      3727367.72     10618835.11
      3727643.37     10620176.99
#Sta/Elev= 30
    4233  301.74  4282.9  301.05  4318.7  307.01  4339.6  299.96  4360.5  302.76
    4411  297.24  4440.7  288.32  4461.6   286.3  4476.4  280.29  4512.1  274.64
  4541.8  264.79  4613.2  257.54  4619.3  254.36  4777.2250.7324  4892.9  251.45
  4924.1254.5132  4933.7254.4255  4971.4  253.91  4977.7  247.99  4982.8  253.83
    4997  245.11  4999.8  244.61    5003  245.11  5012.3  245.17  5042.9  254.78
  5330.2  250.94  5728.1  266.29  6020.1  281.65  6120.8  283.77  6264.7  280.78
#Mann= 6 ,-1 , 0
    4233     .05       0  4777.2     .12       0  4924.1     .16       0
  4933.7     .12       0    4997     .07       0    5003     .12       0
Bank Sta=4982.8,5042.9
XS Rating Curve= 0 ,0
Exp/Cntr=0.3,0.1

Type RM Length L Ch R = 1 ,41496   ,556,556,556
BEGIN DESCRIPTION:
TOWN CREEK 56.0
END DESCRIPTION:
XS GIS Cut Line= 3
      3726399.57     10619010.17      3726749.61     10619210.19
      3727449.63      10619560.2
#Sta/Elev= 30
  4598.1  305.29    4602305.3076  4643.5  302.72  4665.1  299.48  4701.8  292.08
  4708.3  289.34  4729.9  286.66  4736.4  283.83  4751.5  281.76  4788.9   272.3
  4897.6  253.83  4971.7  253.45  4978.2  246.72  4987.6  244.11    4997  243.96
  4999.8  243.46    5003  243.96  5009.6  246.71  5015.2  244.18    5032  253.07
  5037.6  249.86    5046  252.85  5054.4  253.11  5188.5  250.49  5342.2250.8161
  5519.1248.7425  5551.9  247.82  5613.4  255.38  5730.8     267  5783.9  268.08
#Mann= 6 ,-1 , 0
  4598.1     .05       0    4602     .12       0    4997     .07       0
    5003     .12       0  5342.2     .16       0  5519.1     .12       0
Bank Sta=4971.7,5032
XS Rating Curve= 0 ,0
Exp/Cntr=0.3,0.1

Type RM Length L Ch R = 1 ,40940   ,636,636,636
BEGIN DESCRIPTION:
TOWN CREEK 55.0
END DESCRIPTION:
XS GIS Cut Line= 3
      3726199.58     10619210.18      3726999.61     10619560.19
      3727349.65     10619760.21
#Sta/Elev= 30
  4097.8  295.24  4174.2  282.43  4182.4  277.07  4187.9  279.49  4196.1  273.59
  4217.9  277.99  4250.6  276.52  4409.3  253.63  4454.9252.0907  4645.8 251.757
  4787.4  253.19  4796.4  247.05  4805.4  245.14  4810.8  249.24  4828.8  244.09
  4834.2  252.59  4840.1  248.18  4857.6  247.79  4863.1  253.18  4984.7  251.35
    4997  242.55  4999.8  242.05    5003  242.55  5022.2  244.23  5028.6  251.96
  5059.6  251.81  5086.9  247.65  5118.6  248.47  5307.2  279.16  5374.2  286.04
#Mann= 5 ,-1 , 0
  4097.8     .12       0  4454.9     .16       0  4645.8     .12       0
    4997     .07       0    5003     .12       0
Bank Sta=4984.7,5028.6
XS Rating Curve= 0 ,0
Exp/Cntr=0.3,0.1

Type RM Length L Ch R = 1 ,40304   ,530,530,530
BEGIN DESCRIPTION:
TOWN CREEK 54.0
END DESCRIPTION:
XS GIS Cut Line= 3
      3726399.63     10619960.19      3726799.61     10619910.19
       3727299.6     10620110.19
#Sta/Elev= 30
  4573.2  287.06  4603.4  285.16    4674   275.7    4684  275.46  4694.8273.0157
  4764.7  265.26  4784.8  261.11  4825.1  256.76  4875.5  247.39  4885.6  247.18
  4915.8  250.84  4966.2  251.79    4979  250.05  4985.7  245.72  4991.1  249.49
    4997  242.37  4999.8  241.87    5003  242.37  5008.6  244.47  5015.3  250.99
  5020.7  246.73  5030.1  251.35  5116.3  249.65  5159.4  252.77  5314.2   269.7
  5320.9  272.28  5353.3  277.51  5368.1  278.33  5392.3   283.9  5514.8  298.99
#Mann= 4 ,-1 , 0
  4573.2     .16       0  4694.8     .12       0    4997     .07       0
    5003     .12       0
Bank Sta=4991.1,5015.3
XS Rating Curve= 0 ,0
Exp/Cntr=0.3,0.1

Type RM Length L Ch R = 1 ,39774   ,619,619,619
BEGIN DESCRIPTION:
TOWN CREEK 53.0
END DESCRIPTION:
XS GIS Cut Line= 3
      3726399.62     10620210.19      3726849.61     10620310.19
      3727249.63     10620260.19
#Sta/Elev= 30
  4536.9  286.38  4561.2  285.49  4567.6   282.8  4588.1  279.03  4628.5273.6953
  4696.9  262.66  4813.5  250.39  4864.7  248.06  4895.4  250.48  4973.5  250.69
  4978.7  249.74  4987.6  241.93    4997  240.83  4999.8  240.33    5003  240.83
    5018  240.83  5028.1  243.07  5035.7  250.16  5040.7  245.56  5048.3  244.29
  5058.3  250.46  5068.4  251.43    5149  251.98  5189.3  260.88  5196.9  264.46
  5229.7  269.81    5270  278.93  5277.5  283.33  5310.3  288.13    5401  294.69
#Mann= 4 ,-1 , 0
  4536.9     .16       0  4628.5     .12       0    4997     .07       0
    5003     .12       0
Bank Sta=4973.5,5035.7
XS Rating Curve= 0 ,0
Exp/Cntr=0.3,0.1

Type RM Length L Ch R = 1 ,39155   ,541,541,541
BEGIN DESCRIPTION:
TOWN CREEK 52.0
END DESCRIPTION:
XS GIS Cut Line= 3
      3726299.63     10620310.21      3726699.61     10620810.19
      3727049.61     10621010.19
#Sta/Elev= 30
  4345.9  290.35  4383.3288.4495  4460.3  278.59  4516.4  267.09  4580.4  257.49
  4687.6  248.61  4730.1  246.89  4836.5  248.72  4865.3  250.48  4879.7  249.38
  4964.6  250.86    4979  248.04    4983  242.56    4997  240.42  4999.8  239.92
    5003  240.42  5015.7  240.42  5021.5  245.81  5031.5  249.55  5043.8  250.95
  5058.9  250.33  5065.3251.9827  5161.1  274.63  5170.5  275.48  5182.7  278.93
  5192.8  278.67    5205  283.04  5263.3  290.15  5285.2  290.81  5389.3  296.34
#Mann= 6 ,-1 , 0
  4345.9     .05       0  4383.3     .12       0    4997     .07       0
    5003     .12       0  5065.3     .16       0  5285.2     .05       0
Bank Sta=4964.6,5031.5
XS Rating Curve= 0 ,0
Exp/Cntr=0.3,0.1

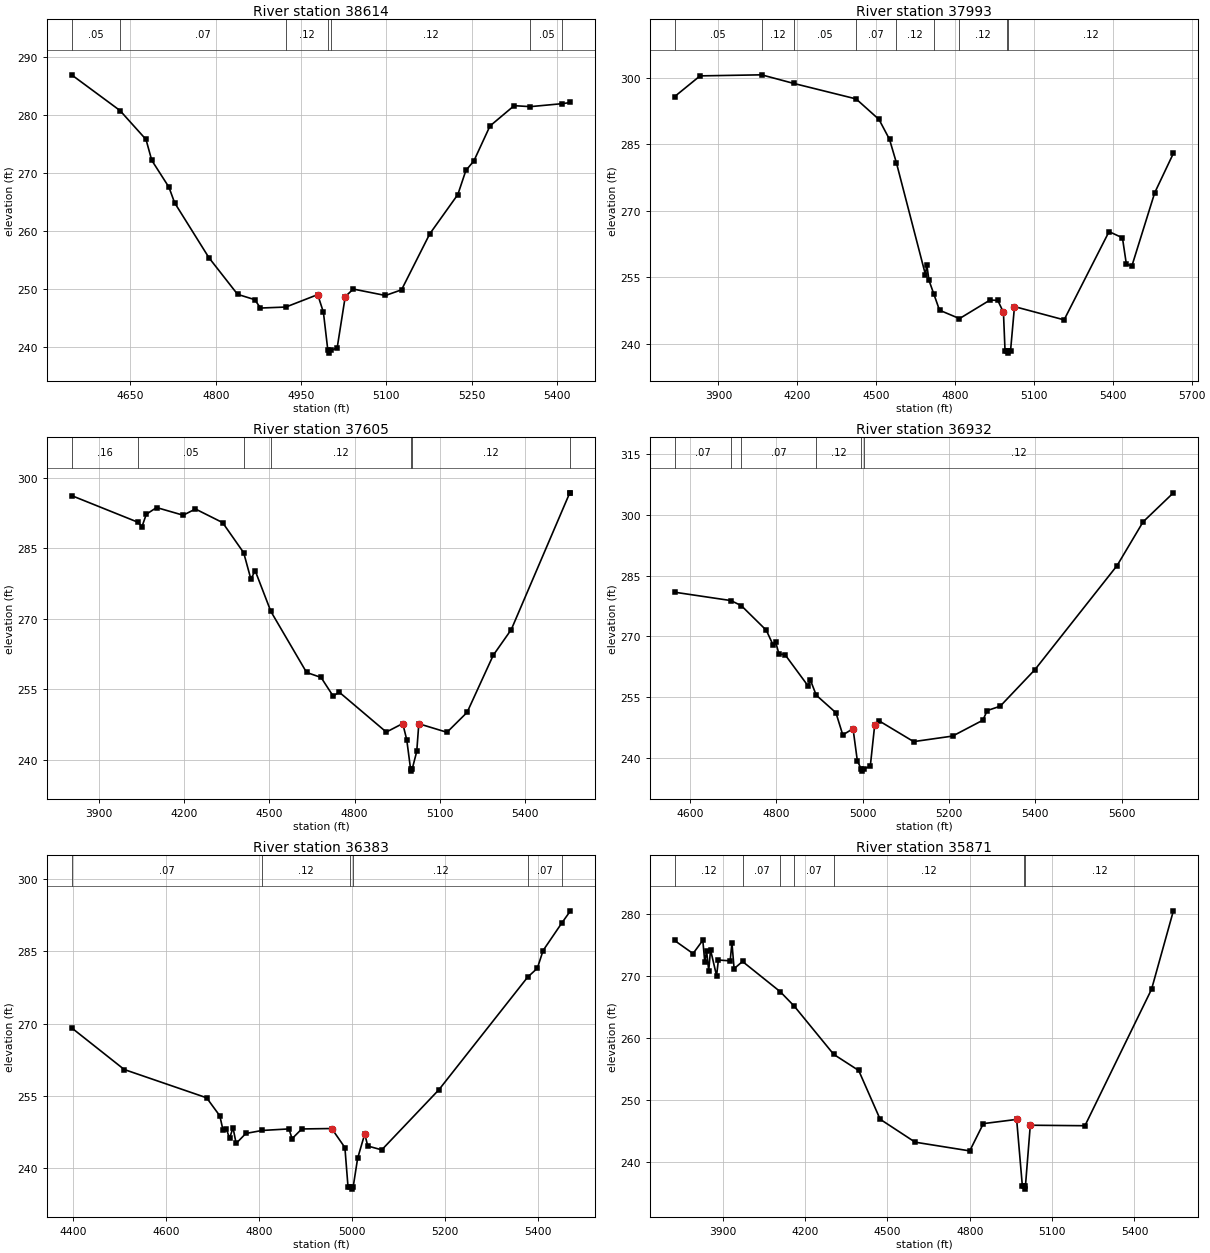
Type RM Length L Ch R = 1 ,38614   ,621,621,621
BEGIN DESCRIPTION:
TOWN CREEK 51.0
END DESCRIPTION:
XS GIS Cut Line= 3
      3726149.61     10620410.17      3726199.61     10620860.19
      3726499.64     10621160.22
#Sta/Elev= 30
  4546.5  286.96  4631.5280.7942  4677.3  275.79  4687.4  272.19  4717.6  267.55
  4727.6  264.85    4788  255.35  4838.3  249.03  4868.5  248.11  4878.6  246.66
  4923.2246.8346  4979.2  248.98  4989.2  245.94    4997  239.37  4999.8  238.87
    5003  239.37  5013.4  239.77  5027.6  248.63  5041.7  249.94  5098.3  248.83
  5126.6  249.81  5176.1  259.46  5225.6  266.28  5239.7  270.43  5253.8  272.09
  5282.1  278.12  5324.6  281.63    5353 281.463  5409.4  281.98  5423.6  282.18
#Mann= 7 ,-1 , 0
  4546.5     .05       0  4631.5     .07       0  4923.2     .12       0
    4997     .07       0    5003     .12       0    5353     .05       0
  5409.4     .12       0
Bank Sta=4979.2,5027.6
XS Rating Curve= 0 ,0
Exp/Cntr=0.3,0.1

Type RM Length L Ch R = 1 ,37993   ,388,388,388
BEGIN DESCRIPTION:
TOWN CREEK 50.0
END DESCRIPTION:
XS GIS Cut Line= 3
      3725576.05     10619783.03      3725622.92     10620944.48
       3726034.4     10621553.88
#Sta/Elev= 30
  3732.8  295.69    3830  300.37    4064 300.608    4186298.6743  4423.5 295.183
  4510.6  290.56  4550.6  286.08  4576.8280.8031  4687.4  255.58  4692.4  257.87
  4700.7  254.34  4718.5251.3651  4740.8  247.61  4816.8 245.714  4933.1   249.9
  4962.4  249.81    4984  247.14  4990.1  238.44    4997  238.44  4999.8  237.94
    5003  238.44  5011.1  238.52    5026  248.42  5214.8  245.43  5385.7   265.3
  5436.7  263.91  5451.6  257.99  5472.6  257.56  5559.5  274.06  5630.5  282.93
#Mann= 9 ,-1 , 0
  3732.8     .05       0    4064     .12       0    4186     .05       0
  4423.5     .07       0  4576.8     .12       0  4718.5     .07       0
  4816.8     .12       0    4997     .07       0    5003     .12       0
Bank Sta=4984,5026
XS Rating Curve= 0 ,0
Exp/Cntr=0.3,0.1

Type RM Length L Ch R = 1 ,37605   ,673,673,673
BEGIN DESCRIPTION:
TOWN CREEK 49.0
END DESCRIPTION:
XS GIS Cut Line= 3
      3724424.97     10620611.12      3725372.92     10621230.94
      3725800.02     10621684.08
#Sta/Elev= 30
  3804.4  296.19  4037.2290.5383  4052.1   289.6  4067.2  292.22  4103.4  293.65
  4196.9  292.02  4240.1  293.34  4335.6  290.45  4409.9284.0368  4435.2  278.42
  4450.3  280.22  4505.5271.5534  4631.2  258.57  4682.1  257.51  4724.7  253.54
  4745.8  254.39  4911.7  245.89  4969.5   247.7  4983.6  244.27    4997  238.08
  4999.8  237.58    5003  238.08  5018.8  241.76  5026.1  247.66  5125.2  245.84
    5196  250.08  5287.9  262.22  5351.4  267.69  5557.3  296.78  5559.7  296.78
#Mann= 7 ,-1 , 0
  3804.4     .16       0  4037.2     .05       0  4409.9     .07       0
  4505.5     .12       0    4997     .07       0    5003     .12       0
  5557.3     .05       0
Bank Sta=4969.5,5026.1
XS Rating Curve= 0 ,0
Exp/Cntr=0.3,0.1

Type RM Length L Ch R = 1 ,36932   ,549,549,549
BEGIN DESCRIPTION:
TOWN CREEK 48.0
END DESCRIPTION:
XS GIS Cut Line= 3
      3724649.59     10621560.18      3724999.61     10621760.19
      3725749.61     10621810.19
#Sta/Elev= 30
  4564.8  280.89  4695.4278.8186  4719.5 277.549  4777.2  271.48    4793  267.83
  4798.8  268.55  4806.7  265.57  4820.4  265.47  4873.6  257.75  4879.4  259.13
  4892.8255.4245  4938.4  251.07  4954.3  245.58    4978  247.13    4988  239.18
    4997  237.13  4999.8  236.63    5003  237.13    5018  237.88  5028.1  247.96
  5038.1  249.08  5118.3  243.93  5208.5   245.3  5278.6  249.23  5288.6  251.61
  5318.7  252.69  5398.9  261.71  5589.3  287.48  5649.4  298.28  5719.6  305.47
#Mann= 6 ,-1 , 0
  4564.8     .07       0  4695.4     .05       0  4719.5     .07       0
  4892.8     .12       0    4997     .07       0    5003     .12       0
Bank Sta=4978,5028.1
XS Rating Curve= 0 ,0
Exp/Cntr=0.3,0.1

Type RM Length L Ch R = 1 ,36383   ,512,512,512
BEGIN DESCRIPTION:
TOWN CREEK 47.0
END DESCRIPTION:
XS GIS Cut Line= 3
      3724699.63     10621810.21      3725099.61     10622260.19
      3725499.57     10622510.17
#Sta/Elev= 30
  4396.9  269.12  4510.2  260.47  4687.5   254.6  4715.9  250.85  4722.6  247.96
  4730.1  248.13  4736.8  246.17  4744.3  248.39    4751  245.12  4771.9   247.2
  4806.8247.8162  4864.7  248.14  4871.4  246.11  4892.3  248.13  4956.7  248.22
  4985.1  244.27  4991.8  236.14    4997  236.14  4999.8  235.64    5003  236.14
  5012.5  242.03  5027.8  247.09  5034.3  244.59  5064.4  243.79  5187.6  256.29
  5378.4279.6391  5399.3  281.49  5411.7  285.17  5452.5290.9575  5470.6  293.41
#Mann= 6 ,-1 , 0
  4396.9     .07       0  4806.8     .12       0    4997     .07       0
    5003     .12       0  5378.4     .07       0  5452.5     .05       0
Bank Sta=4956.7,5027.8
XS Rating Curve= 0 ,0
Exp/Cntr=0.3,0.1

Type RM Length L Ch R = 1 ,35871   ,655,655,655
BEGIN DESCRIPTION:
Mapping XS 52503482
END DESCRIPTION:
XS GIS Cut Line= 3
      3723820.87     10621673.67      3724716.67     10622428.86
      3725221.89     10622829.91
#Sta/Elev= 30
  3725.1  275.77  3792.5  273.65  3828.1   275.8  3835.3  272.26  3841.9  274.08
  3849.6  270.87  3856.2  274.26  3878.2  270.06  3884.8  272.61  3927.7  272.47
  3934.2  275.39    3942  271.21  3972.7272.3692  4109.8267.4965  4161.3265.1403
  4304.8257.3528  4395.8  254.75  4473.8  246.87  4601.3  243.16  4800.2  241.75
  4849.7  246.16    4971  246.84  4991.8  236.07    4997  236.07  4999.8  235.57
    5003  236.07  5020.7   245.9  5219.7  245.82  5462.3  267.88  5541.8  280.56
#Mann= 7 ,-1 , 0
  3725.1     .12       0  3972.7     .07       0  4109.8     .05       0
  4161.3     .07       0  4304.8     .12       0    4997     .07       0
    5003     .12       0
Bank Sta=4971,5020.7
XS Rating Curve= 0 ,0
Exp/Cntr=0.3,0.1

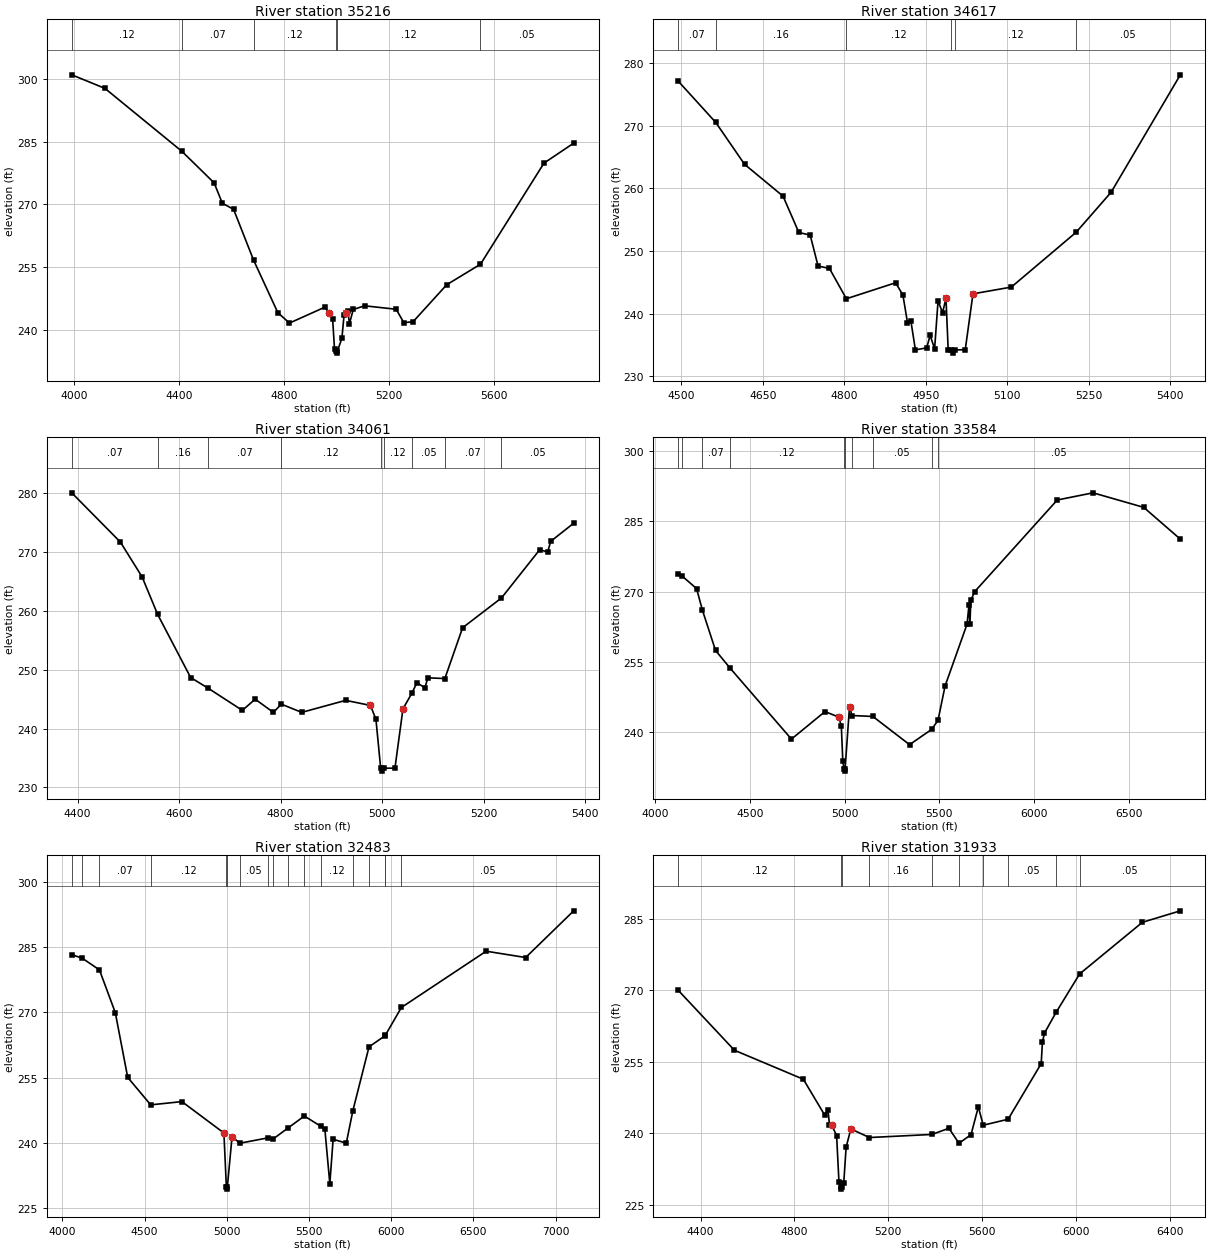
Type RM Length L Ch R = 1 ,35216   ,599,599,599
BEGIN DESCRIPTION:
Mapping XS ad016f22
END DESCRIPTION:
XS GIS Cut Line= 3
      3723512.65     10622052.99      3724283.48     10622506.12
      3724912.51     10623306.71
#Sta/Elev= 30
  3990.8  300.94  4117.1  297.71  4410.7282.6603  4533.1  275.15  4564.4   270.3
  4607.4  268.82  4683.4256.7135  4776.1  244.14  4820.3  241.68  4955.8  245.49
  4970.2  244.16  4984.7  242.68  4991.9  235.37    4997     235  4999.8   234.5
    5003     235    5020  238.06  5028.1  243.49  5034.4  244.17  5042.5  244.49
  5048.9  241.57  5063.3  244.92  5106.3   245.8  5226.9  244.97  5255.8  241.78
  5291.1  241.99  5419.4  250.83    5548255.7255  5789.9  279.86  5903.1  284.63
#Mann= 6 ,-1 , 0
  3990.8     .12       0  4410.7     .07       0  4683.4     .12       0
    4997     .07       0    5003     .12       0    5548     .05       0
Bank Sta=4970.2,5034.4
XS Rating Curve= 0 ,0
Exp/Cntr=0.3,0.1

Type RM Length L Ch R = 1 ,34617   ,556,556,556
BEGIN DESCRIPTION:
TOWN CREEK 44.0
END DESCRIPTION:
XS GIS Cut Line= 3
      3723899.65     10622710.22      3724299.61     10623010.19
       3724599.6     10623310.18
#Sta/Elev= 30
  4494.5  277.09  4563.4270.5164  4616.3  263.84  4687.2  258.75  4716.3  252.95
  4737.2  252.53  4751.7  247.59  4772.6  247.21  4803.8242.3633  4894.5  244.92
    4908  242.93  4916.3  238.56  4922.6  238.81  4930.9   234.2  4951.7  234.52
    4958  236.52  4966.3  234.38  4972.6  242.03  4980.9  240.14  4987.2  242.42
  4991.3  234.18    4997  234.18  4999.8  233.68    5003  234.18  5022.7  234.23
  5036.9  243.15  5107.6  244.23    5227 252.992  5291.4  259.39  5418.7  278.13
#Mann= 6 ,-1 , 0
  4494.5     .07       0  4563.4     .16       0  4803.8     .12       0
    4997     .07       0    5003     .12       0    5227     .05       0
Bank Sta=4987.2,5036.9
XS Rating Curve= 0 ,0
Exp/Cntr=0.3,0.1

Type RM Length L Ch R = 1 ,34061   ,477,477,477
BEGIN DESCRIPTION:
TOWN CREEK 43.0
END DESCRIPTION:
XS GIS Cut Line= 3
      3723699.59     10622760.15      3723899.61     10623310.19
      3724249.62     10623510.19
#Sta/Elev= 30
  4388.7  280.05  4484.5  271.68  4527.1  265.79  4557.8259.3976  4622.8  248.68
  4657.1246.8741  4724.6   243.1  4749.9     245  4785.8  242.75  4801.3244.1543
  4841.6  242.76  4928.1   244.8  4976.9  243.94  4987.7  241.57    4997  233.28
  4999.8  232.78    5003  233.28  5025.1  233.28  5040.9  243.36  5058.9246.0886
  5068.3  247.79  5084.1  246.94  5089.9  248.63  5123.4248.5043  5158.3  257.13
  5234.9262.1947  5310.1  270.38    5326  270.01  5331.7   271.8  5377.1  274.89
#Mann= 9 ,-1 , 0
  4388.7     .07       0  4557.8     .16       0  4657.1     .07       0
  4801.3     .12       0    4997     .07       0    5003     .12       0
  5058.9     .05       0  5123.4     .07       0  5234.9     .05       0
Bank Sta=4976.9,5040.9
XS Rating Curve= 0 ,0
Exp/Cntr=0.3,0.1

Type RM Length L Ch R = 1 ,33584   ,1101,1101,1101
BEGIN DESCRIPTION:
TOWN CREEK 42.0
END DESCRIPTION:
XS GIS Cut Line= 3
       3722986.6     10622709.24       3723674.1     10623636.32
      3725152.28     10623865.34
#Sta/Elev= 30
  4122.8  273.65  4144.1273.2544  4218.8  270.64  4249.7266.0183  4318.9  257.43
  4395.5  253.66  4719.6  238.49  4896.9  244.37    4970  243.18    4983  241.28
  4990.8  233.87    4997  232.15  4999.8  231.65    5003  232.15  5026.3  245.44
  5039.1243.5255  5149.6243.3273  5343.3   237.3  5459.9240.5607  5493.6242.5023
  5530.7  249.83  5646.9  263.05  5656.7  267.04  5661.8  263.05  5667.1  268.17
  5687.3  269.99  6123.1  289.56  6312.1  291.09  6579.4  287.99  6772.8   281.2
#Mann= 10 ,-1 , 0
  4122.8     .16       0  4144.1     .05       0  4249.7     .07       0
  4395.5     .12       0    4997     .07       0    5003     .12       0
  5039.1     .07       0  5149.6     .05       0  5459.9     .16       0
  5493.6     .05       0
Bank Sta=4970,5026.3
XS Rating Curve= 0 ,0
Exp/Cntr=0.3,0.1

Type RM Length L Ch R = 1 ,32483   ,550,550,550
BEGIN DESCRIPTION:
TOWN CREEK 41.0
END DESCRIPTION:
XS GIS Cut Line= 4
      3722804.31     10622756.12      3723043.89     10623521.74
       3723361.6     10623886.32      3723450.14     10625651.98
#Sta/Elev= 30
  4056.4  283.27  4120.8282.4431  4224.9 279.761  4321.3  269.95  4396.7   255.1
  4536.6248.7866  4726.6  249.53    4982  242.33    4997  229.94  4999.8  229.44
    5003  229.94  5031.4  241.44  5080.4239.9875  5249.9241.2066    5278240.8514
  5373.1 243.505  5471.5246.2163  5569.9 243.909  5596.4  243.15  5626.4  230.69
  5646.5  240.88  5726.6     240  5766.7247.4663    5865262.1146  5961.2264.6149
  5963.4264.7095  6061.8271.1412  6577.6  284.06  6817.9  282.61  7110.1  293.33
#Mann= 17 ,-1 , 0
  4056.4     .12       0  4120.8     .16       0  4224.9     .07       0
  4536.6     .12       0    4997     .07       0    5003     .12       0
  5080.4     .05       0  5249.9     .16       0    5278     .07       0
  5373.1     .05       0  5471.5     .07       0  5569.9     .12       0
  5766.7     .05       0    5865     .08       0  5961.2     .07       0
  5963.4     .08       0  6061.8     .05       0
Bank Sta=4982,5031.4
XS Rating Curve= 0 ,0
Exp/Cntr=0.3,0.1

Type RM Length L Ch R = 1 ,31933   ,983,983,983
BEGIN DESCRIPTION:
TOWN CREEK 40.0
END DESCRIPTION:
XS GIS Cut Line= 3
      3722720.98     10623214.47      3722892.85     10624256.12
      3723204.59     10625295.23
#Sta/Elev= 30
  4305.2  269.92  4544.1  257.39    4838  251.31  4929.2  243.79  4943.1  244.95
  4949.5  241.76  4959.7  241.63  4979.9  239.51  4990.1  229.68    4997  228.77
  4999.8  228.27    5003  228.77  5010.3  229.46  5020.5  237.06  5040.7  240.89
  5119.9239.0863  5386.3 239.735  5459.1  241.03  5501.7237.8887  5553.1  239.68
  5584.4  245.51  5605.3  241.67  5711.4242.9232  5852.5  254.59  5857.7  259.11
  5866.3  260.97    5916265.3357  6016.4273.3887  6283.9  284.21  6445.8  286.62
#Mann= 10 ,-1 , 0
  4305.2     .12       0    4997     .07       0    5003     .12       0
  5119.9     .16       0  5386.3     .12       0  5501.7     .05       0
  5605.3     .12       0  5711.4     .05       0    5916     .08       0
  6016.4     .05       0
Bank Sta=4959.7,5040.7
XS Rating Curve= 0 ,0
Exp/Cntr=0.3,0.1