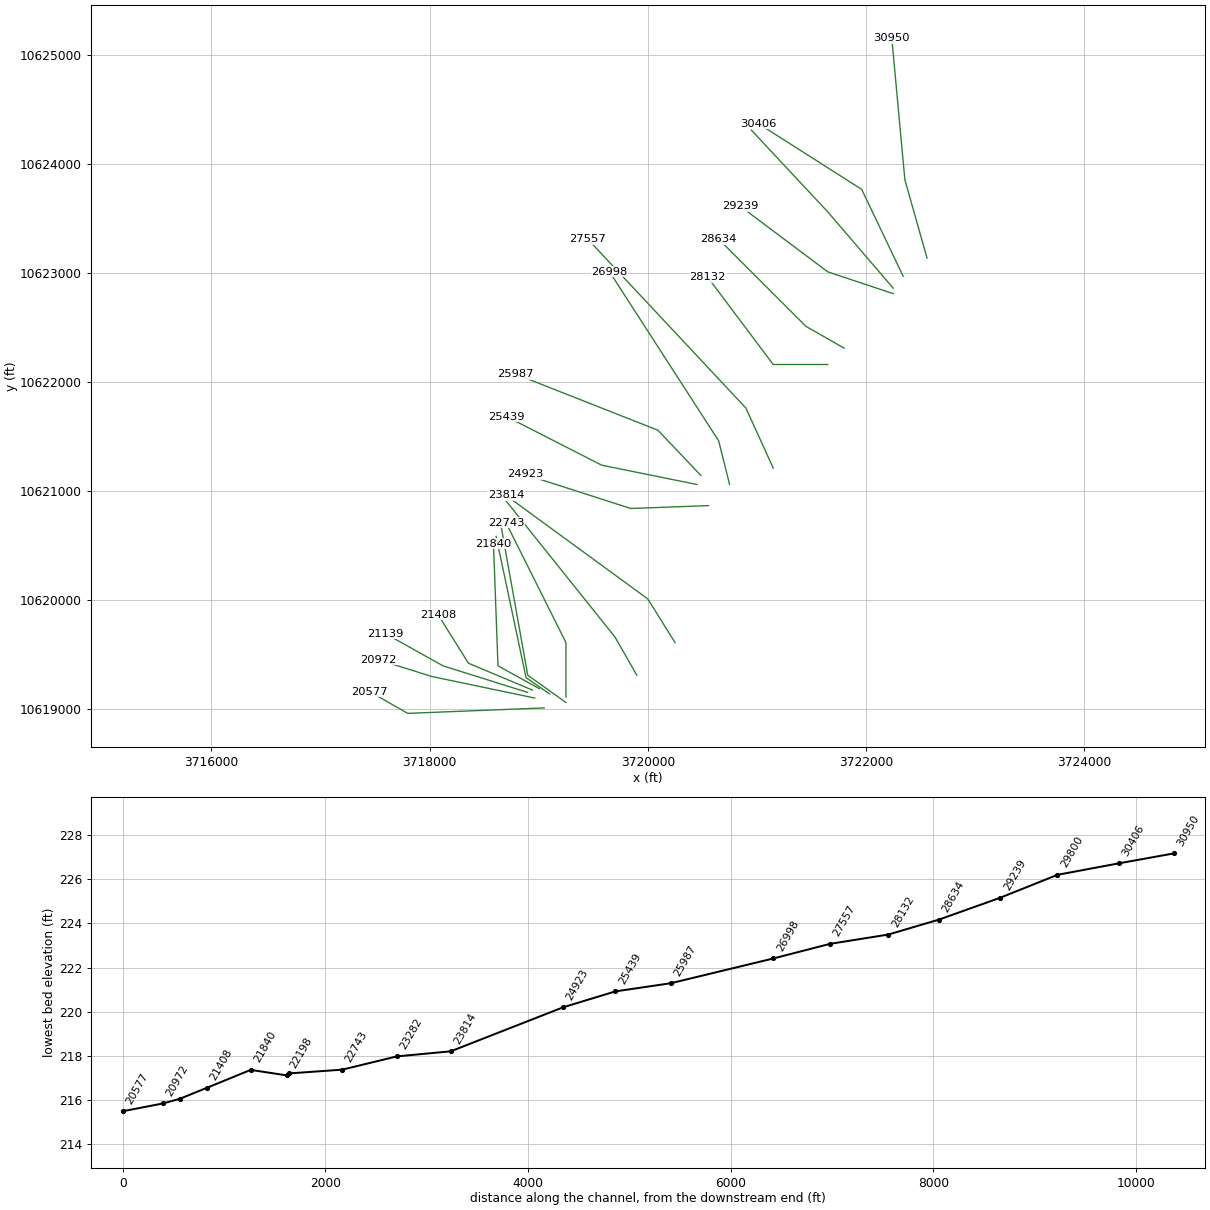
HEC-RAS study TOWN CREEK.prj: TOWN CREEK Base Level Engineering

--- TOWN CREEK.g01 (geometry) --- (continued)

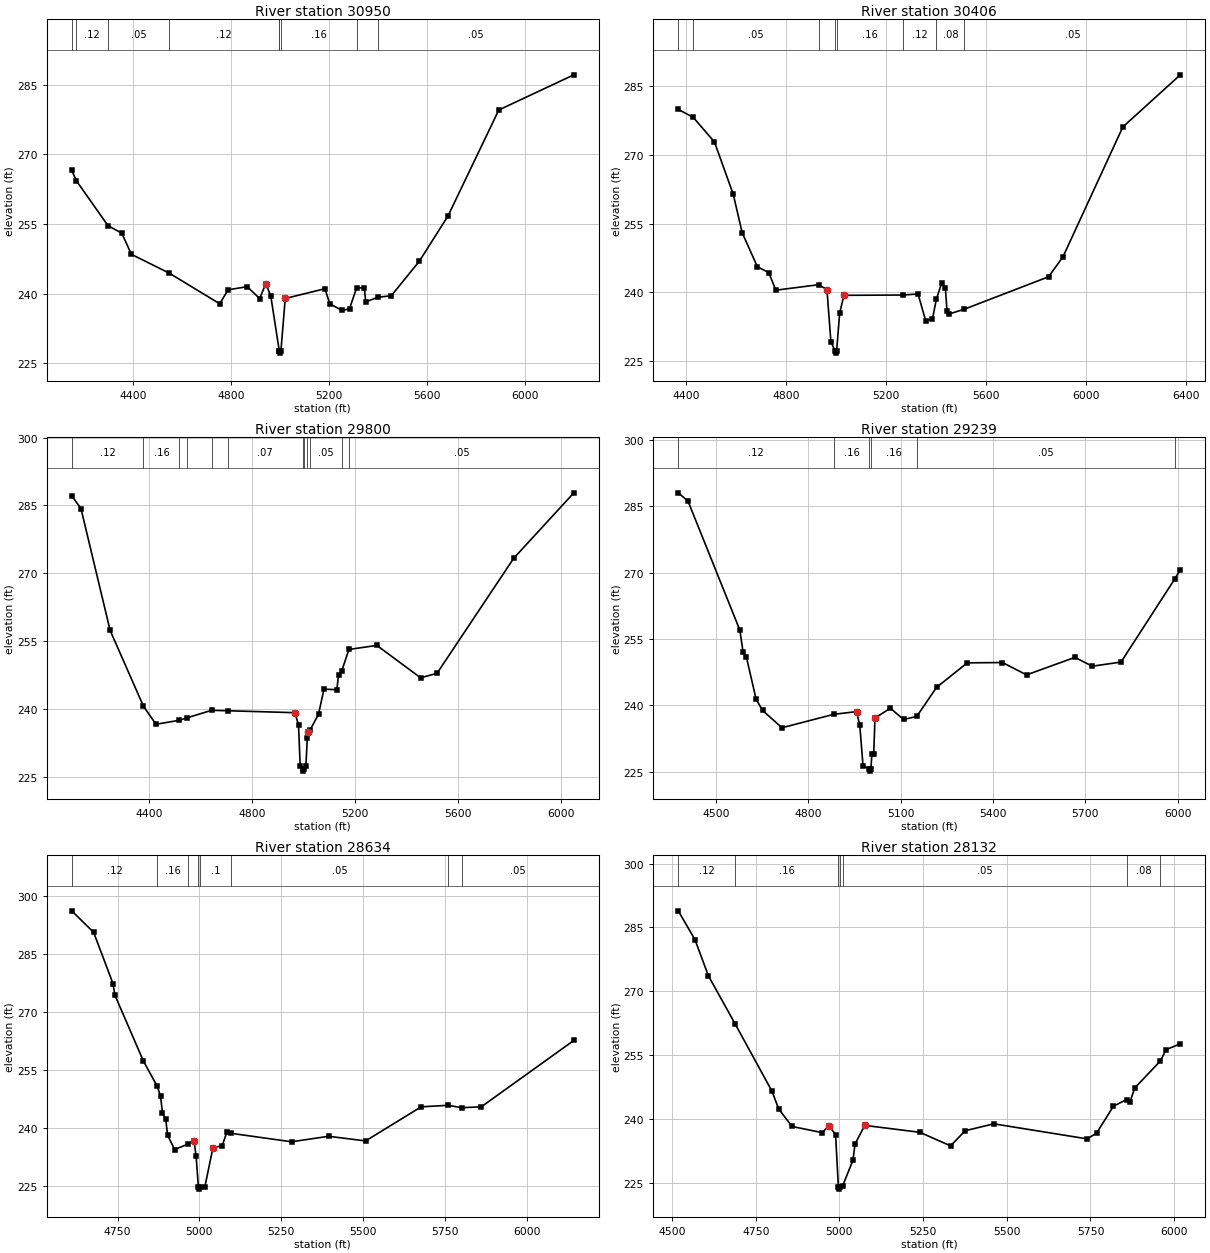
Type RM Length L Ch R = 1 ,30950   ,544,544,544
BEGIN DESCRIPTION:
TOWN CREEK 39.0
END DESCRIPTION:
XS GIS Cut Line= 3
      3722559.51     10623136.34      3722356.39     10623855.07
       3722236.6     10625151.97
#Sta/Elev= 30
  4149.3  266.52  4168.3264.2714    4297 254.621  4353.6  252.98  4392.7  248.44
  4547.5244.3802  4753.2  237.79  4787.2   240.8  4865.5  241.47    4916  238.92
  4941.5  242.14  4961.6  239.45  4996.2227.6841    4997  227.66  4999.8  227.16
    5003  227.66  5020.6  238.93  5182.5  241.03  5202.6  237.76  5252.8  236.35
  5282.9  236.71    5312241.2193  5343.2  241.23  5349.3   238.2  5398.3239.1838
  5453.7  239.53  5568.5     247  5684.6  256.67  5892.3  279.53  6198.6   287.1
#Mann= 9 ,-1 , 0
  4149.3     .07       0  4168.3     .12       0    4297     .05       0
  4547.5     .12       0  4996.2     .16       0    4997     .07       0
    5003     .16       0    5312     .08       0  5398.3     .05       0
Bank Sta=4941.5,5020.6
XS Rating Curve= 0 ,0
Exp/Cntr=0.3,0.1

Type RM Length L Ch R = 1 ,30406   ,606,606,606
BEGIN DESCRIPTION:
TOWN CREEK 38.0
END DESCRIPTION:
XS GIS Cut Line= 3
      3722340.77     10622969.65      3721960.56     10623766.53
      3721013.59      10624370.1
#Sta/Elev= 30
  4370.2  279.99  4429.9278.2689  4514.8  272.88  4590.2  261.39  4625.6  253.03
  4686.5  245.59  4731.9  244.31  4760.1  240.47  4931.4241.6668  4964.3   240.6
  4980.2  229.17    4997  227.21  4999.8  226.71    5003  227.21  5015.2   235.5
  5032.4  239.35  5267.9239.4141  5328.2  239.64  5358.7  233.83  5385.8  234.19
  5401.8 238.551  5422.2  241.97  5437.4  240.99    5444  235.98  5452.6  235.27
  5513.6236.3205  5849.6   243.4  5907.1  247.74  6146.6  276.16  6376.1  287.55
#Mann= 8 ,-1 , 0
  4370.2     .12       0  4429.9     .05       0  4931.4     .16       0
    4997     .07       0    5003     .16       0  5267.9     .12       0
  5401.8     .08       0  5513.6     .05       0
Bank Sta=4964.3,5032.4
XS Rating Curve= 0 ,0
Exp/Cntr=0.3,0.1

Type RM Length L Ch R = 1 ,29800   ,561,561,561
BEGIN DESCRIPTION:
TOWN CREEK 37.0
END DESCRIPTION:
XS GIS Cut Line= 3
      3722249.64     10622860.15      3721649.61     10623560.19
      3720949.62     10624310.18
#Sta/Elev= 30
  4101.1  287.13  4136.8  284.32  4249.9  257.34  4378.9240.5917  4427.7  236.56
  4518.7 237.449  4547.6237.9795  4643.8239.6527  4706.7239.5566  4966.6  239.13
  4980.8  236.42  4987.4  227.23    4997  226.69  4999.8  226.19    5003  226.69
  5009.4  227.22  5014.8233.4789    5016  234.87    5025  235.22  5058.5  238.78
  5079.5  244.35  5129.4  244.21  5136.2  247.57  5148.2248.3206  5176.2253.1244
  5284.7  254.02  5454.7  246.85  5518.2  247.84  5815.7  273.31    6049   287.8
#Mann= 12 ,-1 , 0
  4101.1     .12       0  4378.9     .16       0  4518.7     .05       0
  4547.6     .16       0  4643.8      .1       0  4706.7     .07       0
    4997     .07       0    5003     .07       0  5014.8     .12       0
    5025     .05       0  5148.2     .08       0  5176.2     .05       0
Bank Sta=4966.6,5016
XS Rating Curve= 0 ,0
Exp/Cntr=0.3,0.1

Type RM Length L Ch R = 1 ,29239   ,605,605,605
BEGIN DESCRIPTION:
TOWN CREEK 36.0
END DESCRIPTION:
XS GIS Cut Line= 3
      3722249.62     10622810.18      3721649.61     10623010.19
      3720849.58     10623610.21
#Sta/Elev= 30
  4376.6  288.03  4408.2  286.18  4576.9  257.02  4587.4  252.08    4598  250.98
  4629.6  241.47  4650.7  238.87  4713.9  234.96  4882.5237.9984  4956.4   238.6
  4966.9   235.5  4977.4  226.41    4997  225.66  4999.8  225.16    5003  225.66
  5006.4  229.12  5012.2  229.12  5016.4  237.16  5066.4  239.38  5109.1  236.83
  5152.1 237.513  5216.4  244.07  5316.4  249.62  5430.9  249.69  5509.1   246.9
  5666.4  250.86  5722.6  248.86  5816.4   249.8  5990.4268.5083  6009.1  270.65
#Mann= 6 ,-1 , 0
  4376.6     .12       0  4882.5     .16       0    4997     .07       0
    5003     .16       0  5152.1     .05       0  5990.4     .16       0
Bank Sta=4956.4,5016.4
XS Rating Curve= 0 ,0
Exp/Cntr=0.3,0.1

Type RM Length L Ch R = 1 ,28634   ,502,502,502
BEGIN DESCRIPTION:
TOWN CREEK 35.0
END DESCRIPTION:
XS GIS Cut Line= 3
      3721799.57     10622310.21      3721449.61     10622510.19
      3720649.64     10623310.16
#Sta/Elev= 30
    4610  296.11  4676.9  290.53  4735.9  277.32  4741.7  274.34  4828.8   257.3
    4871250.7801  4881.3  248.22  4887.1  243.93  4897.2  242.21  4902.9  238.09
  4924.5  234.41  4964.3 235.784  4983.6  236.73    4990  232.67    4997  224.67
  4999.8  224.17    5003  224.67  5016.6   224.7  5041.4  234.87  5069.6  235.39
  5083.8  238.84  5097.6238.5855  5281.8  236.41  5394.9  237.83    5508  236.63
  5677.7  245.44    5760245.8412    5802245.2162  5861.6  245.45  6144.4  262.61
#Mann= 8 ,-1 , 0
    4610     .12       0    4871     .16       0  4964.3      .1       0
    4997     .07       0    5003      .1       0  5097.6     .05       0
    5760     .08       0    5802     .05       0
Bank Sta=4983.6,5041.4
XS Rating Curve= 0 ,0
Exp/Cntr=0.3,0.1

Type RM Length L Ch R = 1 ,28132   ,575,575,575
BEGIN DESCRIPTION:
TOWN CREEK 34.0
END DESCRIPTION:
XS GIS Cut Line= 3
      3721649.65     10622160.19      3721149.61     10622160.19
      3720549.63     10622960.16
#Sta/Elev= 30
  4518.5  288.91  4568.5  282.14  4608.5  273.65  4688.6262.3151  4798.5  246.52
  4818.5  242.34  4858.5  238.22  4948.5  236.77  4968.5  238.38  4988.5  236.32
    4997  223.99  4999.8  223.49    5003  223.99  5010.1 224.342  5040.4  230.27
  5046.7  234.09  5075.8  238.47  5240.4  236.85  5332.1  233.66  5375.8  237.22
  5461.2  238.84  5740.4   235.3  5768.5  236.67  5818.5  242.96  5857.8244.5497
  5868.5  244.05  5882.1  247.26  5959.2 253.629  5975.8  256.27  6018.5  257.65
#Mann= 7 ,-1 , 0
  4518.5     .12       0  4688.6     .16       0    4997     .07       0
    5003     .16       0  5010.1     .05       0  5857.8     .08       0
  5959.2     .05       0
Bank Sta=4968.5,5075.8
XS Rating Curve= 0 ,0
Exp/Cntr=0.3,0.1

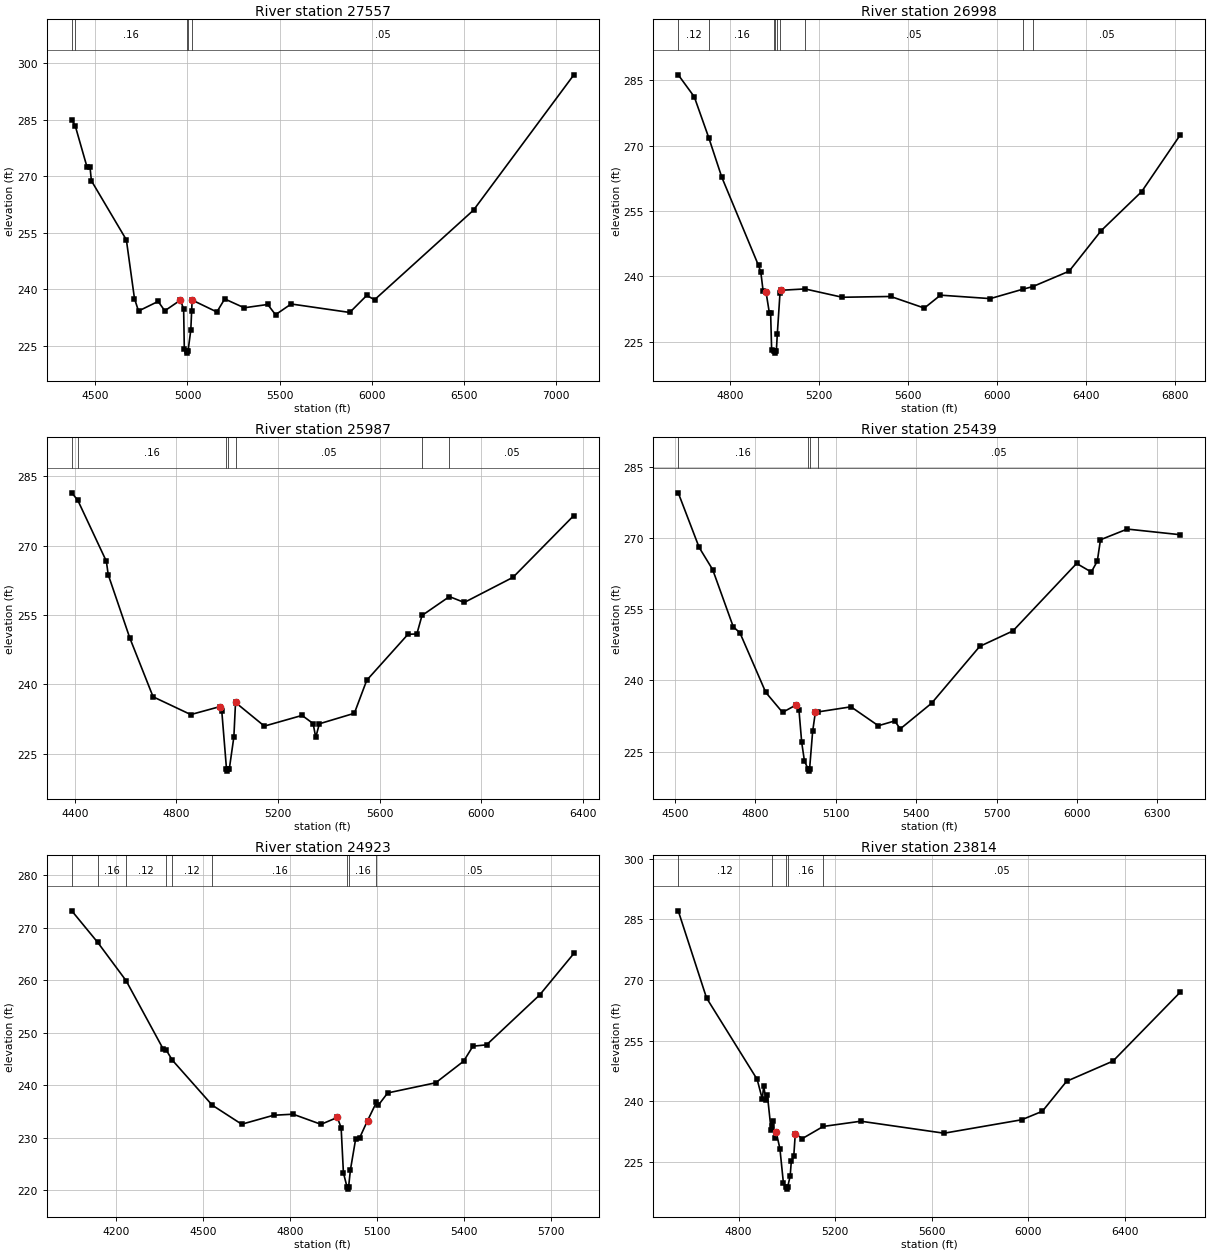
Type RM Length L Ch R = 1 ,27557   ,559,559,559
BEGIN DESCRIPTION:
TOWN CREEK 33.0
END DESCRIPTION:
XS GIS Cut Line= 3
      3721149.59     10621210.23      3720899.61     10621760.19
      3719449.61     10623310.18
#Sta/Elev= 30
  4371.8  285.07    4391283.3652  4455.2  272.38  4470.6  272.62  4478.3  268.85
  4668.3  253.15  4712.3  237.57  4734.2  234.25  4840.8   236.8    4877  234.31
  4961.6  237.14  4979.3  234.79    4983  224.14    4997  223.57  4999.8  223.07
    5003  223.57  5018.2  229.18  5022.9234.3176  5025.5  237.16  5159.8     234
  5202.3  237.46  5308.3  235.11  5435.8  235.99  5478.3  233.27  5563.3  236.12
  5881.3  233.87  5973.6  238.39  6016.1  237.24  6553.5  261.04  7098.4  296.97
#Mann= 5 ,-1 , 0
  4371.8     .12       0    4391     .16       0    4997     .07       0
    5003     .16       0  5022.9     .05       0
Bank Sta=4961.6,5025.5
XS Rating Curve= 0 ,0
Exp/Cntr=0.3,0.1

Type RM Length L Ch R = 1 ,26998   ,1011,1011,1011
BEGIN DESCRIPTION:
TOWN CREEK 32.0
END DESCRIPTION:
XS GIS Cut Line= 3
      3720749.61      10621060.2      3720649.61     10621460.19
       3719649.6      10623010.2
#Sta/Elev= 30
    4567  286.22  4639.1  281.18  4705.1271.6683  4762.8  262.74  4927.8  242.51
  4938.1  241.02  4948.4  236.72  4961.3  236.51  4976.7  231.61  4982.3  231.61
  4986.9  223.03    4997  222.91  4999.8  222.41    5003  222.91    5008  222.91
  5012.4226.8511  5024.6236.3014  5029.1  236.82  5136.7 237.131  5304.3  235.22
  5522.1   235.4  5673.3  232.74  5745.8   235.7  5969.6  234.91  6116.4237.0689
  6160.2237.6524  6324.1   241.2  6468.5  250.51    6650  259.43  6823.9  272.46
#Mann= 9 ,-1 , 0
    4567     .12       0  4705.1     .16       0    4997     .07       0
    5003     .16       0  5012.4     .12       0  5024.6     .16       0
  5136.7     .05       0  6116.4     .08       0  6160.2     .05       0
Bank Sta=4961.3,5029.1
XS Rating Curve= 0 ,0
Exp/Cntr=0.3,0.1

Type RM Length L Ch R = 1 ,25987   ,548,548,548
BEGIN DESCRIPTION:
TOWN CREEK 31.0
END DESCRIPTION:
XS GIS Cut Line= 3
      3720485.72     10621143.42      3720092.48      10621557.6
       3718783.5     10622073.75
#Sta/Elev= 30
  4387.4  281.38  4411.1279.7725  4523.7   266.6    4531  263.71  4615.9  250.06
  4707.8  237.34  4856.2   233.5  4972.4  235.24  4978.5  234.23    4997  221.79
  4999.8  221.29    5003  221.79  5008.2  221.79  5026.1  228.69  5032.6  236.12
  5034.2 236.037  5146.3  231.01  5294.8  233.32  5338.4  231.56  5348.6  228.56
  5362.8  231.51  5500.8  233.78  5549.6  240.91    5712  250.83  5747.1  250.91
  5767.3254.8966  5875.3 258.975  5933.9  257.71    6126  263.14  6365.6  276.48
#Mann= 7 ,-1 , 0
  4387.4     .12       0  4411.1     .16       0    4997     .07       0
    5003     .16       0  5034.2     .05       0  5767.3     .08       0
  5875.3     .05       0
Bank Sta=4972.4,5032.6
XS Rating Curve= 0 ,0
Exp/Cntr=0.3,0.1

Type RM Length L Ch R = 1 ,25439   ,516,516,516
BEGIN DESCRIPTION:
TOWN CREEK 30.0
END DESCRIPTION:
XS GIS Cut Line= 3
      3720450.77     10621059.67      3719578.25      10621236.5
      3718703.99     10621682.93
#Sta/Elev= 30
  4513.2  279.51  4591.1  268.02  4641.8  263.32  4718.4   251.3  4743.2  250.04
  4839.4  237.51  4902.1  233.29  4953.1  234.87  4963.3  233.79  4973.5  226.99
  4983.7  223.05    4997  221.42  4999.8  220.92    5003  221.42  5014.3  229.29
  5024.5  233.31  5033.3233.3783  5157.2  234.46  5259.2  230.48  5320.4  231.49
  5340.9  229.81  5458.1  235.23  5637.3  247.18  5761.2  250.44  5998.5  264.64
  6053.2  262.84  6075.6  265.12  6087.4  269.63  6187.2  271.88  6385.1  270.69
#Mann= 4 ,-1 , 0
  4513.2     .16       0    4997     .07       0    5003     .16       0
  5033.3     .05       0
Bank Sta=4953.1,5024.5
XS Rating Curve= 0 ,0
Exp/Cntr=0.3,0.1

Type RM Length L Ch R = 1 ,24923   ,1109,1109,1109
BEGIN DESCRIPTION:
TOWN CREEK 29.0
END DESCRIPTION:
XS GIS Cut Line= 3
      3720555.36     10620865.69      3719843.59     10620839.64
      3718872.94     10621151.64
#Sta/Elev= 30
    4048  273.24  4137.5267.2231  4235.4259.9265    4364  246.84  4373.4246.7366
  4394.8244.7868  4532.4236.2052  4634.1  232.57  4744.2  234.28  4811.4  234.48
  4907.7  232.55    4964  233.86  4977.1   231.9    4985  223.31    4997   220.7
  4999.8   220.2    5003   220.7  5009.2  223.89    5027  229.69  5041.3  230.02
  5068.1  233.24  5098.8236.7431  5105.5   236.2  5137.6  238.53  5303.3  240.47
  5399.6  244.58  5431.7  247.44  5478.7   247.7  5661.6  257.19  5779.8  265.11
#Mann= 9 ,-1 , 0
    4048     .12       0  4137.5     .16       0  4235.4     .12       0
  4373.4     .16       0  4394.8     .12       0  4532.4     .16       0
    4997     .07       0    5003     .16       0  5098.8     .05       0
Bank Sta=4964,5068.1
XS Rating Curve= 0 ,0
Exp/Cntr=0.3,0.1

Type RM Length L Ch R = 1 ,23814   ,532,532,532
BEGIN DESCRIPTION:
TOWN CREEK 28.0
END DESCRIPTION:
XS GIS Cut Line= 3
      3720249.62     10619610.16      3719999.61     10620010.19
      3718699.57     10620960.22
#Sta/Elev= 30
  4549.4  287.14  4666.8  265.55  4876.7  245.39  4897.9  240.52  4903.8  243.77
  4913.2  240.31  4919.1   241.5  4934.5  232.81  4937.3233.8768  4940.3  235.02
  4949.8  230.94  4955.7  232.28    4971  228.23  4985.7  219.61    4997  218.71
  4999.8  218.21    5003  218.71  5013.5  221.43  5018.2  225.06  5028.5  226.39
  5034.7  231.92    5064  230.73  5150.5233.7357  5306.5  235.03  5651.7  232.06
  5973.7  235.39  6059.4   237.5  6159.8  244.92  6352.1  249.92  6631.3     267
#Mann= 5 ,-1 , 0
  4549.4     .12       0  4937.3     .16       0    4997     .07       0
    5003     .16       0  5150.5     .05       0
Bank Sta=4955.7,5034.7
XS Rating Curve= 0 ,0
Exp/Cntr=0.3,0.1

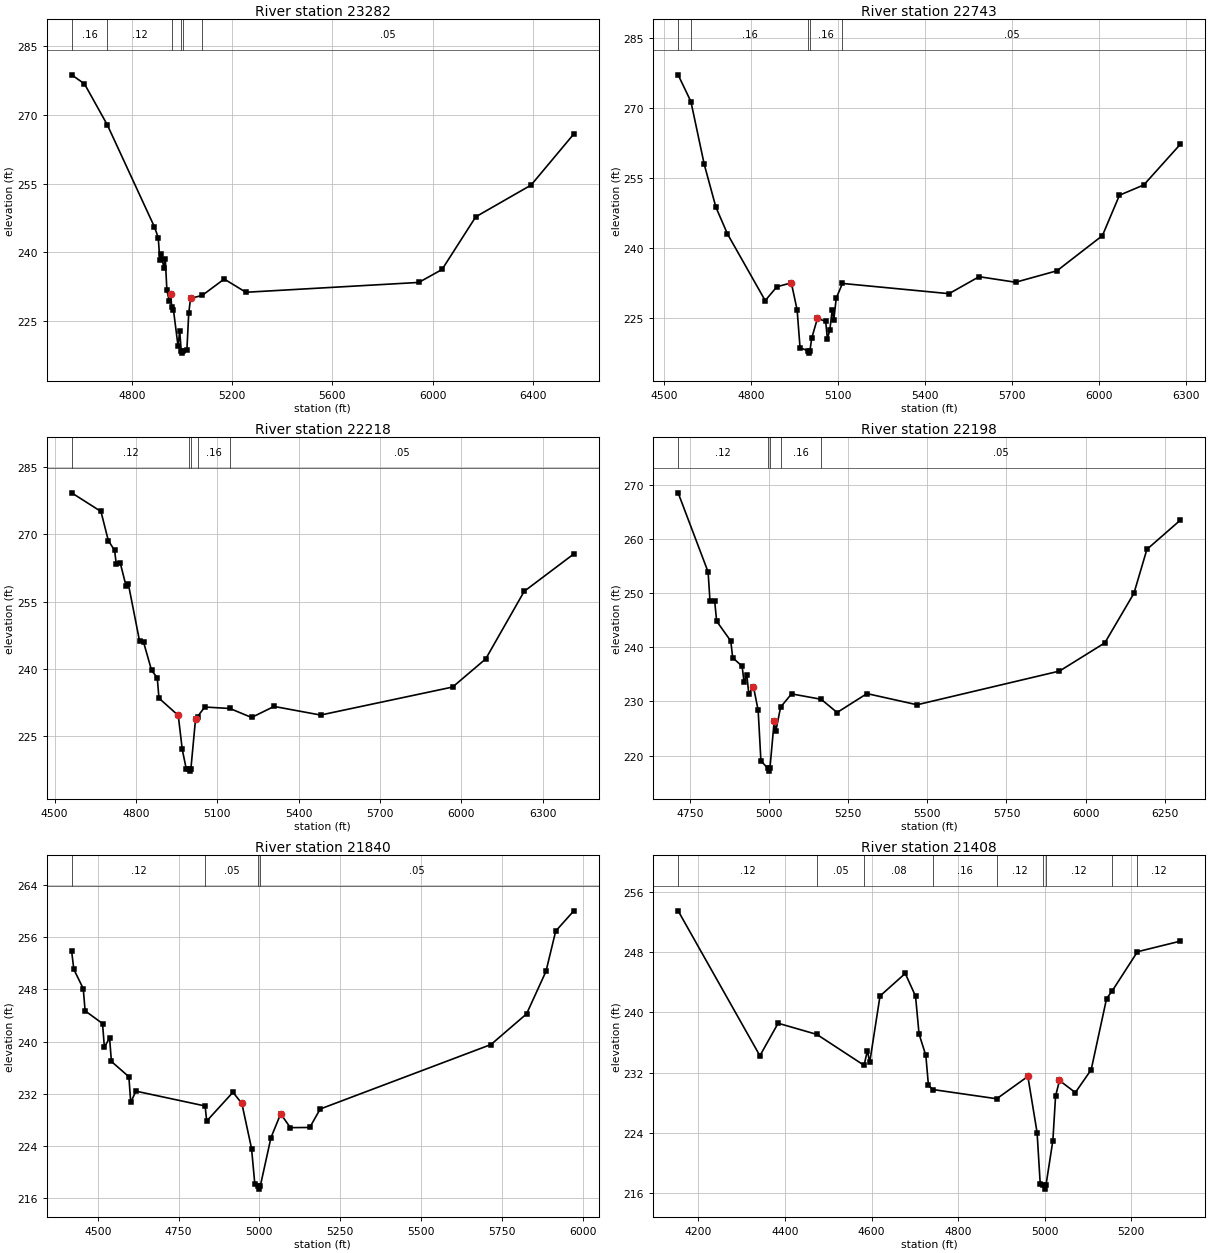
Type RM Length L Ch R = 1 ,23282   ,539,539,539
BEGIN DESCRIPTION:
TOWN CREEK 27.0
END DESCRIPTION:
XS GIS Cut Line= 3
      3719899.61     10619310.18      3719699.61     10619660.19
      3718699.61     10620910.19
#Sta/Elev= 30
  4559.8   278.8  4610.9  276.83  4702.3267.8429  4890.2  245.56  4905.3  243.23
  4911.8  238.28  4917.6  239.71  4927.6  236.53  4933.4  238.61  4939.9  231.68
  4949.2  229.41    4955  230.89  4959.2227.9583  4966.1   227.4  4984.5  219.45
  4990.9  222.88    4997  218.48  4999.8  217.98    5003  218.48  5019.7  218.75
    5027  226.68  5034.2  229.95  5080.6  230.59  5168.6  234.17  5255.1  231.28
    5945  233.43  6037.8  236.26  6172.3  247.77  6393.2  254.71  6563.7  265.88
#Mann= 6 ,-1 , 0
  4559.8     .16       0  4702.3     .12       0  4959.2     .16       0
    4997     .07       0    5003     .16       0  5080.6     .05       0
Bank Sta=4955,5034.2
XS Rating Curve= 0 ,0
Exp/Cntr=0.3,0.1

Type RM Length L Ch R = 1 ,22743   ,525,525,525
BEGIN DESCRIPTION:
TOWN CREEK 26.0
END DESCRIPTION:
XS GIS Cut Line= 3
      3719249.61     10619110.18      3719249.61     10619610.19
      3718699.63     10620710.15
#Sta/Elev= 30
  4548.9  277.06    4593 271.316  4638.9  257.86  4678.9   248.7  4718.9  242.94
  4848.9  228.64  4888.9  231.61  4938.9  232.45  4958.9  226.61  4968.9  218.52
    4997  217.88  4999.8  217.38    5003  217.88  5008.9  220.54  5028.9  224.85
  5057.3  224.17  5062.9  220.48  5071.3  222.27  5079.7  226.63  5085.2  224.58
  5093.6  229.18  5114.9232.3232  5482.1  230.13  5585.6  233.77  5711.3  232.58
  5853.9  235.04  6010.4  242.58  6069.1  251.24    6153  253.45  6278.7  262.16
#Mann= 5 ,-1 , 0
  4548.9     .12       0    4593     .16       0    4997     .07       0
    5003     .16       0  5114.9     .05       0
Bank Sta=4938.9,5028.9
XS Rating Curve= 0 ,0
Exp/Cntr=0.3,0.1

Type RM Length L Ch R = 1 ,22218   ,20,20,20
BEGIN DESCRIPTION:
TOWN CREEK 25.0
END DESCRIPTION:
XS GIS Cut Line= 3
       3719249.6      10619060.2      3718899.61     10619310.19
       3718649.6     10620710.24
#Sta/Elev= 30
  4563.2  279.29  4671.3  275.13  4698.4  268.64  4721.7  266.45  4727.9  263.33
  4742.6  263.61  4763.5  258.59  4772.1  259.03  4813.9  246.15  4828.6  245.94
  4858.1  239.67    4879  238.03  4885.2  233.49  4956.4  229.63  4971.2  222.04
  4985.9  217.71    4997  217.71  4999.8  217.21    5003  217.71  5020.2  228.84
  5027.6229.3849  5054.3  231.51    5147 231.182  5226.9  229.18  5309.7  231.64
  5481.4  229.72  5968.5  235.97  6090.4  242.24  6232.6  257.33  6415.5  265.66
#Mann= 5 ,-1 , 0
  4563.2     .12       0    4997     .07       0    5003     .12       0
  5027.6     .16       0    5147     .05       0
Bank Sta=4956.4,5020.2
XS Rating Curve= 0 ,0
Exp/Cntr=0.3,0.1

Type RM Length L Ch R = 1 ,22198   ,358,358,358
BEGIN DESCRIPTION:
Mapping XS b7b043a8
END DESCRIPTION:
XS GIS Cut Line= 3
      3719099.18     10619139.01      3718883.94      10619288.3
      3718609.64     10620583.42
#Sta/Elev= 30
  4713.1  268.49  4807.8  253.88  4813.8  248.47  4828.7  248.44  4834.8  244.79
  4879.4  241.14  4885.4  238.06  4915.2  236.48  4921.3  233.56    4930  234.89
  4936.1  231.42    4951  232.69  4965.8  228.36  4974.6     219    4997  217.62
  4999.8  217.12    5003  217.62  5016.4  226.31  5021.5  224.51  5036.8228.9415
  5071.2  231.38  5164.8230.3816  5215.2  227.94  5309.4  231.43  5467.6  229.37
  5917.4  235.59  6060.5  240.79  6152.5  249.95  6193.4  258.05  6298.9  263.44
#Mann= 5 ,-1 , 0
  4713.1     .12       0    4997     .07       0    5003     .12       0
  5036.8     .16       0  5164.8     .05       0
Bank Sta=4951,5016.4
XS Rating Curve= 0 ,0
Exp/Cntr=0.3,0.1

Type RM Length L Ch R = 1 ,21840   ,432,432,432
BEGIN DESCRIPTION:
Mapping XS 341f31df
END DESCRIPTION:
XS GIS Cut Line= 3
      3719005.51     10619187.58        3718627.     10619395.93
      3718585.37      10620516.3
#Sta/Elev= 30
  4419.4  253.86  4426.1  251.09  4455.3  248.12    4461  244.72  4514.9  242.77
  4520.6  239.14  4536.7  240.56  4542.4  236.95  4596.4  234.61  4602.1  230.67
  4618.1   232.4  4832.2230.1229  4837.1  227.81  4918.3  232.23  4945.8  230.51
  4975.8   223.6  4985.8  218.21    4997  217.87  4999.8  217.37    5003  217.87
  5035.8  225.26  5065.9  228.92  5095.9   226.8  5155.9  226.83  5188.1  229.66
  5716.3  239.55  5826.4  244.25  5886.4  250.77  5916.5  256.95  5972.6  260.06
#Mann= 4 ,-1 , 0
  4419.4     .12       0  4832.2     .05       0    4997     .03       0
    5003     .05       0
Bank Sta=4945.8,5065.9
XS Rating Curve= 0 ,0
Exp/Cntr=0.3,0.1

Type RM Length L Ch R = 1 ,21408   ,269,269,269
BEGIN DESCRIPTION:
Mapping XS e7455e4a
END DESCRIPTION:
XS GIS Cut Line= 3
      3718942.97     10619173.71      3718356.16     10619420.24
      3718078.39     10619864.68
#Sta/Elev= 30
  4152.9  253.45  4341.9  234.24    4384  238.55  4473.6237.0662  4582.7232.9697
  4590.3  234.93  4595.7  233.36  4619.5  242.16  4677.8  245.15  4701.6  242.14
  4709.7  237.13  4725.4  234.28  4731.4  230.32  4741.8229.7571  4889.2228.5388
  4961.2   231.5  4982.5  224.06  4989.8  217.22    4997  217.06  4999.8  216.56
    5003  217.06    5019     223  5025.2  228.89  5034.3  230.96  5070.9  229.36
  5107.5  232.38  5143.1  241.82  5155.9242.8142  5214.5248.0283  5313.5  249.43
#Mann= 9 ,-1 , 0
  4152.9     .12       0  4473.6     .05       0  4582.7     .08       0
  4741.8     .16       0  4889.2     .12       0    4997     .07       0
    5003     .12       0  5155.9     .16       0  5214.5     .12       0
Bank Sta=4961.2,5034.3
XS Rating Curve= 0 ,0
Exp/Cntr=0.3,0.1

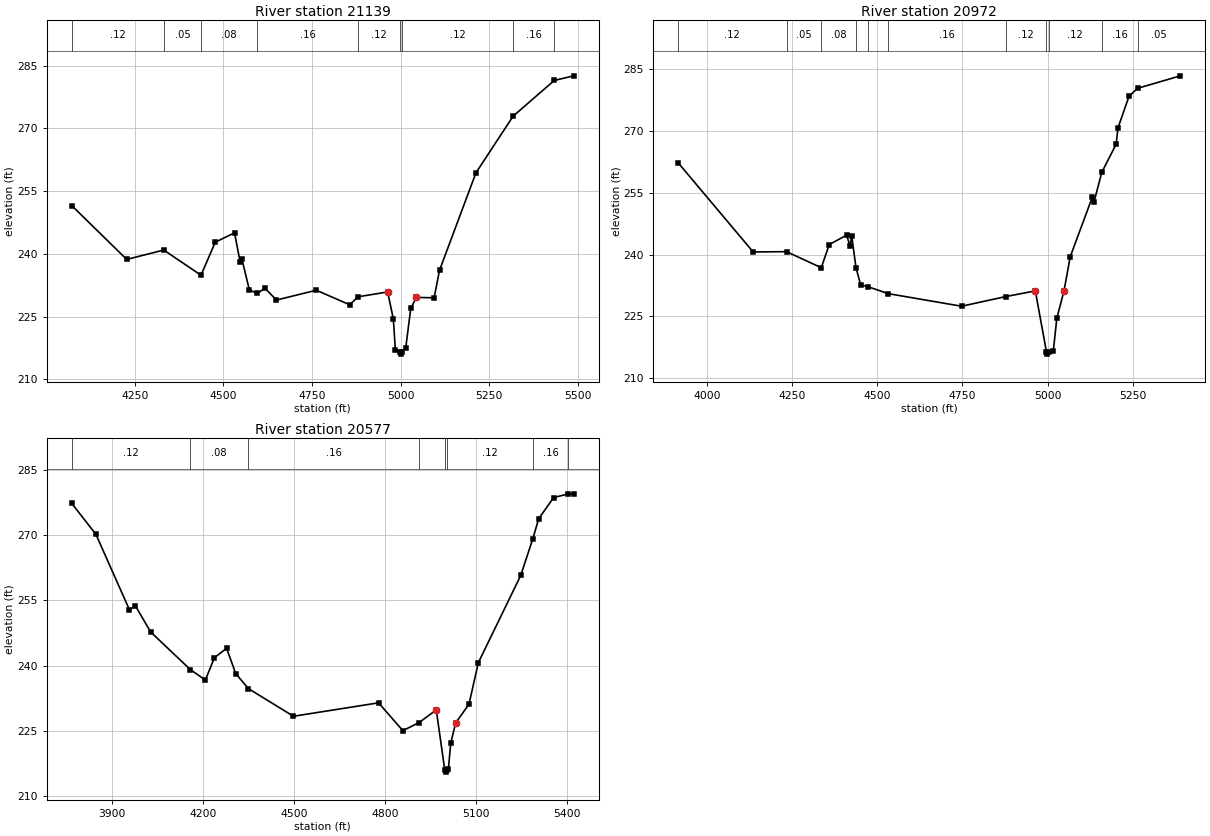
Type RM Length L Ch R = 1 ,21139   ,167,167,167
BEGIN DESCRIPTION:
Mapping XS 1c3ed90e
END DESCRIPTION:
XS GIS Cut Line= 3
       3718897.8     10619152.89      3718123.53     10619395.93
      3717595.76     10619691.06
#Sta/Elev= 30
  4072.3  251.58  4227.6   238.7  4332.1240.9357  4437.1234.9234  4477.3  242.82
  4531.6  245.05  4547.4  238.12  4552.6  238.73  4573.5  231.37  4596.2 230.599
  4617.4   231.8  4649.9  228.99  4762.2  231.33  4856.5  227.86  4880.1229.7716
  4963.5  230.92  4979.5  224.45  4985.2  217.05    4997  216.56  4999.8  216.06
    5003  216.56  5014.3  217.44  5028.6  226.99  5044.6  229.62  5094.5  229.52
  5109.7  236.09  5212.5  259.41  5317.4272.9475  5433.3281.4779  5488.5  282.58
#Mann= 9 ,-1 , 0
  4072.3     .12       0  4332.1     .05       0  4437.1     .08       0
  4596.2     .16       0  4880.1     .12       0    4997     .07       0
    5003     .12       0  5317.4     .16       0  5433.3     .05       0
Bank Sta=4963.5,5044.6
XS Rating Curve= 0 ,0
Exp/Cntr=0.3,0.1

Type RM Length L Ch R = 1 ,20972   ,395,395,395
BEGIN DESCRIPTION:
TOWN CREEK 24.0
END DESCRIPTION:
XS GIS Cut Line= 3
      3718963.79      10619100.8      3718019.36     10619298.71
      3717533.92     10619451.28
#Sta/Elev= 30
  3915.9  262.28  4136.1  240.64  4234.1240.7097    4336236.8225  4359.5  242.44
  4410.6  244.72  4420.3  242.02  4425.4  244.54  4437.9236.8238  4451.5  232.71
  4473.2232.2029  4532.3230.5275  4747.8  227.47  4877.9229.8219  4964.2  231.19
    4997  216.35  4999.8  215.85    5003  216.35  5016.9   216.5  5027.3  224.56
  5048.3  231.15  5066.6  239.47  5131.4  253.91  5136.7  252.84  5159.3259.9649
  5201.5   266.8  5206.7  270.72  5239.1  278.39  5264.2280.3325  5389.7  283.37
#Mann= 11 ,-1 , 0
  3915.9     .12       0  4234.1     .05       0    4336     .08       0
  4437.9     .16       0  4473.2     .08       0  4532.3     .16       0
  4877.9     .12       0    4997     .07       0    5003     .12       0
  5159.3     .16       0  5264.2     .05       0
Bank Sta=4964.2,5048.3
XS Rating Curve= 0 ,0
Exp/Cntr=0.3,0.1

Type RM Length L Ch R = 1 ,20577   ,574,574,574
BEGIN DESCRIPTION:
TOWN CREEK 23.0
END DESCRIPTION:
XS GIS Cut Line= 3
      3719049.61     10619010.19      3717799.61     10618960.19
      3717449.62     10619160.18
#Sta/Elev= 30
  3768.1  277.35  3848.2  270.18  3958.3  252.87  3978.3  253.72  4028.3  247.74
    4159239.0916  4208.5  236.69  4238.5  241.84  4278.5  243.98  4308.5  238.17
  4349.8 234.736  4498.7  228.35  4778.9  231.44    4859  225.05  4911.4226.8456
  4969.1  229.81    4997     216  4999.8   215.5    5003     216  5009.1  216.28
  5016.6   222.1  5032.8  226.82  5076.7  231.09  5107.6  240.68  5247.3  260.75
  5286.9269.1414  5306.3  273.76  5355.3  278.64  5403.4279.5032  5422.2  279.52
#Mann= 8 ,-1 , 0
  3768.1     .12       0    4159     .08       0  4349.8     .16       0
  4911.4     .12       0    4997     .07       0    5003     .12       0
  5286.9     .16       0  5403.4     .05       0
Bank Sta=4969.1,5032.8
XS Rating Curve= 0 ,0
Exp/Cntr=0.3,0.1