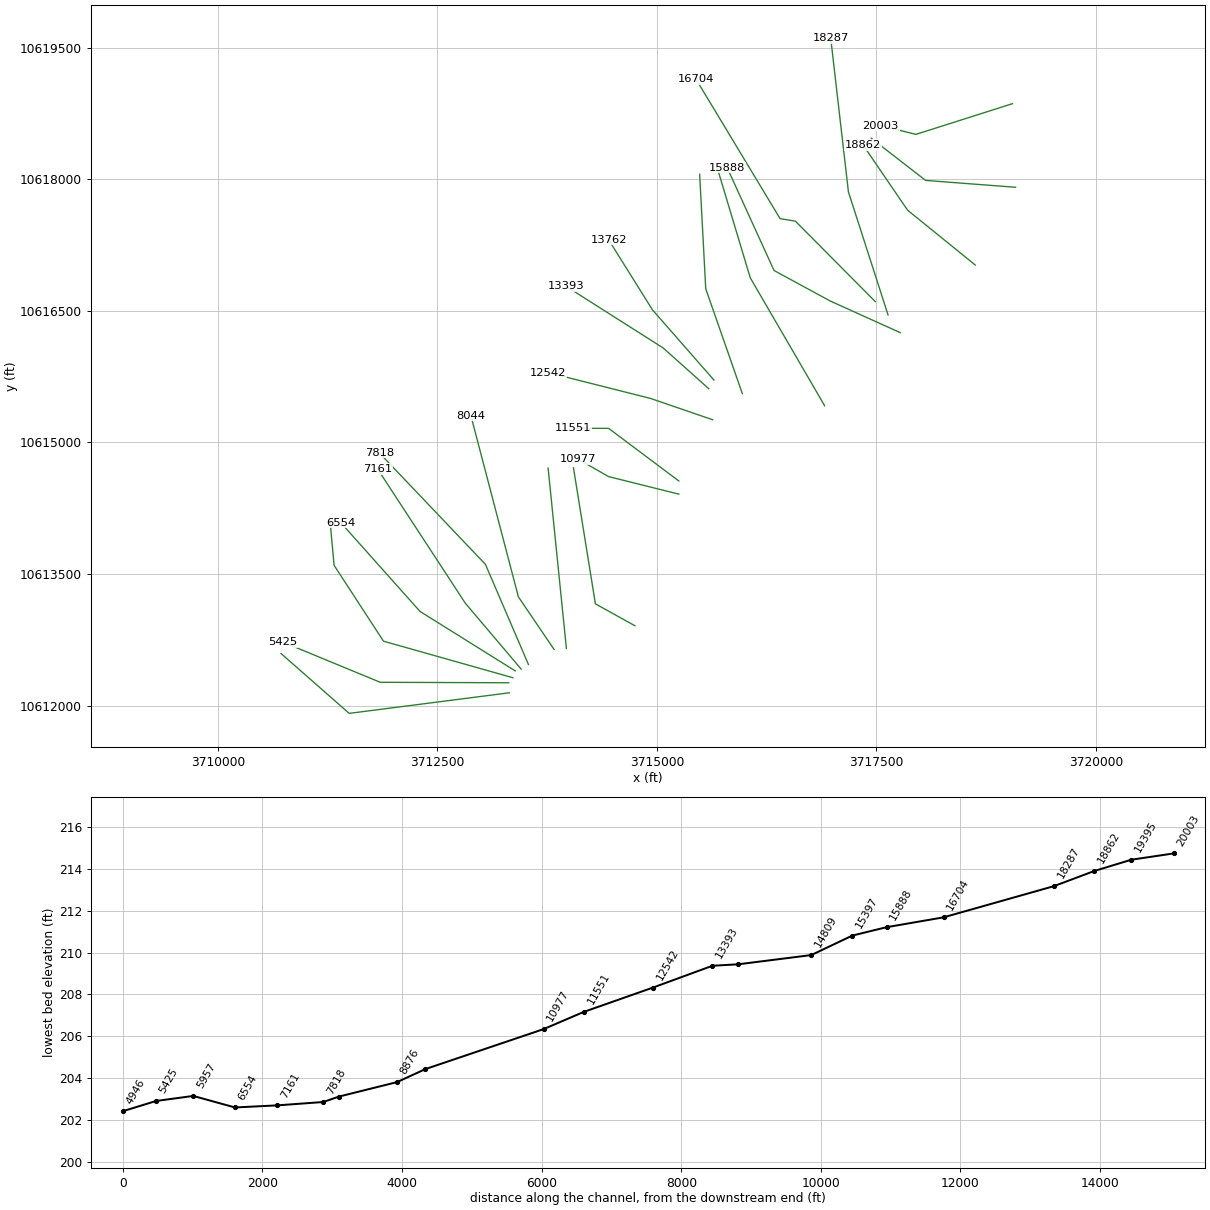
HEC-RAS study TOWN CREEK.prj: TOWN CREEK Base Level Engineering

--- TOWN CREEK.g01 (geometry) --- (continued)

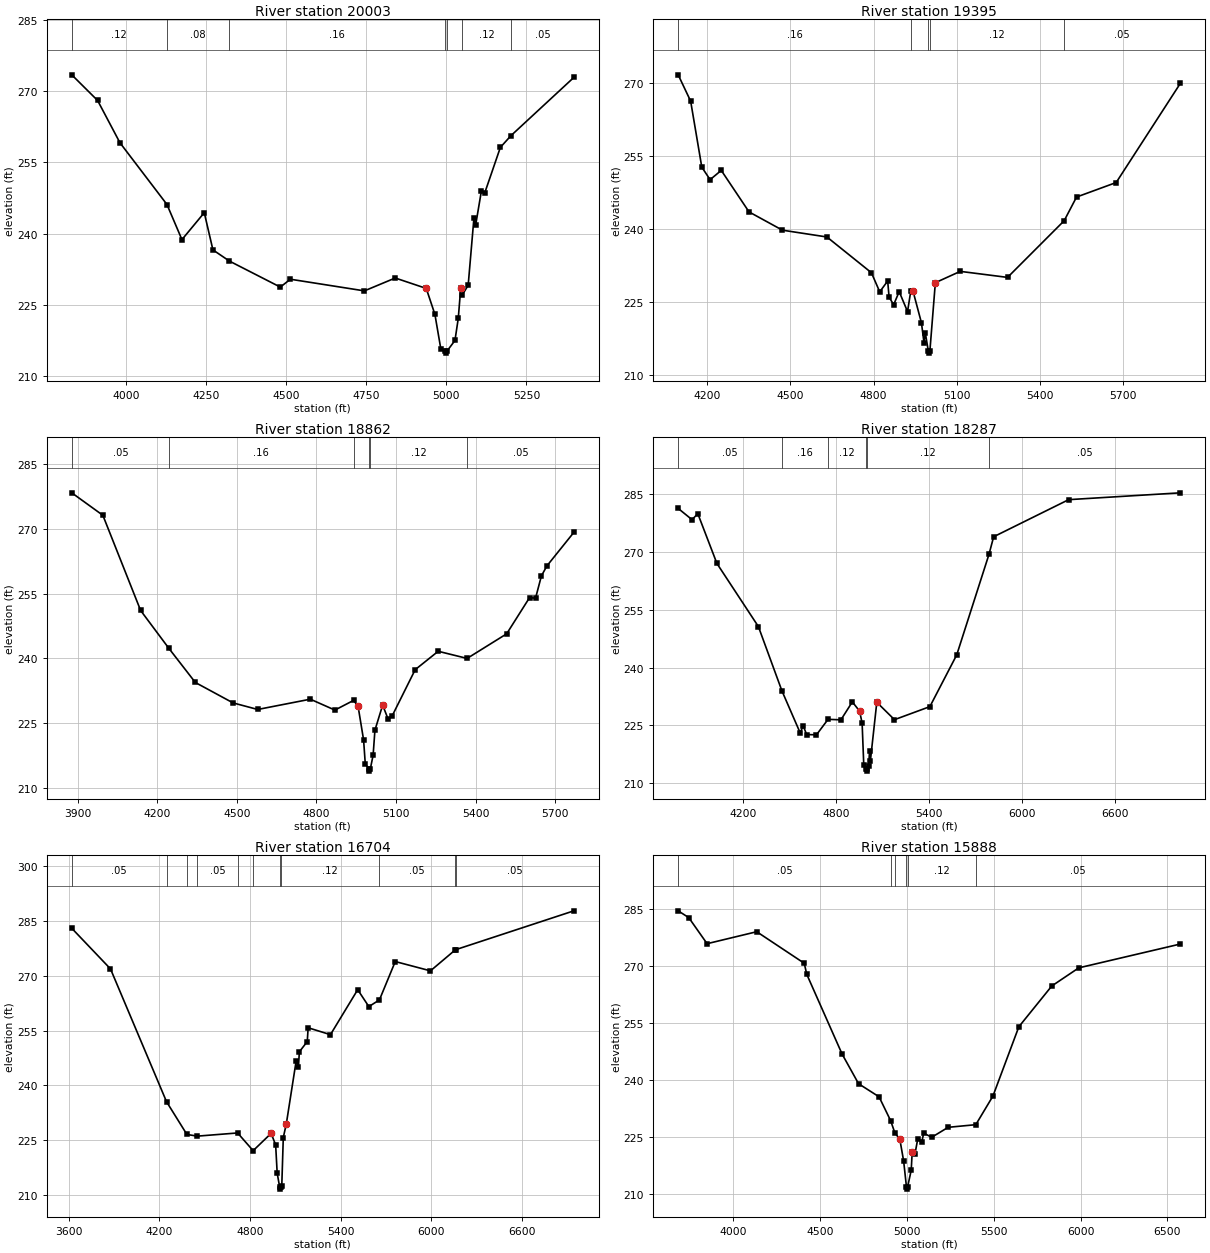
Type RM Length L Ch R = 1 ,20003   ,608,608,608
BEGIN DESCRIPTION:
TOWN CREEK 22.0
END DESCRIPTION:
XS GIS Cut Line= 3
      3719049.64      10618860.2      3717949.61     10618510.19
       3717549.6     10618610.19
#Sta/Elev= 30
  3831.5  273.52  3912.1   268.1  3981.8  259.17  4128.5246.1269  4175.2  238.71
  4244.9   244.4  4271.9  236.54  4323.4234.1731  4482.2  228.68  4513.6  230.34
  4744.5  227.88  4840.8   230.6  4937.5   228.4  4964.5  222.92  4983.3   215.5
    4997  215.23  4999.8  214.73    5003  215.23  5027.1  217.41  5037.4  222.08
  5045.1  228.48  5050.2227.0676  5068.3  229.06  5086.4  243.35  5091.5  241.72
  5109.6  249.01  5119.9  248.55  5168.8   258.2  5201.8260.6689  5398.2  272.98
#Mann= 7 ,-1 , 0
  3831.5     .12       0  4128.5     .08       0  4323.4     .16       0
    4997     .07       0    5003     .16       0  5050.2     .12       0
  5201.8     .05       0
Bank Sta=4937.5,5045.1
XS Rating Curve= 0 ,0
Exp/Cntr=0.3,0.1

Type RM Length L Ch R = 1 ,19395   ,533,533,533
BEGIN DESCRIPTION:
TOWN CREEK 21.0
END DESCRIPTION:
XS GIS Cut Line= 3
      3719084.52     10617907.45      3718060.24     10617985.57
      3717440.96     10618466.27
#Sta/Elev= 30
    4095  271.72    4140   266.3  4180.2  252.71  4210.2  250.14  4250.4  252.05
  4350.6   243.5    4471  239.74  4631.5  238.34  4791.9  230.99    4822  227.05
  4850.7  229.28  4855.7  225.97  4872.2  224.39  4892.2  227.09  4922.3  222.98
  4934.2227.2761  4942.4  227.13  4972.5  220.66  4981.6  216.61  4986.6  218.55
    4997  214.93  4999.8  214.43    5003  214.93  5022.6  228.93  5112.5  231.26
    5283  230.02  5487.3241.6875  5531.9  246.56  5674.9  249.55  5906.2  269.95
#Mann= 5 ,-1 , 0
    4095     .16       0  4934.2     .12       0    4997     .07       0
    5003     .12       0  5487.3     .05       0
Bank Sta=4942.4,5022.6
XS Rating Curve= 0 ,0
Exp/Cntr=0.3,0.1

Type RM Length L Ch R = 1 ,18862   ,575,575,575
BEGIN DESCRIPTION:
TOWN CREEK 20.0
END DESCRIPTION:
XS GIS Cut Line= 3
       3718625.6     10617021.45      3717854.77     10617646.45
      3717347.81     10618389.52
#Sta/Elev= 30
  3878.2  278.35  3995.3  273.15  4137.6   251.1  4244.4242.2992  4343.8  234.42
    4486  229.69  4578.7  228.17    4777  230.55  4869.6  228.03  4939.8230.2658
  4956.7     229  4977.7  221.12    4984  215.59    4997  214.39  4999.8  213.89
    5003  214.39  5013.6  217.58  5020.4  223.37  5049.5  229.18  5070.4  225.89
  5085.4  226.69  5172.1  237.39  5258.8  241.65  5367.7239.9931  5516.7  245.69
  5602.9  254.07  5625.6  253.96  5647.7  259.12  5668.7  261.45  5770.1  269.21
#Mann= 6 ,-1 , 0
  3878.2     .05       0  4244.4     .16       0  4939.8     .12       0
    4997     .07       0    5003     .12       0  5367.7     .05       0
Bank Sta=4956.7,5049.5
XS Rating Curve= 0 ,0
Exp/Cntr=0.3,0.1

Type RM Length L Ch R = 1 ,18287   ,1583,1583,1583
BEGIN DESCRIPTION:
TOWN CREEK 19.0
END DESCRIPTION:
XS GIS Cut Line= 3
      3717632.53     10616452.05      3717181.16     10617854.78
      3716979.77     10619604.77
#Sta/Elev= 30
  3784.6  281.23  3873.8  278.32  3911.2  279.86  4034.2  266.97  4301.4  250.62
    4453233.9719  4570.5  223.09  4590.1  224.89  4612.5  222.64  4675.6  222.58
  4750.2226.5883  4833.1  226.46  4906.7  231.11  4953.5  228.71  4969.7  225.61
  4980.2  214.87    4997  213.67  4999.8  213.17    5003  213.67  5011.7  214.54
  5017.7  218.44  5022.9  215.82  5064.3  231.01  5178.1   226.5  5406.2  229.88
  5579.3  243.29  5786.8 269.302  5817.2  273.89  6300.4   283.5  7019.7  285.27
#Mann= 6 ,-1 , 0
  3784.6     .05       0    4453     .16       0  4750.2     .12       0
    4997     .07       0    5003     .12       0  5786.8     .05       0
Bank Sta=4953.5,5064.3
XS Rating Curve= 0 ,0
Exp/Cntr=0.3,0.1

Type RM Length L Ch R = 1 ,16704   ,816,816,816
BEGIN DESCRIPTION:
TOWN CREEK 18.0
END DESCRIPTION:
XS GIS Cut Line= 4
      3717486.71     10616604.78      3716576.99     10617521.45
      3716403.38     10617549.23      3715445.04     10619139.51
#Sta/Elev= 30
  3620.6  282.96  3876.9  271.86    4248235.5576  4382.8226.6157  4452.2226.1628
  4718.4  227.03  4821.2 222.188  4940.3  226.92  4970.2  223.76  4980.3  216.06
    4997  212.18  4999.8  211.68    5003  212.18  5010.7  212.48  5020.8  225.77
  5041.1  229.58  5105.7  246.63  5121.2  245.16  5127.1   249.2  5179.5  252.01
  5185.3  255.78  5332.9  253.89  5513.4  266.18  5587.2  261.56  5657.2263.3897
    5762  273.87    5995  271.33  6154.7276.8952  6161.8277.1105  6944.6  287.73
#Mann= 11 ,-1 , 0
  3620.6     .05       0    4248     .12       0  4382.8     .16       0
  4452.2     .05       0  4718.4     .16       0  4821.2     .12       0
    4997     .07       0    5003     .12       0  5657.2     .05       0
  6154.7     .12       0  6161.8     .05       0
Bank Sta=4940.3,5041.1
XS Rating Curve= 0 ,0
Exp/Cntr=0.3,0.1

Type RM Length L Ch R = 1 ,15888   ,491,491,491
BEGIN DESCRIPTION:
TOWN CREEK 17.0
END DESCRIPTION:
XS GIS Cut Line= 4
      3717771.45     10616250.61      3716972.82     10616611.73
      3716333.93     10616958.95      3715799.22     10618132.55
#Sta/Elev= 30
  3681.4  284.46  3742.4  282.67    3848  275.81  4134.1  278.96  4407.8  270.66
  4422.4  267.74    4626  246.75  4720.9  238.95  4838.9  235.51  4905.7229.2184
  4929.6226.0517  4958.6  224.32  4980.5  218.62    4997  211.71  4999.8  211.21
    5003  211.71  5024.2  216.19  5029.9  221.09    5046  220.53  5062.2  224.51
    5084   223.5  5096.5  225.95    5142  224.85    5237  227.48  5396.3  228.17
  5495.1  235.71  5644.4  253.95  5834.2  264.68  5989.7  269.45  6574.7  275.72
#Mann= 6 ,-1 , 0
  3681.4     .05       0  4905.7     .16       0  4929.6     .12       0
    4997     .07       0    5003     .12       0  5396.3     .05       0
Bank Sta=4958.6,5029.9
XS Rating Curve= 0 ,0
Exp/Cntr=0.3,0.1

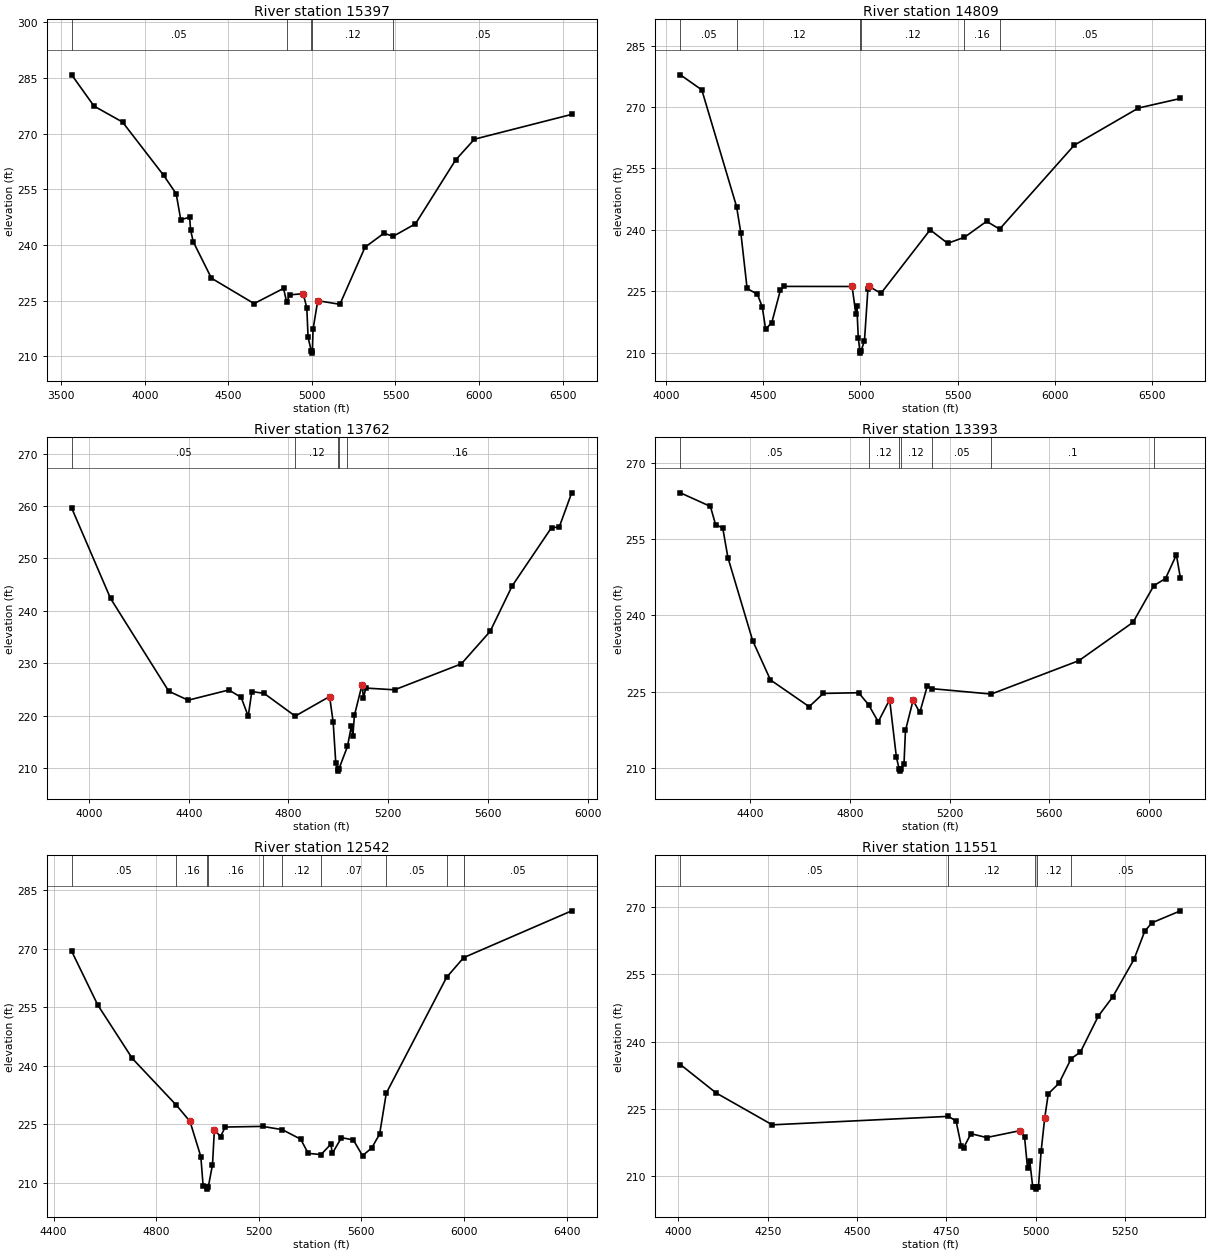
Type RM Length L Ch R = 1 ,15397   ,588,588,588
BEGIN DESCRIPTION:
TOWN CREEK 16.0
END DESCRIPTION:
XS GIS Cut Line= 3
      3716910.34     10615417.26       3716063.1     10616875.62
      3715688.17     10618125.38
#Sta/Elev= 30
    3563  285.87  3696.6  277.44  3867.1  273.14  4113.8  258.72  4188.3  253.79
  4215.6  246.78  4268.6  247.48  4274.4  244.07  4290.1  240.87  4399.1  231.02
  4654.3  224.17  4830.7  228.27    4849224.5655  4867.9  226.53  4948.2  226.83
  4969.7  223.02  4977.3  215.07    4997  211.31  4999.8  210.81    5003  211.31
    5007  217.24  5035.2  224.95  5167.6  223.98  5318.1  239.39  5431.9  243.16
  5485.8242.2985  5619.8  245.69  5859.9   262.9  5972.4  268.51  6554.4   275.2
#Mann= 5 ,-1 , 0
    3563     .05       0    4849     .12       0    4997     .07       0
    5003     .12       0  5485.8     .05       0
Bank Sta=4948.2,5035.2
XS Rating Curve= 0 ,0
Exp/Cntr=0.3,0.1

Type RM Length L Ch R = 1 ,14809   ,1047,1047,1047
BEGIN DESCRIPTION:
TOWN CREEK 15.0
END DESCRIPTION:
XS GIS Cut Line= 3
      3715972.84     10615556.13      3715556.16     10616750.62
      3715486.74      10618055.7
#Sta/Elev= 30
  4073.7  277.87  4183.9  274.19  4362.7245.6848  4385.1  239.13  4416.9  225.67
  4469.9  224.27  4494.9  221.17  4512.2  215.74    4544  217.35  4588.1  225.27
  4607.5  226.18    4957  226.16    4976  219.51  4981.3  221.37  4988.8  213.63
    4997  210.38  4999.8  209.88    5003  210.38  5020.6  212.91  5038.2  225.44
  5043.5  226.18  5105.6   224.5  5358.4     240  5448.5  236.71    5535238.1856
  5648.8  242.08  5715.6240.1735  6099.4  260.67  6429.9  269.76  6645.7  272.09
#Mann= 6 ,-1 , 0
  4073.7     .05       0  4362.7     .12       0    4997     .07       0
    5003     .12       0    5535     .16       0  5715.6     .05       0
Bank Sta=4957,5043.5
XS Rating Curve= 0 ,0
Exp/Cntr=0.3,0.1

Type RM Length L Ch R = 1 ,13762   ,369,369,369
BEGIN DESCRIPTION:
TOWN CREEK 14.0
END DESCRIPTION:
XS GIS Cut Line= 3
      3715649.61     10615710.19      3714949.61     10616510.19
      3714449.62     10617310.18
#Sta/Elev= 30
    3930  259.62  4086.1  242.37  4319.6  224.68  4397.4  222.97  4560.7  224.92
    4610  223.51  4638.5  219.91  4652.8  224.62  4702.1  224.27  4826.9219.9354
    4965  223.67  4979.3  218.78  4989.7  211.04    4997  209.94  4999.8  209.44
    5003  209.94  5036.7214.1578    5052  217.98  5058.5  216.16  5064.4  220.05
    5095  225.89  5100.9  223.44  5110.3  225.28  5225.9  224.95  5493.6   229.9
  5609.2   236.1  5697.6  244.77  5855.6   255.9  5886.3  255.98  5936.4  262.52
#Mann= 5 ,-1 , 0
    3930     .05       0  4826.9     .12       0    4997     .07       0
    5003     .12       0  5036.7     .16       0
Bank Sta=4965,5095
XS Rating Curve= 0 ,0
Exp/Cntr=0.3,0.1

Type RM Length L Ch R = 1 ,13393   ,851,851,851
BEGIN DESCRIPTION:
TOWN CREEK 13.0
END DESCRIPTION:
XS GIS Cut Line= 3
      3715590.91      10615611.7      3715070.05       10616077.
      3713965.91     10616778.37
#Sta/Elev= 30
  4119.5  264.07    4240   261.4  4260.9  257.79  4289.4  257.19  4310.3  251.33
  4409.7     235  4480.8   227.3  4636.3  222.04  4693.1  224.64  4834.7  224.78
  4874.4 222.435  4913.5  219.07  4959.2  223.41  4986.3  212.11    4997  209.87
  4999.8  209.37    5003  209.87  5016.8  210.77  5022.7  217.36  5053.2  223.27
  5080.3   220.9  5110.8  226.18  5127.9225.5832  5366.8224.5159  5718.8  231.09
  5935.8  238.62  6019.4245.8336  6066.2  247.22  6109.8  251.88    6126  247.31
#Mann= 7 ,-1 , 0
  4119.5     .05       0  4874.4     .12       0    4997     .07       0
    5003     .12       0  5127.9     .05       0  5366.8      .1       0
  6019.4     .16       0
Bank Sta=4959.2,5053.2
XS Rating Curve= 0 ,0
Exp/Cntr=0.3,0.1

Type RM Length L Ch R = 1 ,12542   ,991,991,991
BEGIN DESCRIPTION:
TOWN CREEK 12.0
END DESCRIPTION:
XS GIS Cut Line= 3
      3715635.79     10615257.52      3714928.36     10615500.56
      3713763.71     10615794.97
#Sta/Elev= 30
  4470.6   269.4  4572.3   255.6  4707.1  241.87  4879.2229.8441  4931.8  225.72
  4974.1  216.68    4983  209.22    4997  208.83  4999.8  208.33    5003  208.83
  5019.6  214.59    5027  223.62  5050.8  221.81  5069.3  224.27  5214.8224.4342
  5291.7223.6003  5363.4  221.15  5392.7  217.51  5442.8217.2006  5481.3   219.9
  5486.5  217.48  5522.4  221.54  5568.6  220.96  5604.4  216.92  5640.2  218.88
  5671.2  222.48  5697.1232.9623    5932 262.679  5998.8267.7593  6419.9  279.77
#Mann= 10 ,-1 , 0
  4470.6     .05       0  4879.2     .16       0    4997     .07       0
    5003     .16       0  5214.8     .05       0  5291.7     .12       0
  5442.8     .07       0  5697.1     .05       0    5932     .12       0
  5998.8     .05       0
Bank Sta=4931.8,5027
XS Rating Curve= 0 ,0
Exp/Cntr=0.3,0.1

Type RM Length L Ch R = 1 ,11551   ,574,574,574
BEGIN DESCRIPTION:
TOWN CREEK 11.0
END DESCRIPTION:
XS GIS Cut Line= 3
      3715249.64     10614560.17      3714449.61     10615160.19
      3714049.64     10615160.19
#Sta/Elev= 30
  4005.5   234.9  4105.5  228.58  4262.8  221.48  4756.1223.3659  4777.4  222.32
    4792  216.74  4798.2  216.33  4819.1  219.51  4862.8  218.65  4955.5  220.17
  4969.1  218.82  4977.4  211.84  4983.7  213.39    4992  207.69    4997  207.67
  4999.8  207.17    5003  207.67    5008  207.67  5015.5  215.58  5025.5  222.96
  5035.5  228.39  5065.5  230.73  5099.6236.2118  5125.5  237.67  5175.5  245.66
  5215.5   249.9  5275.5   258.3  5305.5  264.55  5325.5  266.44  5405.5  269.11
#Mann= 5 ,-1 , 0
  4005.5     .05       0  4756.1     .12       0    4997     .07       0
    5003     .12       0  5099.6     .05       0
Bank Sta=4955.5,5025.5
XS Rating Curve= 0 ,0
Exp/Cntr=0.3,0.1

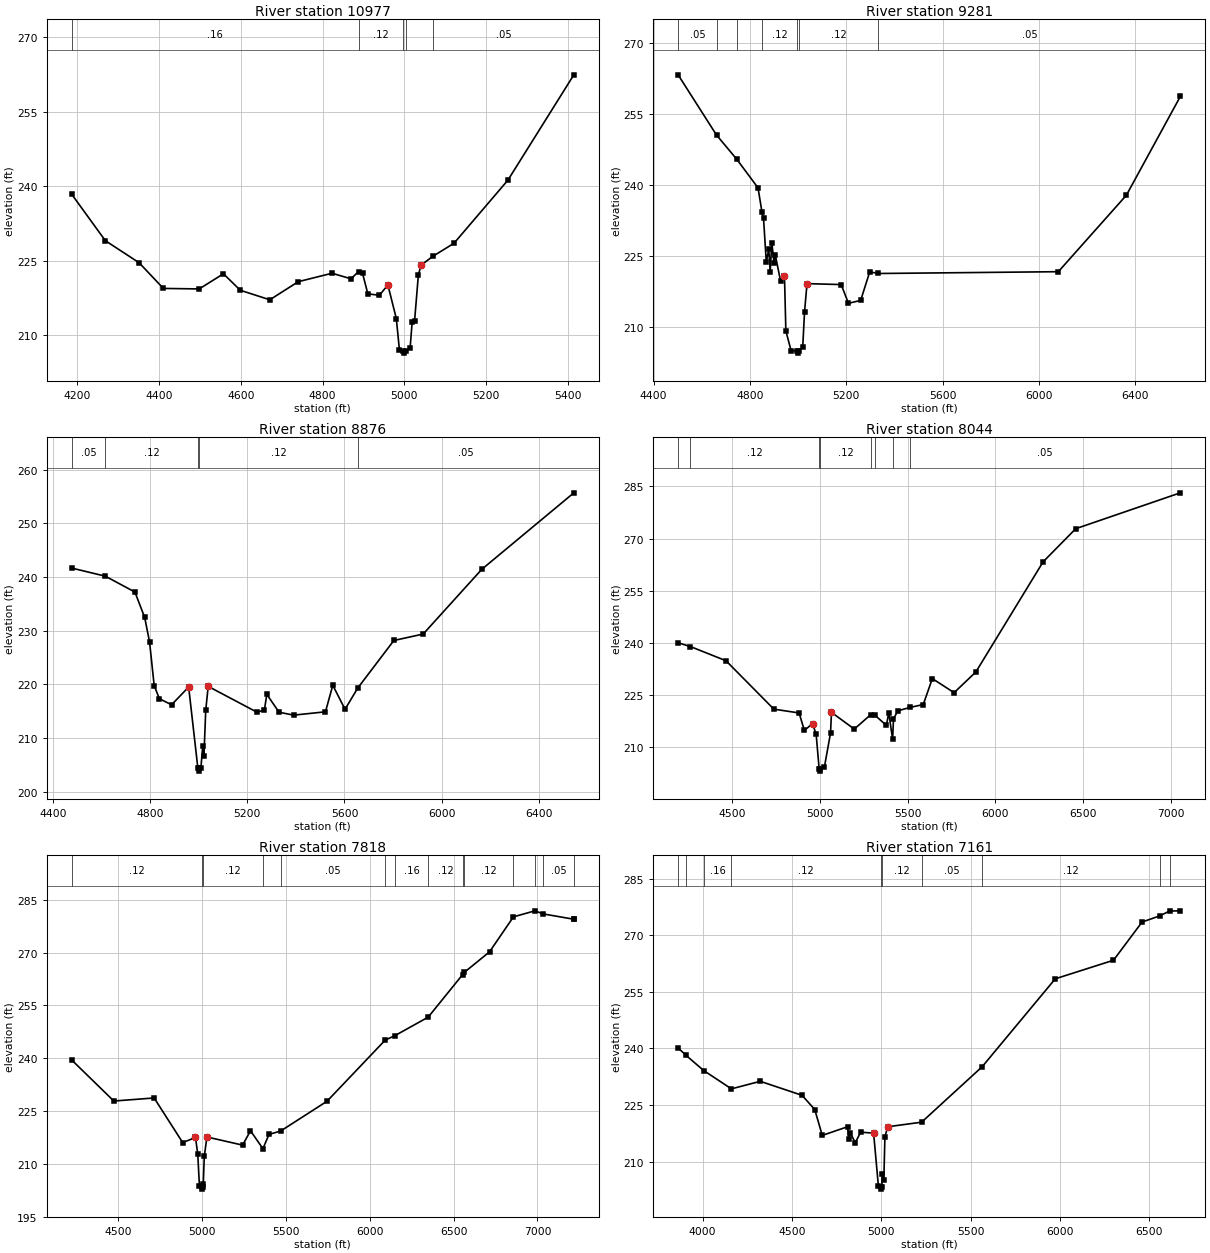
Type RM Length L Ch R = 1 ,10977   ,1696,1696,1696
BEGIN DESCRIPTION:
TOWN CREEK 10.0
END DESCRIPTION:
XS GIS Cut Line= 3
      3715249.59     10614410.19      3714449.61     10614610.19
      3714099.62     10614810.18
#Sta/Elev= 30
  4186.5  238.39  4268.9  229.01  4351.4  224.57  4410.7  219.39  4498.3  219.29
  4557.6  222.34  4598.8  219.02  4670.9   217.1  4740.5  220.75    4823  222.45
  4869.4  221.33  4887.8222.7748  4897.7   222.4  4910.6   218.3  4938.9  218.01
  4959.6  220.09  4980.2  213.32  4987.9  206.91    4997  206.85  4999.8  206.35
    5003  206.85    5014  207.46    5019   212.7  5024.8  212.77  5034.1  222.09
  5040.6  224.07  5069.4225.8535  5121.2  228.49    5253  241.21  5414.2  262.44
#Mann= 5 ,-1 , 0
  4186.5     .16       0  4887.8     .12       0    4997     .07       0
    5003     .12       0  5069.4     .05       0
Bank Sta=4959.6,5040.6
XS Rating Curve= 0 ,0
Exp/Cntr=0.3,0.1

Type RM Length L Ch R = 1 ,9281    ,405,405,405
BEGIN DESCRIPTION:
TOWN CREEK 9.0
END DESCRIPTION:
XS GIS Cut Line= 3
      3714749.62     10612910.18      3714299.61     10613160.19
      3714049.61     10614710.16
#Sta/Elev= 30
  4501.7  263.26  4661.1250.5355  4745.2 245.411  4833.5  239.37  4849.9234.2113
  4856.3  232.95  4867.8  223.63  4878.1  226.48  4883.8  221.62  4890.7  227.78
  4899.8  223.57  4905.5   225.1  4927.3  219.59  4943.3  220.66    4949  209.13
  4970.7  204.96    4997  204.94  4999.8  204.44    5003  204.94    5019  205.74
  5026.6  213.21  5036.8  219.13  5178.6  218.93  5208.9  214.97  5259.6  215.59
  5297.1  221.61  5333.4221.2704  6080.1  221.65  6362.7  237.82  6586.5  258.68
#Mann= 7 ,-1 , 0
  4501.7     .05       0  4661.1     .12       0  4745.2     .05       0
  4849.9     .12       0    4997     .07       0    5003     .12       0
  5333.4     .05       0
Bank Sta=4943.3,5036.8
XS Rating Curve= 0 ,0
Exp/Cntr=0.3,0.1

Type RM Length L Ch R = 1 ,8876    ,832,832,832
BEGIN DESCRIPTION:
TOWN CREEK 8.0
END DESCRIPTION:
XS GIS Cut Line= 2
       3713969.2     10612651.26      3713761.04     10614706.85
#Sta/Elev= 30
  4477.6  241.68    4616 240.172  4737.9  237.21  4778.1  232.47  4798.2  227.89
  4817.1  219.78  4838.4  217.33  4888.6  216.19    4959   219.5    4997  204.32
  4999.8  203.82    5003  204.32  5009.2  204.32  5016.8  208.44  5021.9  206.72
  5029.3  215.21  5039.4  219.62  5240.4   214.8  5270.6  215.23  5280.6  218.13
  5330.9   214.8  5391.2  214.26  5521.8  214.88    5552  219.83  5602.3  215.35
  5654.7219.3151  5803.3  228.18  5923.9  229.38  6165.1  241.45  6543.7  255.71
#Mann= 5 ,-1 , 0
  4477.6     .05       0    4616     .12       0    4997     .07       0
    5003     .12       0  5654.7     .05       0
Bank Sta=4959,5039.4
XS Rating Curve= 0 ,0
Exp/Cntr=0.3,0.1

Type RM Length L Ch R = 1 ,8044    ,226,226,226
BEGIN DESCRIPTION:
TOWN CREEK 7.0
END DESCRIPTION:
XS GIS Cut Line= 3
      3713828.57     10612640.81      3713422.33     10613239.76
      3712880.96     10615306.31
#Sta/Elev= 30
  4193.6  240.03  4262.7238.9686  4466.3  234.87  4738.9  220.95  4882.6  219.86
  4912.5  214.84  4959.1  216.79  4979.8   213.7    4997  203.63  4999.8  203.13
    5003  203.63  5026.5  204.25  5061.7  214.11  5066.9  220.03  5196.9  215.22
  5290.8 219.377  5314.8219.1873  5379.8  216.28  5393.3  219.94  5415.2 212.257
  5420.2  218.16    5445  220.48  5515.5221.4564  5589.7  222.28  5641.4  229.74
  5765.4  225.69  5889.5  231.66    6272   263.3    6458  272.84  7053.6  283.16
#Mann= 8 ,-1 , 0
  4193.6     .05       0  4262.7     .12       0    4997     .07       0
    5003     .12       0  5290.8     .16       0  5314.8     .12       0
  5415.2     .16       0  5515.5     .05       0
Bank Sta=4959.1,5066.9
XS Rating Curve= 0 ,0
Exp/Cntr=0.3,0.1

Type RM Length L Ch R = 1 ,7818    ,657,657,657
BEGIN DESCRIPTION:
TOWN CREEK 6.0
END DESCRIPTION:
XS GIS Cut Line= 3
      3713536.89     10612468.96      3713047.33     10613609.55
        3711839.     10614880.38
#Sta/Elev= 30
    4222  239.53  4473.6  227.87    4714  228.74  4884.3  216.07  4960.5  217.53
  4974.2  212.73    4984  203.71    4997  203.37  4999.8  202.87    5003  203.37
  5006.9  204.36    5013  212.17  5028.6  217.67  5241.4  215.36  5288.5  219.43
  5362.6214.3542    5399  218.39  5468.7219.3685  5744.9  227.81  6092.1245.1726
  6148.4246.3878  6348.2251.6761    6554263.7723  6562.8264.3557  6714.1  270.21
  6856.6280.1374  6984.9281.8447    7035280.9596  7215.4  279.47  7216.8  279.47
#Mann= 14 ,-1 , 0
    4222     .12       0    4997     .07       0    5003     .12       0
  5362.6     .16       0  5468.7     .05       0  6092.1     .12       0
  6148.4     .16       0  6348.2     .12       0    6554     .16       0
  6562.8     .12       0  6856.6     .05       0  6984.9      .1       0
    7035     .05       0  7215.4      .1       0
Bank Sta=4960.5,5028.6
XS Rating Curve= 0 ,0
Exp/Cntr=0.3,0.1

Type RM Length L Ch R = 1 ,7161    ,607,607,607
BEGIN DESCRIPTION:
TOWN CREEK 5.0
END DESCRIPTION:
XS GIS Cut Line= 3
      3713453.59     10612416.83      3712818.16     10613166.84
      3711819.12     10614696.62
#Sta/Elev= 30
  3862.9  240.14  3908.2238.1325  4005.8234.1541  4161.2229.2904  4322.4  231.29
  4556.4  227.58  4627.5  223.81  4669.5  216.95  4811.2  219.25    4819  215.92
  4825.5  217.69  4854.1  215.01  4884.4  217.81  4956.8  217.55  4983.8  203.42
    4997  203.21  4999.8  202.71    5003  203.21  5005.2  206.84  5014.1  205.25
    5020  216.44  5035.1  219.24  5225.3220.4522  5564.3235.1558  5973.3  258.46
  6299.1  263.38    6459  273.51  6557.9  275.14  6612.8276.4245    6673  276.48
#Mann= 10 ,-1 , 0
  3862.9     .16       0  3908.2     .12       0  4005.8     .16       0
  4161.2     .12       0    4997     .07       0    5003     .12       0
  5225.3     .05       0  5564.3     .12       0  6557.9     .16       0
  6612.8      .1       0
Bank Sta=4956.8,5035.1
XS Rating Curve= 0 ,0
Exp/Cntr=0.3,0.1

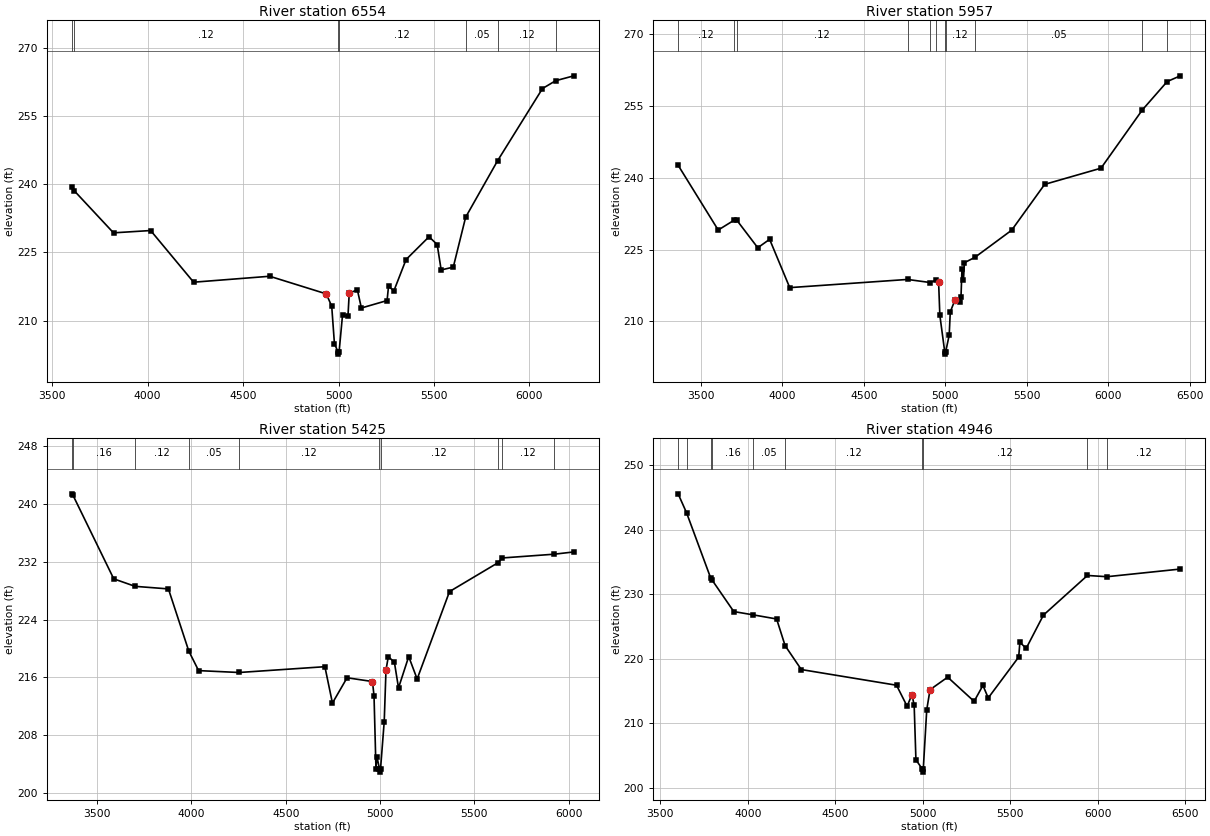
Type RM Length L Ch R = 1 ,6554    ,597,597,597
BEGIN DESCRIPTION:
TOWN CREEK 4.0
END DESCRIPTION:
XS GIS Cut Line= 3
      3713385.88       10612396.      3712302.53     10613073.09
      3711401.46     10614083.55
#Sta/Elev= 30
  3601.6  239.36  3615.7238.5648  3820.9  229.32  4015.5  229.83  4240.7  218.45
  4639.3  219.76  4935.8  215.88  4964.3  213.16  4978.5  204.95    4997  203.11
  4999.8  202.61    5003  203.11  5021.1  211.28  5049.4  210.93  5056.2  216.11
  5098.9  216.73  5119.8  212.77  5254.4  214.41  5261.9  217.51  5290.3  216.57
  5353.9  223.44  5474.2  228.46  5516.9  226.75  5537.8  221.15  5601.3  221.77
    5666232.7545  5833.3245.1908  6068.7   261.1  6137.6262.8227    6233   263.9
#Mann= 7 ,-1 , 0
  3601.6     .16       0  3615.7     .12       0    4997     .07       0
    5003     .12       0    5666     .05       0  5833.3     .12       0
  6137.6     .16       0
Bank Sta=4935.8,5056.2
XS Rating Curve= 0 ,0
Exp/Cntr=0.3,0.1

Type RM Length L Ch R = 1 ,5957    ,532,532,532
BEGIN DESCRIPTION:
TOWN CREEK 3.0
END DESCRIPTION:
XS GIS Cut Line= 4
      3713359.86     10612317.88      3711885.87     10612734.55
      3711323.37     10613599.13      3711276.49      10614114.8
#Sta/Elev= 30
  3361.4  242.61  3607.4  229.08  3703.9231.1144    3720   231.2  3850.1  225.38
  3922.8  227.14  4046.2  217.05  4768.7218.7589  4909.7218.1073  4943.2218.6597
  4959.5  218.28  4967.1  211.28    4997  203.66  4999.8  203.16    5003  203.66
  5024.5  207.12  5031.1  211.98  5060.7  214.54  5090.8  214.01  5096.9  215.15
  5102.9  220.87  5112.1  218.74    5118  222.26  5181.7223.3661  5407.9  229.05
  5610.2  238.62  5955.8     242  6209.7254.1781    6362260.0987  6442.4  261.29
#Mann= 11 ,-1 , 0
  3361.4     .12       0  3703.9     .16       0    3720     .12       0
  4768.7     .05       0  4909.7     .08       0  4943.2     .12       0
    4997     .07       0    5003     .12       0  5181.7     .05       0
  6209.7     .12       0    6362     .16       0
Bank Sta=4959.5,5060.7
XS Rating Curve= 0 ,0
Exp/Cntr=0.3,0.1

Type RM Length L Ch R = 1 ,5425    ,479,479,479
BEGIN DESCRIPTION:
TOWN CREEK 2.0
END DESCRIPTION:
XS GIS Cut Line= 3
      3713312.91     10612260.59      3711849.41      10612265.8
      3710740.06     10612724.12
#Sta/Elev= 30
  3364.4  241.38    3371241.2088  3587.7  229.63  3700.9228.5952  3877.7  228.24
  3985.6219.6588  4037.7  216.95  4252.5216.6888  4707.7  217.49  4747.7  212.46
  4825.3  215.96  4960.1  215.44  4968.3  213.45  4978.6  203.42    4984  205.01
    4997  203.42  4999.8  202.92    5003  203.42  5022.4  209.91  5031.8  217.03
  5044.1  218.89  5076.5  218.08  5098.2  214.56  5152.3  218.89    5197  215.79
  5368.7  227.87  5626.6231.8702  5648.5 232.517  5923.9233.0364  6028.2  233.35
#Mann= 10 ,-1 , 0
  3364.4     .12       0    3371     .16       0  3700.9     .12       0
  3985.6     .05       0  4252.5     .12       0    4997     .07       0
    5003     .12       0  5626.6     .16       0  5648.5     .12       0
  5923.9     .16       0
Bank Sta=4960.1,5031.8
XS Rating Curve= 0 ,0
Exp/Cntr=0.3,0.1

Type RM Length L Ch R = 1 ,4946    ,0,0,0
BEGIN DESCRIPTION:
TOWN CREEK 1.0
END DESCRIPTION:
XS GIS Cut Line= 3
       3713318.2     10612146.01      3711495.24     10611911.63
      3710719.19     10612593.93
#Sta/Elev= 30
  3601.2  245.57  3649.5242.6319  3786.6232.5774  3795.3232.2097  3919.4  227.32
  4031.5226.8028  4164.4  226.17    4213222.0305  4305.5  218.33    4850   215.9
  4910.5  212.64  4938.2  214.46  4950.8   212.8  4960.9  204.33    4997  202.93
  4999.8  202.43    5003  202.93  5022.8  212.11  5041.6  215.21  5142.4  217.15
  5293.6   213.4    5344  215.87  5374.3  213.93  5548.5  220.27  5555.2  222.57
  5591.2  221.61  5689.9  226.77  5941.5232.9154  6053.2232.7237  6472.5  233.91
#Mann= 10 ,-1 , 0
  3601.2     .12       0  3649.5     .16       0  3786.6     .12       0
  3795.3     .16       0  4031.5     .05       0    4213     .12       0
    4997     .07       0    5003     .12       0  5941.5     .16       0
  6053.2     .12       0
Bank Sta=4938.2,5041.6
XS Rating Curve= 0 ,0
Exp/Cntr=0.3,0.1

Chan Stop Cuts=-1
Use User Specified Reach Order=0
Composite Channel Slope=5