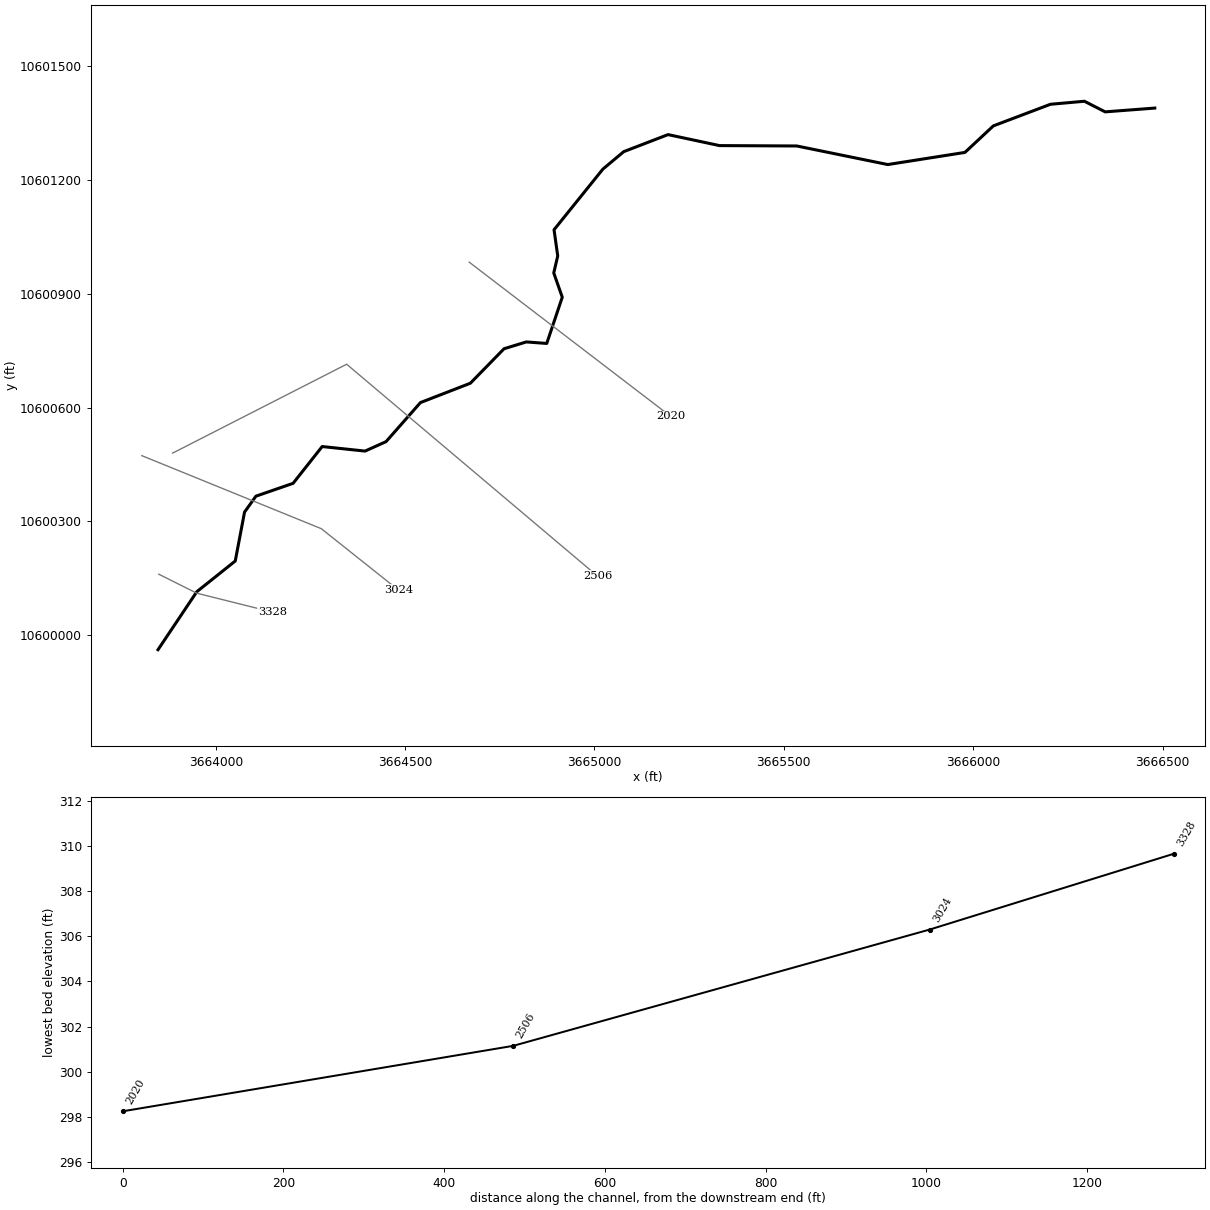
--- UNT 003 IN BOCR.prj (project) ---

Proj Title=UNT 003 IN BOCR Base Level Engineering
Current Plan=p01
Default Exp/Contr=0.3,0.1
English Units
Geom File=g01
Flow File=f01
Plan File=p01
Y Axis Title=Elevation
X Axis Title(PF)=Main Channel Distance
X Axis Title(XS)=Station
BEGIN DESCRIPTION:
UNT 003 IN BOCR
END DESCRIPTION:
DSS Export Rating Curves= 0
DSS Export Rating Curve Sorted= 0
DSS Export Volume Flow Curves= 0
DXF OffsetX= 0
DXF OffsetY= 0
DXF ScaleX= 1
DXF ScaleY= 10

--- UNT 003 IN BOCR.p01 (plan) ---

Plan Title=Multiple Run
Short Identifier=Multiple
Geom File=g01
Flow File=f01
Subcritical Flow
K Sum by GR= 0
Std Step Tol= 0.01
Critical Tol= 0.01
Num of Std Step Trials= 20
Max Error Tol= 0.3
Flow Tol Ratio= 0.001
Split Flow NTrial= 30
Split Flow Tol= 0.02
Split Flow Ratio= 0.02
Log Output Level= 0
Friction Slope Method= 1
Unsteady Friction Slope Method= 2
Unsteady Bridges Friction Slope Method= 1
Parabolic Critical Depth
Global Vel Dist=  1 , 1 , 1
Global Log Level= 0
CheckData=True
Encroach Param= -1, 0, 0, 0
BEGIN DESCRIPTION:
Multiple Run
END DESCRIPTION:

--- UNT 003 IN BOCR.f01 (steady flow) ---

Flow Title=Multiple
Program Version=4.10
Number of Profiles= 7
Profile Names=10-year,25-year,50-year,1pct_min,100-year,1pct_plu,500-year
River Rch & RM=UNT 003 IN BOCR,Reach-1         ,3328
     170     213     246     209     283     383     377
Boundary for River Rch & Prof#=UNT 003 IN BOCR,Reach-1         , 1
Up Type= 0
Dn Type= 3
Dn Slope=0.005
Boundary for River Rch & Prof#=UNT 003 IN BOCR,Reach-1         , 2
Up Type= 0
Dn Type= 3
Dn Slope=0.005
Boundary for River Rch & Prof#=UNT 003 IN BOCR,Reach-1         , 3
Up Type= 0
Dn Type= 3
Dn Slope=0.005
Boundary for River Rch & Prof#=UNT 003 IN BOCR,Reach-1         , 4
Up Type= 0
Dn Type= 3
Dn Slope=0.005
Boundary for River Rch & Prof#=UNT 003 IN BOCR,Reach-1         , 5
Up Type= 0
Dn Type= 3
Dn Slope=0.005
Boundary for River Rch & Prof#=UNT 003 IN BOCR,Reach-1         , 6
Up Type= 0
Dn Type= 3
Dn Slope=0.005
Boundary for River Rch & Prof#=UNT 003 IN BOCR,Reach-1         , 7
Up Type= 0
Dn Type= 3
Dn Slope=0.005
DSS Import GetInterval= 0
DSS Import GetPeak= 0
DSS Import FillOption= 0

--- UNT 003 IN BOCR.g01 (geometry) ---

Geom Title=Existing Conditions

River Reach=UNT 003 IN BOCR,Reach-1
Reach XY= 30
      3663847.56     10599961.03      3663950.00     10600114.00
      3664051.50     10600195.00      3664076.00     10600324.00
      3664106.00     10600366.00      3664204.25     10600400.00
      3664281.00     10600497.00      3664394.25     10600485.00
      3664449.75     10600510.00      3664540.50     10600613.00
      3664672.25     10600664.00      3664761.25     10600755.00
      3664820.00     10600773.00      3664874.00     10600769.00
      3664915.00     10600891.00      3664892.50     10600955.00
      3664903.00     10601000.00      3664893.25     10601069.00
      3665022.25     10601229.00      3665077.25     10601275.00
      3665194.25     10601320.00      3665330.25     10601291.00
      3665534.25     10601290.00      3665774.50     10601241.00
      3665978.25     10601273.00      3666053.25     10601343.00
      3666204.00     10601400.00      3666293.75     10601408.00
      3666348.50     10601380.00      3666479.50     10601390.00

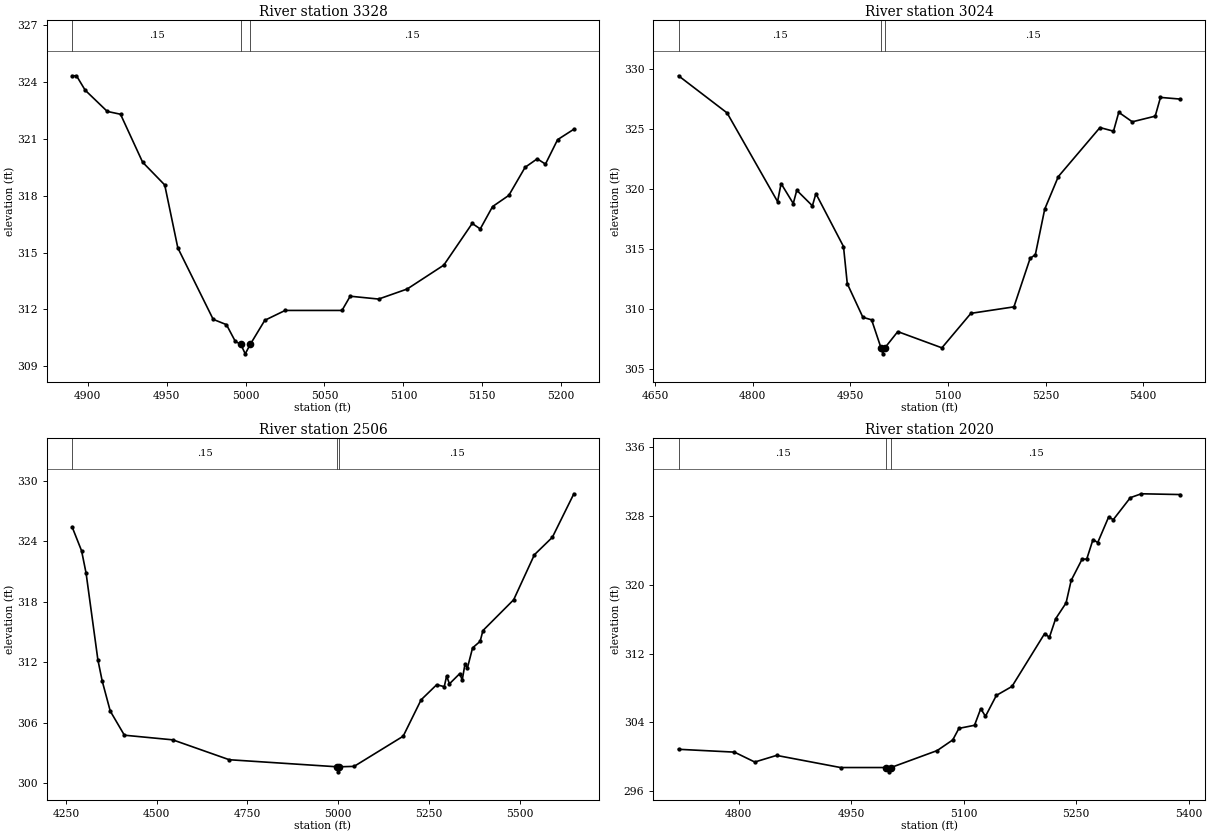
Type RM Length L Ch R = 1,3328,304,304,304
BEGIN DESCRIPTION:
UNT 003 IN BOCR 2.0
END DESCRIPTION:
XS GIS Cut Line= 3
      3663849.65     10600160.17      3663949.61     10600110.19
      3664149.59     10600060.19
#Sta/Elev= 30
  4890.1  324.33  4892.9  324.33  4898.4  323.57  4912.4  322.45  4920.8  322.30
  4934.8  319.77  4948.8  318.57  4957.1  315.25  4979.5  311.48  4987.9  311.20
  4993.5  310.32  4997.0  310.16  4999.8  309.66  5003.0  310.16  5012.2  311.43
  5025.1  311.95  5061.1  311.95  5066.3  312.70  5084.3  312.55  5102.4  313.08
  5125.6  314.34  5143.6  316.54  5148.7  316.25  5156.5  317.43  5166.8  318.02
  5177.1  319.50  5184.8  319.95  5190.0  319.67  5197.7  320.96  5208.0  321.51
#Mann=3,-1,0
  4890.1    0.15       0  4997.0    0.05       0  5003.0    0.15       0
Bank Sta=4997,5003
Exp/Cntr=0.3,0.1

Type RM Length L Ch R = 1,3024,518,518,518
BEGIN DESCRIPTION:
Mapping XS 5ebeb2be
END DESCRIPTION:
XS GIS Cut Line= 3
      3663804.76     10600472.97      3664278.72     10600280.26
      3664481.83     10600118.81
#Sta/Elev= 30
  4685.9  329.44  4760.5  326.35  4838.1  318.97  4843.5  320.47  4862.2  318.81
  4867.6  319.91  4891.6  318.62  4897.0  319.63  4939.4  315.23  4945.2  312.14
  4969.2  309.34  4982.6  309.13  4997.0  306.80  4999.8  306.30  5003.0  306.80
  5022.8  308.15  5090.6  306.80  5135.2  309.67  5201.3  310.21  5226.2  314.25
  5234.2  314.55  5248.6  318.34  5269.5  321.05  5333.5  325.13  5354.3  324.83
  5362.4  326.40  5383.2  325.61  5418.4  326.08  5426.5  327.64  5457.0  327.50
#Mann=3,-1,0
  4685.9    0.15       0  4997.0    0.05       0  5003.0    0.15       0
Bank Sta=4997,5003
Exp/Cntr=0.3,0.1

Type RM Length L Ch R = 1,2506,486,486,486
BEGIN DESCRIPTION:
Mapping XS 88171810
END DESCRIPTION:
XS GIS Cut Line= 3
      3663886.24     10600479.72      3664345.66     10600714.16
      3665007.86     10600155.28
#Sta/Elev= 30
  4267.1  325.43  4293.3  323.05  4305.7  320.84  4338.2  312.25  4350.1  310.15
  4372.3  307.17  4411.2  304.78  4544.5  304.32  4700.1  302.35  4997.0  301.65
  4999.8  301.15  5003.0  301.65  5044.0  301.69  5179.2  304.68  5228.7  308.29
  5271.5  309.78  5292.4  309.59  5298.9  310.64  5306.7  309.87  5335.3  310.89
  5341.8  310.23  5349.6  311.85  5356.1  311.43  5370.4  313.43  5391.2  314.08
  5399.0  315.15  5483.6  318.20  5540.7  322.66  5590.2  324.39  5649.4  328.70
#Mann=3,-1,0
  4267.1    0.15       0  4997.0    0.05       0  5003.0    0.15       0
Bank Sta=4997,5003
Exp/Cntr=0.3,0.1

Type RM Length L Ch R = 1,2020,0,0,0
BEGIN DESCRIPTION:
UNT 003 IN BOCR 1.0
END DESCRIPTION:
XS GIS Cut Line= 2
      3664669.32     10600983.40      3665200.59     10600577.14
#Sta/Elev= 30
  4719.9  300.87  4794.4  300.54  4821.5  299.39  4850.6  300.16  4935.8  298.75
  4997.0  298.75  4999.8  298.25  5003.0  298.75  5064.6  300.72  5085.4  301.96
  5093.6  303.30  5114.4  303.66  5122.7  305.59  5129.0  304.70  5143.5  307.13
  5164.3  308.17  5207.9  314.32  5214.2  313.88  5222.4  316.02  5236.4  317.87
  5243.2  320.49  5257.7  322.95  5264.0  322.98  5272.3  325.24  5278.6  324.89
  5293.1  327.85  5299.4  327.56  5322.1  330.11  5336.7  330.56  5388.7  330.47
#Mann=3,-1,0
  4719.9    0.15       0  4997.0    0.05       0  5003.0    0.15       0
Bank Sta=4997,5003
Exp/Cntr=0.3,0.1

Chan Stop Cuts=-1