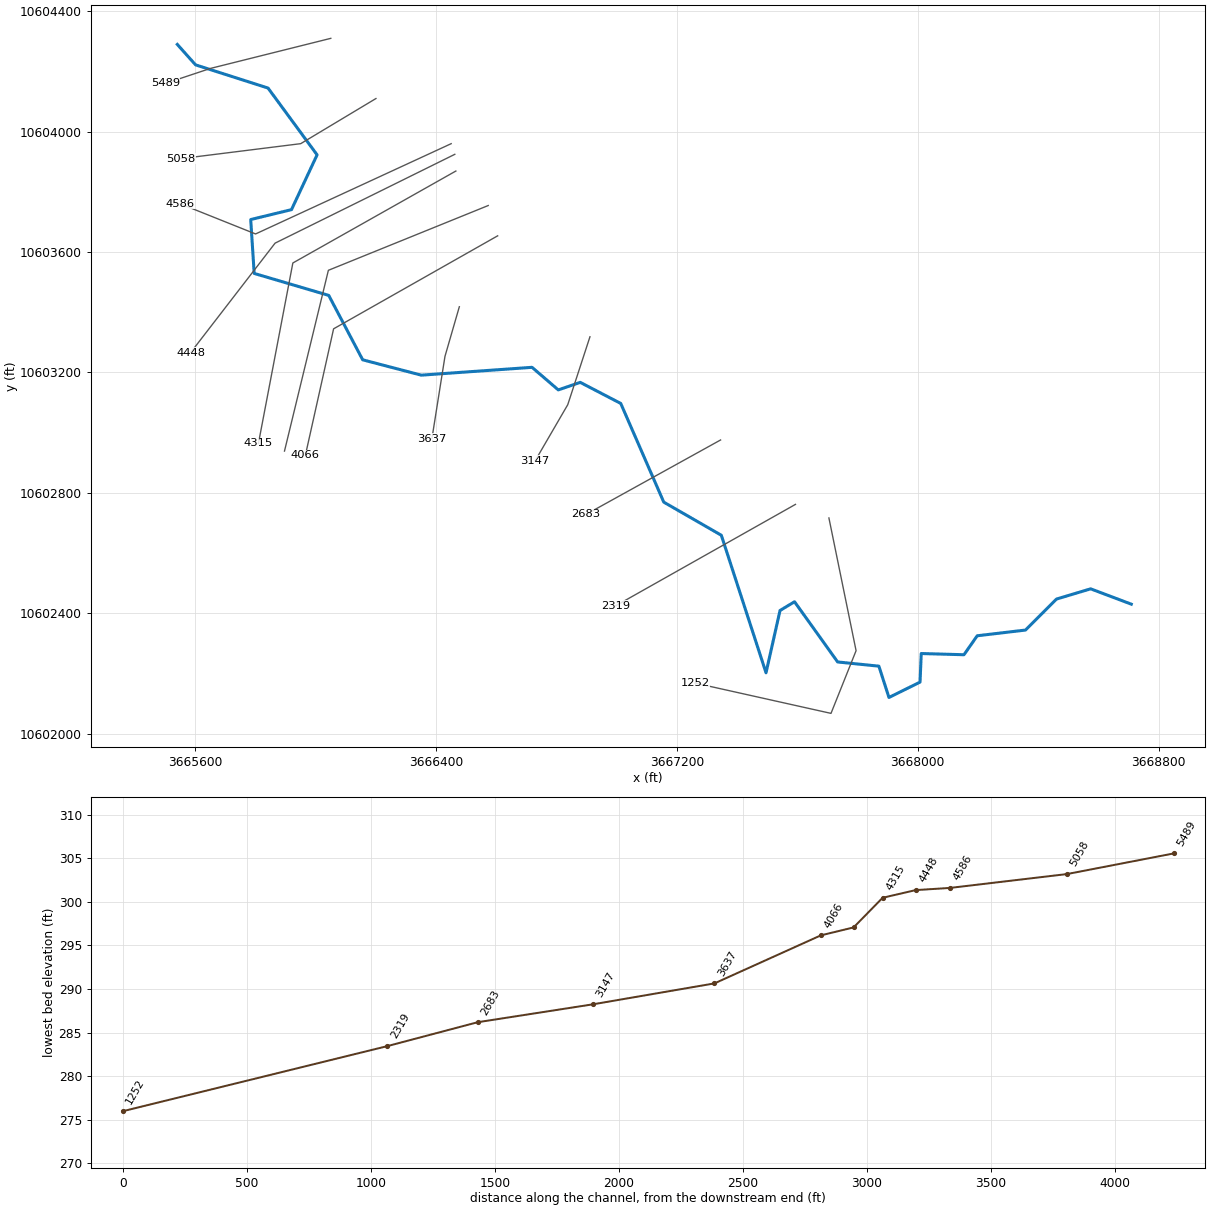
--- UNT 004 IN BOCR.prj (project) ---

Proj Title=UNT 004 IN BOCR Base Level Engineering
Current Plan=p01
Default Exp/Contr=0.3,0.1
English Units
Geom File=g01
Flow File=f01
Plan File=p01
Y Axis Title=Elevation
X Axis Title(PF)=Main Channel Distance
X Axis Title(XS)=Station
BEGIN DESCRIPTION:
UNT 004 IN BOCR
END DESCRIPTION:
DSS Export Rating Curves= 0
DSS Export Rating Curve Sorted= 0
DSS Export Volume Flow Curves= 0
DXF OffsetX= 0
DXF OffsetY= 0
DXF ScaleX= 1
DXF ScaleY= 10

--- UNT 004 IN BOCR.p01 (plan) ---

Plan Title=Multiple Run
Short Identifier=Multiple
Geom File=g01
Flow File=f01
Subcritical Flow
K Sum by GR= 0
Std Step Tol= 0.01
Critical Tol= 0.01
Num of Std Step Trials= 20
Max Error Tol= 0.3
Flow Tol Ratio= 0.001
Split Flow NTrial= 30
Split Flow Tol= 0.02
Split Flow Ratio= 0.02
Log Output Level= 0
Friction Slope Method= 1
Unsteady Friction Slope Method= 2
Unsteady Bridges Friction Slope Method= 1
Parabolic Critical Depth
Global Vel Dist=  1 , 1 , 1
Global Log Level= 0
CheckData=True
Encroach Param= -1, 0, 0, 0
BEGIN DESCRIPTION:
Multiple Run
END DESCRIPTION:

--- UNT 004 IN BOCR.f01 (steady flow) ---

Flow Title=Multiple
Program Version=4.10
Number of Profiles= 7
Profile Names=10-year,25-year,50-year,1pct_min,100-year,1pct_plu,500-year
River Rch & RM=UNT 004 IN BOCR,Reach-1         ,5489
     644     880    1076     967    1308    1769    1941
Boundary for River Rch & Prof#=UNT 004 IN BOCR,Reach-1         , 1
Up Type= 0
Dn Type= 3
Dn Slope=0.007
Boundary for River Rch & Prof#=UNT 004 IN BOCR,Reach-1         , 2
Up Type= 0
Dn Type= 3
Dn Slope=0.007
Boundary for River Rch & Prof#=UNT 004 IN BOCR,Reach-1         , 3
Up Type= 0
Dn Type= 3
Dn Slope=0.007
Boundary for River Rch & Prof#=UNT 004 IN BOCR,Reach-1         , 4
Up Type= 0
Dn Type= 3
Dn Slope=0.007
Boundary for River Rch & Prof#=UNT 004 IN BOCR,Reach-1         , 5
Up Type= 0
Dn Type= 3
Dn Slope=0.007
Boundary for River Rch & Prof#=UNT 004 IN BOCR,Reach-1         , 6
Up Type= 0
Dn Type= 3
Dn Slope=0.007
Boundary for River Rch & Prof#=UNT 004 IN BOCR,Reach-1         , 7
Up Type= 0
Dn Type= 3
Dn Slope=0.007
DSS Import GetInterval= 0
DSS Import GetPeak= 0
DSS Import FillOption= 0

--- UNT 004 IN BOCR.g01 (geometry) ---

Geom Title=Existing Conditions
Program Version=4.10

River Reach=UNT 004 IN BOCR ,Reach-1
Reach XY= 30
       3665539.5       10604290.      3665600.25       10604222.
        3665841.       10604145.        3666004.       10603923.
        3665919.       10603741.       3665783.5       10603708.
        3665795.       10603529.      3666042.75       10603456.
       3666155.5       10603242.      3666350.25       10603191.
      3666718.25       10603217.       3666805.5       10603142.
       3666878.5       10603167.        3667013.       10603097.
        3667156.       10602769.      3667347.25       10602659.
      3667495.75       10602202.      3667542.25       10602409.
       3667590.5       10602438.      3667733.75       10602238.
      3667870.75       10602224.      3667904.25       10602120.
       3668007.5       10602171.       3668011.5       10602266.
       3668153.5       10602262.       3668197.5       10602325.
        3668358.       10602344.        3668461.       10602447.
       3668574.5       10602481.       3668709.5       10602430.

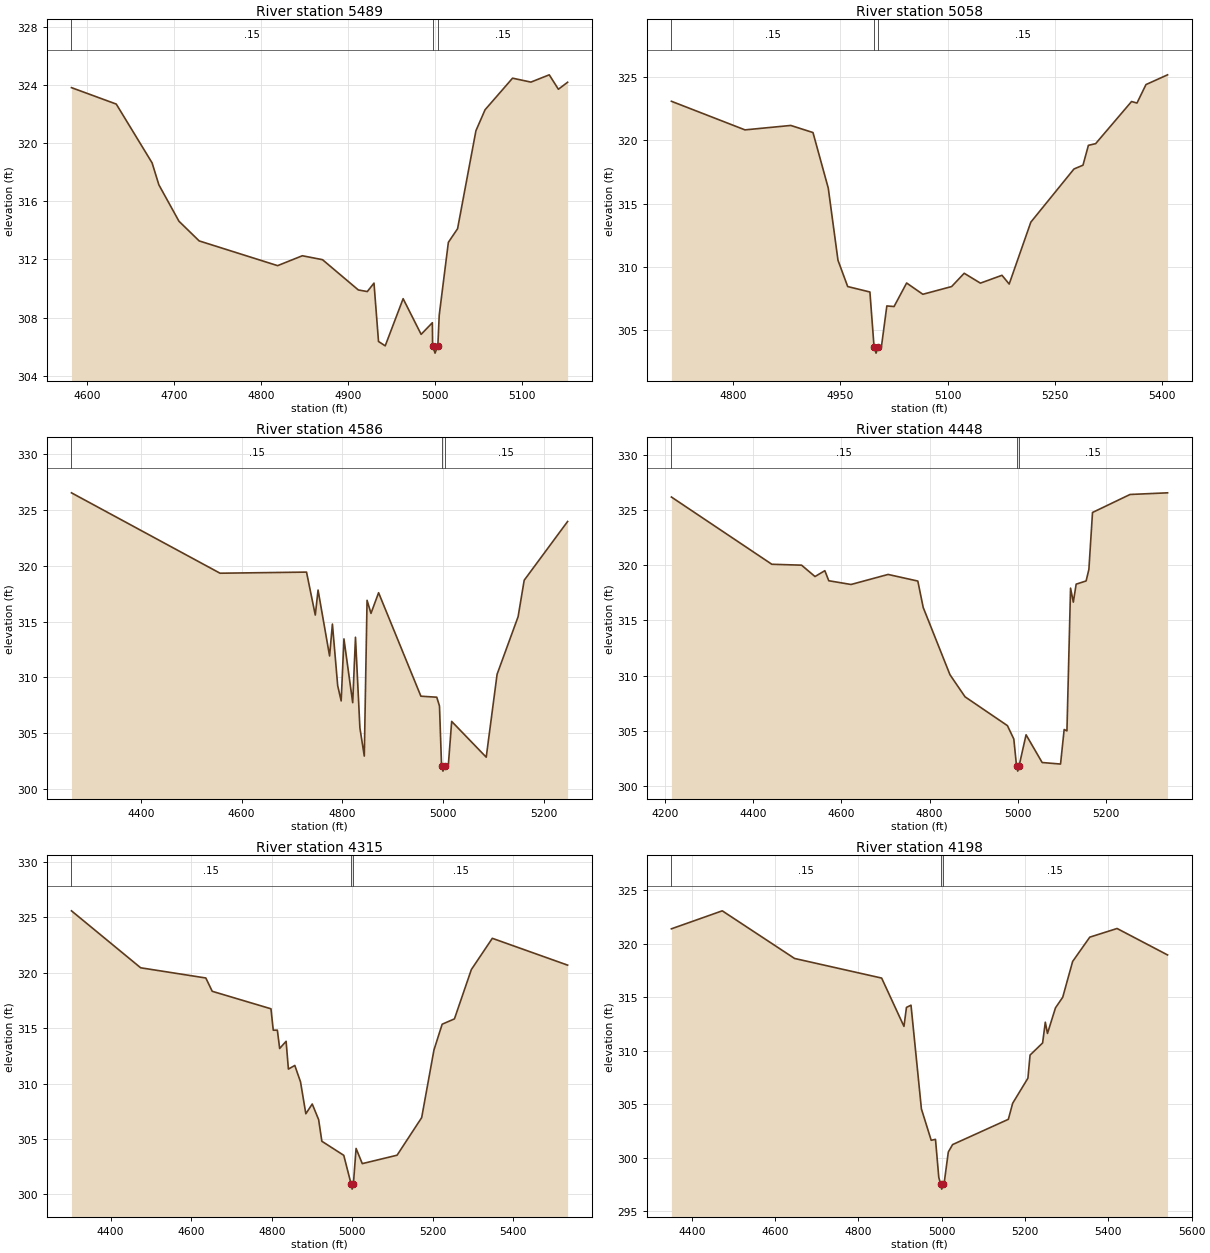
Type RM Length L Ch R = 1 ,5489    ,431,431,431
BEGIN DESCRIPTION:
UNT 004 IN BOCR 8.0
END DESCRIPTION:
XS GIS Cut Line= 3
      3666049.56     10604310.18      3665649.61     10604210.19
      3665499.59     10604160.18
#Sta/Elev= 30
  4581.8   323.8  4633.3  322.67  4674.5  318.63  4682.3  317.12  4705.4  314.62
  4728.6  313.27  4818.8  311.57  4847.2  312.25  4870.4  311.98  4911.6   309.9
  4921.9  309.79  4929.6  310.37  4934.8  306.36  4942.5  306.06  4963.1   309.3
  4983.8  306.85  4996.7  307.65    4997  306.06  4999.8  305.56    5003  306.06
  5004.6  308.17  5015.1  313.17  5025.7  314.11  5046.8  320.84  5057.3  322.28
  5088.9  324.45    5110  324.18  5131.1  324.68  5141.6  323.69  5152.2  324.17
#Mann= 3 ,-1 , 0
  4581.8     .15       0    4997     .05       0    5003     .15       0
Bank Sta=4997,5003
XS Rating Curve= 0 ,0
Exp/Cntr=0.3,0.1

Type RM Length L Ch R = 1 ,5058    ,472,472,472
BEGIN DESCRIPTION:
UNT 004 IN BOCR 7.0
END DESCRIPTION:
XS GIS Cut Line= 3
      3666199.58     10604110.17      3665949.61     10603960.19
      3665549.64     10603910.19
#Sta/Elev= 30
  4713.3  323.09  4816.3  320.83  4880.4  321.18  4911.5  320.62  4932.9  316.23
  4946.5  310.53  4960.1  308.45  4991.2  308.02    4997  303.69  4999.8  303.19
    5003  303.69  5007.3  303.69  5014.9  306.92    5025  306.87  5042.6  308.73
  5065.3  307.84  5105.6  308.45  5123.2   309.5  5145.9  308.72  5176.1  309.34
  5186.2  308.65  5216.5  313.54  5276.9  317.74  5289.5  318.04  5297.1  319.61
  5307.2  319.74  5357.5  323.07  5365.1  322.95  5377.7  324.41  5407.9  325.18
#Mann= 3 ,-1 , 0
  4713.3     .15       0    4997     .05       0    5003     .15       0
Bank Sta=4997,5003
XS Rating Curve= 0 ,0
Exp/Cntr=0.3,0.1

Type RM Length L Ch R = 1 ,4586    ,138,138,138
BEGIN DESCRIPTION:
UNT 004 IN BOCR 6.0
END DESCRIPTION:
XS GIS Cut Line= 3
      3666449.56     10603960.17      3665799.61     10603660.19
      3665549.61     10603760.19
#Sta/Elev= 30
  4262.2  326.56  4557.2  319.35  4728.9  319.45  4746.3   315.6  4751.8  317.84
  4774.7  311.93  4780.3  314.79  4790.8  309.26  4797.7   307.9  4803.2  313.46
  4820.6  307.74  4826.1  313.61  4834.9  305.47  4843.6  302.95  4849.1  316.92
  4856.9  315.75    4872   317.6    4956  308.32  4987.5  308.23  4992.9  307.44
    4997   302.1  4999.8   301.6    5003   302.1  5010.4   302.1  5017.1  306.06
  5085.7  302.85  5107.3  310.29    5149  315.45  5161.1  318.72  5247.3  323.99
#Mann= 3 ,-1 , 0
  4262.2     .15       0    4997     .05       0    5003     .15       0
Bank Sta=4997,5003
XS Rating Curve= 0 ,0
Exp/Cntr=0.3,0.1

Type RM Length L Ch R = 1 ,4448    ,133,133,133
BEGIN DESCRIPTION:
Mapping XS 67d6b308
END DESCRIPTION:
XS GIS Cut Line= 3
      3666461.62     10603924.77      3665864.44     10603629.65
      3665583.97     10603266.09
#Sta/Elev= 30
  4214.3  326.17  4442.1  320.08  4509.5     320    4540  318.97  4562.3   319.5
  4571.2  318.59  4621.7  318.25  4705.8  319.16  4773.2  318.56  4785.4  316.17
  4846.1  310.08  4880.3  308.08  4976.4  305.47  4990.9  304.26    4997  301.85
  4999.8  301.35    5003  301.85  5018.7  304.64  5055.2  302.13  5096.9  301.99
  5105.1  305.12  5111.4  304.99  5119.6  317.92  5125.9  316.65  5132.3  318.28
  5154.9  318.57  5161.2  319.62  5169.4  324.77  5254.5   326.4  5339.6  326.55
#Mann= 3 ,-1 , 0
  4214.3     .15       0    4997     .05       0    5003     .15       0
Bank Sta=4997,5003
XS Rating Curve= 0 ,0
Exp/Cntr=0.3,0.1

Type RM Length L Ch R = 1 ,4315    ,117,117,117
BEGIN DESCRIPTION:
UNT 004 IN BOCR 5.0
END DESCRIPTION:
XS GIS Cut Line= 3
      3666465.11     10603869.22      3665923.46     10603563.68
      3665809.09     10602964.07
#Sta/Elev= 30
  4302.7  325.58  4474.6  320.44  4636.4  319.52  4652.3  318.32  4798.2  316.74
  4803.9  314.81  4814.1  314.81  4819.8  313.16  4835.8  313.81  4841.5   311.3
  4857.4  311.63  4871.6  310.15  4884.8  307.27  4900.7  308.15  4916.6  306.74
  4924.6  304.79    4979  303.52    4997  300.97  4999.8  300.47    5003  300.97
  5009.6  304.14    5025  302.77  5111.4  303.53  5172.5  306.92    5203  313.02
  5223.4  315.35  5253.9  315.83  5295.9  320.28    5348   323.1    5535  320.68
#Mann= 3 ,-1 , 0
  4302.7     .15       0    4997     .05       0    5003     .15       0
Bank Sta=4997,5003
XS Rating Curve= 0 ,0
Exp/Cntr=0.3,0.1

Type RM Length L Ch R = 1 ,4198    ,132,132,132
BEGIN DESCRIPTION:
Mapping XS 43923996
END DESCRIPTION:
XS GIS Cut Line= 3
      3666572.73     10603754.64      3666041.52     10603539.37
      3665895.69     10602938.69
#Sta/Elev= 30
  4350.8  321.38  4472.9  323.06  4646.6  318.61  4855.6  316.78  4909.2  312.27
  4915.2  314.04  4926.1  314.25  4951.1  304.56  4974.6  301.63  4984.9  301.72
  4992.8  298.17    4997  297.57  4999.8  297.07    5003  297.57  5005.5  297.57
  5015.7  300.54    5026  301.23  5159.8  303.59  5170.2  305.09  5206.8  307.43
    5212  309.59  5242.1  310.72  5248.6  312.66  5253.8  311.61    5273     314
  5290.4  314.99  5314.2  318.33  5355.3   320.6  5420.9  321.41  5542.1  318.94
#Mann= 3 ,-1 , 0
  4350.8     .15       0    4997     .05       0    5003     .15       0
Bank Sta=4997,5003
XS Rating Curve= 0 ,0
Exp/Cntr=0.3,0.1

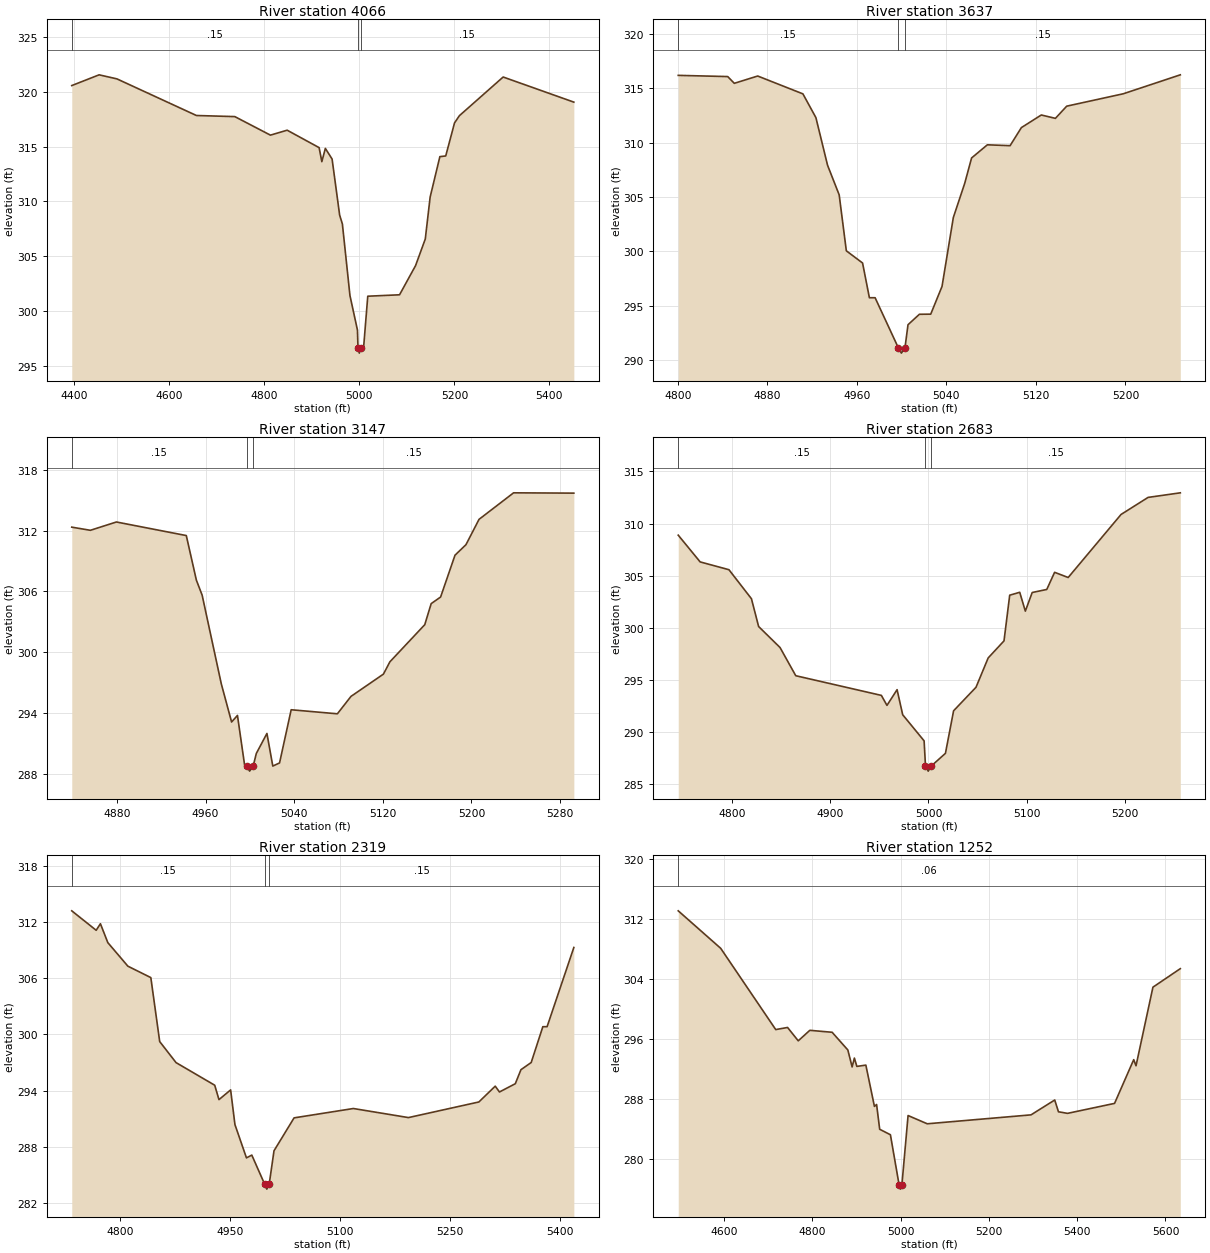
Type RM Length L Ch R = 1 ,4066    ,429,429,429
BEGIN DESCRIPTION:
Mapping XS d941cd25
END DESCRIPTION:
XS GIS Cut Line= 3
      3666604.02     10603653.96      3666058.88     10603344.93
      3665965.18       10602925.
#Sta/Elev= 30
  4394.5  320.56  4452.1  321.54  4489.6  321.17  4656.9  317.83  4737.7  317.73
  4812.7  316.04  4847.9  316.49  4915.2   314.9  4920.9  313.62  4928.3  314.83
  4942.5  313.86  4958.4  308.75  4964.2  307.93  4980.1  301.41  4995.9  298.26
    4997  296.66  4999.8  296.16    5003  296.66  5008.8  296.66  5017.6  301.35
  5084.5  301.48  5118.2  304.14  5138.7  306.57  5148.9  310.39  5169.4  314.08
  5181.7  314.14  5200.2  317.15  5210.4  317.81  5302.6  321.34  5451.4  319.05
#Mann= 3 ,-1 , 0
  4394.5     .15       0    4997     .05       0    5003     .15       0
Bank Sta=4997,5003
XS Rating Curve= 0 ,0
Exp/Cntr=0.3,0.1

Type RM Length L Ch R = 1 ,3637    ,490,490,490
BEGIN DESCRIPTION:
UNT 004 IN BOCR 4.0
END DESCRIPTION:
XS GIS Cut Line= 3
      3666476.69     10603418.35      3666428.95     10603253.41
      3666385.54     10602979.94
#Sta/Elev= 30
  4800.4  316.17  4844.6  316.06  4850.5  315.44  4871.4  316.11  4911.8  314.47
  4923.4  312.29  4933.8  307.92  4944.2  305.19  4950.6  300.05  4965.1  298.93
  4971.2  295.74  4976.3  295.74    4997  291.15  4999.8  290.65    5003  291.15
  5005.7  293.26  5015.9  294.22    5026  294.23  5036.1  296.78  5046.2  303.11
  5056.4  306.26  5062.5  308.58  5076.6  309.79  5096.9  309.71    5107  311.37
  5124.8  312.53  5137.4  312.22  5147.5  313.34  5198.1  314.48    5249  316.22
#Mann= 3 ,-1 , 0
  4800.4     .15       0    4997     .05       0    5003     .15       0
Bank Sta=4997,5003
XS Rating Curve= 0 ,0
Exp/Cntr=0.3,0.1

Type RM Length L Ch R = 1 ,3147    ,464,464,464
BEGIN DESCRIPTION:
UNT 004 IN BOCR 3.0
END DESCRIPTION:
XS GIS Cut Line= 3
      3666910.72     10603318.51      3666836.93     10603092.82
      3666728.44     10602906.21
#Sta/Elev= 30
  4839.2  312.34    4856  312.03  4879.5  312.85  4942.6  311.51  4951.7  307.11
  4956.9  305.63  4974.2  296.87  4983.5   293.1  4988.8  293.75  4995.2  288.88
    4997  288.75  4999.8  288.25    5003  288.75  5005.8  289.99  5015.4  291.97
  5020.7  288.75  5026.8  289.06  5037.3  294.31    5079  293.91  5091.3  295.63
  5120.6  297.83  5126.4  299.04  5157.9  302.71  5163.7  304.79  5172.2  305.44
  5185.2  309.57  5195.1  310.61  5206.9  313.11  5238.1  315.73  5292.5   315.7
#Mann= 3 ,-1 , 0
  4839.2     .15       0    4997     .05       0    5003     .15       0
Bank Sta=4997,5003
XS Rating Curve= 0 ,0
Exp/Cntr=0.3,0.1

Type RM Length L Ch R = 1 ,2683    ,364,364,364
BEGIN DESCRIPTION:
UNT 004 IN BOCR 2.0
END DESCRIPTION:
XS GIS Cut Line= 2
      3667344.75     10602975.63      3666897.74     10602728.26
#Sta/Elev= 30
  4745.4  308.88  4767.7  306.31    4797  305.56  4819.9  302.77  4827.2   300.1
    4849  298.08    4865  295.37  4952.1  293.48  4957.8  292.52  4968.1  294.03
  4973.8  291.62  4995.6  289.11    4997   286.7  4999.8   286.2    5003   286.7
  5017.3  287.91  5025.6     292  5048.4  294.26  5060.8  297.08  5076.9  298.72
  5082.7  303.11  5092.9  303.39  5098.6  301.58  5105.6  303.37  5120.4  303.66
  5128.4  305.31  5142.2  304.81    5196  310.87  5223.5  312.51  5256.3  312.95
#Mann= 3 ,-1 , 0
  4745.4     .15       0    4997     .05       0    5003     .15       0
Bank Sta=4997,5003
XS Rating Curve= 0 ,0
Exp/Cntr=0.3,0.1

Type RM Length L Ch R = 1 ,2319    ,1067,1067,1067
BEGIN DESCRIPTION:
Mapping XS a4283639
END DESCRIPTION:
XS GIS Cut Line= 2
      3667593.58     10602761.58      3666996.75       10602425.
#Sta/Elev= 30
  4733.6  313.22  4766.9  311.14  4772.7  311.84  4782.8  309.82  4810.2   307.3
  4841.5  306.08  4853.6  299.24  4875.9  296.99  4928.7  294.57  4934.5  293.03
  4950.4  294.07  4956.3  290.36    4972   286.8  4979.3   287.1    4997  283.96
  4999.8  283.46    5003  283.96  5009.6  287.56    5037  291.08  5117.9  292.08
  5193.1  291.11  5289.2  292.78  5311.5  294.47  5317.3  293.85  5338.9  294.73
  5346.6  296.23  5360.6     297  5376.5  300.83  5382.3  300.83  5418.8   309.3
#Mann= 3 ,-1 , 0
  4733.6     .15       0    4997     .05       0    5003     .15       0
Bank Sta=4997,5003
XS Rating Curve= 0 ,0
Exp/Cntr=0.3,0.1

Type RM Length L Ch R = 1 ,1252    ,0,0,0
BEGIN DESCRIPTION:
UNT 004 IN BOCR 1.0
END DESCRIPTION:
XS GIS Cut Line= 4
      3667704.71      10602716.5      3667794.99     10602275.49
      3667711.66     10602067.15       3667260.3     10602167.84
#Sta/Elev= 30
  4496.6  313.09  4592.8  308.09  4717.4  297.26  4744.2  297.54  4768.4  295.76
  4794.6  297.16  4845.1   296.9  4880.7  294.54  4890.4  292.28  4895.5  293.46
  4901.1  292.35  4921.5  292.52  4940.9  287.02  4945.8  287.27  4952.8  283.97
  4977.1  283.24    4997  276.49  4999.8  275.99    5003  276.49  5017.1   285.8
  5060.5   284.7  5295.5  285.89  5349.2  287.87  5357.7   286.3  5378.2  286.09
  5484.7  287.42  5528.1  293.25  5533.3  292.43  5571.6  302.91  5633.6  305.38
#Mann= 1 ,-1 , 0
  4496.6     .06       0
Bank Sta=4997,5003
XS Rating Curve= 0 ,0
Exp/Cntr=0.3,0.1

Chan Stop Cuts=-1
Use User Specified Reach Order=0
Composite Channel Slope=5