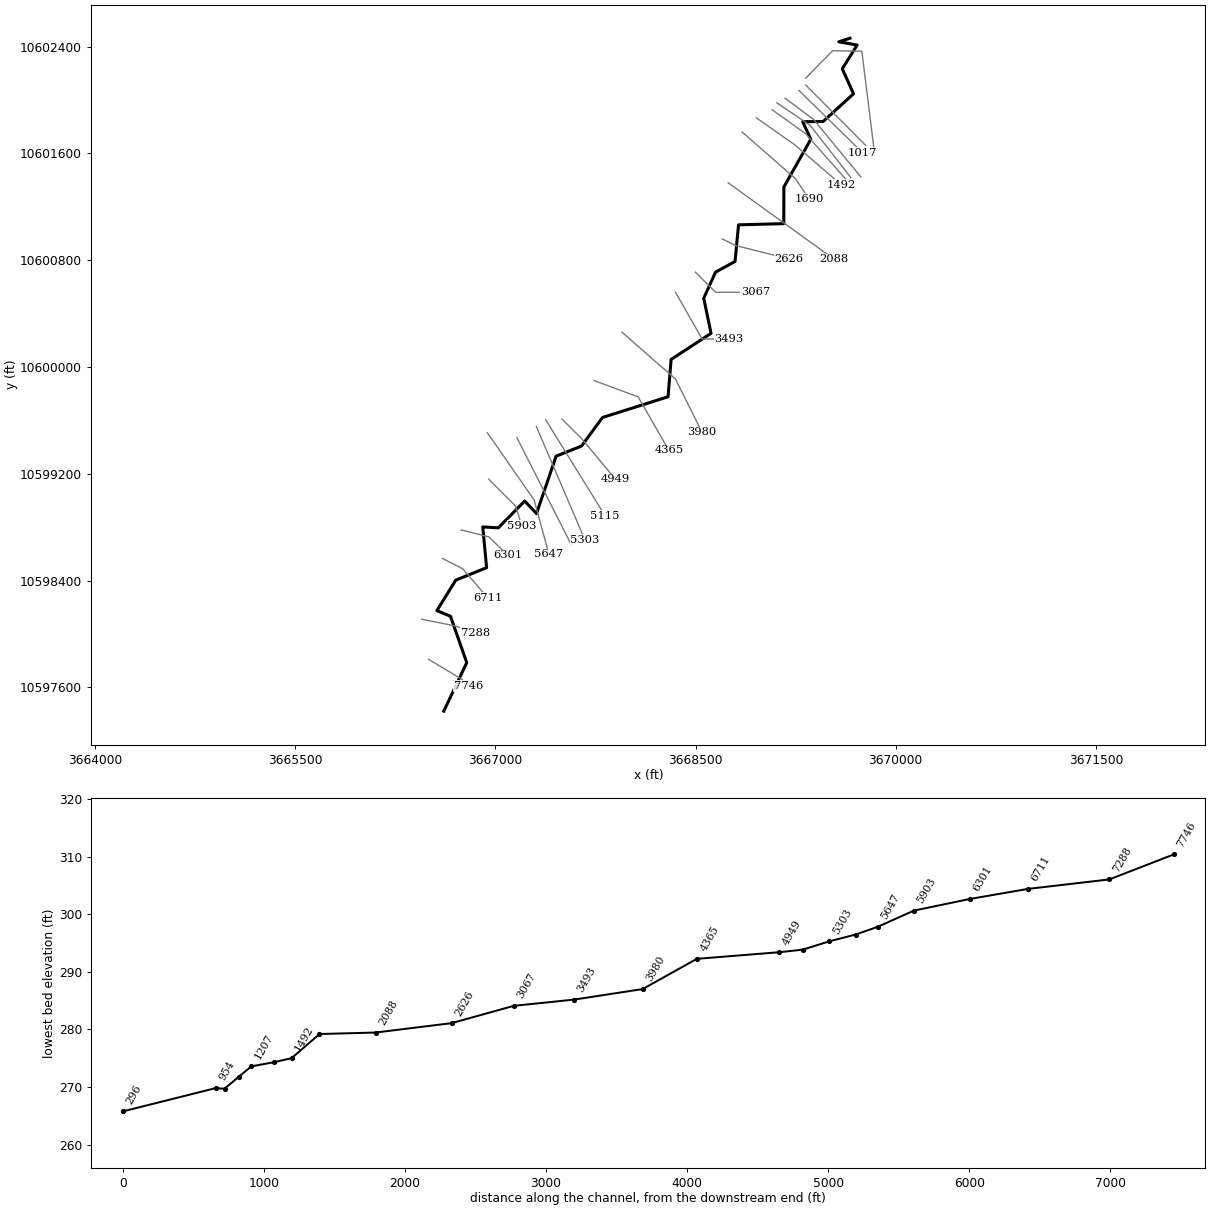
--- UNT 005 IN BOCR.prj (project) ---

Proj Title=UNT 005 IN BOCR Base Level Engineering
Current Plan=p01
Default Exp/Contr=0.3,0.1
English Units
Geom File=g01
Flow File=f01
Plan File=p01
BEGIN DESCRIPTION:
UNT 005 IN BOCR
END DESCRIPTION:

--- UNT 005 IN BOCR.p01 (plan) ---

Plan Title=Multiple Run
Short Identifier=Multiple
Geom File=g01
Flow File=f01
Subcritical Flow
K Sum by GR= 0
Std Step Tol= 0.01
Critical Tol= 0.01
Num of Std Step Trials= 20
Max Error Tol= 0.3
Flow Tol Ratio= 0.001
Split Flow NTrial= 30
Split Flow Tol= 0.02
Split Flow Ratio= 0.02
Log Output Level= 0
Friction Slope Method= 1
Unsteady Friction Slope Method= 2
Unsteady Bridges Friction Slope Method= 1
Parabolic Critical Depth
Global Vel Dist=  1 , 1 , 1
Global Log Level= 0
CheckData=True
Encroach Param= -1, 0, 0, 0
BEGIN DESCRIPTION:
Multiple Run
END DESCRIPTION:

--- UNT 005 IN BOCR.f01 (steady flow) ---

Flow Title=Multiple
Number of Profiles=7
Profile Names=10-year,25-year,50-year,1pct_min,100-year,1pct_plu,500-year
River Rch & RM= UNT 005 IN BOCR,Reach-1,7746
     393     516     614     536     726     981    1018
River Rch & RM= UNT 005 IN BOCR,Reach-1,5490
     531     709     854     755    1021    1381    1466
Boundary for River Rch & Prof#=UNT 005 IN BOCR,Reach-1,1
Up Type=0
Dn Type=3
Dn Slope=0.005
Boundary for River Rch & Prof#=UNT 005 IN BOCR,Reach-1,2
Up Type=0
Dn Type=3
Dn Slope=0.005
Boundary for River Rch & Prof#=UNT 005 IN BOCR,Reach-1,3
Up Type=0
Dn Type=3
Dn Slope=0.005
Boundary for River Rch & Prof#=UNT 005 IN BOCR,Reach-1,4
Up Type=0
Dn Type=3
Dn Slope=0.005
Boundary for River Rch & Prof#=UNT 005 IN BOCR,Reach-1,5
Up Type=0
Dn Type=3
Dn Slope=0.005
Boundary for River Rch & Prof#=UNT 005 IN BOCR,Reach-1,6
Up Type=0
Dn Type=3
Dn Slope=0.005
Boundary for River Rch & Prof#=UNT 005 IN BOCR,Reach-1,7
Up Type=0
Dn Type=3
Dn Slope=0.005

--- UNT 005 IN BOCR.g01 (geometry) ---

Geom Title=Existing Conditions

River Reach=UNT 005 IN BOCR,Reach-1
Reach XY= 30
      3666613.50     10597422.00      3666785.75     10597785.00
      3666663.75     10598133.00      3666562.00     10598175.00
      3666703.00     10598403.00      3666934.50     10598497.00
      3666905.75     10598802.00      3667022.00     10598795.00
      3667220.00     10598996.00      3667308.50     10598902.00
      3667455.25     10599332.00      3667646.00     10599408.00
      3667803.25     10599622.00      3668294.25     10599777.00
      3668317.25     10600057.00      3668616.50     10600252.00
      3668561.50     10600515.00      3668649.75     10600710.00
      3668796.25     10600791.00      3668822.50     10601065.00
      3669161.50     10601074.00      3669162.25     10601349.00
      3669363.75     10601706.00      3669303.25     10601838.00
      3669456.00     10601839.00      3669684.25     10602047.00
      3669599.75     10602234.00      3669711.50     10602412.00
      3669573.50     10602436.00      3669657.25     10602463.00

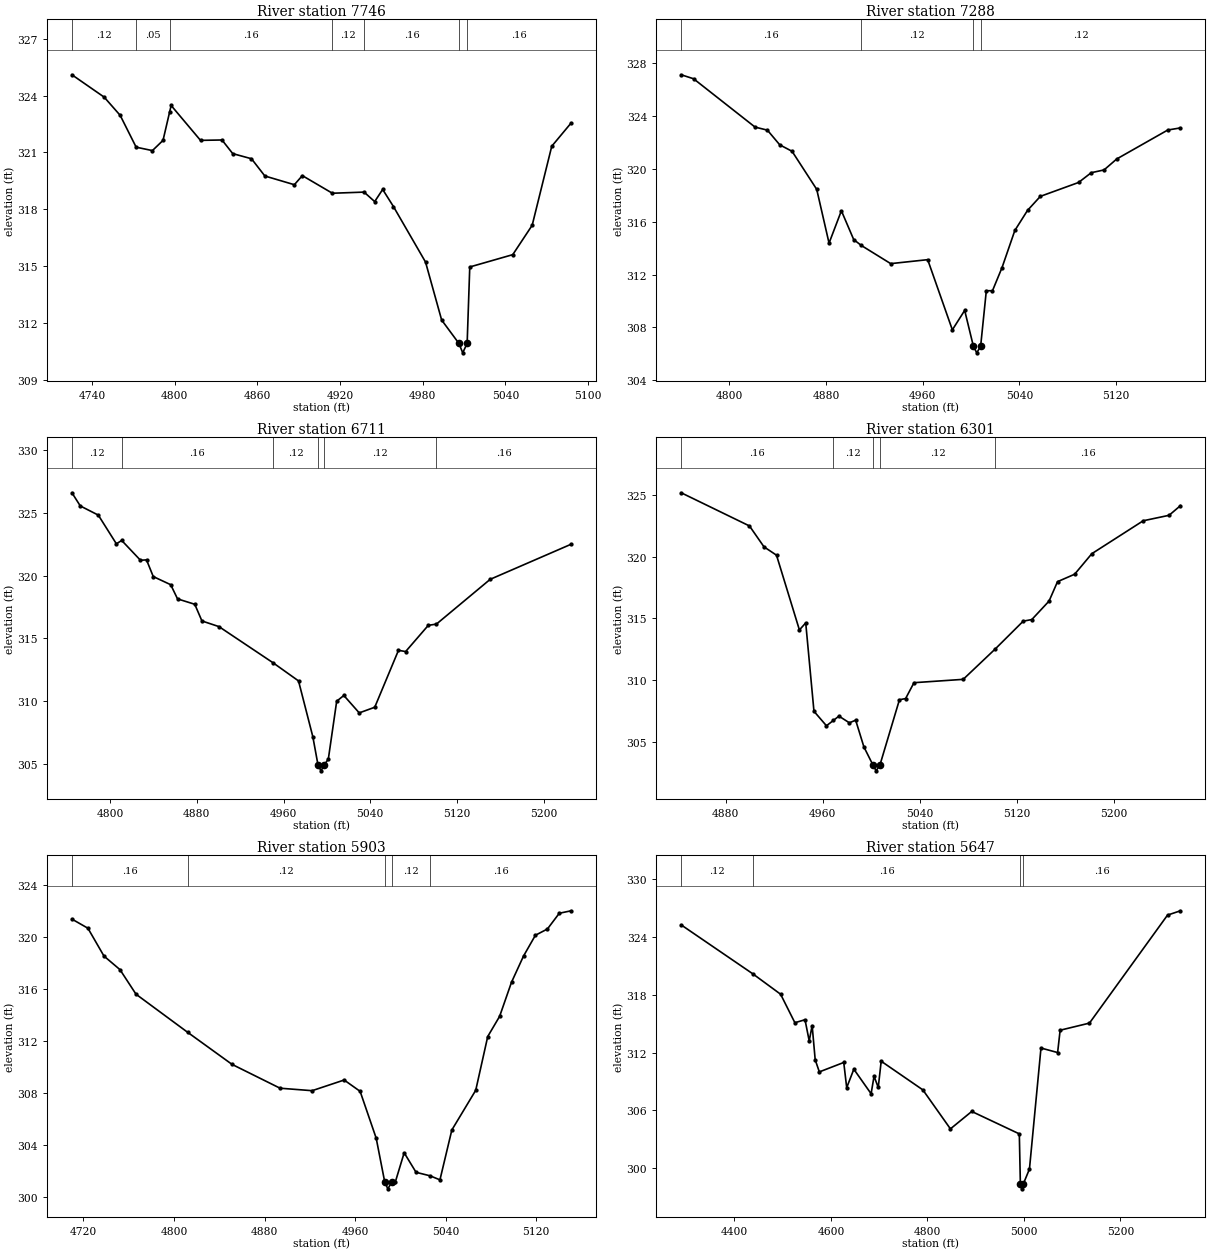
Type RM Length L Ch R = 1,7746,458,458,458
BEGIN DESCRIPTION:
UNT 005 IN BOCR 16.0
END DESCRIPTION:
XS GIS Cut Line= 3
      3666499.57     10597810.21      3666749.61     10597660.19
      3666799.60     10597610.19
#Sta/Elev= 30
  4725.5  325.10  4748.9  323.92  4760.5  322.96  4772.1  321.28  4783.9  321.10
  4791.6  321.64  4796.4  323.14  4797.5  323.48  4818.8  321.64  4834.4  321.66
  4842.2  320.94  4855.8  320.67  4865.5  319.76  4886.9  319.30  4892.7  319.78
  4914.5  318.85  4937.5  318.91  4945.2  318.41  4951.0  319.05  4958.8  318.15
  4982.1  315.22  4993.8  312.16  5006.3  310.93  5009.1  310.43  5012.3  310.93
  5014.2  314.96  5045.4  315.61  5059.5  317.16  5073.7  321.33  5087.8  322.56
#Mann=7,-1,0
  4725.5    0.12       0  4772.1    0.05       0  4796.4    0.16       0
  4914.5    0.12       0  4937.5    0.16       0  5006.3    0.07       0
  5012.3    0.16       0
Bank Sta=5006.3,5012.3
Exp/Cntr=0.3,0.1

Type RM Length L Ch R = 1,7288,577,577,577
BEGIN DESCRIPTION:
UNT 005 IN BOCR 15.0
END DESCRIPTION:
XS GIS Cut Line= 3
      3666449.65     10598110.18      3666699.61     10598060.19
      3666849.59     10598010.19
#Sta/Elev= 30
  4760.3  327.12  4770.5  326.82  4821.4  323.16  4831.6  322.93  4841.8  321.82
  4852.0  321.33  4872.4  318.45  4882.6  314.38  4892.8  316.83  4903.0  314.65
  4909.2  314.21  4933.6  312.83  4964.2  313.13  4984.6  307.82  4994.8  309.29
  5002.0  306.58  5004.8  306.08  5008.0  306.58  5012.7  310.78  5017.8  310.78
  5025.7  312.53  5036.3  315.34  5046.8  316.86  5057.4  317.92  5089.0  318.97
  5099.5  319.71  5110.1  319.92  5120.6  320.75  5162.8  322.94  5173.3  323.10
#Mann=4,-1,0
  4760.3    0.16       0  4909.2    0.12       0  5002.0    0.07       0
  5008.0    0.12       0
Bank Sta=5002,5008
Exp/Cntr=0.3,0.1

Type RM Length L Ch R = 1,6711,410,410,410
BEGIN DESCRIPTION:
UNT 005 IN BOCR 14.0
END DESCRIPTION:
XS GIS Cut Line= 3
      3666602.77     10598566.13      3666756.42     10598488.00
      3666943.93     10598269.24
#Sta/Elev= 30
  4764.8  326.60  4772.5  325.55  4789.1  324.82  4805.8  322.53  4810.7  322.80
  4828.0  321.22  4833.6  321.25  4839.8  319.92  4855.9  319.27  4862.2  318.14
  4878.1  317.71  4884.7  316.38  4900.4  315.93  4950.4  313.04  4973.8  311.60
  4987.0  307.15  4991.7  304.93  4994.5  304.43  4997.7  304.93  5001.3  305.37
  5009.0  309.98  5015.6  310.44  5029.8  309.05  5044.1  309.50  5066.0  314.04
  5072.6  313.94  5093.5  316.03  5101.0  316.13  5150.6  319.70  5225.3  322.50
#Mann=6,-1,0
  4764.8    0.12       0  4810.7    0.16       0  4950.4    0.12       0
  4991.7    0.07       0  4997.7    0.12       0  5101.0    0.16       0
Bank Sta=4991.7,4997.7
Exp/Cntr=0.3,0.1

Type RM Length L Ch R = 1,6301,398,398,398
BEGIN DESCRIPTION:
UNT 005 IN BOCR 13.0
END DESCRIPTION:
XS GIS Cut Line= 3
      3666743.37     10598779.67      3666951.73     10598727.58
      3667092.35     10598589.57
#Sta/Elev= 30
  4843.3  325.15  4899.6  322.47  4911.6  320.78  4921.9  320.11  4940.8  314.07
  4946.0  314.64  4952.8  307.50  4963.1  306.33  4968.8  306.76  4973.4  307.11
  4982.0  306.57  4987.2  306.78  4994.0  304.62  5001.3  303.19  5004.1  302.69
  5007.3  303.19  5023.3  308.43  5028.4  308.53  5035.3  309.81  5075.9  310.08
  5102.5  312.55  5125.4  314.78  5132.5  314.91  5146.7  316.40  5153.7  317.97
  5167.8  318.57  5182.0  320.23  5224.4  322.89  5245.7  323.33  5255.1  324.11
#Mann=5,-1,0
  4843.3    0.16       0  4968.8    0.12       0  5001.3    0.07       0
  5007.3    0.12       0  5102.5    0.16       0
Bank Sta=5001.3,5007.3
Exp/Cntr=0.3,0.1

Type RM Length L Ch R = 1,5903,256,256,256
BEGIN DESCRIPTION:
UNT 005 IN BOCR 12.0
END DESCRIPTION:
XS GIS Cut Line= 3
      3666949.62     10599160.18      3667149.61     10598960.19
      3667199.59     10598810.23
#Sta/Elev= 30
  4709.9  321.38  4724.0  320.68  4738.2  318.54  4752.3  317.50  4766.5  315.61
  4812.0  312.69  4851.3  310.22  4893.7  308.39  4922.0  308.20  4950.3  309.02
  4964.4  308.15  4978.6  304.55  4986.2  301.16  4988.9  300.66  4992.2  301.16
  4995.4  301.16  5003.3  303.43  5013.8  301.93  5026.2  301.66  5034.9  301.35
  5045.4  305.18  5066.5  308.23  5077.1  312.36  5087.6  313.91  5098.1  316.53
  5108.7  318.54  5119.2  320.14  5129.8  320.62  5140.3  321.83  5150.8  322.02
#Mann=5,-1,0
  4709.9    0.16       0  4812.0    0.12       0  4986.2    0.07       0
  4992.2    0.12       0  5026.2    0.16       0
Bank Sta=4986.2,4992.2
Exp/Cntr=0.3,0.1

Type RM Length L Ch R = 1,5647,157,157,157
BEGIN DESCRIPTION:
Mapping XS 436f42b7
END DESCRIPTION:
XS GIS Cut Line= 3
      3666939.59     10599508.07      3667290.30     10599004.57
      3667401.42     10598598.30
#Sta/Elev= 30
  4289.7  325.27  4437.8  320.20  4495.7  318.07  4525.3  315.11  4546.3  315.42
  4555.0  313.22  4561.1  314.81  4567.4  311.26  4576.0  310.00  4626.6  310.98
  4632.7  308.36  4647.5  310.28  4683.3  307.73  4689.4  309.55  4698.1  308.38
  4704.2  311.11  4790.6  308.13  4847.7  304.08  4891.9  305.89  4990.5  303.56
  4992.7  298.35  4995.5  297.85  4998.7  298.35  5011.5  299.90  5035.4  312.48
  5069.9  312.01  5075.1  314.33  5135.9  315.07  5297.7  326.29  5324.5  326.74
#Mann=4,-1,0
  4289.7    0.12       0  4437.8    0.16       0  4992.7    0.07       0
  4998.7    0.16       0
Bank Sta=4992.7,4998.7
Exp/Cntr=0.3,0.1

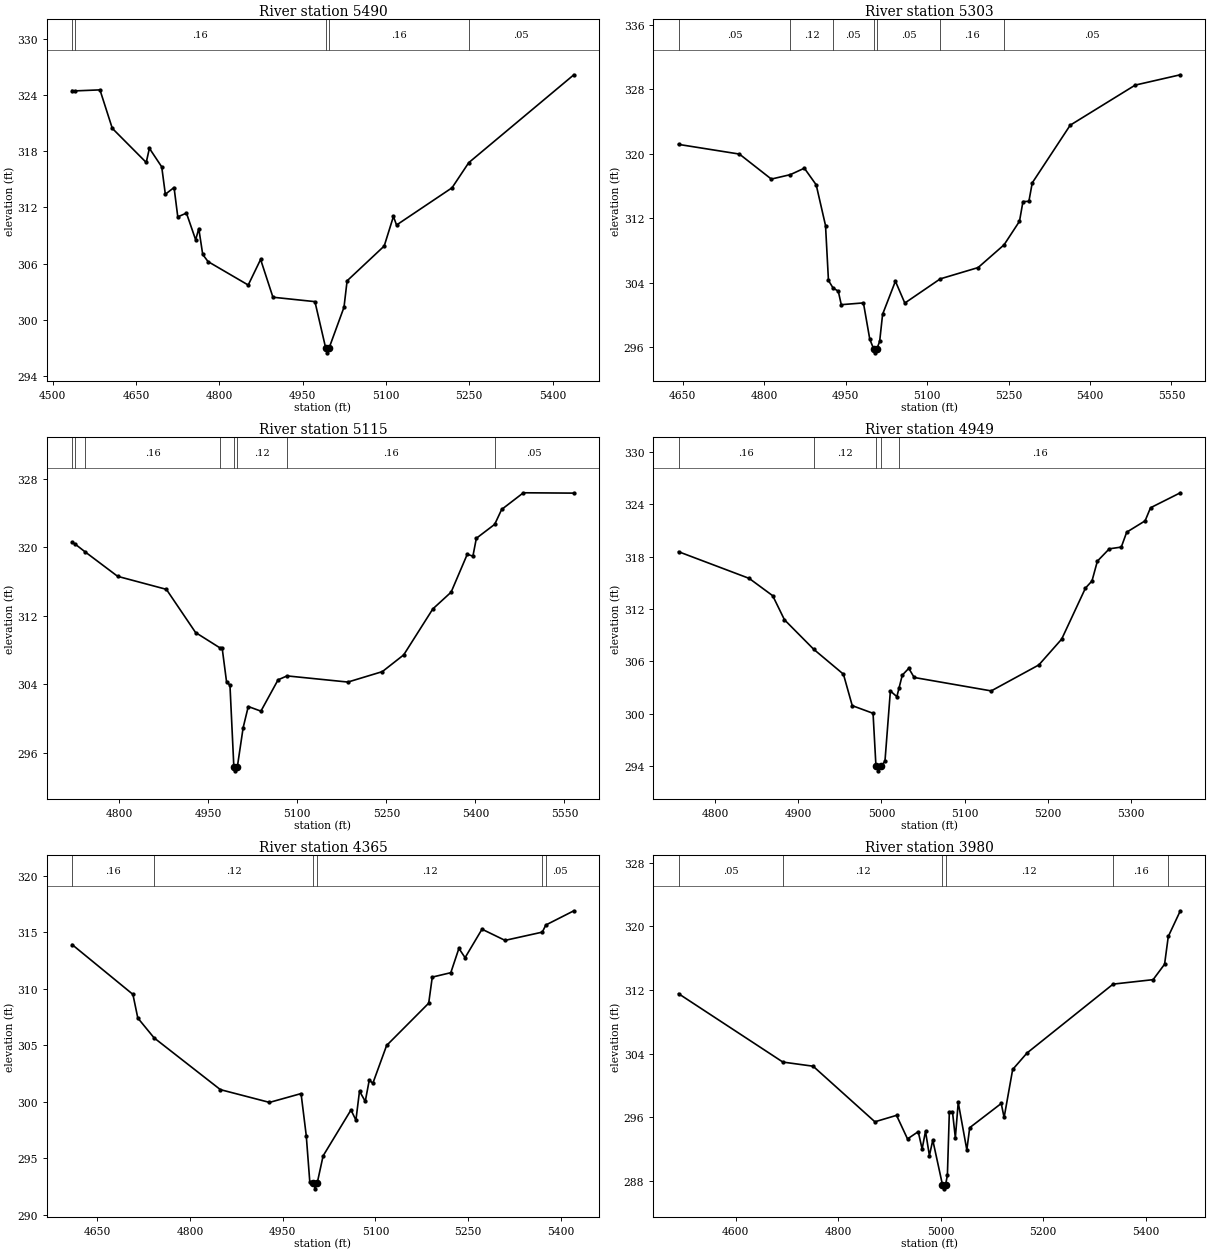
Type RM Length L Ch R = 1,5490,187,187,187
BEGIN DESCRIPTION:
UNT 005 IN BOCR 11.0
END DESCRIPTION:
XS GIS Cut Line= 2
      3667161.84     10599469.84      3667571.35     10598664.69
#Sta/Elev= 30
  4535.1  324.47  4539.6  324.43  4585.3  324.54  4607.5  320.44  4668.6  316.80
  4674.3  318.31  4696.5  316.33  4703.0  313.41  4718.7  314.13  4725.4  311.00
  4741.0  311.40  4757.6  308.55  4763.2  309.75  4770.3  306.99  4779.9  306.23
  4852.2  303.73  4874.5  306.46  4896.7  302.43  4972.3  301.96  4991.7  297.00
  4994.4  296.50  4997.7  297.00  5024.6  301.36  5030.2  304.18  5097.0  307.89
  5113.6  311.04  5119.2  310.13  5219.1  314.10  5249.2  316.78  5438.4  326.15
#Mann=5,-1,0
  4535.1    0.12       0  4539.6    0.16       0  4991.7    0.07       0
  4997.7    0.16       0  5249.2    0.05       0
Bank Sta=4991.7,4997.7
Exp/Cntr=0.3,0.1

Type RM Length L Ch R = 1,5303,188,188,188
BEGIN DESCRIPTION:
Mapping XS 744f2e69
END DESCRIPTION:
XS GIS Cut Line= 2
      3667307.66     10599553.18      3667671.68     10598703.80
#Sta/Elev= 30
  4642.3  321.16  4754.4  319.96  4813.2  316.86  4848.2  317.41  4874.0  318.21
  4895.8  316.15  4913.0  311.10  4918.4  304.29  4926.9  303.36  4936.5  302.96
  4942.0  301.29  4982.8  301.51  4994.5  297.01  5001.6  295.82  5004.3  295.32
  5007.6  295.82  5012.7  296.74  5018.1  300.10  5041.7  304.20  5059.0  301.49
  5124.3  304.49  5194.0  305.89  5241.8  308.71  5270.2  311.63  5276.6  314.07
  5287.5  314.10  5293.7  316.39  5363.6  323.54  5483.3  328.51  5566.4  329.79
#Mann=7,-1,0
  4642.3    0.05       0  4848.2    0.12       0  4926.9    0.05       0
  5001.6    0.04       0  5007.6    0.05       0  5124.3    0.16       0
  5241.8    0.05       0
Bank Sta=5001.6,5007.6
Exp/Cntr=0.3,0.1

Type RM Length L Ch R = 1,5115,166,166,166
BEGIN DESCRIPTION:
Mapping XS 0cffc890
END DESCRIPTION:
XS GIS Cut Line= 2
      3667377.13     10599605.23      3667821.54     10598886.53
#Sta/Elev= 30
  4720.8  320.59  4725.4  320.41  4743.0  319.46  4797.6  316.61  4879.6  315.09
  4928.8  310.04  4970.2  308.23  4973.6  308.20  4980.9  304.30  4986.7  303.86
  4993.2  294.37  4996.0  293.87  4999.2  294.37  5008.9  298.92  5017.5  301.39
  5038.8  300.85  5067.7  304.51  5082.8  304.97  5185.3  304.25  5243.3  305.47
  5279.3  307.43  5328.3  312.80  5359.1  314.76  5386.3  319.19  5395.8  318.97
  5401.6  321.06  5432.5  322.69  5444.2  324.43  5480.8  326.38  5565.8  326.34
#Mann=8,-1,0
  4720.8    0.16       0  4725.4    0.05       0  4743.0    0.16       0
  4970.2    0.12       0  4993.2    0.07       0  4999.2    0.12       0
  5082.8    0.16       0  5432.5    0.05       0
Bank Sta=4993.2,4999.2
Exp/Cntr=0.3,0.1

Type RM Length L Ch R = 1,4949,584,584,584
BEGIN DESCRIPTION:
UNT 005 IN BOCR 10.0
END DESCRIPTION:
XS GIS Cut Line= 3
      3667499.63     10599610.16      3667649.61     10599460.19
      3667899.60     10599160.20
#Sta/Elev= 30
  4756.3  318.57  4841.1  315.51  4869.4  313.52  4883.5  310.76  4918.7  307.37
  4954.3  304.52  4964.9  300.91  4989.9  300.03  4993.4  293.93  4996.1  293.43
  4999.4  293.93  5004.2  294.53  5010.7  302.59  5018.5  301.94  5021.1  302.93
  5025.0  304.41  5032.8  305.19  5039.3  304.14  5131.8  302.60  5189.0  305.58
  5216.4  308.54  5245.0  314.40  5252.8  315.21  5259.3  317.49  5273.6  318.90
  5288.0  319.10  5294.5  320.81  5316.6  322.11  5323.1  323.61  5358.9  325.33
#Mann=5,-1,0
  4756.3    0.16       0  4918.7    0.12       0  4993.4    0.07       0
  4999.4    0.12       0  5021.1    0.16       0
Bank Sta=4993.4,4999.4
Exp/Cntr=0.3,0.1

Type RM Length L Ch R = 1,4365,385,385,385
BEGIN DESCRIPTION:
UNT 005 IN BOCR 9.0
END DESCRIPTION:
XS GIS Cut Line= 3
      3667739.72     10599898.37      3668069.57     10599776.85
      3668299.58     10599377.58
#Sta/Elev= 30
  4609.0  313.90  4707.5  309.49  4715.4  307.40  4741.8  305.64  4849.1  301.06
  4928.6  299.93  4979.7  300.71  4988.1  296.99  4993.9  292.85  4999.8  292.78
  5002.6  292.28  5005.8  292.78  5015.4  295.20  5060.5  299.26  5068.5  298.36
  5074.3  300.93  5083.6  300.02  5090.1  301.90  5095.9  301.62  5118.2  304.97
  5186.3  308.71  5192.1  311.02  5222.1  311.41  5235.2  313.56  5245.2  312.74
  5272.6  315.26  5309.9  314.27  5370.2  315.00  5375.9  315.63  5421.3  316.89
#Mann=6,-1,0
  4609.0    0.16       0  4741.8    0.12       0  4999.8    0.07       0
  5005.8    0.12       0  5370.2    0.07       0  5375.9    0.05       0
Bank Sta=4999.8,5005.8
Exp/Cntr=0.3,0.1

Type RM Length L Ch R = 1,3980,487,487,487
BEGIN DESCRIPTION:
UNT 005 IN BOCR 8.0
END DESCRIPTION:
XS GIS Cut Line= 3
      3667949.59     10600260.21      3668349.61     10599910.19
      3668549.59     10599510.23
#Sta/Elev= 30
  4488.7  311.53  4692.2  302.94  4751.2  302.42  4871.7  295.44  4913.9  296.25
  4935.3  293.29  4956.2  294.20  4963.8  292.03  4970.4  294.25  4978.0  291.19
  4984.6  293.14  5003.5  287.52  5006.2  287.02  5009.5  287.52  5013.1  288.74
  5016.9  296.70  5023.0  296.70  5028.6  293.43  5034.2  297.88  5051.0  291.91
  5056.6  294.70  5118.1  297.74  5123.7  295.98  5140.4  302.01  5168.4  304.08
  5336.3  312.73  5414.3  313.29  5436.7  315.23  5443.9  318.71  5467.4  321.94
#Mann=6,-1,0
  4488.7    0.05       0  4692.2    0.12       0  5003.5    0.07       0
  5009.5    0.12       0  5336.3    0.16       0  5443.9    0.05       0
Bank Sta=5003.5,5009.5
Exp/Cntr=0.3,0.1

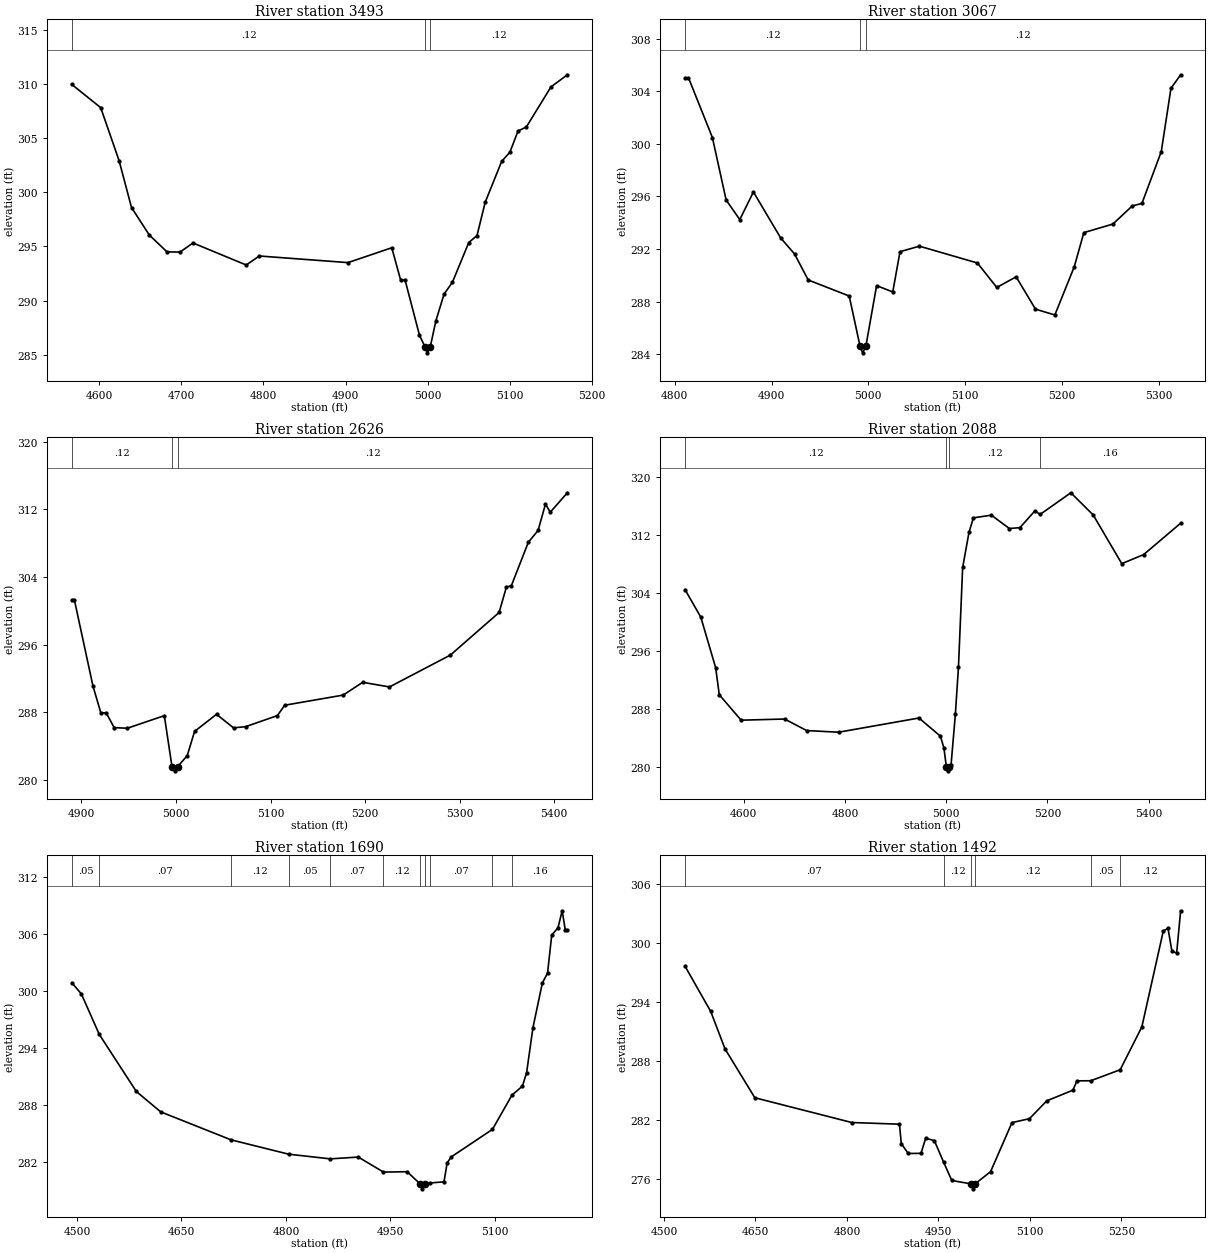
Type RM Length L Ch R = 1,3493,426,426,426
BEGIN DESCRIPTION:
UNT 005 IN BOCR 7.0
END DESCRIPTION:
XS GIS Cut Line= 3
      3668349.63     10600560.16      3668549.61     10600210.19
      3668749.63     10600210.19
#Sta/Elev= 30
  4566.9  309.94  4602.1  307.80  4624.5  302.91  4639.6  298.59  4661.2  296.06
  4682.8  294.50  4698.6  294.48  4714.4  295.32  4779.2  293.29  4795.1  294.12
  4903.0  293.51  4956.3  294.88  4967.1  291.90  4972.5  291.90  4990.0  286.82
  4997.0  285.69  4999.7  285.19  5003.0  285.69  5010.0  288.15  5020.0  290.62
  5030.0  291.68  5050.0  295.36  5060.0  296.00  5070.0  299.08  5090.0  302.84
  5100.0  303.69  5110.0  305.65  5120.0  306.01  5150.0  309.71  5170.0  310.83
#Mann=3,-1,0
  4566.9    0.12       0  4997.0    0.07       0  5003.0    0.12       0
Bank Sta=4997,5003
Exp/Cntr=0.3,0.1

Type RM Length L Ch R = 1,3067,441,441,441
BEGIN DESCRIPTION:
UNT 005 IN BOCR 6.0
END DESCRIPTION:
XS GIS Cut Line= 3
      3668499.59     10600710.21      3668649.61     10600560.19
      3668949.64     10600560.19
#Sta/Elev= 30
  4810.6  305.02  4814.2  305.02  4838.9  300.48  4853.1  295.73  4867.2  294.24
  4881.3  296.34  4909.6  292.83  4923.8  291.63  4937.9  289.65  4980.3  288.43
  4991.5  284.61  4994.2  284.11  4997.5  284.61  5008.6  289.22  5025.3  288.74
  5032.8  291.80  5052.8  292.22  5112.8  290.94  5132.8  289.08  5152.8  289.89
  5172.8  287.43  5192.8  286.99  5212.8  290.64  5222.8  293.25  5252.8  293.90
  5272.8  295.28  5282.8  295.47  5302.8  299.41  5312.8  304.22  5322.8  305.25
#Mann=3,-1,0
  4810.6    0.12       0  4991.5    0.07       0  4997.5    0.12       0
Bank Sta=4991.5,4997.5
Exp/Cntr=0.3,0.1

Type RM Length L Ch R = 1,2626,538,538,538
BEGIN DESCRIPTION:
UNT 005 IN BOCR 5.0
END DESCRIPTION:
XS GIS Cut Line= 3
      3668699.58     10600960.21      3668799.61     10600910.19
      3669199.66     10600810.18
#Sta/Elev= 30
  4889.7  301.28  4892.5  301.28  4912.1  291.13  4920.5  287.93  4926.1  287.96
  4934.5  286.21  4948.4  286.13  4987.6  287.62  4995.7  281.60  4998.5  281.10
  5001.7  281.60  5011.8  282.89  5019.6  285.76  5042.8  287.78  5060.8  286.18
  5073.7  286.32  5107.2  287.63  5114.9  288.85  5176.8  290.05  5197.4  291.56
  5225.7  291.01  5290.2  294.78  5341.7  299.81  5349.4  302.82  5354.6  302.96
  5372.6  308.10  5382.9  309.50  5390.7  312.61  5395.8  311.66  5413.9  313.95
#Mann=3,-1,0
  4889.7    0.12       0  4995.7    0.07       0  5001.7    0.12       0
Bank Sta=4995.7,5001.7
Exp/Cntr=0.3,0.1

Type RM Length L Ch R = 1,2088,398,398,398
BEGIN DESCRIPTION:
UNT 005 IN BOCR 4.0
END DESCRIPTION:
XS GIS Cut Line= 2
      3668744.68     10601380.06      3669538.93     10600807.16
#Sta/Elev= 30
  4484.1  304.48  4515.3  300.68  4544.7  293.69  4551.8  289.97  4595.0  286.46
  4680.9  286.62  4724.4  285.03  4787.6  284.80  4946.4  286.76  4988.8  284.25
  4995.7  282.61  5000.6  279.97  5003.3  279.47  5006.6  279.97  5009.7  280.22
  5018.3  287.27  5024.4  293.77  5032.7  307.54  5045.3  312.40  5053.9  314.38
  5089.4  314.75  5125.0  312.91  5145.9  313.03  5175.3  315.33  5185.9  314.86
  5246.5  317.84  5290.6  314.78  5347.1  308.06  5390.3  309.31  5463.4  313.64
#Mann=4,-1,0
  4484.1    0.12       0  5000.6    0.07       0  5006.6    0.12       0
  5185.9    0.16       0
Bank Sta=5000.6,5006.6
Exp/Cntr=0.3,0.1

Type RM Length L Ch R = 1,1690,198,198,198
BEGIN DESCRIPTION:
UNT 005 IN BOCR 3.0
END DESCRIPTION:
XS GIS Cut Line= 3
      3668849.57     10601760.22      3669249.61     10601410.19
      3669349.59     10601260.21
#Sta/Elev= 30
  4492.4  300.88  4506.2  299.69  4531.9  295.44  4585.0  289.45  4620.1  287.30
  4721.1  284.36  4804.0  282.85  4863.7  282.36  4903.9  282.55  4940.1  280.97
  4974.1  281.01  4993.0  279.71  4995.7  279.21  4999.0  279.71  5006.3  279.82
  5027.0  279.95  5031.5  281.94  5037.5  282.57  5096.6  285.46  5124.6  289.06
  5139.6  290.00  5145.6  291.40  5154.7  296.13  5168.2  300.83  5175.7  301.88
  5181.7  305.87  5190.7  306.64  5196.7  308.43  5201.2  306.41  5204.2  306.41
#Mann=11,-1,0
  4492.4    0.05       0  4531.9    0.07       0  4721.1    0.12       0
  4804.0    0.05       0  4863.7    0.07       0  4940.1    0.12       0
  4993.0    0.07       0  4999.0    0.12       0  5006.3    0.07       0
  5096.6    0.05       0  5124.6    0.16       0
Bank Sta=4993,4999
Exp/Cntr=0.3,0.1

Type RM Length L Ch R = 1,1492,121,121,121
BEGIN DESCRIPTION:
Mapping XS 1bcbdac9
END DESCRIPTION:
XS GIS Cut Line= 3
      3668955.92     10601866.56      3669247.58     10601661.70
      3669593.45     10601364.25
#Sta/Elev= 30
  4534.5  297.67  4576.7  293.06  4600.1  289.25  4649.0  284.28  4807.9  281.76
  4886.1  281.59  4889.1  279.61  4900.5  278.61  4921.4  278.62  4929.1  280.16
  4943.3  279.92  4958.6  277.71  4971.9  275.86  5004.0  275.51  5006.7  275.01
  5010.0  275.51  5035.5  276.76  5070.6  281.75  5099.2  282.15  5127.7  283.97
  5170.5  285.05  5177.1  286.00  5199.7  286.01  5248.0  287.13  5283.5  291.49
  5318.6  301.23  5326.3  301.54  5332.9  299.17  5340.6  299.02  5347.1  303.31
#Mann=6,-1,0
  4534.5    0.07       0  4958.6    0.12       0  5004.0    0.07       0
  5010.0    0.12       0  5199.7    0.05       0  5248.0    0.12       0
Bank Sta=5004,5010
Exp/Cntr=0.3,0.1

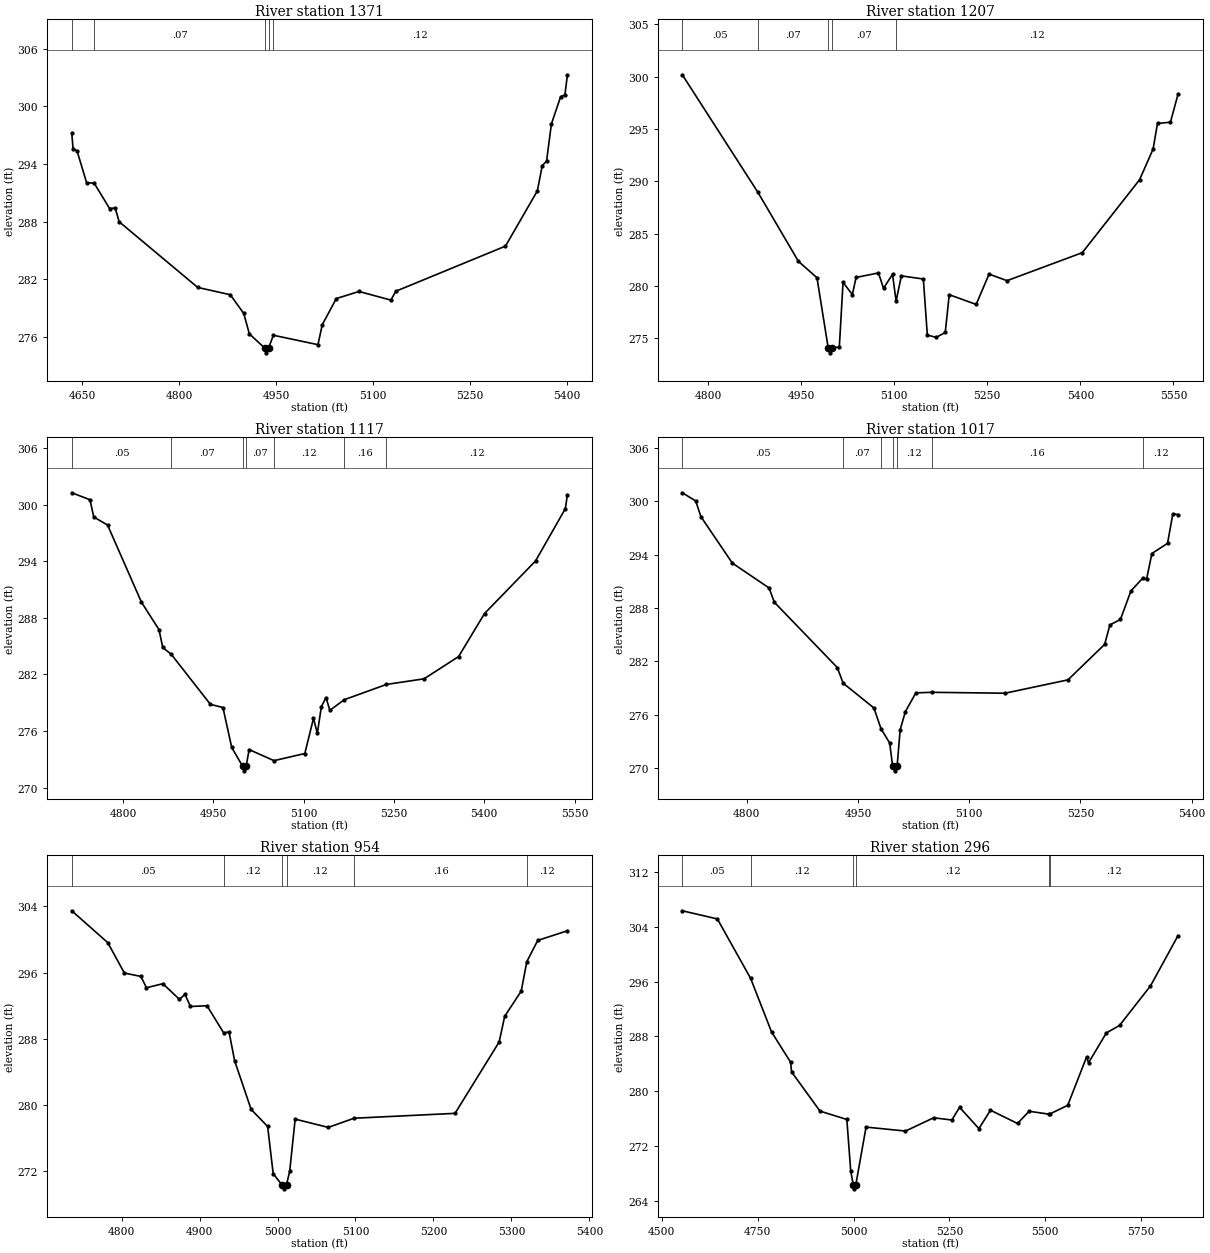
Type RM Length L Ch R = 1,1371,164,164,164
BEGIN DESCRIPTION:
Mapping XS b324f241
END DESCRIPTION:
XS GIS Cut Line= 3
      3669074.14     10601927.23      3669324.13     10601748.42
      3669628.71     10601404.04
#Sta/Elev= 30
  4633.5  297.21  4635.5  295.58  4641.7  295.35  4656.4  292.06  4668.3  291.98
  4692.1  289.35  4700.7  289.42  4706.8  287.98  4828.4  281.14  4878.8  280.38
  4899.7  278.43  4908.3  276.31  4932.0  274.83  4934.8  274.33  4938.0  274.83
  4945.6  276.16  5014.5  275.18  5021.2  277.26  5042.9  279.98  5078.0  280.72
  5127.4  279.82  5134.9  280.74  5304.7  285.44  5354.1  291.20  5361.6  293.82
  5368.3  294.29  5375.8  298.16  5390.1  301.00  5396.7  301.19  5400.6  303.28
#Mann=5,-1,0
  4633.5    0.05       0  4668.3    0.07       0  4932.0    0.07       0
  4938.0    0.07       0  4945.6    0.12       0
Bank Sta=4932,4938
Exp/Cntr=0.3,0.1

Type RM Length L Ch R = 1,1207,90,90,90
BEGIN DESCRIPTION:
Mapping XS 5d848a17
END DESCRIPTION:
XS GIS Cut Line= 3
      3669108.87     10601979.31      3669358.85     10601810.92
      3669664.40     10601418.56
#Sta/Elev= 30
  4758.6  300.18  4880.5  288.93  4945.7  282.34  4975.6  280.77  4993.6  274.09
  4996.4  273.59  4999.6  274.09  5011.6  274.13  5017.6  280.33  5032.6  279.16
  5038.6  280.80  5074.7  281.23  5082.8  279.76  5097.3  281.10  5103.1  278.54
  5111.6  280.95  5147.0  280.65  5153.4  275.29  5167.8  275.07  5182.3  275.54
  5188.7  279.15  5232.1  278.22  5252.9  281.12  5281.8  280.49  5403.1  283.17
  5495.4  290.14  5517.2  293.08  5524.3  295.53  5545.1  295.64  5557.3  298.30
#Mann=5,-1,0
  4758.6    0.05       0  4880.5    0.07       0  4993.6    0.07       0
  4999.6    0.07       0  5103.1    0.12       0
Bank Sta=4993.6,4999.6
Exp/Cntr=0.3,0.1

Type RM Length L Ch R = 1,1117,100,100,100
BEGIN DESCRIPTION:
UNT 005 IN BOCR 2.0
END DESCRIPTION:
XS GIS Cut Line= 3
      3669171.32     10602014.07      3669386.63     10601852.58
      3669738.49     10601424.46
#Sta/Elev= 30
  4714.8  301.29  4745.1  300.55  4751.3  298.72  4774.3  297.86  4830.5  289.68
  4859.7  286.76  4865.9  284.87  4880.2  284.13  4945.1  278.83  4965.9  278.49
  4980.5  274.25  4998.5  272.27  5001.2  271.77  5004.5  272.27  5009.4  274.03
  5050.7  272.85  5101.9  273.61  5116.3  277.34  5122.7  275.75  5129.4  278.58
  5137.1  279.55  5143.5  278.19  5167.4  279.32  5237.3  280.94  5300.0  281.54
  5357.3  283.90  5400.4  288.47  5485.1  294.05  5534.6  299.60  5538.1  301.08
#Mann=7,-1,0
  4714.8    0.05       0  4880.2    0.07       0  4998.5    0.07       0
  5004.5    0.07       0  5050.7    0.12       0  5167.4    0.16       0
  5237.3    0.12       0
Bank Sta=4998.5,5004.5
Exp/Cntr=0.3,0.1

Type RM Length L Ch R = 1,1017,63,63,63
BEGIN DESCRIPTION:
Mapping XS 3175f9ed
END DESCRIPTION:
XS GIS Cut Line= 2
      3669275.36     10602071.43      3669753.22     10601603.95
#Sta/Elev= 30
  4713.0  300.97  4731.1  300.05  4738.1  298.28  4780.5  293.06  4830.1  290.26
  4837.1  288.66  4922.0  281.32  4929.9  279.56  4971.4  276.77  4981.1  274.41
  4992.7  272.83  4996.7  270.20  4999.4  269.70  5002.7  270.20  5006.8  274.31
  5013.8  276.35  5028.0  278.47  5049.1  278.53  5148.3  278.43  5233.1  279.93
  5282.6  283.92  5289.7  286.11  5303.9  286.72  5318.0  289.93  5334.2  291.39
  5339.1  291.23  5346.3  294.14  5367.4  295.28  5374.6  298.61  5381.5  298.51
#Mann=7,-1,0
  4713.0    0.05       0  4929.9    0.07       0  4981.1    0.12       0
  4996.7    0.07       0  5002.7    0.12       0  5049.1    0.16       0
  5334.2    0.12       0
Bank Sta=4996.7,5002.7
Exp/Cntr=0.3,0.1

Type RM Length L Ch R = 1,954,658,658,658
BEGIN DESCRIPTION:
Mapping XS 7736ffa6
END DESCRIPTION:
XS GIS Cut Line= 2
      3669326.28     10602112.26      3669774.19     10601660.88
#Sta/Elev= 30
  4736.0  303.48  4782.2  299.62  4803.5  295.94  4824.7  295.53  4831.8  294.16
  4852.9  294.65  4874.2  292.75  4881.2  293.36  4888.3  291.89  4909.5  291.98
  4930.8  288.71  4937.8  288.80  4944.9  285.33  4966.1  279.43  4987.3  277.36
  4994.4  271.65  5005.5  270.31  5008.3  269.81  5011.5  270.31  5015.6  271.95
  5022.6  278.25  5065.1  277.25  5098.2  278.36  5227.7  278.95  5284.3  287.59
  5291.4  290.70  5312.6  293.75  5319.8  297.32  5333.8  299.89  5371.9  301.06
#Mann=6,-1,0
  4736.0    0.05       0  4930.8    0.12       0  5005.5    0.07       0
  5011.5    0.12       0  5098.2    0.16       0  5319.8    0.12       0
Bank Sta=5005.5,5011.5
Exp/Cntr=0.3,0.1

Type RM Length L Ch R = 1,296,0,0,0
BEGIN DESCRIPTION:
UNT 005 IN BOCR 1.0
END DESCRIPTION:
XS GIS Cut Line= 4
      3669326.26     10602164.39      3669527.63     10602369.24
      3669746.38     10602365.76      3669843.57     10601584.82
#Sta/Elev= 30
  4553.4  306.33  4644.8  305.14  4731.6  296.47  4786.1  288.66  4835.7  284.25
  4838.5  282.82  4912.6  277.10  4982.6  275.88  4992.7  268.36  4999.7  266.26
  5002.4  265.76  5005.7  266.26  5032.7  274.77  5135.6  274.19  5209.1  276.13
  5256.5  275.80  5276.7  277.65  5327.1  274.55  5357.3  277.23  5427.8  275.30
  5458.1  277.08  5510.6  276.65  5512.1  276.68  5558.8  277.95  5608.0  285.00
  5613.1  284.15  5659.6  288.51  5693.9  289.60  5774.7  295.37  5846.4  302.69
#Mann=6,-1,0
  4553.4    0.05       0  4731.6    0.12       0  4999.7    0.07       0
  5005.7    0.12       0  5510.6    0.16       0  5512.1    0.12       0
Bank Sta=4999.7,5005.7
Exp/Cntr=0.3,0.1

Chan Stop Cuts=-1