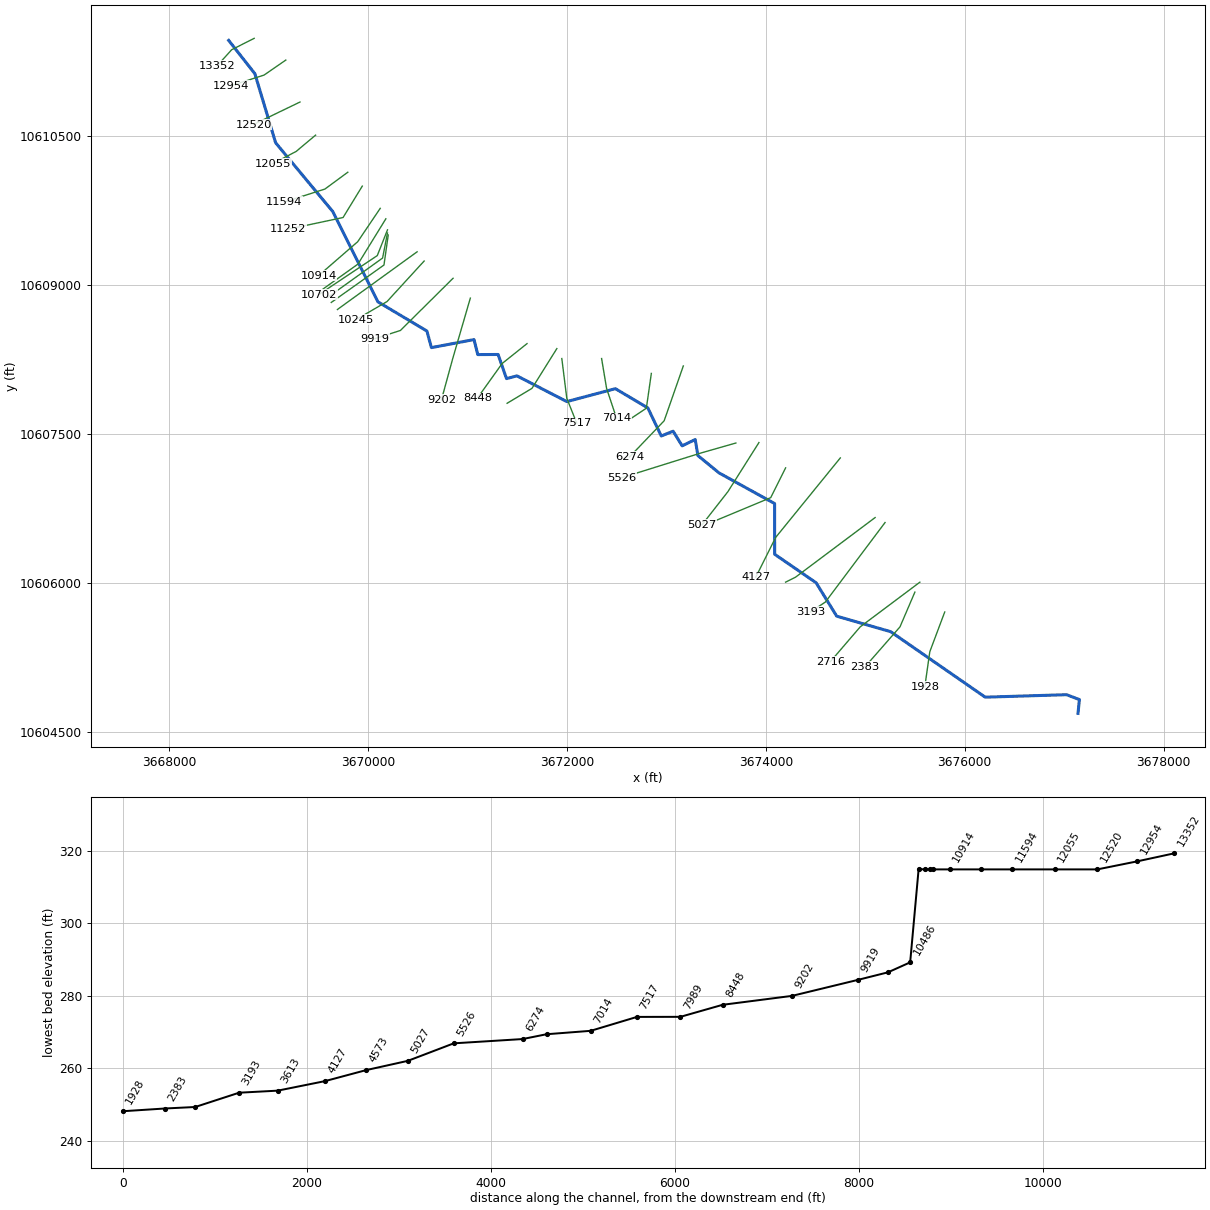
--- UNT 006 IN BOCR.prj (project) ---

Proj Title=UNT 006 IN BOCR Base Level Engineering
Current Plan=p01
Default Exp/Contr=0.3,0.1
English Units
Geom File=g01
Flow File=f01
Plan File=p01
Y Axis Title=Elevation
X Axis Title(PF)=Main Channel Distance
X Axis Title(XS)=Station
BEGIN DESCRIPTION:
UNT 006 IN BOCR
END DESCRIPTION:
DSS File=dss
DSS Export Rating Curves= 0
DSS Export Rating Curve Sorted= 0
DSS Export Volume Flow Curves= 0
DXF OffsetX= 0
DXF OffsetY= 0
DXF ScaleX= 1
DXF ScaleY= 10

--- UNT 006 IN BOCR.p01 (plan) ---

Plan Title=Multiple Run
Program Version=4.10
Short Identifier=Multiple Run
Geom File=g01
Flow File=f01
Subcritical Flow
K Sum by GR= 0
Std Step Tol= 0.01
Critical Tol= 0.01
Num of Std Step Trials= 20
Max Error Tol= 0.3
Flow Tol Ratio= 0.001
Split Flow NTrial= 30
Split Flow Tol= 0.02
Split Flow Ratio= 0.02
Log Output Level= 0
Friction Slope Method= 1
Unsteady Friction Slope Method= 2
Unsteady Bridges Friction Slope Method= 1
Parabolic Critical Depth
Global Vel Dist= 1 , 1 , 1
Global Log Level= 0
CheckData=True
Encroach Param=-1 ,0,0, 0
BEGIN DESCRIPTION:
Multiple Run
END DESCRIPTION:
Computation Interval=1HOUR
Output Interval=1HOUR
Run HTab= 0
Run UNet= 0
Run PostProcess= 0
Run WQNet= 0
UNET Theta= 1
UNET Theta Warmup= 1
UNET ZTol= 0.02
UNET ZSATol= 0.05
UNET MxIter= 20
UNET MaxInSteps= 0
UNET DtIC= 0
UNET DtMin= 0
UNET MaxCRTS= 20
UNET WFStab= 2
UNET SFStab= 1
UNET WFX= 1
UNET SFX= 1
UNET DSS MLevel= 4
UNET DZMax Abort= 100
UNET Convert EG Bridges= 0
UNET Use Existing IB Tables=-1
UNET Froude Reduction=False
UNET Froude Limit= 1
UNET Froude Power= 10
UNET Time Slicing=0,0, 5
UNET Junction Losses=0
Instantaneous Interval=1HOUR
DSS File=dss
Write IC File= 0
Write IC File at Sim End=0
Echo Input=False
Echo Parameters=False
Echo Output=False
Write Detailed= 0
WQ AD Non Conservative
WQ ULTIMATE=-1
WQ Max Comp Step=1HOUR
WQ Output Interval=15MIN
WQ Output Selected Increments= 0
WQ Output face flow=0
WQ Output face velocity=0
WQ Output face area=0
WQ Output face dispersion=0
WQ Output cell volume=0
WQ Output cell surface area=0
WQ Output cell continuity=0
WQ Output cumulative cell continuity=0
WQ Output face conc=0
WQ Output face dconc_dx=0
WQ Output face courant=0
WQ Output face peclet=0
WQ Output face adv mass=0
WQ Output face disp mass=0
WQ Output cell mass=0
WQ Output cell source sink temp=0
WQ Output cell source sink nsm=0
WQ Output MaxMinRange=-1
WQ Daily Max Min Mean=-1
WQ Daily Range=0
WQ Daily Time=0
WQ Create Restart=0
WQ Fixed Restart=0
WQ System Summary=0
WQ Use Fixed Temperature=0
Sorting and Armoring Iterations= 10
XS Update Threshold= 0.02
Hydraulics Update Threshold= 0.02
Energy Slope Method= 1
Volume Change Method= 0
XS Weighting Method= 0
Number of US Weighted Cross Sections= 1
Number of DS Weighted Cross Sections= 1
Upstream XS Weight=0.25
Main XS Weight=0.5
Downstream XS Weight=0.25
Number of DS XS's Weighted with US Boundary= 1
Upstream Boundary Weight= 1
Weight of XSs Associated with US Boundary= 0
Number of US XS's Weighted with DS Boundary= 1
Downstream Boundary Weight= 0.5
Weight of XSs Associated with DS Boundary= 0.5
Sediment Output Level= 4
Mass or Volume Output= 0
Output Increment Type= 1
Profile and TS Output Increment= 10
XS Output Flag= 0
XS Output Increment= 10
Disregard all LS=0
Disregard all Conn=0
Disregard all Breaches=0
Disregard all Pumps=0

--- UNT 006 IN BOCR.f01 (steady flow) ---

Flow Title=Multiple
Program Version=4.10
Number of Profiles= 7
Profile Names=10-year,25-year,50-year,1pct_min,100-year,1pct_plu,500-year
River Rch & RM=UNT 006 IN BOCR,Reach-1         ,13352
     431     578     698     621     839    1135    1218
River Rch & RM=UNT 006 IN BOCR,Reach-1         ,10914
     864    1205    1494    1360    1840    2488    2803
River Rch & RM=UNT 006 IN BOCR,Reach-1         ,5526
    1260    1785    2237    2055    2780    3759    4315
River Rch & RM=UNT 006 IN BOCR,Reach-1         ,5027
    1260    1785    2237    2055    2780    3759    4315
Boundary for River Rch & Prof#=UNT 006 IN BOCR,Reach-1         , 1
Up Type= 0
Dn Type= 3
Dn Slope=0.005
Boundary for River Rch & Prof#=UNT 006 IN BOCR,Reach-1         , 2
Up Type= 0
Dn Type= 3
Dn Slope=0.005
Boundary for River Rch & Prof#=UNT 006 IN BOCR,Reach-1         , 3
Up Type= 0
Dn Type= 3
Dn Slope=0.005
Boundary for River Rch & Prof#=UNT 006 IN BOCR,Reach-1         , 4
Up Type= 0
Dn Type= 3
Dn Slope=0.005
Boundary for River Rch & Prof#=UNT 006 IN BOCR,Reach-1         , 5
Up Type= 0
Dn Type= 3
Dn Slope=0.005
Boundary for River Rch & Prof#=UNT 006 IN BOCR,Reach-1         , 6
Up Type= 0
Dn Type= 3
Dn Slope=0.005
Boundary for River Rch & Prof#=UNT 006 IN BOCR,Reach-1         , 7
Up Type= 0
Dn Type= 3
Dn Slope=0.005
DSS Import GetInterval= 0
DSS Import GetPeak= 0
DSS Import FillOption= 0

--- UNT 006 IN BOCR.g01 (geometry) ---

Geom Title=Existing Conditions
Program Version=4.10

River Reach=UNT 006 IN BOCR ,Reach-1
Reach XY= 30
      3668600.11     10611461.19       3668863.5       10611126.
        3669072.       10610431.       3669647.5       10609738.
      3670100.25       10608831.        3670593.       10608537.
       3670638.5       10608370.      3671066.75       10608451.
       3671104.5       10608300.        3671309.       10608301.
       3671393.5       10608058.       3671498.5       10608086.
      3671999.75       10607827.      3672488.25       10607957.
      3672814.75       10607763.       3672949.5       10607481.
      3673068.75       10607529.      3673159.25       10607382.
        3673291.       10607445.      3673317.75       10607284.
      3673529.75       10607110.        3674089.       10606801.
      3674089.75       10606291.       3674506.5       10606004.
       3674713.5       10605668.        3675256.       10605512.
      3676206.75       10604853.        3677024.       10604878.
      3677153.75       10604829.       3677139.5       10604690.

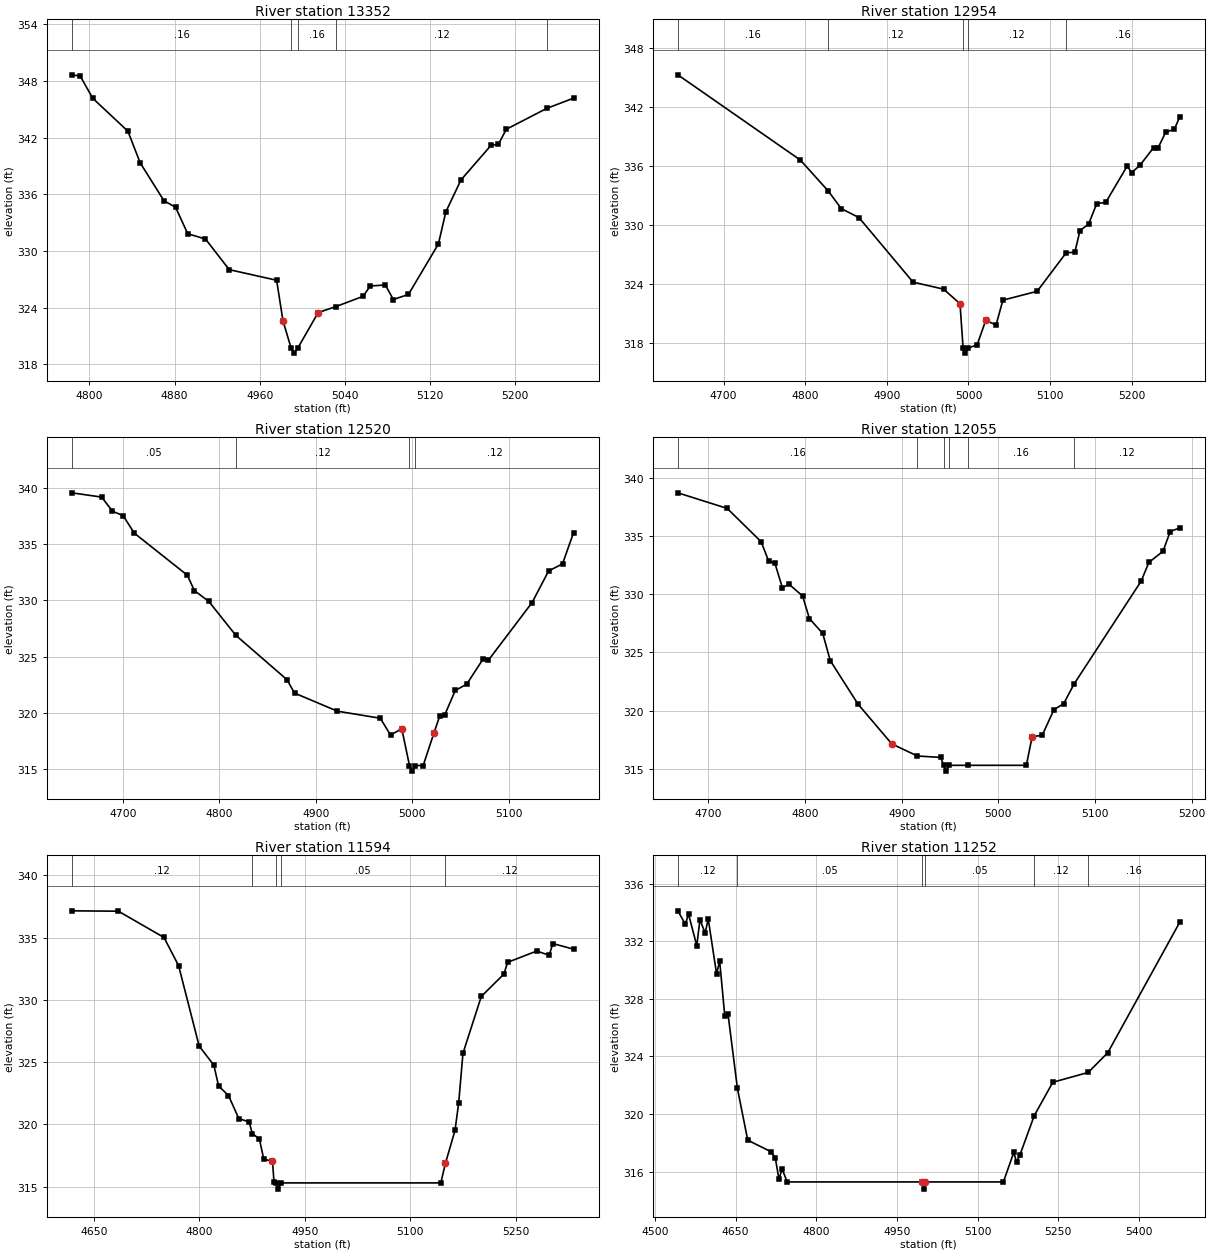
Type RM Length L Ch R = 1 ,13352   ,398,398,398
BEGIN DESCRIPTION:
UNT 006 IN BOCR 27.0
END DESCRIPTION:
XS GIS Cut Line= 3
      3668856.63     10611481.89      3668630.04     10611367.29
       3668484.4     10611206.05
#Sta/Elev= 30
  4783.4  348.64  4791.3  348.51  4803.2  346.15  4836.1  342.68  4847.7  339.32
    4870  335.32  4880.9  334.63  4892.3  331.83    4909  331.27  4931.3  328.03
  4975.8  326.91  4981.8  322.59  4989.5   319.7  4992.3   319.2  4995.5   319.7
  5014.8  323.49  5031.6  324.13    5057  325.21  5063.7   326.3  5077.9  326.41
  5085.4  324.87  5099.6  325.41  5127.7  330.74  5134.7  334.14  5148.9  337.52
  5177.3   341.2    5184  341.28  5191.5  342.88  5229.5  345.09  5254.6  346.17
#Mann= 5 ,-1 , 0
  4783.4     .16       0  4989.5     .07       0  4995.5     .16       0
  5031.6     .12       0  5229.5     .16       0
Bank Sta=4981.8,5014.8
XS Rating Curve= 0 ,0
Exp/Cntr=0.3,0.1

Type RM Length L Ch R = 1 ,12954   ,434,434,434
BEGIN DESCRIPTION:
UNT 006 IN BOCR 26.0
END DESCRIPTION:
XS GIS Cut Line= 3
      3669174.32     10611263.13      3668955.56     10611112.08
      3668623.43      10611005.7
#Sta/Elev= 30
    4644  345.28  4794.1  336.62  4828.1  333.49  4844.2  331.69  4865.8  330.78
  4932.1  324.22  4969.5  323.51  4989.6  322.03  4993.4  317.51  4996.2  317.01
  4999.4  317.51  5010.6  317.86  5021.1  320.33  5033.8  319.87  5042.1  322.39
  5084.1  323.29  5119.8  327.22  5130.2  327.24  5136.6  329.46  5147.1  330.11
  5157.1   332.2  5168.1  332.32  5194.5  336.03  5199.8  335.34  5210.1   336.1
  5226.7  337.88  5231.9  337.81  5241.6  339.46  5252.1  339.74  5258.6  340.98
#Mann= 5 ,-1 , 0
    4644     .16       0  4828.1     .12       0  4993.4     .07       0
  4999.4     .12       0  5119.8     .16       0
Bank Sta=4989.6,5021.1
XS Rating Curve= 0 ,0
Exp/Cntr=0.3,0.1

Type RM Length L Ch R = 1 ,12520   ,465,465,465
BEGIN DESCRIPTION:
UNT 006 IN BOCR 25.0
END DESCRIPTION:
XS GIS Cut Line= 2
       3669317.5     10610841.23      3668849.32     10610614.94
#Sta/Elev= 30
  4647.1  339.58  4678.1   339.2  4689.3  337.94  4700.3  337.55  4711.9  335.99
  4766.9  332.24  4774.2  330.87  4789.1  329.91  4817.1  326.89  4870.1  322.94
    4878  321.74  4922.4  320.13  4966.9   319.5  4977.5     318  4989.1  318.57
  4997.1  315.29  4999.9  314.79  5003.1  315.29  5011.3  315.29  5022.4  318.17
  5028.3  319.66  5033.8  319.83  5044.6  321.98  5056.4  322.53  5073.5  324.79
    5079  324.68  5124.2  329.81  5141.3  332.62  5155.7  333.25  5167.1  336.02
#Mann= 4 ,-1 , 0
  4647.1     .05       0  4817.1     .12       0  4997.1     .07       0
  5003.1     .12       0
Bank Sta=4989.1,5022.4
XS Rating Curve= 0 ,0
Exp/Cntr=0.3,0.1

Type RM Length L Ch R = 1 ,12055   ,461,461,461
BEGIN DESCRIPTION:
UNT 006 IN BOCR 24.0
END DESCRIPTION:
XS GIS Cut Line= 3
      3669473.79     10610507.91      3669278.48     10610343.85
      3669044.35     10610221.59
#Sta/Elev= 30
  4668.3  338.74  4719.3   337.4  4754.5  334.53  4762.2  332.87  4768.8  332.66
  4776.5  330.56  4783.1  330.89  4797.4  329.86  4804.4  327.92  4818.2  326.64
    4826   324.3  4854.6  320.57  4889.7  317.13  4916.2  316.09  4940.5  315.97
  4943.2  315.29  4945.9  314.79  4949.2  315.29  4968.9  315.29  5028.9  315.29
  5034.9  317.76  5045.3  317.87  5057.5  320.09  5067.4  320.58  5078.3  322.29
  5147.7  331.14  5155.7  332.75  5170.3  333.71  5177.8  335.41  5187.5  335.72
#Mann= 6 ,-1 , 0
  4668.3     .16       0  4916.2     .05       0  4943.2     .07       0
  4949.2     .05       0  4968.9     .16       0  5078.3     .12       0
Bank Sta=4889.7,5034.9
XS Rating Curve= 0 ,0
Exp/Cntr=0.3,0.1

Type RM Length L Ch R = 1 ,11594   ,342,342,342
BEGIN DESCRIPTION:
UNT 006 IN BOCR 23.0
END DESCRIPTION:
XS GIS Cut Line= 3
      3669797.83     10610134.75      3669567.79     10609965.47
      3669159.77     10609835.25
#Sta/Elev= 30
  4618.4  337.15  4684.8  337.12  4749.6  335.01  4770.4  332.75  4799.7  326.28
  4820.6  324.75  4827.3  323.08  4841.4  322.31  4856.1  320.46  4870.7  320.19
  4875.4  319.25  4885.4  318.82  4891.6  317.19    4904  317.04  4906.1   315.4
  4909.6  315.29  4912.3  314.79  4915.6  315.29  5143.5  315.29  5150.1  316.87
  5163.7  319.51  5168.9   321.7    5175   325.7  5201.1  330.27  5233.3  332.07
  5238.5  333.01    5280  333.92  5297.7  333.58  5302.9  334.52  5332.3  334.07
#Mann= 5 ,-1 , 0
  4618.4     .12       0  4875.4     .05       0  4909.6    .033       0
  4915.6     .05       0  5150.1     .12       0
Bank Sta=4904,5150.1
XS Rating Curve= 0 ,0
Exp/Cntr=0.3,0.1

Type RM Length L Ch R = 1 ,11252   ,338,338,338
BEGIN DESCRIPTION:
UNT 006 IN BOCR 22.0
END DESCRIPTION:
XS GIS Cut Line= 3
      3669943.26     10609994.78      3669750.08     10609679.02
      3669198.87     10609561.83
#Sta/Elev= 30
  4542.4  334.11  4556.3  333.18  4562.2  333.89  4577.6  331.69  4583.5   333.5
  4593.1  332.56  4598.9  333.55  4614.4  329.74  4620.2  330.62  4629.8  326.78
  4635.7  326.95  4653.2  321.79  4672.4  318.19    4715   317.4  4723.6  316.98
  4730.5  315.48  4736.3  316.19  4745.9  315.29    4997  315.29  4999.8  314.79
    5003  315.29  5148.2  315.29  5167.5  317.34  5172.6  316.67  5178.9  317.16
  5205.7   319.9  5240.2  322.21    5306  322.89  5342.4  324.26  5476.1   333.3
#Mann= 6 ,-1 , 0
  4542.4     .12       0  4653.2     .05       0    4997    .033       0
    5003     .05       0  5205.7     .12       0    5306     .16       0
Bank Sta=4997,5003
XS Rating Curve= 0 ,0
Exp/Cntr=0.3,0.1

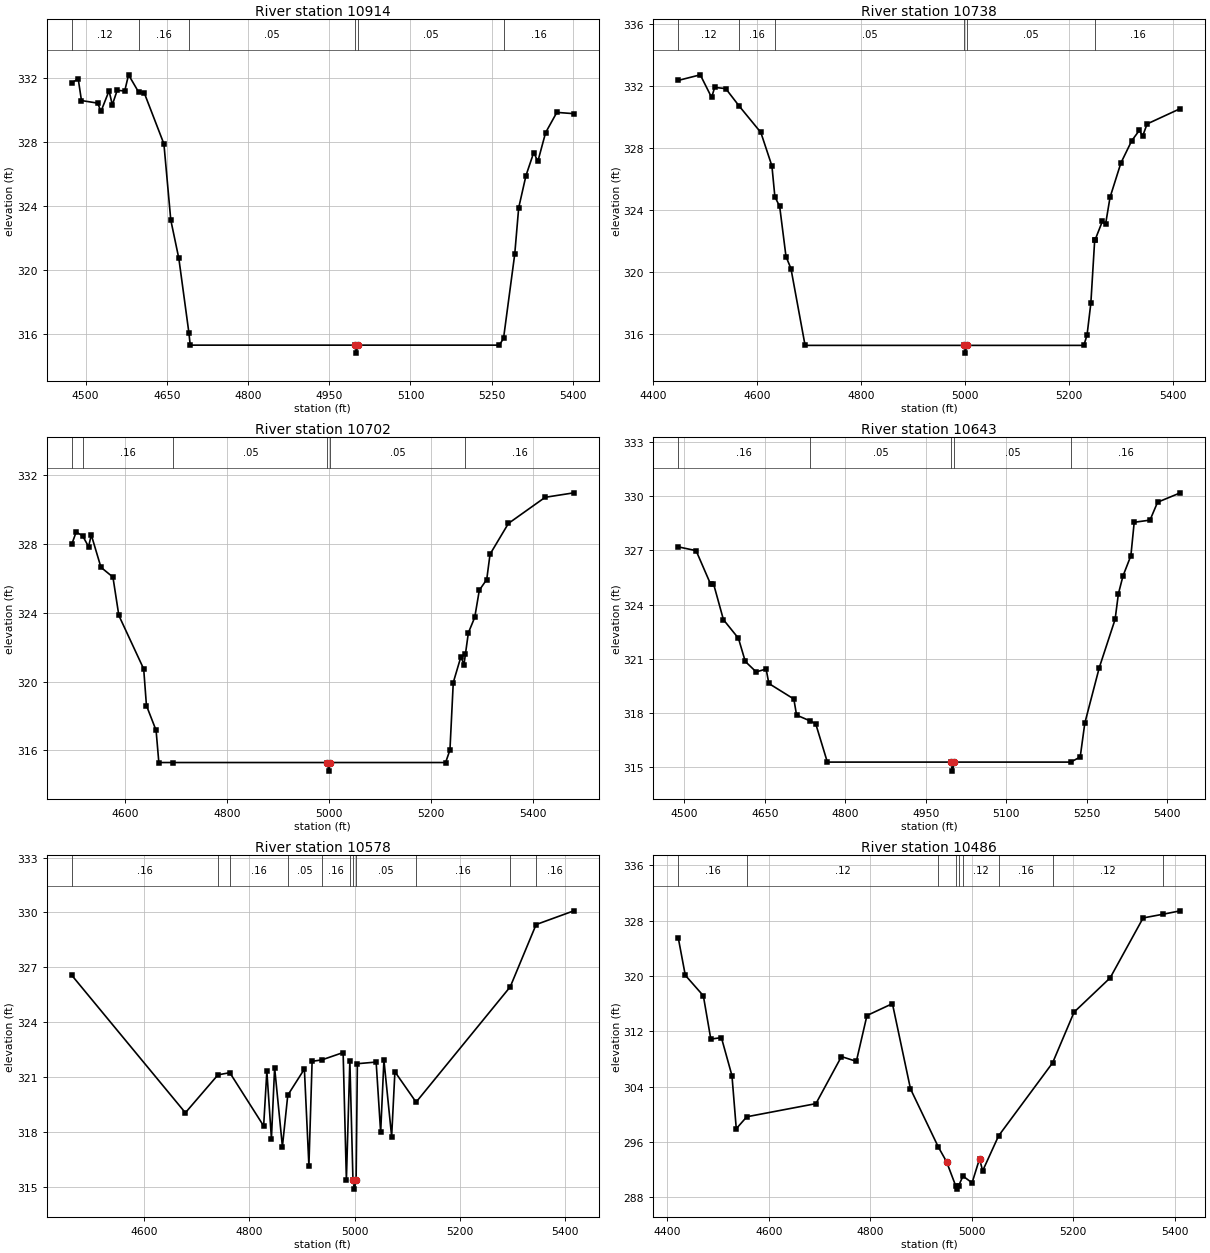
Type RM Length L Ch R = 1 ,10914   ,176,176,176
BEGIN DESCRIPTION:
Mapping XS aa1aaddd
END DESCRIPTION:
XS GIS Cut Line= 3
      3670123.81     10609771.29      3669897.65     10609435.96
      3669502.69     10609093.08
#Sta/Elev= 30
  4474.3   331.7  4486.2  331.95  4492.2  330.59  4522.2  330.43  4528.2  329.91
  4543.2   331.2  4549.2  330.32  4558.2  331.23  4572.1  331.19  4579.2   332.2
  4597.6  331.13  4608.3  331.06  4644.5  327.88  4657.2  323.12  4672.1  320.71
  4690.8  316.03  4693.1  315.29    4997  315.29  4999.8  314.79    5003  315.29
  5264.1  315.29  5271.9  315.71  5292.6  320.98  5299.9  323.88  5313.4   325.9
  5327.7  327.34  5335.3  326.78  5349.6  328.58  5370.4  329.85  5401.8  329.77
#Mann= 6 ,-1 , 0
  4474.3     .12       0  4597.6     .16       0  4690.8     .05       0
    4997    .033       0    5003     .05       0  5271.9     .16       0
Bank Sta=4997,5003
XS Rating Curve= 0 ,0
Exp/Cntr=0.3,0.1

Type RM Length L Ch R = 1 ,10738   ,36,36,36
BEGIN DESCRIPTION:
UNT 006 IN BOCR 21.0
END DESCRIPTION:
XS GIS Cut Line= 3
      3670180.48     10609666.32      3669899.61     10609210.19
       3669549.6     10608960.18
#Sta/Elev= 30
  4447.7  332.39  4490.1  332.75  4511.9  331.29  4517.8  331.94  4539.1  331.86
  4564.8  330.74  4606.6  329.03  4627.9  326.87  4633.6  324.88  4642.8  324.26
    4655  321.02  4664.5  320.25  4691.7  315.29    4997  315.29  4999.8  314.79
    5003  315.29  5227.9  315.29  5234.1  315.96  5241.4  318.01  5248.8  322.09
  5249.6   322.1  5263.6   323.3  5269.7   323.1  5278.3  324.84  5299.2  327.06
  5320.1   328.5  5334.8  329.17    5341  328.79  5349.6  329.58  5413.5  330.57
#Mann= 6 ,-1 , 0
  4447.7     .12       0  4564.8     .16       0  4633.6     .05       0
    4997    .033       0    5003     .05       0  5249.6     .16       0
Bank Sta=4997,5003
XS Rating Curve= 0 ,0
Exp/Cntr=0.3,0.1

Type RM Length L Ch R = 1 ,10702   ,59,59,59
BEGIN DESCRIPTION:
Mapping XS df29d102
END DESCRIPTION:
XS GIS Cut Line= 3
      3670196.93     10609555.25      3670094.21     10609295.96
      3669507.61     10608904.17
#Sta/Elev= 30
    4496  327.98  4504.6  328.69  4517.3  328.47  4528.9  327.84  4534.3  328.52
  4553.2  326.64  4576.7  326.07  4588.3  323.84    4637  320.73  4642.4   318.6
  4661.3  317.16  4666.7  315.29  4695.2  315.29    4997  315.29  4999.8  314.79
    5003  315.29  5228.9  315.29  5237.4  316.02  5243.9  319.94  5258.9  321.44
  5264.9  320.98  5267.8   321.6  5273.5  322.83    5286  323.73    5295  325.31
  5309.5  325.93    5316   327.4    5352  329.19  5424.1  330.71  5480.3  330.97
#Mann= 6 ,-1 , 0
    4496     .12       0  4517.3     .16       0  4695.2     .05       0
    4997    .033       0    5003     .05       0  5267.8     .16       0
Bank Sta=4997,5003
XS Rating Curve= 0 ,0
Exp/Cntr=0.3,0.1

Type RM Length L Ch R = 1 ,10643   ,65,65,65
BEGIN DESCRIPTION:
Mapping XS 135e45b4
END DESCRIPTION:
XS GIS Cut Line= 3
      3670196.52     10609522.92      3670147.58     10609271.21
      3669595.14     10608874.75
#Sta/Elev= 30
  4488.4   327.2  4521.7  326.99    4549  325.12  4554.1  325.17  4572.7  323.17
  4600.7  322.14  4613.4  320.86  4633.8  320.28  4652.3  320.44  4657.4  319.64
    4704  318.78  4709.1  317.89  4734.3  317.57  4744.8  317.41  4766.5  315.29
    4997  315.29  4999.8  314.79    5003  315.29  5220.3  315.29  5238.1  315.57
  5246.7  317.45  5273.7  320.52  5303.2  323.19  5309.3   324.6  5317.9  325.59
  5332.6  326.71  5338.8  328.56  5368.3  328.68  5382.4  329.67  5424.8  330.19
#Mann= 5 ,-1 , 0
  4488.4     .16       0  4734.3     .05       0    4997    .033       0
    5003     .05       0  5220.3     .16       0
Bank Sta=4997,5003
XS Rating Curve= 0 ,0
Exp/Cntr=0.3,0.1

Type RM Length L Ch R = 1 ,10578   ,92,92,92
BEGIN DESCRIPTION:
Mapping XS d7d8c0f8
END DESCRIPTION:
XS GIS Cut Line= 3
      3670204.32     10609503.33       3670161.5     10609201.06
       3669631.8     10608824.67
#Sta/Elev= 30
  4462.1  326.57  4678.2  319.06  4740.2  321.13  4762.7  321.25  4827.1  318.34
  4833.2  321.33  4841.9  317.65    4848  321.52  4862.8  317.21    4873  320.02
  4904.6  321.45  4913.2  316.17  4919.3  321.87    4938  321.95  4978.3  322.35
  4984.5  315.39  4991.1  321.89    4997  315.39  4999.8  314.89    5003  315.39
  5005.4  321.74  5041.1  321.83  5049.7  317.99  5055.9  321.94  5070.6  317.76
  5076.8   321.3  5117.1  319.64  5296.2  325.94  5345.4  329.34  5417.2  330.09
#Mann= 11 ,-1 , 0
  4462.1     .16       0  4740.2     .05       0  4762.7     .16       0
    4873     .05       0    4938     .16       0  4991.1     .05       0
    4997    .033       0    5003     .05       0  5117.1     .16       0
  5296.2     .12       0  5345.4     .16       0
Bank Sta=4997,5003
XS Rating Curve= 0 ,0
Exp/Cntr=0.3,0.1

Type RM Length L Ch R = 1 ,10486   ,241,241,241
BEGIN DESCRIPTION:
Mapping XS cff9ed2a
END DESCRIPTION:
XS GIS Cut Line= 2
      3670494.79     10609334.14      3669693.26     10608753.57
#Sta/Elev= 30
  4421.2  325.53  4435.1   320.1  4470.7  317.13  4485.4  310.86  4506.3  311.07
  4527.1  305.57  4535.6  297.89  4556.3  299.62  4692.6  301.52  4742.9  308.33
  4772.3  307.64  4793.2  314.27  4843.4  315.99    4879  303.66  4933.9  295.24
  4950.1  293.12    4968  289.65  4970.7  289.15    4974  289.65  4982.5  291.04
  5000.4  290.06  5015.1  293.53  5021.3   291.8  5052.7  296.86  5159.2  307.43
  5201.5  314.76  5272.6  319.72  5337.6  328.39    5377  328.93  5410.9  329.42
#Mann= 9 ,-1 , 0
  4421.2     .16       0  4556.3     .12       0  4933.9     .16       0
    4968     .07       0    4974     .16       0  4982.5     .12       0
  5052.7     .16       0  5159.2     .12       0    5377     .16       0
Bank Sta=4950.1,5015.1
XS Rating Curve= 0 ,0
Exp/Cntr=0.3,0.1

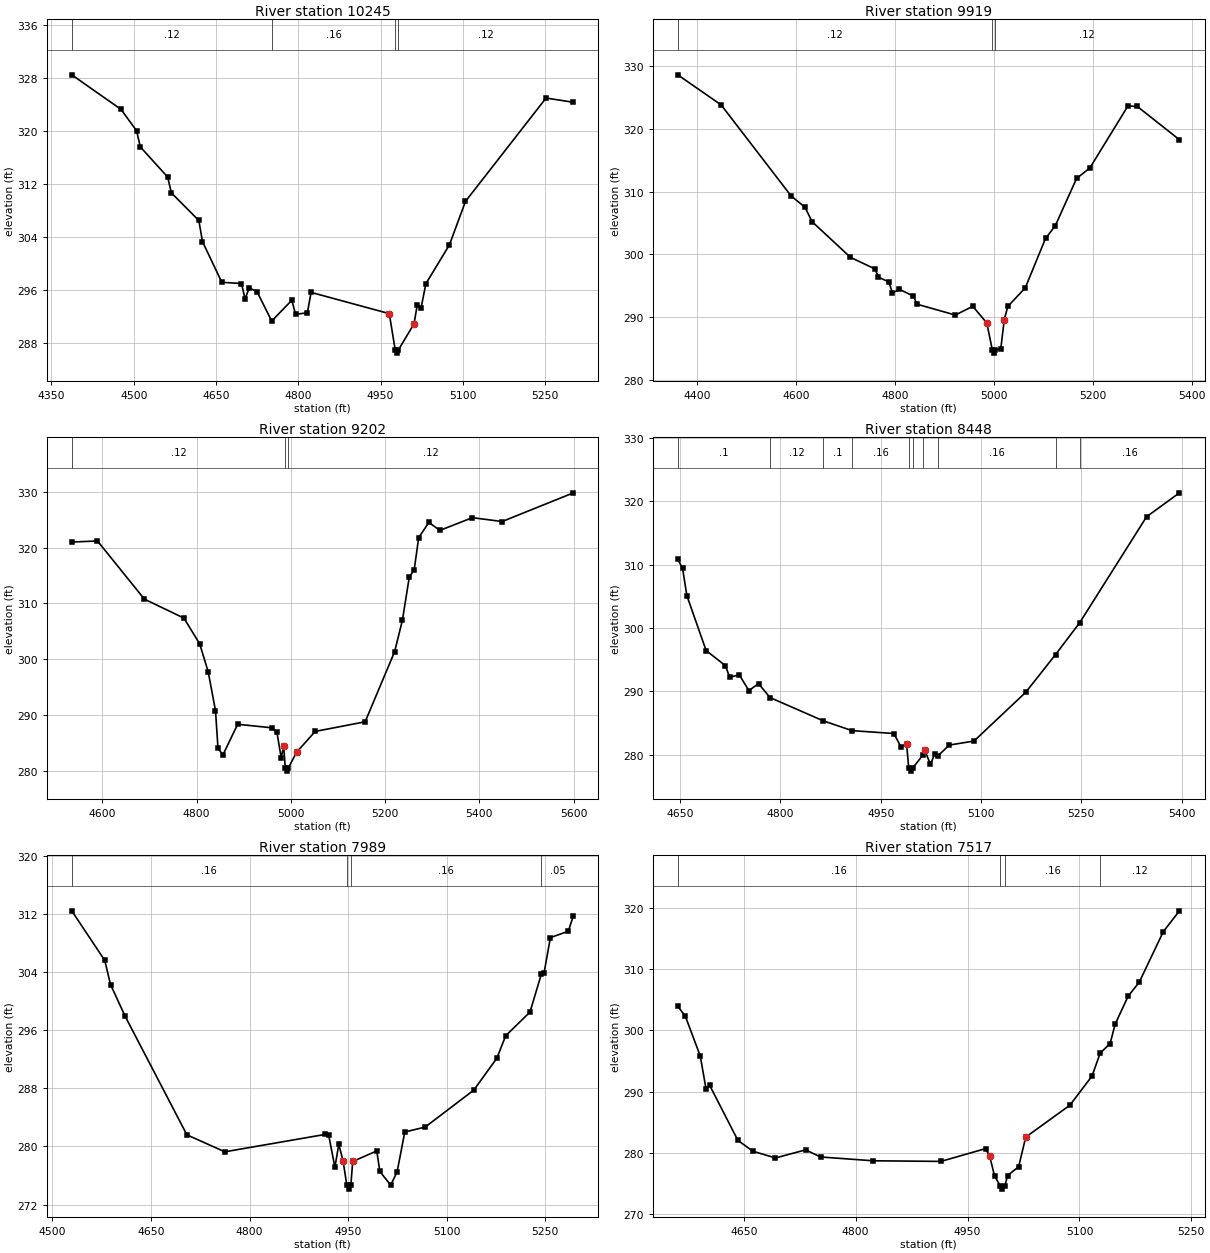
Type RM Length L Ch R = 1 ,10245   ,326,326,326
BEGIN DESCRIPTION:
UNT 006 IN BOCR 20.0
END DESCRIPTION:
XS GIS Cut Line= 3
      3670565.33     10609241.36      3670192.07     10608833.39
      3669879.61     10608651.12
#Sta/Elev= 30
    4387  328.47  4476.8  323.25  4505.2  320.02    4512  317.58  4561.9  313.01
  4568.7  310.62  4618.7  306.45  4625.4  303.25  4660.6  297.11  4696.4  296.92
  4703.1  294.59  4710.5  296.26  4724.7  295.71  4751.6  291.25  4788.2  294.39
  4795.2  292.27  4816.6   292.5  4823.4  295.58    4966  292.37  4976.7   286.9
  4979.5   286.4  4982.7   286.9  5011.1  290.83  5016.9  293.67  5023.8  293.15
  5032.6  296.88  5075.6  302.76  5104.9  309.34  5251.8  324.96  5301.7  324.32
#Mann= 4 ,-1 , 0
    4387     .12       0  4751.6     .16       0  4976.7     .07       0
  4982.7     .12       0
Bank Sta=4966,5011.1
XS Rating Curve= 0 ,0
Exp/Cntr=0.3,0.1

Type RM Length L Ch R = 1 ,9919    ,717,717,717
BEGIN DESCRIPTION:
UNT 006 IN BOCR 19.0
END DESCRIPTION:
XS GIS Cut Line= 3
      3670856.16     10609067.79      3670326.62     10608542.59
       3670070.5     10608460.11
#Sta/Elev= 30
  4360.4  328.54  4448.2  323.76  4589.6  309.31  4617.9  307.49  4632.1  305.21
  4709.8  299.54  4759.3   297.7  4766.4  296.39  4787.6  295.62  4794.7  293.87
  4808.8  294.46  4837.1  293.38  4844.2   292.1  4921.9  290.37  4957.3  291.76
  4985.6  289.11  4996.8  284.82  4999.5  284.32  5002.8  284.82  5013.9  285.02
  5020.9  289.61    5028  291.73  5063.4  294.69  5104.4  302.54  5124.1  304.55
  5167.2  312.07    5194  313.73  5271.2   323.6  5290.2  323.51  5375.3  318.23
#Mann= 3 ,-1 , 0
  4360.4     .12       0  4996.8     .07       0  5002.8     .12       0
Bank Sta=4985.6,5020.9
XS Rating Curve= 0 ,0
Exp/Cntr=0.3,0.1

Type RM Length L Ch R = 1 ,9202    ,754,754,754
BEGIN DESCRIPTION:
UNT 006 IN BOCR 17.0
END DESCRIPTION:
XS GIS Cut Line= 3
      3671029.73     10608868.07      3670851.79     10608256.13
      3670739.12     10607844.45
#Sta/Elev= 30
  4535.3  321.01  4589.9   321.2  4689.3  310.77  4773.2  307.36  4806.7  302.73
  4824.7  297.74  4840.2  290.76  4845.5  284.03  4855.9  282.79  4887.2  288.31
  4960.1  287.67  4970.5  286.88  4979.6  282.27  4984.8  284.45  4988.3   280.4
  4991.1   279.9  4994.3   280.4  5012.1  283.28  5051.8  287.03  5157.6  288.75
  5220.2  301.34  5236.7  306.99  5251.3  314.74  5261.7  316.04  5271.2   321.8
  5292.8  324.53  5316.1   323.1  5385.1  325.38  5448.3  324.69  5599.4  329.84
#Mann= 3 ,-1 , 0
  4535.3     .12       0  4988.3     .07       0  4994.3     .12       0
Bank Sta=4984.8,5012.1
XS Rating Curve= 0 ,0
Exp/Cntr=0.3,0.1

Type RM Length L Ch R = 1 ,8448    ,459,459,459
BEGIN DESCRIPTION:
UNT 006 IN BOCR 16.0
END DESCRIPTION:
XS GIS Cut Line= 3
      3671599.57     10608410.16      3671349.61     10608210.19
      3671099.62     10607860.21
#Sta/Elev= 30
  4646.6  310.85  4653.8   309.4  4660.2  305.11    4689  296.45  4717.8  294.07
  4724.2  292.25  4738.6  292.61    4753  290.14  4767.4  291.24  4784.5  289.04
  4864.2  285.37  4907.3  283.82  4969.8  283.37  4980.2  281.29  4988.8   281.7
    4992  277.94  4994.7  277.44    4998  277.94  5013.6  280.03  5015.9  280.73
  5024.5   278.5  5030.6   280.1  5035.7  279.86  5052.7  281.55  5089.6  282.18
    5167  289.87  5211.5  295.81  5247.7  300.84  5347.7  317.54  5396.8  321.31
#Mann= 10 ,-1 , 0
  4646.6      .1       0  4784.5     .12       0  4864.2      .1       0
  4907.3     .16       0    4992     .07       0    4998     .16       0
  5013.6     .12       0  5035.7     .16       0  5211.5     .12       0
  5247.7     .16       0
Bank Sta=4988.8,5015.9
XS Rating Curve= 0 ,0
Exp/Cntr=0.3,0.1

Type RM Length L Ch R = 1 ,7989    ,472,472,472
BEGIN DESCRIPTION:
UNT 006 IN BOCR 15.0
END DESCRIPTION:
XS GIS Cut Line= 3
      3671899.63     10608360.23      3671649.61     10607960.19
       3671399.6     10607810.18
#Sta/Elev= 30
  4529.5  312.46  4579.7  305.63  4588.5  302.31  4610.3  298.01  4704.7   281.6
  4762.4  279.26  4914.6  281.65  4920.5  281.52  4929.9  277.13  4935.8  280.28
  4942.3  278.02  4948.1  274.62  4950.9  274.12  4954.1  274.62    4957  277.93
  4993.6  279.38  4998.3  276.55  5014.8  274.67  5024.6  276.51  5036.2  281.99
  5067.3  282.67  5141.2  287.76  5176.2  292.14  5189.8  295.25  5226.7  298.51
  5243.9  303.71  5248.1  303.88  5257.8  308.78    5285  309.64  5292.8  311.79
#Mann= 4 ,-1 , 0
  4529.5     .16       0  4948.1     .07       0  4954.1     .16       0
  5243.9     .05       0
Bank Sta=4942.3,4957
XS Rating Curve= 0 ,0
Exp/Cntr=0.3,0.1

Type RM Length L Ch R = 1 ,7517    ,503,503,503
BEGIN DESCRIPTION:
UNT 006 IN BOCR 14.0
END DESCRIPTION:
XS GIS Cut Line= 3
      3671949.61     10608260.17      3671999.61     10607860.19
      3672099.63     10607610.15
#Sta/Elev= 30
  4561.6   303.9  4571.7  302.31  4591.8  295.78  4599.4  290.49  4604.4  291.01
  4642.2  282.05  4662.4  280.27  4692.6  279.18  4732.9   280.5  4753.1  279.34
  4823.6  278.72  4914.3  278.62  4974.1   280.7  4979.5  279.56  4986.2  276.25
    4994   274.6  4996.8   274.1    5000   274.6  5003.7  276.32  5018.5  277.75
    5028  282.58  5087.2  287.78  5116.8  292.53  5127.9   296.3  5141.1  297.82
  5147.8  300.99  5165.3  305.56  5180.1  307.83  5212.4  316.07    5234  319.47
#Mann= 4 ,-1 , 0
  4561.6     .16       0    4994     .07       0    5000     .16       0
  5127.9     .12       0
Bank Sta=4979.5,5028
XS Rating Curve= 0 ,0
Exp/Cntr=0.3,0.1

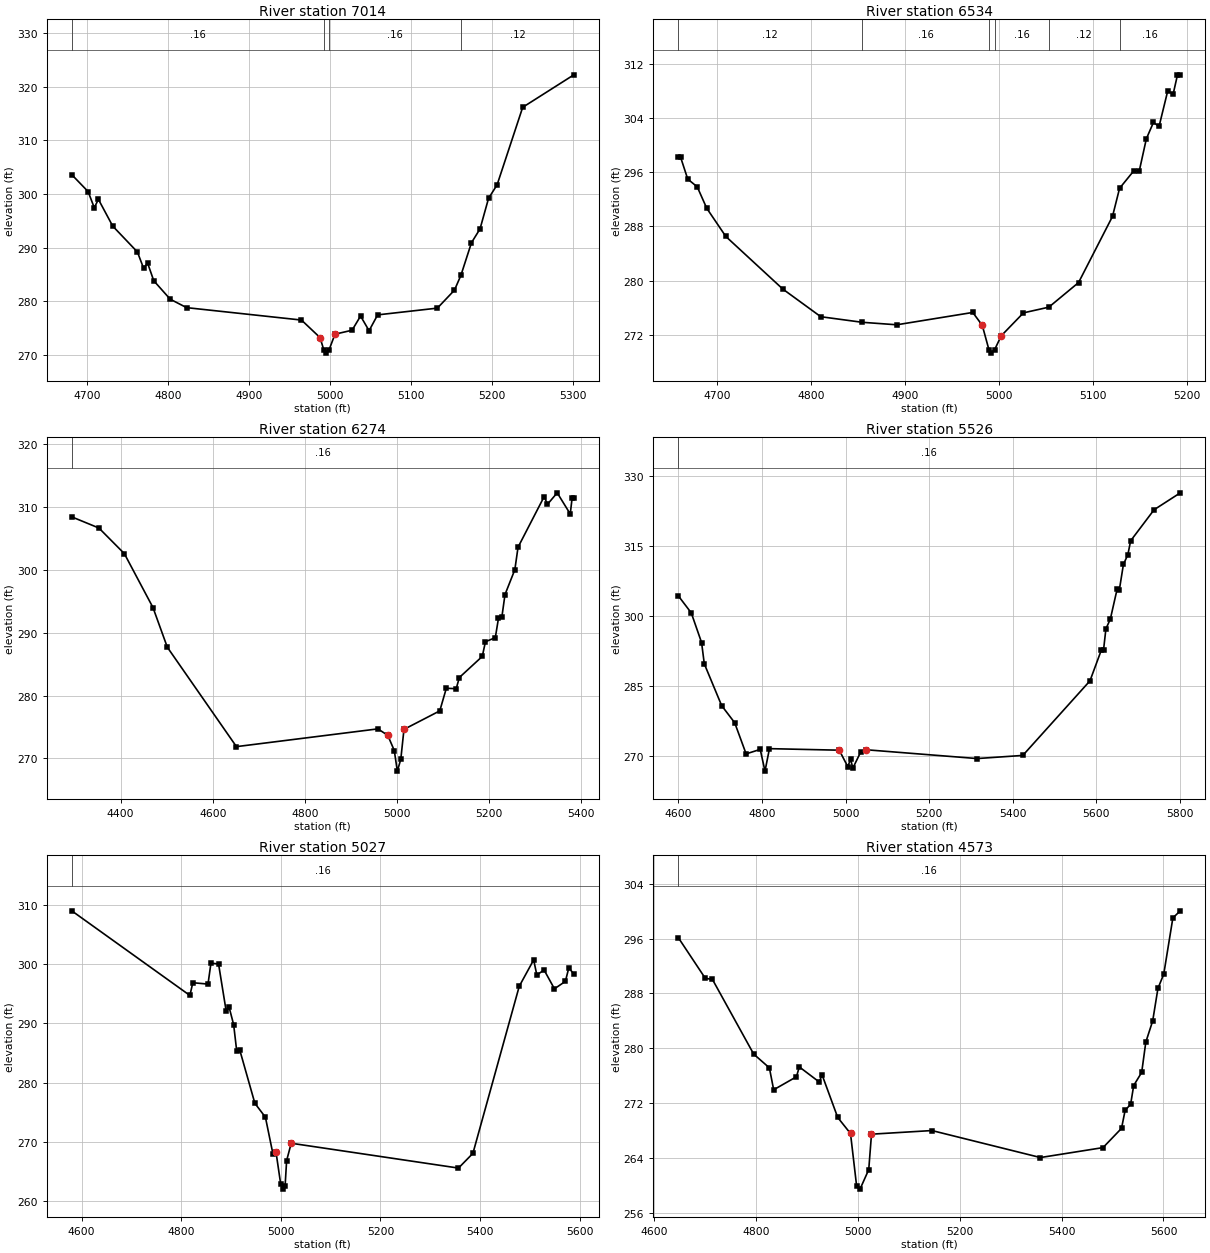
Type RM Length L Ch R = 1 ,7014    ,480,480,480
BEGIN DESCRIPTION:
UNT 006 IN BOCR 13.0
END DESCRIPTION:
XS GIS Cut Line= 3
      3672349.62     10608260.15      3672399.61     10607960.19
       3672499.6     10607660.21
#Sta/Elev= 30
    4681  303.61  4701.2  300.45  4708.8  297.43  4713.9     299  4731.6     294
  4762.1  289.16  4769.7  286.14  4774.7  287.08  4782.3  283.79  4802.6  280.34
  4822.9  278.76  4964.8  276.44  4987.7  273.17  4992.6  270.76  4995.4  270.26
  4998.6  270.76  5006.2   273.8  5027.3  274.54  5037.8  277.19  5048.3  274.45
  5058.9  277.41  5132.7  278.67  5153.8  282.03  5161.8  284.81  5174.8  290.89
  5185.4  293.48  5195.9  299.18  5206.5  301.72  5238.1   316.2  5301.3  322.27
#Mann= 4 ,-1 , 0
    4681     .16       0  4992.6     .07       0  4998.6     .16       0
  5161.8     .12       0
Bank Sta=4987.7,5006.2
XS Rating Curve= 0 ,0
Exp/Cntr=0.3,0.1

Type RM Length L Ch R = 1 ,6534    ,260,260,260
BEGIN DESCRIPTION:
UNT 006 IN BOCR 12.0
END DESCRIPTION:
XS GIS Cut Line= 3
      3672849.61     10608110.23      3672799.61     10607760.19
      3672649.59     10607660.17
#Sta/Elev= 30
    4659  298.18  4661.6  298.18  4669.1  294.99  4679.2  293.85  4689.3  290.69
  4709.6  286.53  4770.2  278.77  4810.6  274.69  4854.5  273.87  4891.4   273.5
  4972.2  275.32  4982.3  273.42  4989.4  269.82  4992.1  269.32  4995.4  269.82
  5002.5  271.88  5026.1  275.26  5053.1   276.1  5084.7  279.73  5120.8  289.49
  5128.3  293.63  5143.3  296.19  5149.3  296.22  5156.8  300.94  5164.3  303.34
  5170.3  302.76  5179.4  307.93  5185.4  307.59  5189.9  310.37  5192.9  310.37
#Mann= 6 ,-1 , 0
    4659     .12       0  4854.5     .16       0  4989.4     .07       0
  4995.4     .16       0  5053.1     .12       0  5128.3     .16       0
Bank Sta=4982.3,5002.5
XS Rating Curve= 0 ,0
Exp/Cntr=0.3,0.1

Type RM Length L Ch R = 1 ,6274    ,748,748,748
BEGIN DESCRIPTION:
UNT 006 IN BOCR 11.0
END DESCRIPTION:
XS GIS Cut Line= 3
      3673171.22     10608185.78      3672978.53     10607633.73
      3672629.56     10607269.14
#Sta/Elev= 30
  4294.2  308.37  4353.1   306.6  4408.3  302.53  4470.4  293.97  4501.5  287.67
  4651.5  271.88  4958.4   274.7  4979.8  273.68    4994  271.26  5000.6  267.99
  5008.1  269.86    5015  274.62  5092.7  277.56  5106.9  281.15  5128.3  281.08
  5135.2  282.86  5184.9  286.21  5191.8  288.54  5213.2  289.19  5220.1  292.29
  5227.3   292.4  5234.2  296.03  5255.6  299.99  5262.5  303.55  5319.2  311.59
  5326.4  310.37  5347.5  312.19  5375.8  308.83  5379.9  311.41  5383.6  311.41
#Mann= 1 ,-1 , 0
  4294.2     .16       0
Bank Sta=4979.8,5015
XS Rating Curve= 0 ,0
Exp/Cntr=0.3,0.1

Type RM Length L Ch R = 1 ,5526    ,499,499,499
BEGIN DESCRIPTION:
UNT 006 IN BOCR 10.0
END DESCRIPTION:
XS GIS Cut Line= 3
       3673699.6     10607410.19      3673349.61     10607310.19
      3672549.65      10607060.2
#Sta/Elev= 30
  4599.4  304.34  4630.6  300.67  4655.3  294.32  4661.8  289.77  4703.4  280.82
  4734.6  277.16  4761.9   270.5  4795.7  271.46  4807.1  266.81  4817.8  271.62
  4984.9  271.29  5005.3  267.77  5012.1  269.36  5017.4  267.44  5036.7  270.98
  5049.8  271.38  5314.9   269.5  5424.4  270.17  5585.2  286.13  5612.4  292.71
  5617.7  292.75  5623.4  297.28  5633.9  299.32  5650.2  305.75  5655.4  305.51
  5665.3  311.06  5675.8  313.09  5682.6   316.1  5738.7  322.74  5801.5  326.36
#Mann= 1 ,-1 , 0
  4599.4     .16       0
Bank Sta=4984.9,5049.8
XS Rating Curve= 0 ,0
Exp/Cntr=0.3,0.1

Type RM Length L Ch R = 1 ,5027    ,454,454,454
BEGIN DESCRIPTION:
UNT 006 IN BOCR 9.0
END DESCRIPTION:
XS GIS Cut Line= 3
      3673931.68     10607415.02      3673619.15     10606920.19
      3673358.71     10606586.82
#Sta/Elev= 30
  4580.1  309.05  4817.3  294.74  4823.2  296.89  4853.7  296.66  4859.6   300.2
  4874.9  300.06  4890.2  292.08  4896.1  292.74  4905.2   289.8  4911.4   285.3
  4917.3  285.56  4947.8   276.5    4969  274.14  4984.3  267.85  4990.2  268.28
  4999.6  262.88  5005.3  261.98  5008.5  262.48  5011.6  266.81  5020.8  269.74
  5356.7  265.54  5385.7  268.03  5478.8   296.3  5507.7  300.75  5514.1  298.19
  5528.6  299.05  5549.4  295.86  5571.4  297.12  5578.3  299.41  5588.4  298.35
#Mann= 1 ,-1 , 0
  4580.1     .16       0
Bank Sta=4990.2,5020.8
XS Rating Curve= 0 ,0
Exp/Cntr=0.3,0.1

Type RM Length L Ch R = 1 ,4573    ,446,446,446
BEGIN DESCRIPTION:
UNT 006 IN BOCR 8.0
END DESCRIPTION:
XS GIS Cut Line= 3
       3674199.6     10607160.18      3674049.61     10606860.19
      3673449.61     10606610.19
#Sta/Elev= 30
  4647.6  296.14  4700.7  290.19  4714.7  290.03  4795.7  279.13  4826.5  277.12
  4834.9  273.92  4879.6  275.82  4885.2  277.26  4924.3  275.06  4929.9   276.1
  4960.6  269.88  4985.7  267.54  4997.6  259.94  5004.4  259.42  5021.5  262.27
  5026.9  267.44  5145.5  267.97  5358.4  264.03  5481.3  265.48  5517.6  268.29
  5524.7  270.93  5535.5   271.8  5541.5  274.54  5557.2  276.46  5565.3  280.88
  5578.8  283.98  5589.1  288.72  5600.5   290.8  5618.4  299.01    5633  300.04
#Mann= 1 ,-1 , 0
  4647.6     .16       0
Bank Sta=4985.7,5026.9
XS Rating Curve= 0 ,0
Exp/Cntr=0.3,0.1

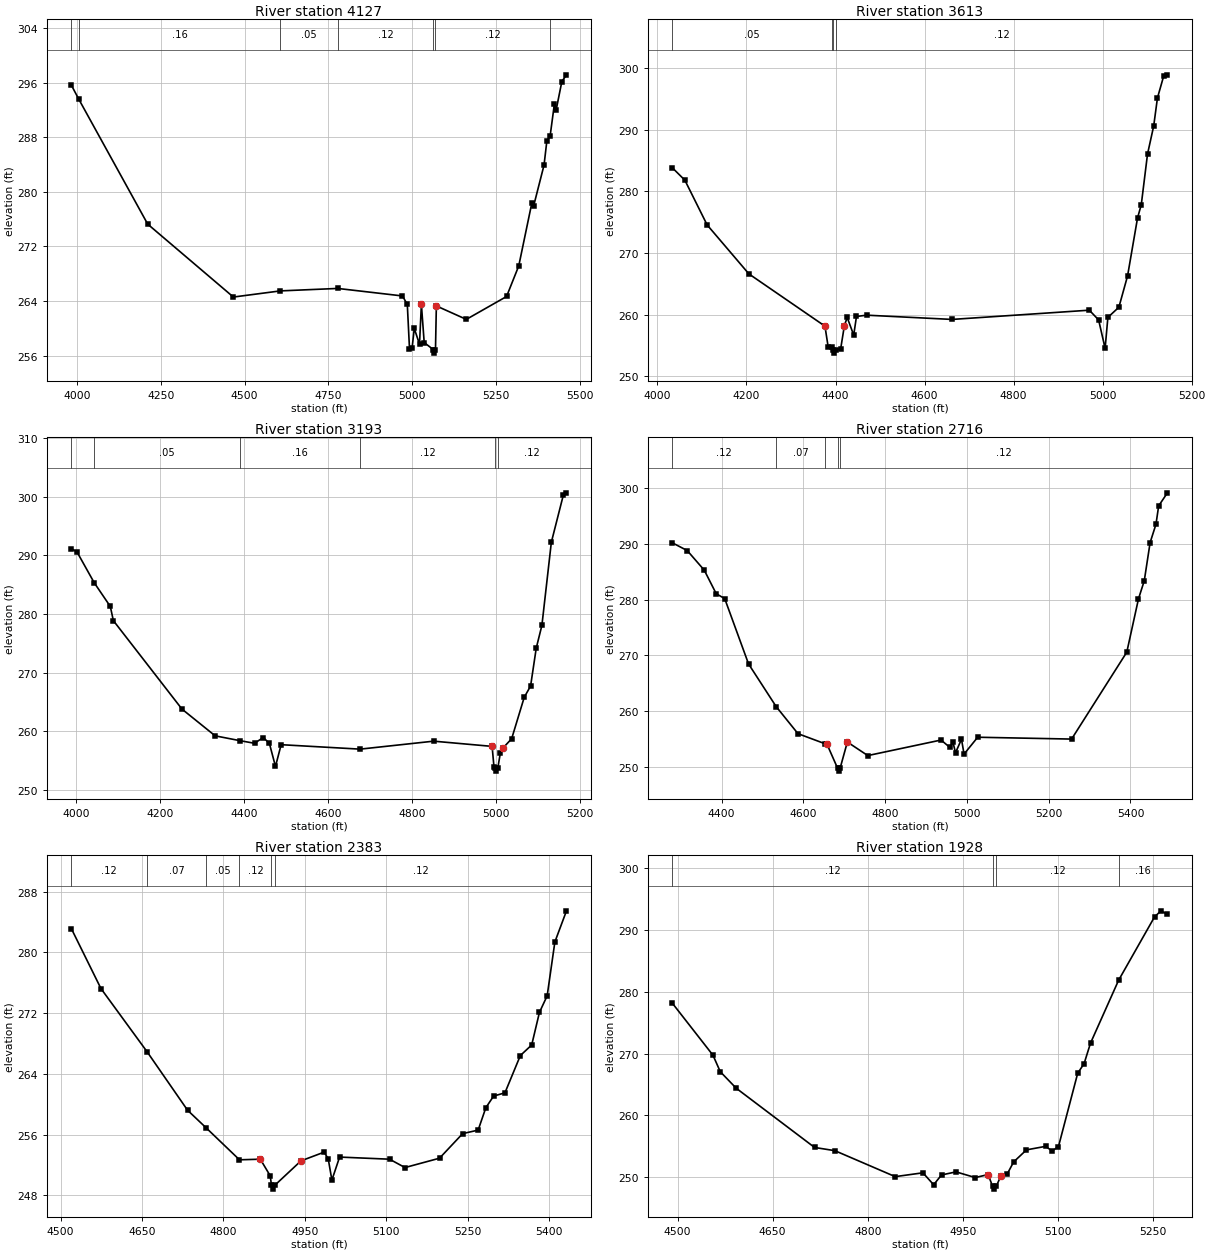
Type RM Length L Ch R = 1 ,4127    ,514,514,514
BEGIN DESCRIPTION:
UNT 006 IN BOCR 7.0
END DESCRIPTION:
XS GIS Cut Line= 3
      3674749.64     10607260.22      3674099.61     10606460.19
      3673899.62     10606060.22
#Sta/Elev= 30
  3982.9   295.6  4004.9  293.56  4210.7  275.27  4466.4   264.6  4606.7   265.5
  4777.9  265.86  4971.3  264.76  4985.7  263.51  4992.2  257.04  5000.1   257.2
  5006.5  260.01  5022.1  257.68  5027.7  263.52  5036.1  257.94  5063.8  256.89
  5066.6  256.39  5069.8  256.89  5072.4   263.3  5161.9  261.33    5282  264.68
  5318.4  269.16  5357.5  278.38  5363.1  277.99  5393.9  283.92  5402.2  287.41
  5412.1  288.19  5424.6  292.79  5430.2  292.02    5447  296.14  5460.9  297.13
#Mann= 7 ,-1 , 0
  3982.9     .05       0  4004.9     .16       0  4606.7     .05       0
  4777.9     .12       0  5063.8     .07       0  5069.8     .12       0
  5412.1     .16       0
Bank Sta=5027.7,5072.4
XS Rating Curve= 0 ,0
Exp/Cntr=0.3,0.1

Type RM Length L Ch R = 1 ,3613    ,420,420,420
BEGIN DESCRIPTION:
UNT 006 IN BOCR 6.0
END DESCRIPTION:
XS GIS Cut Line= 3
      3675099.59     10606660.17      3674299.61     10606060.19
      3674199.59     10606010.18
#Sta/Elev= 30
  4033.6  283.84  4061.7  281.83  4111.7  274.57  4205.5  266.62  4376.3  258.14
  4383.6  254.74  4391.4  254.82  4394.1  254.26  4396.9  253.76  4400.1  254.26
  4411.7   254.5    4420  258.24  4426.3  259.55  4440.9  256.68  4447.1  259.71
    4470  259.92  4661.7  259.23    4970  260.73  4990.9  259.15  5005.5  254.53
  5011.7  259.56  5036.4  261.21  5055.9  266.29  5078.3   275.7  5086.7  277.85
  5100.7  286.06  5114.6  290.63    5123  295.17    5137  298.73  5145.4  298.93
#Mann= 4 ,-1 , 0
  4033.6     .05       0  4391.4     .12       0  4394.1     .07       0
  4400.1     .12       0
Bank Sta=4376.3,4420
XS Rating Curve= 0 ,0
Exp/Cntr=0.3,0.1

Type RM Length L Ch R = 1 ,3193    ,477,477,477
BEGIN DESCRIPTION:
UNT 006 IN BOCR 5.0
END DESCRIPTION:
XS GIS Cut Line= 3
      3675199.62      10606610.2      3674599.61     10605810.19
       3674449.6     10605710.19
#Sta/Elev= 30
  3988.2  291.14  4001.8  290.54  4042.5  285.33  4080.9  281.28  4088.2  278.86
  4251.8  263.77  4330.9  259.21    4389   258.4  4424.7  257.94  4445.5  258.92
  4460.1  257.94  4474.7  253.99  4488.2   257.7  4676.5  256.94  4851.8   258.3
  4991.2  257.41  4995.7  253.83  4998.7  253.69  5001.5  253.19  5004.7  253.69
  5010.8  256.27  5016.8  257.11  5037.8  258.72  5067.8  265.79  5082.9   267.7
  5096.4  274.17  5109.9  278.06  5132.4  292.23    5161  300.28  5168.5  300.66
#Mann= 6 ,-1 , 0
  3988.2     .16       0  4042.5     .05       0    4389     .16       0
  4676.5     .12       0  4998.7     .07       0  5004.7     .12       0
Bank Sta=4991.2,5016.8
XS Rating Curve= 0 ,0
Exp/Cntr=0.3,0.1

Type RM Length L Ch R = 1 ,2716    ,333,333,333
BEGIN DESCRIPTION:
UNT 006 IN BOCR 4.0
END DESCRIPTION:
XS GIS Cut Line= 3
       3675549.6     10606010.18      3674949.61     10605560.19
      3674649.58     10605210.16
#Sta/Elev= 30
  4279.4  290.21  4315.8  288.82  4357.5   285.3  4386.7  281.08  4407.5   280.2
  4465.8  268.48  4533.3  260.83  4586.7  255.97  4653.4  254.15  4657.5  254.11
  4683.7  249.75  4686.4  249.25  4689.7  249.75  4707.5  254.47  4757.5  252.04
  4936.7  254.83  4957.5  253.55  4965.8  254.43  4972.1  252.54  4986.7  254.98
  4992.9   252.3  5026.3  255.33    5256     255    5391  270.59  5419.6  280.15
  5433.8  283.41  5448.1  290.26  5462.4  293.54    5469  296.84  5490.4  299.18
#Mann= 5 ,-1 , 0
  4279.4     .12       0  4533.3     .07       0  4653.4     .12       0
  4683.7     .07       0  4689.7     .12       0
Bank Sta=4657.5,4707.5
XS Rating Curve= 0 ,0
Exp/Cntr=0.3,0.1

Type RM Length L Ch R = 1 ,2383    ,455,455,455
BEGIN DESCRIPTION:
UNT 006 IN BOCR 3.0
END DESCRIPTION:
XS GIS Cut Line= 3
       3675499.6     10605910.17      3675349.61     10605560.19
       3674999.6     10605160.17
#Sta/Elev= 30
  4519.8  283.11  4574.2  275.24  4659.1  266.93  4733.8  259.22  4767.6  256.93
  4829.5  252.69  4867.9  252.77  4886.1  250.59  4888.5  249.33  4891.3  248.83
  4894.5  249.33  4942.8  252.55  4985.5   253.7  4993.1   252.8  4999.8  250.02
    5014  253.05  5106.1  252.77  5134.5  251.67  5198.1   252.9  5240.8  256.14
  5269.3   256.6  5283.5  259.55  5297.8  261.08  5318.7  261.51  5347.1  266.42
    5368  267.81  5382.3  272.11  5396.5  274.28  5410.7  281.37  5432.1  285.47
#Mann= 6 ,-1 , 0
  4519.8     .12       0  4659.1     .07       0  4767.6     .05       0
  4829.5     .12       0  4888.5     .07       0  4894.5     .12       0
Bank Sta=4867.9,4942.8
XS Rating Curve= 0 ,0
Exp/Cntr=0.3,0.1

Type RM Length L Ch R = 1 ,1928    ,280,280,280
BEGIN DESCRIPTION:
UNT 006 IN BOCR 2.0
END DESCRIPTION:
XS GIS Cut Line= 3
      3675799.61     10605710.19      3675649.61     10605310.19
       3675599.6     10604960.14
#Sta/Elev= 30
  4491.8  278.15  4555.9  269.73  4567.4  267.07  4592.4  264.41  4716.1  254.82
  4748.1   254.3  4843.3   250.1    4887  250.72  4903.9  248.79  4916.3  250.37
  4939.2  250.87  4969.5  249.95  4989.7  250.43  4996.8  248.58  4999.6  248.08
  5002.8  248.58  5009.9  250.19    5020  250.54  5030.1  252.48  5050.3  254.43
  5080.6     255  5090.7  254.24  5100.8  254.97  5131.1  266.82  5141.2  268.38
  5151.3  271.69  5195.6  281.86  5252.3  292.11  5262.4  293.09  5272.6   292.5
#Mann= 4 ,-1 , 0
  4491.8     .12       0  4996.8     .07       0  5002.8     .12       0
  5195.6     .16       0
Bank Sta=4989.7,5009.9
XS Rating Curve= 0 ,0
Exp/Cntr=0.3,0.1