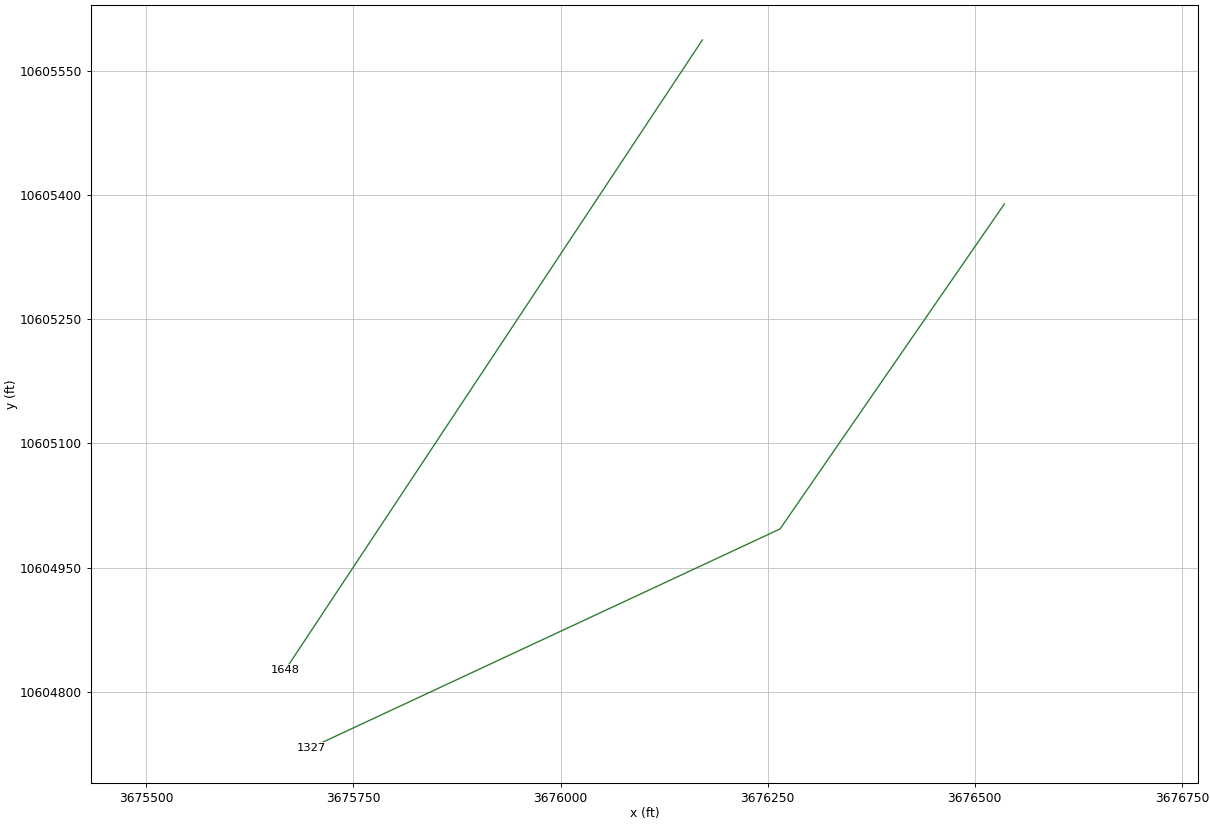
HEC-RAS study UNT 006 IN BOCR.prj: UNT 006 IN BOCR Base Level Engineering

--- UNT 006 IN BOCR.g01 (geometry) --- (continued)

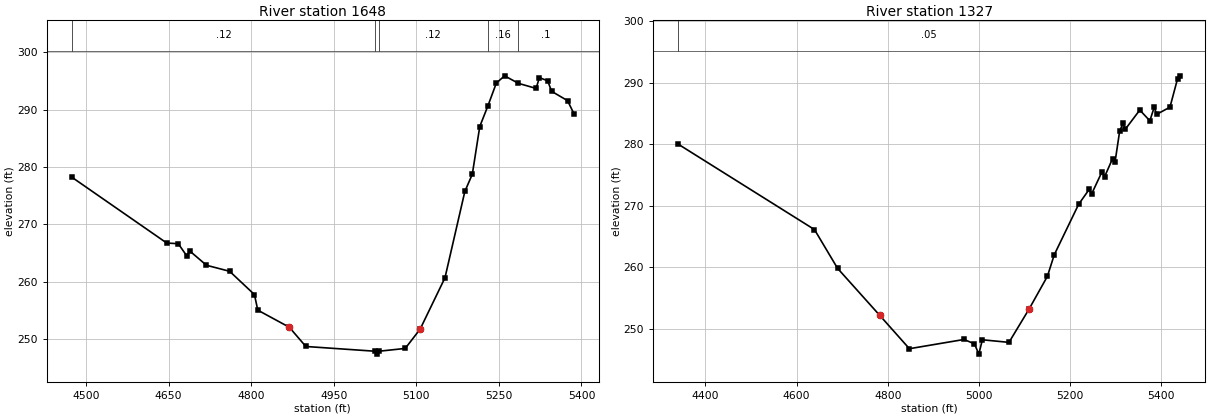
Type RM Length L Ch R = 1 ,1648    ,321,321,321
BEGIN DESCRIPTION:
Mapping XS c9974a38
END DESCRIPTION:
XS GIS Cut Line= 2
      3676171.24     10605586.87      3675667.76     10604826.44
#Sta/Elev= 30
  4474.2  278.23  4646.7  266.77  4667.7  266.65  4682.8  264.57  4688.8  265.36
  4718.9   262.9    4761  261.85    4806   257.8  4812.1  255.09  4869.3  252.12
  4899.4  248.77  5025.8  247.94  5028.5  247.44  5031.8  247.94  5079.9  248.43
    5107  251.79  5152.1  260.72  5188.2  275.74  5201.8  278.75  5215.3  287.04
  5229.9  290.58  5245.4   294.6  5260.4  295.86  5285.6  294.55  5317.6  293.67
  5323.6  295.54  5338.7     295  5345.7  293.17  5374.8  291.54  5386.2   289.3
#Mann= 5 ,-1 , 0
  4474.2     .12       0  5025.8     .07       0  5031.8     .12       0
  5229.9     .16       0  5285.6      .1       0
Bank Sta=4869.3,5107
XS Rating Curve= 0 ,0
Exp/Cntr=0.3,0.1

Type RM Length L Ch R = 1 ,1327    ,0,0,0
BEGIN DESCRIPTION:
UNT 006 IN BOCR 1.0
END DESCRIPTION:
XS GIS Cut Line= 3
      3676535.81     10605388.93      3676264.99     10604996.58
      3675699.02     10604732.69
#Sta/Elev= 30
  4340.5  280.01  4639.3  266.14    4690  259.84  4782.6  252.19  4847.5  246.79
  4967.3  248.29  4990.2  247.58  4999.8  245.91  5007.5  248.24  5065.9  247.82
    5110  253.23  5150.2  258.55  5165.2  262.04  5218.8  270.26  5241.7  272.65
  5247.2  271.93  5270.1  275.55  5275.6  274.72    5293  277.64  5298.5  277.09
  5308.6  282.09  5315.8  283.39  5321.3  282.46  5352.8  285.55  5374.9  283.81
  5384.4     286  5389.9  284.86    5419  286.02  5435.7  290.65  5441.7  291.11
#Mann= 1 ,-1 , 0
  4340.5     .05       0
Bank Sta=4782.6,5110
XS Rating Curve= 0 ,0
Exp/Cntr=0.3,0.1

Chan Stop Cuts=-1
Use User Specified Reach Order=0
Composite Channel Slope=5