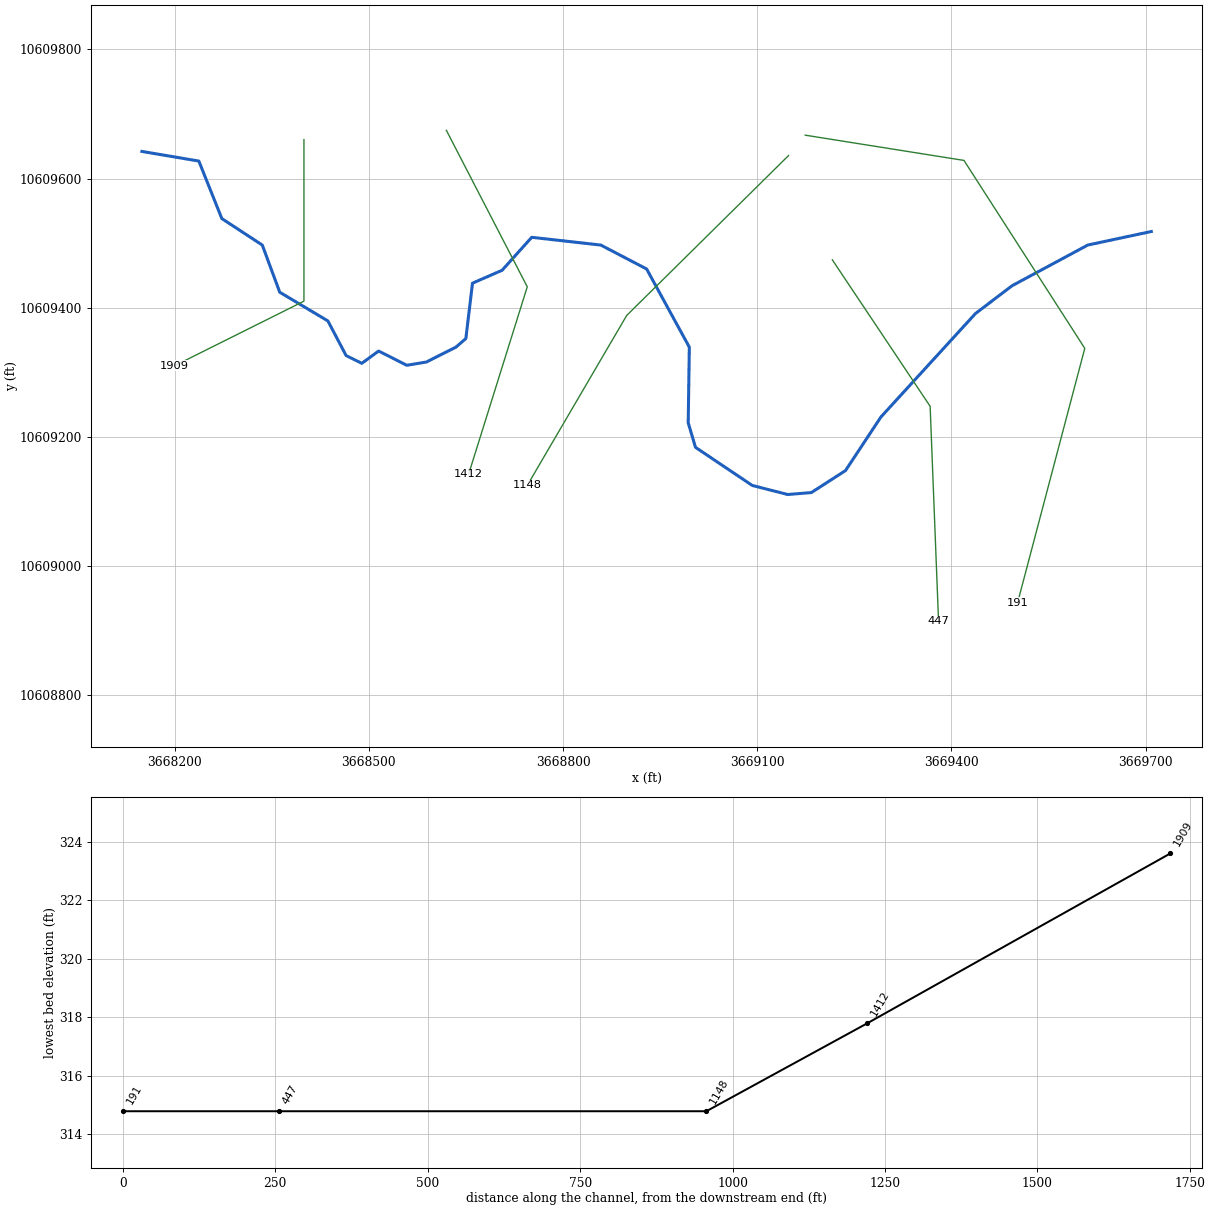
--- UNT 007 IN BOCR.prj (project) ---

Proj Title=UNT 007 IN BOCR Base Level Engineering
Current Plan=p01
Default Exp/Contr=0.3,0.1
English Units
Geom File=g01
Flow File=f01
Plan File=p01
BEGIN DESCRIPTION:
UNT 007 IN BOCR
END DESCRIPTION:

--- UNT 007 IN BOCR.p01 (plan) ---

Plan Title=Multiple Run
Short Identifier=Multiple
Geom File=g01
Flow File=f01
Subcritical Flow
K Sum by GR= 0
Std Step Tol= 0.01
Critical Tol= 0.01
Num of Std Step Trials= 20
Max Error Tol= 0.3
Flow Tol Ratio= 0.001
Split Flow NTrial= 30
Split Flow Tol= 0.02
Split Flow Ratio= 0.02
Log Output Level= 0
Friction Slope Method= 1
Unsteady Friction Slope Method= 2
Unsteady Bridges Friction Slope Method= 1
Parabolic Critical Depth
Global Vel Dist=  1 , 1 , 1
Global Log Level= 0
CheckData=True
Encroach Param= -1, 0, 0, 0
BEGIN DESCRIPTION:
Multiple Run
END DESCRIPTION:

--- UNT 007 IN BOCR.f01 (steady flow) ---

Flow Title=Multiple
Number of Profiles=7
Profile Names=10-year,25-year,50-year,1pct_min,100-year,1pct_plu,500-year
River Rch & RM= UNT 007 IN BOCR,Reach-1,1909
     219     281     330     286     387     523     532
Boundary for River Rch & Prof#=UNT 007 IN BOCR,Reach-1,1
Up Type=0
Dn Type=3
Dn Slope=0.005
Boundary for River Rch & Prof#=UNT 007 IN BOCR,Reach-1,2
Up Type=0
Dn Type=3
Dn Slope=0.005
Boundary for River Rch & Prof#=UNT 007 IN BOCR,Reach-1,3
Up Type=0
Dn Type=3
Dn Slope=0.005
Boundary for River Rch & Prof#=UNT 007 IN BOCR,Reach-1,4
Up Type=0
Dn Type=3
Dn Slope=0.005
Boundary for River Rch & Prof#=UNT 007 IN BOCR,Reach-1,5
Up Type=0
Dn Type=3
Dn Slope=0.005
Boundary for River Rch & Prof#=UNT 007 IN BOCR,Reach-1,6
Up Type=0
Dn Type=3
Dn Slope=0.005
Boundary for River Rch & Prof#=UNT 007 IN BOCR,Reach-1,7
Up Type=0
Dn Type=3
Dn Slope=0.005

--- UNT 007 IN BOCR.g01 (geometry) ---

Geom Title=Existing Conditions

River Reach=UNT 007 IN BOCR,Reach-1
Reach XY= 30
      3668149.25     10609641.90      3668237.25     10609627.00
      3668272.75     10609538.00      3668335.25     10609497.00
      3668362.25     10609424.00      3668436.64     10609379.57
      3668464.75     10609326.00      3668489.00     10609314.00
      3668515.00     10609333.00      3668558.50     10609311.00
      3668588.75     10609316.00      3668634.45     10609339.08
      3668649.73     10609352.28      3668660.00     10609438.00
      3668705.75     10609458.00      3668751.50     10609509.00
      3668858.25     10609497.00      3668929.00     10609460.00
      3668995.00     10609339.00      3668993.25     10609222.00
      3669004.50     10609184.00      3669092.25     10609125.00
      3669147.00     10609111.00      3669183.50     10609114.00
      3669236.25     10609148.00      3669291.00     10609231.00
      3669437.00     10609391.00      3669493.50     10609434.00
      3669610.50     10609497.00      3669708.75     10609518.00

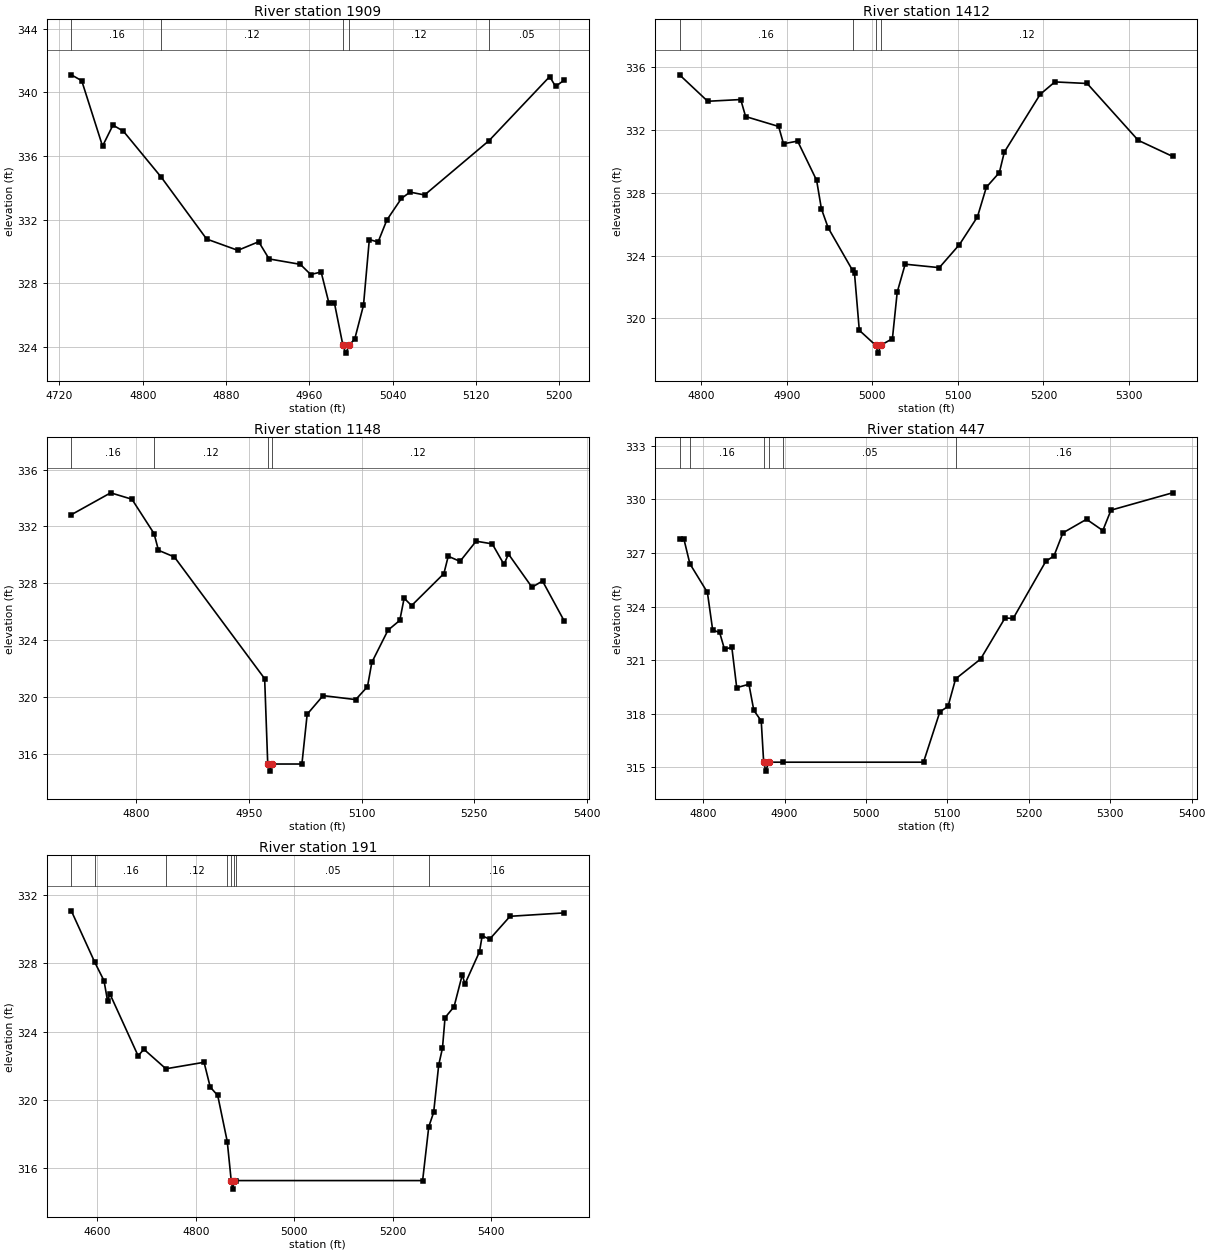
Type RM Length L Ch R = 1,1909,497,497,497
BEGIN DESCRIPTION:
UNT 007 IN BOCR 4.0
END DESCRIPTION:
XS GIS Cut Line= 3
      3668399.61     10609660.16      3668399.61     10609410.19
      3668199.59     10609310.18
#Sta/Elev= 30
  4731.4  341.10  4741.4  340.73  4761.4  336.62  4771.4  337.94  4781.4  337.56
  4818.0  334.65  4861.4  330.78  4891.4  330.07  4911.4  330.61  4921.4  329.53
  4951.4  329.19  4961.4  328.55  4971.4  328.71  4978.9  326.75  4984.2  326.75
  4992.3  324.11  4995.1  323.61  4998.3  324.11  5003.7  324.50  5012.1  326.62
  5017.7  330.75  5026.1  330.59  5034.5  331.97  5048.5  333.33  5056.8  333.73
  5070.8  333.55  5132.8  336.97  5191.0  340.99  5196.6  340.37  5205.0  340.77
#Mann=5,-1,0
  4731.4    0.16       0  4818.0    0.12       0  4992.3    0.07       0
  4998.3    0.12       0  5132.8    0.05       0
Bank Sta=4992.3,4998.3
Exp/Cntr=0.3,0.1

Type RM Length L Ch R = 1,1412,264,264,264
BEGIN DESCRIPTION:
UNT 007 IN BOCR 3.0
END DESCRIPTION:
XS GIS Cut Line= 3
      3668619.63     10609674.56      3668744.62     10609432.39
      3668654.04     10609142.54
#Sta/Elev= 30
  4774.7  335.48  4807.6  333.80  4846.2  333.91  4851.9  332.83  4890.5  332.20
  4896.2  331.10  4912.7  331.27  4934.9  328.78  4940.5  326.97  4948.4  325.76
  4977.0  323.05  4979.2  322.86  4984.8  319.25  5003.9  318.30  5006.7  317.80
  5009.9  318.30  5023.5  318.72  5029.1  321.67  5038.4  323.45  5078.3  323.23
  5101.9  324.70  5122.9  326.46  5133.3  328.34  5148.5  329.27  5154.3  330.57
  5196.2  334.24  5213.4  335.03  5251.1  334.93  5310.8  331.32  5350.9  330.30
#Mann=4,-1,0
  4774.7    0.16       0  4977.0    0.12       0  5003.9    0.07       0
  5009.9    0.12       0
Bank Sta=5003.9,5009.9
Exp/Cntr=0.3,0.1

Type RM Length L Ch R = 1,1148,701,701,701
BEGIN DESCRIPTION:
UNT 007 IN BOCR 2.0
END DESCRIPTION:
XS GIS Cut Line= 3
      3669148.30     10609635.55      3668898.27     10609388.12
      3668744.66     10609125.16
#Sta/Elev= 30
  4713.5  332.82  4765.9  334.36  4794.2  333.91  4823.7  331.49  4829.5  330.32
  4850.7  329.85  4970.9  321.29  4975.0  315.29  4977.8  314.79  4981.0  315.29
  5020.5  315.29  5027.5  318.79  5048.7  320.10  5092.1  319.82  5107.8  320.73
  5113.6  322.44  5135.1  324.70  5150.8  325.39  5156.6  326.95  5166.5  326.43
  5209.5  328.68  5215.3  329.90  5231.0  329.54  5252.4  330.96  5273.9  330.77
  5289.6  329.32  5295.4  330.06  5326.8  327.72  5340.8  328.16  5369.8  325.34
#Mann=4,-1,0
  4713.5    0.16       0  4823.7    0.12       0  4975.0    0.07       0
  4981.0    0.12       0
Bank Sta=4975,4981
Exp/Cntr=0.3,0.1

Type RM Length L Ch R = 1,447,256,256,256
BEGIN DESCRIPTION:
UNT 007 IN BOCR 1.0
END DESCRIPTION:
XS GIS Cut Line= 3
      3669215.97     10609474.07      3669367.02     10609247.50
      3669380.02     10608914.66
#Sta/Elev= 30
  4771.1  327.78  4776.4  327.78  4783.8  326.39  4805.3  324.79  4811.8  322.68
  4820.3  322.55  4826.3  321.61  4835.3  321.72  4841.3  319.46  4856.3  319.65
  4862.3  318.19  4871.4  317.60  4874.4  315.29  4877.1  314.79  4880.4  315.29
  4898.7  315.29  5070.7  315.29  5090.8  318.11  5100.8  318.41  5110.1  319.95
  5140.8  321.06  5170.8  323.36  5180.8  323.33  5220.9  326.53  5230.9  326.83
  5241.9  328.12  5270.9  328.88  5290.9  328.25  5300.9  329.39  5376.5  330.36
#Mann=6,-1,0
  4771.1    0.12       0  4783.8    0.16       0  4874.4   0.033       0
  4880.4    0.16       0  4898.7    0.05       0  5110.1    0.16       0
Bank Sta=4874.4,4880.4
Exp/Cntr=0.3,0.1

Type RM Length L Ch R = 1,191,0,0,0
BEGIN DESCRIPTION:
Mapping XS f4b42b2c
END DESCRIPTION:
XS GIS Cut Line= 4
      3669174.02     10609667.06      3669419.29     10609627.99
      3669605.92     10609337.19      3669502.16     10608943.74
#Sta/Elev= 30
  4547.3  331.07  4595.1  328.05  4613.7  326.98  4620.8  325.81  4625.8  326.20
  4682.9  322.59  4694.7  322.97  4739.3  321.83  4816.8  322.21  4829.3  320.76
  4844.5  320.27  4863.9  317.57  4871.9  315.29  4874.7  314.79  4877.9  315.29
  4881.7  315.29  5260.5  315.29  5273.0  318.44  5282.9  319.28  5293.2  322.06
  5300.8  323.04  5306.0  324.82  5324.3  325.46  5341.1  327.34  5346.3  326.78
  5376.0  328.68  5381.4  329.61  5396.6  329.41  5438.0  330.75  5548.1  330.95
#Mann=8,-1,0
  4547.3    0.12       0  4595.1    0.16       0  4739.3    0.12       0
  4863.9    0.07       0  4871.9   0.033       0  4877.9    0.07       0
  4881.7    0.05       0  5273.0    0.16       0
Bank Sta=4871.9,4877.9
Exp/Cntr=0.3,0.1

Chan Stop Cuts=-1