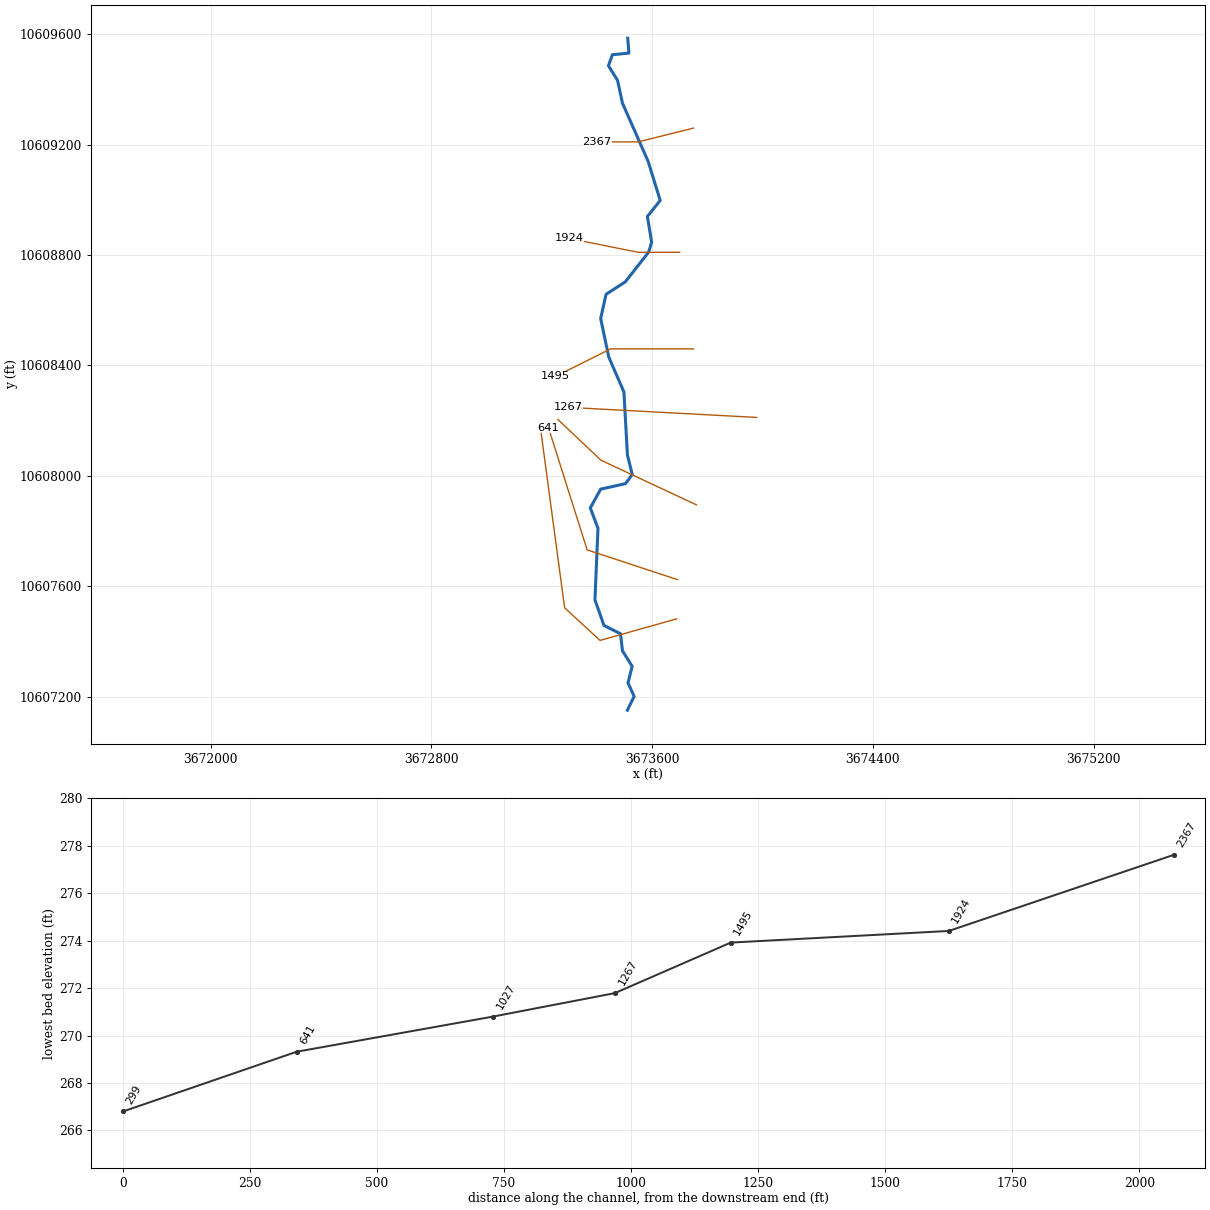
--- UNT 008 IN BOCR.prj (project) ---

Proj Title=UNT 008 IN BOCR Base Level Engineering
Current Plan=p01
Default Exp/Contr=0.3,0.1
English Units
Geom File=g01
Flow File=f01
Plan File=p01
Y Axis Title=Elevation
X Axis Title(PF)=Main Channel Distance
X Axis Title(XS)=Station
BEGIN DESCRIPTION:
UNT 008 IN BOCR
END DESCRIPTION:
DSS Export Rating Curves= 0
DSS Export Rating Curve Sorted= 0
DSS Export Volume Flow Curves= 0
DXF OffsetX= 0
DXF OffsetY= 0
DXF ScaleX= 1
DXF ScaleY= 10

--- UNT 008 IN BOCR.p01 (plan) ---

Plan Title=Multiple Run
Short Identifier=Multiple
Geom File=g01
Flow File=f01
Subcritical Flow
K Sum by GR= 0
Std Step Tol= 0.01
Critical Tol= 0.01
Num of Std Step Trials= 20
Max Error Tol= 0.3
Flow Tol Ratio= 0.001
Split Flow NTrial= 30
Split Flow Tol= 0.02
Split Flow Ratio= 0.02
Log Output Level= 0
Friction Slope Method= 1
Unsteady Friction Slope Method= 2
Unsteady Bridges Friction Slope Method= 1
Parabolic Critical Depth
Global Vel Dist=  1 , 1 , 1
Global Log Level= 0
CheckData=True
Encroach Param= -1, 0, 0, 0
BEGIN DESCRIPTION:
Multiple Run
END DESCRIPTION:

--- UNT 008 IN BOCR.f01 (steady flow) ---

Flow Title=Multiple
Program Version=4.10
Number of Profiles= 7
Profile Names=10-year,25-year,50-year,1pct_min,100-year,1pct_plu,500-year
River Rch & RM=UNT 008 IN BOCR,Reach-1         ,2367
     568     773     944     847    1145    1549    1694
Boundary for River Rch & Prof#=UNT 008 IN BOCR,Reach-1         , 1
Up Type= 0
Dn Type= 3
Dn Slope=0.005
Boundary for River Rch & Prof#=UNT 008 IN BOCR,Reach-1         , 2
Up Type= 0
Dn Type= 3
Dn Slope=0.005
Boundary for River Rch & Prof#=UNT 008 IN BOCR,Reach-1         , 3
Up Type= 0
Dn Type= 3
Dn Slope=0.005
Boundary for River Rch & Prof#=UNT 008 IN BOCR,Reach-1         , 4
Up Type= 0
Dn Type= 3
Dn Slope=0.005
Boundary for River Rch & Prof#=UNT 008 IN BOCR,Reach-1         , 5
Up Type= 0
Dn Type= 3
Dn Slope=0.005
Boundary for River Rch & Prof#=UNT 008 IN BOCR,Reach-1         , 6
Up Type= 0
Dn Type= 3
Dn Slope=0.005
Boundary for River Rch & Prof#=UNT 008 IN BOCR,Reach-1         , 7
Up Type= 0
Dn Type= 3
Dn Slope=0.005
DSS Import GetInterval= 0
DSS Import GetPeak= 0
DSS Import FillOption= 0

--- UNT 008 IN BOCR.g01 (geometry) ---

Geom Title=Existing Conditions
Program Version=4.10

River Reach=UNT 008 IN BOCR ,Reach-1
Reach XY= 30
       3673511.5       10609586.      3673515.75       10609532.
      3673455.75       10609526.      3673441.75       10609486.
      3673474.75       10609433.      3673492.25       10609351.
      3673585.75       10609139.      3673629.25       10608998.
      3673582.75       10608940.      3673598.25       10608847.
       3673587.5       10608811.      3673502.75       10608703.
        3673433.       10608658.       3673413.5       10608570.
      3673442.75       10608431.      3673497.75       10608304.
       3673510.5       10608075.        3673528.       10608005.
      3673503.75       10607972.       3673413.5       10607952.
        3673376.       10607884.      3673403.75       10607810.
      3673392.75       10607551.       3673425.5       10607458.
      3673485.25       10607428.       3673492.5       10607366.
      3673527.75       10607310.       3673512.5       10607250.
      3673534.75       10607201.      3673510.25       10607151.

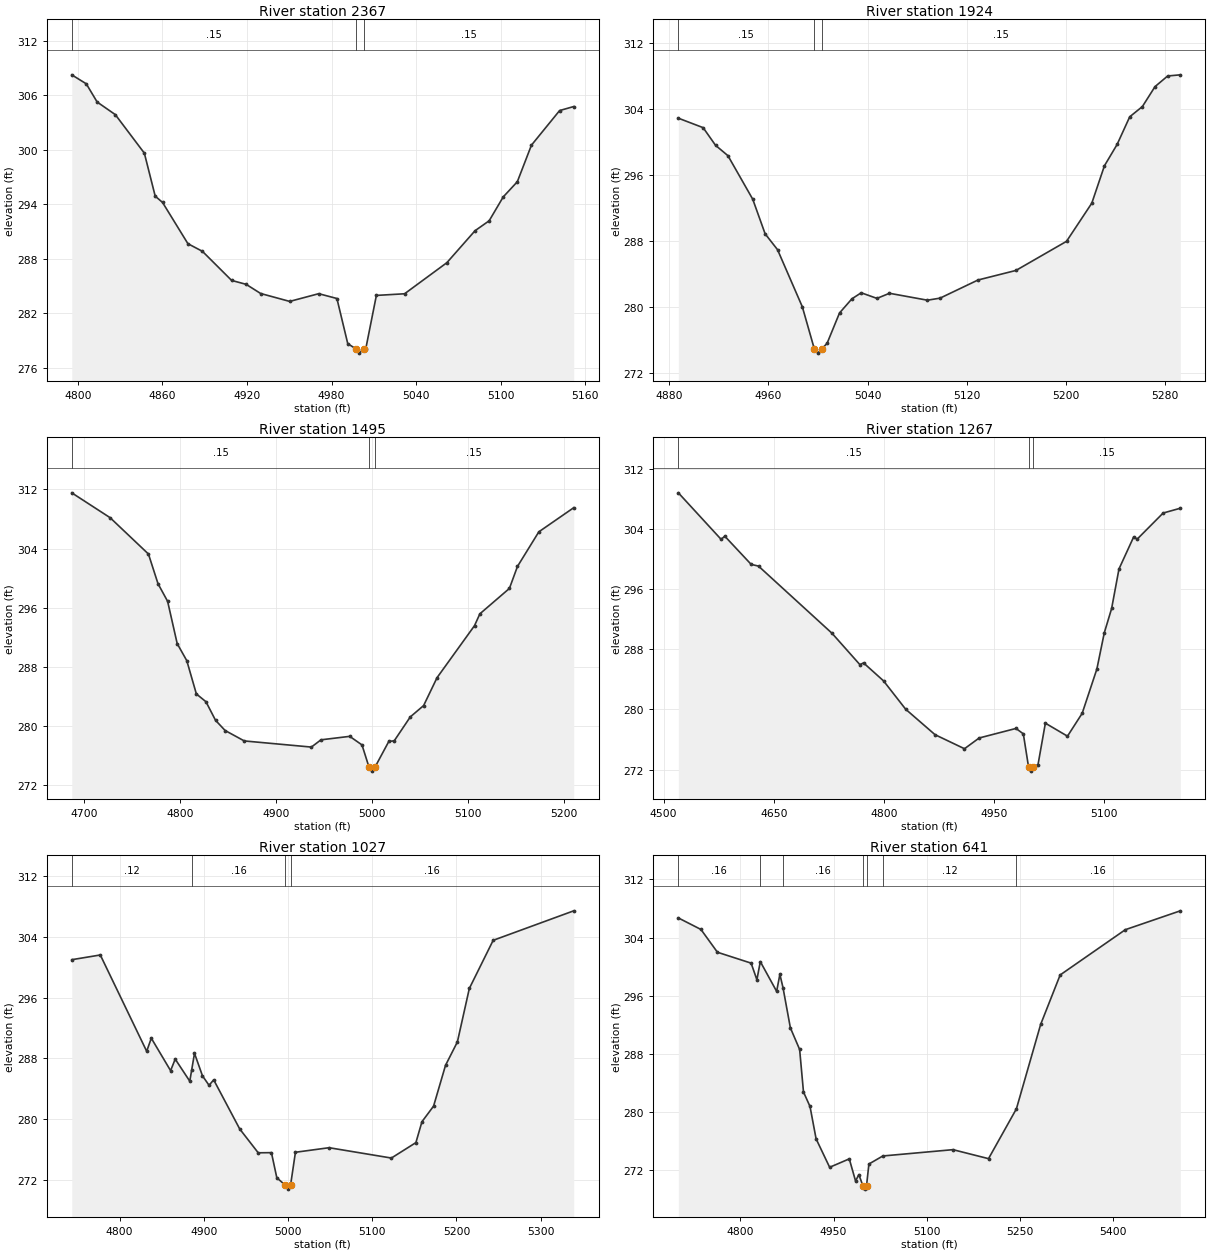
Type RM Length L Ch R = 1 ,2367    ,443,443,443
BEGIN DESCRIPTION:
UNT 008 IN BOCR 4.0
END DESCRIPTION:
XS GIS Cut Line= 3
      3673749.58     10609260.18      3673549.61     10609210.19
      3673399.63     10609210.19
#Sta/Elev= 30
  4795.7  308.24    4806  307.25  4813.7  305.25  4826.6  303.86  4847.2  299.62
  4854.9  294.89  4860.1   294.2  4878.1  289.66  4888.4  288.82  4909.1  285.62
  4919.4  285.19  4929.7  284.18  4950.3  283.31  4970.9  284.16  4983.8  283.63
  4991.5  278.66    4997  278.12  4999.8  277.62    5003  278.12  5004.3  278.12
  5011.8  283.97  5031.8  284.15  5061.8  287.57  5081.8  291.09  5091.8  292.18
  5101.8  294.81  5111.8  296.48  5121.8   300.5  5141.8  304.31  5151.8  304.75
#Mann= 3 ,-1 , 0
  4795.7     .15       0    4997     .05       0    5003     .15       0
Bank Sta=4997,5003
XS Rating Curve= 0 ,0
Exp/Cntr=0.3,0.1

Type RM Length L Ch R = 1 ,1924    ,429,429,429
BEGIN DESCRIPTION:
UNT 008 IN BOCR 3.0
END DESCRIPTION:
XS GIS Cut Line= 3
      3673699.56     10608810.19      3673549.61     10608810.19
      3673299.61     10608860.19
#Sta/Elev= 30
  4887.3  302.91  4907.3  301.76  4917.3  299.62  4927.3  298.36  4947.3  293.08
  4957.3  288.88  4967.3  286.96  4987.3  280.03    4997  274.91  4999.8  274.41
    5003  274.91  5007.3  275.61  5017.3  279.28  5027.3     281  5034.8  281.73
  5047.5  281.05  5057.6  281.67  5088.2  280.83  5098.4  281.08    5129  283.28
  5159.6  284.44  5200.4  287.97  5220.8   292.6    5231  297.14  5241.2  299.72
  5251.4  303.08  5261.6  304.32  5271.8  306.74    5282  308.03  5292.2  308.17
#Mann= 3 ,-1 , 0
  4887.3     .15       0    4997     .05       0    5003     .15       0
Bank Sta=4997,5003
XS Rating Curve= 0 ,0
Exp/Cntr=0.3,0.1

Type RM Length L Ch R = 1 ,1495    ,228,228,228
BEGIN DESCRIPTION:
UNT 008 IN BOCR 2.0
END DESCRIPTION:
XS GIS Cut Line= 3
      3673749.66     10608460.19      3673449.61     10608460.19
      3673249.57     10608360.17
#Sta/Elev= 30
  4686.8  311.53  4726.8  308.17  4766.8  303.26  4776.8  299.24  4786.8  296.87
  4796.8  291.15  4806.8  288.85  4816.8  284.35  4826.8   283.3  4836.8  280.79
  4846.8  279.41  4866.8     278  4936.8  277.17  4946.8  278.15  4976.8  278.62
  4989.6  277.46    4997  274.42  4999.8  273.92    5003  274.42  5017.6  277.94
  5023.2  278.01    5040  281.25  5053.9  282.78  5067.9  286.55    5107  293.58
  5112.6  295.18  5143.4  298.61  5151.8  301.58  5174.1  306.26  5210.5  309.52
#Mann= 3 ,-1 , 0
  4686.8     .15       0    4997     .05       0    5003     .15       0
Bank Sta=4997,5003
XS Rating Curve= 0 ,0
Exp/Cntr=0.3,0.1

Type RM Length L Ch R = 1 ,1267    ,240,240,240
BEGIN DESCRIPTION:
Mapping XS 627c85ce
END DESCRIPTION:
XS GIS Cut Line= 2
      3673978.55     10608211.86      3673296.22     10608248.32
#Sta/Elev= 30
  4520.2  308.82  4578.4  302.63  4583.4  303.05  4619.3   299.3  4629.3  299.07
  4729.4  290.13  4767.3  285.96  4772.3  286.19  4799.5   283.8  4829.6  280.03
  4869.6  276.64  4909.7  274.77  4929.7   276.2  4979.8  277.47  4989.8  276.75
    4997  272.29  4999.8  271.79    5003  272.29  5009.8  272.66  5019.8  278.17
  5049.9  276.44  5069.9  279.48  5089.9  285.37    5100  290.19    5110  293.43
    5120  298.69  5139.9  302.93  5144.9  302.67  5180.1  306.13  5203.5  306.77
#Mann= 3 ,-1 , 0
  4520.2     .15       0    4997     .05       0    5003     .15       0
Bank Sta=4997,5003
XS Rating Curve= 0 ,0
Exp/Cntr=0.3,0.1

Type RM Length L Ch R = 1 ,1027    ,386,386,386
BEGIN DESCRIPTION:
Mapping XS 5b15e404
END DESCRIPTION:
XS GIS Cut Line= 3
       3673760.3     10607895.17      3673414.79     10608056.65
      3673258.54     10608204.21
#Sta/Elev= 30
  4743.1  300.99    4777  301.61  4832.1  288.94  4837.6  290.66  4860.5  286.39
    4866  287.91  4883.3     285  4885.6  286.51  4888.9  288.67  4898.4   285.7
  4906.2  284.46  4911.7  285.18  4942.6  278.72  4964.6  275.58  4980.3   275.6
  4986.7  272.29    4997   271.3  4999.8   270.8    5003   271.3  5008.8  275.65
  5048.8  276.25  5122.8  274.89  5151.9  276.92  5159.1  279.67  5172.9  281.72
  5187.1  287.09  5201.2  290.17  5215.4  297.21  5243.7  303.54  5339.4  307.42
#Mann= 4 ,-1 , 0
  4743.1     .12       0  4885.6     .16       0    4997     .07       0
    5003     .16       0
Bank Sta=4997,5003
XS Rating Curve= 0 ,0
Exp/Cntr=0.3,0.1

Type RM Length L Ch R = 1 ,641     ,342,342,342
BEGIN DESCRIPTION:
Mapping XS d8db30a6
END DESCRIPTION:
XS GIS Cut Line= 3
      3673690.87     10607624.34      3673364.44     10607731.99
      3673224.41     10608174.55
#Sta/Elev= 30
  4700.1   306.7  4736.5  305.11    4763  301.97  4817.2  300.47  4826.5  298.18
    4832  300.68  4858.3  296.58  4863.5  298.93  4868.5   297.1  4880.4  291.55
  4895.3  288.57  4901.5  282.71    4912  280.71  4921.8  276.25  4943.6  272.33
  4975.2  273.49  4985.3  270.44  4990.6  271.32    4997  269.82  4999.8  269.32
    5003  269.82  5006.8  272.78  5029.2  273.89  5142.1  274.76  5199.3  273.52
  5244.2  280.39  5283.2  292.02  5314.6  298.84  5419.5  305.08    5508  307.68
#Mann= 7 ,-1 , 0
  4700.1     .16       0    4832     .12       0  4868.5     .16       0
    4997     .07       0    5003     .16       0  5029.2     .12       0
  5244.2     .16       0
Bank Sta=4997,5003
XS Rating Curve= 0 ,0
Exp/Cntr=0.3,0.1

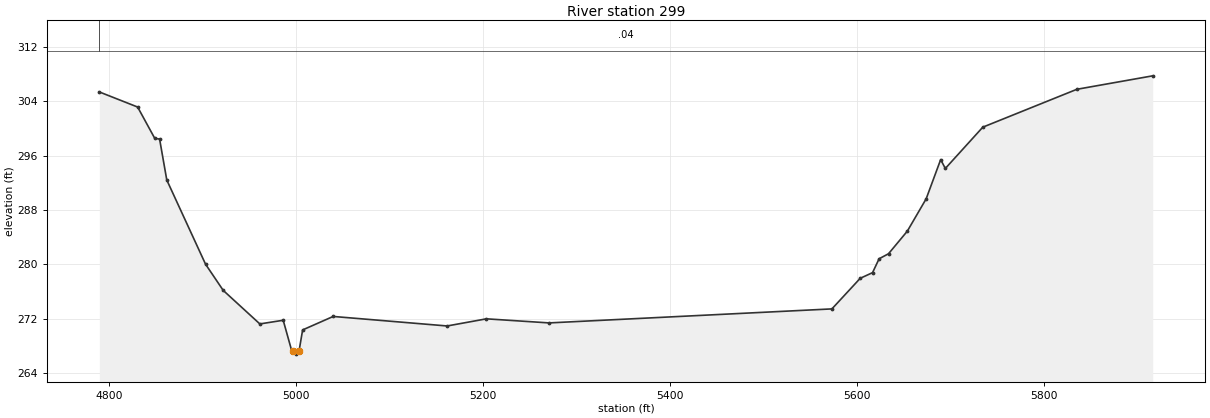
Type RM Length L Ch R = 1 ,299     ,0,0,0
BEGIN DESCRIPTION:
UNT 008 IN BOCR 1.0
END DESCRIPTION:
XS GIS Cut Line= 4
      3673689.07     10607481.99      3673411.31     10607403.87
      3673282.84     10607521.93      3673194.45     10608180.51
#Sta/Elev= 30
  4789.2  305.35  4830.2  303.13  4848.5  298.53  4853.7  298.42  4861.4   292.4
  4902.9  280.02  4921.8  276.17    4961  271.24    4986  271.78  4995.1   267.3
    4997   267.3  4999.8   266.8    5003   267.3  5006.8  270.36  5039.5  272.34
  5161.5  270.94  5203.5  271.99  5270.6  271.39  5573.3  273.45  5603.6  277.95
  5616.8  278.78  5623.8  280.82  5633.9  281.56    5654  284.88  5674.2  289.64
  5689.7   295.4  5694.7   294.1  5734.8  300.17  5835.5  305.74  5916.7  307.72
#Mann= 1 ,-1 , 0
  4789.2     .04       0
Bank Sta=4997,5003
XS Rating Curve= 0 ,0
Exp/Cntr=0.3,0.1

Chan Stop Cuts=-1
Use User Specified Reach Order=0
Composite Channel Slope=5