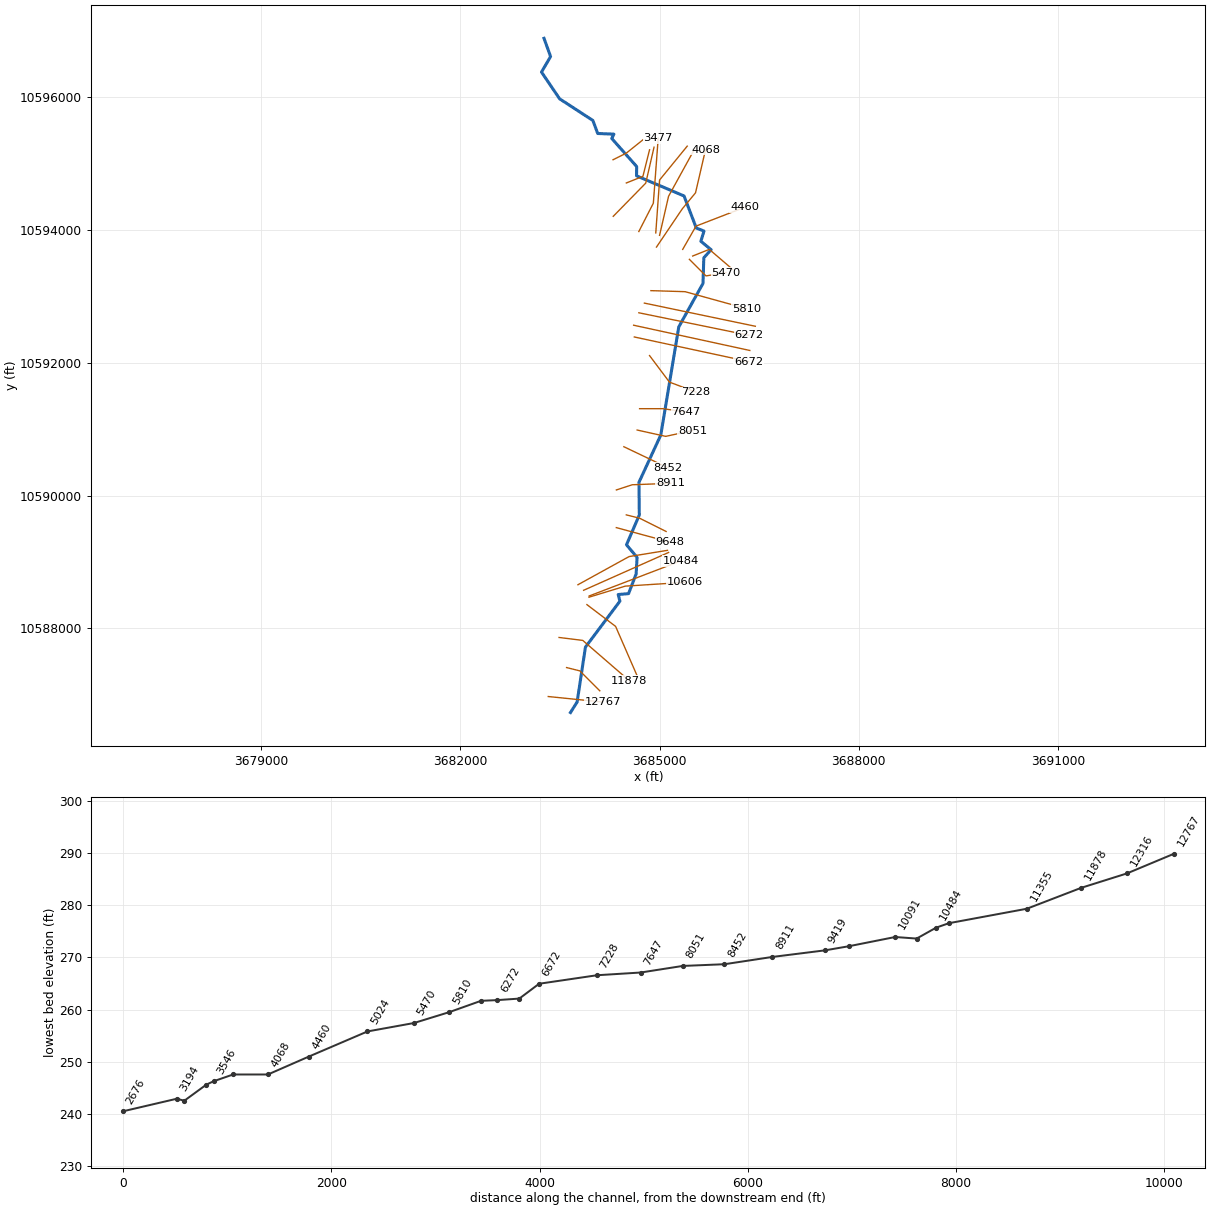
--- UNT 010 IN BOCR.prj (project) ---

Proj Title=UNT 010 IN BOCR Base Level Engineering
Current Plan=p01
Default Exp/Contr=0.3,0.1
English Units
Geom File=g01
Flow File=f01
Plan File=p01
Y Axis Title=Elevation
X Axis Title(PF)=Main Channel Distance
X Axis Title(XS)=Station
BEGIN DESCRIPTION:
UNT 010 IN BOCR
END DESCRIPTION:
DSS Export Rating Curves= 0
DSS Export Rating Curve Sorted= 0
DSS Export Volume Flow Curves= 0
DXF OffsetX= 0
DXF OffsetY= 0
DXF ScaleX= 1
DXF ScaleY= 10

--- UNT 010 IN BOCR.p01 (plan) ---

Plan Title=Multiple Run
Short Identifier=Multiple
Geom File=g01
Flow File=f01
Subcritical Flow
K Sum by GR= 0
Std Step Tol= 0.01
Critical Tol= 0.01
Num of Std Step Trials= 20
Max Error Tol= 0.3
Flow Tol Ratio= 0.001
Split Flow NTrial= 30
Split Flow Tol= 0.02
Split Flow Ratio= 0.02
Log Output Level= 0
Friction Slope Method= 1
Unsteady Friction Slope Method= 2
Unsteady Bridges Friction Slope Method= 1
Parabolic Critical Depth
Global Vel Dist=  1 , 1 , 1
Global Log Level= 0
CheckData=True
Encroach Param= -1, 0, 0, 0
BEGIN DESCRIPTION:
Multiple Run
END DESCRIPTION:

--- UNT 010 IN BOCR.f01 (steady flow) ---

Flow Title=Multiple
Program Version=4.10
Number of Profiles= 7
Profile Names=10-year,25-year,50-year,1pct_min,100-year,1pct_plu,500-year
River Rch & RM=UNT 010 IN BOCR,Reach-1         ,12767
     496     666     805     716     968    1309    1404
River Rch & RM=UNT 010 IN BOCR,Reach-1         ,11355
     710     970    1186    1064    1439    1946    2128
River Rch & RM=UNT 010 IN BOCR,Reach-1         ,3265
     820    1127    1383    1245    1684    2277    2507
Boundary for River Rch & Prof#=UNT 010 IN BOCR,Reach-1         , 1
Up Type= 0
Dn Type= 3
Dn Slope=0.005
Boundary for River Rch & Prof#=UNT 010 IN BOCR,Reach-1         , 2
Up Type= 0
Dn Type= 3
Dn Slope=0.005
Boundary for River Rch & Prof#=UNT 010 IN BOCR,Reach-1         , 3
Up Type= 0
Dn Type= 3
Dn Slope=0.005
Boundary for River Rch & Prof#=UNT 010 IN BOCR,Reach-1         , 4
Up Type= 0
Dn Type= 3
Dn Slope=0.005
Boundary for River Rch & Prof#=UNT 010 IN BOCR,Reach-1         , 5
Up Type= 0
Dn Type= 3
Dn Slope=0.005
Boundary for River Rch & Prof#=UNT 010 IN BOCR,Reach-1         , 6
Up Type= 0
Dn Type= 3
Dn Slope=0.005
Boundary for River Rch & Prof#=UNT 010 IN BOCR,Reach-1         , 7
Up Type= 0
Dn Type= 3
Dn Slope=0.005
DSS Import GetInterval= 0
DSS Import GetPeak= 0
DSS Import FillOption= 0

--- UNT 010 IN BOCR.g01 (geometry) ---

Geom Title=Existing Conditions

River Reach=UNT 010 IN BOCR,Reach-1
Reach XY= 30
      3683658.75     10586733.00      3683758.50     10586891.00
      3683883.75     10587718.00      3684403.00     10588410.00
      3684377.50     10588510.00      3684533.75     10588524.00
      3684647.75     10588821.00      3684661.50     10589070.00
      3684502.00     10589260.00      3684695.50     10589707.00
      3684690.25     10590201.00      3685019.25     10590914.00
      3685290.25     10592543.00      3685654.75     10593197.00
      3685667.50     10593584.00      3685777.25     10593705.00
      3685623.00     10593832.00      3685669.75     10593986.00
      3685553.75     10594032.00      3685369.25     10594515.00
      3684653.50     10594818.00      3684655.75     10594958.00
      3684280.75     10595380.00      3684312.25     10595446.00
      3684068.75     10595456.00      3683995.75     10595652.00
      3683495.00     10595978.00      3683221.75     10596381.00
      3683358.50     10596615.00      3683259.50     10596890.00

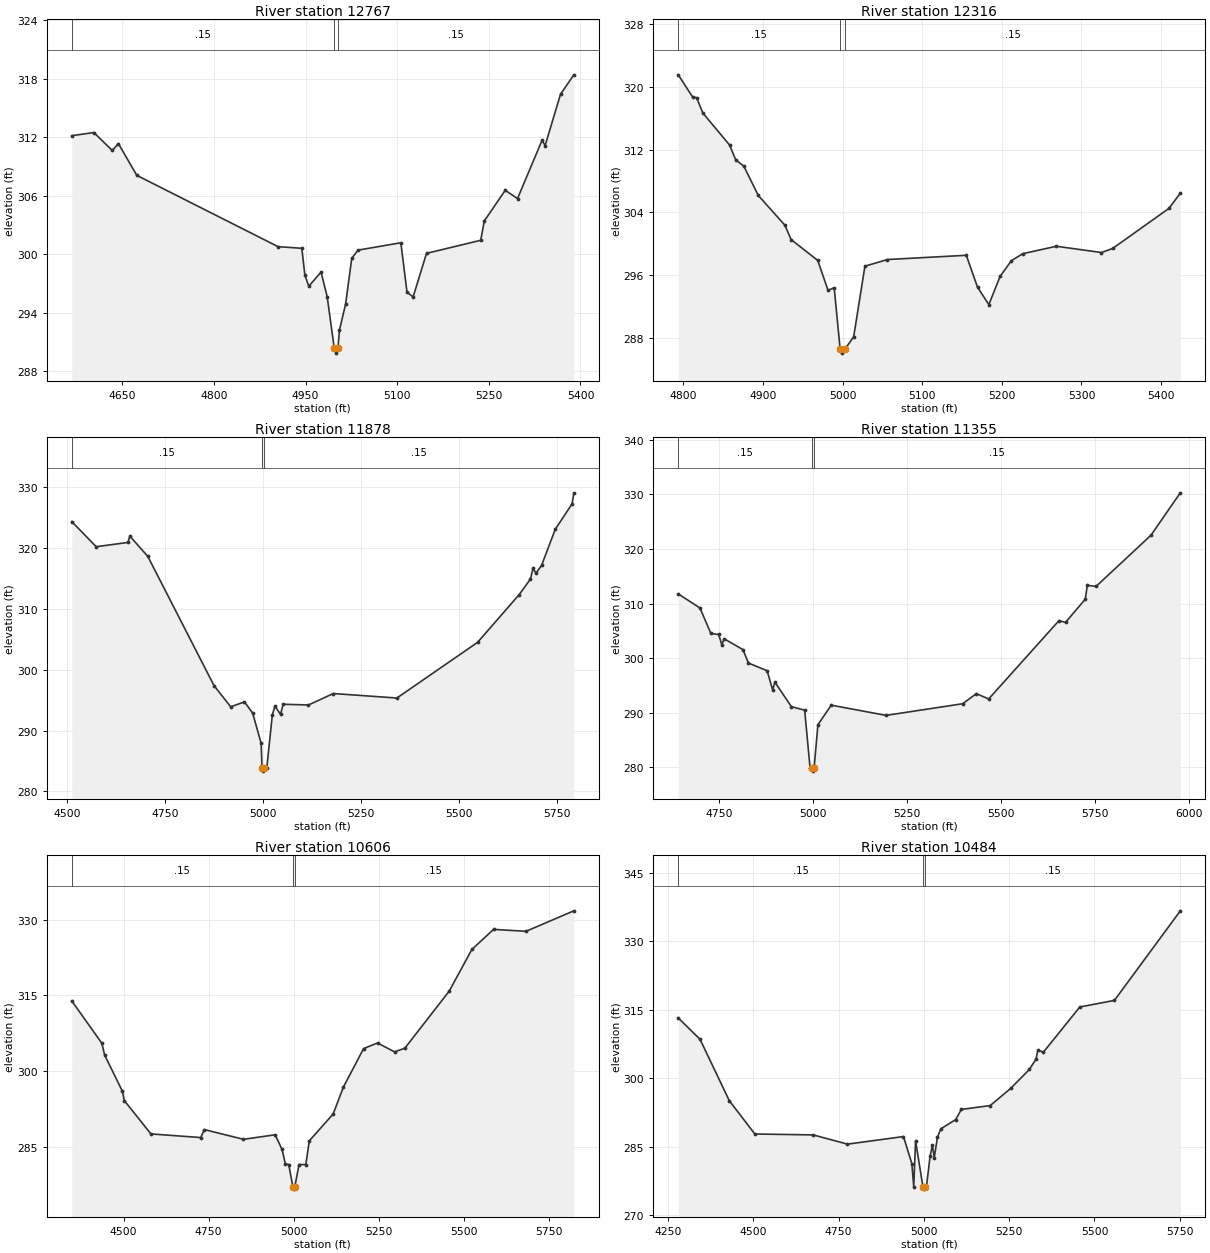
Type RM Length L Ch R = 1,12767,451,451,451
BEGIN DESCRIPTION:
UNT 010 IN BOCR 27.0
END DESCRIPTION:
XS GIS Cut Line= 2
      3683323.64     10586973.74      3684141.31     10586890.41
#Sta/Elev= 30
  4567.3  312.15  4603.5  312.47  4633.6  310.63  4643.7  311.33  4673.8  308.08
  4905.0  300.77  4943.9  300.60  4948.9  297.85  4955.3  296.71  4975.4  298.16
  4985.4  295.64  4997.0  290.35  4999.8  289.85  5003.0  290.35  5005.5  292.20
  5015.6  294.89  5025.6  299.56  5035.7  300.41  5106.0  301.17  5116.1  296.10
  5126.1  295.61  5148.0  300.08  5236.7  301.42  5242.6  303.40  5276.9  306.55
  5297.0  305.70  5337.1  311.67  5342.2  311.14  5367.4  316.40  5389.2  318.39
#Mann=3,-1,0
  4567.3    0.15       0  4997.0    0.05       0  5003.0    0.15       0
Bank Sta=4997,5003
Exp/Cntr=0.3,0.1

Type RM Length L Ch R = 1,12316,438,438,438
BEGIN DESCRIPTION:
UNT 010 IN BOCR 26.0
END DESCRIPTION:
XS GIS Cut Line= 3
      3683599.65     10587410.18      3683799.61     10587360.19
      3684099.63     10587060.17
#Sta/Elev= 30
  4793.7  321.53  4811.7  318.72  4816.8  318.61  4824.6  316.67  4858.1  312.60
  4865.8  310.72  4876.1  309.89  4894.2  306.17  4927.7  302.37  4935.4  300.55
  4968.9  297.89  4981.8  294.08  4989.5  294.42  4997.0  286.59  4999.8  286.09
  5003.0  286.59  5014.0  288.18  5028.1  297.16  5056.4  298.01  5155.4  298.55
  5169.5  294.48  5183.7  292.27  5197.8  295.86  5211.9  297.85  5226.1  298.75
  5268.5  299.70  5325.1  298.90  5339.2  299.42  5409.9  304.53  5424.1  306.46
#Mann=3,-1,0
  4793.7    0.15       0  4997.0    0.05       0  5003.0    0.15       0
Bank Sta=4997,5003
Exp/Cntr=0.3,0.1

Type RM Length L Ch R = 1,11878,523,523,523
BEGIN DESCRIPTION:
UNT 010 IN BOCR 25.0
END DESCRIPTION:
XS GIS Cut Line= 3
      3683486.79     10587863.39      3683843.55     10587819.12
      3684541.32     10587215.08
#Sta/Elev= 30
  4511.2  324.27  4573.6  320.15  4654.5  320.85  4659.6  321.89  4705.5  318.55
  4874.4  297.38  4917.2  293.89  4952.3  294.70  4973.1  292.87  4995.0  287.90
  4997.0  283.84  4999.8  283.34  5003.0  283.84  5009.3  283.84  5023.5  292.57
  5030.2  294.02  5044.4  292.64  5051.0  294.31  5115.7  294.19  5179.3  296.07
  5341.7  295.33  5547.8  304.47  5654.2  312.31  5682.7  314.84  5689.3  316.59
  5696.9  315.80  5711.2  317.09  5746.3  323.03  5789.1  327.18  5793.6  328.99
#Mann=3,-1,0
  4511.2    0.15       0  4997.0    0.05       0  5003.0    0.15       0
Bank Sta=4997,5003
Exp/Cntr=0.3,0.1

Type RM Length L Ch R = 1,11355,749,749,749
BEGIN DESCRIPTION:
UNT 010 IN BOCR 24.0
END DESCRIPTION:
XS GIS Cut Line= 3
      3683906.05     10588358.18      3684338.34     10588030.06
      3684655.33     10587302.54
#Sta/Elev= 30
  4641.5  311.76  4699.3  309.18  4728.4  304.52  4749.2  304.33  4757.5  302.44
  4763.7  303.54  4813.7  301.57  4828.2  299.11  4878.1  297.70  4892.7  294.21
  4898.9  295.60  4942.6  291.13  4978.0  290.48  4992.5  279.83  4997.0  279.83
  4999.8  279.33  5003.0  279.83  5013.3  287.83  5048.7  291.40  5194.7  289.53
  5398.5  291.66  5435.0  293.51  5467.7  292.53  5654.6  306.85  5672.5  306.56
  5724.8  310.79  5730.3  313.32  5753.7  313.14  5899.7  322.49  5977.8  330.25
#Mann=3,-1,0
  4641.5    0.15       0  4997.0    0.05       0  5003.0    0.15       0
Bank Sta=4997,5003
Exp/Cntr=0.3,0.1

Type RM Length L Ch R = 1,10606,122,122,122
BEGIN DESCRIPTION:
UNT 010 IN BOCR 23.0
END DESCRIPTION:
XS GIS Cut Line= 3
      3683937.33     10588470.17      3684484.17     10588636.83
      3685384.88     10588694.10
#Sta/Elev= 30
  4348.0  313.90  4436.5  305.48  4444.5  303.15  4496.7  295.97  4502.2  294.13
  4580.4  287.51  4726.7  286.79  4737.2  288.37  4852.2  286.44  4945.2  287.34
  4965.2  284.46  4975.2  281.56  4985.2  281.44  4997.0  277.06  4999.8  276.56
  5003.0  277.06  5015.3  281.44  5035.3  281.43  5045.4  286.14  5115.5  291.46
  5145.6  296.81  5204.8  304.43  5245.8  305.55  5295.9  303.78  5325.9  304.51
  5456.2  315.83  5522.7  324.09  5586.4  328.08  5681.7  327.70  5822.2  331.76
#Mann=3,-1,0
  4348.0    0.15       0  4997.0    0.05       0  5003.0    0.15       0
Bank Sta=4997,5003
Exp/Cntr=0.3,0.1

Type RM Length L Ch R = 1,10484,187,187,187
BEGIN DESCRIPTION:
UNT 010 IN BOCR 22.0
END DESCRIPTION:
XS GIS Cut Line= 2
      3683939.91     10588488.39      3685314.73     10589014.37
#Sta/Elev= 30
  4279.6  313.19  4343.5  308.51  4429.2  295.09  4504.1  287.78  4675.4  287.58
  4775.8  285.56  4940.0  287.22  4964.5  281.30  4970.1  276.21  4975.4  286.34
  4997.0  276.21  4999.8  275.71  5003.0  276.21  5007.3  276.27  5018.1  282.95
  5024.8  285.32  5030.2  282.60  5039.5  287.06  5049.5  288.91  5093.0  290.93
  5109.6  293.16  5194.4  294.01  5254.6  297.79  5309.3  301.93  5328.6  304.19
  5334.0  306.17  5350.0  305.68  5457.0  315.59  5558.4  317.03  5751.6  336.64
#Mann=3,-1,0
  4279.6    0.15       0  4997.0    0.05       0  5003.0    0.15       0
Bank Sta=4997,5003
Exp/Cntr=0.3,0.1

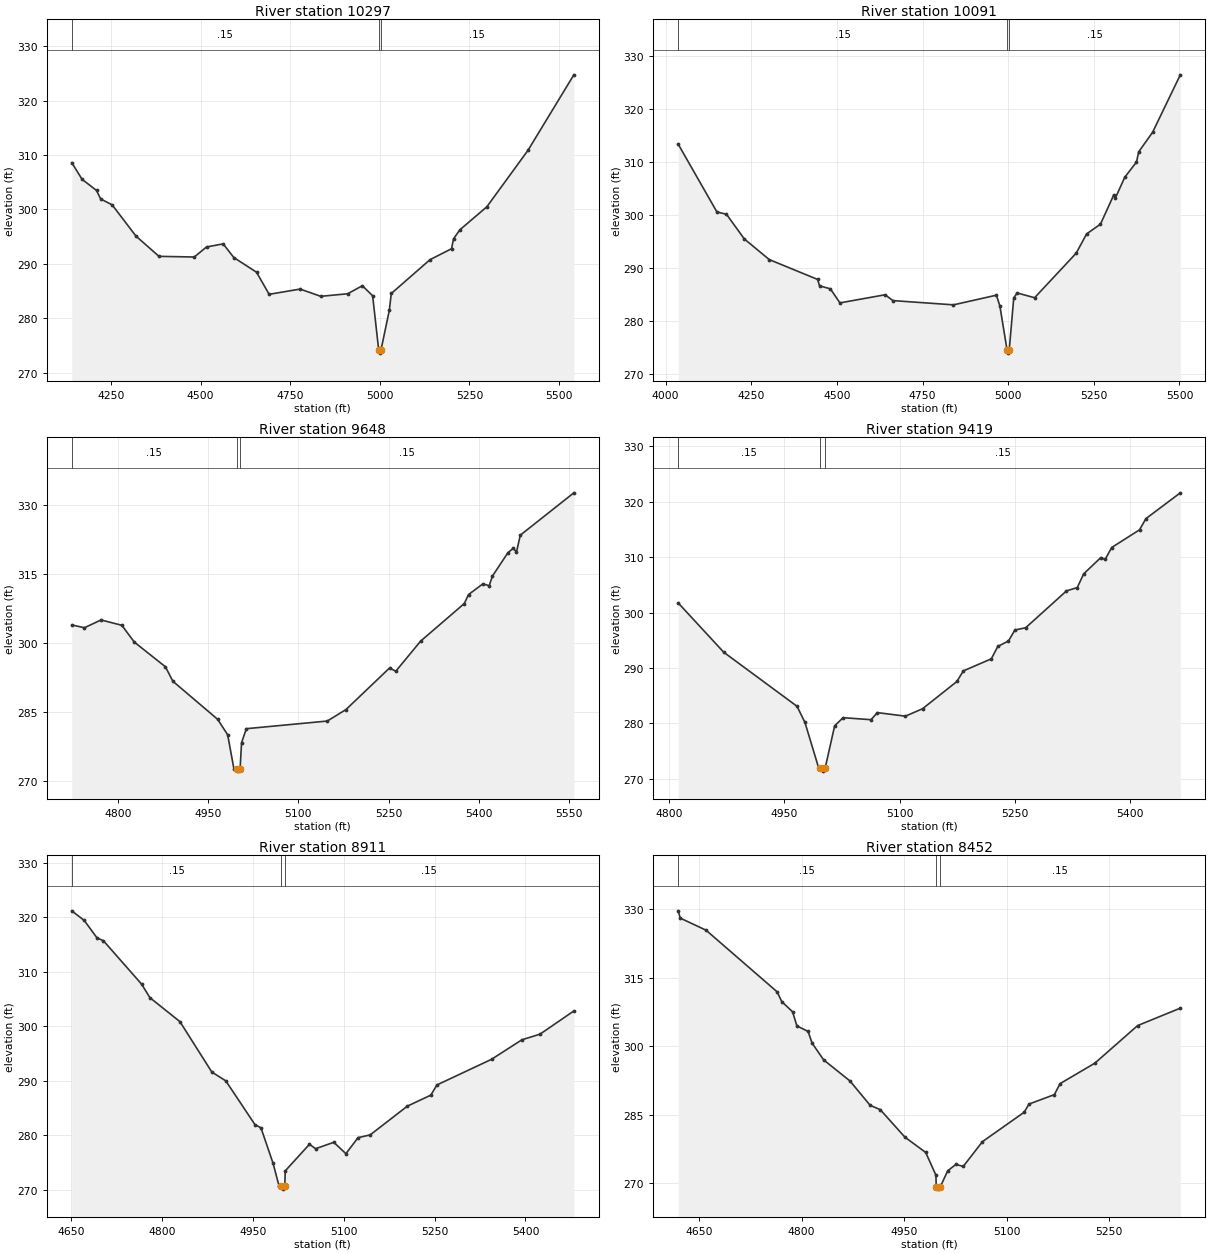
Type RM Length L Ch R = 1,10297,206,206,206
BEGIN DESCRIPTION:
Mapping XS 269a40b9
END DESCRIPTION:
XS GIS Cut Line= 2
      3683856.59     10588574.34      3685136.24     10589143.94
#Sta/Elev= 30
  4140.6  308.59  4169.3  305.54  4209.6  303.49  4221.2  301.93  4253.4  300.84
  4319.7  295.11  4383.9  291.39  4482.4  291.27  4516.5  293.11  4563.0  293.68
  4592.7  291.17  4656.0  288.48  4691.2  284.42  4777.7  285.38  4835.1  284.05
  4910.3  284.52  4951.3  286.00  4980.0  284.15  4997.0  274.12  4999.8  273.62
  5003.0  274.12  5026.5  281.47  5032.0  284.57  5140.0  290.78  5200.1  292.79
  5205.7  294.62  5223.4  296.27  5298.6  300.49  5413.6  310.88  5541.3  324.72
#Mann=3,-1,0
  4140.6    0.15       0  4997.0    0.05       0  5003.0    0.15       0
Bank Sta=4997,5003
Exp/Cntr=0.3,0.1

Type RM Length L Ch R = 1,10091,443,443,443
BEGIN DESCRIPTION:
Mapping XS cac93bf6
END DESCRIPTION:
XS GIS Cut Line= 3
      3683770.66     10588657.68      3684541.46     10589082.14
      3685119.56     10589175.89
#Sta/Elev= 30
  4036.9  313.29  4149.9  300.52  4177.6  300.10  4229.8  295.44  4302.6  291.55
  4443.7  287.81  4449.4  286.60  4480.9  286.04  4509.0  283.39  4640.8  284.92
  4663.6  283.82  4840.4  283.02  4965.6  284.84  4975.8  282.81  4997.0  274.42
  4999.8  273.92  5003.0  274.42  5016.3  284.33  5026.4  285.26  5077.1  284.36
  5198.6  292.76  5229.0  296.39  5269.5  298.23  5307.9  303.69  5312.9  303.15
  5340.5  307.08  5374.6  309.93  5381.0  311.86  5421.5  315.53  5502.5  326.37
#Mann=3,-1,0
  4036.9    0.15       0  4997.0    0.05       0  5003.0    0.15       0
Bank Sta=4997,5003
Exp/Cntr=0.3,0.1

Type RM Length L Ch R = 1,9648,229,229,229
BEGIN DESCRIPTION:
UNT 010 IN BOCR 21.0
END DESCRIPTION:
XS GIS Cut Line= 2
      3684349.24     10589518.35      3685155.56     10589299.86
#Sta/Elev= 30
  4722.9  303.89  4744.0  303.28  4771.6  304.97  4806.2  303.81  4826.9  300.17
  4878.7  294.81  4891.1  291.67  4965.6  283.41  4982.3  280.04  4992.7  272.66
  4997.0  272.66  4999.8  272.16  5003.0  272.66  5005.4  278.33  5013.4  281.37
  5148.1  283.03  5179.2  285.53  5251.7  294.55  5262.0  293.84  5303.4  300.38
  5376.0  308.53  5383.1  310.48  5407.1  312.82  5417.4  312.39  5422.9  314.50
  5448.5  319.55  5457.6  320.55  5462.8  319.68  5469.2  323.37  5558.3  332.56
#Mann=3,-1,0
  4722.9    0.15       0  4997.0    0.05       0  5003.0    0.15       0
Bank Sta=4997,5003
Exp/Cntr=0.3,0.1

Type RM Length L Ch R = 1,9419,508,508,508
BEGIN DESCRIPTION:
UNT 010 IN BOCR 20.0
END DESCRIPTION:
XS GIS Cut Line= 3
      3684499.64     10589710.18      3684699.61     10589660.19
      3685099.57     10589460.21
#Sta/Elev= 30
  4811.9  301.72  4871.1  292.83  4966.5  283.07  4976.8  280.15  4994.8  271.87
  4997.0  271.87  4999.8  271.37  5003.0  271.87  5015.4  279.53  5026.4  281.02
  5062.7  280.65  5071.1  281.93  5107.5  281.29  5129.8  282.63  5174.5  287.55
  5182.9  289.46  5219.3  291.64  5227.7  293.87  5241.6  294.86  5250.0  296.84
  5264.0  297.25  5317.1  303.90  5331.1  304.50  5339.5  306.98  5361.8  309.92
  5367.4  309.57  5375.8  311.72  5412.1  314.92  5420.5  316.95  5465.2  321.60
#Mann=3,-1,0
  4811.9    0.15       0  4997.0    0.05       0  5003.0    0.15       0
Bank Sta=4997,5003
Exp/Cntr=0.3,0.1

Type RM Length L Ch R = 1,8911,459,459,459
BEGIN DESCRIPTION:
UNT 010 IN BOCR 19.0
END DESCRIPTION:
XS GIS Cut Line= 3
      3684350.02     10590085.82      3684588.77     10590163.96
      3685165.36     10590185.63
#Sta/Elev= 30
  4651.6  321.21  4672.2  319.44  4693.3  316.23  4703.8  315.72  4766.9  307.73
  4780.4  305.27  4830.0  300.86  4882.6  291.61  4905.7  289.98  4953.7  281.96
  4963.7  281.35  4983.7  274.83  4993.7  270.60  4997.0  270.60  4999.8  270.10
  5003.0  270.60  5003.7  273.45  5043.7  278.34  5053.8  277.52  5083.8  278.70
  5103.8  276.61  5123.8  279.55  5143.8  280.06  5205.3  285.35  5243.9  287.36
  5253.9  289.23  5344.0  293.94  5394.0  297.52  5424.0  298.56  5479.8  302.82
#Mann=3,-1,0
  4651.6    0.15       0  4997.0    0.05       0  5003.0    0.15       0
Bank Sta=4997,5003
Exp/Cntr=0.3,0.1

Type RM Length L Ch R = 1,8452,401,401,401
BEGIN DESCRIPTION:
UNT 010 IN BOCR 18.0
END DESCRIPTION:
XS GIS Cut Line= 2
      3684462.91     10590736.87      3685125.82     10590420.58
#Sta/Elev= 30
  4619.6  329.62  4622.5  328.03  4660.3  325.38  4764.2  311.90  4771.1  309.74
  4786.9  307.52  4793.2  304.43  4809.6  303.22  4815.4  300.67  4832.3  297.00
  4870.8  292.39  4900.3  287.06  4915.1  286.11  4951.2  280.09  4981.6  276.74
  4996.6  271.76  4997.0  269.21  4999.8  268.71  5003.0  269.21  5013.8  272.72
  5025.9  274.13  5036.5  273.67  5064.7  279.11  5125.6  285.53  5132.8  287.33
  5169.9  289.40  5178.2  291.80  5229.1  296.28  5291.6  304.50  5354.1  308.32
#Mann=3,-1,0
  4619.6    0.15       0  4997.0    0.05       0  5003.0    0.15       0
Bank Sta=4997,5003
Exp/Cntr=0.3,0.1

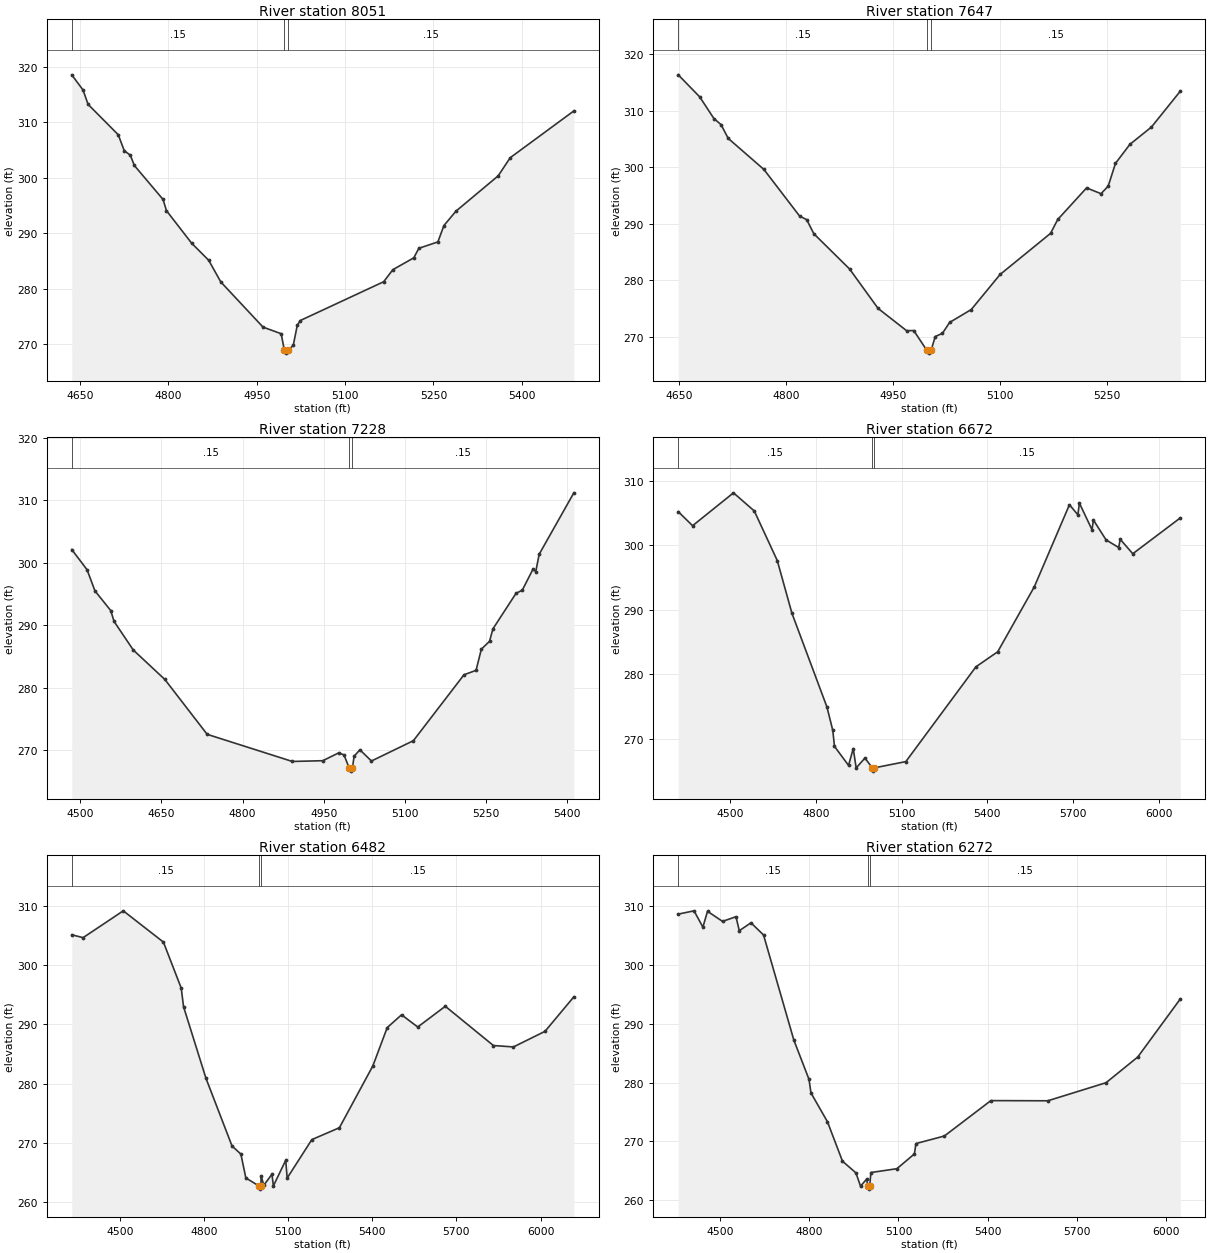
Type RM Length L Ch R = 1,8051,404,404,404
BEGIN DESCRIPTION:
UNT 010 IN BOCR 17.0
END DESCRIPTION:
XS GIS Cut Line= 3
      3684662.60     10590988.60      3685092.24     10590893.12
      3685495.21     10590979.78
#Sta/Elev= 30
  4636.1  318.58  4655.2  315.84  4663.8  313.25  4715.0  307.77  4725.2  304.89
  4735.5  304.09  4742.3  302.23  4791.0  296.11  4796.9  294.07  4839.6  288.21
  4868.6  285.12  4889.1  281.22  4960.8  273.07  4991.6  271.88  4997.0  268.88
  4999.8  268.38  5003.0  268.88  5012.1  269.79  5018.9  273.39  5024.0  274.26
  5165.6  281.26  5181.1  283.43  5216.7  285.57  5225.3  287.29  5257.6  288.44
  5267.9  291.40  5288.3  293.99  5359.9  300.35  5380.4  303.63  5488.4  312.07
#Mann=3,-1,0
  4636.1    0.15       0  4997.0    0.05       0  5003.0    0.15       0
Bank Sta=4997,5003
Exp/Cntr=0.3,0.1

Type RM Length L Ch R = 1,7647,419,419,419
BEGIN DESCRIPTION:
UNT 010 IN BOCR 16.0
END DESCRIPTION:
XS GIS Cut Line= 3
      3684699.65     10591310.19      3685049.61     10591310.19
      3685399.60     10591260.19
#Sta/Elev= 30
  4648.7  316.40  4678.7  312.51  4698.7  308.66  4708.7  307.58  4718.7  305.15
  4768.7  299.65  4818.7  291.40  4828.7  290.75  4838.7  288.26  4888.7  282.03
  4928.7  275.04  4968.7  271.09  4978.7  271.12  4997.0  267.62  4999.8  267.12
  5003.0  267.62  5008.8  270.05  5018.9  270.63  5029.0  272.56  5059.3  274.84
  5099.7  281.05  5170.4  288.33  5180.5  290.79  5220.9  296.38  5241.1  295.35
  5251.2  296.70  5261.3  300.71  5281.5  304.08  5311.8  307.16  5352.2  313.51
#Mann=3,-1,0
  4648.7    0.15       0  4997.0    0.05       0  5003.0    0.15       0
Bank Sta=4997,5003
Exp/Cntr=0.3,0.1

Type RM Length L Ch R = 1,7228,556,556,556
BEGIN DESCRIPTION:
UNT 010 IN BOCR 15.0
END DESCRIPTION:
XS GIS Cut Line= 3
      3684849.58     10592110.23      3685149.61     10591710.19
      3685549.57     10591560.20
#Sta/Elev= 30
  4484.7  302.11  4512.9  298.88  4527.5  295.49  4556.6  292.34  4562.9  290.58
  4598.3  286.01  4656.6  281.29  4734.7  272.50  4892.0  268.15  4948.3  268.27
  4977.5  269.52  4987.4  269.21  4997.0  267.10  4999.8  266.60  5003.0  267.10
  5006.1  268.99  5016.8  270.02  5038.1  268.22  5115.6  271.48  5209.0  282.04
  5231.3  282.75  5241.1  286.15  5256.2  287.40  5262.4  289.39  5305.1  295.09
  5316.7  295.60  5336.3  298.94  5341.6  298.59  5347.9  301.36  5411.9  311.20
#Mann=3,-1,0
  4484.7    0.15       0  4997.0    0.05       0  5003.0    0.15       0
Bank Sta=4997,5003
Exp/Cntr=0.3,0.1

Type RM Length L Ch R = 1,6672,190,190,190
BEGIN DESCRIPTION:
Mapping XS c6aa43b5
END DESCRIPTION:
XS GIS Cut Line= 2
      3684620.48     10592390.41      3686339.25     10592020.61
#Sta/Elev= 30
  4317.3  305.23  4367.6  303.05  4510.8  308.15  4583.7  305.33  4664.2  297.63
  4715.3  289.48  4838.1  274.91  4858.5  271.29  4864.4  268.81  4913.7  265.86
  4930.1  268.47  4940.4  265.47  4971.1  267.00  4997.0  265.47  4999.8  264.97
  5003.0  265.47  5114.3  266.45  5359.8  281.16  5436.0  283.49  5564.3  293.58
  5687.1  306.30  5716.8  304.74  5721.9  306.57  5766.1  302.43  5771.2  303.92
  5815.4  300.85  5859.7  299.66  5864.8  300.95  5909.0  298.70  6075.4  304.26
#Mann=3,-1,0
  4317.3    0.15       0  4997.0    0.05       0  5003.0    0.15       0
Bank Sta=4997,5003
Exp/Cntr=0.3,0.1

Type RM Length L Ch R = 1,6482,210,210,210
BEGIN DESCRIPTION:
UNT 010 IN BOCR 14.0
END DESCRIPTION:
XS GIS Cut Line= 2
      3684610.12     10592567.48      3686360.09     10592187.28
#Sta/Elev= 30
  4328.1  305.17  4368.5  304.68  4511.8  309.22  4655.0  303.93  4718.6  296.13
  4726.7  293.01  4806.7  280.89  4899.8  269.42  4931.3  268.06  4949.0  264.02
  4997.0  262.63  4999.8  262.13  5003.0  262.63  5003.2  264.40  5013.2  262.79
  5042.1  264.65  5047.2  262.68  5091.2  267.01  5096.4  264.00  5184.4  270.51
  5282.7  272.52  5402.1  282.99  5453.2  289.46  5504.4  291.63  5562.1  289.56
  5660.4  293.07  5831.9  286.43  5903.5  286.19  6016.1  288.83  6118.9  294.67
#Mann=3,-1,0
  4328.1    0.15       0  4997.0    0.05       0  5003.0    0.15       0
Bank Sta=4997,5003
Exp/Cntr=0.3,0.1

Type RM Length L Ch R = 1,6272,158,158,158
BEGIN DESCRIPTION:
UNT 010 IN BOCR 13.0
END DESCRIPTION:
XS GIS Cut Line= 2
      3684688.24     10592754.98      3686344.50     10592416.44
#Sta/Elev= 30
  4358.5  308.69  4411.7  309.25  4441.5  306.47  4457.1  309.17  4507.6  307.45
  4553.0  308.25  4564.0  305.86  4603.4  307.21  4645.7  305.14  4747.7  287.24
  4798.8  280.54  4805.4  278.23  4861.0  273.31  4911.5  266.60  4956.8  264.61
  4972.3  262.34  4992.7  263.54  4997.0  262.34  4999.8  261.84  5003.0  262.34
  5007.3  264.67  5094.8  265.32  5153.7  267.84  5158.8  269.60  5254.6  270.89
  5411.2  276.92  5602.9  276.89  5799.0  279.97  5905.8  284.35  6049.0  294.24
#Mann=3,-1,0
  4358.5    0.15       0  4997.0    0.05       0  5003.0    0.15       0
Bank Sta=4997,5003
Exp/Cntr=0.3,0.1

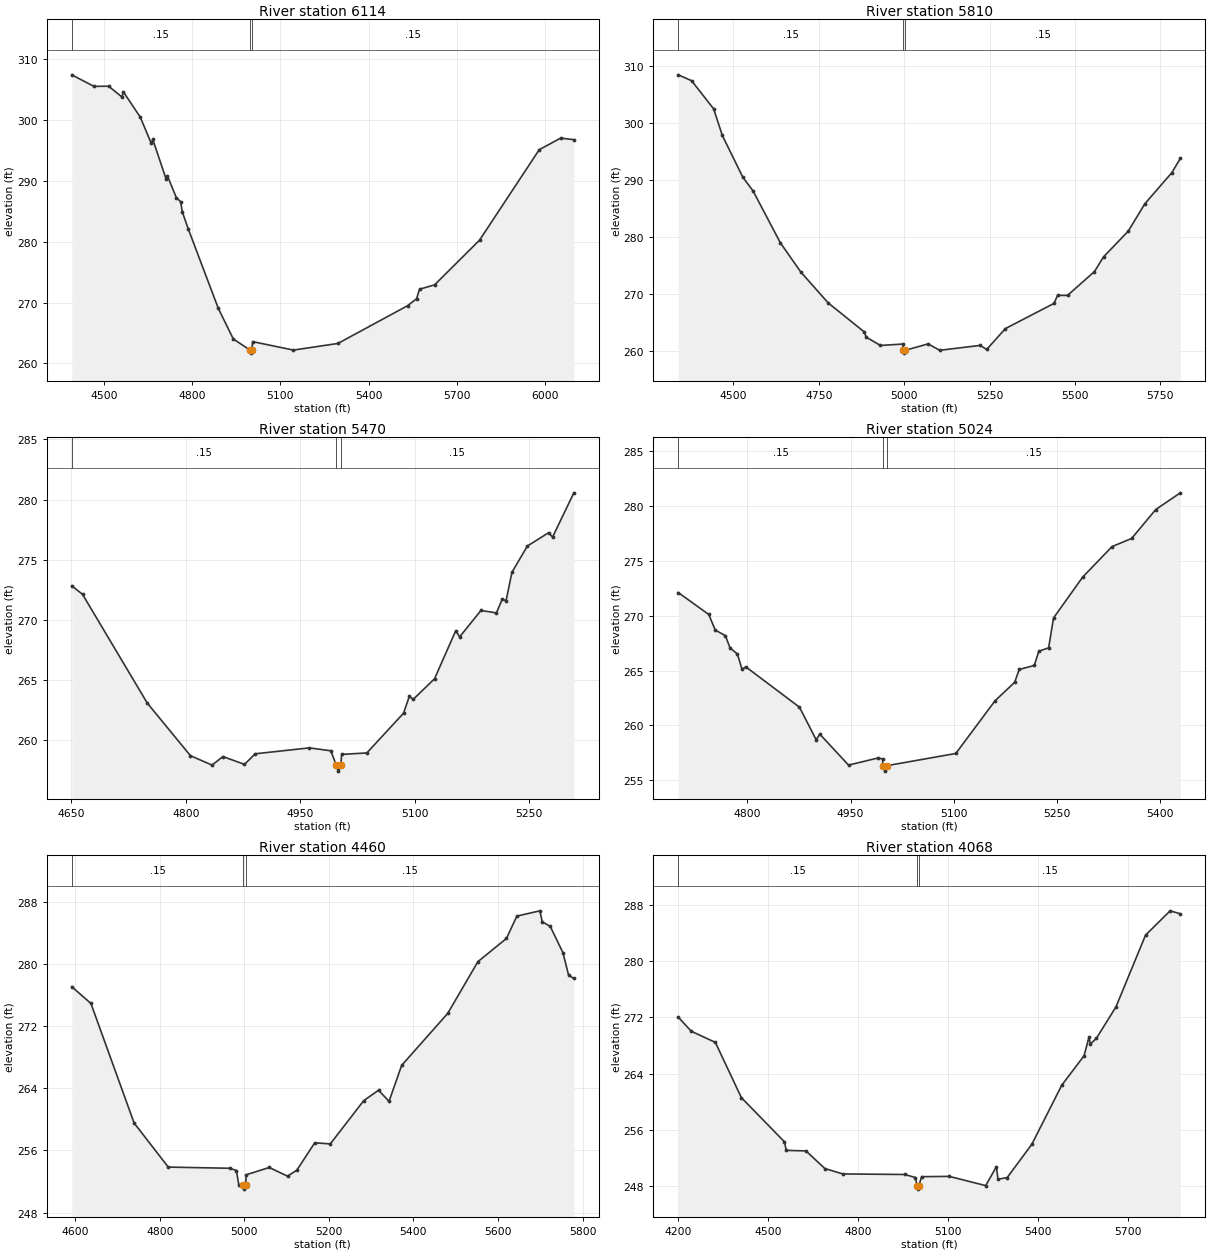
Type RM Length L Ch R = 1,6114,304,304,304
BEGIN DESCRIPTION:
Mapping XS fea17d4f
END DESCRIPTION:
XS GIS Cut Line= 2
      3684771.59     10592900.81      3686443.46     10592551.86
#Sta/Elev= 30
  4390.6  307.45  4466.1  305.55  4516.1  305.58  4561.0  303.81  4566.2  304.65
  4623.5  300.51  4661.1  296.17  4666.2  296.83  4711.1  290.37  4716.2  290.82
  4746.1  287.28  4761.1  286.57  4766.6  284.92  4787.0  282.10  4889.1  269.05
  4940.2  264.02  4997.0  262.20  4999.8  261.70  5003.0  262.20  5006.0  263.59
  5144.5  262.20  5295.9  263.29  5532.7  269.49  5563.4  270.63  5573.6  272.21
  5624.7  272.92  5777.9  280.28  5980.7  295.14  6053.7  297.05  6098.5  296.79
#Mann=3,-1,0
  4390.6    0.15       0  4997.0    0.05       0  5003.0    0.15       0
Bank Sta=4997,5003
Exp/Cntr=0.3,0.1

Type RM Length L Ch R = 1,5810,340,340,340
BEGIN DESCRIPTION:
UNT 010 IN BOCR 12.0
END DESCRIPTION:
XS GIS Cut Line= 3
      3684870.49     10593088.32      3685386.13     10593072.70
      3686306.34     10592817.95
#Sta/Elev= 30
  4338.2  308.49  4377.3  307.46  4442.0  302.50  4467.4  297.82  4527.4  290.48
  4557.4  288.07  4637.5  278.93  4697.5  273.79  4777.5  268.37  4882.9  263.28
  4888.8  262.36  4930.3  260.89  4996.2  261.14  4997.0  260.04  4999.8  259.54
  5003.0  260.04  5070.0  261.16  5104.3  260.04  5222.8  260.90  5241.6  260.18
  5296.6  263.86  5438.7  268.28  5449.4  269.70  5478.5  269.69  5557.5  273.89
  5584.0  276.47  5656.6  281.01  5705.1  285.82  5784.1  291.28  5808.9  293.79
#Mann=3,-1,0
  4338.2    0.15       0  4997.0    0.05       0  5003.0    0.15       0
Bank Sta=4997,5003
Exp/Cntr=0.3,0.1

Type RM Length L Ch R = 1,5470,446,446,446
BEGIN DESCRIPTION:
UNT 010 IN BOCR 11.0
END DESCRIPTION:
XS GIS Cut Line= 3
      3685449.64     10593560.16      3685699.61     10593310.19
      3685999.65     10593360.20
#Sta/Elev= 30
  4650.6  272.84  4664.7  272.13  4749.6  263.09  4806.1  258.73  4834.4  257.95
  4848.6  258.66  4876.8  258.01  4891.0  258.89  4961.7  259.38  4990.0  259.14
  4997.0  257.95  4999.8  257.45  5003.0  257.95  5004.1  258.84  5037.1  258.96
  5085.2  262.26  5092.8  263.66  5097.9  263.41  5125.8  265.12  5153.6  269.11
  5158.7  268.60  5186.6  270.79  5206.9  270.59  5214.5  271.73  5219.5  271.60
  5227.2  273.96  5247.4  276.14  5275.3  277.25  5280.4  276.88  5308.3  280.56
#Mann=3,-1,0
  4650.6    0.15       0  4997.0    0.05       0  5003.0    0.15       0
Bank Sta=4997,5003
Exp/Cntr=0.3,0.1

Type RM Length L Ch R = 1,5024,564,564,564
BEGIN DESCRIPTION:
UNT 010 IN BOCR 10.0
END DESCRIPTION:
XS GIS Cut Line= 3
      3685499.65     10593610.21      3685749.61     10593710.19
      3686099.62     10593410.18
#Sta/Elev= 30
  4699.4  272.12  4743.8  270.12  4753.2  268.70  4768.0  268.19  4774.7  267.08
  4785.5  266.51  4792.2  265.11  4797.6  265.35  4875.7  261.67  4900.0  258.70
  4905.3  259.21  4947.1  256.39  4990.0  257.04  4996.6  256.95  4997.0  256.34
  4999.8  255.84  5003.0  256.34  5103.1  257.45  5160.1  262.25  5188.7  263.94
  5195.3  265.11  5217.2  265.47  5223.8  266.77  5238.1  267.08  5245.2  269.80
  5287.5  273.52  5330.3  276.31  5358.8  277.05  5393.9  279.69  5429.6  281.21
#Mann=3,-1,0
  4699.4    0.15       0  4997.0    0.05       0  5003.0    0.15       0
Bank Sta=4997,5003
Exp/Cntr=0.3,0.1

Type RM Length L Ch R = 1,4460,392,392,392
BEGIN DESCRIPTION:
UNT 010 IN BOCR 9.0
END DESCRIPTION:
XS GIS Cut Line= 3
      3685349.62     10593710.21      3685549.61     10594060.19
      3686281.16     10594343.54
#Sta/Elev= 30
  4591.9  277.11  4637.2  274.95  4739.4  259.54  4820.1  253.86  4965.5  253.71
  4981.3  253.42  4987.1  251.52  4997.0  251.52  4999.8  251.02  5003.0  251.52
  5004.6  252.87  5059.1  253.81  5102.2  252.69  5124.3  253.46  5166.6  256.99
  5203.4  256.85  5282.4  262.42  5317.7  263.77  5342.3  262.33  5372.2  266.97
  5481.2  273.67  5552.6  280.34  5620.1  283.33  5644.7  286.21  5699.2  286.89
  5704.6  285.50  5723.8  284.87  5753.7  281.50  5767.1  278.59  5779.5  278.17
#Mann=3,-1,0
  4591.9    0.15       0  4997.0    0.05       0  5003.0    0.15       0
Bank Sta=4997,5003
Exp/Cntr=0.3,0.1

Type RM Length L Ch R = 1,4068,334,334,334
BEGIN DESCRIPTION:
UNT 010 IN BOCR 8.0
END DESCRIPTION:
XS GIS Cut Line= 4
      3684953.82     10593744.54      3685344.46     10594322.70
      3685542.38     10594562.28      3685693.43     10595213.37
#Sta/Elev= 30
  4199.2  272.05  4242.3  270.05  4323.2  268.45  4410.1  260.60  4553.9  254.33
  4559.9  253.11  4625.8  253.03  4688.8  250.53  4748.7  249.76  4956.0  249.68
  4991.2  249.25  4997.0  248.10  4999.8  247.60  5003.0  248.10  5012.0  249.37
  5104.5  249.41  5226.1  248.10  5261.9  250.79  5267.2  249.00  5298.0  249.25
  5380.1  253.97  5480.3  262.38  5554.6  266.55  5570.8  269.15  5575.9  268.21
  5595.7  269.03  5661.2  273.50  5759.9  283.69  5842.1  287.15  5876.1  286.73
#Mann=3,-1,0
  4199.2    0.15       0  4997.0    0.05       0  5003.0    0.15       0
Bank Sta=4997,5003
Exp/Cntr=0.3,0.1

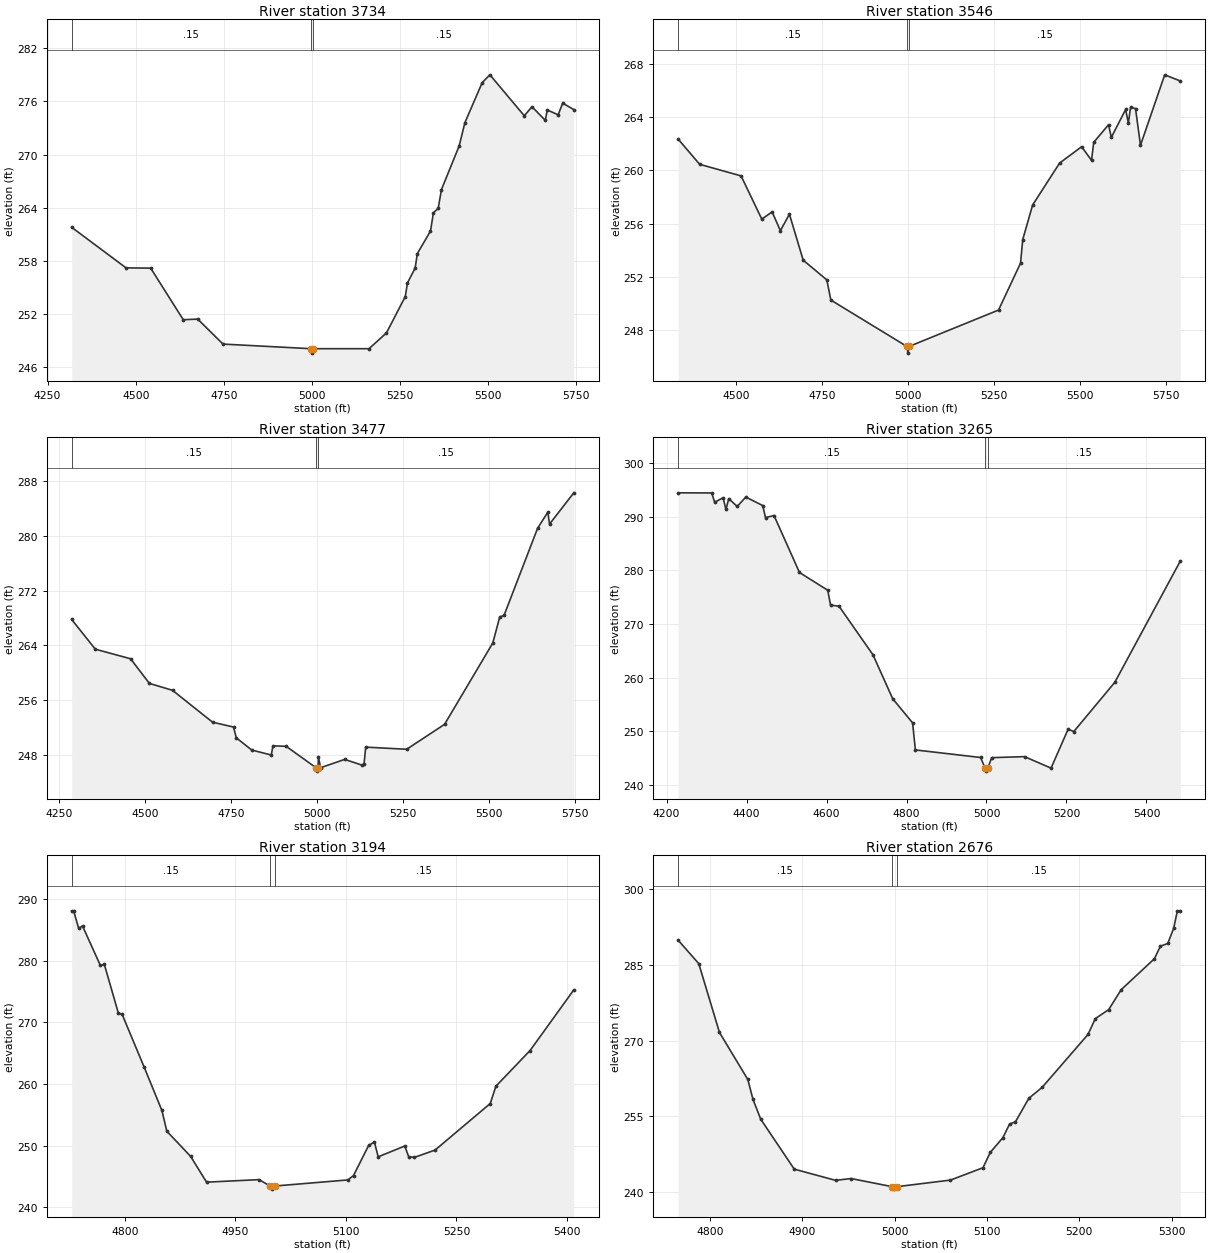
Type RM Length L Ch R = 1,3734,188,188,188
BEGIN DESCRIPTION:
Mapping XS f5559050
END DESCRIPTION:
XS GIS Cut Line= 3
      3685000.72     10593921.68      3685136.13     10594510.20
      3685531.95     10595228.92
#Sta/Elev= 30
  4318.3  261.80  4472.6  257.22  4542.5  257.19  4634.9  251.37  4675.9  251.44
  4747.7  248.62  4997.0  248.10  4999.8  247.60  5003.0  248.10  5161.9  248.10
  5211.3  249.88  5264.7  253.98  5270.9  255.52  5292.7  257.19  5298.9  258.83
  5336.2  261.37  5344.6  263.44  5358.0  263.92  5367.4  266.06  5417.7  270.99
  5433.7  273.59  5483.0  278.13  5504.8  279.00  5602.3  274.38  5624.1  275.40
  5661.9  273.86  5667.6  275.03  5698.5  274.49  5711.2  275.81  5742.7  275.08
#Mann=3,-1,0
  4318.3    0.15       0  4997.0    0.05       0  5003.0    0.15       0
Bank Sta=4997,5003
Exp/Cntr=0.3,0.1

Type RM Length L Ch R = 1,3546,69,69,69
BEGIN DESCRIPTION:
Mapping XS 64717bae
END DESCRIPTION:
XS GIS Cut Line= 3
      3684943.42     10593958.10      3685000.71     10594754.99
      3685417.29     10595265.30
#Sta/Elev= 30
  4332.9  262.35  4395.2  260.46  4515.5  259.59  4575.6  256.35  4605.7  256.89
  4629.6  255.48  4655.8  256.72  4695.9  253.27  4764.5  251.79  4776.1  250.28
  4997.0  246.80  4999.8  246.30  5003.0  246.80  5262.9  249.53  5326.8  253.05
  5333.2  254.82  5361.9  257.41  5440.2  260.55  5504.1  261.78  5532.8  260.76
  5539.3  262.11  5582.3  263.43  5590.3  262.48  5631.9  264.57  5639.8  263.55
  5646.2  264.73  5660.6  264.64  5675.0  261.89  5745.3  267.17  5790.6  266.71
#Mann=3,-1,0
  4332.9    0.15       0  4997.0    0.05       0  5003.0    0.15       0
Bank Sta=4997,5003
Exp/Cntr=0.3,0.1

Type RM Length L Ch R = 1,3477,212,212,212
BEGIN DESCRIPTION:
UNT 010 IN BOCR 7.0
END DESCRIPTION:
XS GIS Cut Line= 3
      3684688.19     10593978.90      3684906.96     10594406.03
      3684979.88     10595385.23
#Sta/Elev= 30
  4285.7  267.79  4354.6  263.45  4457.3  262.05  4511.9  258.46  4579.3  257.45
  4695.9  252.80  4756.9  252.09  4765.1  250.52  4809.9  248.74  4866.8  248.01
  4871.8  249.35  4910.2  249.28  4997.0  246.16  4999.8  245.66  5003.0  246.16
  5004.3  247.71  5010.4  246.16  5080.6  247.37  5130.8  246.54  5136.8  246.66
  5141.8  249.16  5261.1  248.85  5371.4  252.49  5511.8  264.36  5531.9  268.14
  5544.4  268.37  5642.2  281.09  5671.9  283.44  5676.9  281.70  5747.5  286.26
#Mann=3,-1,0
  4285.7    0.15       0  4997.0    0.05       0  5003.0    0.15       0
Bank Sta=4997,5003
Exp/Cntr=0.3,0.1

Type RM Length L Ch R = 1,3265,71,71,71
BEGIN DESCRIPTION:
Mapping XS 32e94a20
END DESCRIPTION:
XS GIS Cut Line= 3
      3684302.81     10594208.12      3684792.38     10594708.11
      3684917.39     10595249.81
#Sta/Elev= 30
  4229.0  294.42  4313.1  294.40  4320.1  292.67  4341.4  293.50  4348.4  291.32
  4355.5  293.33  4376.7  291.88  4398.0  293.63  4440.4  292.05  4447.4  289.80
  4468.7  290.19  4532.3  279.58  4603.0  276.27  4610.0  273.51  4631.3  273.29
  4716.1  264.25  4765.6  256.04  4815.2  251.57  4822.2  246.52  4985.2  245.11
  4997.0  243.07  4999.8  242.57  5003.0  243.07  5013.0  245.08  5095.1  245.27
  5161.4  243.13  5204.2  250.38  5218.3  249.94  5320.9  259.12  5484.7  281.71
#Mann=3,-1,0
  4229.0    0.15       0  4997.0    0.05       0  5003.0    0.15       0
Bank Sta=4997,5003
Exp/Cntr=0.3,0.1

Type RM Length L Ch R = 1,3194,518,518,518
BEGIN DESCRIPTION:
UNT 010 IN BOCR 6.0
END DESCRIPTION:
XS GIS Cut Line= 3
      3684499.62     10594710.19      3684749.61     10594810.19
      3684849.62     10595210.23
#Sta/Elev= 30
  4727.6  288.09  4730.3  288.09  4737.0  285.29  4742.4  285.62  4766.6  279.23
  4772.0  279.39  4790.9  271.55  4796.2  271.28  4825.9  262.78  4850.1  255.72
  4856.8  252.35  4889.1  248.27  4910.7  244.09  4982.0  244.50  4997.0  243.46
  4999.8  242.96  5003.0  243.46  5102.5  244.45  5110.2  245.16  5130.8  250.06
  5138.6  250.58  5143.7  248.20  5179.8  249.95  5185.0  248.24  5192.7  248.10
  5221.0  249.30  5295.8  256.84  5303.5  259.65  5349.9  265.44  5409.2  275.27
#Mann=3,-1,0
  4727.6    0.15       0  4997.0    0.05       0  5003.0    0.15       0
Bank Sta=4997,5003
Exp/Cntr=0.3,0.1

Type RM Length L Ch R = 1,2676,507,507,507
BEGIN DESCRIPTION:
UNT 010 IN BOCR 5.0
END DESCRIPTION:
XS GIS Cut Line= 3
      3684299.64     10595060.20      3684499.61     10595160.19
      3684749.58     10595360.17
#Sta/Elev= 30
  4765.6  289.90  4787.9  285.26  4810.3  271.62  4841.0  262.29  4846.6  258.34
  4855.0  254.41  4891.3  244.51  4936.1  242.29  4952.8  242.65  4997.0  241.05
  4999.8  240.55  5003.0  241.05  5060.4  242.34  5095.6  244.79  5103.6  247.84
  5117.2  250.76  5124.4  253.44  5130.8  253.90  5145.3  258.56  5159.7  260.73
  5209.3  271.21  5217.3  274.36  5231.7  276.14  5245.3  280.10  5281.3  286.24
  5287.7  288.71  5295.7  289.26  5302.1  292.24  5306.1  295.73  5309.3  295.73
#Mann=3,-1,0
  4765.6    0.15       0  4997.0    0.05       0  5003.0    0.15       0
Bank Sta=4997,5003
Exp/Cntr=0.3,0.1