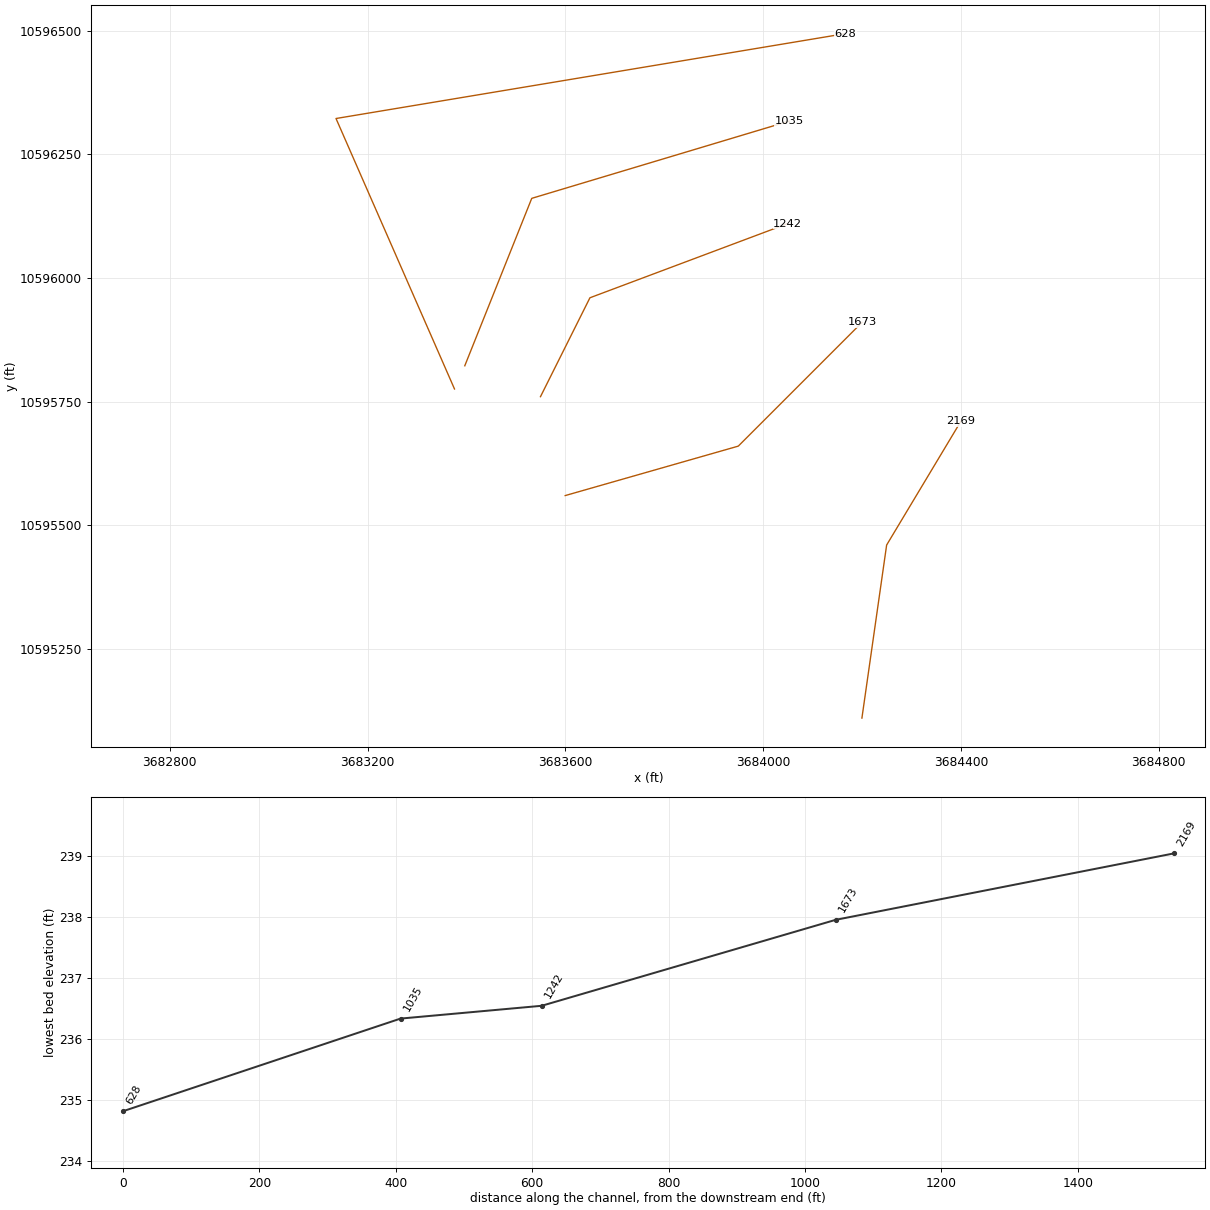
HEC-RAS study UNT 010 IN BOCR.prj: UNT 010 IN BOCR Base Level Engineering

--- UNT 010 IN BOCR.g01 (geometry) --- (continued)

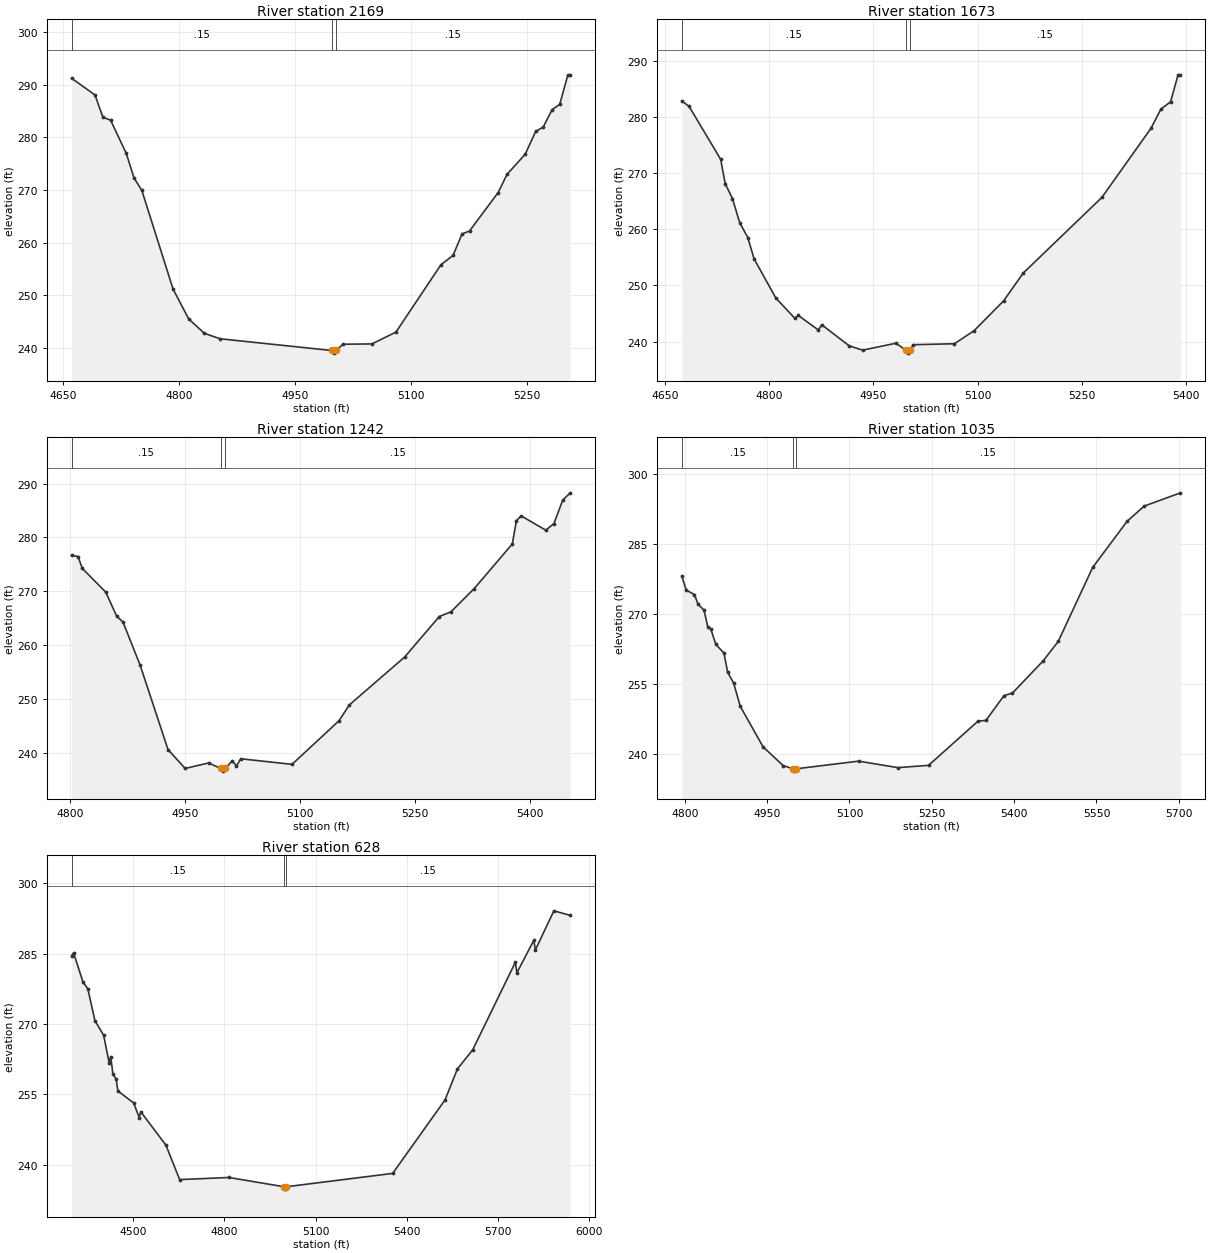
Type RM Length L Ch R = 1,2169,496,496,496
BEGIN DESCRIPTION:
UNT 010 IN BOCR 4.0
END DESCRIPTION:
XS GIS Cut Line= 3
      3684199.61     10595110.23      3684249.61     10595460.19
      3684399.63     10595710.22
#Sta/Elev= 30
  4660.7  291.25  4691.0  288.07  4701.1  283.87  4711.2  283.27  4731.4  276.98
  4741.5  272.31  4751.6  269.93  4792.0  251.19  4812.2  245.53  4832.4  242.81
  4852.6  241.77  4997.0  239.54  4999.8  239.04  5003.0  239.54  5011.7  240.73
  5049.2  240.79  5080.3  243.03  5138.6  255.84  5154.2  257.60  5165.8  261.68
  5175.5  262.24  5212.5  269.53  5224.1  273.01  5247.5  276.81  5261.1  281.15
  5270.8  281.97  5282.4  285.29  5292.2  286.29  5302.8  291.90  5305.8  291.90
#Mann=3,-1,0
  4660.7    0.15       0  4997.0    0.05       0  5003.0    0.15       0
Bank Sta=4997,5003
Exp/Cntr=0.3,0.1

Type RM Length L Ch R = 1,1673,431,431,431
BEGIN DESCRIPTION:
UNT 010 IN BOCR 3.0
END DESCRIPTION:
XS GIS Cut Line= 3
      3683599.58     10595560.18      3683949.61     10595660.19
      3684199.62     10595910.20
#Sta/Elev= 30
  4674.3  282.84  4684.7  281.88  4730.2  272.44  4736.7  268.12  4747.1  265.47
  4757.5  261.20  4769.2  258.53  4778.3  254.73  4809.5  247.77  4836.8  244.17
  4842.0  244.65  4870.6  242.08  4875.8  242.99  4914.8  239.28  4934.3  238.48
  4982.4  239.71  4997.0  238.45  4999.8  237.95  5003.0  238.45  5007.1  239.45
  5066.6  239.62  5094.9  241.95  5137.3  247.25  5165.6  252.20  5278.8  265.67
  5349.5  277.98  5363.6  281.36  5377.7  282.71  5388.4  287.49  5391.9  287.49
#Mann=3,-1,0
  4674.3    0.15       0  4997.0    0.05       0  5003.0    0.15       0
Bank Sta=4997,5003
Exp/Cntr=0.3,0.1

Type RM Length L Ch R = 1,1242,207,207,207
BEGIN DESCRIPTION:
UNT 010 IN BOCR 2.0
END DESCRIPTION:
XS GIS Cut Line= 3
      3683549.60     10595760.17      3683649.61     10595960.19
      3684049.58     10596110.18
#Sta/Elev= 30
  4802.3  276.67  4810.7  276.43  4816.3  274.22  4847.0  269.80  4861.0  265.38
  4869.4  264.24  4891.8  256.22  4928.1  240.56  4950.5  237.04  4981.2  238.06
  4997.0  237.04  4999.8  236.54  5003.0  237.04  5012.0  238.45  5017.5  237.49
  5023.1  238.84  5090.0  237.80  5151.4  245.92  5164.8  248.85  5236.9  257.74
  5282.2  265.28  5297.4  266.16  5327.6  270.45  5377.5  278.78  5382.8  283.08
  5389.0  284.00  5421.1  281.34  5431.8  282.55  5443.3  286.93  5453.1  288.28
#Mann=3,-1,0
  4802.3    0.15       0  4997.0    0.05       0  5003.0    0.15       0
Bank Sta=4997,5003
Exp/Cntr=0.3,0.1

Type RM Length L Ch R = 1,1035,407,407,407
BEGIN DESCRIPTION:
Mapping XS b815774c
END DESCRIPTION:
XS GIS Cut Line= 3
      3683396.54     10595822.67      3683531.96     10596161.24
      3684052.78     10596317.48
#Sta/Elev= 30
  4794.6  278.12  4802.7  275.13  4817.6  274.19  4824.2  272.10  4835.0  270.84
  4841.8  267.33  4847.2  266.86  4856.5  263.53  4871.4  261.61  4878.1  257.51
  4888.9  255.24  4901.1  250.21  4942.7  241.52  4979.1  237.53  4997.0  236.83
  4999.8  236.33  5003.0  236.83  5116.5  238.47  5188.1  237.08  5244.1  237.57
  5334.3  247.06  5348.5  247.19  5381.5  252.52  5396.9  253.07  5452.9  259.98
  5480.4  264.16  5543.1  280.01  5605.7  289.89  5637.0  293.16  5703.0  296.00
#Mann=3,-1,0
  4794.6    0.15       0  4997.0    0.05       0  5003.0    0.15       0
Bank Sta=4997,5003
Exp/Cntr=0.3,0.1

Type RM Length L Ch R = 1,628,0,0,0
BEGIN DESCRIPTION:
UNT 010 IN BOCR 1.0
END DESCRIPTION:
XS GIS Cut Line= 3
      3683375.73     10595775.79      3683136.13     10596322.70
      3684166.04     10596494.35
#Sta/Elev= 30
  4297.2  284.51  4303.7  285.16  4334.8  278.92  4350.5  277.51  4373.9  270.73
  4402.7  267.59  4420.6  261.78  4426.1  263.01  4433.0  259.40  4443.9  258.24
  4449.4  255.74  4501.7  253.16  4519.6  250.07  4525.0  251.28  4607.7  244.18
  4652.8  236.84  4815.1  237.29  4997.0  235.31  4999.8  234.81  5003.0  235.31
  5354.0  238.16  5526.4  253.83  5566.9  260.40  5617.6  264.52  5757.7  283.15
  5762.8  280.90  5818.6  287.84  5823.6  285.77  5884.5  294.11  5938.4  293.14
#Mann=3,-1,0
  4297.2    0.15       0  4997.0    0.05       0  5003.0    0.15       0
Bank Sta=4997,5003
Exp/Cntr=0.3,0.1

Chan Stop Cuts=-1