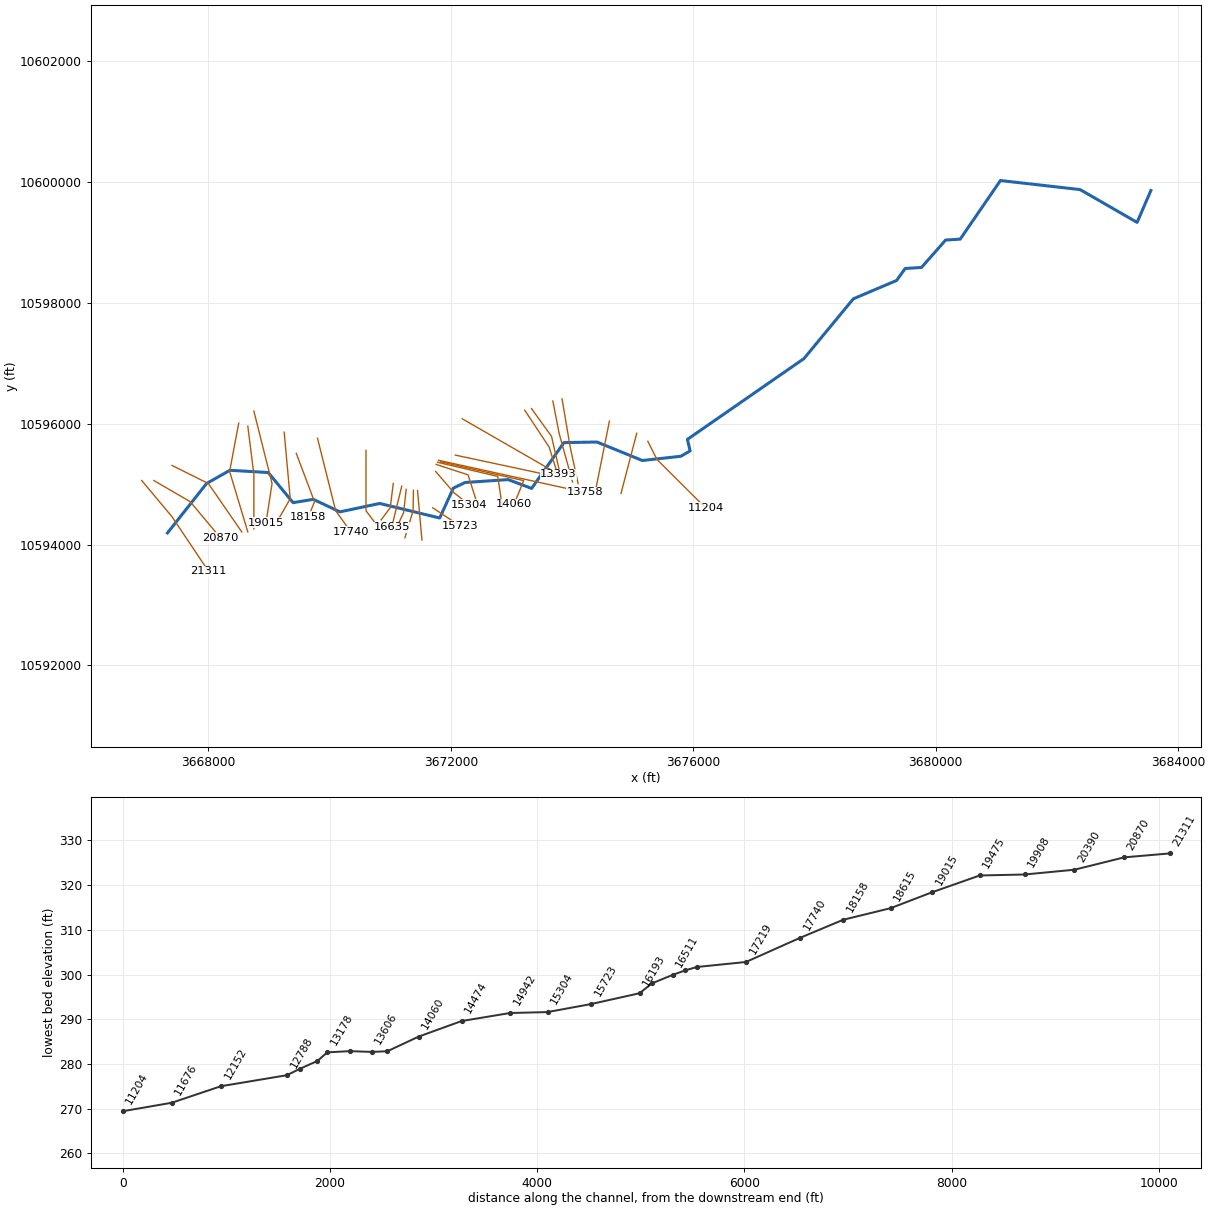
--- UNT 011 IN BOCR.prj (project) ---

Proj Title=UNT 011 IN BOCR Base Level Engineering
Current Plan=p01
Default Exp/Contr=0.3,0.1
English Units
Geom File=g01
Flow File=f01
Plan File=p01
BEGIN DESCRIPTION:
UNT 011 IN BOCR
END DESCRIPTION:

--- UNT 011 IN BOCR.p01 (plan) ---

Plan Title=Multiple Run
Short Identifier=Multiple
Geom File=g01
Flow File=f01
Subcritical Flow
K Sum by GR= 0
Std Step Tol= 0.01
Critical Tol= 0.01
Num of Std Step Trials= 20
Max Error Tol= 0.3
Flow Tol Ratio= 0.001
Split Flow NTrial= 30
Split Flow Tol= 0.02
Split Flow Ratio= 0.02
Log Output Level= 0
Friction Slope Method= 1
Unsteady Friction Slope Method= 2
Unsteady Bridges Friction Slope Method= 1
Parabolic Critical Depth
Global Vel Dist=  1 , 1 , 1
Global Log Level= 0
CheckData=True
Encroach Param= -1, 0, 0, 0
BEGIN DESCRIPTION:
Multiple Run
END DESCRIPTION:

--- UNT 011 IN BOCR.f01 (steady flow) ---

Flow Title=Multiple
Number of Profiles=7
Profile Names=10-year,25-year,50-year,1pct_min,100-year,1pct_plu,500-year
River Rch & RM= UNT 011 IN BOCR,Reach-1,21311
     440     585     702     619     837    1132    1195
River Rch & RM= UNT 011 IN BOCR,Reach-1,20390
     688     937    1143    1023    1383    1870    2035
River Rch & RM= UNT 011 IN BOCR,Reach-1,13758
    1270    1784    2221    2026    2740    3706    4192
River Rch & RM= UNT 011 IN BOCR,Reach-1,5886
    1451    2049    2559    2341    3166    4281    4870
River Rch & RM= UNT 011 IN BOCR,Reach-1,3182
    1466    2067    2580    2358    3189    4313    4897
Boundary for River Rch & Prof#=UNT 011 IN BOCR,Reach-1,1
Up Type=0
Dn Type=3
Dn Slope=0.005
Boundary for River Rch & Prof#=UNT 011 IN BOCR,Reach-1,2
Up Type=0
Dn Type=3
Dn Slope=0.005
Boundary for River Rch & Prof#=UNT 011 IN BOCR,Reach-1,3
Up Type=0
Dn Type=3
Dn Slope=0.005
Boundary for River Rch & Prof#=UNT 011 IN BOCR,Reach-1,4
Up Type=0
Dn Type=3
Dn Slope=0.005
Boundary for River Rch & Prof#=UNT 011 IN BOCR,Reach-1,5
Up Type=0
Dn Type=3
Dn Slope=0.005
Boundary for River Rch & Prof#=UNT 011 IN BOCR,Reach-1,6
Up Type=0
Dn Type=3
Dn Slope=0.005
Boundary for River Rch & Prof#=UNT 011 IN BOCR,Reach-1,7
Up Type=0
Dn Type=3
Dn Slope=0.005

--- UNT 011 IN BOCR.g01 (geometry) ---

Geom Title=Existing Conditions

River Reach=UNT 011 IN BOCR,Reach-1
Reach XY= 30
      3667324.25     10594193.00      3667969.25     10595011.00
      3668354.00     10595230.00      3668986.50     10595193.00
      3669397.00     10594694.00      3669729.50     10594749.00
      3670169.50     10594542.00      3670825.75     10594681.00
      3671816.00     10594440.00      3672041.00     10594935.00
      3672236.00     10595028.00      3672945.00     10595076.00
      3673332.25     10594930.00      3673865.50     10595688.00
      3674410.00     10595698.00      3675159.50     10595392.00
      3675793.75     10595462.00      3675947.00     10595551.00
      3675903.50     10595742.00      3677825.25     10597078.00
      3678640.50     10598068.00      3679354.25     10598372.00
      3679496.00     10598570.00      3679766.00     10598588.00
      3680163.25     10599041.00      3680403.50     10599056.00
      3681067.75     10600026.00      3682382.75     10599876.00
      3683322.75     10599333.00      3683549.61     10599860.19

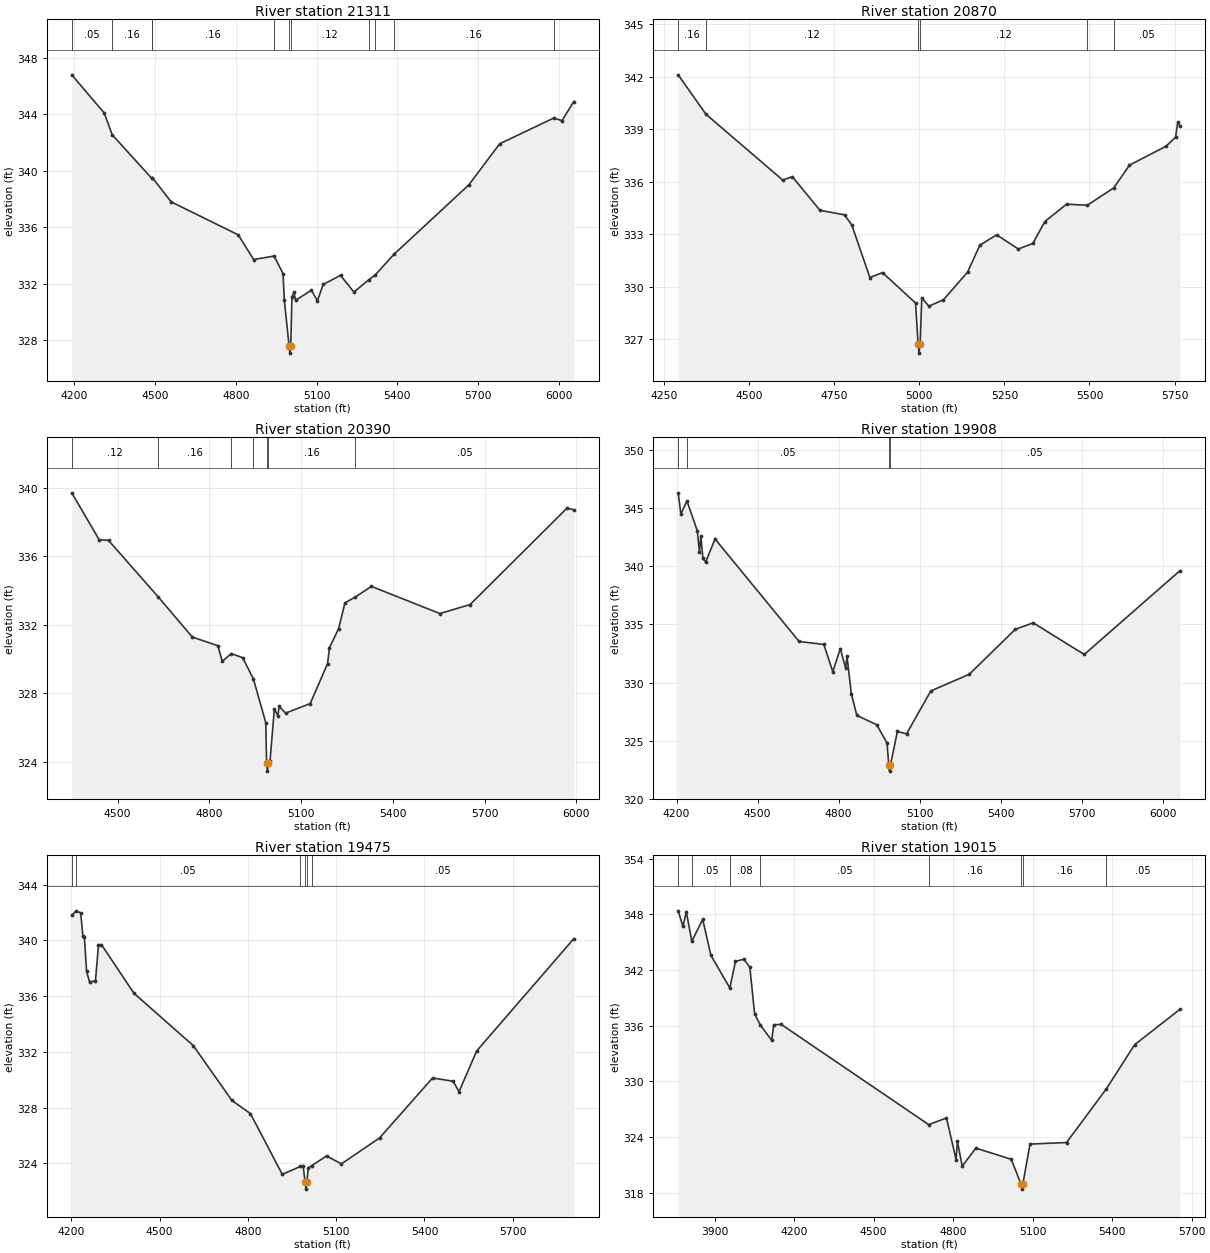
Type RM Length L Ch R = 1,21311,441,441,441
BEGIN DESCRIPTION:
UNT 011 IN BOCR 46.0
END DESCRIPTION:
XS GIS Cut Line= 3
      3666899.63     10595060.16      3667399.61     10594460.19
      3667999.64     10593560.15
#Sta/Elev= 30
  4191.6  346.79  4312.0  344.09  4341.7  342.55  4488.2  339.47  4490.4  339.52
  4560.6  337.80  4809.2  335.47  4866.5  333.72  4942.3  333.97  4975.6  332.72
  4980.1  330.88  4998.1  327.60  5000.9  327.10  5004.1  327.60  5008.6  331.09
  5016.2  331.41  5022.2  330.84  5080.8  331.55  5103.3  330.80  5124.3  331.96
  5188.9  332.60  5238.5  331.42  5293.7  332.29  5316.6  332.61  5386.6  334.08
  5665.2  339.01  5779.3  341.91  5979.7  343.73  6010.7  343.55  6054.3  344.90
#Mann=11,-1,0
  4191.6    0.05       0  4341.7    0.16       0  4488.2    0.05       0
  4490.4    0.16       0  4942.3    0.12       0  4998.1    0.07       0
  5004.1    0.12       0  5293.7    0.16       0  5316.6    0.12       0
  5386.6    0.16       0  5979.7    0.05       0
Bank Sta=4998.1,5004.1
Exp/Cntr=0.3,0.1

Type RM Length L Ch R = 1,20870,480,480,480
BEGIN DESCRIPTION:
UNT 011 IN BOCR 45.0
END DESCRIPTION:
XS GIS Cut Line= 3
      3667099.61     10595060.19      3667699.61     10594710.19
      3668199.58     10594110.22
#Sta/Elev= 30
  4291.0  342.12  4372.7  339.87  4598.2  336.11  4626.7  336.30  4707.8  334.38
  4780.1  334.12  4801.6  333.53  4854.6  330.54  4891.8  330.82  4988.9  329.08
  4996.3  326.72  4999.0  326.22  5002.3  326.72  5007.1  329.38  5027.9  328.90
  5070.9  329.27  5141.8  330.85  5177.6  332.38  5227.1  332.98  5290.9  332.17
  5333.8  332.49  5369.0  333.74  5432.8  334.73  5493.7  334.67  5571.5  335.66
  5617.6  336.96  5724.3  338.03  5753.0  338.55  5759.5  339.42  5766.6  339.20
#Mann=6,-1,0
  4291.0    0.16       0  4372.7    0.12       0  4996.3    0.07       0
  5002.3    0.12       0  5493.7    0.16       0  5571.5    0.05       0
Bank Sta=4996.3,5002.3
Exp/Cntr=0.3,0.1

Type RM Length L Ch R = 1,20390,482,482,482
BEGIN DESCRIPTION:
UNT 011 IN BOCR 44.0
END DESCRIPTION:
XS GIS Cut Line= 3
      3667399.59     10595310.20      3667999.61     10595010.19
      3668549.63     10594210.16
#Sta/Elev= 30
  4350.1  339.72  4439.6  336.98  4470.3  336.94  4633.6  333.62  4744.2  331.29
  4828.1  330.78  4842.1  329.87  4872.0  330.32  4909.1  330.08  4944.1  328.84
  4984.6  326.28  4987.2  323.95  4989.9  323.45  4993.2  323.95  4998.6  324.07
  5012.6  327.08  5024.0  326.69  5028.4  327.24  5049.3  326.84  5129.9  327.40
  5186.7  329.74  5192.8  330.67  5222.6  331.77  5243.5  333.29  5276.8  333.62
  5330.1  334.25  5554.1  332.66  5652.8  333.19  5969.4  338.82  5991.8  338.73
#Mann=7,-1,0
  4350.1    0.12       0  4633.6    0.16       0  4872.0    0.05       0
  4944.1    0.16       0  4987.2    0.07       0  4993.2    0.16       0
  5276.8    0.05       0
Bank Sta=4987.2,4993.2
Exp/Cntr=0.3,0.1

Type RM Length L Ch R = 1,19908,433,433,433
BEGIN DESCRIPTION:
UNT 011 IN BOCR 43.0
END DESCRIPTION:
XS GIS Cut Line= 3
      3668499.61     10596010.21      3668349.61     10595210.19
      3668649.61     10594210.19
#Sta/Elev= 30
  4205.9  346.31  4216.1  344.48  4238.3  345.62  4277.1  343.03  4284.8  341.18
  4289.9  342.62  4297.5  340.67  4307.7  340.36  4342.4  342.34  4653.6  333.53
  4745.2  333.27  4778.2  330.93  4806.2  332.92  4825.7  331.23  4830.8  332.26
  4846.9  329.03  4867.3  327.17  4941.0  326.37  4979.2  324.78  4985.5  322.88
  4988.2  322.38  4991.5  322.88  5017.3  325.79  5051.2  325.58  5140.8  329.27
  5283.5  330.71  5454.0  334.58  5520.1  335.13  5708.9  332.41  6063.9  339.63
#Mann=4,-1,0
  4205.9    0.08       0  4238.3    0.05       0  4985.5    0.03       0
  4991.5    0.05       0
Bank Sta=4985.5,4991.5
Exp/Cntr=0.3,0.1

Type RM Length L Ch R = 1,19475,460,460,460
BEGIN DESCRIPTION:
UNT 011 IN BOCR 42.0
END DESCRIPTION:
XS GIS Cut Line= 3
      3668649.61     10595960.21      3668749.61     10595160.19
      3668749.61     10594260.23
#Sta/Elev= 30
  4201.2  341.79  4215.7  342.12  4231.5  341.97  4239.0  340.32  4244.1  340.23
  4251.6  337.78  4261.7  337.01  4281.8  337.11  4291.9  339.67  4302.0  339.70
  4412.9  336.20  4614.4  332.45  4745.4  328.52  4808.4  327.58  4916.7  323.22
  4978.5  323.79  4987.3  323.85  4994.4  322.66  4997.1  322.16  5000.4  322.66
  5004.9  323.68  5017.0  323.85  5067.4  324.54  5117.4  323.97  5247.4  325.83
  5427.4  330.13  5497.4  329.90  5517.4  329.15  5577.4  332.07  5907.4  340.12
#Mann=6,-1,0
  4201.2    0.08       0  4215.7    0.05       0  4978.5    0.16       0
  4994.4    0.07       0  5000.4    0.16       0  5017.0    0.05       0
Bank Sta=4994.4,5000.4
Exp/Cntr=0.3,0.1

Type RM Length L Ch R = 1,19015,400,400,400
BEGIN DESCRIPTION:
UNT 011 IN BOCR 41.0
END DESCRIPTION:
XS GIS Cut Line= 3
      3668749.62     10596210.14      3669049.61     10595010.19
      3668949.61     10594360.22
#Sta/Elev= 30
  3762.2  348.37  3780.2  346.72  3793.1  348.25  3813.8  345.09  3854.9  347.45
  3885.8  343.58  3957.2  340.06  3978.6  342.92  4009.5  343.16  4032.7  342.31
  4050.8  337.28  4071.5  336.11  4115.2  334.42  4122.9  336.10  4151.3  336.14
  4707.6  325.35  4774.9  326.06  4811.0  321.59  4816.1  323.55  4834.2  320.87
  4885.7  322.82  5019.3  321.61  5056.8  318.90  5059.5  318.40  5062.8  318.90
  5090.1  323.25  5228.0  323.42  5378.5  329.21  5484.7  333.95  5656.7  337.78
#Mann=8,-1,0
  3762.2    0.16       0  3813.8    0.05       0  3957.2    0.08       0
  4071.5    0.05       0  4707.6    0.16       0  5056.8    0.07       0
  5062.8    0.16       0  5378.5    0.05       0
Bank Sta=5056.8,5062.8
Exp/Cntr=0.3,0.1

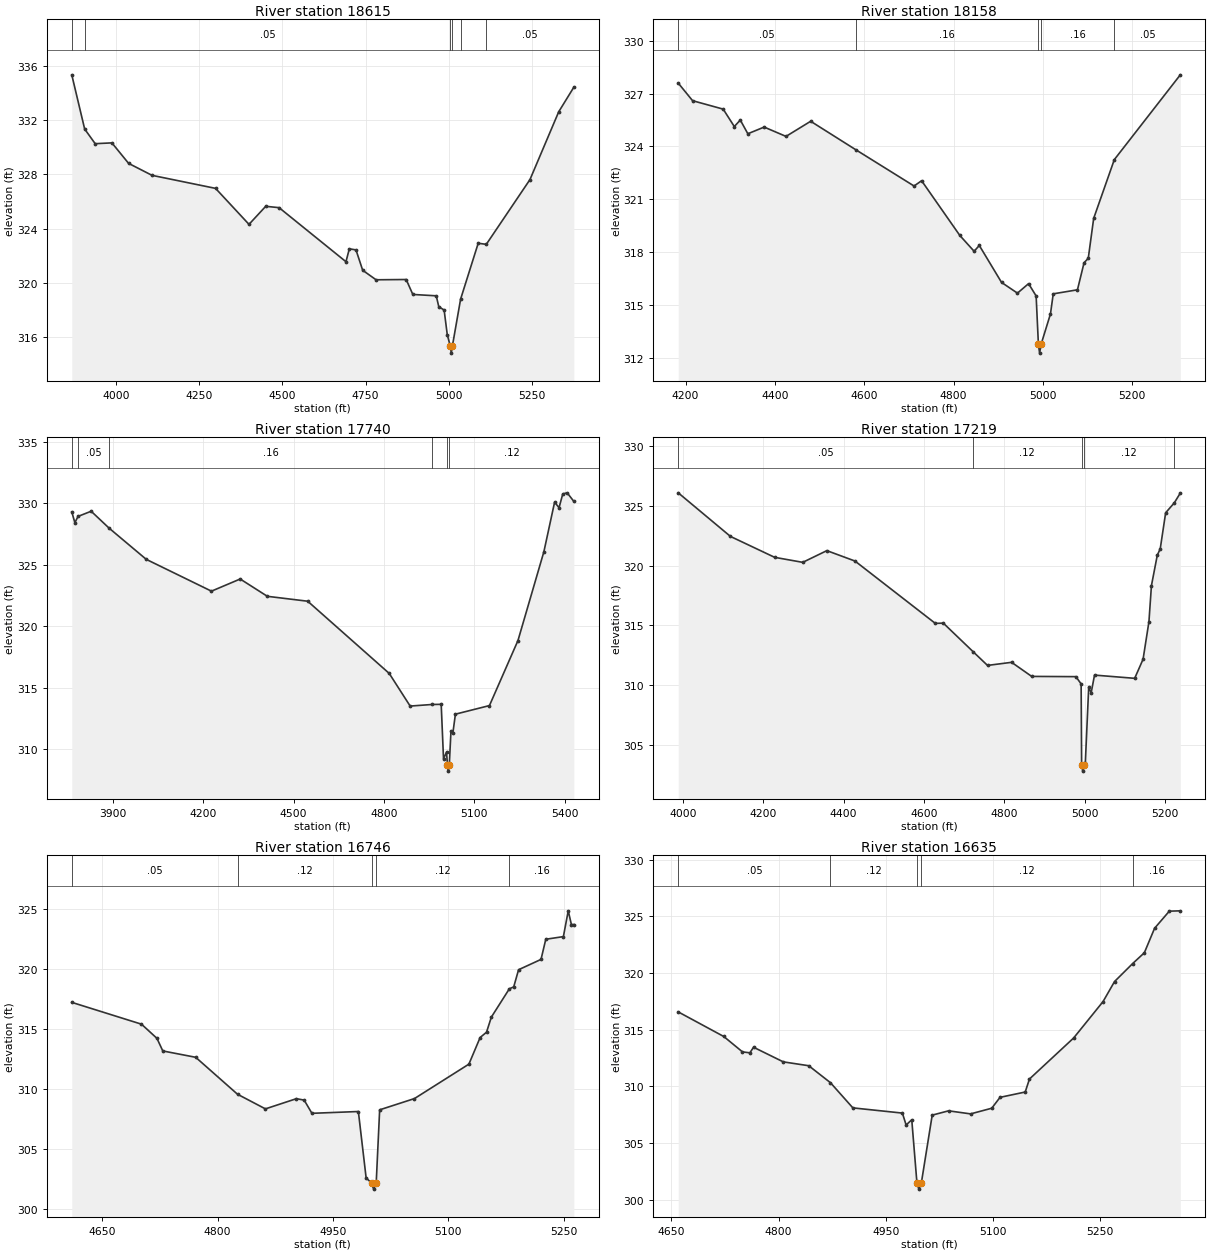
Type RM Length L Ch R = 1,18615,457,457,457
BEGIN DESCRIPTION:
UNT 011 IN BOCR 40.0
END DESCRIPTION:
XS GIS Cut Line= 3
      3669249.61     10595860.22      3669349.61     10594760.19
      3669149.60     10594410.17
#Sta/Elev= 30
  3867.4  335.33  3906.1  331.34  3937.7  330.26  3987.9  330.32  4038.1  328.81
  4108.4  327.93  4299.2  326.97  4399.6  324.32  4449.8  325.65  4490.0  325.55
  4690.8  321.57  4700.9  322.52  4720.9  322.44  4741.0  320.94  4781.2  320.24
  4871.6  320.26  4891.6  319.16  4961.9  319.06  4969.5  318.26  4985.6  318.01
  4995.0  316.20  5004.2  315.34  5007.0  314.84  5010.2  315.34  5035.1  318.82
  5087.9  322.93  5112.2  322.85  5243.4  327.62  5329.7  332.61  5375.1  334.42
#Mann=6,-1,0
  3867.4    0.08       0  3906.1    0.05       0  5004.2    0.03       0
  5010.2    0.05       0  5035.1    0.16       0  5112.2    0.05       0
Bank Sta=5004.2,5010.2
Exp/Cntr=0.3,0.1

Type RM Length L Ch R = 1,18158,418,418,418
BEGIN DESCRIPTION:
UNT 011 IN BOCR 39.0
END DESCRIPTION:
XS GIS Cut Line= 3
      3669449.59     10595510.23      3669749.61     10594710.19
      3669649.61     10594460.19
#Sta/Elev= 30
  4183.6  327.60  4215.7  326.60  4284.2  326.12  4309.1  325.13  4322.5  325.50
  4339.4  324.72  4375.9  325.10  4424.8  324.57  4480.0  325.43  4581.1  323.81
  4711.4  321.75  4728.3  322.05  4813.8  318.94  4845.8  318.04  4857.4  318.37
  4907.2  316.27  4942.8  315.66  4967.7  316.20  4984.6  315.50  4989.7  312.75
  4992.4  312.25  4995.7  312.75  5016.7  314.48  5022.9  315.62  5077.1  315.85
  5091.9  317.39  5101.3  317.64  5113.4  319.91  5159.6  323.25  5307.3  328.07
#Mann=5,-1,0
  4183.6    0.05       0  4581.1    0.16       0  4989.7    0.07       0
  4995.7    0.16       0  5159.6    0.05       0
Bank Sta=4989.7,4995.7
Exp/Cntr=0.3,0.1

Type RM Length L Ch R = 1,17740,521,521,521
BEGIN DESCRIPTION:
UNT 011 IN BOCR 38.0
END DESCRIPTION:
XS GIS Cut Line= 3
      3669799.61     10595760.18      3670099.61     10594560.19
      3670349.59     10594210.22
#Sta/Elev= 30
  3763.3  329.31  3773.6  328.43  3784.2  328.94  3827.7  329.36  3887.4  327.98
  4010.7  325.44  4227.1  322.85  4322.5  323.84  4412.7  322.43  4546.7  322.03
  4817.3  316.15  4886.8  313.49  4960.3  313.62  4989.9  313.63  4997.6  309.19
  5007.6  309.74  5010.7  308.69  5013.5  308.19  5016.7  308.69  5022.3  311.42
  5028.5  311.27  5037.1  312.83  5150.1  313.53  5244.8  318.83  5330.8  326.06
  5366.4  330.10  5381.2  329.65  5393.5  330.77  5408.2  330.86  5430.3  330.16
#Mann=6,-1,0
  3763.3    0.08       0  3784.2    0.05       0  3887.4    0.16       0
  4960.3    0.12       0  5010.7    0.07       0  5016.7    0.12       0
Bank Sta=5010.7,5016.7
Exp/Cntr=0.3,0.1

Type RM Length L Ch R = 1,17219,473,473,473
BEGIN DESCRIPTION:
UNT 011 IN BOCR 37.0
END DESCRIPTION:
XS GIS Cut Line= 3
      3670599.61     10595560.17      3670599.61     10594560.19
      3670749.62     10594360.17
#Sta/Elev= 30
  3988.3  326.10  4118.3  322.45  4228.3  320.70  4298.3  320.28  4358.3  321.26
  4428.3  320.39  4628.3  315.17  4648.3  315.19  4722.4  312.80  4758.3  311.65
  4818.3  311.91  4868.3  310.73  4978.3  310.71  4991.4  310.10  4992.6  303.30
  4995.3  302.80  4998.6  303.30  5001.8  303.47  5010.2  309.81  5016.4  309.36
  5024.7  310.84  5124.7  310.57  5145.6  312.17  5160.2  315.31  5166.4  318.33
  5181.0  320.88  5188.3  321.41  5201.8  324.43  5223.3  325.26  5238.3  326.08
#Mann=5,-1,0
  3988.3    0.05       0  4722.4    0.12       0  4992.6    0.07       0
  4998.6    0.12       0  5223.3    0.16       0
Bank Sta=4992.6,4998.6
Exp/Cntr=0.3,0.1

Type RM Length L Ch R = 1,16746,111,111,111
BEGIN DESCRIPTION:
UNT 011 IN BOCR 36.0
END DESCRIPTION:
XS GIS Cut Line= 3
      3671049.60     10595010.14      3670999.61     10594610.19
      3670849.59     10594410.16
#Sta/Elev= 30
  4610.2  317.25  4700.9  315.43  4721.0  314.25  4728.6  313.20  4771.4  312.67
  4825.8  309.59  4862.1  308.37  4902.4  309.22  4912.5  309.10  4922.6  308.00
  4983.0  308.15  4993.1  302.62  5000.2  302.18  5002.9  301.68  5006.2  302.18
  5010.7  308.29  5056.0  309.23  5126.8  312.10  5141.4  314.32  5149.7  314.76
  5156.0  316.02  5179.4  318.38  5185.1  318.54  5191.4  319.97  5220.6  320.83
  5226.8  322.51  5249.7  322.73  5256.0  324.88  5260.1  323.74  5263.3  323.74
#Mann=5,-1,0
  4610.2    0.05       0  4825.8    0.12       0  5000.2    0.07       0
  5006.2    0.12       0  5179.4    0.16       0
Bank Sta=5000.2,5006.2
Exp/Cntr=0.3,0.1

Type RM Length L Ch R = 1,16635,124,124,124
BEGIN DESCRIPTION:
Mapping XS 598820bd
END DESCRIPTION:
XS GIS Cut Line= 2
      3671189.61     10594967.55      3671022.93     10594285.21
#Sta/Elev= 30
  4659.5  316.58  4723.2  314.41  4749.4  313.05  4759.7  312.97  4764.9  313.46
  4806.5  312.17  4842.1  311.83  4872.5  310.33  4903.8  308.11  4973.1  307.65
  4978.3  306.60  4986.2  307.06  4993.5  301.44  4996.2  300.94  4999.5  301.44
  5014.8  307.47  5037.7  307.85  5068.5  307.58  5098.1  308.08  5109.7  309.04
  5144.9  309.51  5150.9  310.66  5212.7  314.28  5253.8  317.49  5269.9  319.26
  5295.3  320.85  5311.6  321.80  5325.9  323.96  5346.5  325.47  5361.9  325.50
#Mann=5,-1,0
  4659.5    0.05       0  4872.5    0.12       0  4993.5    0.07       0
  4999.5    0.12       0  5295.3    0.16       0
Bank Sta=4993.5,4999.5
Exp/Cntr=0.3,0.1

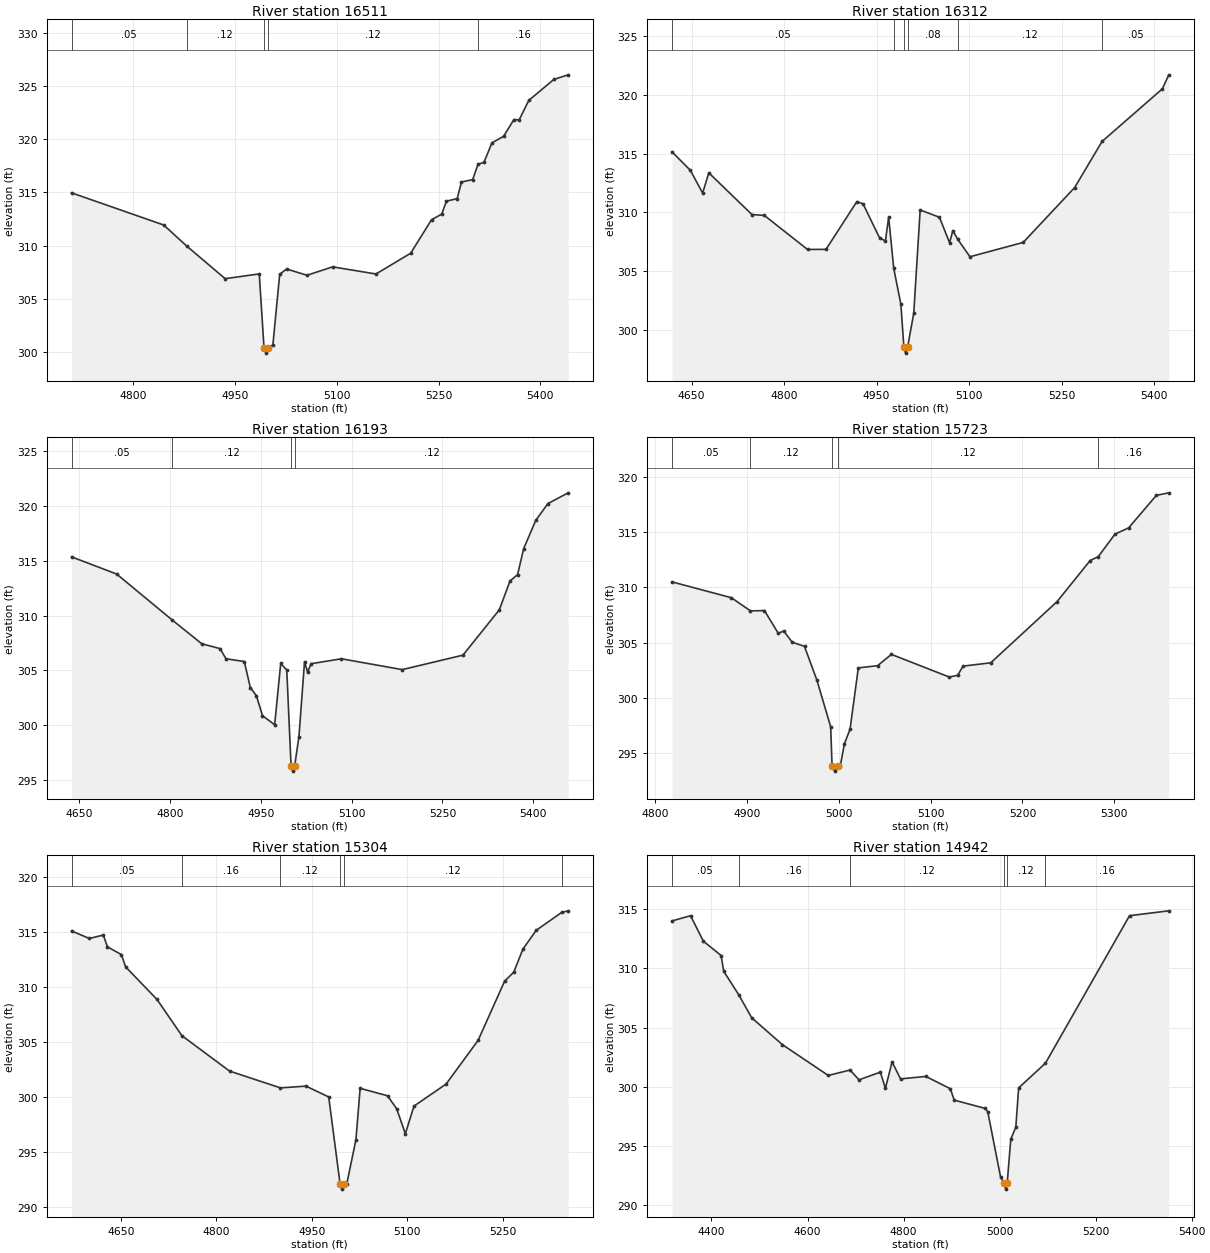
Type RM Length L Ch R = 1,16511,199,199,199
BEGIN DESCRIPTION:
UNT 011 IN BOCR 35.0
END DESCRIPTION:
XS GIS Cut Line= 3
      3671262.52     10594915.45      3671220.85     10594530.02
      3671075.03     10594217.54
#Sta/Elev= 30
  4708.7  314.95  4844.7  311.93  4878.5  309.96  4935.3  306.89  4985.6  307.34
  4992.6  300.40  4995.4  299.90  4998.6  300.40  5005.7  300.68  5015.7  307.29
  5025.8  307.80  5056.0  307.21  5093.8  308.00  5157.7  307.33  5208.9  309.28
  5239.6  312.42  5254.6  312.95  5261.7  314.17  5277.5  314.41  5283.8  315.97
  5300.3  316.19  5308.3  317.64  5316.9  317.80  5328.7  319.64  5346.0  320.26
  5361.0  321.82  5368.9  321.81  5383.1  323.63  5420.1  325.60  5441.2  326.03
#Mann=5,-1,0
  4708.7    0.05       0  4878.5    0.12       0  4992.6    0.07       0
  4998.6    0.12       0  5308.3    0.16       0
Bank Sta=4992.6,4998.6
Exp/Cntr=0.3,0.1

Type RM Length L Ch R = 1,16312,119,119,119
BEGIN DESCRIPTION:
Mapping XS 1121ee09
END DESCRIPTION:
XS GIS Cut Line= 3
      3671382.31     10594899.82      3671377.10     10594561.27
      3671241.95     10594114.24
#Sta/Elev= 30
  4618.3  315.14  4647.9  313.58  4667.9  311.64  4677.9  313.36  4747.9  309.81
  4767.9  309.74  4838.0  306.84  4868.0  306.85  4918.0  310.91  4928.0  310.73
  4954.9  307.82  4964.4  307.57  4969.6  309.60  4977.8  305.24  4989.4  302.19
  4994.3  298.52  4997.1  298.02  5000.3  298.52  5010.3  301.41  5020.7  310.20
  5052.0  309.58  5068.4  307.41  5073.7  308.44  5081.5  307.72  5101.4  306.22
  5187.8  307.44  5271.3  312.11  5315.7  316.03  5413.6  320.51  5423.9  321.70
#Mann=6,-1,0
  4618.3    0.05       0  4977.8    0.08       0  4994.3    0.07       0
  5000.3    0.08       0  5081.5    0.12       0  5315.7    0.05       0
Bank Sta=4994.3,5000.3
Exp/Cntr=0.3,0.1

Type RM Length L Ch R = 1,16193,470,470,470
BEGIN DESCRIPTION:
Mapping XS 15d3b8ba
END DESCRIPTION:
XS GIS Cut Line= 2
      3671450.01     10594894.62      3671522.93     10594076.87
#Sta/Elev= 30
  4636.9  315.36  4711.6  313.79  4802.6  309.63  4852.2  307.43  4882.3  306.99
  4892.3  306.06  4922.5  305.81  4932.5  303.43  4942.5  302.69  4952.6  300.87
  4972.7  300.04  4982.7  305.63  4992.7  305.04  4999.8  296.31  5002.5  295.81
  5005.8  296.31  5012.8  298.94  5022.1  305.80  5027.1  304.84  5032.9  305.61
  5083.1  306.06  5183.5  305.07  5283.9  306.39  5344.1  310.53  5361.7  313.16
  5374.2  313.73  5384.3  316.11  5404.4  318.70  5424.4  320.22  5457.9  321.20
#Mann=4,-1,0
  4636.9    0.05       0  4802.6    0.12       0  4999.8    0.07       0
  5005.8    0.12       0
Bank Sta=4999.8,5005.8
Exp/Cntr=0.3,0.1

Type RM Length L Ch R = 1,15723,419,419,419
BEGIN DESCRIPTION:
UNT 011 IN BOCR 34.0
END DESCRIPTION:
XS GIS Cut Line= 3
      3671699.65     10594610.16      3671849.61     10594510.19
      3672149.62     10594310.18
#Sta/Elev= 30
  4818.5  310.48  4883.1  309.05  4903.9  307.86  4919.1  307.89  4934.1  305.84
  4940.1  306.04  4949.2  305.04  4962.7  304.65  4976.2  301.60  4991.2  297.39
  4992.7  293.88  4995.5  293.38  4998.7  293.88  5001.7  293.88  5006.2  295.86
  5012.3  297.17  5021.3  302.71  5042.3  302.91  5057.3  303.93  5120.4  301.88
  5129.4  302.04  5135.4  302.87  5165.5  303.17  5237.6  308.69  5273.7  312.41
  5282.5  312.76  5300.7  314.79  5315.7  315.37  5345.8  318.30  5359.3  318.53
#Mann=5,-1,0
  4818.5    0.05       0  4903.9    0.12       0  4992.7    0.07       0
  4998.7    0.12       0  5282.5    0.16       0
Bank Sta=4992.7,4998.7
Exp/Cntr=0.3,0.1

Type RM Length L Ch R = 1,15304,362,362,362
BEGIN DESCRIPTION:
UNT 011 IN BOCR 33.0
END DESCRIPTION:
XS GIS Cut Line= 3
      3671749.60     10595210.20      3672049.61     10594860.19
      3672299.57     10594660.22
#Sta/Elev= 30
  4572.1  315.13  4600.1  314.44  4622.1  314.75  4628.6  313.68  4650.6  312.97
  4657.2  311.85  4706.6  308.88  4745.7  305.58  4820.7  302.35  4900.7  300.82
  4940.9  300.98  4976.6  299.99  4994.4  292.09  4997.2  291.59  5000.4  292.09
  5005.1  292.10  5019.4  296.10  5026.0  300.78  5069.1  300.10  5083.5  298.91
  5097.1  296.64  5110.7  299.16  5161.2  301.17  5211.6  305.16  5253.2  310.55
  5267.6  311.37  5282.0  313.47  5302.8  315.18  5342.8  316.81  5353.2  316.96
#Mann=6,-1,0
  4572.1    0.05       0  4745.7    0.16       0  4900.7    0.12       0
  4994.4    0.07       0  5000.4    0.12       0  5342.8    0.16       0
Bank Sta=4994.4,5000.4
Exp/Cntr=0.3,0.1

Type RM Length L Ch R = 1,14942,468,468,468
BEGIN DESCRIPTION:
UNT 011 IN BOCR 32.0
END DESCRIPTION:
XS GIS Cut Line= 3
      3671757.29     10595326.90      3672283.35     10595155.02
      3672429.18     10594696.68
#Sta/Elev= 30
  4317.9  314.01  4356.4  314.45  4383.0  312.30  4420.1  311.09  4425.5  309.76
  4456.4  307.80  4483.9  305.83  4547.7  303.57  4643.3  300.97  4688.7  301.43
  4707.1  300.60  4751.7  301.25  4762.2  299.88  4776.1  302.11  4793.8  300.68
  4846.4  300.89  4897.4  299.85  4905.5  298.89  4970.0  298.19  4975.3  297.92
  5002.2  292.37  5009.8  291.88  5012.6  291.38  5015.8  291.88  5023.3  295.59
  5033.8  296.61  5039.7  299.92  5095.4  302.00  5270.6  314.45  5352.3  314.86
#Mann=6,-1,0
  4317.9    0.05       0  4456.4    0.16       0  4688.7    0.12       0
  5009.8    0.07       0  5015.8    0.12       0  5095.4    0.16       0
Bank Sta=5009.8,5015.8
Exp/Cntr=0.3,0.1

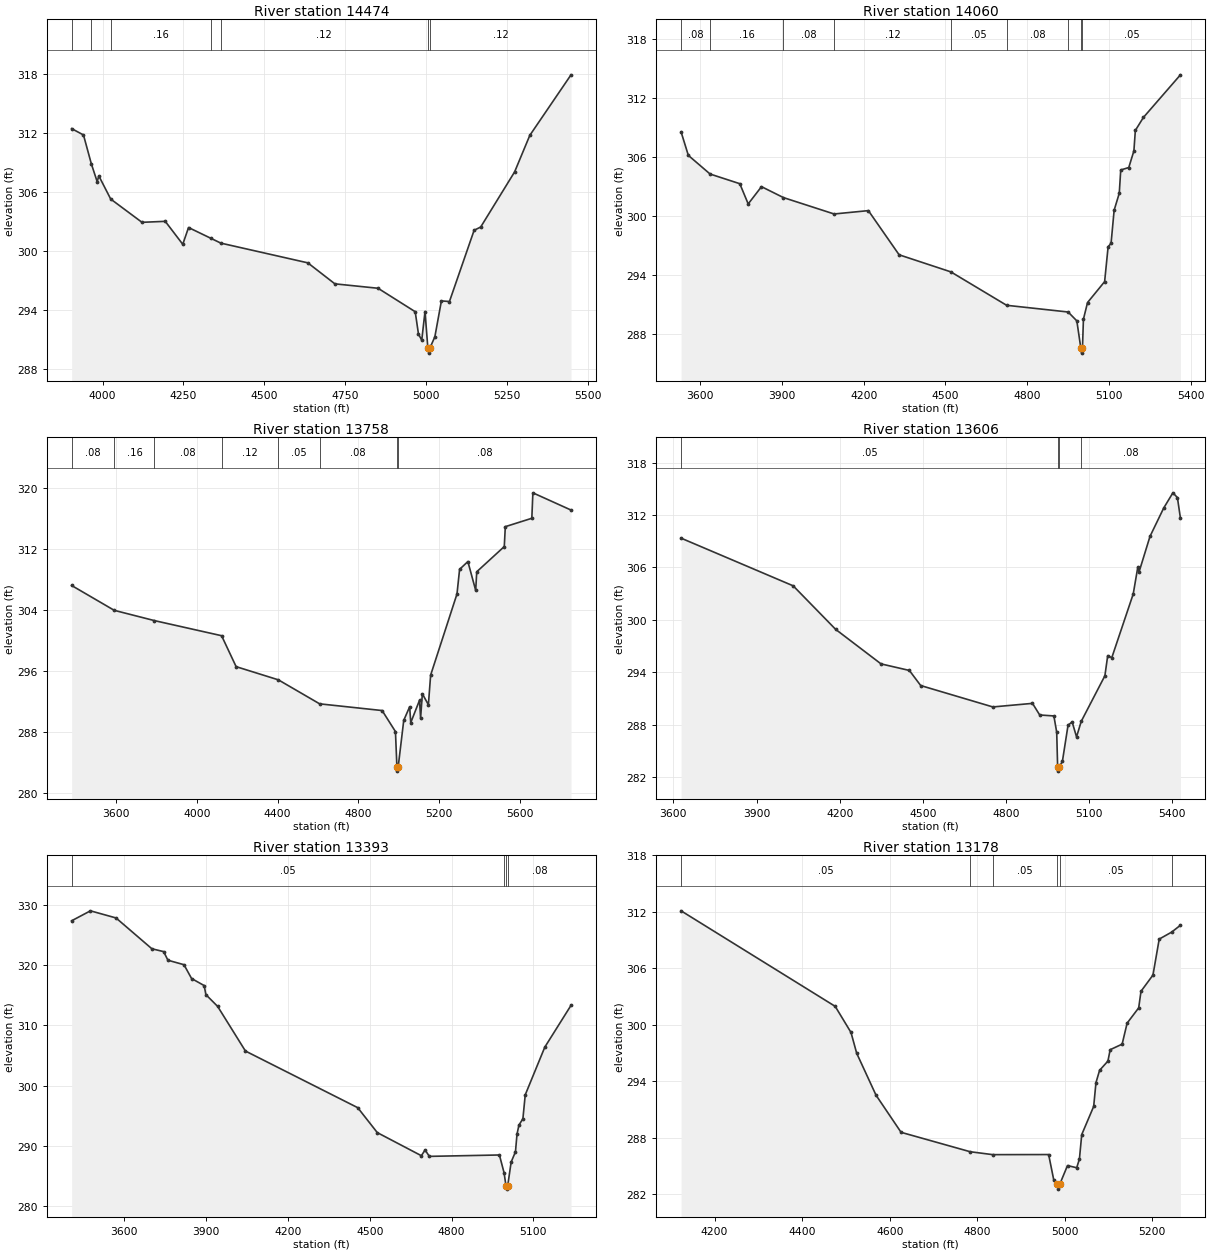
Type RM Length L Ch R = 1,14474,414,414,414
BEGIN DESCRIPTION:
UNT 011 IN BOCR 31.0
END DESCRIPTION:
XS GIS Cut Line= 3
      3671778.12     10595363.36      3672772.93     10595128.98
      3672850.91     10594614.30
#Sta/Elev= 30
  3904.5  312.46  3941.1  311.81  3965.2  308.89  3983.4  307.05  3988.5  307.64
  4025.2  305.28  4121.8  302.91  4193.7  303.01  4247.8  300.67  4265.6  302.38
  4334.7  301.28  4365.4  300.79  4634.1  298.78  4717.7  296.64  4851.0  296.19
  4965.8  293.80  4975.9  291.52  4986.0  290.90  4996.1  293.82  5004.9  290.08
  5007.6  289.58  5010.9  290.08  5026.5  291.24  5046.7  294.90  5071.6  294.84
  5147.8  302.10  5168.1  302.43  5272.9  308.05  5319.8  311.77  5447.1  317.94
#Mann=7,-1,0
  3904.5    0.08       0  3965.2    0.05       0  4025.2    0.16       0
  4334.7    0.08       0  4365.4    0.12       0  5004.9    0.07       0
  5010.9    0.12       0
Bank Sta=5004.9,5010.9
Exp/Cntr=0.3,0.1

Type RM Length L Ch R = 1,14060,302,302,302
BEGIN DESCRIPTION:
Mapping XS 99c8cf41
END DESCRIPTION:
XS GIS Cut Line= 3
      3671829.50     10595371.34      3673201.06     10595058.84
      3673041.76     10594664.07
#Sta/Elev= 30
  3529.8  308.54  3556.5  306.15  3636.3  304.26  3745.3  303.28  3776.1  301.23
  3824.9  302.98  3905.6  301.87  4091.3  300.21  4217.1  300.55  4329.9  296.07
  4519.7  294.34  4724.4  290.95  4950.1  290.27  4982.0  289.37  4996.7  286.60
  4999.5  286.10  5002.7  286.60  5006.2  289.54  5021.3  291.23  5084.0  293.35
  5096.8  296.89  5107.6  297.23  5118.9  300.59  5137.7  302.31  5143.1  304.67
  5172.6  304.92  5191.4  306.61  5196.7  308.68  5226.3  310.00  5362.2  314.32
#Mann=9,-1,0
  3529.8    0.08       0  3636.3    0.16       0  3905.6    0.08       0
  4091.3    0.12       0  4519.7    0.05       0  4724.4    0.08       0
  4950.1    0.05       0  4996.7    0.03       0  5002.7    0.05       0
Bank Sta=4996.7,5002.7
Exp/Cntr=0.3,0.1

Type RM Length L Ch R = 1,13758,152,152,152
BEGIN DESCRIPTION:
UNT 011 IN BOCR 30.0
END DESCRIPTION:
XS GIS Cut Line= 2
      3671794.76     10595395.65      3674207.98     10594864.40
#Sta/Elev= 30
  3380.9  307.18  3591.8  303.92  3790.9  302.57  4122.9  300.59  4194.8  296.53
  4403.8  294.80  4608.1  291.65  4917.3  290.77  4983.2  288.01  4990.5  283.32
  4993.2  282.82  4996.5  283.32  5024.2  289.48  5053.6  291.27  5058.8  289.18
  5102.5  292.13  5107.6  289.76  5116.3  292.97  5146.2  291.53  5157.3  295.42
  5287.7  306.07  5300.6  309.30  5341.6  310.32  5380.3  306.53  5385.4  308.98
  5521.7  312.29  5526.8  314.90  5658.0  316.00  5663.2  319.34  5851.9  317.08
#Mann=8,-1,0
  3380.9    0.08       0  3591.8    0.16       0  3790.9    0.08       0
  4122.9    0.12       0  4403.8    0.05       0  4608.1    0.08       0
  4990.5    0.07       0  4996.5    0.08       0
Bank Sta=4990.5,4996.5
Exp/Cntr=0.3,0.1

Type RM Length L Ch R = 1,13606,213,213,213
BEGIN DESCRIPTION:
UNT 011 IN BOCR 29.0
END DESCRIPTION:
XS GIS Cut Line= 2
      3672073.97     10595481.19      3673836.26     10595103.06
#Sta/Elev= 30
  3627.7  309.36  4032.3  303.90  4185.8  298.91  4349.4  294.96  4451.7  294.21
  4492.6  292.48  4753.0  290.03  4896.1  290.44  4922.1  289.11  4973.3  289.00
  4983.5  287.13  4986.8  283.18  4989.5  282.68  4992.8  283.18  5004.0  283.79
  5024.4  287.94  5039.2  288.31  5055.1  286.60  5072.0  288.38  5157.4  293.60
  5167.6  295.91  5182.3  295.67  5259.7  302.97  5276.0  306.00  5281.1  305.53
  5320.3  309.57  5369.7  312.81  5402.8  314.55  5419.1  314.01  5430.1  311.64
#Mann=4,-1,0
  3627.7    0.05       0  4986.8    0.03       0  4992.8    0.05       0
  5072.0    0.08       0
Bank Sta=4986.8,4992.8
Exp/Cntr=0.3,0.1

Type RM Length L Ch R = 1,13393,215,215,215
BEGIN DESCRIPTION:
Mapping XS d9d3a46f
END DESCRIPTION:
XS GIS Cut Line= 2
      3672188.64     10596081.85      3673774.97     10595165.46
#Sta/Elev= 30
  3406.4  327.33  3475.4  328.98  3569.2  327.80  3700.8  322.69  3743.9  322.22
  3759.7  320.79  3818.5  320.05  3846.4  317.76  3892.6  316.59  3898.9  315.09
  3942.0  313.14  4044.0  305.74  4456.0  296.35  4527.7  292.22  4689.4  288.39
  4703.0  289.34  4718.7  288.28  4975.7  288.51  4992.8  285.57  5000.0  283.35
  5002.8  282.85  5006.0  283.35  5018.8  287.34  5034.6  289.03  5040.3  291.97
  5047.4  293.46  5061.9  294.52  5070.5  298.48  5142.3  306.39  5238.4  313.31
#Mann=4,-1,0
  3406.4    0.05       0  4992.8    0.08       0  5000.0    0.07       0
  5006.0    0.08       0
Bank Sta=5000,5006
Exp/Cntr=0.3,0.1

Type RM Length L Ch R = 1,13178,95,95,95
BEGIN DESCRIPTION:
Mapping XS 2963b201
END DESCRIPTION:
XS GIS Cut Line= 3
      3673218.10     10596225.12      3673621.76     10595613.13
      3673742.86     10595223.86
#Sta/Elev= 30
  4123.4  312.11  4475.5  301.97  4511.6  299.20  4524.6  296.99  4568.8  292.54
  4626.0  288.60  4783.8  286.54  4835.5  286.23  4963.1  286.24  4974.8  283.54
  4982.3  283.07  4985.0  282.57  4988.3  283.07  5006.2  285.07  5027.2  284.84
  5033.4  285.76  5038.7  288.36  5066.0  291.35  5071.2  293.87  5079.5  295.18
  5098.5  296.16  5103.7  297.37  5131.0  297.96  5142.4  300.19  5168.8  301.81
  5174.1  303.57  5201.4  305.29  5215.7  309.11  5244.1  309.85  5264.2  310.58
#Mann=6,-1,0
  4123.4    0.05       0  4783.8    0.16       0  4835.5    0.05       0
  4982.3    0.07       0  4988.3    0.05       0  5244.1    0.08       0
Bank Sta=4982.3,4988.3
Exp/Cntr=0.3,0.1

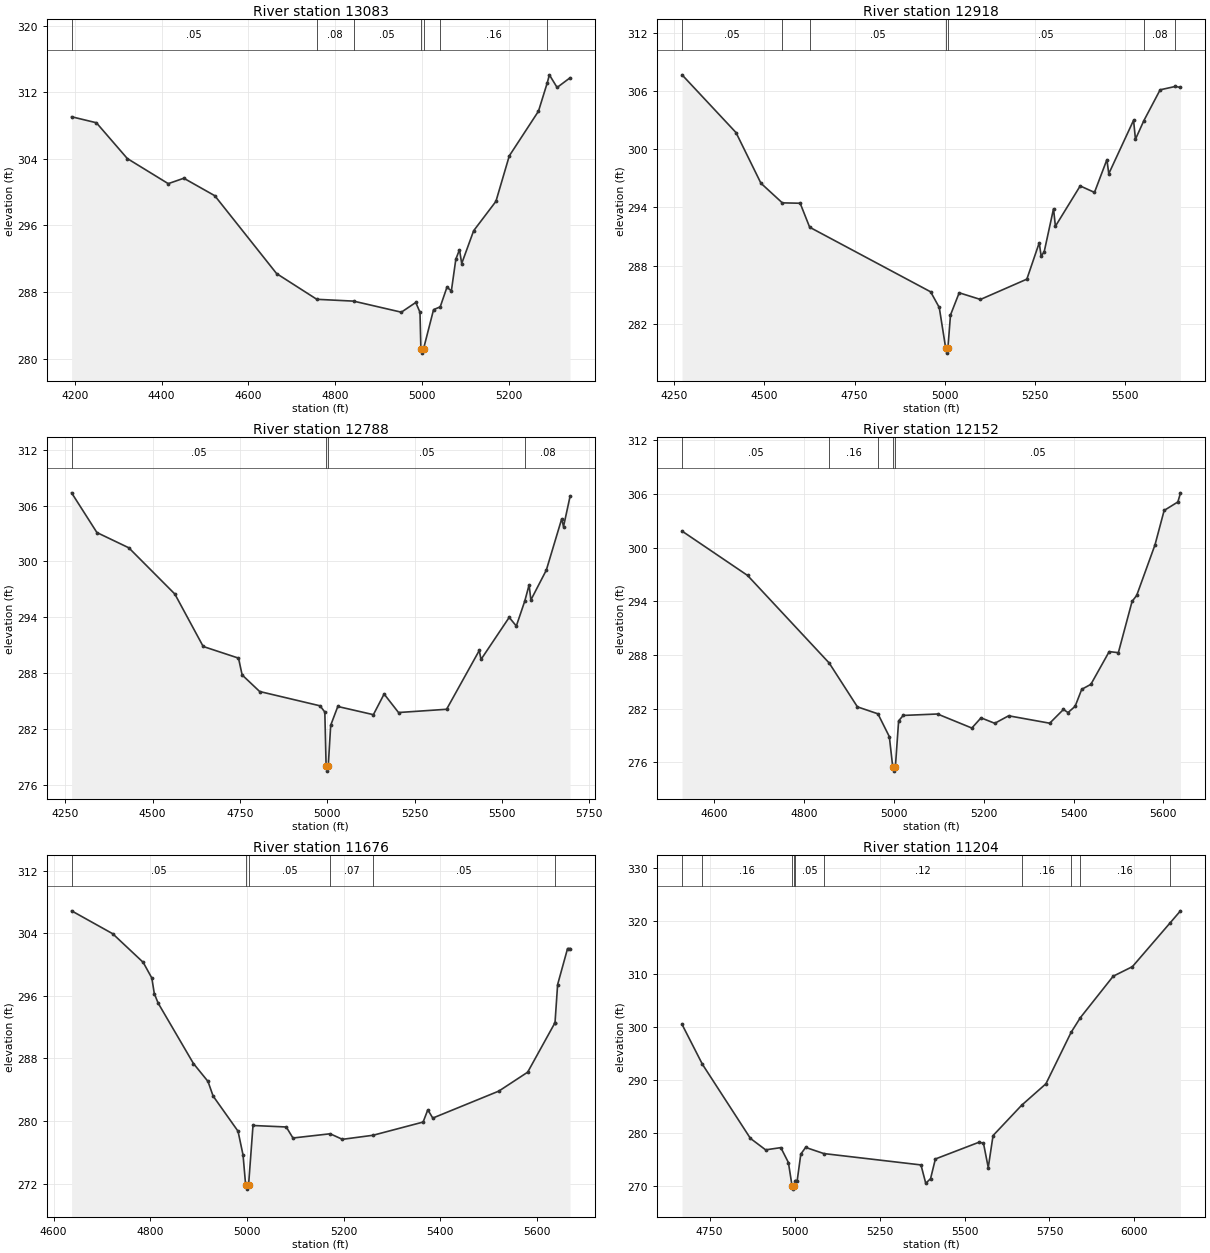
Type RM Length L Ch R = 1,13083,165,165,165
BEGIN DESCRIPTION:
UNT 011 IN BOCR 28.0
END DESCRIPTION:
XS GIS Cut Line= 3
      3673330.98     10596251.11      3673660.82     10595791.08
      3673790.72     10595223.83
#Sta/Elev= 30
  4192.7  309.06  4249.8  308.34  4321.0  304.04  4415.3  301.02  4451.2  301.67
  4522.5  299.57  4664.9  290.21  4757.4  287.12  4842.2  286.90  4952.2  285.57
  4985.4  286.74  4995.1  285.56  4997.2  281.15  5000.0  280.65  5003.2  281.15
  5026.4  285.88  5041.7  286.21  5057.2  288.57  5067.4  288.13  5077.7  291.95
  5086.1  293.08  5091.2  291.42  5118.7  295.36  5170.0  298.89  5200.8  304.36
  5268.0  309.73  5288.3  313.15  5293.1  314.10  5310.9  312.58  5340.7  313.74
#Mann=7,-1,0
  4192.7    0.05       0  4757.4    0.08       0  4842.2    0.05       0
  4997.2    0.04       0  5003.2    0.05       0  5041.7    0.16       0
  5288.3    0.05       0
Bank Sta=4997.2,5003.2
Exp/Cntr=0.3,0.1

Type RM Length L Ch R = 1,12918,130,130,130
BEGIN DESCRIPTION:
UNT 011 IN BOCR 27.0
END DESCRIPTION:
XS GIS Cut Line= 3
      3673682.52     10596377.00      3673786.69     10595838.82
      3674008.05     10595035.84
#Sta/Elev= 30
  4271.9  307.72  4421.4  301.75  4490.5  296.51  4549.7  294.48  4599.2  294.44
  4625.5  291.96  4960.7  285.28  4984.6  283.66  5002.5  279.44  5005.2  278.94
  5008.5  279.44  5015.7  282.88  5039.8  285.18  5098.7  284.49  5227.3  286.59
  5261.6  290.35  5266.8  289.00  5275.1  289.38  5301.2  293.87  5306.4  292.06
  5375.1  296.23  5414.7  295.56  5449.1  298.95  5454.3  297.49  5523.0  303.02
  5528.2  301.06  5551.6  302.99  5596.6  306.17  5639.0  306.52  5653.0  306.41
#Mann=7,-1,0
  4271.9    0.05       0  4549.7    0.08       0  4625.5    0.05       0
  5002.5    0.03       0  5008.5    0.05       0  5551.6    0.08       0
  5639.0     0.1       0
Bank Sta=5002.5,5008.5
Exp/Cntr=0.3,0.1

Type RM Length L Ch R = 1,12788,636,636,636
BEGIN DESCRIPTION:
Mapping XS 13a86876
END DESCRIPTION:
XS GIS Cut Line= 3
      3673834.43     10596411.72      3673968.98     10595613.13
      3674099.18     10595009.86
#Sta/Elev= 30
  4268.2  307.38  4340.7  303.11  4432.0  301.47  4563.8  296.50  4645.0  290.86
  4746.0  289.61  4756.5  287.80  4806.6  286.02  4979.6  284.48  4993.2  283.81
  4996.9  277.96  4999.6  277.46  5002.9  277.96  5010.0  282.39  5030.3  284.41
  5132.2  283.53  5162.9  285.75  5204.2  283.76  5341.8  284.11  5435.3  290.43
  5440.4  289.47  5521.0  293.99  5541.4  293.06  5565.6  295.74  5578.0  297.48
  5583.1  295.86  5627.3  299.07  5671.4  304.59  5676.5  303.74  5695.2  306.99
#Mann=4,-1,0
  4268.2    0.05       0  4996.9    0.03       0  5002.9    0.05       0
  5565.6    0.08       0
Bank Sta=4996.9,5002.9
Exp/Cntr=0.3,0.1

Type RM Length L Ch R = 1,12152,476,476,476
BEGIN DESCRIPTION:
UNT 011 IN BOCR 26.0
END DESCRIPTION:
XS GIS Cut Line= 2
      3674615.76     10596043.28      3674398.87     10594954.48
#Sta/Elev= 30
  4527.8  301.85  4673.7  296.89  4855.6  287.09  4918.4  282.19  4964.1  281.41
  4989.5  278.86  4997.0  275.50  4999.7  275.00  5003.0  275.50  5010.2  280.62
  5020.4  281.23  5096.8  281.39  5173.3  279.82  5193.7  280.96  5224.3  280.35
  5255.2  281.19  5346.7  280.36  5377.3  281.90  5387.5  281.55  5403.3  282.25
  5418.0  284.15  5438.4  284.71  5479.2  288.37  5499.6  288.25  5530.2  293.99
  5540.4  294.65  5581.2  300.31  5601.6  304.16  5632.2  305.11  5638.0  306.13
#Mann=5,-1,0
  4527.8    0.05       0  4855.6    0.16       0  4964.1    0.05       0
  4997.0    0.03       0  5003.0    0.05       0
Bank Sta=4997,5003
Exp/Cntr=0.3,0.1

Type RM Length L Ch R = 1,11676,472,472,472
BEGIN DESCRIPTION:
UNT 011 IN BOCR 25.0
END DESCRIPTION:
XS GIS Cut Line= 2
      3675067.14     10595843.57      3674806.71     10594845.28
#Sta/Elev= 30
  4637.1  306.89  4722.2  303.96  4785.3  300.30  4803.2  298.29  4808.3  296.30
  4816.3  295.08  4889.3  287.36  4919.4  285.07  4930.0  283.20  4981.6  278.70
  4992.0  275.65  4997.4  271.79  5000.2  271.29  5003.4  271.79  5012.6  279.43
  5081.4  279.24  5095.3  277.83  5172.3  278.37  5197.6  277.66  5261.0  278.18
  5364.7  279.87  5374.4  281.44  5384.7  280.38  5521.4  283.83  5581.1  286.25
  5636.8  292.48  5637.7  292.57  5643.1  297.46  5663.7  302.07  5668.8  302.07
#Mann=6,-1,0
  4637.1    0.05       0  4997.4    0.03       0  5003.4    0.05       0
  5172.3    0.07       0  5261.0    0.05       0  5636.8    0.08       0
Bank Sta=4997.4,5003.4
Exp/Cntr=0.3,0.1

Type RM Length L Ch R = 1,11204,478,478,478
BEGIN DESCRIPTION:
UNT 011 IN BOCR 24.0
END DESCRIPTION:
XS GIS Cut Line= 3
      3675249.61     10595710.18      3675399.61     10595410.19
      3676199.63     10594610.17
#Sta/Elev= 30
  4668.8  300.44  4728.6  292.94  4870.0  278.96  4914.8  276.80  4959.5  277.22
  4981.8  274.41  4992.8  269.90  4995.6  269.40  4998.8  269.90  5001.9  271.02
  5007.7  271.02  5018.3  276.00  5032.5  277.26  5086.1  276.10  5371.9  273.96
  5386.0  270.49  5400.2  271.39  5414.3  275.08  5541.6  278.21  5555.7  278.09
  5569.9  273.46  5584.0  279.49  5668.2  285.21  5739.6  289.25  5813.7  298.94
  5840.7  301.69  5937.6  309.52  5994.1  311.32  6104.8  319.55  6135.6  321.84
#Mann=10,-1,0
  4668.8    0.05       0  4728.6    0.16       0  4992.8    0.07       0
  4998.8    0.16       0  5001.9    0.05       0  5086.1    0.12       0
  5668.2    0.16       0  5813.7    0.12       0  5840.7    0.16       0
  6104.8    0.05       0
Bank Sta=4992.8,4998.8
Exp/Cntr=0.3,0.1