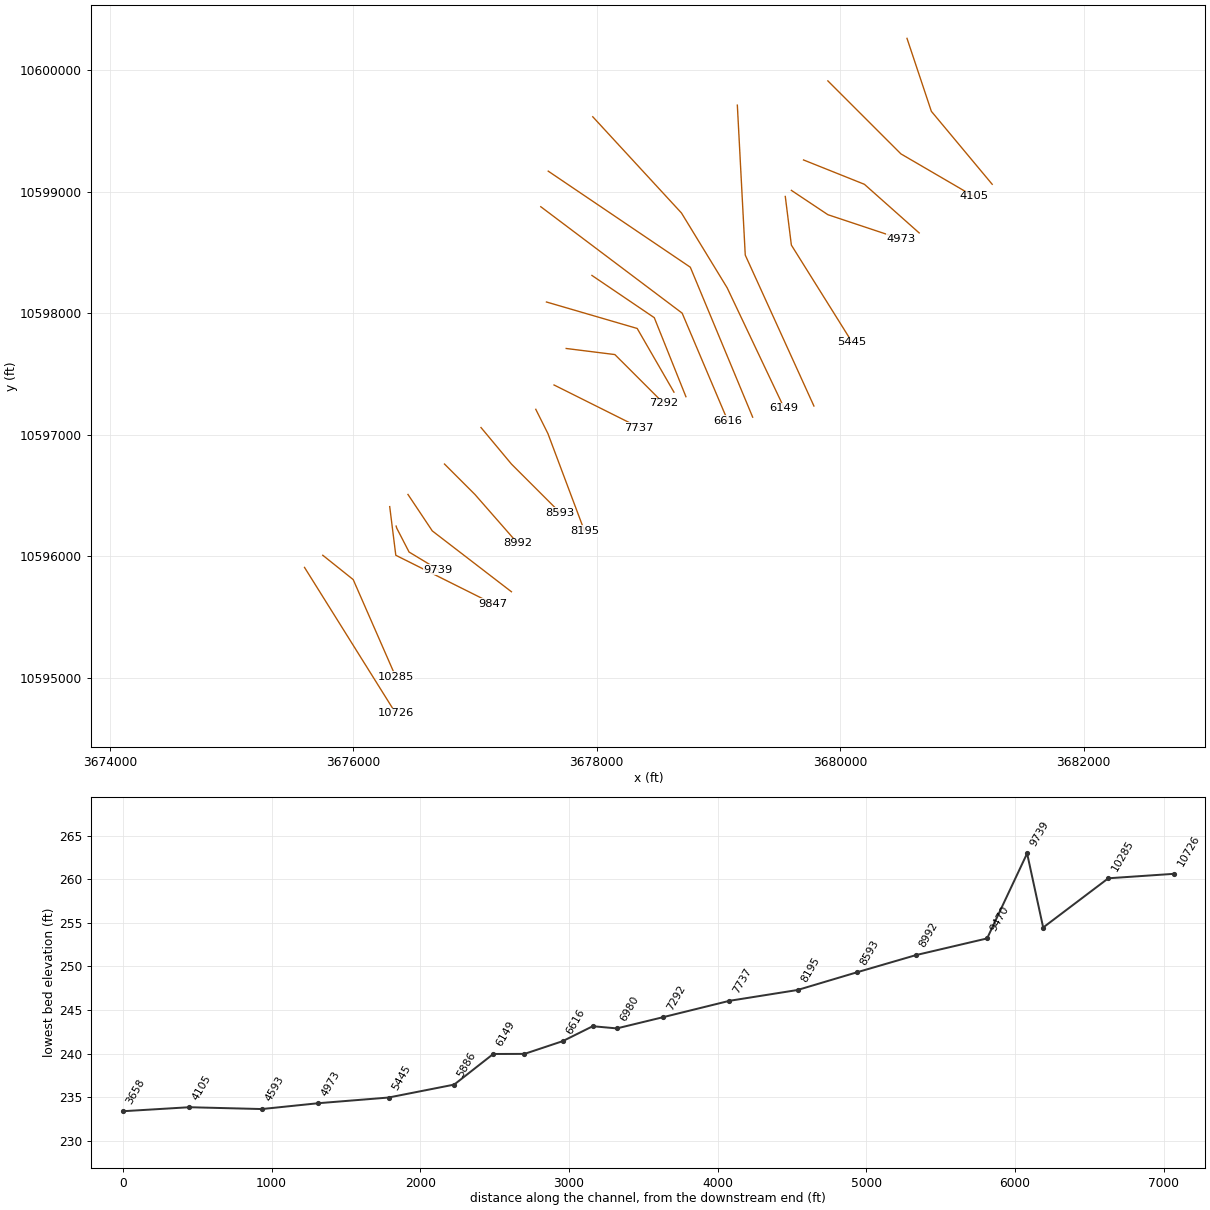
HEC-RAS study UNT 011 IN BOCR.prj: UNT 011 IN BOCR Base Level Engineering

--- UNT 011 IN BOCR.g01 (geometry) --- (continued)

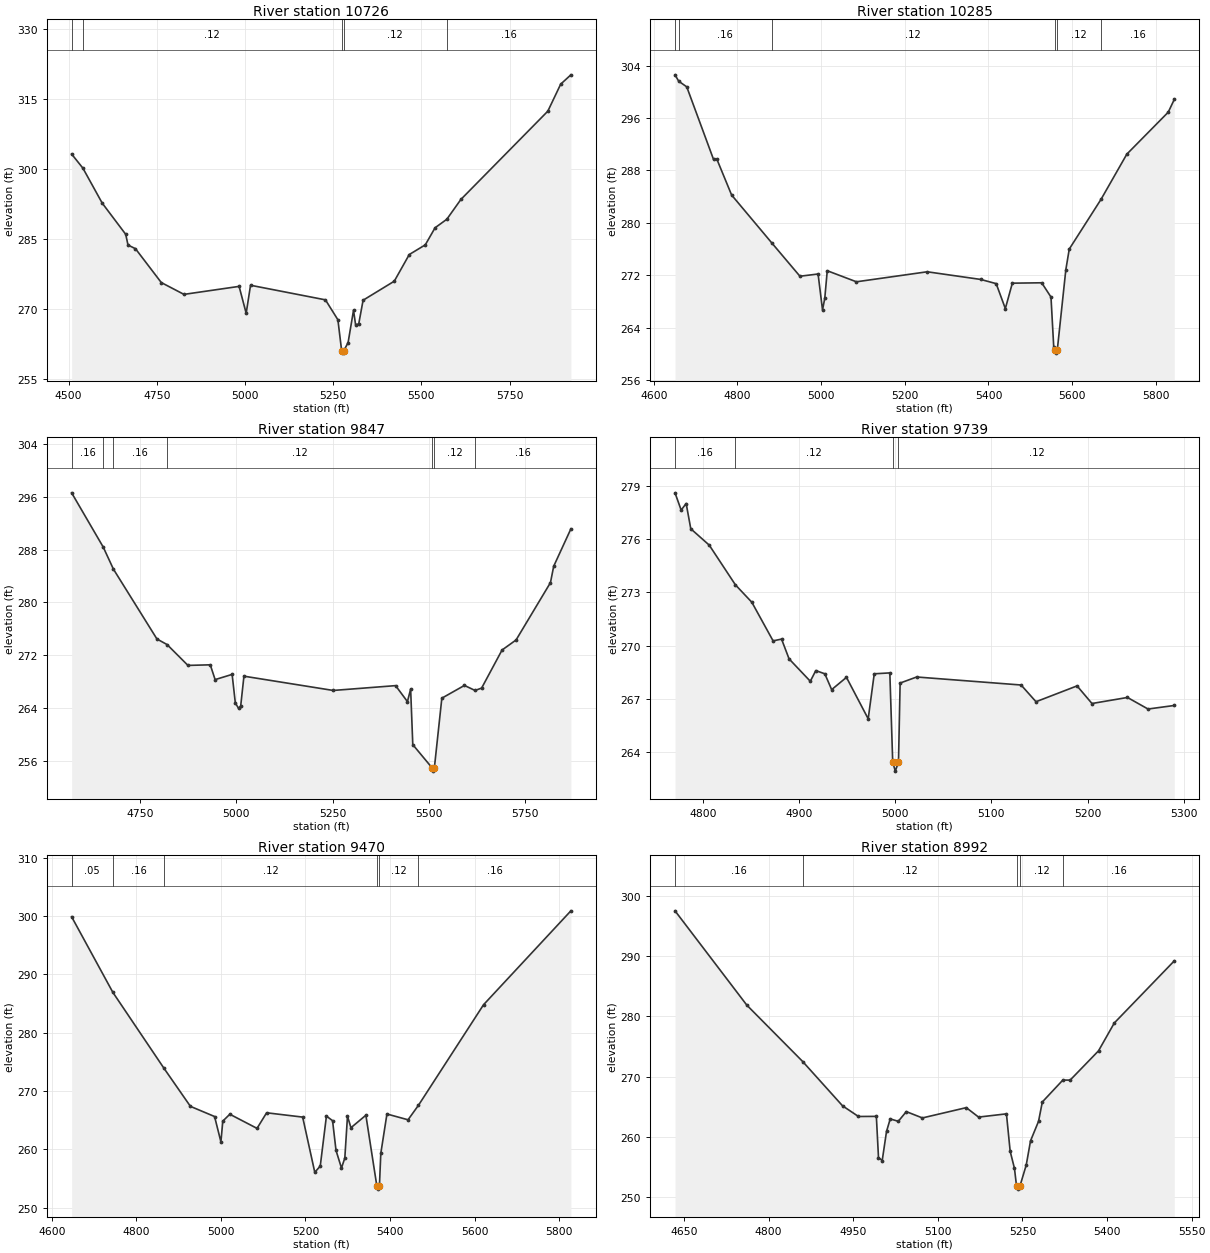
Type RM Length L Ch R = 1,10726,441,441,441
BEGIN DESCRIPTION:
UNT 011 IN BOCR 23.0
END DESCRIPTION:
XS GIS Cut Line= 3
      3675599.60     10595910.20      3675849.61     10595510.19
      3676349.60     10594710.20
#Sta/Elev= 30
  4508.8  303.17  4540.8  300.15  4595.5  292.68  4662.1  286.01  4668.6  283.72
  4689.8  282.93  4762.9  275.70  4827.2  273.17  4983.5  274.88  5003.5  269.13
  5015.9  275.12  5228.2  272.00  5263.5  267.74  5274.1  261.11  5276.8  260.61
  5280.1  261.11  5292.4  262.86  5307.8  269.78  5313.6  266.69  5322.5  266.84
  5334.9  271.92  5423.3  275.99  5465.8  281.69  5511.2  283.76  5538.9  287.41
  5572.2  289.23  5612.0  293.46  5858.5  312.34  5895.0  318.12  5923.9  320.11
#Mann=5,-1,0
  4508.8    0.16       0  4540.8    0.12       0  5274.1    0.07       0
  5280.1    0.12       0  5572.2    0.16       0
Bank Sta=5274.1,5280.1
Exp/Cntr=0.3,0.1

Type RM Length L Ch R = 1,10285,438,438,438
BEGIN DESCRIPTION:
UNT 011 IN BOCR 22.0
END DESCRIPTION:
XS GIS Cut Line= 3
      3675749.57     10596010.22      3675999.61     10595810.19
      3676349.60     10595010.20
#Sta/Elev= 30
  4650.8  302.59  4659.6  301.62  4678.9  300.75  4742.9  289.67  4750.9  289.70
  4786.1  284.24  4882.2  276.92  4949.4  271.84  4992.8  272.18  5003.4  266.69
  5008.8  268.48  5014.7  272.68  5084.4  270.99  5253.6  272.52  5381.5  271.35
  5418.5  270.71  5440.4  266.90  5457.1  270.78  5527.3  270.84  5549.5  268.66
  5556.1  261.00  5558.6  260.60  5561.3  260.10  5564.6  260.60  5585.0  272.84
  5593.2  275.99  5669.2  283.59  5730.8  290.48  5829.8  296.89  5844.2  298.83
#Mann=6,-1,0
  4650.8    0.05       0  4659.6    0.16       0  4882.2    0.12       0
  5558.6    0.07       0  5564.6    0.12       0  5669.2    0.16       0
Bank Sta=5558.6,5564.6
Exp/Cntr=0.3,0.1

Type RM Length L Ch R = 1,9847,108,108,108
BEGIN DESCRIPTION:
UNT 011 IN BOCR 21.0
END DESCRIPTION:
XS GIS Cut Line= 3
      3676299.61     10596410.16      3676349.61     10596010.19
      3677149.60     10595610.20
#Sta/Elev= 30
  4572.0  296.58  4654.1  288.37  4680.6  285.03  4793.7  274.46  4820.2  273.61
  4874.3  270.46  4932.3  270.55  4944.9  268.31  4989.1  269.10  4997.4  264.78
  5005.8  263.96  5011.4  264.33  5019.8  268.83  5251.8  266.67  5413.9  267.40
  5444.7  264.98  5453.0  266.88  5458.6  258.47  5508.7  254.96  5511.5  254.46
  5514.7  254.96  5534.1  265.50  5592.8  267.43  5620.4  266.67  5637.5  267.03
  5690.6  272.79  5727.0  274.31  5816.4  282.99  5824.8  285.47  5869.5  291.13
#Mann=7,-1,0
  4572.0    0.16       0  4654.1    0.05       0  4680.6    0.16       0
  4820.2    0.12       0  5508.7    0.07       0  5514.7    0.12       0
  5620.4    0.16       0
Bank Sta=5508.7,5514.7
Exp/Cntr=0.3,0.1

Type RM Length L Ch R = 1,9739,269,269,269
BEGIN DESCRIPTION:
Mapping XS 4f00ba84
END DESCRIPTION:
XS GIS Cut Line= 4
      3676352.38     10596249.93      3676357.25     10596233.25
      3676458.64     10596036.72      3676698.90     10595891.60
#Sta/Elev= 30
  4771.0  278.59  4777.4  277.62  4782.6  277.99  4787.4  276.57  4806.6  275.65
  4833.8  273.42  4850.9  272.44  4873.0  270.27  4881.8  270.37  4889.6  269.26
  4911.7  268.00  4917.4  268.60  4926.8  268.42  4933.9  267.53  4949.3  268.22
  4971.9  265.89  4978.2  268.42  4994.4  268.47  4997.4  263.45  5000.1  262.95
  5003.4  263.45  5005.1  267.90  5022.3  268.24  5130.9  267.79  5146.4  266.85
  5189.1  267.74  5204.6  266.75  5241.5  267.09  5262.9  266.44  5290.2  266.64
#Mann=4,-1,0
  4771.0    0.16       0  4833.8    0.12       0  4997.4    0.07       0
  5003.4    0.12       0
Bank Sta=4997.4,5003.4
Exp/Cntr=0.3,0.1

Type RM Length L Ch R = 1,9470,478,478,478
BEGIN DESCRIPTION:
UNT 011 IN BOCR 20.0
END DESCRIPTION:
XS GIS Cut Line= 3
      3676449.62     10596510.17      3676649.61     10596210.19
      3677299.61     10595710.18
#Sta/Elev= 30
  4647.1  299.87  4744.6  286.92  4865.5  273.91  4928.0  267.39  4985.1  265.65
  5000.1  261.31  5004.6  264.87  5021.2  266.04  5085.5  263.62  5108.2  266.29
  5193.4  265.55  5222.1  256.09  5235.0  257.16  5249.6  265.72  5264.1  264.94
  5272.3  259.84  5285.2  256.82  5293.1  258.54  5299.4  265.70  5307.6  263.73
  5342.9  265.87  5368.9  253.71  5371.7  253.21  5374.9  253.71  5378.2  259.33
  5392.7  266.08  5442.6  265.09  5467.3  267.58  5621.1  284.80  5827.7  300.89
#Mann=6,-1,0
  4647.1    0.05       0  4744.6    0.16       0  4865.5    0.12       0
  5368.9    0.07       0  5374.9    0.12       0  5467.3    0.16       0
Bank Sta=5368.9,5374.9
Exp/Cntr=0.3,0.1

Type RM Length L Ch R = 1,8992,399,399,399
BEGIN DESCRIPTION:
UNT 011 IN BOCR 19.0
END DESCRIPTION:
XS GIS Cut Line= 3
      3676749.62     10596760.17      3676999.61     10596510.19
      3677349.58     10596110.22
#Sta/Elev= 30
  4634.2  297.51  4761.5  281.85  4860.5  272.49  4931.2  265.13  4959.4  263.36
  4991.1  263.38  4994.9  256.55  5001.5  256.05  5009.1  260.87  5015.7  262.96
  5030.0  262.56  5044.2  264.17  5072.7  263.12  5150.5  264.83  5172.3  263.26
  5221.7  263.80  5228.3  257.59  5235.9  254.75  5239.6  251.80  5242.3  251.30
  5245.6  251.80  5256.8  255.31  5264.4  259.32  5278.6  262.56  5285.3  265.77
  5321.7  269.41  5334.6  269.40  5384.9  274.26  5412.9  278.89  5519.2  289.20
#Mann=5,-1,0
  4634.2    0.16       0  4860.5    0.12       0  5239.6    0.07       0
  5245.6    0.12       0  5321.7    0.16       0
Bank Sta=5239.6,5245.6
Exp/Cntr=0.3,0.1

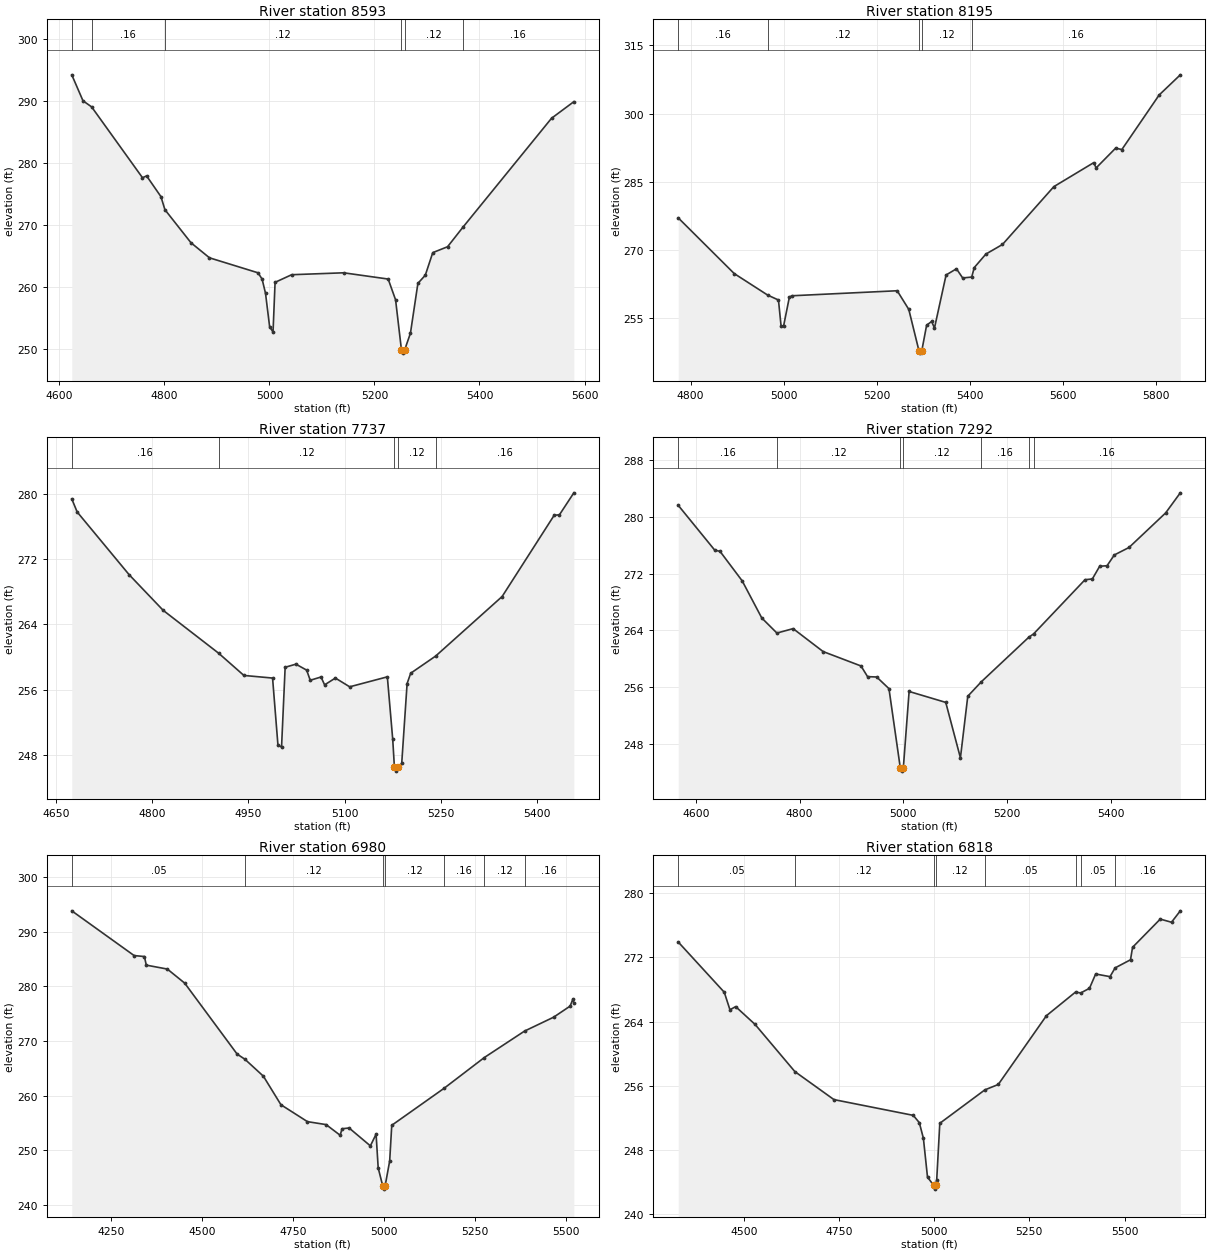
Type RM Length L Ch R = 1,8593,398,398,398
BEGIN DESCRIPTION:
UNT 011 IN BOCR 18.0
END DESCRIPTION:
XS GIS Cut Line= 3
      3677049.64     10597060.16      3677299.61     10596760.19
      3677699.64     10596360.16
#Sta/Elev= 30
  4623.5  294.29  4644.9  290.09  4661.3  289.11  4758.2  277.66  4766.0  277.96
  4793.3  274.61  4800.9  272.50  4850.6  267.15  4885.8  264.72  4978.2  262.30
  4986.0  261.28  4992.5  258.98  5000.3  253.60  5006.8  252.72  5010.7  260.76
  5042.3  261.99  5141.3  262.30  5226.1  261.29  5240.2  257.93  5251.4  249.82
  5254.1  249.32  5257.4  249.82  5268.5  252.54  5282.7  260.59  5296.8  261.91
  5311.0  265.56  5339.2  266.51  5368.3  269.65  5537.2  287.27  5579.7  289.95
#Mann=6,-1,0
  4623.5     0.1       0  4661.3    0.16       0  4800.9    0.12       0
  5251.4    0.07       0  5257.4    0.12       0  5368.3    0.16       0
Bank Sta=5251.4,5257.4
Exp/Cntr=0.3,0.1

Type RM Length L Ch R = 1,8195,458,458,458
BEGIN DESCRIPTION:
UNT 011 IN BOCR 17.0
END DESCRIPTION:
XS GIS Cut Line= 3
      3677499.62     10597210.16      3677599.61     10597010.19
      3677899.62     10596210.17
#Sta/Elev= 30
  4773.6  277.05  4893.8  264.80  4965.7  260.06  4988.8  258.98  4994.4  253.27
  4999.8  253.27  5012.3  259.65  5018.5  259.92  5243.7  261.02  5268.6  256.92
  5290.5  247.80  5293.3  247.30  5296.5  247.80  5306.9  253.44  5317.6  254.26
  5323.8  252.83  5348.7  264.49  5371.0  265.85  5384.3  263.83  5403.7  264.03
  5409.2  266.12  5434.2  269.09  5469.8  271.20  5580.1  283.92  5665.6  289.19
  5670.9  288.04  5712.7  292.38  5726.1  292.08  5806.2  304.08  5851.6  308.51
#Mann=5,-1,0
  4773.6    0.16       0  4965.7    0.12       0  5290.5    0.07       0
  5296.5    0.12       0  5403.7    0.16       0
Bank Sta=5290.5,5296.5
Exp/Cntr=0.3,0.1

Type RM Length L Ch R = 1,7737,445,445,445
BEGIN DESCRIPTION:
UNT 011 IN BOCR 16.0
END DESCRIPTION:
XS GIS Cut Line= 3
      3677649.62     10597410.18      3677949.61     10597260.19
      3678349.60     10597060.19
#Sta/Elev= 30
  4674.8  279.35  4683.2  277.75  4764.2  270.08  4817.3  265.72  4903.7  260.48
  4943.1  257.76  4987.8  257.44  4996.2  249.22  5001.8  249.01  5007.4  258.76
  5024.2  259.14  5040.9  258.41  5046.5  257.17  5063.3  257.57  5068.9  256.61
  5085.7  257.44  5108.0  256.37  5166.7  257.59  5175.1  249.93  5177.7  246.56
  5180.4  246.06  5183.7  246.56  5189.1  247.00  5197.5  256.77  5203.1  258.03
  5242.0  260.13  5345.6  267.41  5426.7  277.34  5435.0  277.41  5457.4  280.09
#Mann=5,-1,0
  4674.8    0.16       0  4903.7    0.12       0  5177.7    0.07       0
  5183.7    0.12       0  5242.0    0.16       0
Bank Sta=5177.7,5183.7
Exp/Cntr=0.3,0.1

Type RM Length L Ch R = 1,7292,312,312,312
BEGIN DESCRIPTION:
UNT 011 IN BOCR 15.0
END DESCRIPTION:
XS GIS Cut Line= 3
      3677749.62     10597710.19      3678149.61     10597660.19
      3678549.62     10597260.18
#Sta/Elev= 30
  4565.7  281.63  4636.2  275.31  4646.3  275.15  4689.1  270.99  4726.9  265.76
  4756.1  263.64  4787.4  264.26  4845.3  261.03  4918.4  259.00  4931.0  257.50
  4948.6  257.45  4972.3  255.81  4994.1  244.69  4996.8  244.19  5000.1  244.69
  5011.2  255.41  5081.9  253.87  5110.2  246.06  5124.4  254.74  5150.6  256.78
  5242.0  263.04  5251.4  263.52  5350.6  271.15  5364.8  271.26  5378.9  273.05
  5393.1  273.12  5407.2  274.64  5435.5  275.69  5506.2  280.56  5534.5  283.39
#Mann=7,-1,0
  4565.7    0.16       0  4756.1    0.12       0  4994.1    0.07       0
  5000.1    0.12       0  5150.6    0.16       0  5242.0    0.12       0
  5251.4    0.16       0
Bank Sta=4994.1,5000.1
Exp/Cntr=0.3,0.1

Type RM Length L Ch R = 1,6980,162,162,162
BEGIN DESCRIPTION:
Mapping XS 80b5c59e
END DESCRIPTION:
XS GIS Cut Line= 3
      3677587.26     10598092.47      3678332.88     10597874.83
      3678634.90     10597351.34
#Sta/Elev= 30
  4141.5  293.79  4313.0  285.61  4341.3  285.43  4346.5  283.86  4404.4  283.14
  4452.1  280.57  4596.4  267.59  4617.8  266.65  4668.6  263.55  4716.9  258.33
  4789.8  255.24  4841.1  254.70  4879.8  252.75  4885.0  253.94  4904.4  254.08
  4962.9  250.81  4978.6  252.95  4984.4  246.78  4997.2  243.40  4999.9  242.90
  5003.2  243.40  5016.0  248.05  5021.7  254.57  5165.5  261.33  5276.3  266.96
  5387.0  271.80  5467.0  274.34  5512.4  276.37  5520.1  277.67  5522.6  276.95
#Mann=7,-1,0
  4141.5    0.05       0  4617.8    0.12       0  4997.2    0.07       0
  5003.2    0.12       0  5165.5    0.16       0  5276.3    0.12       0
  5387.0    0.16       0
Bank Sta=4997.2,5003.2
Exp/Cntr=0.3,0.1

Type RM Length L Ch R = 1,6818,202,202,202
BEGIN DESCRIPTION:
UNT 011 IN BOCR 14.0
END DESCRIPTION:
XS GIS Cut Line= 3
      3677961.13     10598310.68      3678473.32     10597963.44
      3678733.18     10597313.78
#Sta/Elev= 30
  4327.9  273.90  4448.8  267.65  4463.7  265.47  4478.7  265.86  4529.6  263.65
  4634.1  257.78  4736.8  254.29  4945.1  252.33  4961.0  251.42  4971.7  249.48
  4982.5  244.64  4998.3  243.65  5001.1  243.15  5004.3  243.65  5006.7  244.32
  5014.8  251.34  5133.1  255.50  5168.3  256.17  5294.8  264.73  5371.2  267.67
  5384.8  267.56  5407.9  268.14  5424.1  269.92  5461.8  269.59  5475.2  270.68
  5515.6  271.69  5521.0  273.24  5593.7  276.75  5623.3  276.36  5646.4  277.78
#Mann=8,-1,0
  4327.9    0.05       0  4634.1    0.12       0  4998.3    0.07       0
  5004.3    0.12       0  5133.1    0.05       0  5371.2    0.12       0
  5384.8    0.05       0  5475.2    0.16       0
Bank Sta=4998.3,5004.3
Exp/Cntr=0.3,0.1

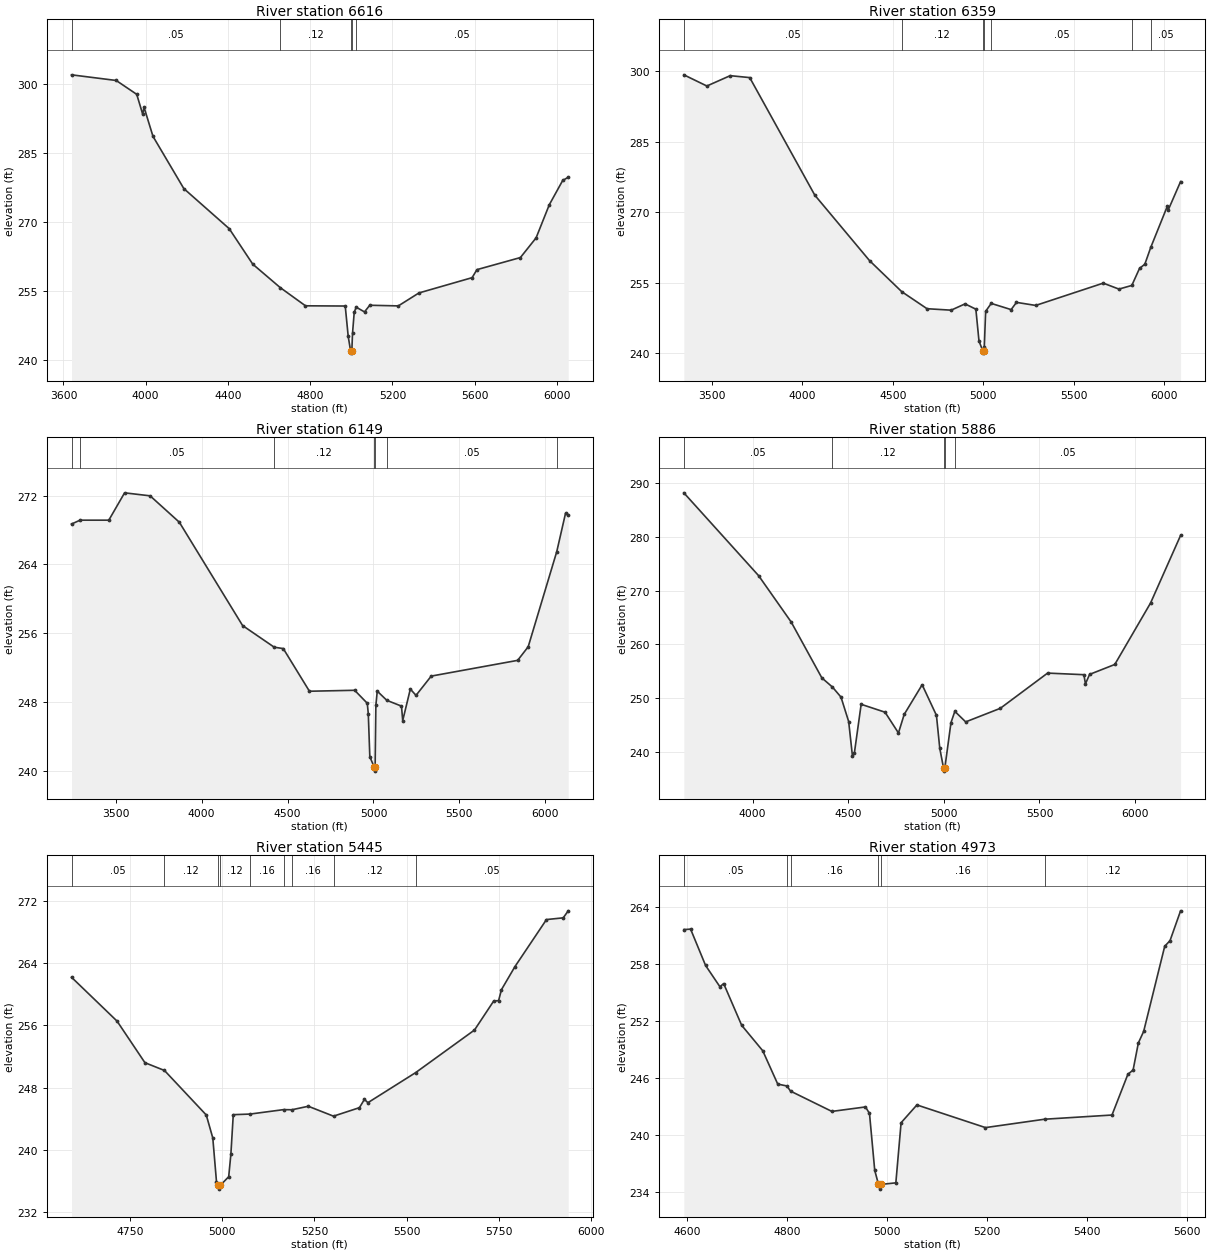
Type RM Length L Ch R = 1,6616,257,257,257
BEGIN DESCRIPTION:
Mapping XS cca579ca
END DESCRIPTION:
XS GIS Cut Line= 3
      3677540.82     10598875.75      3678702.27     10598000.75
      3679077.26     10597115.35
#Sta/Elev= 30
  3639.3  302.07  3856.6  300.84  3956.5  297.82  3985.7  293.47  3991.9  295.02
  4035.6  288.66  4185.5  277.29  4406.2  268.56  4520.8  260.82  4654.0  255.73
  4777.1  251.75  4970.5  251.70  4985.0  245.07  4996.6  241.94  4999.4  241.44
  5002.6  241.94  5005.9  245.74  5014.2  250.33  5023.8  251.45  5064.2  250.42
  5089.8  251.87  5228.7  251.73  5328.9  254.55  5587.4  257.88  5611.1  259.63
  5822.3  262.26  5898.7  266.55  5962.9  273.77  6028.0  279.05  6055.0  279.76
#Mann=5,-1,0
  3639.3    0.05       0  4654.0    0.12       0  4996.6    0.07       0
  5002.6    0.12       0  5023.8    0.05       0
Bank Sta=4996.6,5002.6
Exp/Cntr=0.3,0.1

Type RM Length L Ch R = 1,6359,210,210,210
BEGIN DESCRIPTION:
UNT 011 IN BOCR 13.0
END DESCRIPTION:
XS GIS Cut Line= 3
      3677601.85     10599168.26      3678769.40     10598378.32
      3679281.56     10597145.66
#Sta/Elev= 30
  3345.1  299.26  3472.3  296.88  3601.2  299.08  3709.1  298.67  4068.6  273.63
  4371.2  259.68  4548.7  253.08  4688.8  249.44  4821.8  249.13  4898.8  250.47
  4958.5  249.34  4975.8  242.56  4996.7  240.48  4999.4  239.98  5002.7  240.48
  5005.1  241.28  5012.6  248.89  5043.4  250.57  5153.4  249.25  5182.9  250.79
  5289.2  250.14  5662.4  254.89  5749.0  253.62  5820.2  254.40  5862.8  258.03
  5892.1  258.92  5924.7  262.49  6016.8  271.31  6022.2  270.55  6089.6  276.52
#Mann=7,-1,0
  3345.1    0.05       0  4548.7    0.12       0  4996.7    0.07       0
  5002.7    0.12       0  5043.4    0.05       0  5820.2    0.08       0
  5924.7    0.05       0
Bank Sta=4996.7,5002.7
Exp/Cntr=0.3,0.1

Type RM Length L Ch R = 1,6149,263,263,263
BEGIN DESCRIPTION:
Mapping XS 55578a13
END DESCRIPTION:
XS GIS Cut Line= 4
      3677967.91     10599615.32      3678697.06     10598823.67
      3679072.06     10598209.08      3679540.80     10597219.52
#Sta/Elev= 30
  3242.3  268.70  3292.0  269.15  3459.4  269.15  3551.3  272.33  3699.9  271.98
  3870.0  268.91  4238.0  256.90  4422.2  254.38  4474.9  254.22  4627.2  249.26
  4890.3  249.37  4963.9  247.86  4969.7  246.65  4978.7  241.64  5003.5  240.47
  5006.2  239.97  5009.5  240.47  5013.8  247.62  5021.9  249.27  5077.7  248.20
  5162.9  247.53  5170.1  245.85  5214.4  249.51  5247.5  248.78  5336.1  251.02
  5839.1  252.85  5900.4  254.43  6066.8  265.50  6117.6  269.94  6133.5  269.78
#Mann=7,-1,0
  3242.3    0.12       0  3292.0    0.05       0  4422.2    0.12       0
  5003.5    0.07       0  5009.5    0.12       0  5077.7    0.05       0
  6066.8    0.16       0
Bank Sta=5003.5,5009.5
Exp/Cntr=0.3,0.1

Type RM Length L Ch R = 1,5886,441,441,441
BEGIN DESCRIPTION:
UNT 011 IN BOCR 12.0
END DESCRIPTION:
XS GIS Cut Line= 3
      3679155.68     10599710.75      3679220.79     10598478.14
      3679784.83     10597237.25
#Sta/Elev= 30
  3640.6  288.18  4031.7  272.78  4201.9  264.17  4362.2  253.79  4417.7  252.08
  4462.3  250.22  4502.4  245.68  4522.4  239.22  4532.4  239.85  4567.8  248.88
  4692.6  247.41  4762.8  243.55  4792.8  247.00  4886.7  252.51  4961.4  246.83
  4978.9  240.68  4999.0  236.96  5001.7  236.46  5005.0  236.96  5037.4  245.47
  5057.6  247.57  5114.3  245.61  5295.3  248.13  5542.7  254.68  5732.5  254.38
  5740.5  252.69  5762.4  254.44  5893.9  256.28  6081.0  267.70  6238.0  280.26
#Mann=5,-1,0
  3640.6    0.05       0  4417.7    0.12       0  4999.0    0.07       0
  5005.0    0.12       0  5057.6    0.05       0
Bank Sta=4999,5005
Exp/Cntr=0.3,0.1

Type RM Length L Ch R = 1,5445,472,472,472
BEGIN DESCRIPTION:
UNT 011 IN BOCR 11.0
END DESCRIPTION:
XS GIS Cut Line= 3
      3679549.61     10598960.19      3679599.61     10598560.19
      3680099.60     10597760.20
#Sta/Elev= 30
  4591.6  262.16  4715.1  256.53  4790.6  251.20  4843.6  250.20  4956.9  244.49
  4974.6  241.54  4984.6  235.94  4989.2  235.48  4991.9  234.98  4995.2  235.48
  5017.7  236.57  5023.6  239.44  5030.1  244.53  5075.9  244.61  5166.7  245.18
  5188.9  245.16  5233.5  245.61  5301.8  244.34  5372.1  245.43  5385.6  246.49
  5395.1  246.07  5524.6  249.93  5684.0  255.39  5735.9  259.10  5749.4  259.17
  5757.1  260.57  5793.7  263.53  5879.1  269.56  5924.5  269.78  5938.1  270.68
#Mann=9,-1,0
  4591.6    0.05       0  4843.6    0.12       0  4989.2    0.07       0
  4995.2    0.12       0  5075.9    0.16       0  5166.7    0.12       0
  5188.9    0.16       0  5301.8    0.12       0  5524.6    0.05       0
Bank Sta=4989.2,4995.2
Exp/Cntr=0.3,0.1

Type RM Length L Ch R = 1,4973,380,380,380
BEGIN DESCRIPTION:
UNT 011 IN BOCR 10.0
END DESCRIPTION:
XS GIS Cut Line= 3
      3679599.64     10599010.17      3679899.61     10598810.19
      3680499.64     10598610.18
#Sta/Elev= 30
  4594.0  261.58  4607.5  261.63  4637.5  257.81  4666.1  255.58  4673.6  255.91
  4709.6  251.53  4751.7  248.86  4781.7  245.36  4800.0  245.16  4807.3  244.62
  4889.9  242.49  4957.1  242.96  4965.1  242.28  4975.6  236.30  4983.1  234.83
  4985.9  234.33  4989.1  234.83  5017.8  234.99  5028.3  241.30  5059.9  243.17
  5197.0  240.79  5315.1  241.67  5449.9  242.11  5481.6  246.38  5492.1  246.84
  5502.6  249.68  5513.2  250.89  5555.3  259.83  5565.9  260.42  5587.0  263.55
#Mann=6,-1,0
  4594.0    0.05       0  4800.0    0.12       0  4807.3    0.16       0
  4983.1    0.07       0  4989.1    0.16       0  5315.1    0.12       0
Bank Sta=4983.1,4989.1
Exp/Cntr=0.3,0.1

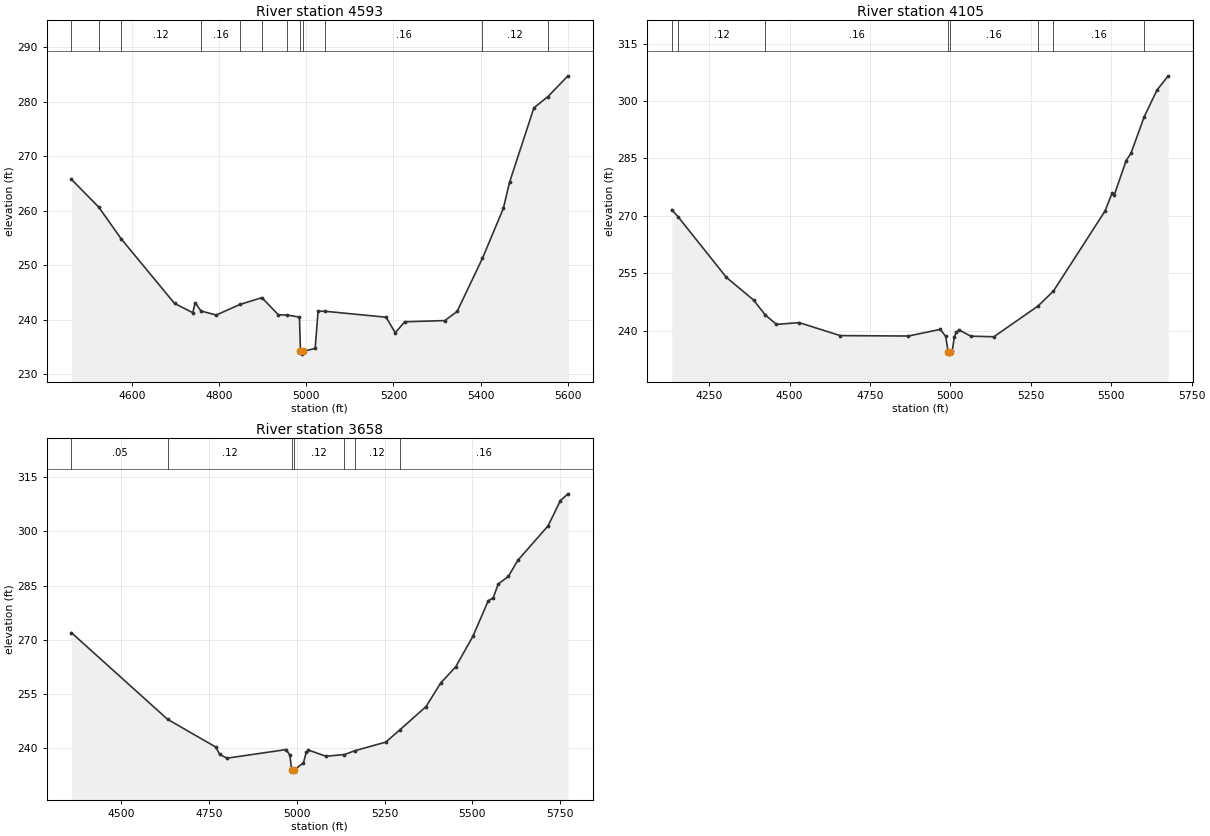
Type RM Length L Ch R = 1,4593,488,488,488
BEGIN DESCRIPTION:
UNT 011 IN BOCR 9.0
END DESCRIPTION:
XS GIS Cut Line= 3
      3679699.63     10599260.18      3680199.61     10599060.19
      3680649.63     10598660.17
#Sta/Elev= 30
  4460.3  265.75  4522.9  260.66  4574.6  254.82  4697.2  242.96  4739.0  241.27
  4744.3  243.09  4757.9  241.58  4792.8  240.84  4847.6  242.79  4897.7  244.03
  4935.5  240.89  4955.8  240.83  4984.0  240.47  4986.4  234.16  4989.1  233.66
  4992.4  234.16  5020.1  234.71  5026.8  241.54  5041.6  241.54  5183.2  240.44
  5204.1  237.57  5225.8  239.60  5317.8  239.82  5346.2  241.49  5404.4  251.25
  5452.4  260.41  5466.7  265.23  5522.7  278.90  5554.7  280.94  5600.9  284.77
#Mann=12,-1,0
  4460.3    0.05       0  4522.9    0.16       0  4574.6    0.12       0
  4757.9    0.16       0  4847.6    0.12       0  4897.7    0.16       0
  4955.8    0.12       0  4986.4    0.07       0  4992.4    0.12       0
  5041.6    0.16       0  5404.4    0.12       0  5554.7    0.16       0
Bank Sta=4986.4,4992.4
Exp/Cntr=0.3,0.1

Type RM Length L Ch R = 1,4105,447,447,447
BEGIN DESCRIPTION:
UNT 011 IN BOCR 8.0
END DESCRIPTION:
XS GIS Cut Line= 3
      3679899.60     10599910.20      3680499.61     10599310.19
      3681099.63     10598960.17
#Sta/Elev= 30
  4134.1  271.61  4154.2  269.69  4303.8  253.92  4388.7  247.97  4424.6  244.11
  4459.4  241.64  4530.1  242.10  4657.4  238.71  4869.5  238.60  4968.5  240.33
  4985.5  238.51  4993.3  234.37  4996.0  233.87  4999.3  234.37  5005.8  234.67
  5012.0  238.24  5017.8  239.60  5027.7  240.15  5063.7  238.56  5135.2  238.41
  5272.2  246.42  5320.3  250.34  5480.5  271.22  5503.2  276.04  5509.0  275.33
  5546.2  284.41  5561.5  286.36  5602.1  295.79  5642.1  302.84  5677.3  306.57
#Mann=8,-1,0
  4134.1    0.05       0  4154.2    0.12       0  4424.6    0.16       0
  4993.3    0.07       0  4999.3    0.16       0  5272.2    0.12       0
  5320.3    0.16       0  5602.1    0.05       0
Bank Sta=4993.3,4999.3
Exp/Cntr=0.3,0.1

Type RM Length L Ch R = 1,3658,476,476,476
BEGIN DESCRIPTION:
UNT 011 IN BOCR 7.0
END DESCRIPTION:
XS GIS Cut Line= 3
      3680549.62     10600260.14      3680749.61     10599660.19
      3681249.59     10599060.21
#Sta/Elev= 30
  4358.7  271.95  4632.1  248.03  4769.7  240.33  4780.3  238.33  4801.4  237.27
  4970.0  239.65  4980.6  238.05  4985.5  233.91  4988.2  233.41  4991.5  233.91
  5019.1  235.99  5026.9  238.89  5033.4  239.51  5082.9  237.80  5135.9  238.27
  5164.9  239.31  5253.4  241.72  5293.0  245.06  5368.0  251.53  5409.6  258.03
  5452.6  262.55  5502.0  271.07  5545.0  280.77  5559.3  281.61  5573.6  285.43
  5602.3  287.52  5629.6  292.01  5715.5  301.52  5750.7  308.50  5772.1  310.37
#Mann=7,-1,0
  4358.7    0.05       0  4632.1    0.12       0  4985.5    0.07       0
  4991.5    0.12       0  5135.9    0.16       0  5164.9    0.12       0
  5293.0    0.16       0
Bank Sta=4985.5,4991.5
Exp/Cntr=0.3,0.1