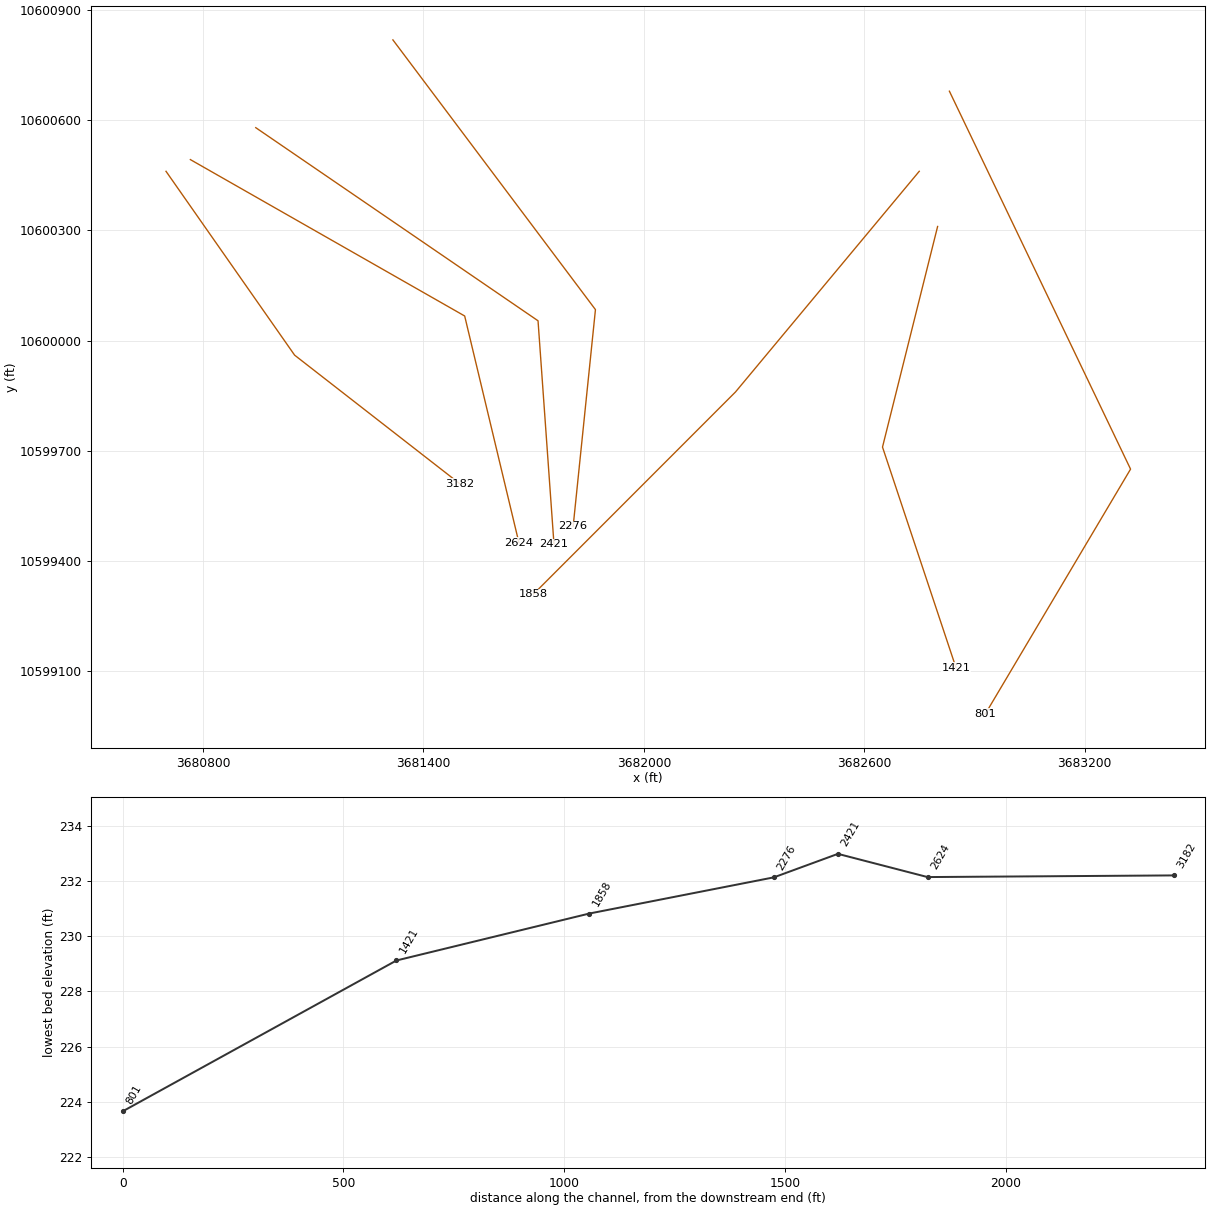
HEC-RAS study UNT 011 IN BOCR.prj: UNT 011 IN BOCR Base Level Engineering

--- UNT 011 IN BOCR.g01 (geometry) --- (continued)

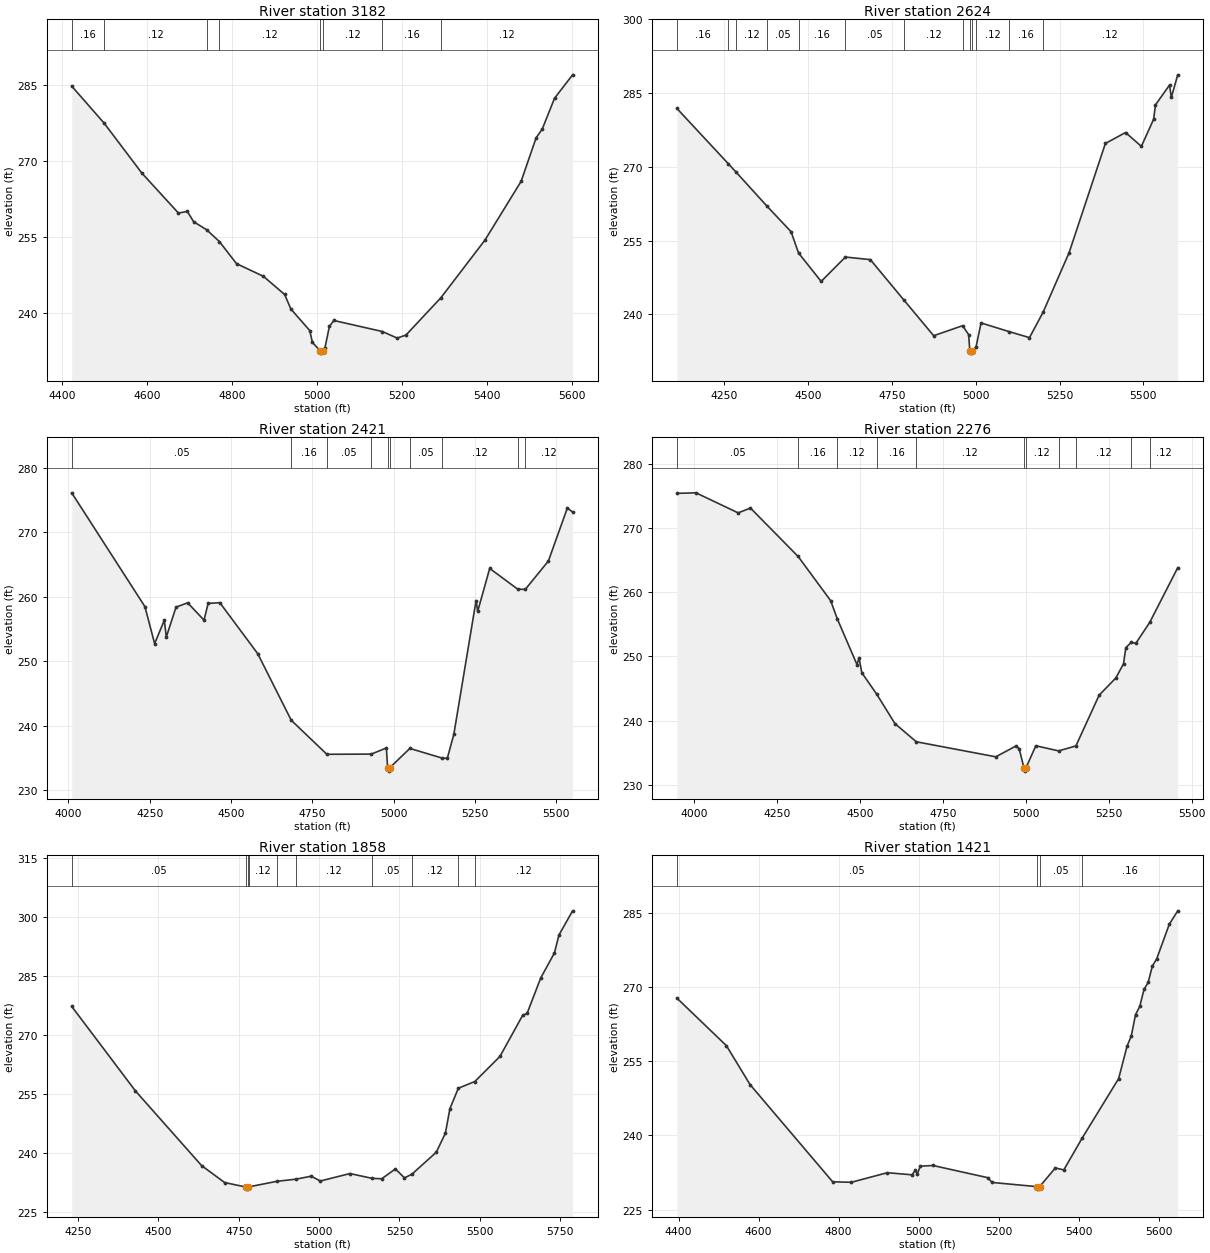
Type RM Length L Ch R = 1,3182,558,558,558
BEGIN DESCRIPTION:
UNT 011 IN BOCR 6.0
END DESCRIPTION:
XS GIS Cut Line= 3
      3680699.62     10600460.18      3681049.61     10599960.19
      3681499.61     10599610.19
#Sta/Elev= 30
  4422.0  284.70  4498.5  277.41  4587.2  267.61  4673.5  259.74  4694.5  260.06
  4709.3  258.04  4740.0  256.45  4770.0  254.14  4810.4  249.79  4873.6  247.31
  4923.8  243.73  4938.6  240.86  4983.0  236.64  4989.2  234.31  5007.1  232.70
  5009.8  232.20  5013.1  232.70  5018.8  233.25  5029.3  237.45  5039.6  238.62
  5154.1  236.45  5188.9  235.16  5209.7  235.75  5292.3  243.12  5396.1  254.45
  5481.1  265.98  5516.4  274.52  5530.9  276.26  5559.9  282.32  5602.4  286.92
#Mann=8,-1,0
  4422.0    0.16       0  4498.5    0.12       0  4740.0    0.16       0
  4770.0    0.12       0  5007.1    0.07       0  5013.1    0.12       0
  5154.1    0.16       0  5292.3    0.12       0
Bank Sta=5007.1,5013.1
Exp/Cntr=0.3,0.1

Type RM Length L Ch R = 1,2624,203,203,203
BEGIN DESCRIPTION:
UNT 011 IN BOCR 5.0
END DESCRIPTION:
XS GIS Cut Line= 3
      3680765.94     10600492.03      3681512.45     10600066.69
      3681660.02     10599450.39
#Sta/Elev= 30
  4109.4  281.90  4262.5  270.67  4286.5  268.90  4378.9  261.96  4449.8  256.83
  4472.0  252.51  4539.5  246.72  4611.8  251.68  4686.1  251.15  4787.0  242.86
  4874.8  235.68  4961.0  237.72  4979.1  235.90  4982.5  232.64  4985.3  232.14
  4988.5  232.64  5000.8  233.30  5016.0  238.28  5100.8  236.49  5160.4  235.29
  5200.7  240.42  5278.5  252.57  5386.6  274.77  5446.7  277.00  5493.9  274.19
  5530.5  279.71  5535.9  282.62  5577.9  286.66  5583.1  284.12  5602.3  288.73
#Mann=13,-1,0
  4109.4    0.16       0  4262.5    0.05       0  4286.5    0.12       0
  4378.9    0.05       0  4472.0    0.16       0  4611.8    0.05       0
  4787.0    0.12       0  4961.0    0.05       0  4982.5    0.04       0
  4988.5    0.05       0  5000.8    0.12       0  5100.8    0.16       0
  5200.7    0.12       0
Bank Sta=4982.5,4988.5
Exp/Cntr=0.3,0.1

Type RM Length L Ch R = 1,2421,145,145,145
BEGIN DESCRIPTION:
UNT 011 IN BOCR 4.0
END DESCRIPTION:
XS GIS Cut Line= 3
      3680943.88     10600578.84      3681712.11     10600053.66
      3681755.51     10599445.99
#Sta/Elev= 30
  4010.4  276.13  4235.5  258.48  4265.3  252.75  4295.1  256.37  4301.2  253.77
  4331.0  258.40  4366.9  259.08  4417.1  256.39  4429.8  258.98  4465.7  259.10
  4582.3  251.19  4685.2  240.87  4794.8  235.59  4931.3  235.62  4977.8  236.57
  4981.6  233.48  4984.3  232.98  4987.6  233.48  5049.9  236.50  5148.0  235.02
  5165.0  234.96  5185.1  238.68  5253.5  259.43  5258.5  257.76  5295.4  264.41
  5381.6  261.19  5404.8  261.16  5475.8  265.56  5534.2  273.79  5550.2  273.15
#Mann=10,-1,0
  4010.4    0.05       0  4685.2    0.16       0  4794.8    0.05       0
  4931.3    0.12       0  4981.6    0.07       0  4987.6    0.12       0
  5049.9    0.05       0  5148.0    0.12       0  5381.6    0.16       0
  5404.8    0.12       0
Bank Sta=4981.6,4987.6
Exp/Cntr=0.3,0.1

Type RM Length L Ch R = 1,2276,418,418,418
BEGIN DESCRIPTION:
Mapping XS bbe3553e
END DESCRIPTION:
XS GIS Cut Line= 3
      3681317.13     10600817.57      3681868.36     10600084.05
      3681807.67     10599494.52
#Sta/Elev= 30
  3947.9  275.37  4005.6  275.45  4132.7  272.33  4169.8  273.08  4313.6  265.54
  4411.7  258.66  4431.4  255.86  4490.9  248.72  4497.1  249.76  4505.5  247.45
  4550.6  244.10  4605.4  239.53  4669.8  236.70  4909.5  234.36  4969.9  236.03
  4979.9  235.65  4994.4  232.63  4997.1  232.13  5000.4  232.63  5030.2  236.08
  5099.0  235.28  5151.0  236.05  5221.2  243.96  5271.5  246.63  5294.6  248.84
  5301.6  251.36  5317.7  252.16  5331.8  252.03  5373.5  255.27  5458.1  263.80
#Mann=11,-1,0
  3947.9    0.05       0  4313.6    0.16       0  4431.4    0.12       0
  4550.6    0.16       0  4669.8    0.12       0  4994.4    0.07       0
  5000.4    0.12       0  5099.0    0.05       0  5151.0    0.12       0
  5317.7    0.16       0  5373.5    0.12       0
Bank Sta=4994.4,5000.4
Exp/Cntr=0.3,0.1

Type RM Length L Ch R = 1,1858,437,437,437
BEGIN DESCRIPTION:
UNT 011 IN BOCR 3.0
END DESCRIPTION:
XS GIS Cut Line= 3
      3682749.61     10600460.19      3682249.61     10599860.19
      3681699.64     10599310.22
#Sta/Elev= 30
  4230.0  277.29  4428.5  255.78  4634.2  236.81  4705.8  232.50  4773.7  231.32
  4776.5  230.82  4779.7  231.32  4780.2  231.38  4869.3  232.82  4927.9  233.35
  4975.2  234.11  5003.9  232.89  5095.9  234.78  5165.5  233.55  5194.9  233.46
  5237.3  235.96  5265.6  233.67  5288.9  234.63  5364.6  240.21  5392.9  245.04
  5407.0  251.27  5433.2  256.48  5484.5  258.19  5562.6  264.56  5633.3  275.00
  5647.4  275.55  5689.9  284.57  5732.3  290.89  5746.4  295.45  5788.8  301.60
#Mann=10,-1,0
  4230.0    0.05       0  4773.7    0.07       0  4779.7    0.05       0
  4780.2    0.12       0  4869.3    0.05       0  4927.9    0.12       0
  5165.5    0.05       0  5288.9    0.12       0  5433.2    0.16       0
  5484.5    0.12       0
Bank Sta=4773.7,4779.7
Exp/Cntr=0.3,0.1

Type RM Length L Ch R = 1,1421,620,620,620
BEGIN DESCRIPTION:
UNT 011 IN BOCR 2.0
END DESCRIPTION:
XS GIS Cut Line= 3
      3682799.60     10600310.16      3682649.61     10599710.19
      3682849.61     10599110.18
#Sta/Elev= 30
  4395.9  267.73  4519.6  258.12  4578.8  250.24  4785.0  230.60  4831.4  230.50
  4921.6  232.44  4983.4  232.01  4991.1  232.90  4996.3  232.20  5004.0  233.76
  5035.4  233.90  5172.5  231.43  5183.0  230.47  5295.9  229.62  5298.7  229.12
  5301.9  229.62  5341.1  233.40  5362.2  233.00  5407.9  239.41  5499.2  251.46
  5520.3  258.04  5530.8  260.08  5541.4  264.39  5551.9  266.04  5562.5  269.47
  5573.0  270.92  5583.5  274.24  5594.1  275.63  5625.7  282.66  5646.8  285.37
#Mann=4,-1,0
  4395.9    0.05       0  5295.9    0.03       0  5301.9    0.05       0
  5407.9    0.16       0
Bank Sta=5295.9,5301.9
Exp/Cntr=0.3,0.1

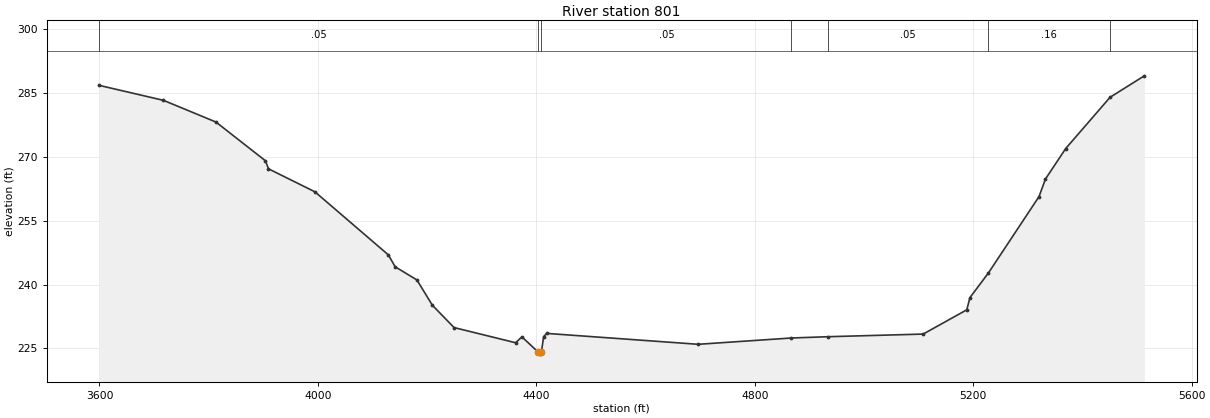
Type RM Length L Ch R = 1,801,0,0,0
BEGIN DESCRIPTION:
UNT 011 IN BOCR 1.0
END DESCRIPTION:
XS GIS Cut Line= 3
      3682831.69     10600678.00      3683324.74     10599650.23
      3682929.39     10598984.37
#Sta/Elev= 30
  3599.0  286.82  3717.2  283.29  3813.3  278.19  3903.9  269.09  3909.5  267.20
  3994.5  261.80  4128.9  246.99  4141.5  244.18  4181.3  241.09  4209.5  235.16
  4249.3  229.90  4361.9  226.34  4373.6  227.71  4403.2  224.16  4406.0  223.66
  4409.2  224.16  4413.4  227.77  4418.9  228.53  4696.3  225.97  4867.0  227.45
  4933.5  227.75  5108.3  228.37  5188.2  234.07  5194.0  236.95  5227.7  242.71
  5320.5  260.68  5332.3  264.81  5369.4  271.97  5450.6  284.01  5513.3  289.05
#Mann=7,-1,0
  3599.0    0.05       0  4403.2    0.03       0  4409.2    0.05       0
  4867.0    0.16       0  4933.5    0.05       0  5227.7    0.16       0
  5450.6    0.05       0
Bank Sta=4403.2,4409.2
Exp/Cntr=0.3,0.1

Chan Stop Cuts=-1