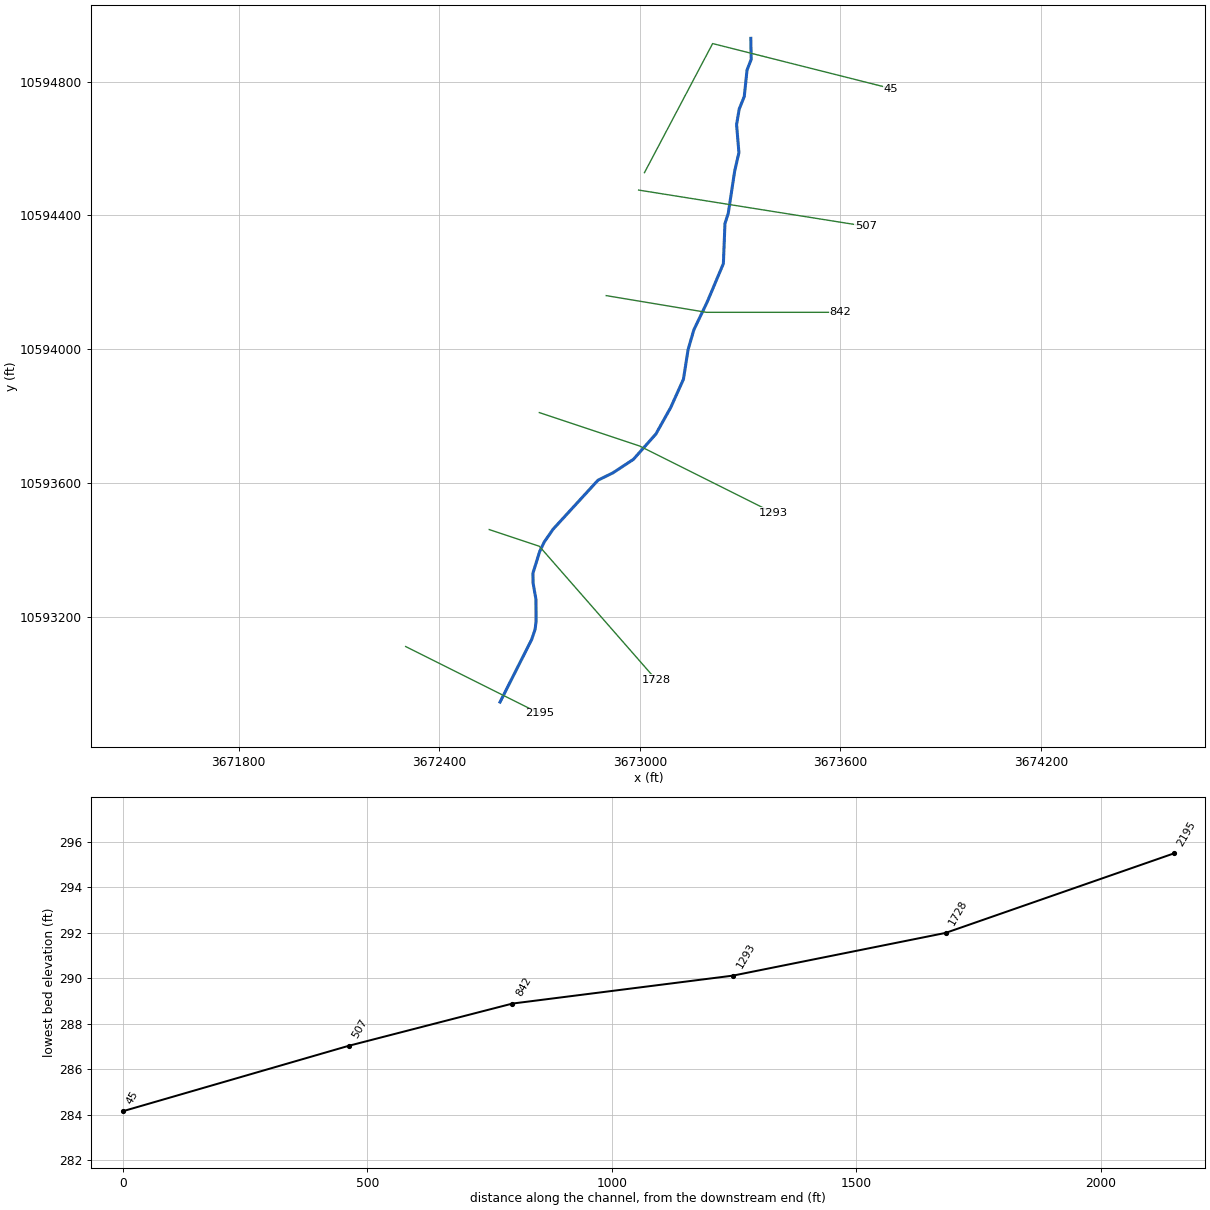
--- UNT 012 IN BOCR.prj (project) ---

Proj Title=UNT 012 IN BOCR Base Level Engineering
Current Plan=p01
Default Exp/Contr=0.3,0.1
English Units
Geom File=g01
Flow File=f01
Plan File=p01
BEGIN DESCRIPTION:
UNT 012 IN BOCR
END DESCRIPTION:

--- UNT 012 IN BOCR.p01 (plan) ---

Plan Title=Multiple Run
Short Identifier=Multiple
Geom File=g01
Flow File=f01
Subcritical Flow
K Sum by GR= 0
Std Step Tol= 0.01
Critical Tol= 0.01
Num of Std Step Trials= 20
Max Error Tol= 0.3
Flow Tol Ratio= 0.001
Split Flow NTrial= 30
Split Flow Tol= 0.02
Split Flow Ratio= 0.02
Log Output Level= 0
Friction Slope Method= 1
Unsteady Friction Slope Method= 2
Unsteady Bridges Friction Slope Method= 1
Parabolic Critical Depth
Global Vel Dist=  1 , 1 , 1
Global Log Level= 0
CheckData=True
Encroach Param= -1, 0, 0, 0
BEGIN DESCRIPTION:
Multiple Run
END DESCRIPTION:

--- UNT 012 IN BOCR.f01 (steady flow) ---

Flow Title=Multiple
Number of Profiles=7
Profile Names=10-year,25-year,50-year,1pct_min,100-year,1pct_plu,500-year
River Rch & RM= UNT 012 IN BOCR,Reach-1,2195
     625     853    1042     936    1266    1712    1875
Boundary for River Rch & Prof#=UNT 012 IN BOCR,Reach-1,1
Up Type=0
Dn Type=3
Dn Slope=0.005
Boundary for River Rch & Prof#=UNT 012 IN BOCR,Reach-1,2
Up Type=0
Dn Type=3
Dn Slope=0.005
Boundary for River Rch & Prof#=UNT 012 IN BOCR,Reach-1,3
Up Type=0
Dn Type=3
Dn Slope=0.005
Boundary for River Rch & Prof#=UNT 012 IN BOCR,Reach-1,4
Up Type=0
Dn Type=3
Dn Slope=0.005
Boundary for River Rch & Prof#=UNT 012 IN BOCR,Reach-1,5
Up Type=0
Dn Type=3
Dn Slope=0.005
Boundary for River Rch & Prof#=UNT 012 IN BOCR,Reach-1,6
Up Type=0
Dn Type=3
Dn Slope=0.005
Boundary for River Rch & Prof#=UNT 012 IN BOCR,Reach-1,7
Up Type=0
Dn Type=3
Dn Slope=0.005

--- UNT 012 IN BOCR.g01 (geometry) ---

Geom Title=Existing Conditions

River Reach=UNT 012 IN BOCR,Reach-1
Reach XY= 30
      3672582.00     10592944.00      3672676.50     10593131.00
      3672686.75     10593161.00      3672689.75     10593184.00
      3672689.50     10593251.00      3672680.75     10593301.00
      3672680.50     10593330.00      3672700.75     10593395.00
      3672714.25     10593423.00      3672740.50     10593461.00
      3672875.25     10593608.00      3672920.00     10593630.00
      3672980.75     10593670.00      3673048.25     10593746.00
      3673092.50     10593825.00      3673130.75     10593910.00
      3673144.75     10593999.00      3673162.00     10594058.00
      3673202.25     10594142.00      3673250.25     10594256.00
      3673255.00     10594376.00      3673264.75     10594406.00
      3673284.25     10594534.00      3673296.75     10594588.00
      3673289.75     10594672.00      3673297.50     10594718.00
      3673312.75     10594756.00      3673321.00     10594835.00
      3673333.50     10594867.00      3673332.25     10594930.00

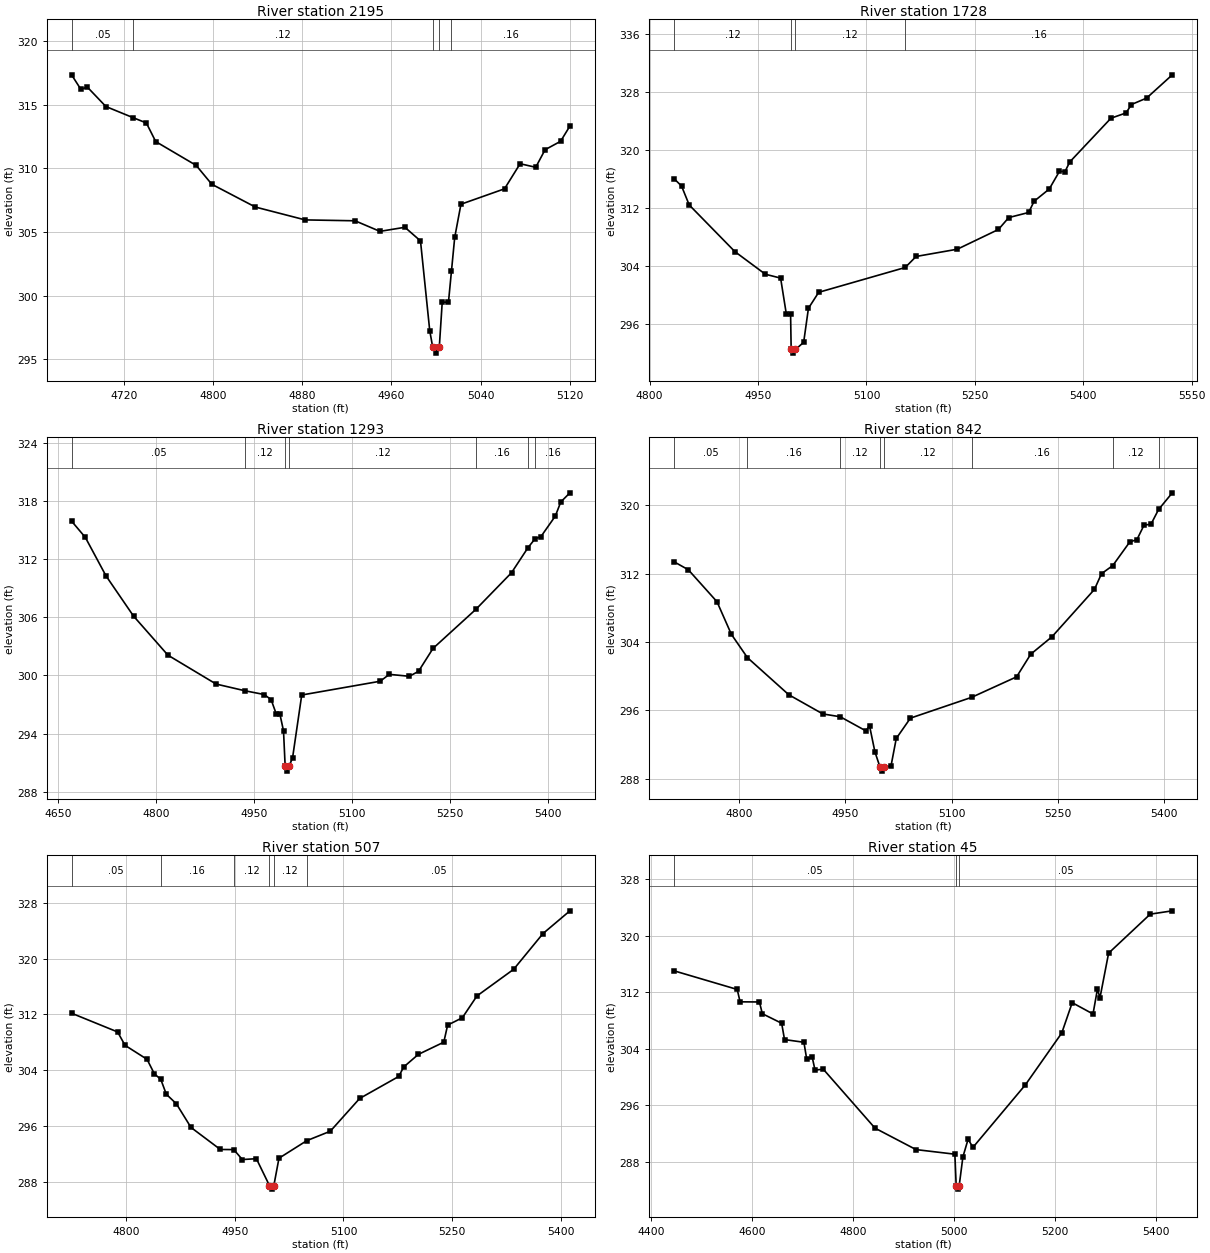
Type RM Length L Ch R = 1,2195,467,467,467
BEGIN DESCRIPTION:
UNT 012 IN BOCR 5.0
END DESCRIPTION:
XS GIS Cut Line= 3
      3672299.60     10593110.19      3672599.61     10592960.19
      3672699.59     10592910.20
#Sta/Elev= 30
  4673.0  317.35  4681.4  316.20  4687.0  316.40  4703.8  314.86  4728.4  313.98
  4740.1  313.57  4748.5  312.11  4784.8  310.24  4798.8  308.76  4837.9  306.97
  4882.6  305.96  4927.4  305.89  4949.7  305.06  4972.1  305.38  4986.1  304.31
  4994.4  297.26  4997.0  296.00  4999.8  295.50  5003.0  296.00  5005.6  299.50
  5011.2  299.50  5013.9  301.95  5016.8  304.58  5022.4  307.19  5061.5  308.40
  5075.5  310.37  5089.5  310.09  5097.9  311.47  5111.8  312.13  5120.2  313.33
#Mann=5,-1,0
  4673.0    0.05       0  4728.4    0.12       0  4997.0    0.07       0
  5003.0    0.12       0  5013.9    0.16       0
Bank Sta=4997,5003
Exp/Cntr=0.3,0.1

Type RM Length L Ch R = 1,1728,435,435,435
BEGIN DESCRIPTION:
UNT 012 IN BOCR 4.0
END DESCRIPTION:
XS GIS Cut Line= 3
      3672549.61     10593460.19      3672699.61     10593410.19
      3673049.60     10593010.20
#Sta/Elev= 30
  4833.6  316.05  4844.1  315.03  4854.7  312.42  4917.9  305.99  4960.1  302.87
  4981.2  302.34  4989.1  297.39  4995.0  297.39  4995.8  292.50  4998.6  292.00
  5001.8  292.50  5013.1  293.49  5019.7  298.18  5033.9  300.38  5153.6  303.80
  5168.7  305.32  5225.7  306.32  5282.6  309.04  5296.9  310.68  5324.4  311.38
  5332.0  312.93  5352.9  314.61  5367.1  317.06  5374.7  317.01  5381.3  318.34
  5438.3  324.37  5459.2  325.10  5466.7  326.26  5487.6  327.14  5523.2  330.35
#Mann=4,-1,0
  4833.6    0.12       0  4995.8    0.07       0  5001.8    0.12       0
  5153.6    0.16       0
Bank Sta=4995.8,5001.8
Exp/Cntr=0.3,0.1

Type RM Length L Ch R = 1,1293,451,451,451
BEGIN DESCRIPTION:
UNT 012 IN BOCR 3.0
END DESCRIPTION:
XS GIS Cut Line= 3
      3672699.57     10593810.20      3672999.61     10593710.19
      3673399.63     10593510.18
#Sta/Elev= 30
  4670.7  315.90  4691.8  314.22  4723.4  310.26  4765.6  306.11  4818.3  302.08
  4892.1  299.10  4936.8  298.40  4965.9  298.02  4976.4  297.49  4984.3  296.01
  4989.8  296.01  4995.4  294.27  4997.9  290.62  5000.7  290.12  5003.9  290.62
  5009.3  291.51  5023.3  297.97  5143.5  299.39  5157.5  300.10  5188.2  299.90
  5202.2  300.41  5224.5  302.78  5290.2  306.81  5344.7  310.58  5370.0  313.17
  5381.0  314.10  5389.5  314.28  5411.8  316.42  5420.2  317.88  5434.2  318.82
#Mann=7,-1,0
  4670.7    0.05       0  4936.8    0.12       0  4997.9    0.07       0
  5003.9    0.12       0  5290.2    0.16       0  5370.0     0.1       0
  5381.0    0.16       0
Bank Sta=4997.9,5003.9
Exp/Cntr=0.3,0.1

Type RM Length L Ch R = 1,842,335,335,335
BEGIN DESCRIPTION:
UNT 012 IN BOCR 2.0
END DESCRIPTION:
XS GIS Cut Line= 3
      3672899.62     10594160.19      3673199.61     10594110.19
      3673599.58     10594110.19
#Sta/Elev= 30
  4707.7  313.39  4728.0  312.45  4768.5  308.71  4788.8  304.90  4811.5  302.17
  4869.9  297.83  4918.1  295.58  4942.7  295.25  4978.9  293.60  4984.0  294.21
  4991.6  291.16  4998.7  289.39  5001.4  288.89  5004.7  289.39  5014.3  289.46
  5021.8  292.71  5041.8  295.09  5128.2  297.52  5191.8  299.92  5211.8  302.57
  5241.8  304.61  5301.8  310.15  5311.8  311.99  5327.7  312.94  5351.8  315.71
  5361.8  315.97  5371.8  317.66  5381.8  317.79  5392.4  319.50  5411.8  321.45
#Mann=8,-1,0
  4707.7    0.05       0  4811.5    0.16       0  4942.7    0.12       0
  4998.7    0.07       0  5004.7    0.12       0  5128.2    0.16       0
  5327.7    0.12       0  5392.4    0.05       0
Bank Sta=4998.7,5004.7
Exp/Cntr=0.3,0.1

Type RM Length L Ch R = 1,507,462,462,462
BEGIN DESCRIPTION:
Mapping XS d98bb640
END DESCRIPTION:
XS GIS Cut Line= 2
      3672996.74     10594475.98      3673676.38     10594367.75
#Sta/Elev= 30
  4724.5  312.18  4788.1  309.50  4798.3  307.59  4828.7  305.59  4838.8  303.52
  4847.7  302.72  4855.3  300.60  4869.2  299.23  4889.4  295.85  4929.9  292.70
  4948.5  292.68  4960.3  291.26  4979.7  291.38  4997.8  287.53  5000.6  287.03
  5003.8  287.53  5010.9  291.45  5049.3  293.96  5081.8  295.31  5122.3  299.99
  5176.3  303.14  5183.1  304.49  5203.3  306.29  5238.5  308.04  5243.8  310.48
  5264.1  311.53  5284.3  314.65  5335.0  318.46  5375.5  323.57  5412.7  326.82
#Mann=6,-1,0
  4724.5    0.05       0  4847.7    0.16       0  4948.5    0.12       0
  4997.8    0.07       0  5003.8    0.12       0  5049.3    0.05       0
Bank Sta=4997.8,5003.8
Exp/Cntr=0.3,0.1

Type RM Length L Ch R = 1,45,0,0,0
BEGIN DESCRIPTION:
UNT 012 IN BOCR 1.0
END DESCRIPTION:
XS GIS Cut Line= 3
      3673014.10     10594528.02      3673218.11     10594914.34
      3673751.94     10594779.80
#Sta/Elev= 30
  4444.5  315.03  4569.9  312.39  4575.5  310.64  4613.9  310.62  4619.6  308.96
  4657.9  307.61  4663.6  305.30  4702.0  304.92  4707.6  302.52  4718.3  302.86
  4724.0  300.99  4740.4  301.11  4842.8  292.78  4924.2  289.74  5001.1  289.09
  5003.7  284.65  5006.4  284.15  5009.7  284.65  5017.0  288.70  5027.3  291.20
  5037.0  290.06  5140.7  298.89  5212.9  306.23  5233.6  310.52  5274.8  308.92
  5283.5  312.40  5288.7  311.24  5305.7  317.52  5388.2  323.04  5431.9  323.51
#Mann=3,-1,0
  4444.5    0.05       0  5003.7    0.03       0  5009.7    0.05       0
Bank Sta=5003.7,5009.7
Exp/Cntr=0.3,0.1

Chan Stop Cuts=-1