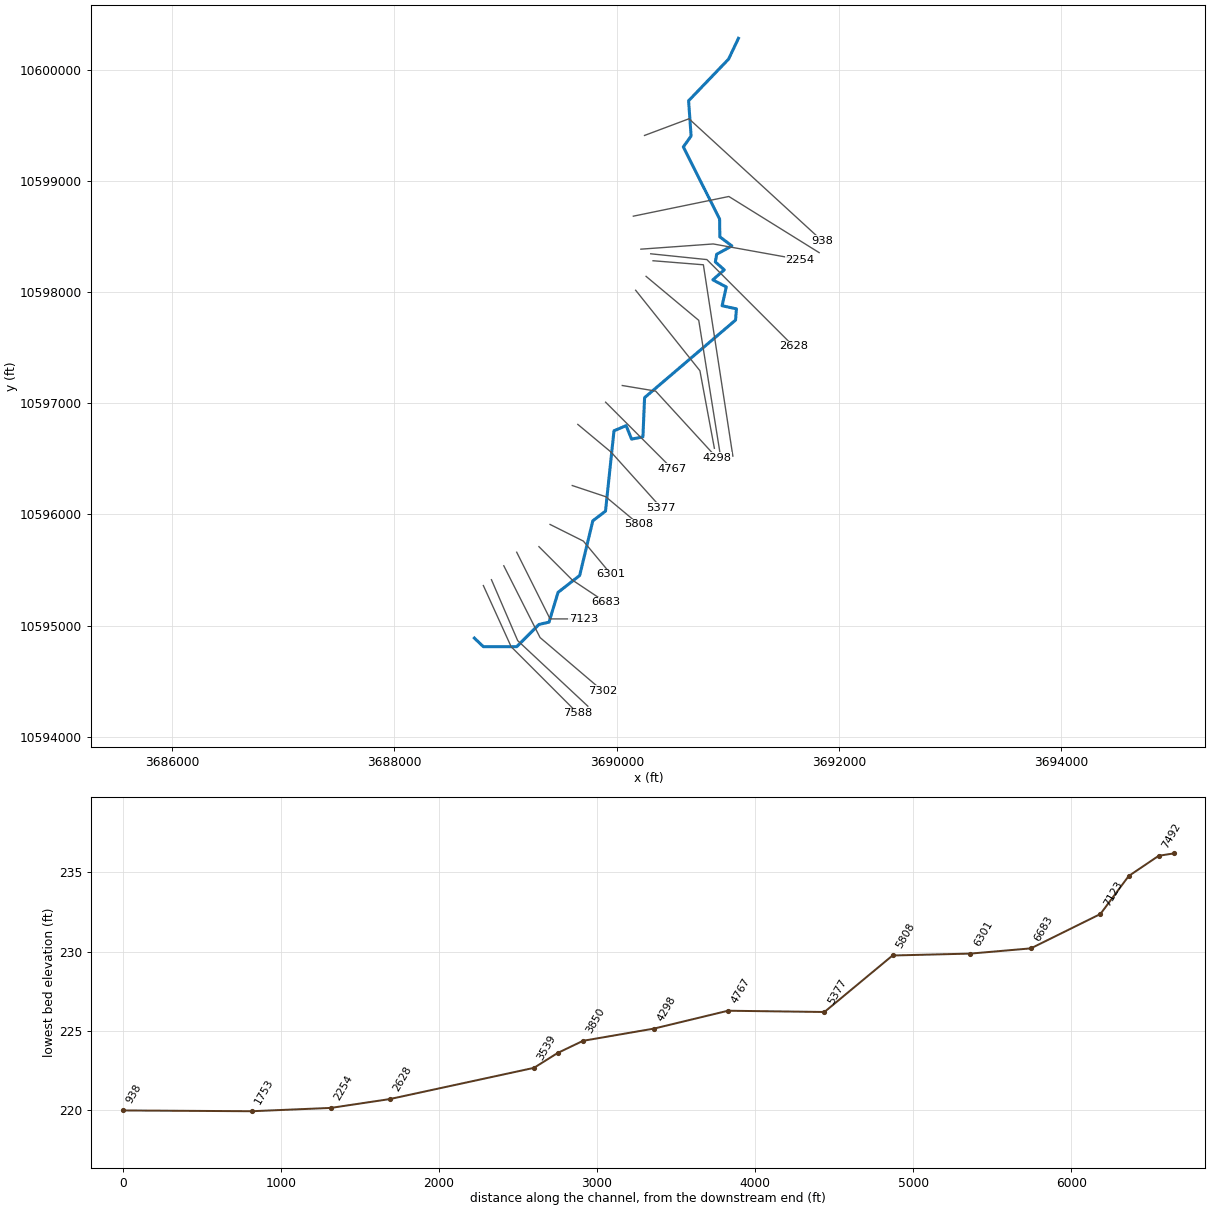
--- UNT 015 IN BOCR.prj (project) ---

Proj Title=UNT 015 IN BOCR Base Level Engineering
Current Plan=p01
Default Exp/Contr=0.3,0.1
English Units
Geom File=g01
Flow File=f01
Plan File=p01
BEGIN DESCRIPTION:
UNT 015 IN BOCR
END DESCRIPTION:

--- UNT 015 IN BOCR.p01 (plan) ---

Plan Title=Multiple Run
Short Identifier=Multiple
Geom File=g01
Flow File=f01
Subcritical Flow
K Sum by GR= 0
Std Step Tol= 0.01
Critical Tol= 0.01
Num of Std Step Trials= 20
Max Error Tol= 0.3
Flow Tol Ratio= 0.001
Split Flow NTrial= 30
Split Flow Tol= 0.02
Split Flow Ratio= 0.02
Log Output Level= 0
Friction Slope Method= 1
Unsteady Friction Slope Method= 2
Unsteady Bridges Friction Slope Method= 1
Parabolic Critical Depth
Global Vel Dist=  1 , 1 , 1
Global Log Level= 0
CheckData=True
Encroach Param= -1, 0, 0, 0
BEGIN DESCRIPTION:
Multiple Run
END DESCRIPTION:

--- UNT 015 IN BOCR.f01 (steady flow) ---

Flow Title=Multiple
Number of Profiles=7
Profile Names=10-year,25-year,50-year,1pct_min,100-year,1pct_plu,500-year
River Rch & RM= UNT 015 IN BOCR,Reach-1,7588
     526     712     866     774    1047    1416    1537
River Rch & RM= UNT 015 IN BOCR,Reach-1,3850
     559     756     918     819    1107    1497    1619
Boundary for River Rch & Prof#=UNT 015 IN BOCR,Reach-1,1
Up Type=0
Dn Type=3
Dn Slope=0.005
Boundary for River Rch & Prof#=UNT 015 IN BOCR,Reach-1,2
Up Type=0
Dn Type=3
Dn Slope=0.005
Boundary for River Rch & Prof#=UNT 015 IN BOCR,Reach-1,3
Up Type=0
Dn Type=3
Dn Slope=0.005
Boundary for River Rch & Prof#=UNT 015 IN BOCR,Reach-1,4
Up Type=0
Dn Type=3
Dn Slope=0.005
Boundary for River Rch & Prof#=UNT 015 IN BOCR,Reach-1,5
Up Type=0
Dn Type=3
Dn Slope=0.005
Boundary for River Rch & Prof#=UNT 015 IN BOCR,Reach-1,6
Up Type=0
Dn Type=3
Dn Slope=0.005
Boundary for River Rch & Prof#=UNT 015 IN BOCR,Reach-1,7
Up Type=0
Dn Type=3
Dn Slope=0.005

--- UNT 015 IN BOCR.g01 (geometry) ---

Geom Title=Existing Conditions

River Reach=UNT 015 IN BOCR,Reach-1
Reach XY= 30
      3688718.62     10594887.78      3688799.61     10594810.19
      3689099.61     10594810.19      3689299.61     10595010.19
      3689390.25     10595031.00      3689471.75     10595299.00
      3689666.25     10595451.00      3689784.50     10595943.00
      3689898.50     10596030.00      3689975.00     10596753.00
      3690084.25     10596799.00      3690133.25     10596678.00
      3690235.25     10596698.00      3690250.25     10597051.00
      3691068.75     10597749.00      3691076.75     10597850.00
      3690947.75     10597878.00      3690985.25     10598047.00
      3690864.25     10598111.00      3690967.00     10598201.00
      3690886.77     10598272.09      3690898.75     10598341.00
      3691035.75     10598416.00      3690927.25     10598498.00
      3690925.25     10598658.00      3690598.75     10599307.00
      3690668.75     10599405.00      3690646.25     10599722.00
      3691006.00     10600097.00      3691094.75     10600284.00

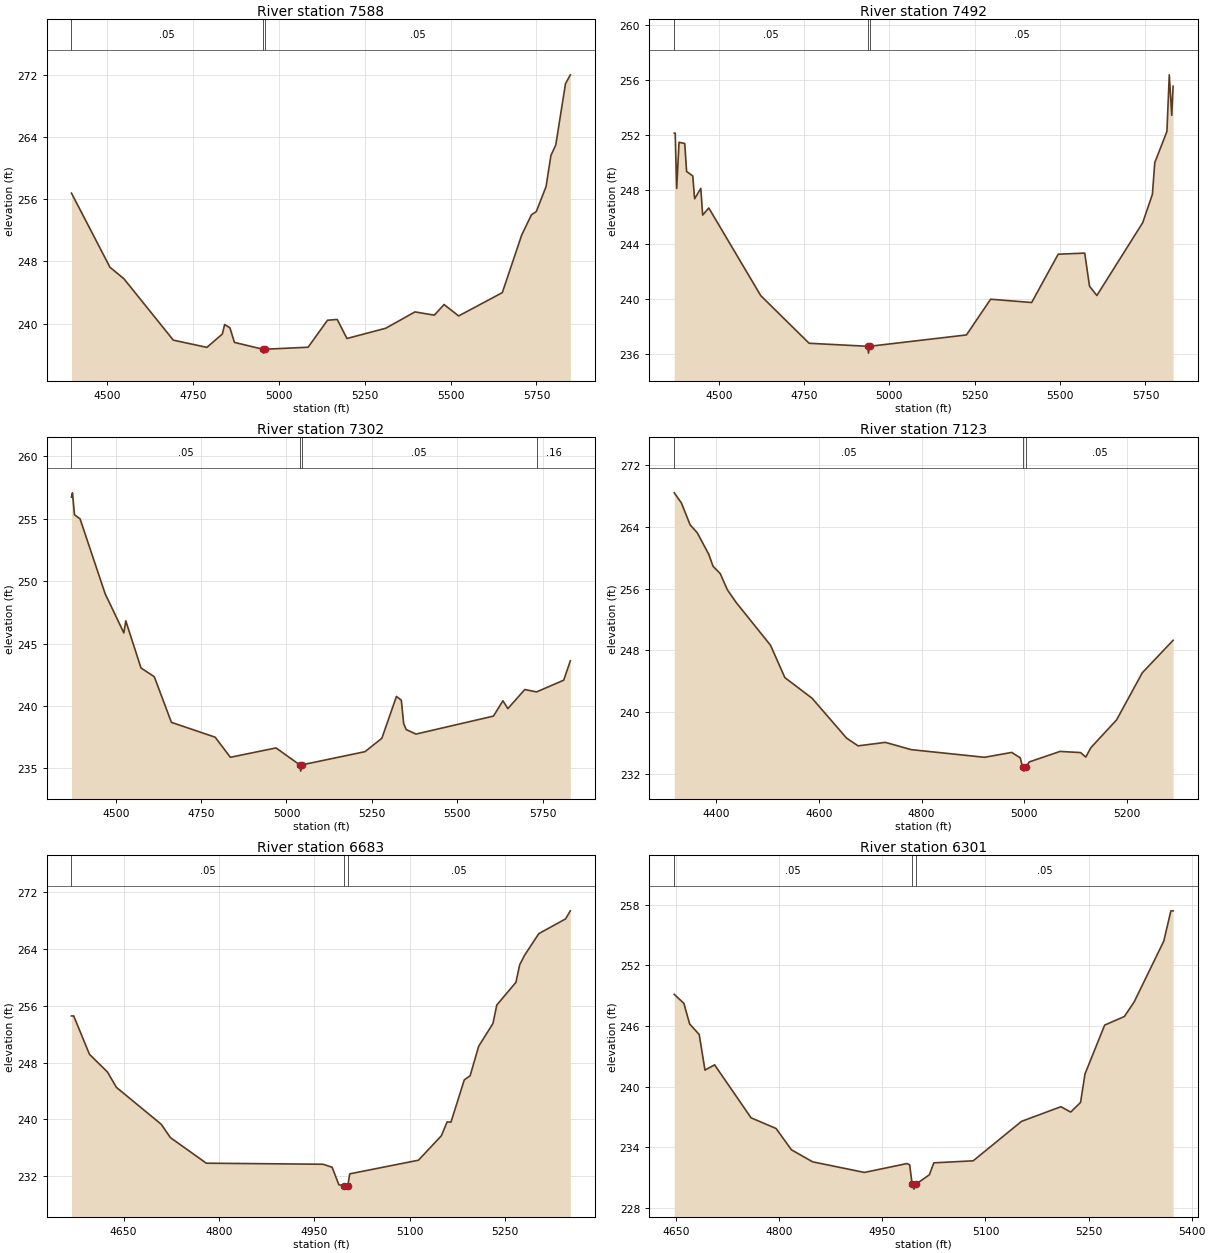
Type RM Length L Ch R = 1,7588,96,96,96
BEGIN DESCRIPTION:
UNT 015 IN BOCR 13.0
END DESCRIPTION:
XS GIS Cut Line= 3
      3688799.59     10595360.23      3689049.61     10594810.19
      3689649.59     10594210.21
#Sta/Elev= 30
  4395.8  256.77  4507.9  247.24  4548.5  245.76  4692.4  237.87  4790.2  236.94
  4835.2  238.66  4841.8  239.88  4857.2  239.45  4870.4  237.58  4953.1  236.70
  4955.8  236.20  4959.1  236.70  5084.9  236.96  5141.4  240.43  5169.7  240.53
  5198.0  238.08  5311.1  239.40  5396.0  241.50  5452.5  241.08  5480.8  242.45
  5523.3  240.98  5650.5  243.98  5707.1  251.41  5735.4  253.99  5749.5  254.40
  5777.8  257.61  5792.0  261.61  5806.1  262.96  5834.4  270.83  5848.5  271.98
#Mann=3,-1,0
  4395.8    0.05       0  4953.1    0.03       0  4959.1    0.05       0
Bank Sta=4953.1,4959.1
Exp/Cntr=0.3,0.1

Type RM Length L Ch R = 1,7492,190,190,190
BEGIN DESCRIPTION:
Mapping XS 62d51173
END DESCRIPTION:
XS GIS Cut Line= 3
      3688872.36     10595413.05      3689108.46     10594864.47
      3689739.84     10594274.72
#Sta/Elev= 30
  4369.8  252.13  4372.6  252.13  4376.9  248.09  4383.8  251.46  4400.5  251.37
  4405.9  249.33  4424.0  249.00  4429.4  247.33  4447.5  248.09  4453.0  246.14
  4470.9  246.66  4623.2  240.25  4764.8  236.77  4936.0  236.55  4938.8  236.05
  4942.0  236.55  5225.7  237.38  5296.5  239.99  5416.7  239.75  5494.4  243.28
  5572.1  243.36  5586.2  240.94  5607.7  240.26  5742.1  245.59  5770.4  247.66
  5777.3  249.97  5812.9  252.25  5819.8  256.39  5827.1  253.43  5831.0  255.56
#Mann=3,-1,0
  4369.8    0.05       0  4936.0    0.03       0  4942.0    0.05       0
Bank Sta=4936,4942
Exp/Cntr=0.3,0.1

Type RM Length L Ch R = 1,7302,179,179,179
BEGIN DESCRIPTION:
Mapping XS 9e380144
END DESCRIPTION:
XS GIS Cut Line= 3
      3688983.44     10595538.13      3689309.85     10594892.25
      3689871.14     10594414.12
#Sta/Elev= 30
  4370.4  256.73  4373.3  257.08  4379.3  255.32  4395.6  254.99  4468.9  249.00
  4523.8  245.85  4529.4  246.82  4574.0  243.04  4612.9  242.34  4663.1  238.68
  4791.2  237.49  4835.8  235.88  4969.6  236.63  5039.0  235.27  5041.8  234.77
  5045.0  235.27  5230.0  236.33  5279.4  237.40  5322.2  240.76  5336.5  240.45
  5343.3  238.57  5350.8  238.10  5379.4  237.74  5606.1  239.18  5634.1  240.41
  5648.4  239.78  5698.0  241.31  5732.6  241.12  5812.0  242.06  5831.4  243.61
#Mann=4,-1,0
  4370.4    0.05       0  5039.0    0.03       0  5045.0    0.05       0
  5732.6    0.16       0
Bank Sta=5039,5045
Exp/Cntr=0.3,0.1

Type RM Length L Ch R = 1,7123,440,440,440
BEGIN DESCRIPTION:
UNT 015 IN BOCR 12.0
END DESCRIPTION:
XS GIS Cut Line= 3
      3689099.59     10595660.22      3689399.61     10595060.19
      3689699.65     10595060.19
#Sta/Elev= 30
  4318.8  268.38  4332.8  267.06  4349.6  264.25  4363.6  263.21  4385.9  260.43
  4394.3  258.88  4408.3  257.93  4422.3  255.82  4439.0  254.22  4506.1  248.66
  4534.1  244.47  4587.2  241.79  4654.2  236.64  4676.6  235.64  4729.7  236.09
  4780.0  235.15  4922.6  234.16  4975.7  234.79  4992.2  234.09  4996.7  232.87
  4999.4  232.37  5002.7  232.87  5009.7  233.56  5069.7  234.92  5109.7  234.77
  5119.7  234.19  5129.7  235.41  5179.7  239.00  5229.7  245.09  5289.7  249.30
#Mann=3,-1,0
  4318.8    0.05       0  4996.7    0.03       0  5002.7    0.05       0
Bank Sta=4996.7,5002.7
Exp/Cntr=0.3,0.1

Type RM Length L Ch R = 1,6683,382,382,382
BEGIN DESCRIPTION:
UNT 015 IN BOCR 11.0
END DESCRIPTION:
XS GIS Cut Line= 3
      3689299.62     10595710.18      3689599.61     10595410.19
      3689899.61     10595210.19
#Sta/Elev= 30
  4568.0  254.57  4571.5  254.57  4596.3  249.17  4624.6  246.68  4638.7  244.52
  4709.4  239.31  4723.5  237.46  4780.1  233.85  4964.0  233.70  4978.1  233.27
  4988.7  230.81  4996.8  230.70  4999.5  230.20  5002.8  230.70  5005.8  232.35
  5113.9  234.27  5150.0  237.72  5159.0  239.67  5165.0  239.62  5186.0  245.58
  5195.1  246.14  5208.6  250.30  5231.1  253.51  5237.1  256.10  5267.2  259.30
  5273.2  261.78  5280.7  263.09  5303.2  266.15  5345.3  268.22  5352.8  269.36
#Mann=3,-1,0
  4568.0    0.05       0  4996.8    0.03       0  5002.8    0.05       0
Bank Sta=4996.8,5002.8
Exp/Cntr=0.3,0.1

Type RM Length L Ch R = 1,6301,493,493,493
BEGIN DESCRIPTION:
UNT 015 IN BOCR 10.0
END DESCRIPTION:
XS GIS Cut Line= 3
      3689399.60     10595910.19      3689699.61     10595760.19
      3689949.59     10595460.21
#Sta/Elev= 30
  4647.1  249.13  4661.1  248.24  4669.5  246.20  4683.4  245.16  4691.8  241.64
  4705.8  242.16  4758.9  236.92  4795.2  235.87  4817.6  233.76  4848.4  232.57
  4923.8  231.52  4985.8  232.40  4989.7  232.27  4993.2  230.37  4995.9  229.87
  4999.2  230.37  5018.3  231.29  5024.8  232.47  5082.1  232.67  5152.4  236.57
  5209.7  238.02  5224.0  237.49  5238.3  238.44  5244.8  241.26  5273.4  246.09
  5302.1  246.94  5316.4  248.39  5359.4  254.39  5369.8  257.39  5373.0  257.39
#Mann=3,-1,0
  4647.1    0.05       0  4993.2    0.03       0  4999.2    0.05       0
Bank Sta=4993.2,4999.2
Exp/Cntr=0.3,0.1

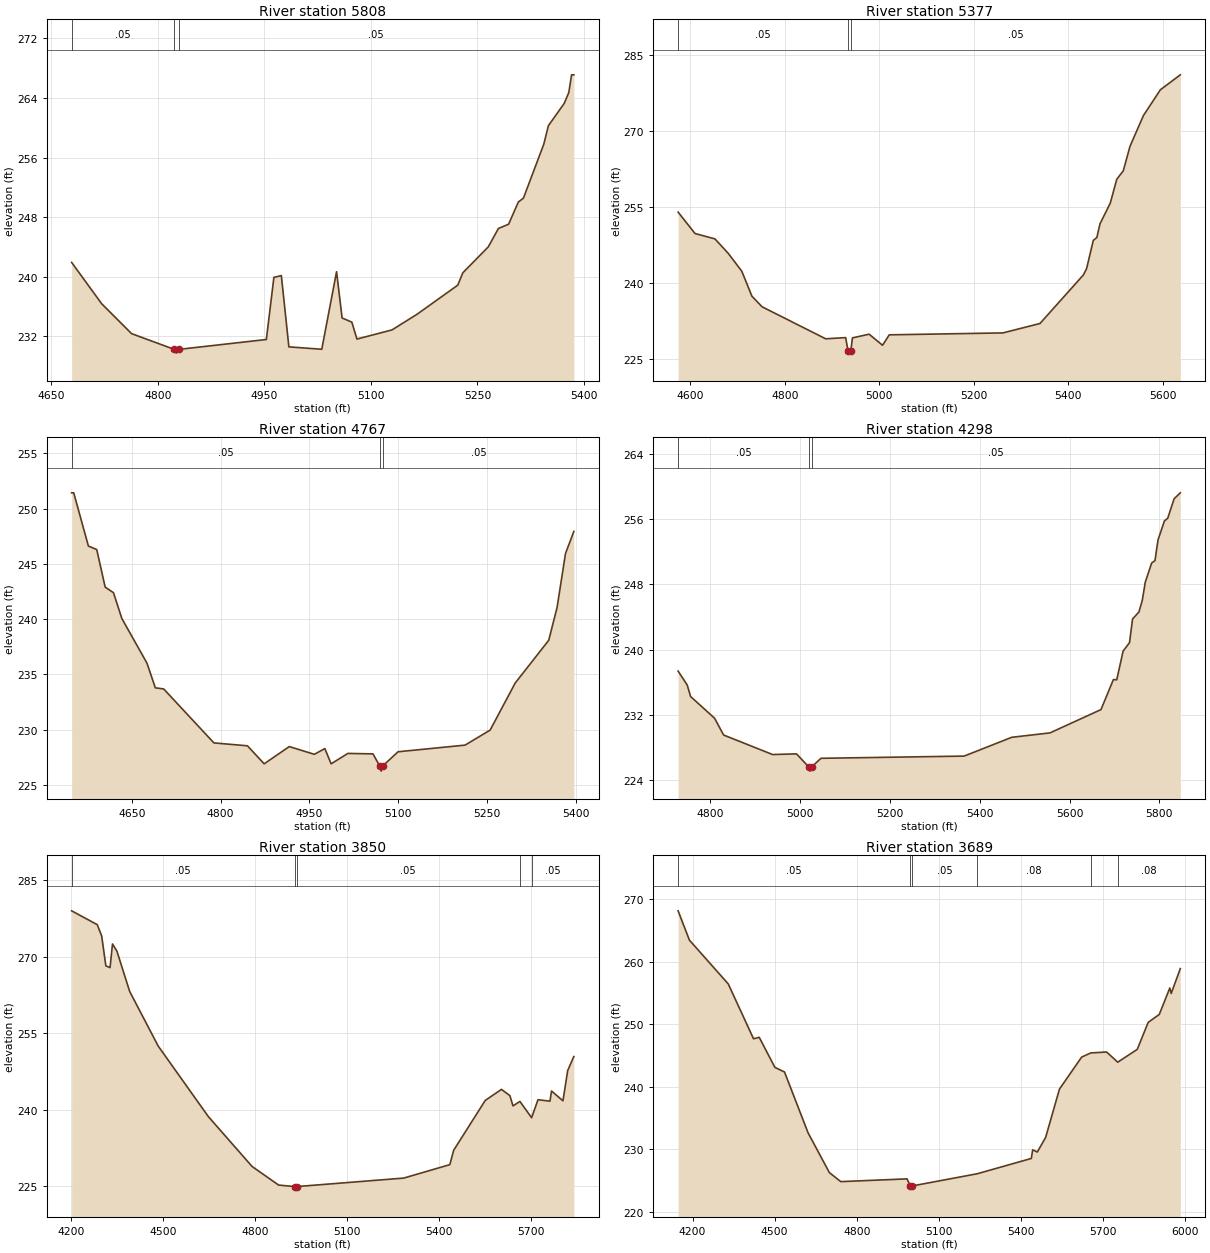
Type RM Length L Ch R = 1,5808,431,431,431
BEGIN DESCRIPTION:
UNT 015 IN BOCR 9.0
END DESCRIPTION:
XS GIS Cut Line= 3
      3689599.63     10596260.18      3689899.61     10596160.19
      3690199.60     10595910.20
#Sta/Elev= 30
  4678.9  241.93  4721.0  236.40  4763.2  232.37  4823.4  230.25  4826.2  229.75
  4829.4  230.25  4952.9  231.58  4963.5  239.92  4974.0  240.16  4984.6  230.59
  5030.9  230.27  5051.7  240.68  5059.5  234.47  5073.2  233.91  5080.4  231.64
  5129.8  232.87  5165.0  234.97  5222.3  238.88  5229.4  240.54  5265.2  244.02
  5279.5  246.49  5293.8  247.06  5307.5  250.04  5314.7  250.57  5343.3  257.80
  5349.8  260.29  5371.9  263.26  5378.5  264.73  5382.4  267.12  5385.6  267.12
#Mann=3,-1,0
  4678.9    0.05       0  4823.4    0.03       0  4829.4    0.05       0
Bank Sta=4823.4,4829.4
Exp/Cntr=0.3,0.1

Type RM Length L Ch R = 1,5377,610,610,610
BEGIN DESCRIPTION:
UNT 015 IN BOCR 8.0
END DESCRIPTION:
XS GIS Cut Line= 3
      3689649.58     10596810.21      3689949.61     10596560.19
      3690399.59     10596060.21
#Sta/Elev= 30
  4574.2  254.01  4610.0  249.79  4652.3  248.72  4680.3  245.88  4709.0  242.35
  4730.4  237.43  4751.9  235.33  4886.6  229.01  4929.0  229.24  4933.8  226.68
  4936.5  226.18  4939.8  226.68  4943.3  229.19  4978.6  229.92  5007.0  227.73
  5021.2  229.79  5261.9  230.17  5340.3  232.03  5432.3  241.62  5439.0  242.86
  5453.2  248.43  5460.7  249.00  5467.4  251.72  5489.1  255.78  5502.9  260.50
  5516.7  262.17  5530.9  267.00  5559.3  273.07  5595.2  278.16  5637.4  281.11
#Mann=3,-1,0
  4574.2    0.05       0  4933.8    0.03       0  4939.8    0.05       0
Bank Sta=4933.8,4939.8
Exp/Cntr=0.3,0.1

Type RM Length L Ch R = 1,4767,469,469,469
BEGIN DESCRIPTION:
UNT 015 IN BOCR 7.0
END DESCRIPTION:
XS GIS Cut Line= 3
      3689899.62     10597010.18      3690199.61     10596710.19
      3690499.60     10596410.20
#Sta/Elev= 30
  4548.5  251.42  4552.0  251.42  4576.8  246.61  4590.9  246.29  4605.1  242.90
  4619.2  242.39  4633.3  240.06  4675.8  236.02  4689.9  233.79  4704.0  233.69
  4788.9  228.81  4845.5  228.55  4873.8  226.92  4916.2  228.48  4958.6  227.78
  4976.3  228.30  4986.9  226.92  5015.2  227.86  5057.6  227.82  5068.7  226.76
  5071.5  226.26  5074.7  226.76  5100.0  228.01  5213.2  228.61  5255.6  229.97
  5298.0  234.23  5354.6  238.09  5368.7  241.06  5382.9  245.93  5397.0  247.93
#Mann=3,-1,0
  4548.5    0.05       0  5068.7    0.03       0  5074.7    0.05       0
Bank Sta=5068.7,5074.7
Exp/Cntr=0.3,0.1

Type RM Length L Ch R = 1,4298,448,448,448
BEGIN DESCRIPTION:
UNT 015 IN BOCR 6.0
END DESCRIPTION:
XS GIS Cut Line= 3
      3690049.64     10597160.18      3690349.61     10597110.19
      3690899.58     10596510.22
#Sta/Elev= 30
  4728.5  237.37  4748.7  235.68  4756.3  234.26  4809.6  231.61  4829.8  229.55
  4938.8  227.16  4992.1  227.24  5019.5  225.63  5022.2  225.13  5025.5  225.63
  5046.5  226.70  5365.3  226.97  5471.3  229.27  5556.4  229.81  5669.9  232.66
  5697.6  236.34  5705.0  236.30  5719.2  239.82  5733.4  240.85  5740.2  243.75
  5754.4  244.61  5761.8  246.01  5768.5  248.25  5782.7  250.60  5790.1  250.89
  5796.9  253.43  5811.1  255.74  5818.5  256.08  5832.7  258.46  5846.5  259.19
#Mann=3,-1,0
  4728.5    0.05       0  5019.5    0.03       0  5025.5    0.05       0
Bank Sta=5019.5,5025.5
Exp/Cntr=0.3,0.1

Type RM Length L Ch R = 1,3850,161,161,161
BEGIN DESCRIPTION:
UNT 015 IN BOCR 5.0
END DESCRIPTION:
XS GIS Cut Line= 3
      3690169.95     10598017.21      3690748.04     10597293.29
      3690878.26     10596595.35
#Sta/Elev= 30
  4203.0  279.03  4286.5  276.31  4300.9  274.08  4314.4  268.23  4328.1  267.87
  4336.1  272.52  4350.5  271.11  4392.1  263.19  4485.0  252.47  4648.3  238.62
  4790.8  228.82  4877.3  225.16  4930.3  224.86  4933.1  224.36  4936.3  224.86
  5285.2  226.53  5435.3  229.17  5447.9  232.00  5550.8  241.79  5603.5  243.95
  5631.0  242.73  5641.2  240.71  5663.7  241.59  5701.8  238.39  5722.6  241.92
  5761.6  241.64  5766.7  243.63  5804.0  241.71  5819.4  247.66  5839.4  250.40
#Mann=5,-1,0
  4203.0    0.05       0  4930.3    0.03       0  4936.3    0.05       0
  5663.7    0.08       0  5701.8    0.05       0
Bank Sta=4930.3,4936.3
Exp/Cntr=0.3,0.1

Type RM Length L Ch R = 1,3689,150,150,150
BEGIN DESCRIPTION:
UNT 015 IN BOCR 4.0
END DESCRIPTION:
XS GIS Cut Line= 3
      3690263.64     10598142.27      3690737.63     10597746.42
      3690930.18     10596544.28
#Sta/Elev= 30
  4147.3  268.14  4188.6  263.45  4330.5  256.44  4422.9  247.66  4443.7  247.89
  4500.9  243.08  4536.1  242.34  4622.0  232.62  4700.1  226.23  4741.7  224.79
  4983.8  225.23  4995.8  224.09  4998.6  223.59  5001.8  224.09  5241.2  226.06
  5437.9  228.50  5442.9  229.88  5459.8  229.53  5490.2  231.86  5540.8  239.61
  5621.9  244.73  5655.0  245.39  5713.0  245.54  5753.8  243.91  5825.1  245.97
  5864.9  250.28  5905.4  251.55  5944.0  255.79  5949.0  254.91  5982.3  258.89
#Mann=6,-1,0
  4147.3    0.05       0  4995.8    0.03       0  5001.8    0.05       0
  5241.2    0.08       0  5655.0    0.05       0  5753.8    0.08       0
Bank Sta=4995.8,5001.8
Exp/Cntr=0.3,0.1

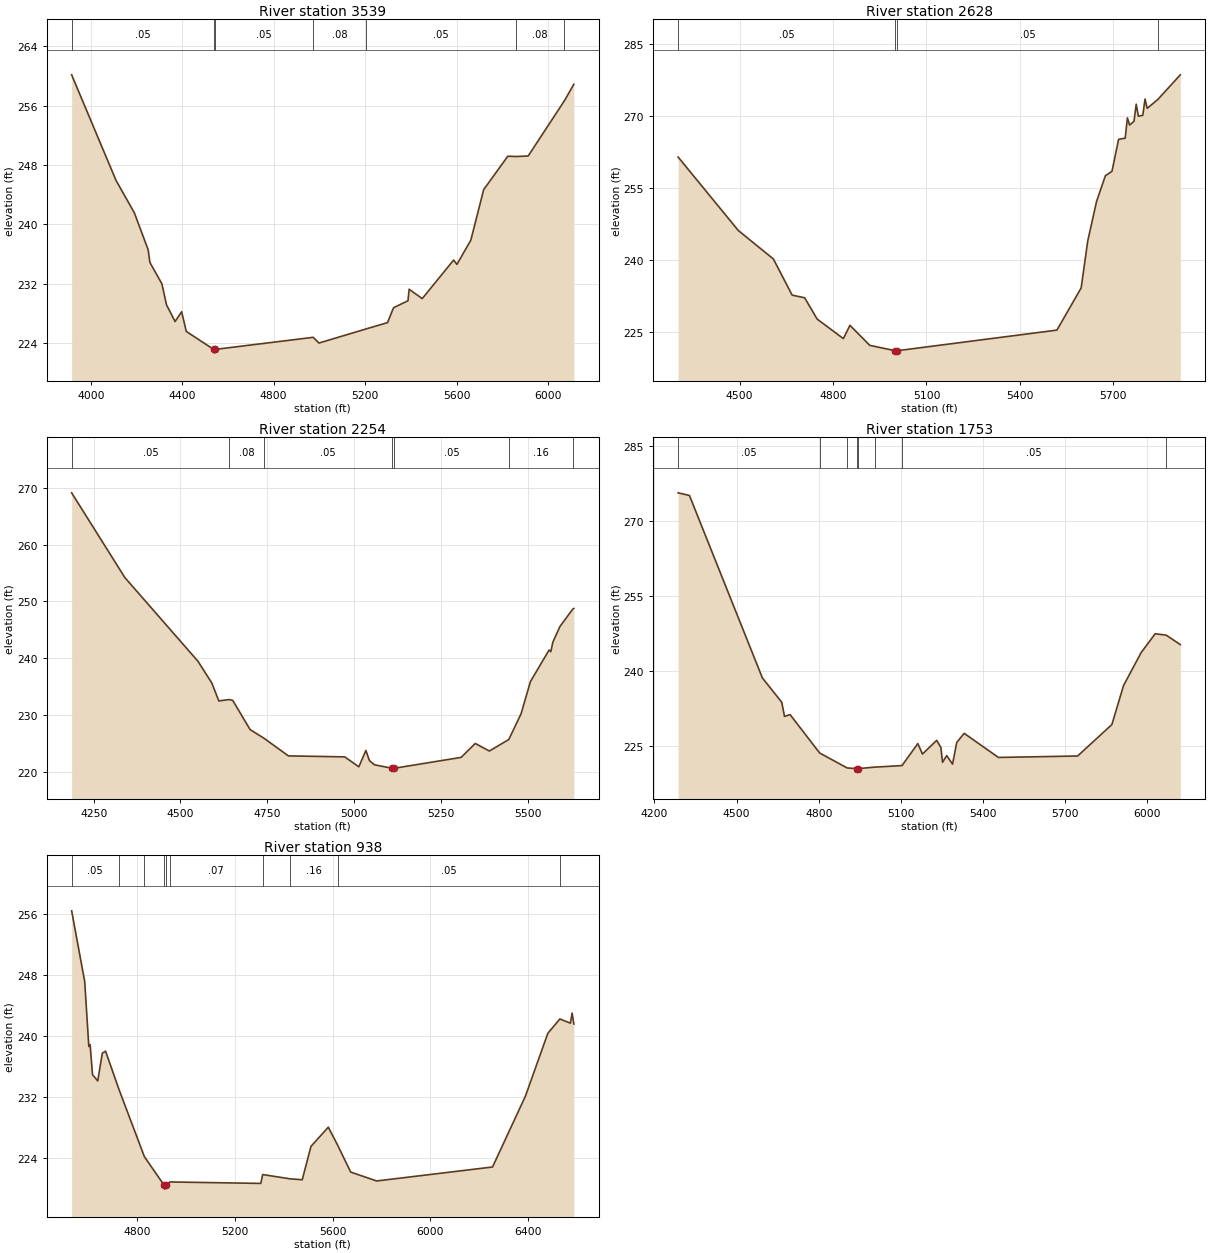
Type RM Length L Ch R = 1,3539,911,911,911
BEGIN DESCRIPTION:
UNT 015 IN BOCR 3.0
END DESCRIPTION:
XS GIS Cut Line= 3
      3690326.15     10598282.88      3690779.29     10598246.42
      3691044.55     10596524.84
#Sta/Elev= 30
  3916.6  260.16  4110.7  245.93  4190.9  241.56  4251.1  236.59  4259.0  234.86
  4311.3  232.00  4331.4  229.17  4368.9  226.91  4397.7  228.23  4418.0  225.58
  4537.9  223.15  4540.7  222.65  4543.9  223.15  4972.9  224.78  4998.4  224.01
  5204.5  225.91  5298.2  226.76  5324.5  228.77  5387.7  229.71  5392.7  231.26
  5450.0  230.00  5587.4  235.20  5601.8  234.61  5662.5  237.87  5718.8  244.69
  5824.4  249.19  5860.7  249.15  5913.4  249.22  6072.2  256.68  6113.1  258.89
#Mann=7,-1,0
  3916.6    0.05       0  4537.9    0.07       0  4543.9    0.05       0
  4972.9    0.08       0  5204.5    0.05       0  5860.7    0.08       0
  6072.2    0.16       0
Bank Sta=4537.9,4543.9
Exp/Cntr=0.3,0.1

Type RM Length L Ch R = 1,2628,374,374,374
BEGIN DESCRIPTION:
Mapping XS 83ec3e4a
END DESCRIPTION:
XS GIS Cut Line= 3
      3690305.34     10598345.37      3690810.54     10598293.29
      3691591.77     10597512.07
#Sta/Elev= 30
  4302.4  261.49  4496.0  246.18  4608.3  240.28  4668.6  232.75  4708.8  232.20
  4749.0  227.76  4833.0  223.71  4854.2  226.47  4917.9  222.30  4999.7  221.18
  5002.5  220.68  5005.7  221.18  5518.9  225.47  5596.7  234.25  5617.9  244.04
  5646.2  252.25  5674.5  257.60  5695.7  258.52  5716.9  265.18  5738.1  265.42
  5745.2  269.65  5752.3  268.14  5766.4  268.94  5773.5  272.49  5780.5  269.99
  5794.7  270.18  5801.8  273.56  5808.8  271.63  5842.9  273.47  5915.1  278.60
#Mann=4,-1,0
  4302.4    0.05       0  4999.7    0.03       0  5005.7    0.05       0
  5842.9    0.16       0
Bank Sta=4999.7,5005.7
Exp/Cntr=0.3,0.1

Type RM Length L Ch R = 1,2254,501,501,501
BEGIN DESCRIPTION:
Mapping XS 23f9ea14
END DESCRIPTION:
XS GIS Cut Line= 3
      3690216.83     10598387.04      3690867.84     10598433.92
      3691649.09     10598293.29
#Sta/Elev= 30
  4186.5  269.11  4339.7  254.20  4550.2  239.47  4590.3  235.63  4610.4  232.48
  4640.6  232.72  4650.5  232.57  4700.6  227.43  4739.5  225.95  4810.9  222.80
  4973.1  222.63  5013.7  220.88  5034.0  223.76  5044.2  221.98  5058.6  221.24
  5109.3  220.62  5112.0  220.12  5115.3  220.62  5308.4  222.54  5349.0  224.99
  5389.7  223.66  5445.6  225.68  5481.1  230.23  5508.0  235.89  5561.6  241.43
  5566.7  241.15  5572.6  242.83  5592.9  245.57  5629.8  248.64  5633.0  248.75
#Mann=7,-1,0
  4186.5    0.05       0  4640.6    0.08       0  4739.5    0.05       0
  5109.3    0.03       0  5115.3    0.05       0  5445.6    0.16       0
  5629.8    0.05       0
Bank Sta=5109.3,5115.3
Exp/Cntr=0.3,0.1

Type RM Length L Ch R = 1,1753,815,815,815
BEGIN DESCRIPTION:
UNT 015 IN BOCR 2.0
END DESCRIPTION:
XS GIS Cut Line= 3
      3690149.04     10598683.91      3691008.46     10598861.00
      3691820.93     10598355.81
#Sta/Elev= 30
  4286.5  275.66  4327.9  275.13  4594.3  238.58  4664.9  233.72  4675.1  230.88
  4695.5  231.23  4803.6  223.54  4903.8  220.55  4938.3  220.41  4941.1  219.91
  4944.3  220.41  5004.0  220.71  5104.2  221.02  5162.0  225.43  5179.0  223.33
  5230.9  226.08  5246.3  224.64  5252.2  221.68  5267.5  223.02  5288.8  221.31
  5304.1  225.65  5331.3  227.48  5456.4  222.65  5745.7  222.94  5870.8  229.24
  5913.3  237.04  5977.8  243.67  6029.0  247.43  6069.2  247.15  6120.7  245.26
#Mann=8,-1,0
  4286.5    0.05       0  4803.6    0.16       0  4903.8    0.05       0
  4938.3   0.035       0  4944.3    0.05       0  5004.0    0.16       0
  5104.2    0.05       0  6069.2    0.16       0
Bank Sta=4938.3,4944.3
Exp/Cntr=0.3,0.1

Type RM Length L Ch R = 1,938,0,0,0
BEGIN DESCRIPTION:
UNT 015 IN BOCR 1.0
END DESCRIPTION:
XS GIS Cut Line= 3
      3690249.64     10599410.20      3690649.61     10599560.19
      3691849.65     10598460.16
#Sta/Elev= 30
  4532.5  256.43  4585.9  247.18  4602.8  238.66  4608.1  238.90  4617.9  234.96
  4639.3  234.14  4658.0  237.78  4671.3  238.04  4726.1  233.03  4830.3  224.21
  4911.3  220.46  4914.0  219.96  4917.3  220.46  4934.4  220.90  5306.5  220.71
  5314.2  221.87  5426.6  221.31  5476.1  221.19  5511.9  225.56  5582.8  228.08
  5621.5  225.69  5674.6  222.19  5780.7  221.03  6254.9  222.86  6389.3  232.13
  6481.2  240.38  6530.4  242.26  6573.7  241.71  6580.5  243.03  6587.6  241.60
#Mann=10,-1,0
  4532.5    0.05       0  4726.1    0.16       0  4830.3    0.12       0
  4911.3    0.07       0  4917.3    0.12       0  4934.4    0.07       0
  5314.2    0.05       0  5426.6    0.16       0  5621.5    0.05       0
  6530.4    0.16       0
Bank Sta=4911.3,4917.3
Exp/Cntr=0.3,0.1

Chan Stop Cuts=-1