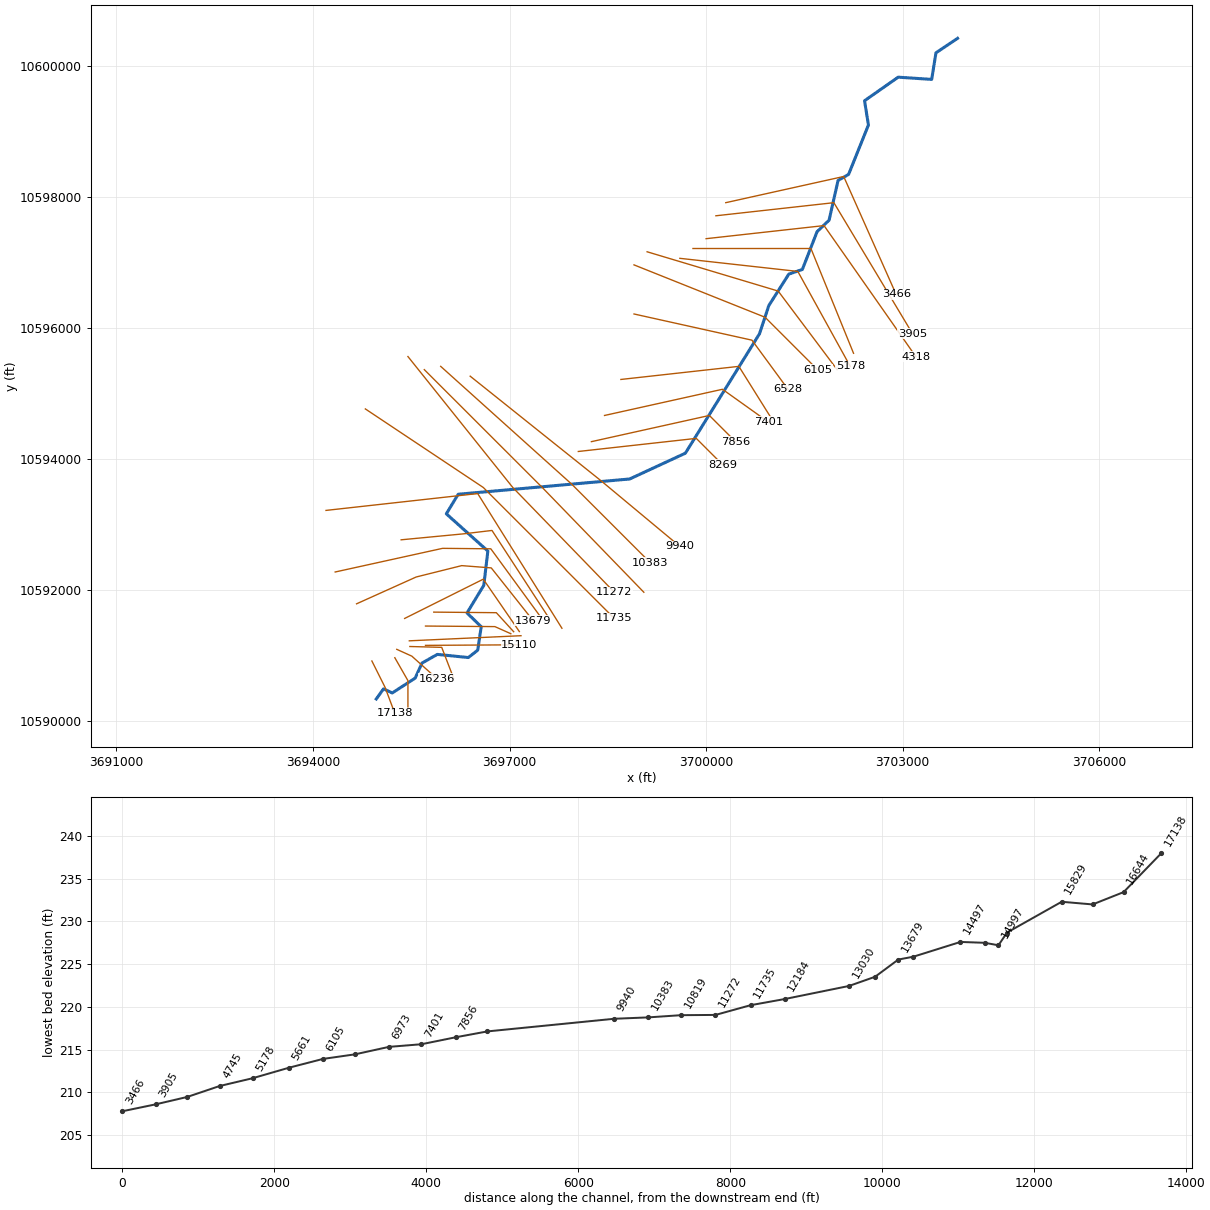
--- UNT 016 IN BOCR.prj (project) ---

Proj Title=UNT 016 IN BOCR Base Level Engineering
Current Plan=p01
Default Exp/Contr=0.3,0.1
English Units
Geom File=g01
Flow File=f01
Plan File=p01
Y Axis Title=Elevation
X Axis Title(PF)=Main Channel Distance
X Axis Title(XS)=Station
BEGIN DESCRIPTION:
UNT 016 IN BOCR
END DESCRIPTION:
DSS Export Rating Curves= 0
DSS Export Rating Curve Sorted= 0
DSS Export Volume Flow Curves= 0
DXF OffsetX= 0
DXF OffsetY= 0
DXF ScaleX= 1
DXF ScaleY= 10

--- UNT 016 IN BOCR.p01 (plan) ---

Plan Title=Multiple Run
Short Identifier=Multiple
Geom File=g01
Flow File=f01
Subcritical Flow
K Sum by GR= 0
Std Step Tol= 0.01
Critical Tol= 0.01
Num of Std Step Trials= 20
Max Error Tol= 0.3
Flow Tol Ratio= 0.001
Split Flow NTrial= 30
Split Flow Tol= 0.02
Split Flow Ratio= 0.02
Log Output Level= 0
Friction Slope Method= 1
Unsteady Friction Slope Method= 2
Unsteady Bridges Friction Slope Method= 1
Parabolic Critical Depth
Global Vel Dist=  1 , 1 , 1
Global Log Level= 0
CheckData=True
Encroach Param= -1, 0, 0, 0
BEGIN DESCRIPTION:
Multiple Run
END DESCRIPTION:

--- UNT 016 IN BOCR.f01 (steady flow) ---

Flow Title=Multiple
Number of Profiles=7
Profile Names=10-year,25-year,50-year,1pct_min,100-year,1pct_plu,500-year
River Rch & RM= UNT 016 IN BOCR,Reach-1,17138
     792    1085    1328    1192    1612    2180    2387
River Rch & RM= UNT 016 IN BOCR,Reach-1,8269
     883    1210    1482    1330    1799    2433    2665
River Rch & RM= UNT 016 IN BOCR,Reach-1,3905
    1221    1701    2106    1908    2581    3490    3898
Boundary for River Rch & Prof#=UNT 016 IN BOCR,Reach-1,1
Up Type=0
Dn Type=3
Dn Slope=0.005
Boundary for River Rch & Prof#=UNT 016 IN BOCR,Reach-1,2
Up Type=0
Dn Type=3
Dn Slope=0.005
Boundary for River Rch & Prof#=UNT 016 IN BOCR,Reach-1,3
Up Type=0
Dn Type=3
Dn Slope=0.005
Boundary for River Rch & Prof#=UNT 016 IN BOCR,Reach-1,4
Up Type=0
Dn Type=3
Dn Slope=0.005
Boundary for River Rch & Prof#=UNT 016 IN BOCR,Reach-1,5
Up Type=0
Dn Type=3
Dn Slope=0.005
Boundary for River Rch & Prof#=UNT 016 IN BOCR,Reach-1,6
Up Type=0
Dn Type=3
Dn Slope=0.005
Boundary for River Rch & Prof#=UNT 016 IN BOCR,Reach-1,7
Up Type=0
Dn Type=3
Dn Slope=0.005

--- UNT 016 IN BOCR.g01 (geometry) ---

Geom Title=Existing Conditions
Program Version=4.10

River Reach=UNT 016 IN BOCR ,Reach-1
Reach XY= 30
       3694966.5       10590330.      3695077.25       10590485.
       3695210.5       10590422.       3695560.5       10590649.
        3695664.       10590878.        3695898.       10591011.
      3696371.75       10590963.      3696514.75       10591076.
      3696567.75       10591434.       3696351.5       10591644.
      3696607.25       10592066.      3696669.16     10592589.38
       3696035.5       10593158.       3696216.5       10593457.
      3698833.25       10593690.       3699683.5       10594084.
        3700814.       10595907.        3700957.       10596339.
        3701262.       10596819.       3701468.5       10596890.
       3701693.5       10597468.      3701876.25       10597642.
       3702013.5       10598250.      3702174.25       10598342.
      3702477.25       10599097.      3702417.25       10599467.
        3702931.       10599827.      3703442.25       10599793.
       3703507.5       10600199.      3703836.87      10600420.2

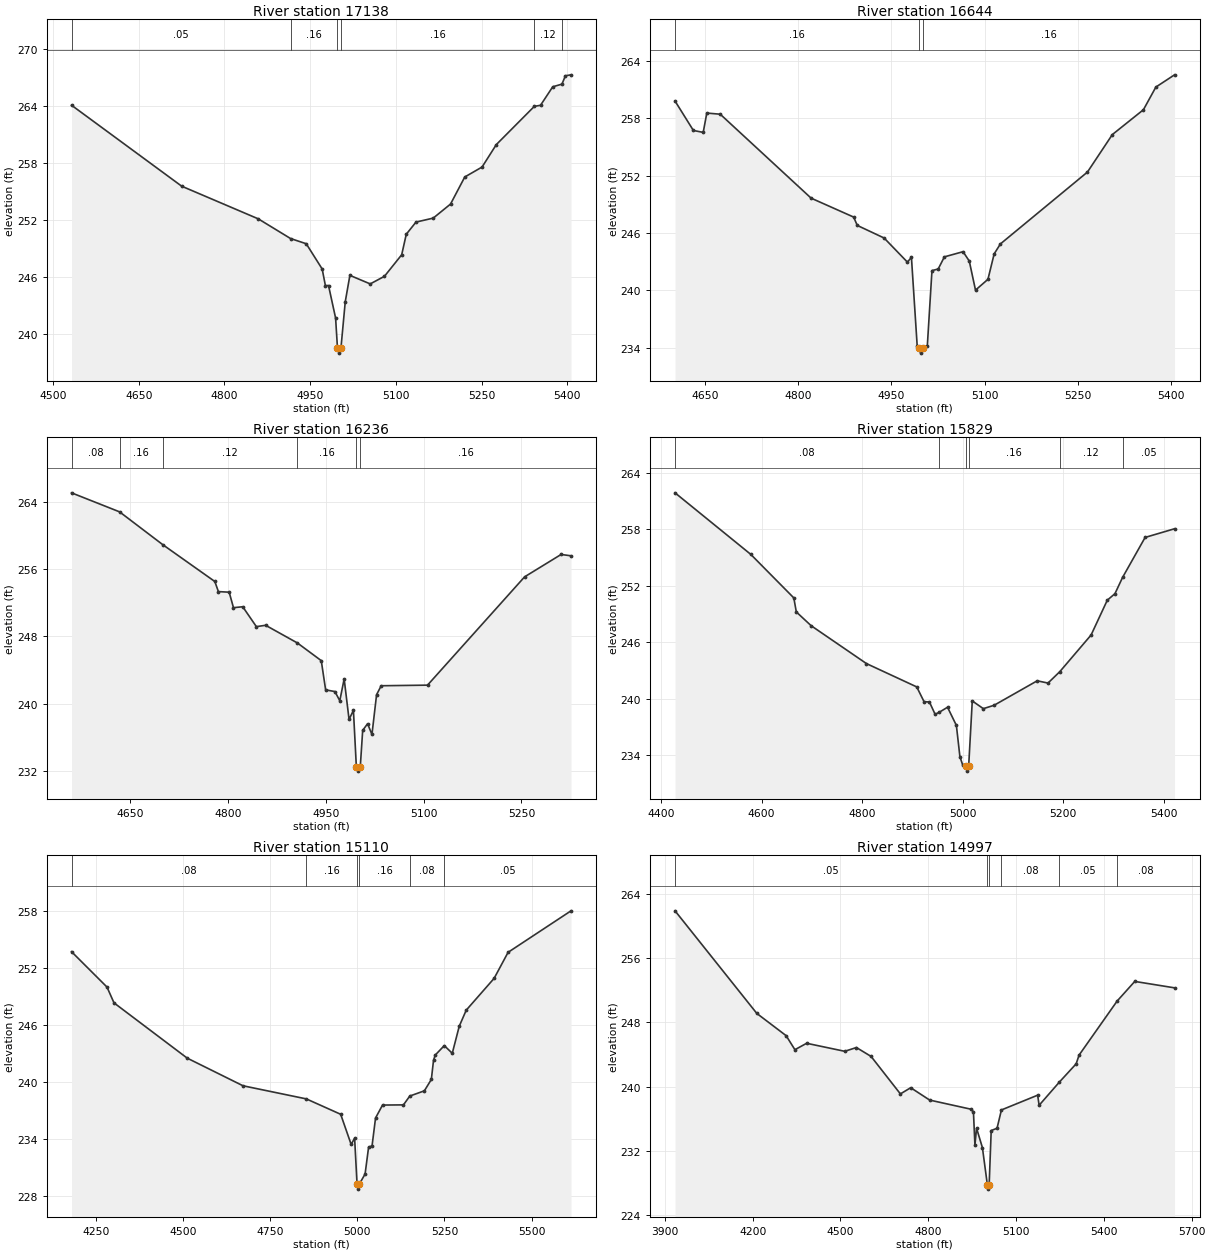
Type RM Length L Ch R = 1 ,17138   ,494,494,494
BEGIN DESCRIPTION:
UNT 016 IN BOCR 30.0
END DESCRIPTION:
XS GIS Cut Line= 3
      3694899.61     10590910.18      3695099.61     10590510.19
      3695249.61     10590110.19
#Sta/Elev= 30
  4532.3  264.07  4725.2  255.54  4859.3   252.1  4915.7  250.03  4943.2  249.48
  4971.1  246.82  4976.7  245.08  4982.2  245.08  4994.6  241.65  4997.9  238.46
  5000.6  237.96  5003.9  238.46  5011.5  243.38  5019.6  246.15  5055.2  245.25
  5080.1  246.05  5110.3  248.32  5118.3  250.48  5135.3  251.76  5165.5  252.18
  5195.8  253.66  5220.7  256.51    5251  257.56  5275.9  259.92  5342.5  263.95
  5353.3  264.06  5374.7  266.01  5390.8  266.29  5396.9  267.17  5406.7  267.27
#Mann= 6 ,-1 , 0
  4532.3     .05       0  4915.7     .16       0  4997.9     .07       0
  5003.9     .16       0  5342.5     .12       0  5390.8     .16       0
Bank Sta=4997.9,5003.9
XS Rating Curve= 0 ,0
Exp/Cntr=0.3,0.1

Type RM Length L Ch R = 1 ,16644   ,408,408,408
BEGIN DESCRIPTION:
UNT 016 IN BOCR 29.0
END DESCRIPTION:
XS GIS Cut Line= 3
      3695249.62     10590960.17      3695449.61     10590610.19
      3695449.61     10590210.18
#Sta/Elev= 30
  4602.2   259.8  4631.7  256.72  4647.5  256.52  4653.3  258.54  4674.9  258.42
    4821  249.64  4889.4  247.66  4895.2  246.79  4938.4  245.47  4975.8  242.95
  4982.3  243.45  4991.6  234.13  4994.4  233.93  4997.1  233.43  5000.4  233.93
  5007.8  234.15  5015.3  242.06  5025.3  242.23  5035.3   243.5  5065.3  244.04
  5075.3  243.06  5085.3  240.02  5105.3  241.15  5115.3  243.81  5125.3  244.85
  5265.3  252.37  5305.3  256.29  5355.3  258.89  5375.3  261.26  5405.3  262.54
#Mann= 3 ,-1 , 0
  4602.2     .16       0  4994.4     .07       0  5000.4     .16       0
Bank Sta=4994.4,5000.4
XS Rating Curve= 0 ,0
Exp/Cntr=0.3,0.1

Type RM Length L Ch R = 1 ,16236   ,407,407,407
BEGIN DESCRIPTION:
UNT 016 IN BOCR 28.0
END DESCRIPTION:
XS GIS Cut Line= 3
      3695279.45     10591088.11      3695509.45     10590983.96
      3695891.42     10590641.05
#Sta/Elev= 30
  4560.3  265.04    4634  262.78  4700.1  258.89    4780  254.51  4785.5  253.31
    4802  253.24  4808.6   251.4  4822.8  251.51  4843.7  249.15  4857.9  249.31
  4906.6  247.21  4943.2  245.11  4949.9  241.64  4964.1  241.44  4971.6  240.35
  4978.3  242.94  4985.8  238.13  4992.5  239.21    4997  232.49  4999.7  231.99
    5003  232.49  5006.7  236.83  5014.2  237.62  5020.9  236.34    5028  241.07
  5035.1  242.13  5106.1   242.2  5254.9  255.06  5310.9  257.72  5326.1  257.56
#Mann= 6 ,-1 , 0
  4560.3     .08       0    4634     .16       0  4700.1     .12       0
  4906.6     .16       0    4997     .07       0    5003     .16       0
Bank Sta=4997,5003
XS Rating Curve= 0 ,0
Exp/Cntr=0.3,0.1

Type RM Length L Ch R = 1 ,15829   ,719,719,719
BEGIN DESCRIPTION:
UNT 016 IN BOCR 27.0
END DESCRIPTION:
XS GIS Cut Line= 3
      3695479.08     10591131.53      3695965.18     10591118.51
      3696147.48     10590645.39
#Sta/Elev= 30
    4428  261.88  4578.6  255.34  4664.2  250.71  4669.2  249.22  4698.6  247.76
  4808.7  243.73  4908.7  241.25  4923.2  239.68  4933.9  239.65  4945.2  238.34
  4953.2  238.55  4969.9  239.09  4987.5  237.16  4994.5  233.84  4999.8  232.99
  5005.9   232.8  5008.7   232.3  5011.9   232.8  5019.1  239.76  5041.1  238.94
  5062.5   239.3  5148.2   241.9  5169.7  241.66  5193.3  242.88  5255.4  246.77
  5287.6  250.47  5302.8  251.16    5318  252.89  5362.8  257.14  5421.3  258.06
#Mann= 6 ,-1 , 0
    4428     .08       0  4953.2     .16       0  5005.9     .07       0
  5011.9     .16       0  5193.3     .12       0    5318     .05       0
Bank Sta=5005.9,5011.9
XS Rating Curve= 0 ,0
Exp/Cntr=0.3,0.1

Type RM Length L Ch R = 1 ,15110   ,113,113,113
BEGIN DESCRIPTION:
UNT 016 IN BOCR 26.0
END DESCRIPTION:
XS GIS Cut Line= 2
       3695717.8     10591148.89      3697150.07     10591157.57
#Sta/Elev= 30
  4180.5   253.7  4282.3  249.97  4302.3  248.31  4512.3  242.49  4672.3  239.58
  4853.8   238.2  4952.3  236.58  4982.3  233.41  4992.3  234.06  4999.3   229.2
  5002.1   228.7  5005.3   229.2  5022.3  230.29  5032.3   233.1  5042.3  233.26
  5052.3  236.19  5072.3  237.55  5132.3  237.57  5150.5   238.5  5192.3  239.05
  5212.3  240.25  5218.6  242.28  5223.6  242.82  5249.4  243.81  5272.3     243
  5292.3  245.85  5312.3  247.54  5392.3  250.89  5432.3  253.63  5612.8     258
#Mann= 6 ,-1 , 0
  4180.5     .08       0  4853.8     .16       0  4999.3     .07       0
  5005.3     .16       0  5150.5     .08       0  5249.4     .05       0
Bank Sta=4999.3,5005.3
XS Rating Curve= 0 ,0
Exp/Cntr=0.3,0.1

Type RM Length L Ch R = 1 ,14997   ,181,181,181
BEGIN DESCRIPTION:
UNT 016 IN BOCR 25.0
END DESCRIPTION:
XS GIS Cut Line= 2
      3695470.42     10591218.34      3697175.33     10591296.42
#Sta/Elev= 30
  3934.8   261.9  4214.3  249.11  4314.4  246.34  4344.4  244.59  4384.5  245.39
  4514.6  244.39  4554.6  244.86  4604.7  243.75  4704.8  239.08  4740.1  239.85
  4804.9  238.31    4945  237.18  4954.4  236.86  4959.5  232.71  4965.1   234.8
  4985.1  232.38  5002.1  227.71  5004.9  227.21  5008.1  227.71  5015.1  234.51
  5035.1   234.8    5050  237.08  5173.8  238.92  5178.8  237.66  5247.7  240.54
  5305.4  242.83  5315.4  243.92  5445.3  250.65  5505.6   253.1  5641.5   252.3
#Mann= 6 ,-1 , 0
  3934.8     .05       0  5002.1     .04       0  5008.1     .05       0
    5050     .08       0  5247.7     .05       0  5445.3     .08       0
Bank Sta=5002.1,5008.1
XS Rating Curve= 0 ,0
Exp/Cntr=0.3,0.1

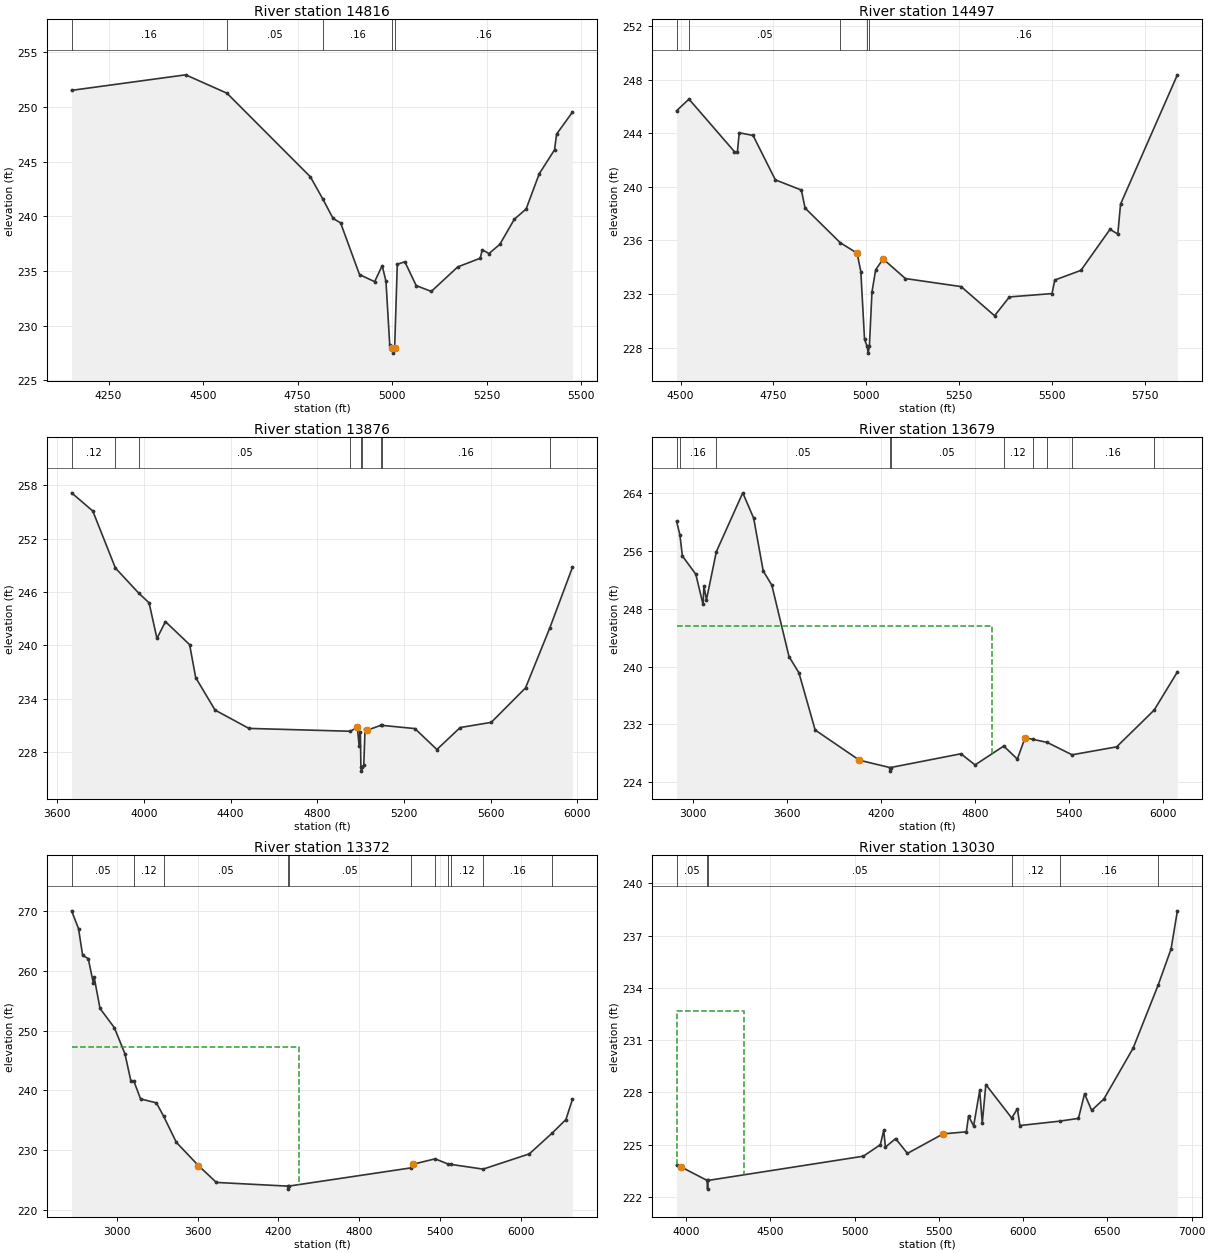
Type RM Length L Ch R = 1 ,14816   ,319,319,319
BEGIN DESCRIPTION:
Mapping XS c0360093
END DESCRIPTION:
XS GIS Cut Line= 3
      3695717.77     10591444.03      3696776.81     10591435.35
      3697019.91     10591326.82
#Sta/Elev= 30
    4152  251.51  4453.8  252.93  4563.2  251.25  4783.9  243.61  4816.9  241.58
  4843.9  239.81  4863.9   239.4  4913.9  234.68  4953.9  234.03  4973.9  235.49
  4983.9  234.07  4993.9  228.24  5000.9     228  5003.6   227.5  5006.9     228
  5013.9  235.62  5033.9  235.85  5063.9  233.67  5103.9  233.14  5173.9  235.38
  5233.3  236.17  5238.8  236.94  5256.5   236.6  5285.2  237.44  5323.7  239.74
  5354.8  240.67  5389.4  243.88    5430  246.08  5435.4  247.51  5477.3  249.52
#Mann= 5 ,-1 , 0
    4152     .16       0  4563.2     .05       0  4816.9     .16       0
  5000.9     .07       0  5006.9     .16       0
Bank Sta=5000.9,5006.9
XS Rating Curve= 0 ,0
Exp/Cntr=0.3,0.1

Type RM Length L Ch R = 1 ,14497   ,621,621,621
BEGIN DESCRIPTION:
UNT 016 IN BOCR 24.0
END DESCRIPTION:
XS GIS Cut Line= 3
      3695843.68      10591656.7      3696798.51     10591648.02
      3697063.24     10591357.25
#Sta/Elev= 30
  4489.1  245.67  4522.5  246.54    4645  242.62  4652.8  242.58  4657.8  244.03
    4695  243.83    4755  240.52    4825  239.76    4835  238.42  4929.4  235.84
  4975.1  235.05  4985.1  233.68  4995.1  228.62  5002.1   228.1  5004.8   227.6
  5008.1   228.1  5015.1  232.16  5025.1  233.82  5045.1  234.62  5105.1  233.16
  5255.1  232.56  5345.1  230.39  5385.1  231.79  5499.7  232.04  5507.2  233.05
  5577.5  233.77  5655.8  236.83  5676.8  236.48  5684.2  238.71  5837.2  248.35
#Mann= 5 ,-1 , 0
  4489.1     .16       0  4522.5     .05       0  4929.4     .16       0
  5002.1     .07       0  5008.1     .16       0
Bank Sta=4975.1,5045.1
XS Rating Curve= 0 ,0
Exp/Cntr=0.3,0.1

Type RM Length L Ch R = 1 ,13876   ,197,197,197
BEGIN DESCRIPTION:
UNT 016 IN BOCR 23.0
END DESCRIPTION:
XS GIS Cut Line= 3
      3695399.57     10591560.17      3696599.61     10592160.19
       3697149.6      10591360.2
#Sta/Elev= 30
  3665.7  257.14  3763.6   255.1  3868.1  248.69  3976.6  245.85  4023.5  244.78
  4059.9  240.78    4099  242.67  4210.8  240.08  4238.7  236.38  4328.2  232.73
  4484.7  230.67  4952.9  230.35    4985  230.81  4993.4  228.74    4999  230.29
  5001.6  226.37  5004.3  225.87  5007.6  226.37  5014.8  226.51  5020.9  230.64
  5029.7  230.46  5093.9  231.02  5099.5  231.01  5250.9  230.65  5352.4   228.3
    5460  230.77  5603.4  231.35  5761.7  235.22  5873.8  241.96  5978.2  248.76
#Mann= 9 ,-1 , 0
  3665.7     .12       0  3868.1     .16       0  3976.6     .05       0
  4952.9     .16       0  5001.6     .07       0  5007.6     .16       0
  5093.9     .12       0  5099.5     .16       0  5873.8     .05       0
Bank Sta=4985,5029.7
XS Rating Curve= 0 ,0
Exp/Cntr=0.3,0.1

Type RM Length L Ch R = 1 ,13679   ,307,307,307
BEGIN DESCRIPTION:
Mapping XS 4e1e69cd
END DESCRIPTION:
XS GIS Cut Line= 5
       3694665.7     10591783.46      3695575.44     10592193.19
      3696269.88      10592366.8      3696721.27     10592332.07
      3697360.13     10591526.55
#Sta/Elev= 30
  2895.4   260.1  2916.5  258.25  2932.6  255.31  3018.1  252.79  3064.2  248.61
  3069.9  251.18  3086.1  249.25  3149.2  255.91  3317.8  264.05  3387.2  260.54
  3448.1  253.24  3502.9  251.28  3612.6  241.39  3675.9  239.15  3779.4  231.23
  4061.8  227.05  4255.2  226.04    4258  225.54  4261.2  226.04    4709  227.94
  4799.3   226.4  4982.2  229.01  5068.8  227.21  5118.4  230.15  5166.4  229.95
  5259.8  229.51  5418.1   227.8  5702.3   228.9  5941.5  233.98  6089.8  239.27
#Mann= 10 ,-1 , 0
  2895.4     .08       0  2916.5     .16       0  3149.2     .05       0
  4255.2     .07       0  4261.2     .05       0  4982.2     .12       0
  5166.4     .16       0  5259.8     .12       0  5418.1     .16       0
  5941.5     .05       0
#XS Ineff= 2 , 0
         4909.09  245.59
Permanent Ineff=
       F       F
Bank Sta=4061.8,5118.4
XS Rating Curve= 0 ,0
Exp/Cntr=0.3,0.1

Type RM Length L Ch R = 1 ,13372   ,342,342,342
BEGIN DESCRIPTION:
Mapping XS b38bc928
END DESCRIPTION:
XS GIS Cut Line= 4
      3694339.32     10592269.57      3695978.21     10592630.69
      3696714.33     10592623.74      3697484.87     10591568.59
#Sta/Elev= 30
  2663.1  270.01  2714.6  267.05  2745.3  262.57  2786.8  262.03  2825.4  257.89
  2830.5  258.97  2874.2  253.71  2980.8  250.49  3059.3  246.14    3103  241.66
  3125.1   241.6  3175.4  238.59  3293.2  237.93  3346.2  235.73  3441.6  231.33
  3605.5  227.45  3738.6  224.64  4269.7  224.02  4272.5  223.52  4275.7  224.02
  5184.6  227.07  5198.1  227.67  5364.1  228.58  5459.4  227.72  5482.2  227.65
  5720.4  226.86  6063.8  229.41  6235.8  232.93  6335.7  235.15    6384  238.51
#Mann= 11 ,-1 , 0
  2663.1     .05       0  3125.1     .12       0  3346.2     .05       0
  4269.7     .03       0  4275.7     .05       0  5184.6     .12       0
  5364.1     .05       0  5459.4     .16       0  5482.2     .12       0
  5720.4     .16       0  6235.8     .05       0
#XS Ineff= 2 , 0
         4354.55  247.26
Permanent Ineff=
       F       F
Bank Sta=3605.5,5198.1
XS Rating Curve= 0 ,0
Exp/Cntr=0.3,0.1

Type RM Length L Ch R = 1 ,13030   ,846,846,846
BEGIN DESCRIPTION:
Mapping XS 427cacf5
END DESCRIPTION:
XS GIS Cut Line= 4
      3695346.27     10592761.17      3696299.35     10592852.31
      3696732.46     10592903.98      3697592.72     10591579.79
#Sta/Elev= 30
  3942.8  223.83  3966.2  223.74    4124  222.95  4126.7  222.45    4130  222.95
  5051.6  224.34  5152.3     225  5172.4  225.82  5182.6  224.86  5242.9  225.35
  5313.4   224.5  5524.8  225.62  5662.9  225.74  5675.8  226.64  5706.1  226.08
  5742.3  228.12  5757.4  226.24  5778.5  228.45  5932.2  226.53  5965.7  227.06
  5980.9   226.1  6215.8  226.35  6328.2  226.51  6364.4  227.92  6406.6  226.97
  6479.1  227.62  6652.7  230.54  6802.1  234.18  6877.8  236.23  6915.5  238.42
#Mann= 6 ,-1 , 0
  3942.8     .05       0    4124     .03       0    4130     .05       0
  5932.2     .12       0  6215.8     .16       0  6802.1     .05       0
#XS Ineff= 2 , 0
         4341.19   232.7
Permanent Ineff=
       F       F
Bank Sta=3966.2,5524.8
XS Rating Curve= 0 ,0
Exp/Cntr=0.3,0.1

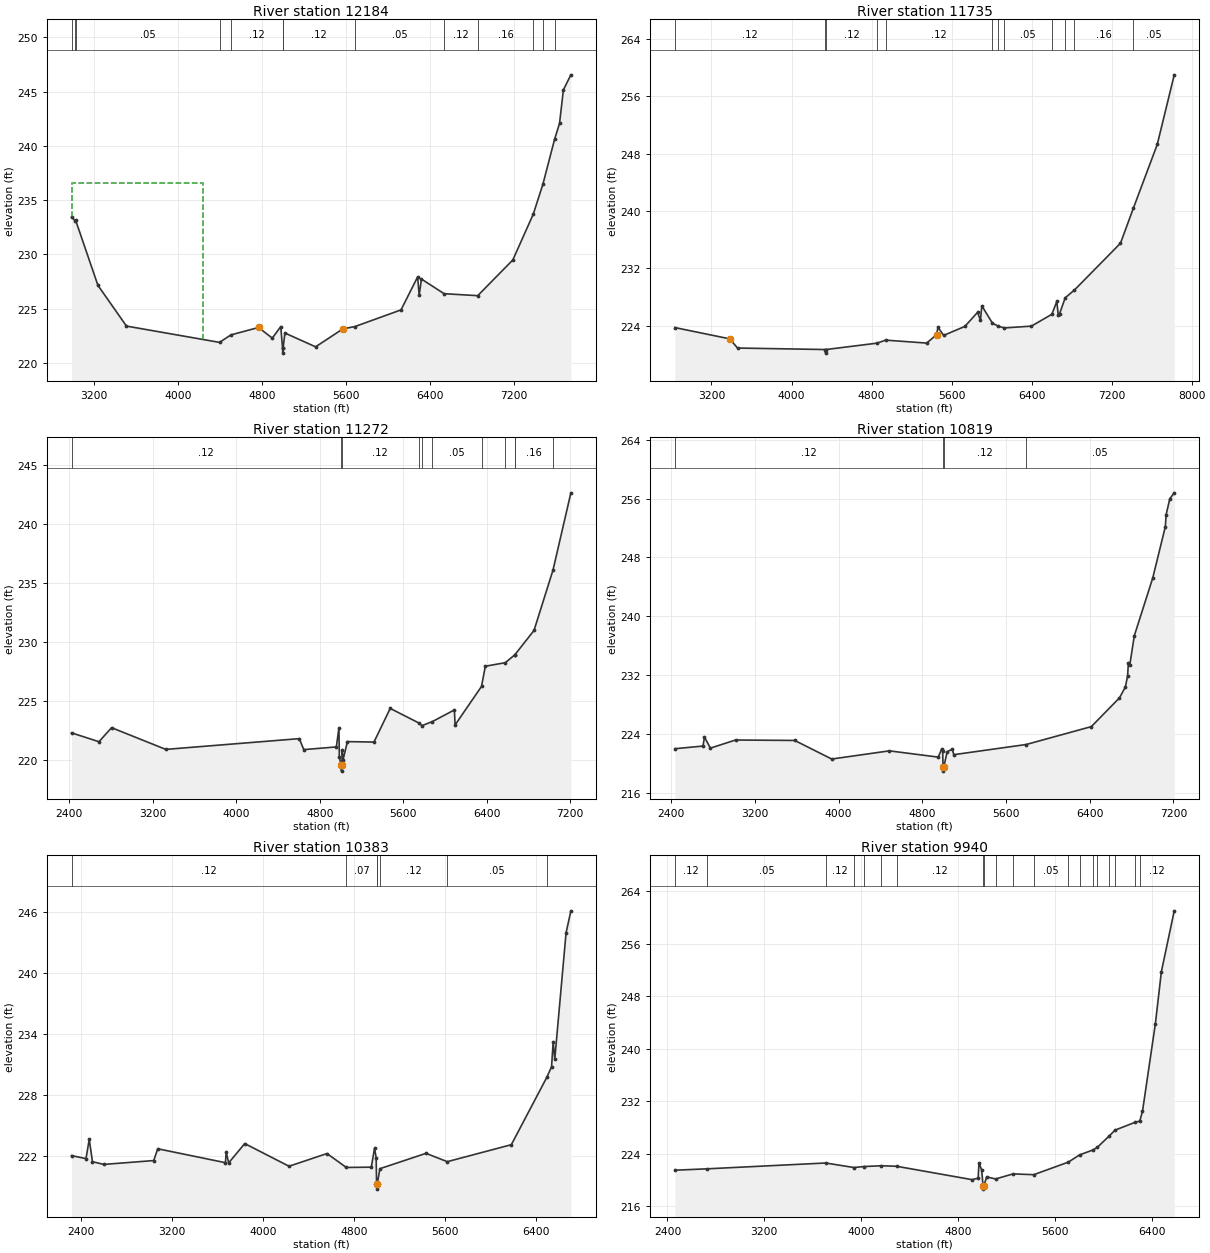
Type RM Length L Ch R = 1 ,12184   ,449,449,449
BEGIN DESCRIPTION:
UNT 016 IN BOCR 22.0
END DESCRIPTION:
XS GIS Cut Line= 3
      3694199.63     10593210.19       3696514.3     10593467.54
      3697799.62     10591410.16
#Sta/Elev= 30
  2986.6  233.44    3023   233.1  3026.6  233.13  3238.1  227.16  3509.8  223.41
  4395.7  221.91  4505.1   222.6  4767.5  223.28  4898.3   222.3  4978.8  223.36
  4995.9  221.42  4998.7  220.92  5001.9  221.42  5018.4  222.77  5310.7   221.5
  5571.8  223.16  5683.4  223.36  6123.9   224.9  6281.9  227.93  6297.3  226.26
  6318.5  227.74  6534.5  226.39  6854.4  226.21  7188.8   229.5  7383.5  233.72
  7474.5  236.45  7586.1   240.6  7633.5  242.07    7670  245.15  7741.4  246.54
#Mann= 13 ,-1 , 0
  2986.6     .05       0    3023     .12       0  3026.6     .05       0
  4395.7     .07       0  4505.1     .12       0  4995.9     .07       0
  5001.9     .12       0  5683.4     .05       0  6534.5     .12       0
  6854.4     .16       0  7383.5     .05       0  7474.5     .16       0
  7586.1     .05       0
#XS Ineff= 2 , 0
         4239.77   236.6
Permanent Ineff=
       F       F
Bank Sta=4767.5,5571.8
XS Rating Curve= 0 ,0
Exp/Cntr=0.3,0.1

Type RM Length L Ch R = 1 ,11735   ,463,463,463
BEGIN DESCRIPTION:
UNT 016 IN BOCR 21.0
END DESCRIPTION:
XS GIS Cut Line= 3
      3694799.61     10594760.19      3696599.61     10593560.19
      3698599.64     10591560.16
#Sta/Elev= 30
  2834.2  223.76  3382.5  222.19  3460.7  220.91    4338   220.7  4340.8   220.2
    4344   220.7  4855.7  221.59  4940.7  222.01  5351.1   221.6  5450.1  222.77
  5464.2   223.8  5520.8  222.67  5732.9  223.92  5860.2  225.89  5888.5  224.78
  5902.6  226.79  6008.9  224.37  6068.5  223.94  6128.7  223.71  6397.6  223.96
  6602.6  225.61  6652.2   227.4  6666.3  225.54  6680.4  225.72  6736.1  227.91
  6828.2  228.99  7288.6  235.51  7418.4  240.43  7656.2  249.27    7826  258.97
#Mann= 12 ,-1 , 0
  2834.2     .12       0    4338     .07       0    4344     .12       0
  4855.7     .07       0  4940.7     .12       0  6008.9     .05       0
  6068.5     .07       0  6128.7     .05       0  6602.6     .16       0
  6736.1     .12       0  6828.2     .16       0  7418.4     .05       0
Bank Sta=3382.5,5450.1
XS Rating Curve= 0 ,0
Exp/Cntr=0.3,0.1

Type RM Length L Ch R = 1 ,11272   ,453,453,453
BEGIN DESCRIPTION:
UNT 016 IN BOCR 20.0
END DESCRIPTION:
XS GIS Cut Line= 3
       3695449.6      10595560.2      3697049.61     10593560.19
      3698599.59     10591960.21
#Sta/Elev= 30
  2419.9   222.3  2683.2  221.55  2804.1  222.74  3323.6   220.9  4604.2  221.81
  4647.4  220.88  4959.6  221.11  4984.6  222.73  4988.2  220.23  5006.4  219.56
  5009.1  219.06  5012.4  219.56  5016.5  220.83  5023.5     220  5065.9  221.56
  5320.6  221.52  5476.2  224.37  5750.1  223.14  5780.8  222.91  5881.7  223.26
  6091.5  224.24  6098.5  222.97  6351.7  226.23  6388.4  227.94  6579.7  228.24
  6669.2  228.89  6671.4  228.91  6855.3  230.97  7037.3  236.08  7208.8  242.62
#Mann= 11 ,-1 , 0
  2419.9     .12       0  5006.4     .07       0  5012.4     .12       0
  5750.1     .05       0  5780.8     .12       0  5881.7     .05       0
  6351.7     .12       0  6579.7     .16       0  6669.2     .12       0
  6671.4     .16       0  7037.3     .05       0
Bank Sta=5006.4,5012.4
XS Rating Curve= 0 ,0
Exp/Cntr=0.3,0.1

Type RM Length L Ch R = 1 ,10819   ,436,436,436
BEGIN DESCRIPTION:
UNT 016 IN BOCR 19.0
END DESCRIPTION:
XS GIS Cut Line= 3
       3695699.6      10595360.2      3697499.61     10593560.19
      3699049.64     10591960.16
#Sta/Elev= 30
  2434.9  222.07  2703.6  222.43  2717.8  223.64  2774.3  222.15  3014.7  223.25
  3580.4  223.19    3934  220.67  4485.5  221.78  4952.2  220.93    4984  221.99
  4994.5  221.78  4998.7  219.53  5001.5  219.03  5004.7  219.53    5037  221.65
  5086.6  222.01  5100.7  221.26  5792.9  222.64    6416  225.07  6684.8  228.97
  6741.4  230.45  6762.6  231.97  6769.7  233.74  6783.8  233.47  6826.3  237.38
    7003  245.24  7123.4   252.2  7130.4   253.8  7165.8  255.97  7208.2  256.77
#Mann= 4 ,-1 , 0
  2434.9     .12       0  4998.7     .07       0  5004.7     .12       0
  5792.9     .05       0
Bank Sta=4998.7,5004.7
XS Rating Curve= 0 ,0
Exp/Cntr=0.3,0.1

Type RM Length L Ch R = 1 ,10383   ,443,443,443
BEGIN DESCRIPTION:
UNT 016 IN BOCR 18.0
END DESCRIPTION:
XS GIS Cut Line= 3
      3695949.61     10595410.19      3697949.61     10593610.19
      3699149.62     10592410.18
#Sta/Elev= 30
  2318.3  222.07  2445.7  221.77  2474.1  223.67  2502.5  221.47  2601.2   221.2
  3040.7  221.58  3075.8  222.74  3670.8  221.37  3677.5  222.43  3699.2  221.35
  3840.4  223.25  4229.8  221.02  4563.2  222.27  4732.9   220.9  4952.6  220.93
    4981   222.8  4995.2  221.85  4998.9  219.27  5001.7  218.77  5004.9  219.27
  5027.9  220.78  5433.3  222.29    5620  221.47  6182.8  223.14  6494.4  229.76
  6536.4  230.81  6550.5  233.25  6564.7  231.57  6663.7  243.97  6706.1  246.14
#Mann= 7 ,-1 , 0
  2318.3     .12       0  4732.9     .07       0  4998.9     .07       0
  5004.9     .07       0  5027.9     .12       0    5620     .05       0
  6494.4     .12       0
Bank Sta=4998.9,5004.9
XS Rating Curve= 0 ,0
Exp/Cntr=0.3,0.1

Type RM Length L Ch R = 1 ,9940    ,1671,1671,1671
BEGIN DESCRIPTION:
UNT 016 IN BOCR 17.0
END DESCRIPTION:
XS GIS Cut Line= 3
      3696399.62     10595260.18      3698399.61     10593660.19
      3699599.62     10592660.18
#Sta/Elev= 30
  2461.3  221.49  2725.9   221.7    3707  222.59  3939.3   221.9  4023.5  222.05
    4166  222.17  4292.6  222.09  4916.1  220.05  4965.7  220.29  4972.1  222.61
  4994.5  221.53  5005.9  219.11  5008.7  218.61  5011.9  219.11  5036.2  220.47
  5109.8  220.16  5253.7  220.93  5424.5  220.81  5709.9  222.72  5802.7  223.82
  5915.6  224.59  5949.1  224.97  6048.6  226.72  6095.5  227.59  6259.1  228.77
  6299.9  228.98  6322.3  230.45  6428.4  243.75  6478.5  251.74  6584.6  260.99
#Mann= 20 ,-1 , 0
  2461.3     .12       0  2725.9     .05       0    3707     .12       0
  3939.3     .07       0  4023.5     .12       0    4166     .05       0
  4292.6     .12       0  5005.9     .07       0  5011.9     .12       0
  5109.8     .07       0  5253.7     .12       0  5424.5     .05       0
  5709.9     .16       0  5802.7     .12       0  5915.6     .16       0
  5949.1     .12       0  6048.6     .16       0  6095.5     .12       0
  6259.1     .16       0  6299.9     .12       0
Bank Sta=5005.9,5011.9
XS Rating Curve= 0 ,0
Exp/Cntr=0.3,0.1

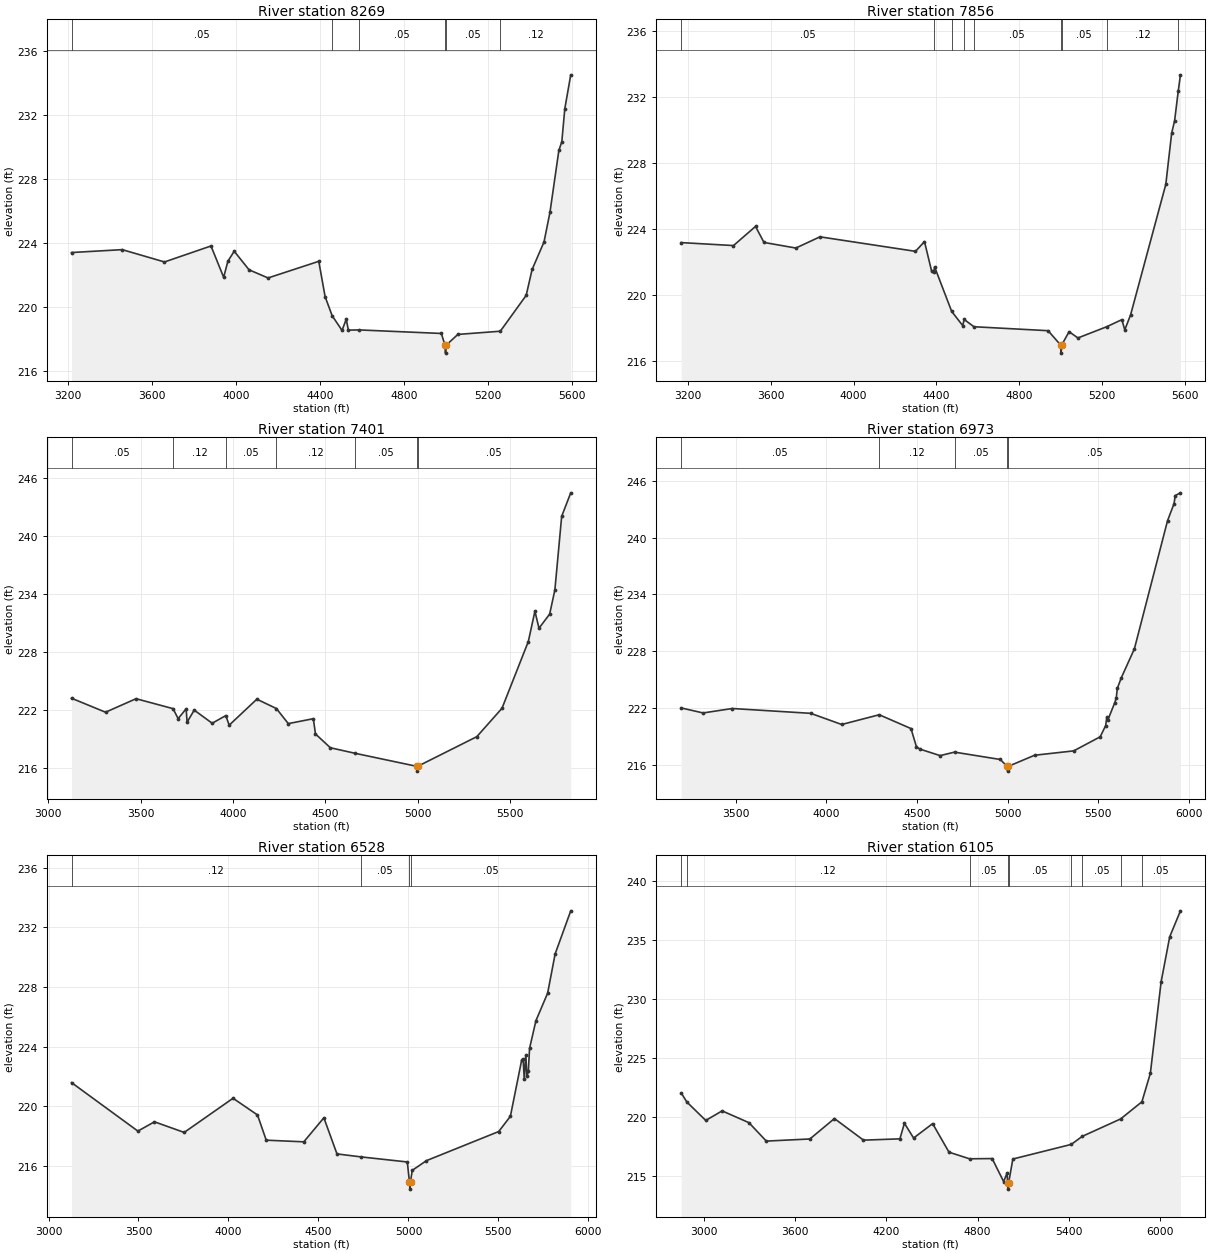
Type RM Length L Ch R = 1 ,8269    ,413,413,413
BEGIN DESCRIPTION:
UNT 016 IN BOCR 16.0
END DESCRIPTION:
XS GIS Cut Line= 3
      3698049.61     10594110.19      3699849.61     10594310.19
      3700249.63     10593910.16
#Sta/Elev= 30
  3218.1  223.42  3459.6   223.6  3660.8  222.83  3882.2  223.83  3942.5  221.87
  3962.7  222.88  3992.8   223.5  4063.3  222.34  4153.8  221.83  4395.3  222.87
  4425.5  220.66    4459  219.47    4506  218.55  4526.1  219.25  4536.2  218.57
  4588.9  218.58  4978.9  218.36    4996  217.63  4998.7  217.13    5002  217.63
  5057.5   218.3  5259.6   218.5  5382.7  220.74    5411  222.36  5467.6  224.08
  5495.9  225.93  5538.3   229.8  5552.4  230.35  5566.6  232.41  5594.9  234.53
#Mann= 6 ,-1 , 0
  3218.1     .05       0    4459     .07       0  4588.9     .05       0
    4996     .03       0    5002     .05       0  5259.6     .12       0
Bank Sta=4996,5002
XS Rating Curve= 0 ,0
Exp/Cntr=0.3,0.1

Type RM Length L Ch R = 1 ,7856    ,455,455,455
BEGIN DESCRIPTION:
UNT 016 IN BOCR 15.0
END DESCRIPTION:
XS GIS Cut Line= 3
      3698249.58     10594260.18      3700049.61     10594660.19
      3700449.59      10594260.2
#Sta/Elev= 30
  3168.1  223.15  3420.4  222.97  3526.7  224.13  3567.6  223.16  3721.3  222.82
  3837.8   223.5  4298.8  222.62  4342.3  223.21  4376.9  221.41  4387.9  221.38
    4391  221.68  4473.5  218.98  4526.7  218.12    4534  218.49  4580.9  218.05
    4939  217.81  4998.8  216.95  5001.5  216.45  5004.8  216.95  5040.3  217.75
  5082.7  217.37  5221.8  218.05  5294.9  218.48    5309  217.86  5337.3  218.78
    5507  226.68  5535.3  229.79  5549.4  230.53  5567.2  232.35  5577.7  233.32
#Mann= 9 ,-1 , 0
  3168.1     .05       0  4387.9     .12       0  4473.5     .07       0
    4534     .12       0  4580.9     .05       0  4998.8     .03       0
  5004.8     .05       0  5221.8     .12       0  5567.2     .05       0
Bank Sta=4998.8,5004.8
XS Rating Curve= 0 ,0
Exp/Cntr=0.3,0.1

Type RM Length L Ch R = 1 ,7401    ,428,428,428
BEGIN DESCRIPTION:
UNT 016 IN BOCR 14.0
END DESCRIPTION:
XS GIS Cut Line= 3
      3698449.63     10594660.19      3700249.61     10595060.19
      3700949.59      10594560.2
#Sta/Elev= 30
  3125.4  223.18  3309.8  221.73    3475  223.13  3675.4   222.1  3702.9  221.07
  3746.4  222.08  3751.5   220.7    3790  221.95  3887.3  220.59    3961  221.38
  3979.5  220.39  4129.3  223.08  4235.3  222.11  4299.6  220.55  4435.3  221.06
  4446.8  219.48  4527.5  218.05  4658.3  217.49  4994.6  216.13  4997.3  215.63
  5000.6  216.13  5320.8   219.2  5457.2  222.14  5599.7  229.05  5635.4  232.19
  5657.5  230.43  5715.2  231.89  5743.5  234.39  5780.4  242.02  5829.5  244.45
#Mann= 7 ,-1 , 0
  3125.4     .05       0  3675.4     .12       0    3961     .05       0
  4235.3     .12       0  4658.3     .05       0  4994.6     .03       0
  5000.6     .05       0
Bank Sta=4994.6,5000.6
XS Rating Curve= 0 ,0
Exp/Cntr=0.3,0.1

Type RM Length L Ch R = 1 ,6973    ,445,445,445
BEGIN DESCRIPTION:
UNT 016 IN BOCR 13.0
END DESCRIPTION:
XS GIS Cut Line= 3
      3698699.64     10595210.19      3700499.61     10595410.19
      3700999.59     10594610.23
#Sta/Elev= 30
  3198.7     222  3319.4  221.47  3480.4  221.94    3913  221.43  4084.1  220.25
  4291.2  221.28  4466.4  219.82  4496.6  217.89  4516.7  217.64  4627.4  216.96
  4706.5  217.33  4959.4  216.55  4996.7  215.82  4999.4  215.32  5002.7  215.82
  5148.3     217  5364.1  217.46  5510.3  218.95  5540.4  220.13  5546.9  221.04
  5552.8  220.74  5589.3  222.49  5598.8  223.01  5604.7  224.06  5625.9  225.15
    5699  228.25  5881.8  241.79  5917.8   243.6  5924.3  244.45  5953.1  244.74
#Mann= 5 ,-1 , 0
  3198.7     .05       0  4291.2     .12       0  4706.5     .05       0
  4996.7     .03       0  5002.7     .05       0
Bank Sta=4996.7,5002.7
XS Rating Curve= 0 ,0
Exp/Cntr=0.3,0.1

Type RM Length L Ch R = 1 ,6528    ,423,423,423
BEGIN DESCRIPTION:
UNT 016 IN BOCR 12.0
END DESCRIPTION:
XS GIS Cut Line= 3
      3698899.59     10596210.19      3700699.61     10595810.19
      3701249.62     10595060.17
#Sta/Elev= 30
  3127.8  221.59  3496.6  218.34  3588.8  218.96    3754  218.25  4025.4  220.54
  4161.2  219.42  4209.8  217.73  4418.6  217.62    4530  219.23  4602.9  216.81
  4736.3  216.61  4993.7  216.27  5005.4  214.95  5008.1  214.45  5011.4  214.95
  5021.3  215.71  5100.2  216.36  5501.6  218.31  5566.4  219.33    5629  223.09
  5637.4  223.17  5643.6   221.8  5652.1  223.45  5658.3  222.01  5666.2  222.35
  5672.9  223.88  5708.4  225.74  5773.3  227.58    5815  230.21  5901.8   233.1
#Mann= 4 ,-1 , 0
  3127.8     .12       0  4736.3     .05       0  5005.4     .03       0
  5011.4     .05       0
Bank Sta=5005.4,5011.4
XS Rating Curve= 0 ,0
Exp/Cntr=0.3,0.1

Type RM Length L Ch R = 1 ,6105    ,444,444,444
BEGIN DESCRIPTION:
UNT 016 IN BOCR 11.0
END DESCRIPTION:
XS GIS Cut Line= 3
      3698899.57      10596960.2      3700899.61     10596160.19
      3701699.63     10595360.17
#Sta/Elev= 30
    2850  222.06  2887.3  221.29  3011.6  219.73  3119.3  220.54  3295.7  219.54
  3410.1  217.98  3696.9  218.16  3858.4  219.89  4049.6  218.06  4289.2  218.17
  4318.8  219.49  4379.4  218.24  4504.6  219.46  4612.3  217.04  4747.3  216.48
  4896.4   216.5  4971.8  214.55  4994.7  215.27  4998.4  214.41  5001.2  213.91
  5004.4  214.41  5032.4  216.46    5417   217.7  5489.2  218.38  5742.1  219.86
  5881.8  221.31  5937.5  223.73  6008.2  231.47  6064.8  235.29  6135.5  237.49
#Mann= 9 ,-1 , 0
    2850     .05       0  2887.3     .12       0  4747.3     .05       0
  4998.4     .03       0  5004.4     .05       0    5417     .07       0
  5489.2     .05       0  5742.1     .12       0  5881.8     .05       0
Bank Sta=4998.4,5004.4
XS Rating Curve= 0 ,0
Exp/Cntr=0.3,0.1

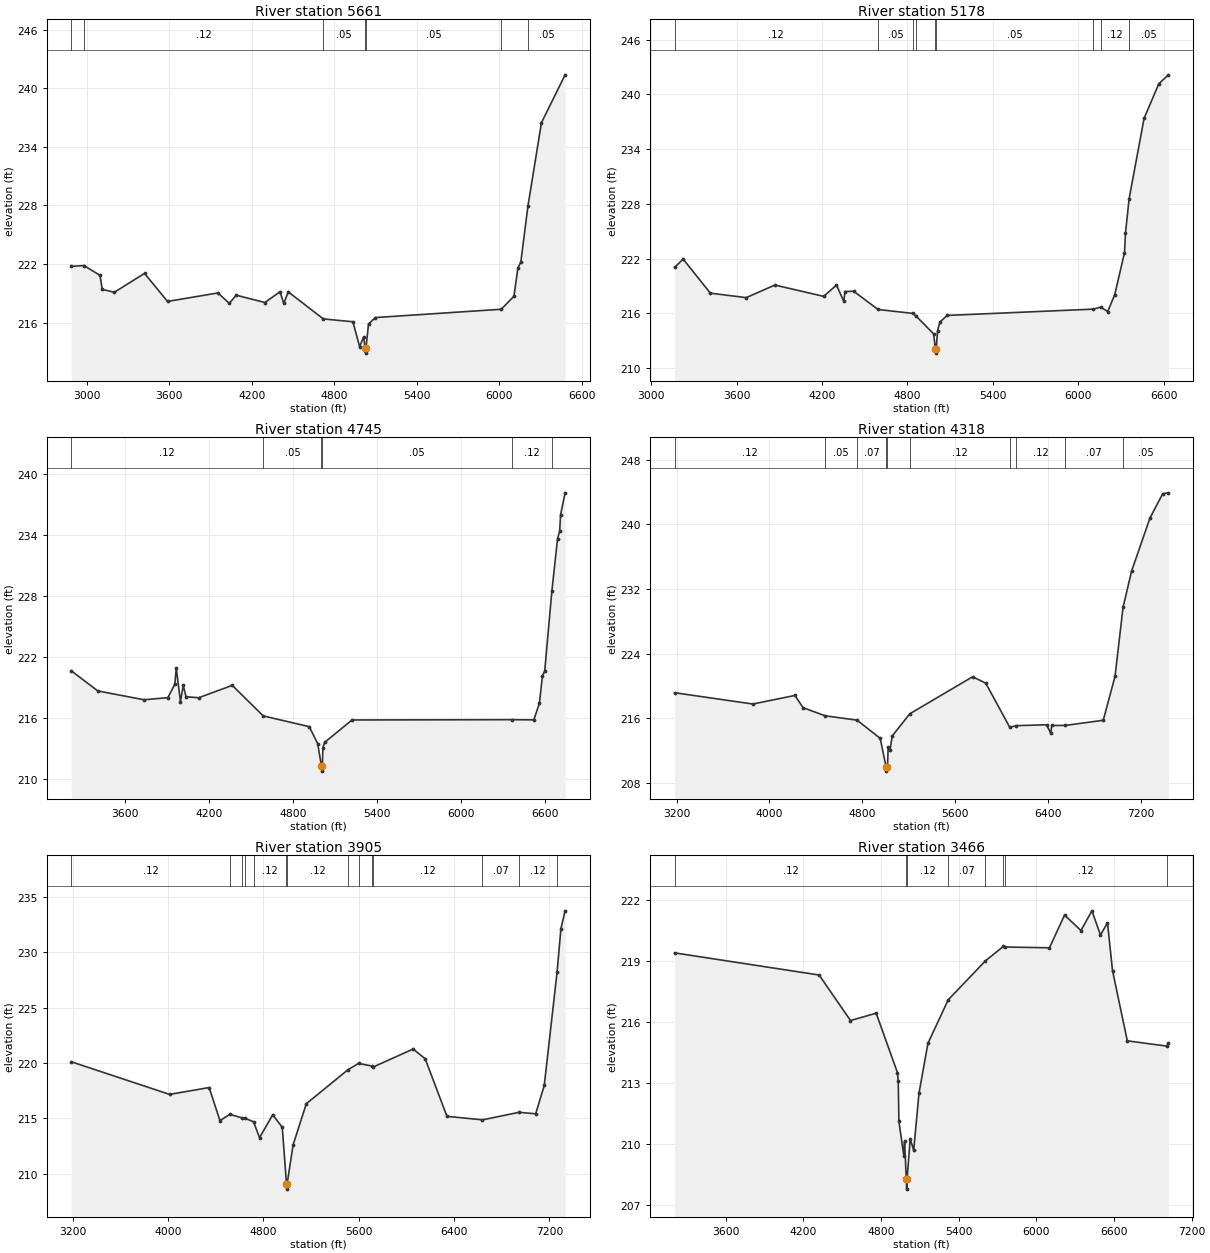
Type RM Length L Ch R = 1 ,5661    ,483,483,483
BEGIN DESCRIPTION:
UNT 016 IN BOCR 10.0
END DESCRIPTION:
XS GIS Cut Line= 3
      3699099.56      10597160.2      3701099.61     10596560.19
       3701999.6      10595360.2
#Sta/Elev= 30
    2889  221.77  2981.8  221.85  3097.9  220.85  3114.4  219.41  3202.3  219.12
  3421.5  221.05  3588.6  218.18  3954.8  219.05  4037.5  217.98  4087.1  218.82
  4295.9  218.07  4405.5  219.17  4433.3  217.97  4465.5  219.16  4720.7  216.39
  4935.3   216.1  4984.4  213.55  5013.6  214.56  5024.1  213.39  5026.9  212.89
  5030.1  213.39    5049  215.88    5099  216.53  6012.9  217.38  6105.2  218.71
  6134.4  221.62  6155.2   222.2  6207.5  227.98  6305.2  236.47  6477.1  241.37
#Mann= 7 ,-1 , 0
    2889     .05       0  2981.8     .12       0  4720.7     .05       0
  5024.1     .03       0  5030.1     .05       0  6012.9     .12       0
  6207.5     .05       0
Bank Sta=5024.1,5030.1
XS Rating Curve= 0 ,0
Exp/Cntr=0.3,0.1

Type RM Length L Ch R = 1 ,5178    ,433,433,433
BEGIN DESCRIPTION:
UNT 016 IN BOCR 9.0
END DESCRIPTION:
XS GIS Cut Line= 3
      3699599.66     10597060.18      3701399.61     10596860.19
      3702199.62     10595410.17
#Sta/Elev= 30
  3164.8  221.04  3225.1  221.95  3416.3  218.22  3667.8  217.73  3869.1  219.11
  4211.2  217.87  4301.7   219.1    4352  217.35  4362.1   218.4  4422.4  218.43
  4593.3  216.43  4838.6     216  4860.6  215.71  4983.9  213.75  4995.7  212.15
  4998.4  211.65  5001.7  212.15  5011.3  214.11  5027.4  215.05  5078.6  215.78
  6105.4  216.47  6157.1  216.69  6205.6   216.2    6255  218.05  6323.5  222.66
  6330.5  224.82  6356.1  228.58  6461.1  237.37  6564.2  241.16  6631.9  242.14
#Mann= 9 ,-1 , 0
  3164.8     .12       0  4593.3     .05       0  4838.6     .07       0
  4860.6     .05       0  4995.7     .03       0  5001.7     .05       0
  6105.4     .07       0  6157.1     .12       0  6356.1     .05       0
Bank Sta=4995.7,5001.7
XS Rating Curve= 0 ,0
Exp/Cntr=0.3,0.1

Type RM Length L Ch R = 1 ,4745    ,427,427,427
BEGIN DESCRIPTION:
UNT 016 IN BOCR 8.0
END DESCRIPTION:
XS GIS Cut Line= 3
      3699799.59     10597210.19      3701599.61     10597210.19
      3702249.61     10595610.19
#Sta/Elev= 30
  3213.5  220.63  3403.5  218.64  3733.5  217.77  3903.5  217.98  3953.5  219.31
  3963.5   220.9  3993.5   217.6  4013.5  219.18  4033.5  218.07  4123.5  217.97
  4363.5  219.19  4584.8  216.18  4913.5  215.12  4973.5  213.45  5000.5  211.24
  5003.3  210.74  5006.5  211.24    5011  213.06  5022.9  213.57  5218.6  215.78
    6361  215.81    6517  215.79    6557  217.43  6578.6  220.14  6594.6  220.57
  6645.7  228.45  6686.5  233.65  6701.7  234.37  6708.1     236  6740.5  238.16
#Mann= 6 ,-1 , 0
  3213.5     .12       0  4584.8     .05       0  5000.5     .03       0
  5006.5     .05       0    6361     .12       0  6645.7     .05       0
Bank Sta=5000.5,5006.5
XS Rating Curve= 0 ,0
Exp/Cntr=0.3,0.1

Type RM Length L Ch R = 1 ,4318    ,413,413,413
BEGIN DESCRIPTION:
UNT 016 IN BOCR 7.0
END DESCRIPTION:
XS GIS Cut Line= 3
      3699999.65     10597360.19      3701799.61     10597560.19
      3703199.58     10595560.23
#Sta/Elev= 30
  3182.9  219.17    3857  217.77  4219.2  218.83  4289.6  217.32  4479.9  216.31
  4754.5  215.77  4953.7  213.52  5004.5  209.96  5007.2  209.46  5010.5  209.96
  5016.2     210  5022.3  212.46  5037.1  212.04    5058  213.83  5208.3  216.56
  5748.6  221.14  5861.9  220.36  6069.1  214.89    6124  215.09  6385.9   215.2
  6422.1  214.15  6430.4  215.11  6548.6  215.12  6874.2  215.76  6975.3  221.19
  7044.4  229.73  7118.3  234.24  7276.6  240.81    7386  243.81  7435.2  243.92
#Mann= 10 ,-1 , 0
  3182.9     .12       0  4479.9     .05       0  4754.5     .07       0
  5004.5     .07       0  5010.5     .07       0  5208.3     .12       0
  6069.1     .07       0    6124     .12       0  6548.6     .07       0
  7044.4     .05       0
Bank Sta=5004.5,5010.5
XS Rating Curve= 0 ,0
Exp/Cntr=0.3,0.1

Type RM Length L Ch R = 1 ,3905    ,439,439,439
BEGIN DESCRIPTION:
UNT 016 IN BOCR 6.0
END DESCRIPTION:
XS GIS Cut Line= 3
      3700149.61     10597710.19      3701949.61     10597910.19
      3703149.63     10595910.15
#Sta/Elev= 30
  3187.6  220.11  4012.6  217.16  4344.7  217.78  4435.2  214.79    4519  215.36
  4619.3  215.04  4644.6     215  4717.2  214.69  4767.3  213.25  4877.9  215.32
  4958.4  214.18  4993.2   209.1  4995.9   208.6  4999.2   209.1  5049.2  212.61
    5160  216.32  5509.4  219.39    5598  219.96  5713.1  219.72  5721.3  219.64
    6056  221.26  6157.1  220.38  6339.8  215.18  6637.5  214.86  6944.1  215.54
  7084.2  215.41  7156.1  217.97  7263.4  228.19  7296.1  232.15  7331.1  233.75
#Mann= 14 ,-1 , 0
  3187.6     .12       0    4519     .07       0  4619.3     .12       0
  4644.6     .07       0  4717.2     .12       0  4993.2     .07       0
  4999.2     .12       0  5509.4     .07       0    5598     .12       0
  5713.1     .07       0  5721.3     .12       0  6637.5     .07       0
  6944.1     .12       0  7263.4     .05       0
Bank Sta=4993.2,4999.2
XS Rating Curve= 0 ,0
Exp/Cntr=0.3,0.1

Type RM Length L Ch R = 1 ,3466    ,479,479,479
BEGIN DESCRIPTION:
UNT 016 IN BOCR 5.0
END DESCRIPTION:
XS GIS Cut Line= 3
      3700299.61     10597910.19      3702099.61     10598310.19
      3702899.62     10596510.17
#Sta/Elev= 30
  3206.4  219.42    4323  218.33    4565  216.09  4763.5  216.45  4927.4  213.53
  4933.8  213.09  4938.9  211.13  4977.3  209.41  4982.4  210.14  4996.1  208.29
  4998.8  207.79  5002.1  208.29    5026  210.27    5053   209.7  5094.1  212.52
  5163.2  214.97  5319.7  217.11  5607.3  219.03  5746.1  219.74  5755.5  219.71
  6101.5  219.67  6217.8  221.28    6345  220.52  6429.2  221.49  6495.5   220.3
  6549.5   220.9  6588.5  218.54  6702.7  215.09  7007.6  214.83  7020.1  214.99
#Mann= 8 ,-1 , 0
  3206.4     .12       0  4996.1     .07       0  5002.1     .12       0
  5319.7     .07       0  5607.3     .12       0  5746.1     .07       0
  5755.5     .12       0  7007.6     .07       0
Bank Sta=4996.1,5002.1
XS Rating Curve= 0 ,0
Exp/Cntr=0.3,0.1