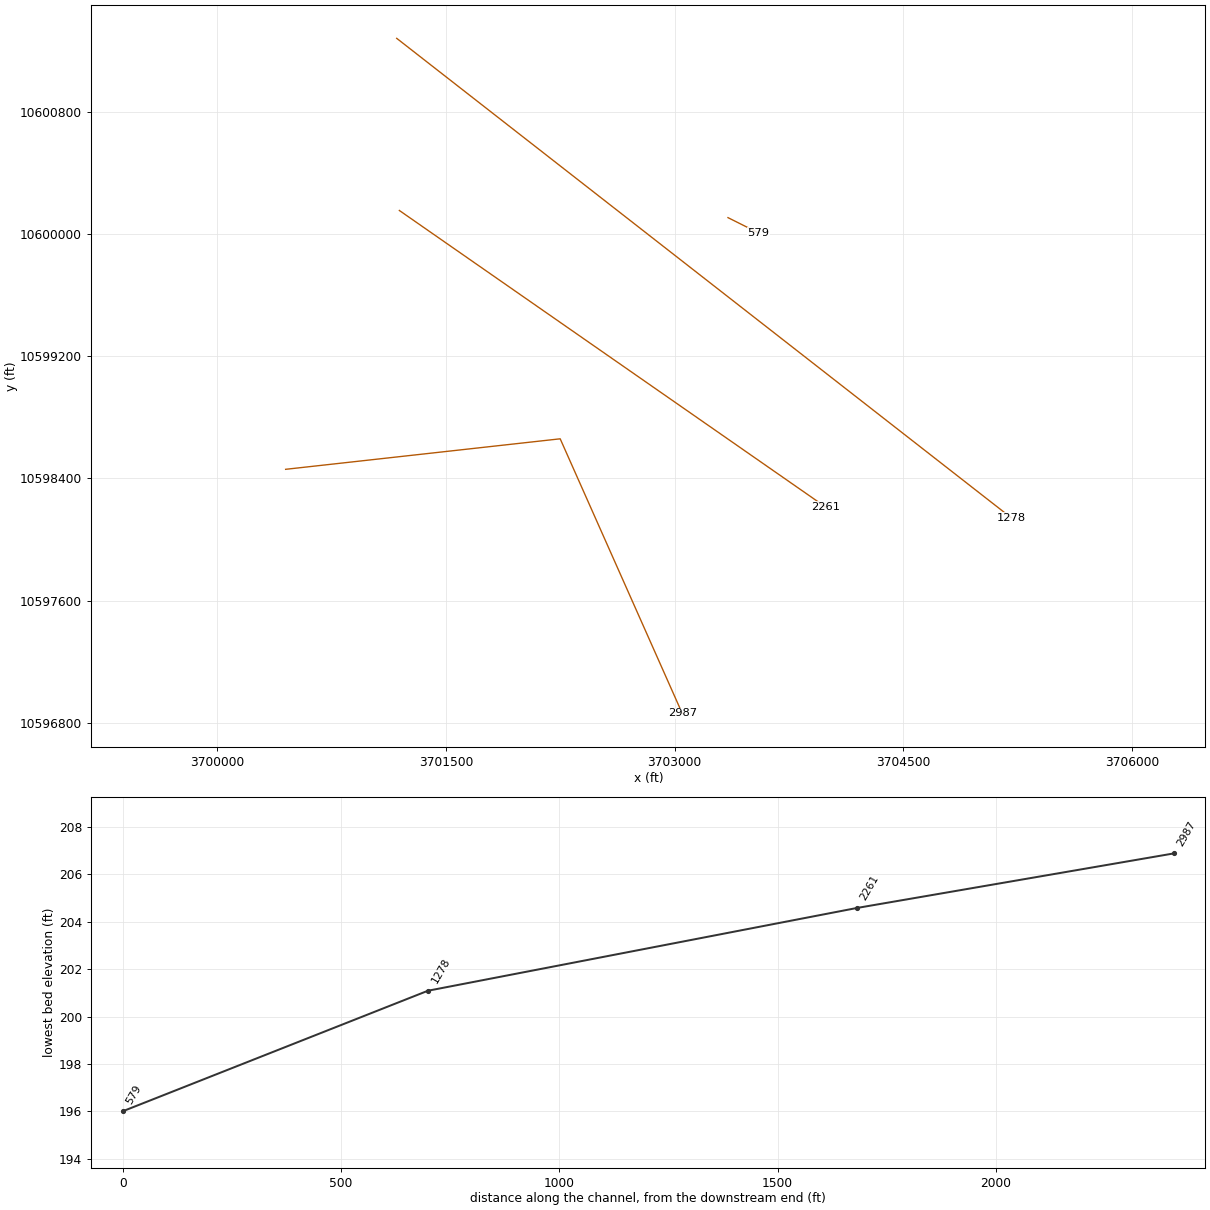
HEC-RAS study UNT 016 IN BOCR.prj: UNT 016 IN BOCR Base Level Engineering

--- UNT 016 IN BOCR.g01 (geometry) --- (continued)

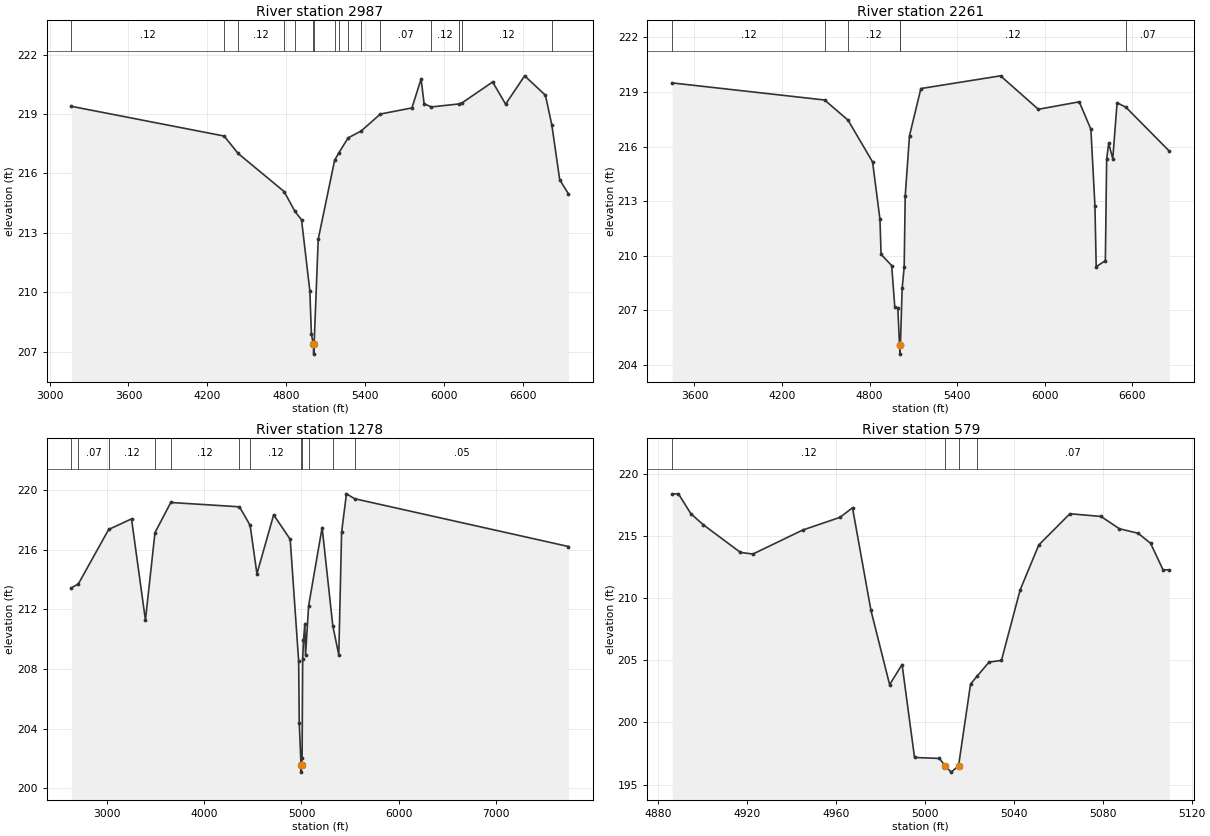
Type RM Length L Ch R = 1 ,2987    ,726,726,726
BEGIN DESCRIPTION:
UNT 016 IN BOCR 4.0
END DESCRIPTION:
XS GIS Cut Line= 3
      3700449.58     10598460.19      3702249.61     10598660.19
      3703049.62     10596860.17
#Sta/Elev= 30
  3165.8  219.39  4327.6  217.89  4434.1  217.01  4783.7  215.09    4866  214.09
  4916.5  213.66  4979.6  210.07  4991.3   207.9  5006.1  207.38  5008.8  206.88
  5012.1  207.38  5043.3  212.68  5168.2  216.67  5199.1  217.03  5271.1   217.8
  5369.1  218.14  5515.8     219  5755.9  219.31  5825.7  220.77  5848.9  219.52
  5904.2  219.36  6112.7  219.51  6138.6  219.57  6370.1  220.62  6468.6   219.5
  6613.6  220.93  6771.6  219.95  6820.5  218.44  6880.3  215.68  6946.7  214.97
#Mann= 16 ,-1 , 0
  3165.8     .12       0  4327.6     .07       0  4434.1     .12       0
  4783.7     .07       0    4866     .12       0  5006.1     .07       0
  5012.1     .12       0  5168.2     .07       0  5199.1     .12       0
  5271.1     .07       0  5369.1     .12       0  5515.8     .07       0
  5904.2     .12       0  6112.7     .07       0  6138.6     .12       0
  6820.5     .07       0
Bank Sta=5006.1,5012.1
XS Rating Curve= 0 ,0
Exp/Cntr=0.3,0.1

Type RM Length L Ch R = 1 ,2261    ,983,983,983
BEGIN DESCRIPTION:
UNT 016 IN BOCR 3.0
END DESCRIPTION:
XS GIS Cut Line= 2
      3701195.19     10600157.15      3703990.37     10598212.68
#Sta/Elev= 30
  3447.4   219.5  4491.4  218.56    4652  217.45    4820  215.15  4870.6  211.99
    4878  210.07  4950.9  209.45  4971.9  207.19  4992.8   207.1  5004.6  205.08
  5007.4  204.58  5010.6  205.08  5022.5   208.2  5036.4  209.35  5043.4  213.27
  5072.9   216.6  5150.8  219.19  5696.3  219.89  5955.5  218.05  6235.7  218.46
  6315.5  216.95  6343.1  212.75  6351.8  209.39  6414.6  209.72  6423.4  215.29
  6437.3  216.18  6465.3  215.33  6494.9  218.41  6555.6  218.16  6852.4  215.75
#Mann= 6 ,-1 , 0
  3447.4     .12       0  4491.4     .07       0    4652     .12       0
  5004.6     .07       0  5010.6     .12       0  6555.6     .07       0
Bank Sta=5004.6,5010.6
XS Rating Curve= 0 ,0
Exp/Cntr=0.3,0.1

Type RM Length L Ch R = 1 ,1278    ,699,699,699
BEGIN DESCRIPTION:
UNT 016 IN BOCR 2.0
END DESCRIPTION:
XS GIS Cut Line= 2
      3701177.83     10601285.63      3705205.64     10598143.24
#Sta/Elev= 30
  2635.2  213.44  2706.5   213.7    3018  217.35  3253.1  218.06  3396.1  211.28
  3494.4  217.14  3656.6  219.16  4362.7  218.87  4472.1  217.63  4542.1  214.38
    4714  218.33  4884.1  216.69  4970.9  208.53  4977.2  204.38    4995  201.59
  4997.8  201.09    5001  201.59  5006.2  202.07  5012.5  208.65  5020.6  209.94
  5034.6  211.02  5041.5  208.93  5073.4  212.24  5212.2  217.48  5321.5  210.91
  5383.4  208.95  5412.3  217.17  5462.1  219.74  5547.2  219.41  7743.8  216.21
#Mann= 12 ,-1 , 0
  2635.2     .12       0  2706.5     .07       0    3018     .12       0
  3494.4     .07       0  3656.6     .12       0  4362.7     .07       0
  4472.1     .12       0    4995     .07       0    5001     .12       0
  5073.4     .07       0  5321.5     .12       0  5547.2     .05       0
Bank Sta=4995,5001
XS Rating Curve= 0 ,0
Exp/Cntr=0.3,0.1

Type RM Length L Ch R = 1 ,579     ,0,0,0
BEGIN DESCRIPTION:
UNT 016 IN BOCR 1.0
END DESCRIPTION:
XS GIS Cut Line= 3
      3703349.61     10600110.19      3703449.61     10600060.19
      3703549.61     10600010.19
#Sta/Elev= 30
  4886.3  218.38  4889.1  218.38  4894.7  216.78  4900.3  215.89    4917  213.67
  4922.6  213.54    4945  215.47  4961.8  216.49  4967.4  217.26  4975.7  209.01
  4984.1  203.04  4989.7  204.66  4995.3  197.19  5006.5  197.11  5009.1  196.51
  5011.8  196.01  5015.1  196.51  5020.5  203.09  5023.5  203.73  5028.8  204.85
  5034.4  204.99  5042.8  210.65  5051.2  214.27  5065.2  216.78  5079.2  216.56
  5087.5  215.57  5095.9  215.21  5101.5   214.4  5107.1  212.27  5109.9  212.27
#Mann= 4 ,-1 , 0
  4886.3     .12       0  5009.1     .07       0  5015.1     .12       0
  5023.5     .07       0
Bank Sta=5009.1,5015.1
XS Rating Curve= 0 ,0
Exp/Cntr=0.3,0.1

Chan Stop Cuts=-1
Use User Specified Reach Order=0
Composite Channel Slope=5