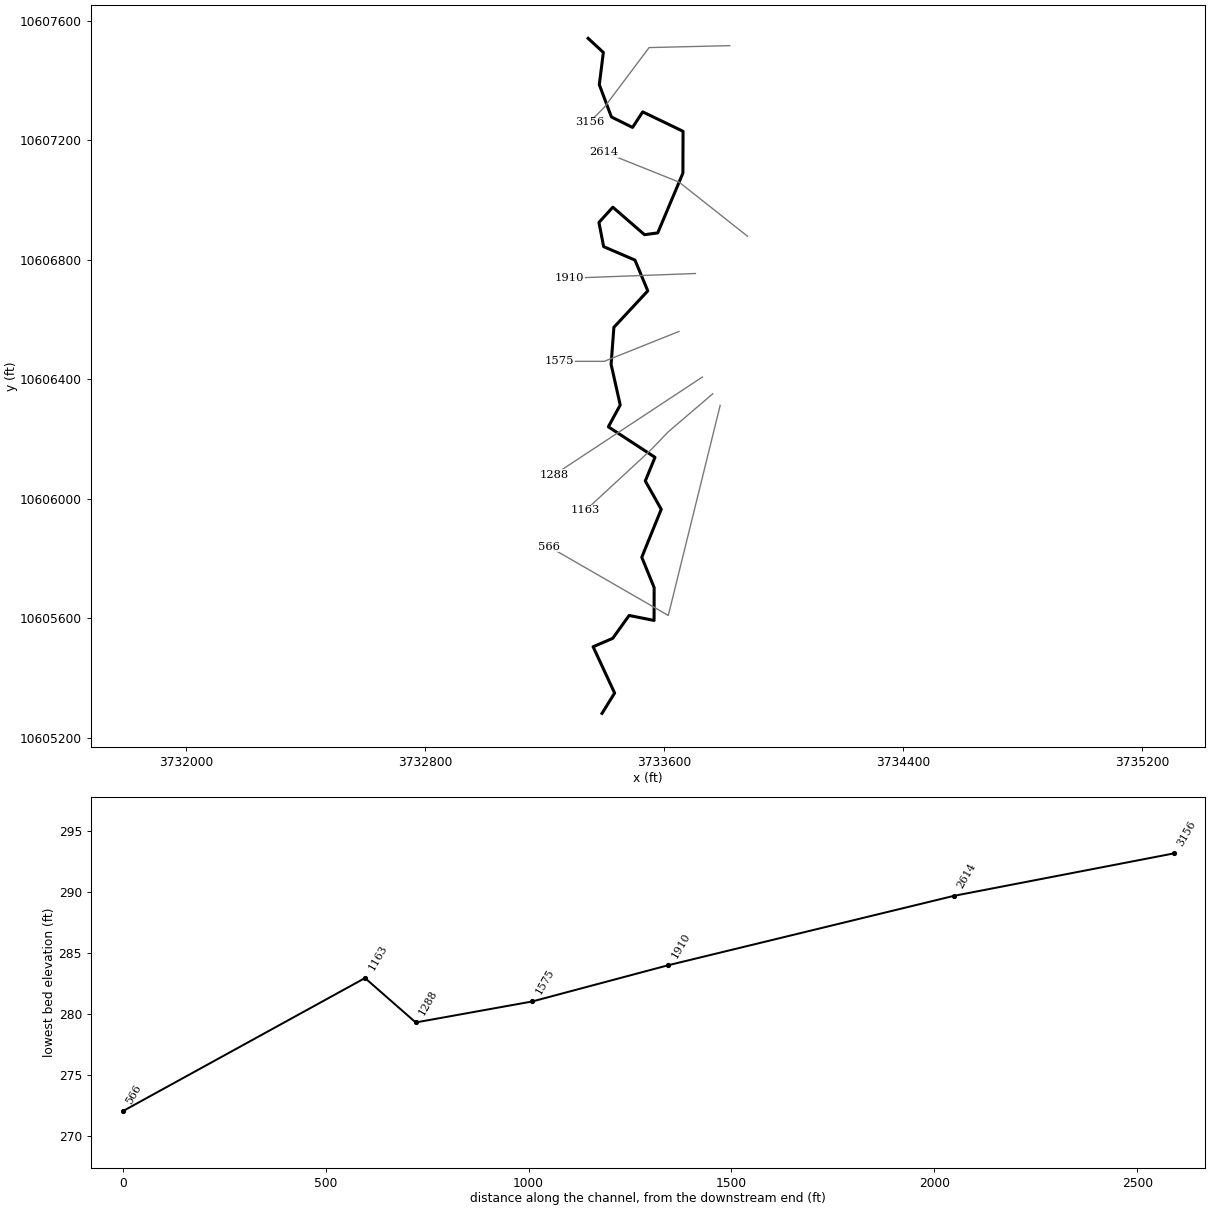
--- UNT 019 IN BOCR.prj (project) ---

Proj Title=UNT 019 IN BOCR Base Level Engineering
Current Plan=p01
Default Exp/Contr=0.3,0.1
English Units
Geom File=g01
Flow File=f01
Plan File=p01
Y Axis Title=Elevation
X Axis Title(PF)=Main Channel Distance
X Axis Title(XS)=Station
BEGIN DESCRIPTION:
UNT 019 IN BOCR
END DESCRIPTION:
DSS Export Rating Curves= 0
DSS Export Rating Curve Sorted= 0
DSS Export Volume Flow Curves= 0
DXF OffsetX= 0
DXF OffsetY= 0
DXF ScaleX= 1
DXF ScaleY= 10

--- UNT 019 IN BOCR.p01 (plan) ---

Plan Title=Multiple Run
Short Identifier=Multiple
Geom File=g01
Flow File=f01
Subcritical Flow
K Sum by GR= 0
Std Step Tol= 0.01
Critical Tol= 0.01
Num of Std Step Trials= 20
Max Error Tol= 0.3
Flow Tol Ratio= 0.001
Split Flow NTrial= 30
Split Flow Tol= 0.02
Split Flow Ratio= 0.02
Log Output Level= 0
Friction Slope Method= 1
Unsteady Friction Slope Method= 2
Unsteady Bridges Friction Slope Method= 1
Parabolic Critical Depth
Global Vel Dist=  1 , 1 , 1
Global Log Level= 0
CheckData=True
Encroach Param= -1, 0, 0, 0
BEGIN DESCRIPTION:
Multiple Run
END DESCRIPTION:

--- UNT 019 IN BOCR.f01 (steady flow) ---

Flow Title=Multiple
Program Version=4.10
Number of Profiles= 7
Profile Names=10-year,25-year,50-year,1pct_min,100-year,1pct_plu,500-year
River Rch & RM=UNT 019 IN BOCR,Reach-1         ,3156
     292     375     440     380     514     695     704
Boundary for River Rch & Prof#=UNT 019 IN BOCR,Reach-1         , 1
Up Type= 0
Dn Type= 3
Dn Slope=0.018
Boundary for River Rch & Prof#=UNT 019 IN BOCR,Reach-1         , 2
Up Type= 0
Dn Type= 3
Dn Slope=0.018
Boundary for River Rch & Prof#=UNT 019 IN BOCR,Reach-1         , 3
Up Type= 0
Dn Type= 3
Dn Slope=0.018
Boundary for River Rch & Prof#=UNT 019 IN BOCR,Reach-1         , 4
Up Type= 0
Dn Type= 3
Dn Slope=0.018
Boundary for River Rch & Prof#=UNT 019 IN BOCR,Reach-1         , 5
Up Type= 0
Dn Type= 3
Dn Slope=0.018
Boundary for River Rch & Prof#=UNT 019 IN BOCR,Reach-1         , 6
Up Type= 0
Dn Type= 3
Dn Slope=0.018
Boundary for River Rch & Prof#=UNT 019 IN BOCR,Reach-1         , 7
Up Type= 0
Dn Type= 3
Dn Slope=0.018
DSS Import GetInterval= 0
DSS Import GetPeak= 0
DSS Import FillOption= 0

--- UNT 019 IN BOCR.g01 (geometry) ---

Geom Title=Existing Conditions
Program Version=4.10

River Reach=UNT 019 IN BOCR ,Reach-1
Reach XY= 30
      3733345.51     10607541.13       3733396.5       10607494.
        3733383.       10607386.       3733423.5       10607278.
      3733494.25       10607243.      3733528.25       10607295.
      3733663.25       10607230.      3733662.75       10607090.
       3733578.5       10606890.      3733534.25       10606884.
      3733428.25       10606976.      3733381.75       10606925.
       3733397.5       10606844.      3733502.25       10606799.
      3733545.25       10606696.      3733431.75       10606574.
       3733422.5       10606450.        3733453.       10606314.
      3733413.25       10606241.      3733569.38     10606138.94
      3733536.83     10606059.73      3733590.25       10605965.
      3733525.11     10605804.52       3733566.5       10605703.
      3733566.25       10605593.      3733482.75     10605609.68
      3733427.75       10605533.      3733362.25       10605505.
      3733434.25       10605350.        3733392.       10605282.

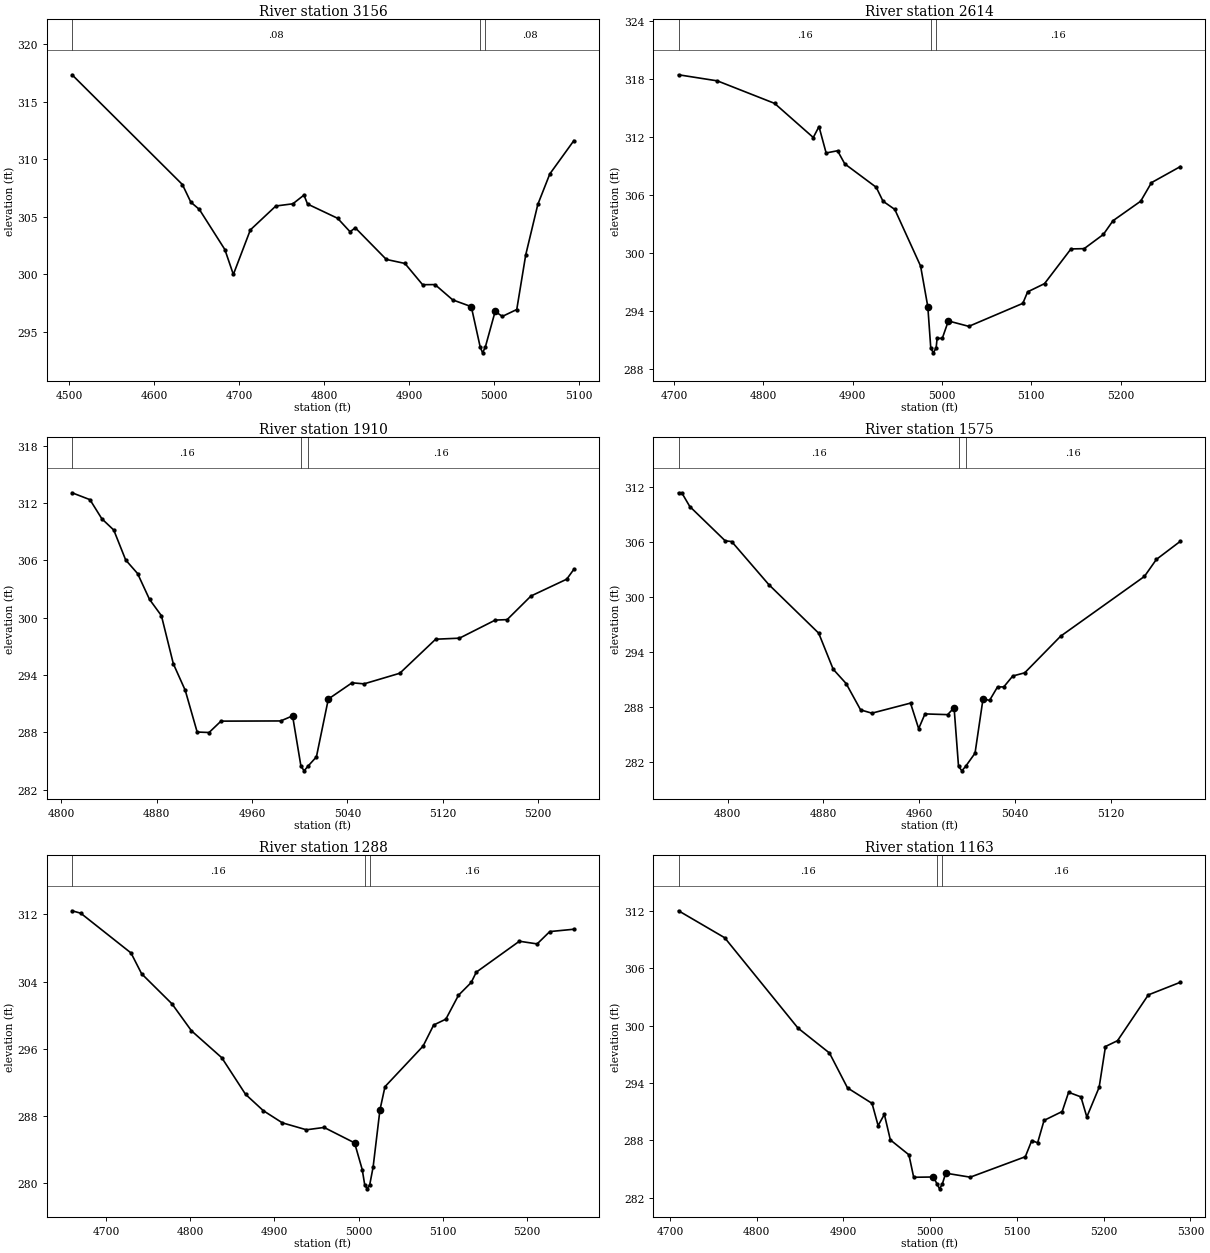
Type RM Length L Ch R = 1 ,3156    ,542,542,542
BEGIN DESCRIPTION:
UNT 019 IN BOCR 5.0
END DESCRIPTION:
XS GIS Cut Line= 4
      3733819.33     10607516.66      3733549.61     10607510.19
      3733399.61     10607310.19      3733349.62      10607260.2
#Sta/Elev= 30
  4503.2  317.35    4633   307.8    4643  306.26    4653  305.63    4683  302.14
    4693  299.97    4713  303.85    4743  305.93    4763  306.12  4776.1  306.88
  4780.3   306.1  4815.7  304.86  4830.3  303.69  4836.5  304.03    4873  301.28
  4894.9  300.93  4915.7  299.08  4930.3  299.09  4951.1  297.76    4973  297.17
  4983.5  293.65  4986.3  293.15  4989.5  293.65  5001.1  296.76  5009.5  296.32
  5026.5  296.92  5037.1  301.69  5051.3  306.07  5065.4  308.72  5093.7  311.62
#Mann= 3 ,-1 , 0
  4503.2     .08       0  4983.5     .07       0  4989.5     .08       0
Bank Sta=4973,5001.1
XS Rating Curve= 0 ,0
Exp/Cntr=0.3,0.1

Type RM Length L Ch R = 1 ,2614    ,704,704,704
BEGIN DESCRIPTION:
UNT 019 IN BOCR 4.0
END DESCRIPTION:
XS GIS Cut Line= 3
      3733879.26     10606878.64      3733649.61     10607060.19
      3733399.61     10607160.19
#Sta/Elev= 30
    4705  318.44  4748.5  317.81  4812.6  315.48  4855.9  311.95  4862.3  313.08
  4870.3  310.35  4883.1  310.58  4891.2  309.22  4926.4   306.8    4934  305.36
  4947.2  304.51  4976.1  298.65  4984.2  294.44  4987.5  290.17  4990.3  289.67
  4993.5  290.17  4994.6  291.17  5000.4  291.17  5007.2  292.97  5030.1  292.41
  5090.6  294.79    5096  295.98  5114.9  296.83  5144.5  300.42  5159.3  300.45
  5180.8  301.92  5191.6  303.34  5222.6  305.36  5234.7  307.28    5267  308.94
#Mann= 3 ,-1 , 0
    4705     .16       0  4987.5     .07       0  4993.5     .16       0
Bank Sta=4984.2,5007.2
XS Rating Curve= 0 ,0
Exp/Cntr=0.3,0.1

Type RM Length L Ch R = 1 ,1910    ,335,335,335
BEGIN DESCRIPTION:
UNT 019 IN BOCR 3.0
END DESCRIPTION:
XS GIS Cut Line= 2
      3733704.55     10606754.07      3733283.64     10606738.48
#Sta/Elev= 30
  4808.9  313.07  4823.9  312.35  4833.9  310.35  4843.9  309.17  4853.9  306.04
  4863.9  304.62  4873.9  301.92  4883.9  300.21  4893.9  295.18  4903.9   292.4
  4913.9  288.04  4923.9  287.99  4933.9  289.18    4984   289.2    4994  289.73
    5001  284.48  5003.7  283.98    5007  284.48    5014  285.44    5024  291.49
  5043.9  293.19    5054  293.08    5084  294.19  5114.1  297.75  5134.1  297.86
  5164.1  299.75  5174.1   299.8  5194.1  302.27  5224.1  304.03  5230.1  305.06
#Mann= 3 ,-1 , 0
  4808.9     .16       0    5001     .07       0    5007     .16       0
Bank Sta=4994,5024
XS Rating Curve= 0 ,0
Exp/Cntr=0.3,0.1

Type RM Length L Ch R = 1 ,1575    ,287,287,287
BEGIN DESCRIPTION:
UNT 019 IN BOCR 2.0
END DESCRIPTION:
XS GIS Cut Line= 3
      3733649.58     10606560.18      3733399.61     10606460.19
      3733249.63     10606460.19
#Sta/Elev= 30
    4759  311.39  4761.7  311.39  4768.4  309.89    4798  306.14  4803.4  306.06
  4834.4  301.36  4876.1  296.05  4888.2  292.11    4899  290.55  4911.1  287.67
  4920.5  287.31  4952.8  288.41  4959.6  285.62  4964.9  287.23  4983.8  287.15
  4989.2  287.91  4992.9  281.51  4995.7  281.01  4998.9  281.51  5006.7  282.94
  5013.4   288.9  5018.8   288.7  5025.5  290.18  5030.7  290.18  5038.2  291.37
  5048.2  291.72  5078.2  295.72  5148.2  302.25  5158.2  304.11  5178.2  306.09
#Mann= 3 ,-1 , 0
    4759     .16       0  4992.9     .07       0  4998.9     .16       0
Bank Sta=4989.2,5013.4
XS Rating Curve= 0 ,0
Exp/Cntr=0.3,0.1

Type RM Length L Ch R = 1 ,1288    ,125,125,125
BEGIN DESCRIPTION:
Mapping XS e19bf281
END DESCRIPTION:
XS GIS Cut Line= 2
      3733728.01      10606407.7      3733230.59     10606079.56
#Sta/Elev= 30
  4659.7  312.44    4670  312.15  4729.7  307.41  4742.3  304.93  4778.4  301.34
  4801.5  298.13  4837.5  294.92  4865.7  290.56  4886.8  288.61  4909.4  287.16
    4938  286.33    4959  286.61  4995.2  284.77  5004.3  281.58  5007.2  279.79
    5010  279.29  5013.2  279.79  5017.2  281.88  5025.3  288.69  5031.3  291.47
  5076.5   296.3  5089.1  298.82  5103.6  299.52  5118.6  302.37  5133.7  303.89
  5139.7  305.12  5190.9  308.81    5212  308.49    5227  309.96  5255.6  310.24
#Mann= 3 ,-1 , 0
  4659.7     .16       0  5007.2     .07       0  5013.2     .16       0
Bank Sta=4995.2,5025.3
XS Rating Curve= 0 ,0
Exp/Cntr=0.3,0.1

Type RM Length L Ch R = 1 ,1163    ,597,597,597
BEGIN DESCRIPTION:
Mapping XS a3a7c04f
END DESCRIPTION:
XS GIS Cut Line= 5
      3733762.82     10606351.64       3733614.2     10606224.72
      3733558.86     10606167.21      3733521.97     10606132.49
      3733336.45     10605961.08
#Sta/Elev= 30
  4709.9  312.02  4763.1   309.2  4847.6  299.75  4883.9  297.14  4904.7  293.49
    4933  291.87    4940  289.54  4947.2  290.72  4954.1  288.05  4975.5  286.49
    4981  284.14  5003.7  284.17    5008  283.43  5010.8  282.93    5014  283.43
  5017.9  284.57  5046.2  284.15  5109.7  286.29  5117.1  287.98  5123.9  287.75
  5131.3  290.09  5152.2  291.02  5159.6  293.03  5173.8  292.55  5180.6  290.45
  5194.8  293.55  5202.1  297.82    5216  298.43  5251.5  303.22  5288.4  304.54
#Mann= 3 ,-1 , 0
  4709.9     .16       0    5008     .07       0    5014     .16       0
Bank Sta=5003.7,5017.9
XS Rating Curve= 0 ,0
Exp/Cntr=0.3,0.1

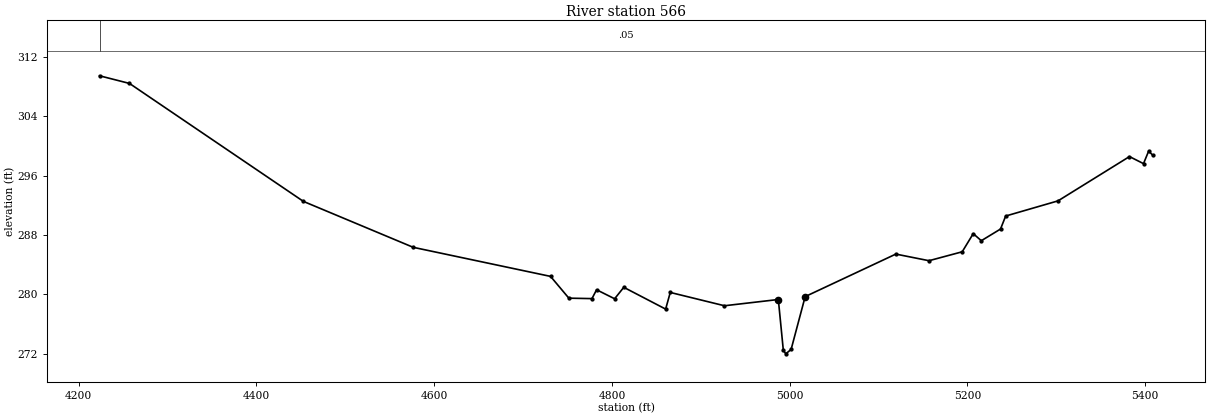
Type RM Length L Ch R = 1 ,566     ,0,0,0
BEGIN DESCRIPTION:
UNT 019 IN BOCR 1.0
END DESCRIPTION:
XS GIS Cut Line= 3
       3733787.5     10606312.91      3733613.88     10605609.75
      3733214.57     10605839.79
#Sta/Elev= 30
  4223.4  309.42  4257.1  308.39  4452.8  292.52  4576.4  286.34  4730.9  282.43
  4751.5   279.5  4777.5  279.44  4782.7  280.63    4803  279.42  4813.3  280.96
  4860.4  278.03  4865.6  280.27  4926.6  278.48  4987.2  279.32  4992.8  272.51
  4995.6  272.01  5001.6  272.61  5017.4  279.71  5119.4  285.43  5156.7  284.54
  5194.1  285.74  5206.5  288.18  5215.6  287.23  5237.2   288.8    5243  290.55
  5301.9  292.59  5382.3  298.55  5398.1   297.6  5403.9  299.29  5408.5  298.73
#Mann= 1 ,-1 , 0
  4223.4     .05       0
Bank Sta=4987.2,5017.4
XS Rating Curve= 0 ,0
Exp/Cntr=0.3,0.1

Chan Stop Cuts=-1
Use User Specified Reach Order=0
Composite Channel Slope=5