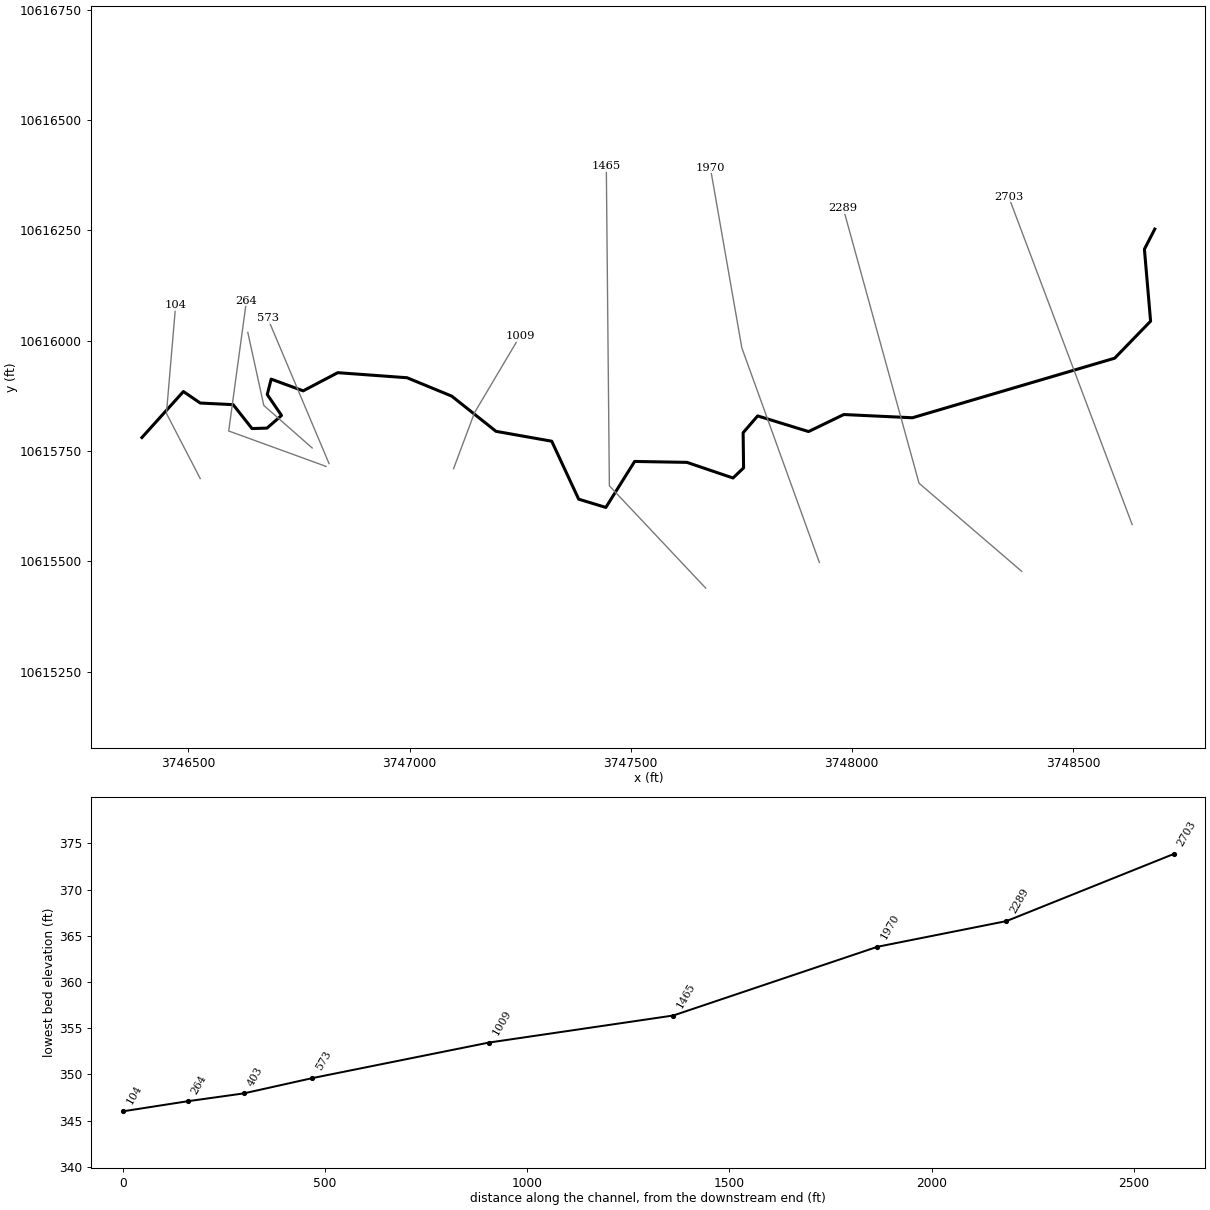
--- UNT 0197 IN BOCR.prj (project) ---

Proj Title=UNT 0197 IN BOCR Base Level Engineering
Current Plan=p01
Default Exp/Contr=0.3,0.1
English Units
Geom File=g01
Flow File=f01
Plan File=p01
Y Axis Title=Elevation
X Axis Title(PF)=Main Channel Distance
X Axis Title(XS)=Station
BEGIN DESCRIPTION:
UNT 0197 IN BOCR
END DESCRIPTION:
DSS Export Rating Curves= 0
DSS Export Rating Curve Sorted= 0
DSS Export Volume Flow Curves= 0
DXF OffsetX= 0
DXF OffsetY= 0
DXF ScaleX= 1
DXF ScaleY= 10

--- UNT 0197 IN BOCR.p01 (plan) ---

Plan Title=Multiple Run
Short Identifier=Multiple
Geom File=g01
Flow File=f01
Subcritical Flow
K Sum by GR= 0
Std Step Tol= 0.01
Critical Tol= 0.01
Num of Std Step Trials= 20
Max Error Tol= 0.3
Flow Tol Ratio= 0.001
Split Flow NTrial= 30
Split Flow Tol= 0.02
Split Flow Ratio= 0.02
Log Output Level= 0
Friction Slope Method= 1
Unsteady Friction Slope Method= 2
Unsteady Bridges Friction Slope Method= 1
Parabolic Critical Depth
Global Vel Dist=  1 , 1 , 1
Global Log Level= 0
CheckData=True
Encroach Param= -1, 0, 0, 0
BEGIN DESCRIPTION:
Multiple Run
END DESCRIPTION:

--- UNT 0197 IN BOCR.f01 (steady flow) ---

Flow Title=Multiple
Number of Profiles=7
Profile Names=10-year,25-year,50-year,1pct_min,100-year,1pct_plu,500-year
River Rch & RM= UNT 0197 IN BOCR,Reach-1,2703
    1431    2046    2583    2393    3236    4377    5101
Boundary for River Rch & Prof#=UNT 0197 IN BOCR,Reach-1,1
Up Type=0
Dn Type=3
Dn Slope=0.005
Boundary for River Rch & Prof#=UNT 0197 IN BOCR,Reach-1,2
Up Type=0
Dn Type=3
Dn Slope=0.005
Boundary for River Rch & Prof#=UNT 0197 IN BOCR,Reach-1,3
Up Type=0
Dn Type=3
Dn Slope=0.005
Boundary for River Rch & Prof#=UNT 0197 IN BOCR,Reach-1,4
Up Type=0
Dn Type=3
Dn Slope=0.005
Boundary for River Rch & Prof#=UNT 0197 IN BOCR,Reach-1,5
Up Type=0
Dn Type=3
Dn Slope=0.005
Boundary for River Rch & Prof#=UNT 0197 IN BOCR,Reach-1,6
Up Type=0
Dn Type=3
Dn Slope=0.005
Boundary for River Rch & Prof#=UNT 0197 IN BOCR,Reach-1,7
Up Type=0
Dn Type=3
Dn Slope=0.005

--- UNT 0197 IN BOCR.g01 (geometry) ---

Geom Title=Existing Conditions
Program Version=4.10

River Reach=UNT 0197 IN BOCR,Reach-1
Reach XY= 30
      3748685.14     10616252.88      3748661.71     10616207.31
       3748675.7     10616044.28      3748594.45     10615960.43
      3748137.16     10615825.53      3747981.95     10615832.83
      3747902.27     10615794.28      3747787.16      10615829.7
      3747754.35     10615791.68      3747755.39     10615711.99
      3747731.43     10615689.08      3747627.27     10615724.49
      3747509.04     10615726.58      3747443.93     10615622.41
      3747382.47     10615641.16      3747321.54     10615772.41
       3747195.5     10615794.81       3747095.5     10615874.49
      3746994.45     10615916.16      3746837.68     10615927.62
      3746759.56     10615886.47      3746687.16     10615913.03
      3746678.31     10615878.14       3746710.6     10615830.74
      3746677.79      10615802.1      3746643.93     10615801.06
      3746601.22     10615855.22      3746526.75     10615858.87
      3746488.72     10615884.91      3746394.96     10615780.77

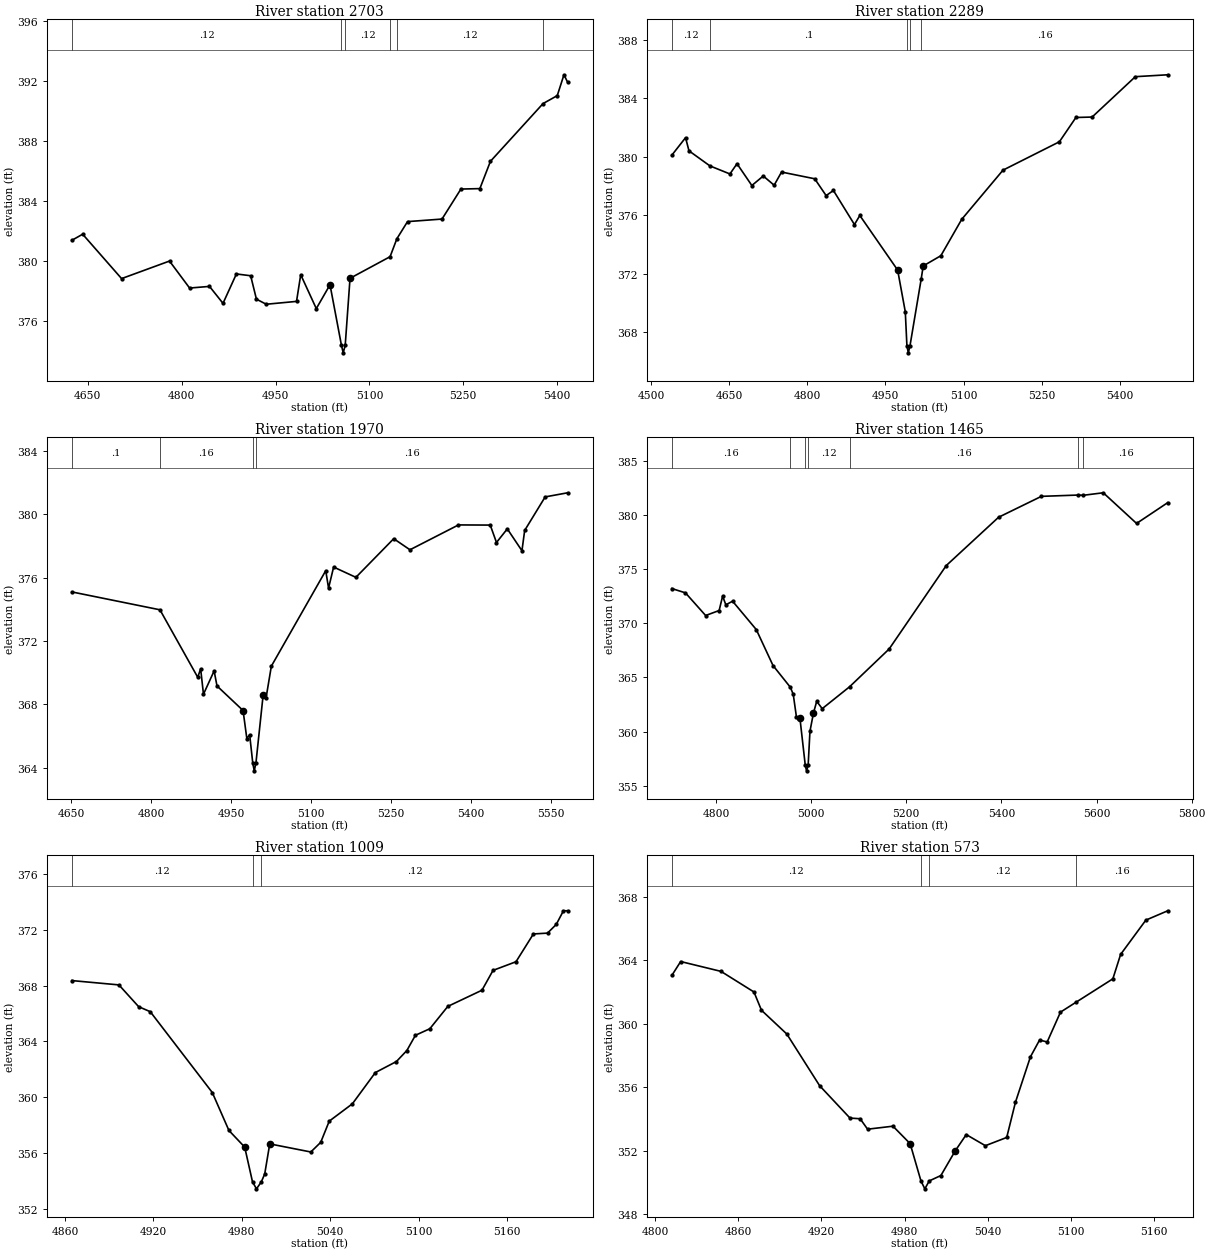
Type RM Length L Ch R = 1 ,2703    ,414,414,414
BEGIN DESCRIPTION:
Mapping XS 3da54064
END DESCRIPTION:
XS GIS Cut Line= 2
      3748633.88     10615583.94      3748354.87     10616325.81
#Sta/Elev= 30
  4624.3  381.36  4641.7  381.77  4703.9  378.81  4780.5  379.98  4812.6  378.18
  4844.4  378.29    4866  377.16  4887.4  379.12  4910.2     379  4919.4  377.44
  4935.1   377.1  4983.5  377.29  4990.2  379.07  5015.1  376.81    5037   378.4
  5055.3  374.36  5058.1  373.86  5061.3  374.36    5069  378.83    5133  380.27
  5143.9  381.47  5160.9  382.61    5216  382.78  5246.2  384.78  5276.5  384.81
  5293.4  386.63  5377.5  390.48  5400.2  391.01  5410.9   392.4  5416.9  391.89
#Mann= 6 ,-1 , 0
  4624.3     .12       0  5055.3     .07       0  5061.3     .12       0
    5133     .16       0  5143.9     .12       0  5377.5     .16       0
Bank Sta=5037,5069
XS Rating Curve= 0 ,0
Exp/Cntr=0.3,0.1

Type RM Length L Ch R = 1 ,2289    ,319,319,319
BEGIN DESCRIPTION:
Mapping XS a47debff
END DESCRIPTION:
XS GIS Cut Line= 3
      3748384.26     10615477.68      3748152.09      10615677.3
      3747980.65     10616300.15
#Sta/Elev= 30
  4539.7   380.1  4566.1   381.3  4572.7   380.4  4612.9  379.37  4651.3  378.82
  4664.9  379.52  4693.4  378.03  4715.3  378.68  4736.2  378.05  4750.4  378.95
  4814.1  378.49    4836  377.34    4850  377.69  4890.4  375.36  4900.7  375.98
  4973.3  372.25    4988   369.4  4991.1  367.09  4993.8  366.59  4997.1  367.09
  5018.6  371.65  5022.4  372.53  5056.3  373.23  5096.4  375.72  5175.6  379.08
  5283.9  381.02  5315.6  382.68  5346.7  382.71  5429.7  385.47  5491.9   385.6
#Mann= 5 ,-1 , 0
  4539.7     .12       0  4612.9      .1       0  4991.1     .07       0
  4997.1      .1       0  5018.6     .16       0
Bank Sta=4973.3,5022.4
XS Rating Curve= 0 ,0
Exp/Cntr=0.3,0.1

Type RM Length L Ch R = 1 ,1970    ,505,505,505
BEGIN DESCRIPTION:
Mapping XS ee173ba3
END DESCRIPTION:
XS GIS Cut Line= 3
      3747926.73     10615497.81       3747751.4     10615983.88
      3747680.22     10616391.89
#Sta/Elev= 30
  4650.8  375.11  4816.3  373.98  4887.2  369.72  4892.7  370.25    4898  368.65
    4918  370.12  4923.4  369.17  4972.3  367.62  4979.4  365.85  4984.7  366.09
  4990.5  364.31  4993.3  363.81  4996.5  364.31  5010.1  368.63  5015.4   368.4
  5025.4  370.42  5127.5  376.45  5132.8  375.35  5142.3  376.68  5184.1  376.03
  5255.1  378.47  5285.6  377.77  5376.7  379.34  5436.3  379.33    5448  378.23
  5468.3  379.09  5495.8  377.71  5500.9  378.99  5539.4  381.11  5581.7  381.37
#Mann= 4 ,-1 , 0
  4650.8      .1       0  4816.3     .16       0  4990.5     .07       0
  4996.5     .16       0
Bank Sta=4972.3,5010.1
XS Rating Curve= 0 ,0
Exp/Cntr=0.3,0.1

Type RM Length L Ch R = 1 ,1465    ,456,456,456
BEGIN DESCRIPTION:
Mapping XS 7cd8aaaa
END DESCRIPTION:
XS GIS Cut Line= 3
      3747669.81      10615439.6      3747451.92     10615671.38
      3747444.98     10616395.73
#Sta/Elev= 30
  4707.2   373.2  4735.9   372.8  4778.3  370.71  4806.7  371.17    4814   372.5
  4820.8   371.7    4835  372.03  4884.8  369.41    4920  366.09  4956.5  364.08
  4962.5  363.43  4969.3  361.31  4976.6  361.21  4987.8  356.87  4990.5  356.37
  4993.8  356.87  4997.6  360.02  5004.9  361.69  5011.8  362.79  5023.4  362.11
  5080.9  364.13  5164.1  367.62  5284.1  375.32  5394.1  379.78  5484.1  381.71
  5561.1  381.83  5572.4  381.81  5614.2  382.04  5684.2  379.21  5749.7  381.13
#Mann= 7 ,-1 , 0
  4707.2     .16       0  4956.5     .12       0  4987.8     .07       0
  4993.8     .12       0  5080.9     .16       0  5561.1     .12       0
  5572.4     .16       0
Bank Sta=4976.6,5004.9
XS Rating Curve= 0 ,0
Exp/Cntr=0.3,0.1

Type RM Length L Ch R = 1 ,1009    ,436,436,436
BEGIN DESCRIPTION:
UNT 0197 IN BOCR 2.0
END DESCRIPTION:
XS GIS Cut Line= 3
      3747099.62     10615710.22      3747146.98     10615837.06
      3747249.63     10616010.22
#Sta/Elev= 30
  4864.6  368.36  4896.6  368.05    4910  366.49  4917.9  366.13    4960  360.34
  4971.3  357.62    4982  356.43  4987.3  353.94    4990  353.44  4993.3  353.94
  4995.6  354.51    4999  356.66  5026.9  356.08  5033.6  356.77  5039.4  358.29
  5055.1  359.53  5070.7  361.77    5085  362.56  5092.1  363.35  5097.9  364.44
  5107.7  364.91  5119.9  366.51  5143.1  367.67  5150.6  369.09  5166.2  369.71
    5178   371.7  5187.6  371.76  5193.5  372.38  5198.4  373.36  5201.3  373.36
#Mann= 3 ,-1 , 0
  4864.6     .12       0  4987.3     .07       0  4993.3     .12       0
Bank Sta=4982,4999
XS Rating Curve= 0 ,0
Exp/Cntr=0.3,0.1

Type RM Length L Ch R = 1 ,573     ,170,170,170
BEGIN DESCRIPTION:
UNT 0197 IN BOCR 1.0
END DESCRIPTION:
XS GIS Cut Line= 2
      3746818.07     10615721.67      3746679.19     10616051.52
#Sta/Elev= 30
    4812  363.05  4818.4  363.93  4847.5  363.31  4871.3  362.01  4876.7  360.86
    4895  359.36  4918.7   356.1  4940.6  354.06  4947.9  354.02  4953.3  353.36
  4971.6  353.55    4984  352.45  4991.8   350.1  4994.6   349.6  4997.8   350.1
  5006.2  350.44  5016.5  351.99  5024.5  353.02  5038.3  352.32  5053.7  352.84
    5060  355.06  5070.8  357.92  5077.4  358.98  5082.9  358.86  5092.5  360.74
    5104  361.38  5130.3  362.84  5135.9  364.38  5154.1  366.54  5169.9  367.13
#Mann= 4 ,-1 , 0
    4812     .12       0  4991.8     .07       0  4997.8     .12       0
    5104     .16       0
Bank Sta=4984,5016.5
XS Rating Curve= 0 ,0
Exp/Cntr=0.3,0.1

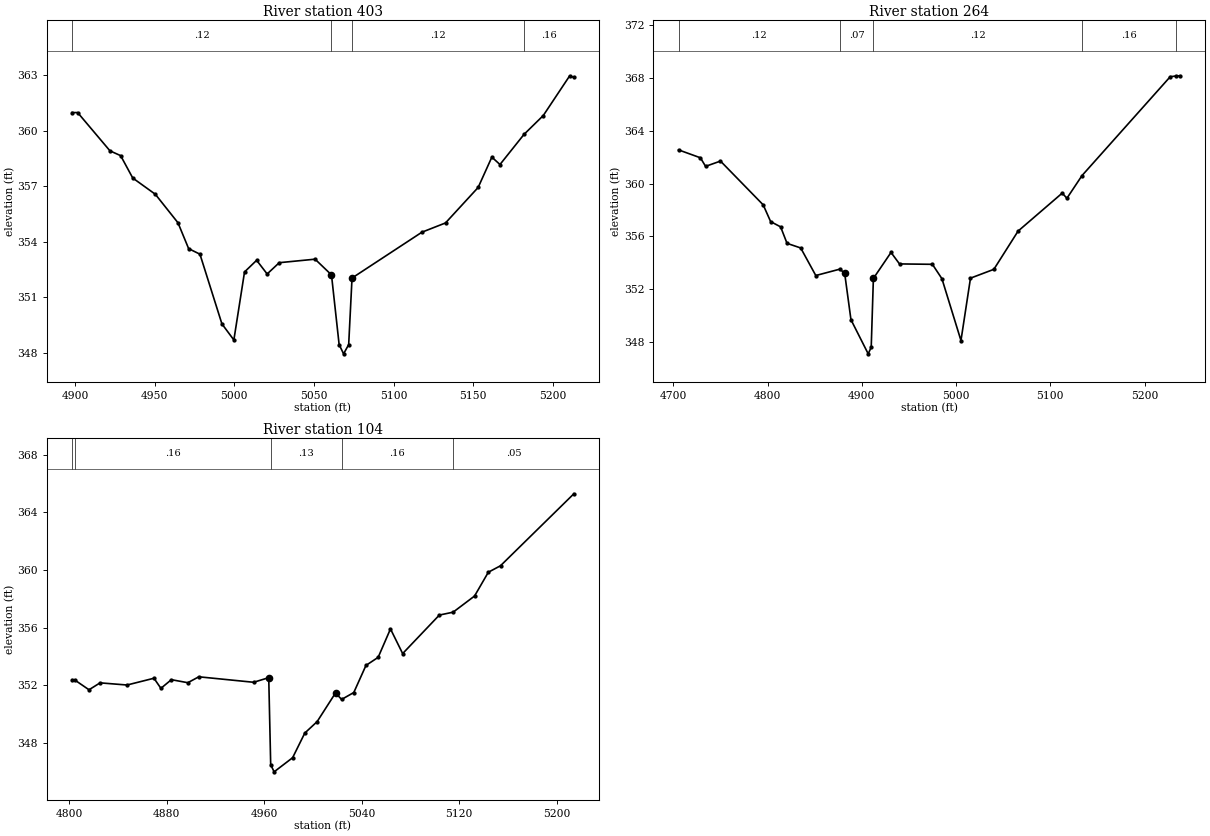
Type RM Length L Ch R = 1 ,403     ,139,139,139
BEGIN DESCRIPTION:
Mapping XS fdf547f1
END DESCRIPTION:
XS GIS Cut Line= 3
      3746779.87     10615757.11      3746670.52     10615853.44
      3746634.33      10616018.9
#Sta/Elev= 30
  4898.1  360.99  4901.6  360.99  4921.9  358.92  4928.6  358.66  4936.2  357.45
  4950.4  356.57  4964.6  355.03  4971.3  353.63  4978.4  353.33  4992.2  349.56
  4999.7  348.69  5006.4  352.37    5014     353  5020.6  352.26  5028.2  352.87
  5050.7  353.06    5061  352.21  5065.8  348.44  5068.6  347.94  5071.8  348.44
  5073.9  352.04  5117.8  354.52  5132.6  355.02  5153.1  356.94  5161.7  358.58
  5166.8  358.18  5181.9  359.81    5194  360.83  5210.6  362.98  5213.2  362.89
#Mann= 4 ,-1 , 0
  4898.1     .12       0    5061     .07       0  5073.9     .12       0
  5181.9     .16       0
Bank Sta=5061,5073.9
XS Rating Curve= 0 ,0
Exp/Cntr=0.3,0.1

Type RM Length L Ch R = 1 ,264     ,160,160,160
BEGIN DESCRIPTION:
Mapping XS 9a661b79
END DESCRIPTION:
XS GIS Cut Line= 3
       3746811.4     10615715.31      3746591.17     10615795.59
      3746631.32     10616090.76
#Sta/Elev= 30
  4705.6  362.56  4728.8  361.96  4734.3  361.31  4750.1  361.71  4795.4  358.39
  4803.3  357.12  4813.9  356.72  4820.7  355.47  4835.2  355.12  4851.2  353.03
  4876.5  353.51  4881.8  353.22  4888.5  349.68  4906.8  347.09    4910  347.59
  4912.3  352.81    4931  354.78    4940  353.91  4974.9  353.88    4985  352.79
  5005.2   348.1  5015.3  352.83  5040.1   353.5  5065.8   356.4  5112.6  359.28
  5117.6  358.89  5133.6  360.61  5227.2  368.11  5233.1  368.16  5237.9  368.18
#Mann= 5 ,-1 , 0
  4705.6     .12       0  4876.5     .07       0  4912.3     .12       0
  5133.6     .16       0  5233.1     .05       0
Bank Sta=4881.8,4912.3
XS Rating Curve= 0 ,0
Exp/Cntr=0.3,0.1

Type RM Length L Ch R = 1 ,104     ,0,0,0
BEGIN DESCRIPTION:
Mapping XS 188e1b8b
END DESCRIPTION:
XS GIS Cut Line= 3
      3746526.75     10615687.85      3746450.36     10615835.41
      3746471.19     10616080.17
#Sta/Elev= 30
  4802.4  352.38  4804.4  352.38  4816.3  351.69  4825.4  352.17  4847.5  352.02
  4869.6  352.49  4875.3  351.79  4883.9  352.39  4897.4  352.18  4906.4  352.59
  4951.4  352.21  4963.8  352.53  4965.4   346.5  4968.2     346  4983.4  346.98
  4993.4  348.69  5003.5  349.48  5018.6  351.47  5023.6  351.02  5033.6   351.5
  5043.6  353.38  5053.6  353.94  5063.7  355.91  5073.7   354.2  5103.8  356.87
  5115.1  357.07  5132.7  358.19    5144  359.84    5154  360.29  5214.2  365.28
#Mann= 5 ,-1 , 0
  4802.4     .12       0  4804.4     .16       0  4965.4     .13       0
  5023.6     .16       0  5115.1     .05       0
Bank Sta=4963.8,5018.6
XS Rating Curve= 0 ,0
Exp/Cntr=0.3,0.1

Chan Stop Cuts=-1
Use User Specified Reach Order=0
Composite Channel Slope=5