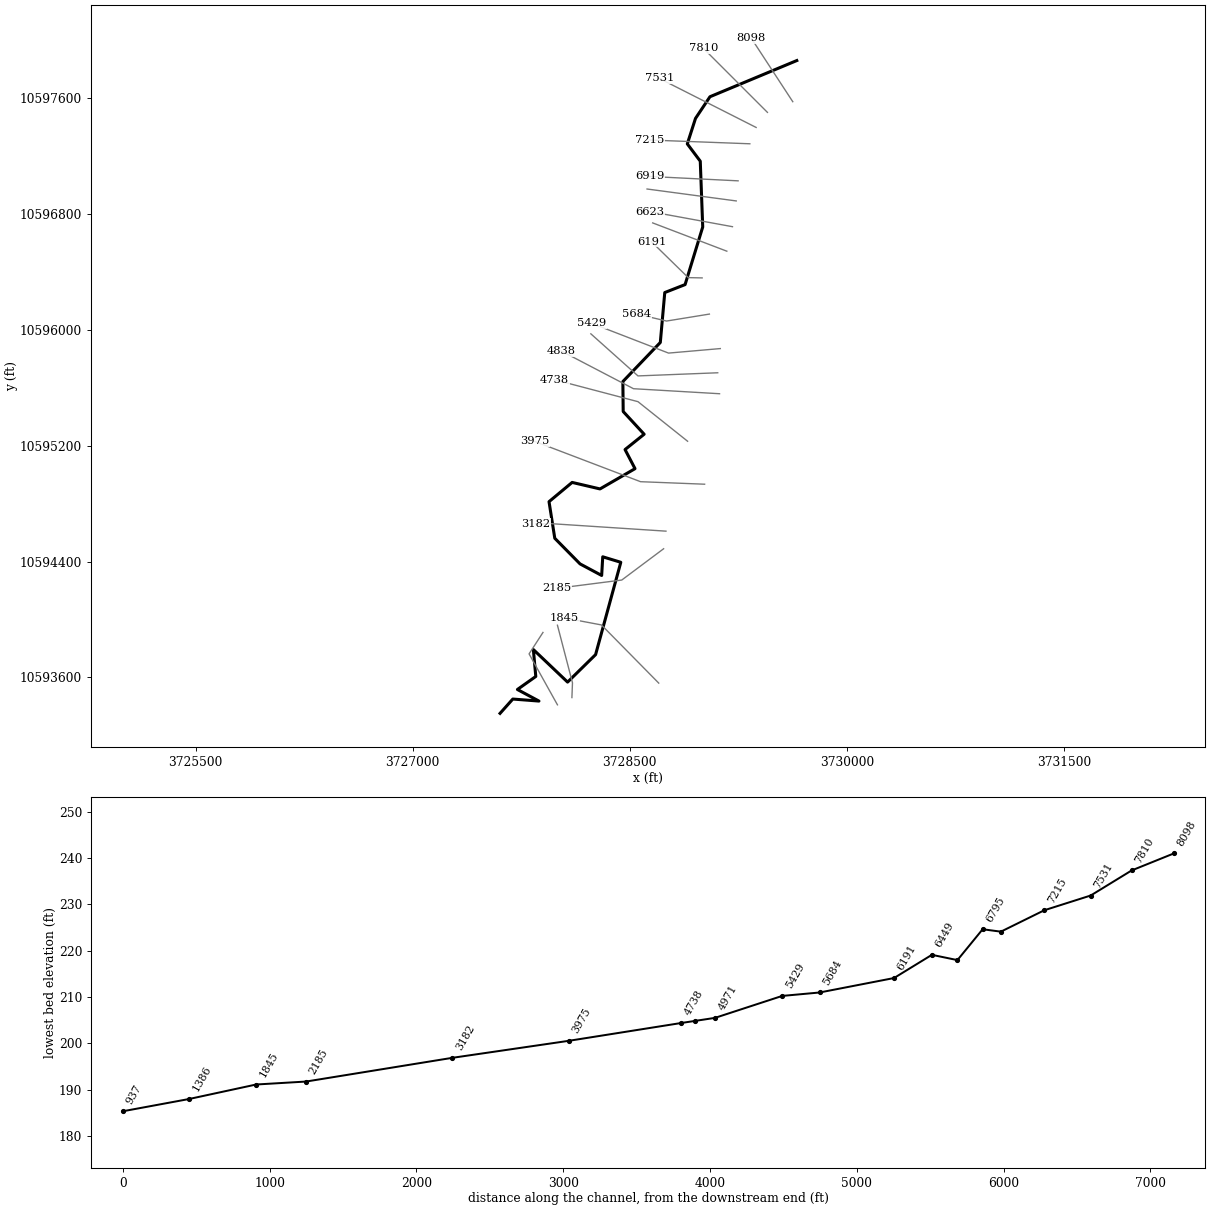
--- UNT 020 IN BOCR.prj (project) ---

Proj Title=UNT 020 IN BOCR Base Level Engineering
Current Plan=p01
Default Exp/Contr=0.3,0.1
English Units
Geom File=g01
Flow File=f01
Plan File=p01
BEGIN DESCRIPTION:
UNT 020 IN BOCR
END DESCRIPTION:

--- UNT 020 IN BOCR.p01 (plan) ---

Plan Title=Multiple Run
Short Identifier=Multiple
Geom File=g01
Flow File=f01
Subcritical Flow
K Sum by GR= 0
Std Step Tol= 0.01
Critical Tol= 0.01
Num of Std Step Trials= 20
Max Error Tol= 0.3
Flow Tol Ratio= 0.001
Split Flow NTrial= 30
Split Flow Tol= 0.02
Split Flow Ratio= 0.02
Log Output Level= 0
Friction Slope Method= 1
Unsteady Friction Slope Method= 2
Unsteady Bridges Friction Slope Method= 1
Parabolic Critical Depth
Global Vel Dist=  1 , 1 , 1
Global Log Level= 0
CheckData=True
Encroach Param= -1, 0, 0, 0
BEGIN DESCRIPTION:
Multiple Run
END DESCRIPTION:

--- UNT 020 IN BOCR.f01 (steady flow) ---

Flow Title=Multiple
Number of Profiles=7
Profile Names=10-year,25-year,50-year,1pct_min,100-year,1pct_plu,500-year
River Rch & RM= UNT 020 IN BOCR,Reach-1,8098
     600     814     992     888    1201    1625    1769
Boundary for River Rch & Prof#=UNT 020 IN BOCR,Reach-1,1
Up Type=0
Dn Type=3
Dn Slope=0.005
Boundary for River Rch & Prof#=UNT 020 IN BOCR,Reach-1,2
Up Type=0
Dn Type=3
Dn Slope=0.005
Boundary for River Rch & Prof#=UNT 020 IN BOCR,Reach-1,3
Up Type=0
Dn Type=3
Dn Slope=0.005
Boundary for River Rch & Prof#=UNT 020 IN BOCR,Reach-1,4
Up Type=0
Dn Type=3
Dn Slope=0.005
Boundary for River Rch & Prof#=UNT 020 IN BOCR,Reach-1,5
Up Type=0
Dn Type=3
Dn Slope=0.005
Boundary for River Rch & Prof#=UNT 020 IN BOCR,Reach-1,6
Up Type=0
Dn Type=3
Dn Slope=0.005
Boundary for River Rch & Prof#=UNT 020 IN BOCR,Reach-1,7
Up Type=0
Dn Type=3
Dn Slope=0.005

--- UNT 020 IN BOCR.g01 (geometry) ---

Geom Title=Existing Conditions

River Reach=UNT 020 IN BOCR,Reach-1
Reach XY= 30
      3729653.60     10597862.11      3729053.60     10597612.11
      3728953.60     10597462.11      3728897.04     10597286.26
      3728986.62     10597166.81      3729003.60     10596712.11
      3728881.75     10596314.00      3728741.25     10596259.00
      3728710.50     10595914.00      3728451.75     10595644.00
      3728454.00     10595437.00      3728598.75     10595280.00
      3728466.75     10595174.00      3728535.75     10595042.00
      3728293.75     10594902.00      3728101.25     10594947.00
      3727941.50     10594814.00      3727981.25     10594561.00
      3728155.75     10594384.00      3728305.25     10594304.00
      3728312.75     10594433.00      3728437.50     10594395.00
      3728263.25     10593757.00      3728069.75     10593567.00
      3727833.26     10593791.98      3727850.00     10593606.00
      3727723.00     10593516.00      3727872.00     10593436.00
      3727691.25     10593450.00      3727603.00     10593351.00

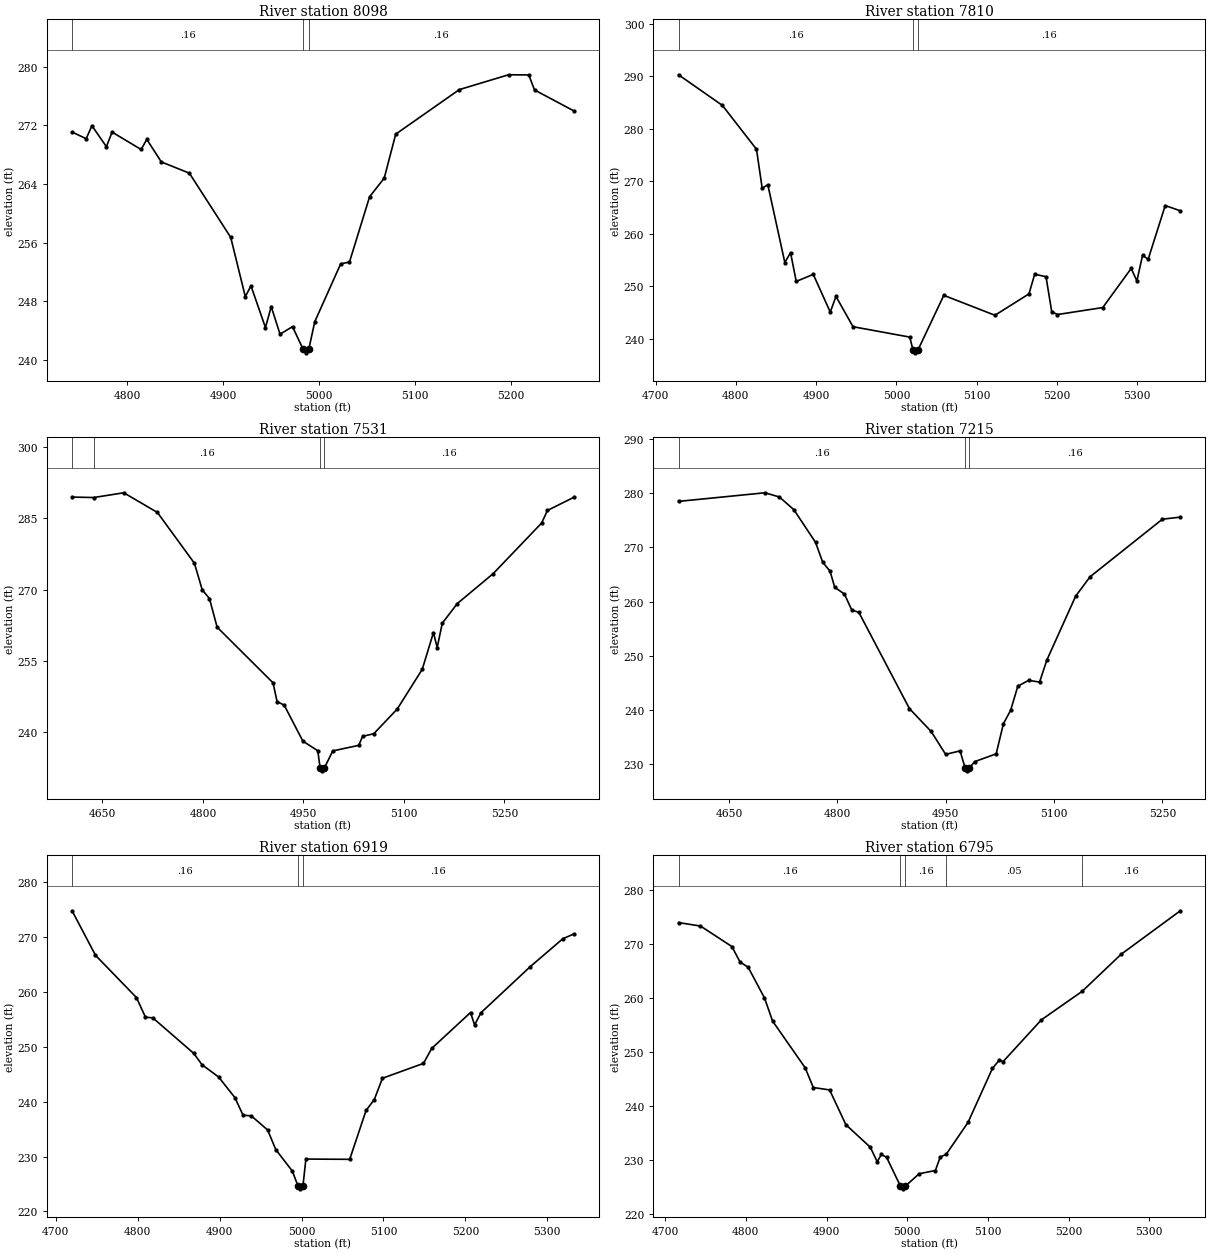
Type RM Length L Ch R = 1,8098,288,288,288
BEGIN DESCRIPTION:
UNT 020 IN BOCR 14.0
END DESCRIPTION:
XS GIS Cut Line= 2
      3729625.82     10597577.78      3729339.68     10598015.68
#Sta/Elev= 30
  4742.4  271.09  4757.1  270.18  4763.1  271.95  4778.2  269.09  4784.1  271.08
  4814.4  268.71  4820.3  270.09  4835.4  267.02  4864.7  265.48  4907.8  256.73
  4923.0  248.65  4928.9  250.13  4944.0  244.44  4950.0  247.30  4959.2  243.54
  4972.2  244.57  4983.2  241.50  4986.0  241.00  4989.2  241.50  4995.4  245.24
  5022.4  253.12  5031.6  253.38  5052.6  262.28  5067.8  264.80  5079.8  270.80
  5146.1  276.87  5197.4  278.89  5218.5  278.87  5224.5  276.82  5265.5  273.97
#Mann=3,-1,0
  4742.4    0.16       0  4983.2    0.07       0  4989.2    0.16       0
Bank Sta=4983.2,4989.2
Exp/Cntr=0.3,0.1

Type RM Length L Ch R = 1,7810,279,279,279
BEGIN DESCRIPTION:
Mapping XS 123185ca
END DESCRIPTION:
XS GIS Cut Line= 2
      3729450.75     10597504.02      3729008.81     10597945.97
#Sta/Elev= 30
  4728.6  290.32  4783.3  284.47  4825.7  276.12  4832.8  268.69  4839.8  269.36
  4861.0  254.53  4868.1  256.42  4875.2  250.93  4896.4  252.28  4917.6  245.08
  4924.7  248.08  4945.9  242.30  5016.6  240.32  5020.7  237.82  5023.4  237.32
  5026.7  237.82  5059.0  248.28  5122.7  244.48  5165.1  248.56  5172.2  252.31
  5186.3  251.83  5193.4  245.18  5200.5  244.62  5257.0  245.95  5292.4  253.41
  5299.5  251.01  5306.5  255.88  5313.6  255.18  5334.8  265.40  5353.6  264.39
#Mann=3,-1,0
  4728.6    0.16       0  5020.7    0.07       0  5026.7    0.16       0
Bank Sta=5020.7,5026.7
Exp/Cntr=0.3,0.1

Type RM Length L Ch R = 1,7531,316,316,316
BEGIN DESCRIPTION:
Mapping XS 901f8667
END DESCRIPTION:
XS GIS Cut Line= 2
      3729372.62     10597399.87      3728704.44     10597738.30
#Sta/Elev= 30
  4604.7  289.47  4637.0  289.37  4681.9  290.37  4732.1  286.23  4787.4  275.54
  4798.9  269.99  4809.8  268.12  4821.2  262.12  4904.7  250.41  4910.7  246.47
  4921.3  245.73  4949.2  238.16  4971.5  236.13  4975.0  232.41  4977.7  231.91
  4981.0  232.41  4993.8  236.10  5032.7  237.27  5038.3  239.16  5055.0  239.71
  5090.1  244.91  5127.4  253.25  5144.1  260.98  5149.7  257.83  5157.3  262.95
  5179.8  267.09  5233.2  273.36  5305.6  284.01  5314.3  286.66  5353.7  289.42
#Mann=4,-1,0
  4604.7    0.05       0  4637.0    0.16       0  4975.0    0.07       0
  4981.0    0.16       0
Bank Sta=4975,4981
Exp/Cntr=0.3,0.1

Type RM Length L Ch R = 1,7215,296,296,296
BEGIN DESCRIPTION:
Mapping XS 4df8f075
END DESCRIPTION:
XS GIS Cut Line= 2
      3729329.21     10597287.02      3728634.80     10597313.06
#Sta/Elev= 30
  4580.0  278.52  4699.7  280.11  4719.7  279.33  4739.7  276.99  4769.7  270.95
  4779.7  267.27  4789.8  265.62  4796.3  262.65  4809.8  261.38  4819.8  258.48
  4829.8  257.99  4899.8  240.22  4929.9  236.00  4949.9  231.77  4969.9  232.42
  4976.9  229.23  4979.6  228.73  4982.9  229.23  4989.9  230.42  5019.9  231.87
  5029.9  237.44  5039.9  239.91  5049.9  244.38  5064.9  245.45  5080.0  245.13
  5090.0  249.18  5130.0  261.02  5150.0  264.60  5250.1  275.23  5274.9  275.61
#Mann=3,-1,0
  4580.0    0.16       0  4976.9    0.07       0  4982.9    0.16       0
Bank Sta=4976.9,4982.9
Exp/Cntr=0.3,0.1

Type RM Length L Ch R = 1,6919,124,124,124
BEGIN DESCRIPTION:
Mapping XS dbdc15ba
END DESCRIPTION:
XS GIS Cut Line= 2
      3729248.15     10597030.95      3728636.20     10597061.33
#Sta/Elev= 30
  4719.8  274.80  4748.4  266.69  4798.4  258.98  4809.4  255.41  4818.5  255.27
  4868.5  248.79  4878.5  246.73  4898.6  244.52  4918.6  240.75  4928.6  237.53
  4938.6  237.42  4958.6  234.84  4968.6  231.25  4988.7  227.36  4995.7  224.61
  4998.4  224.11  5001.7  224.61  5005.3  229.54  5058.8  229.49  5078.8  238.41
  5088.8  240.38  5098.8  244.27  5148.9  246.98  5158.9  249.70  5206.3  256.25
  5211.3  253.98  5219.0  256.20  5279.0  264.58  5319.1  269.71  5332.5  270.57
#Mann=3,-1,0
  4719.8    0.16       0  4995.7    0.07       0  5001.7    0.16       0
Bank Sta=4995.7,5001.7
Exp/Cntr=0.3,0.1

Type RM Length L Ch R = 1,6795,172,172,172
BEGIN DESCRIPTION:
Mapping XS 475cbd15
END DESCRIPTION:
XS GIS Cut Line= 2
      3729235.13     10596892.06      3728618.83     10596974.53
#Sta/Elev= 30
  4716.6  274.00  4743.8  273.36  4782.7  269.56  4792.8  266.70  4802.9  265.71
  4823.1  260.03  4833.2  255.73  4873.5  247.08  4883.6  243.42  4903.8  242.97
  4924.0  236.52  4954.2  232.35  4962.8  229.66  4967.9  231.00  4974.4  230.48
  4991.6  225.13  4994.3  224.63  4997.6  225.13  5014.8  227.43  5034.9  228.03
  5040.9  230.54  5048.2  231.02  5075.3  236.94  5105.6  246.97  5113.9  248.47
  5118.9  248.24  5166.1  255.95  5216.9  261.27  5265.0  268.12  5338.4  276.19
#Mann=5,-1,0
  4716.6    0.16       0  4991.6    0.07       0  4997.6    0.16       0
  5048.2    0.05       0  5216.9    0.16       0
Bank Sta=4991.6,4997.6
Exp/Cntr=0.3,0.1

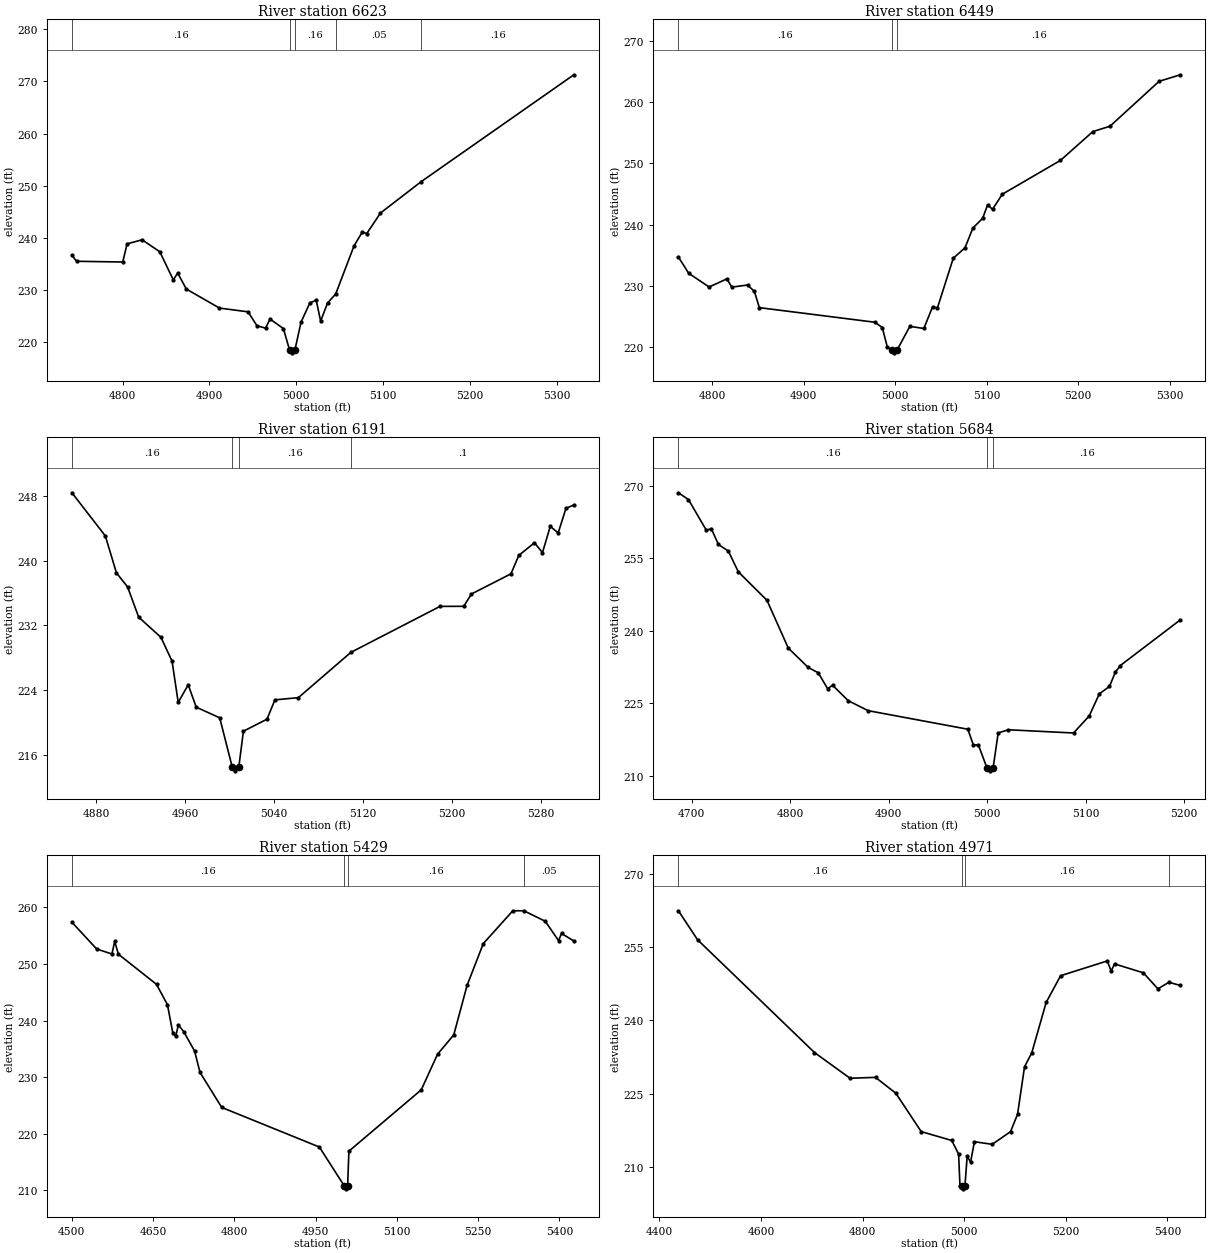
Type RM Length L Ch R = 1,6623,174,174,174
BEGIN DESCRIPTION:
Mapping XS 51483882
END DESCRIPTION:
XS GIS Cut Line= 2
      3729209.12     10596714.11      3728640.59     10596818.27
#Sta/Elev= 30
  4741.7  236.66  4747.0  235.52  4800.2  235.38  4805.2  238.86  4822.5  239.64
  4842.9  237.34  4858.4  231.96  4863.5  233.26  4873.4  230.20  4911.6  226.55
  4944.5  225.83  4954.7  223.17  4964.7  222.70  4969.8  224.45  4985.2  222.62
  4992.4  218.47  4995.1  217.97  4998.4  218.47  5005.5  223.84  5015.7  227.55
  5023.0  228.06  5028.1  224.05  5036.0  227.50  5045.5  229.28  5066.5  238.45
  5076.1  241.14  5081.2  240.83  5097.0  244.77  5144.1  250.81  5319.7  271.27
#Mann=5,-1,0
  4741.7    0.16       0  4992.4    0.07       0  4998.4    0.16       0
  5045.5    0.05       0  5144.1    0.16       0
Bank Sta=4992.4,4998.4
Exp/Cntr=0.3,0.1

Type RM Length L Ch R = 1,6449,258,258,258
BEGIN DESCRIPTION:
Mapping XS 4b01a2fe
END DESCRIPTION:
XS GIS Cut Line= 2
      3729170.11     10596544.82      3728657.89     10596740.16
#Sta/Elev= 30
  4763.3  234.74  4774.5  232.09  4796.8  229.85  4816.2  231.17  4821.6  229.83
  4838.8  230.17  4846.3  229.13  4851.7  226.48  4977.9  224.10  4986.0  223.23
  4991.4  220.08  4996.3  219.61  4999.0  219.11  5002.3  219.61  5016.1  223.43
  5031.4  223.08  5040.9  226.62  5046.2  226.43  5063.5  234.54  5076.3  236.24
  5084.9  239.45  5095.6  241.06  5101.0  243.24  5106.4  242.52  5117.0  244.97
  5180.6  250.50  5216.0  255.20  5234.7  256.07  5288.3  263.39  5311.5  264.46
#Mann=3,-1,0
  4763.3    0.16       0  4996.3    0.07       0  5002.3    0.16       0
Bank Sta=4996.3,5002.3
Exp/Cntr=0.3,0.1

Type RM Length L Ch R = 1,6191,507,507,507
BEGIN DESCRIPTION:
UNT 020 IN BOCR 10.0
END DESCRIPTION:
XS GIS Cut Line= 3
      3728999.62     10596360.19      3728903.60     10596362.11
      3728649.60     10596610.20
#Sta/Elev= 30
  4858.2  248.34  4888.2  243.03  4898.2  238.47  4908.2  236.75  4918.2  233.02
  4938.2  230.54  4948.2  227.59  4953.7  222.53  4962.7  224.69  4969.9  221.94
  4991.0  220.63  5002.2  214.60  5004.9  214.10  5008.2  214.60  5012.3  218.98
  5033.5  220.46  5040.6  222.84  5061.7  223.11  5108.8  228.68  5189.0  234.35
  5210.3  234.36  5217.3  235.88  5252.8  238.36  5259.8  240.63  5273.9  242.18
  5281.1  240.97  5288.1  244.21  5295.2  243.39  5302.2  246.42  5309.3  246.84
#Mann=4,-1,0
  4858.2    0.16       0  5002.2    0.07       0  5008.2    0.16       0
  5108.8     0.1       0
Bank Sta=5002.2,5008.2
Exp/Cntr=0.3,0.1

Type RM Length L Ch R = 1,5684,255,255,255
BEGIN DESCRIPTION:
UNT 020 IN BOCR 9.0
END DESCRIPTION:
XS GIS Cut Line= 3
      3729049.65     10596110.20      3728753.60     10596062.11
      3728549.62     10596110.19
#Sta/Elev= 30
  4686.6  268.59  4696.8  267.18  4714.9  260.84  4720.0  261.15  4727.2  257.88
  4737.3  256.50  4747.4  252.22  4776.5  246.31  4798.1  236.42  4818.3  232.41
  4828.5  231.30  4838.1  227.99  4843.1  228.72  4858.9  225.53  4879.1  223.45
  4980.4  219.60  4986.0  216.35  4991.1  216.35  5000.0  211.48  5002.8  210.98
  5006.0  211.48  5011.2  218.82  5021.5  219.49  5087.7  218.82  5103.6  222.35
  5113.9  226.94  5124.2  228.46  5130.0  231.36  5135.2  232.80  5196.1  242.26
#Mann=3,-1,0
  4686.6    0.16       0  5000.0    0.07       0  5006.0    0.16       0
Bank Sta=5000,5006
Exp/Cntr=0.3,0.1

Type RM Length L Ch R = 1,5429,458,458,458
BEGIN DESCRIPTION:
Mapping XS 70299bed
END DESCRIPTION:
XS GIS Cut Line= 3
      3729125.11     10595871.88      3728767.45     10595840.63
      3728238.29     10596045.35
#Sta/Elev= 30
  4500.3  257.36  4546.0  252.64  4574.1  251.76  4579.2  253.98  4586.1  251.72
  4656.4  246.39  4676.5  242.81  4686.5  237.79  4691.8  237.20  4696.8  239.23
  4706.6  238.03  4726.7  234.60  4736.7  230.81  4776.8  224.63  4957.0  217.63
  5003.1  210.74  5005.9  210.24  5009.1  210.74  5011.5  216.90  5145.1  227.75
  5175.1  234.04  5205.0  237.45  5229.6  246.20  5259.5  253.59  5314.0  259.40
  5334.5  259.40  5373.9  257.55  5398.5  254.12  5403.9  255.39  5426.7  254.06
#Mann=4,-1,0
  4500.3    0.16       0  5003.1    0.07       0  5009.1    0.16       0
  5334.5    0.05       0
Bank Sta=5003.1,5009.1
Exp/Cntr=0.3,0.1

Type RM Length L Ch R = 1,4971,133,133,133
BEGIN DESCRIPTION:
UNT 020 IN BOCR 8.0
END DESCRIPTION:
XS GIS Cut Line= 3
      3729107.28     10595704.63      3728556.11     10595682.93
      3728230.59     10595973.73
#Sta/Elev= 30
  4437.3  262.40  4475.0  256.47  4705.2  233.39  4775.2  228.13  4825.3  228.31
  4865.3  225.07  4915.3  217.21  4975.4  215.40  4988.9  212.61  4991.6  206.16
  4995.3  206.00  4998.1  205.50  5001.3  206.00  5005.8  212.17  5012.5  210.96
  5020.0  215.14  5055.1  214.61  5091.1  217.20  5104.9  220.73  5118.7  230.47
  5132.9  233.31  5161.3  243.65  5189.7  249.11  5281.7  252.14  5289.2  250.05
  5295.9  251.53  5352.7  249.70  5381.2  246.43  5402.8  247.76  5425.4  247.13
#Mann=4,-1,0
  4437.3    0.16       0  4995.3    0.07       0  5001.3    0.16       0
  5402.8    0.05       0
Bank Sta=4995.3,5001.3
Exp/Cntr=0.3,0.1

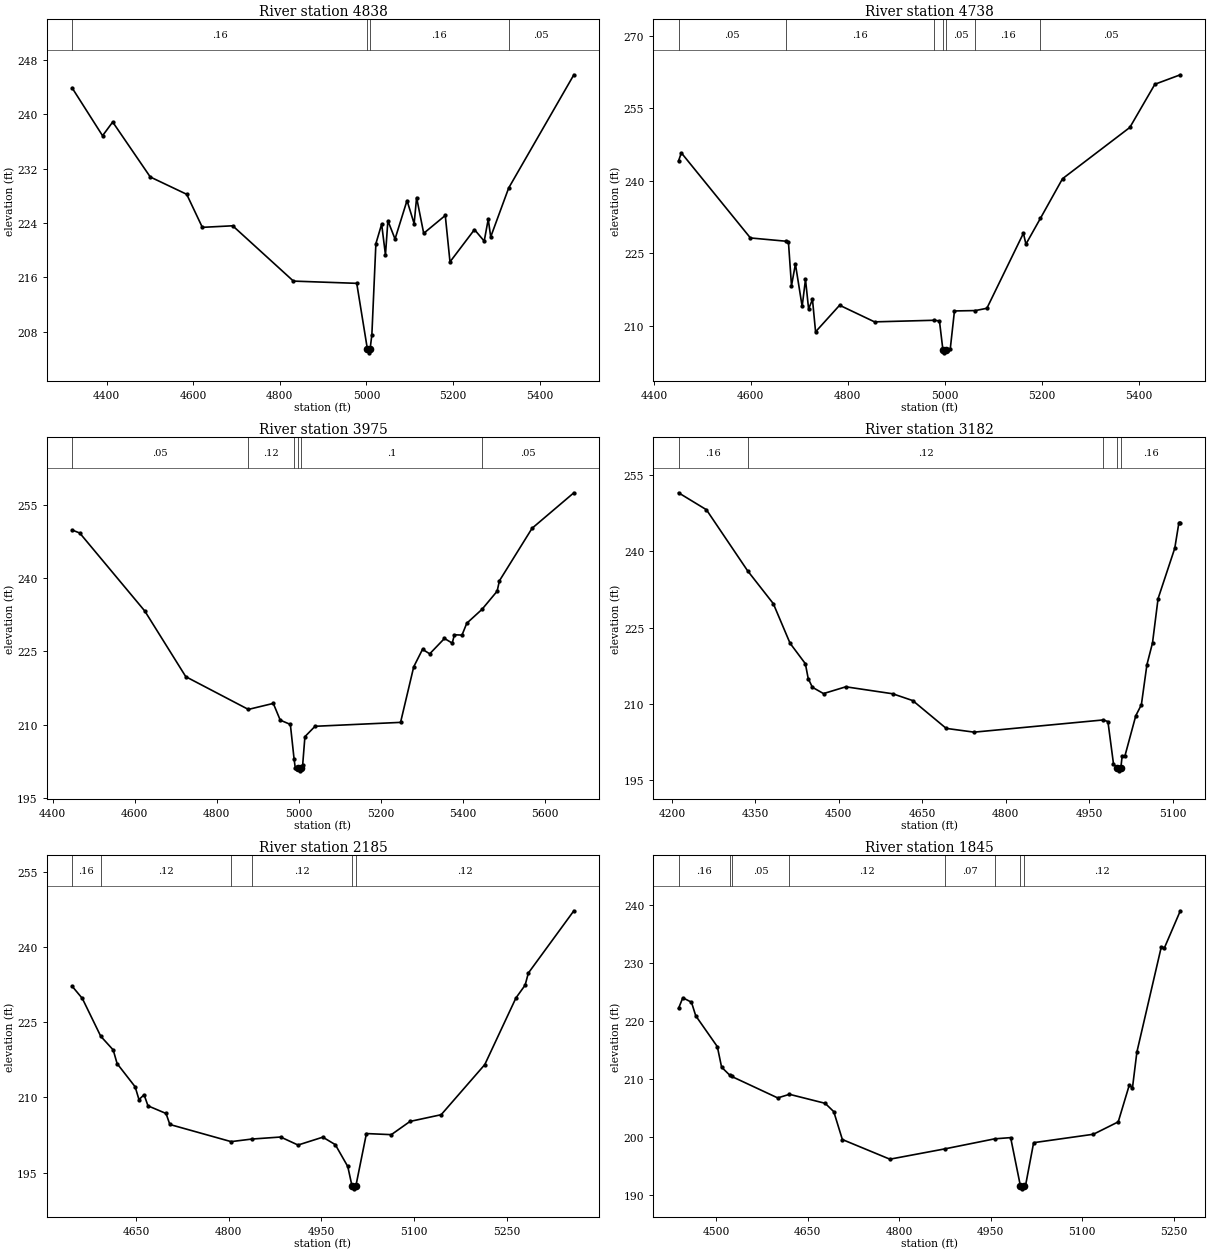
Type RM Length L Ch R = 1,4838,100,100,100
BEGIN DESCRIPTION:
Mapping XS f427b746
END DESCRIPTION:
XS GIS Cut Line= 3
      3729119.86     10595559.82      3728525.26     10595594.54
      3728026.13     10595854.96
#Sta/Elev= 30
  4320.3  243.91  4390.7  236.85  4414.1  238.87  4500.9  230.77  4585.0  228.22
  4621.1  223.35  4691.2  223.58  4831.4  215.43  4977.6  215.10  5002.3  205.36
  5005.1  204.86  5008.3  205.36  5012.5  207.51  5021.8  220.95  5035.1  223.82
  5043.9  219.29  5049.5  224.33  5066.0  221.63  5093.7  227.30  5110.1  223.89
  5115.8  227.74  5132.2  222.47  5182.0  225.10  5192.9  218.26  5249.4  223.02
  5271.9  221.32  5281.2  224.55  5286.9  221.94  5328.4  229.15  5478.9  245.83
#Mann=4,-1,0
  4320.3    0.16       0  5002.3    0.07       0  5008.3    0.16       0
  5328.4    0.05       0
Bank Sta=5002.3,5008.3
Exp/Cntr=0.3,0.1

Type RM Length L Ch R = 1,4738,763,763,763
BEGIN DESCRIPTION:
UNT 020 IN BOCR 7.0
END DESCRIPTION:
XS GIS Cut Line= 3
      3728899.02     10595231.52      3728556.11     10595504.98
      3727978.86     10595656.89
#Sta/Elev= 30
  4450.8  244.10  4456.6  245.77  4599.1  228.16  4671.7  227.49  4677.6  227.31
  4683.9  218.27  4692.0  222.75  4705.9  213.99  4712.8  219.59  4719.2  213.46
  4727.2  215.43  4733.6  208.73  4783.2  214.23  4855.3  210.79  4977.7  211.12
  4989.2  210.99  4996.5  204.88  4999.3  204.38  5002.5  204.88  5011.6  205.25
  5020.2  213.05  5063.4  213.13  5087.1  213.60  5162.5  229.13  5167.7  226.88
  5197.6  232.22  5243.2  240.42  5382.1  251.03  5433.8  259.97  5486.3  261.93
#Mann=7,-1,0
  4450.8    0.05       0  4671.7    0.16       0  4977.7    0.05       0
  4996.5    0.03       0  5002.5    0.05       0  5063.4    0.16       0
  5197.6    0.05       0
Bank Sta=4996.5,5002.5
Exp/Cntr=0.3,0.1

Type RM Length L Ch R = 1,3975,793,793,793
BEGIN DESCRIPTION:
UNT 020 IN BOCR 6.0
END DESCRIPTION:
XS GIS Cut Line= 3
      3729016.74     10594934.59      3728574.00     10594951.95
      3727844.80     10595229.74
#Sta/Elev= 30
  4447.4  249.80  4466.1  249.18  4624.7  233.23  4724.7  219.80  4877.2  213.11
  4938.0  214.34  4954.9  210.92  4979.6  210.04  4988.7  202.96  4991.5  201.20
  4999.2  201.05  5001.9  200.55  5005.2  201.05  5009.7  201.83  5015.1  207.54
  5039.8  209.66  5248.3  210.46  5280.4  221.83  5301.8  225.39  5319.4  224.48
  5355.3  227.62  5374.2  226.67  5379.6  228.37  5398.1  228.31  5409.7  230.73
  5446.8  233.57  5483.7  237.28  5489.3  239.41  5568.9  250.15  5670.8  257.41
#Mann=6,-1,0
  4447.4    0.05       0  4877.2    0.12       0  4988.7     0.1       0
  4999.2    0.07       0  5005.2     0.1       0  5446.8    0.05       0
Bank Sta=4999.2,5005.2
Exp/Cntr=0.3,0.1

Type RM Length L Ch R = 1,3182,997,997,997
BEGIN DESCRIPTION:
UNT 020 IN BOCR 5.0
END DESCRIPTION:
XS GIS Cut Line= 3
      3728749.58     10594610.19      3727953.60     10594662.11
      3727849.59     10594660.19
#Sta/Elev= 30
  4212.0  251.51  4262.1  248.18  4336.2  236.17  4382.3  229.73  4412.4  221.95
  4439.9  217.93  4445.0  215.02  4452.5  213.30  4472.5  212.06  4512.6  213.39
  4596.9  212.02  4632.9  210.68  4693.0  205.22  4743.1  204.48  4975.3  206.88
  4983.6  206.56  4993.6  198.24  5000.7  197.38  5003.4  196.88  5006.7  197.38
  5009.2  199.83  5014.2  199.83  5033.7  207.72  5043.7  209.86  5053.7  217.75
  5063.7  222.01  5073.7  230.71  5103.7  240.61  5111.2  245.66  5113.7  245.66
#Mann=5,-1,0
  4212.0    0.16       0  4336.2    0.12       0  4975.3    0.16       0
  5000.7    0.07       0  5006.7    0.16       0
Bank Sta=5000.7,5006.7
Exp/Cntr=0.3,0.1

Type RM Length L Ch R = 1,2185,340,340,340
BEGIN DESCRIPTION:
UNT 020 IN BOCR 4.0
END DESCRIPTION:
XS GIS Cut Line= 3
      3728733.31     10594488.57      3728444.25     10594272.43
      3727996.53     10594215.16
#Sta/Elev= 30
  4546.6  232.20  4563.2  229.75  4593.0  222.21  4613.2  219.47  4619.5  216.75
  4648.7  212.12  4654.9  209.57  4663.2  210.53  4669.5  208.32  4698.7  206.80
  4704.9  204.60  4804.0  201.18  4837.4  201.69  4884.2  202.10  4912.4  200.50
  4952.5  202.07  4972.7  200.58  4992.9  196.22  4999.9  192.26  5002.7  191.76
  5005.9  192.26  5023.1  202.79  5063.4  202.57  5093.7  205.21  5144.1  206.55
  5214.7  216.55  5265.1  229.84  5280.0  232.40  5285.2  234.81  5358.9  247.24
#Mann=6,-1,0
  4546.6    0.16       0  4593.0    0.12       0  4804.0    0.05       0
  4837.4    0.12       0  4999.9    0.07       0  5005.9    0.12       0
Bank Sta=4999.9,5005.9
Exp/Cntr=0.3,0.1

Type RM Length L Ch R = 1,1845,459,459,459
BEGIN DESCRIPTION:
UNT 020 IN BOCR 3.0
END DESCRIPTION:
XS GIS Cut Line= 3
      3728699.59     10593560.21      3728303.60     10593962.11
      3728049.62     10594010.19
#Sta/Elev= 30
  4438.4  222.15  4445.4  223.99  4459.6  223.22  4466.6  220.89  4502.0  215.58
  4509.0  212.05  4522.2  210.69  4525.4  210.46  4601.0  206.76  4620.3  207.38
  4678.8  205.83  4692.9  204.40  4707.0  199.60  4784.9  196.22  4875.8  198.01
  4956.6  199.72  4982.9  199.93  4998.9  191.62  5001.6  191.12  5004.9  191.62
  5007.2  191.62  5020.6  199.06  5118.6  200.51  5159.3  202.64  5177.5  209.00
  5182.6  208.47  5189.9  214.66  5229.9  232.74  5235.0  232.57  5261.1  238.95
#Mann=8,-1,0
  4438.4    0.16       0  4522.2    0.12       0  4525.4    0.05       0
  4620.3    0.12       0  4875.8    0.07       0  4956.6    0.12       0
  4998.9    0.07       0  5004.9    0.12       0
Bank Sta=4998.9,5004.9
Exp/Cntr=0.3,0.1

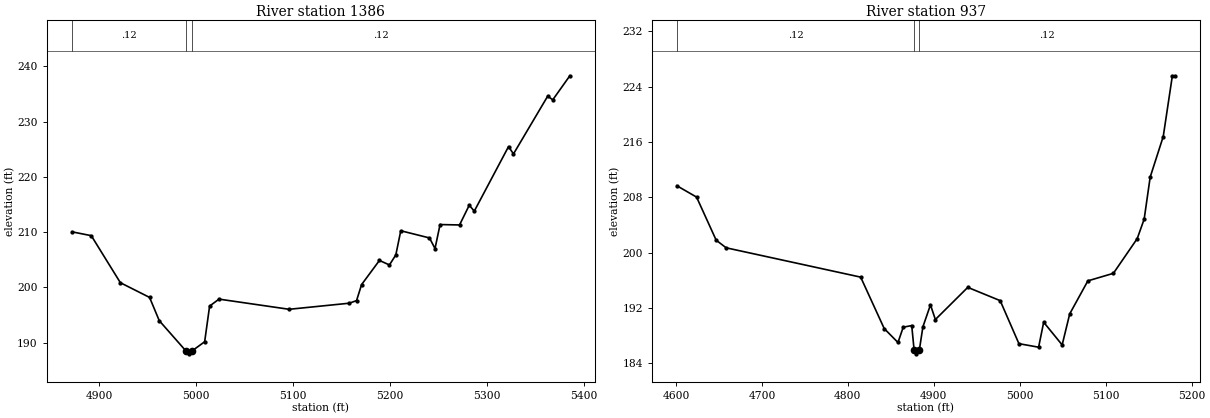
Type RM Length L Ch R = 1,1386,449,449,449
BEGIN DESCRIPTION:
UNT 020 IN BOCR 2.0
END DESCRIPTION:
XS GIS Cut Line= 3
      3728099.61     10593460.20      3728103.60     10593562.11
      3727999.62     10593960.16
#Sta/Elev= 30
  4872.1  210.06  4892.1  209.36  4922.1  200.85  4952.2  198.19  4962.2  193.98
  4989.8  188.48  4992.5  187.98  4995.8  188.48  5009.0  190.17  5014.1  196.62
  5023.8  197.88  5096.1  196.04  5158.1  197.14  5165.6  197.61  5170.8  200.51
  5189.2  204.88  5199.5  204.06  5206.1  205.88  5211.2  210.25  5240.8  208.95
  5246.5  207.03  5251.7  211.37  5271.8  211.30  5281.8  214.87  5287.0  213.80
  5322.3  225.48  5327.4  224.15  5362.7  234.61  5367.9  233.94  5385.5  238.29
#Mann=3,-1,0
  4872.1    0.12       0  4989.8    0.07       0  4995.8    0.12       0
Bank Sta=4989.8,4995.8
Exp/Cntr=0.3,0.1

Type RM Length L Ch R = 1,937,0,0,0
BEGIN DESCRIPTION:
UNT 020 IN BOCR 1.0
END DESCRIPTION:
XS GIS Cut Line= 3
      3727999.62     10593410.17      3727803.60     10593762.11
      3727899.59     10593910.16
#Sta/Elev= 30
  4601.1  209.65  4624.0  208.01  4646.8  201.78  4658.4  200.68  4814.9  196.44
  4842.3  189.00  4858.3  186.99  4864.4  189.20  4874.3  189.44  4877.1  185.85
  4879.8  185.35  4883.1  185.85  4887.3  189.26  4896.1  192.43  4901.8  190.31
  4939.5  194.96  4977.2  193.04  4999.0  186.82  5021.9  186.31  5027.8  189.92
  5049.3  186.64  5058.1  191.13  5079.2  195.90  5108.9  196.99  5136.6  202.00
  5144.7  204.82  5151.7  210.90  5166.9  216.77  5177.5  225.55  5180.4  225.55
#Mann=3,-1,0
  4601.1    0.12       0  4877.1    0.07       0  4883.1    0.12       0
Bank Sta=4877.1,4883.1
Exp/Cntr=0.3,0.1

Chan Stop Cuts=-1