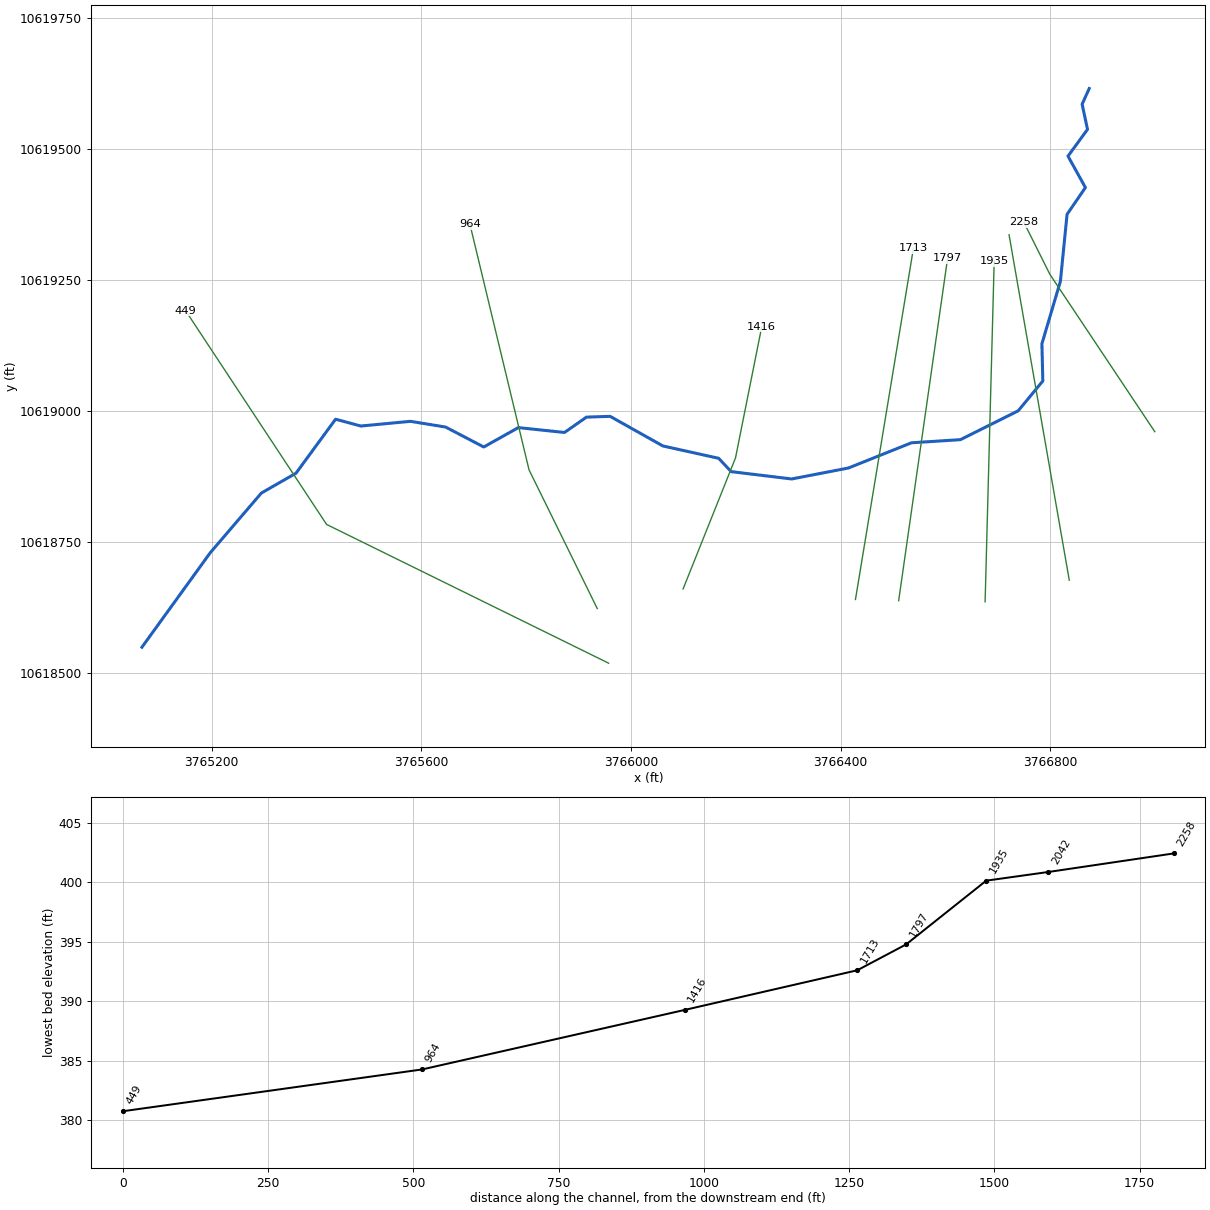
--- UNT 022 IN BOCR.prj (project) ---

Proj Title=UNT 022 IN BOCR Base Level Engineering
Current Plan=p01
Default Exp/Contr=0.3,0.1
English Units
Geom File=g01
Flow File=f01
Plan File=p01
Y Axis Title=Elevation
X Axis Title(PF)=Main Channel Distance
X Axis Title(XS)=Station
BEGIN DESCRIPTION:
UNT 022 IN BOCR
END DESCRIPTION:
DSS Export Rating Curves= 0
DSS Export Rating Curve Sorted= 0
DSS Export Volume Flow Curves= 0
DXF OffsetX= 0
DXF OffsetY= 0
DXF ScaleX= 1
DXF ScaleY= 10

--- UNT 022 IN BOCR.p01 (plan) ---

Plan Title=Multiple Run
Short Identifier=Multiple
Geom File=g01
Flow File=f01
Subcritical Flow
K Sum by GR= 0
Std Step Tol= 0.01
Critical Tol= 0.01
Num of Std Step Trials= 20
Max Error Tol= 0.3
Flow Tol Ratio= 0.001
Split Flow NTrial= 30
Split Flow Tol= 0.02
Split Flow Ratio= 0.02
Log Output Level= 0
Friction Slope Method= 1
Unsteady Friction Slope Method= 2
Unsteady Bridges Friction Slope Method= 1
Parabolic Critical Depth
Global Vel Dist=  1 , 1 , 1
Global Log Level= 0
CheckData=True
Encroach Param= -1, 0, 0, 0
BEGIN DESCRIPTION:
Multiple Run
END DESCRIPTION:

--- UNT 022 IN BOCR.f01 (steady flow) ---

Flow Title=Multiple
Program Version=4.10
Number of Profiles= 7
Profile Names=10-year,25-year,50-year,1pct_min,100-year,1pct_plu,500-year
River Rch & RM=UNT 022 IN BOCR,Reach-1         ,2258
     430     573     690     612     828    1120    1194
Boundary for River Rch & Prof#=UNT 022 IN BOCR,Reach-1         , 1
Up Type= 0
Dn Type= 3
Dn Slope=0.007
Boundary for River Rch & Prof#=UNT 022 IN BOCR,Reach-1         , 2
Up Type= 0
Dn Type= 3
Dn Slope=0.007
Boundary for River Rch & Prof#=UNT 022 IN BOCR,Reach-1         , 3
Up Type= 0
Dn Type= 3
Dn Slope=0.007
Boundary for River Rch & Prof#=UNT 022 IN BOCR,Reach-1         , 4
Up Type= 0
Dn Type= 3
Dn Slope=0.007
Boundary for River Rch & Prof#=UNT 022 IN BOCR,Reach-1         , 5
Up Type= 0
Dn Type= 3
Dn Slope=0.007
Boundary for River Rch & Prof#=UNT 022 IN BOCR,Reach-1         , 6
Up Type= 0
Dn Type= 3
Dn Slope=0.007
Boundary for River Rch & Prof#=UNT 022 IN BOCR,Reach-1         , 7
Up Type= 0
Dn Type= 3
Dn Slope=0.007
DSS Import GetInterval= 0
DSS Import GetPeak= 0
DSS Import FillOption= 0

--- UNT 022 IN BOCR.g01 (geometry) ---

Geom Title=Existing Conditions
Program Version=4.10

River Reach=UNT 022 IN BOCR ,Reach-1
Reach XY= 30
      3766874.51     10619615.01        3766861.       10619585.
      3766871.25       10619537.        3766834.       10619486.
      3766867.25       10619426.      3766832.25       10619375.
       3766819.5       10619247.      3766784.25       10619128.
        3766786.       10619057.        3766739.       10619000.
      3766628.75       10618945.      3766535.25       10618939.
      3766415.15     10618890.92      3766306.75       10618870.
      3766191.25       10618884.      3766167.49     10618909.41
        3766061.       10618933.      3765960.35     10618989.47
      3765915.25       10618988.      3765873.33      10618958.7
      3765785.25       10618968.      3765719.25       10618931.
       3765646.5       10618969.       3765579.5       10618980.
      3765484.75       10618971.       3765436.5       10618984.
        3765361.       10618881.      3765294.75       10618843.
      3765197.33     10618729.21        3765067.       10618549.

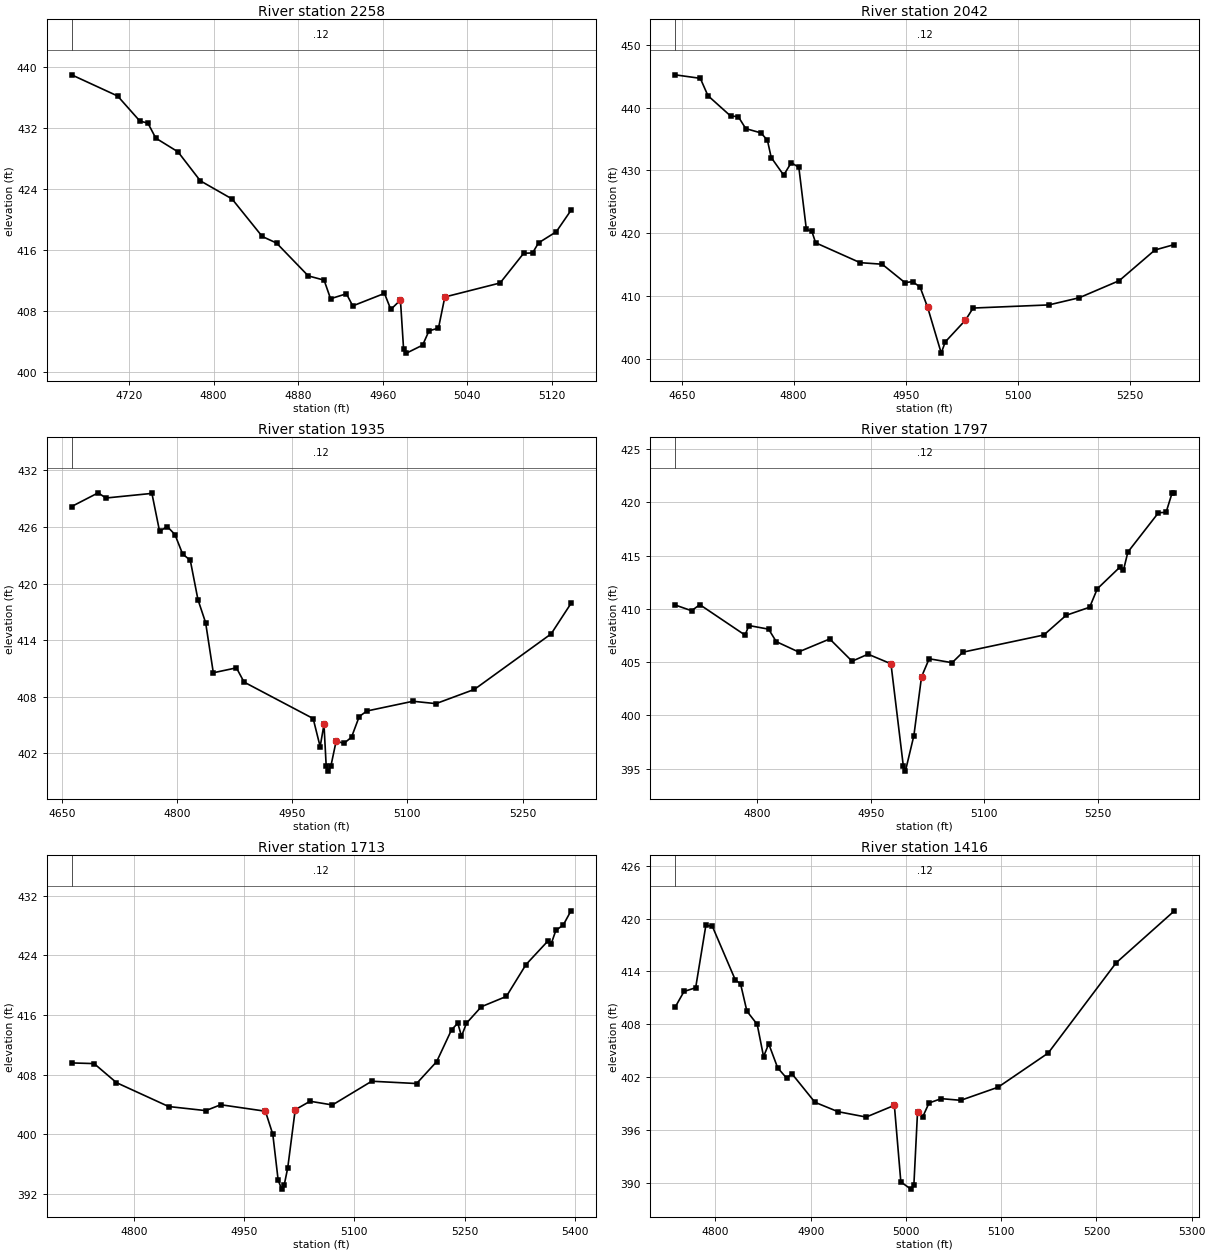
Type RM Length L Ch R = 1 ,2258    ,216,216,216
BEGIN DESCRIPTION:
UNT 022 IN BOCR 4.0
END DESCRIPTION:
XS GIS Cut Line= 3
       3766999.6     10618960.21      3766799.61     10619260.19
      3766749.63     10619360.15
#Sta/Elev= 30
  4665.7  438.95  4709.2  436.17  4730.3  432.87  4737.8  432.62  4745.3  430.64
  4766.3  428.84  4787.4  425.04  4817.4  422.66    4846  417.73  4859.5  416.87
  4889.5  412.56  4904.5     412  4910.6  409.56  4925.6  410.21  4931.6  408.62
  4961.6  410.26  4967.6  408.15  4976.7  409.39  4979.7  402.92  4982.4  402.42
  4997.7  403.47  5003.7  405.34  5012.7  405.71  5018.7  409.79    5071  411.63
  5093.3  415.53  5101.7  415.57  5107.3  416.89  5124.1  418.35    5138  421.16
#Mann= 1 ,-1 , 0
  4665.7     .12       0
Bank Sta=4976.7,5018.7
XS Rating Curve= 0 ,0
Exp/Cntr=0.3,0.1

Type RM Length L Ch R = 1 ,2042    ,107,107,107
BEGIN DESCRIPTION:
Mapping XS 68e3955d
END DESCRIPTION:
XS GIS Cut Line= 2
      3766836.46     10618676.86      3766721.56     10619335.92
#Sta/Elev= 30
  4641.1  445.25  4674.9  444.69  4685.1  441.93  4715.5  438.68  4725.7  438.59
  4735.8  436.67  4756.1  435.99  4764.8  434.82  4769.9  432.06  4786.6  429.25
  4796.7  431.23  4806.9   430.5    4817  420.58  4824.3  420.31  4829.4  418.46
    4889  415.29  4918.6  415.04    4949  412.11  4959.2  412.26  4969.3  411.41
  4979.5  408.15  4997.7  400.86    5003  402.64  5030.2  406.13  5040.4  408.05
  5141.9  408.55  5182.5  409.69  5236.2  412.42    5284  417.31  5310.1  418.18
#Mann= 1 ,-1 , 0
  4641.1     .12       0
Bank Sta=4979.5,5030.2
XS Rating Curve= 0 ,0
Exp/Cntr=0.3,0.1

Type RM Length L Ch R = 1 ,1935    ,138,138,138
BEGIN DESCRIPTION:
Mapping XS 4768c20c
END DESCRIPTION:
XS GIS Cut Line= 2
      3766675.87     10618635.61      3766693.21     10619285.98
#Sta/Elev= 30
  4662.5  428.16  4697.1  429.61  4707.1  429.06  4767.1  429.55  4777.1  425.53
  4787.1  426.04  4797.1  425.19  4807.1  423.13  4817.1  422.46  4827.1  418.29
  4837.1  415.85  4847.1  410.55  4877.2  411.07  4887.2  409.56  4977.2   405.7
  4986.3  402.72  4991.3  405.07  4994.2  400.63  4996.9  400.13  5000.2  400.63
  5007.2  403.33  5017.2  403.06  5027.2  403.73  5037.2  405.91  5047.2   406.5
  5107.2  407.53  5137.2  407.28  5187.3  408.79  5287.3  414.67  5313.1  417.89
#Mann= 1 ,-1 , 0
  4662.5     .12       0
Bank Sta=4991.3,5007.2
XS Rating Curve= 0 ,0
Exp/Cntr=0.3,0.1

Type RM Length L Ch R = 1 ,1797    ,84,84,84
BEGIN DESCRIPTION:
UNT 022 IN BOCR 3.0
END DESCRIPTION:
XS GIS Cut Line= 2
      3766510.93      10618637.8      3766604.26     10619291.06
#Sta/Elev= 30
  4691.4  410.37  4713.2  409.83  4724.1   410.4  4783.9  407.54  4788.9  408.44
    4815   408.1  4825.1  406.93  4854.6  405.96  4895.8  407.18  4925.3  405.09
  4946.4  405.75  4976.7  404.85    4993  395.27  4995.8  394.77    5007  398.11
  5017.1  403.63  5027.2  405.32  5057.5  404.95  5071.8  405.94  5178.7  407.55
  5208.2   409.4  5239.3  410.16  5249.4  411.89  5278.9   413.9  5283.9  413.62
  5289.8  415.34  5330.2  419.03  5340.3  419.07  5348.3   420.9  5351.3   420.9
#Mann= 1 ,-1 , 0
  4691.4     .12       0
Bank Sta=4976.7,5017.1
XS Rating Curve= 0 ,0
Exp/Cntr=0.3,0.1

Type RM Length L Ch R = 1 ,1713    ,297,297,297
BEGIN DESCRIPTION:
Mapping XS 18ebea75
END DESCRIPTION:
XS GIS Cut Line= 2
      3766428.47       10618640.      3766539.14     10619310.53
#Sta/Elev= 30
  4715.2  409.56  4745.8  409.47  4776.2  406.91  4847.2   403.7  4897.8  403.15
  4918.1  403.94  4978.9  403.07    4989  399.97  4996.3  393.79  5001.1   392.6
  5004.4   393.1  5009.3  395.45  5019.5  403.27  5039.7  404.41  5070.1  403.91
  5123.6   407.1  5184.7  406.79    5212  409.73  5232.3  414.02  5240.8   414.9
  5245.8  413.14  5252.6   414.9  5272.8  417.11  5306.9   418.5  5333.6  422.78
    5363   425.9    5368  425.59  5374.2  427.37  5384.3  428.09  5394.8     430
#Mann= 1 ,-1 , 0
  4715.2     .12       0
Bank Sta=4978.9,5019.5
XS Rating Curve= 0 ,0
Exp/Cntr=0.3,0.1

Type RM Length L Ch R = 1 ,1416    ,452,452,452
BEGIN DESCRIPTION:
UNT 022 IN BOCR 2.0
END DESCRIPTION:
XS GIS Cut Line= 3
       3766099.6     10618660.17      3766199.61     10618910.19
       3766249.6     10619160.16
#Sta/Elev= 30
  4757.7  409.93  4767.1  411.73  4779.3  412.15    4790  419.23  4796.8  419.14
    4821  413.02  4826.4  412.61  4833.1  409.49  4843.9  407.99  4850.6  404.32
    4856  405.78  4865.4  403.05  4874.9  401.87  4880.2   402.4  4904.5  399.14
  4928.7  398.07  4958.3  397.46  4987.9  398.79  4994.7  390.09  5005.2  389.27
  5008.4  389.77  5012.2  397.98  5017.6  397.46  5024.3  399.06  5037.2  399.55
  5057.6  399.36  5096.8  400.85  5149.4  404.73  5220.7  414.98  5281.9  420.89
#Mann= 1 ,-1 , 0
  4757.7     .12       0
Bank Sta=4987.9,5012.2
XS Rating Curve= 0 ,0
Exp/Cntr=0.3,0.1

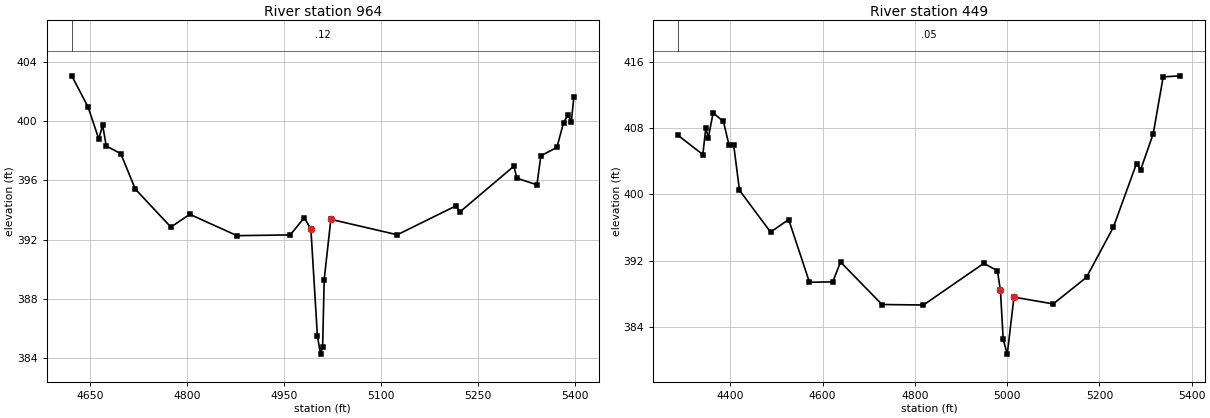
Type RM Length L Ch R = 1 ,964     ,515,515,515
BEGIN DESCRIPTION:
Mapping XS 34cc217b
END DESCRIPTION:
XS GIS Cut Line= 3
      3765935.84     10618622.64      3765805.64     10618887.39
       3765692.9     10619355.68
#Sta/Elev= 30
    4622  403.04  4647.3  400.93  4663.8  398.78  4669.8  399.71  4675.3  398.31
  4697.8  397.79  4720.3   395.4  4775.3  392.84  4804.6   393.7  4877.6  392.26
    4960  392.31  4981.6  393.47  4991.9  392.72    5002  385.49  5006.9  384.27
  5010.1  384.77  5012.5   389.3  5022.8  393.36  5125.6  392.32  5216.8  394.28
  5221.9  393.84  5305.8  396.94  5310.9  396.13  5341.6  395.69  5347.7  397.65
  5372.5  398.21  5382.8  399.88  5389.7   400.4  5394.8  399.95  5398.7  401.59
#Mann= 1 ,-1 , 0
    4622     .12       0
Bank Sta=4991.9,5022.8
XS Rating Curve= 0 ,0
Exp/Cntr=0.3,0.1

Type RM Length L Ch R = 1 ,449     ,0,0,0
BEGIN DESCRIPTION:
UNT 022 IN BOCR 1.0
END DESCRIPTION:
XS GIS Cut Line= 3
      3765957.55     10618518.47      3765419.36     10618783.22
      3765150.27     10619191.19
#Sta/Elev= 30
  4286.9  407.11  4340.3  404.81  4346.7  408.02  4352.2  406.86  4362.6  409.83
  4384.9   408.8  4397.2  405.93  4407.2  405.95  4419.7  400.51  4487.1  395.47
  4526.4  396.98  4571.4  389.42  4621.9  389.47  4638.8  391.86  4728.7  386.74
  4818.6  386.68  4949.4   391.7  4978.9  390.81  4985.5  388.44  4991.5  382.54
  5000.3  380.76  5014.8  387.63  5099.9  386.81  5172.1  390.02  5230.4  396.06
  5280.5  403.73  5289.6     403  5316.7  407.31  5338.3  414.17  5375.4   414.3
#Mann= 1 ,-1 , 0
  4286.9     .05       0
Bank Sta=4985.5,5014.8
XS Rating Curve= 0 ,0
Exp/Cntr=0.3,0.1

Chan Stop Cuts=-1
Use User Specified Reach Order=0
Composite Channel Slope=5