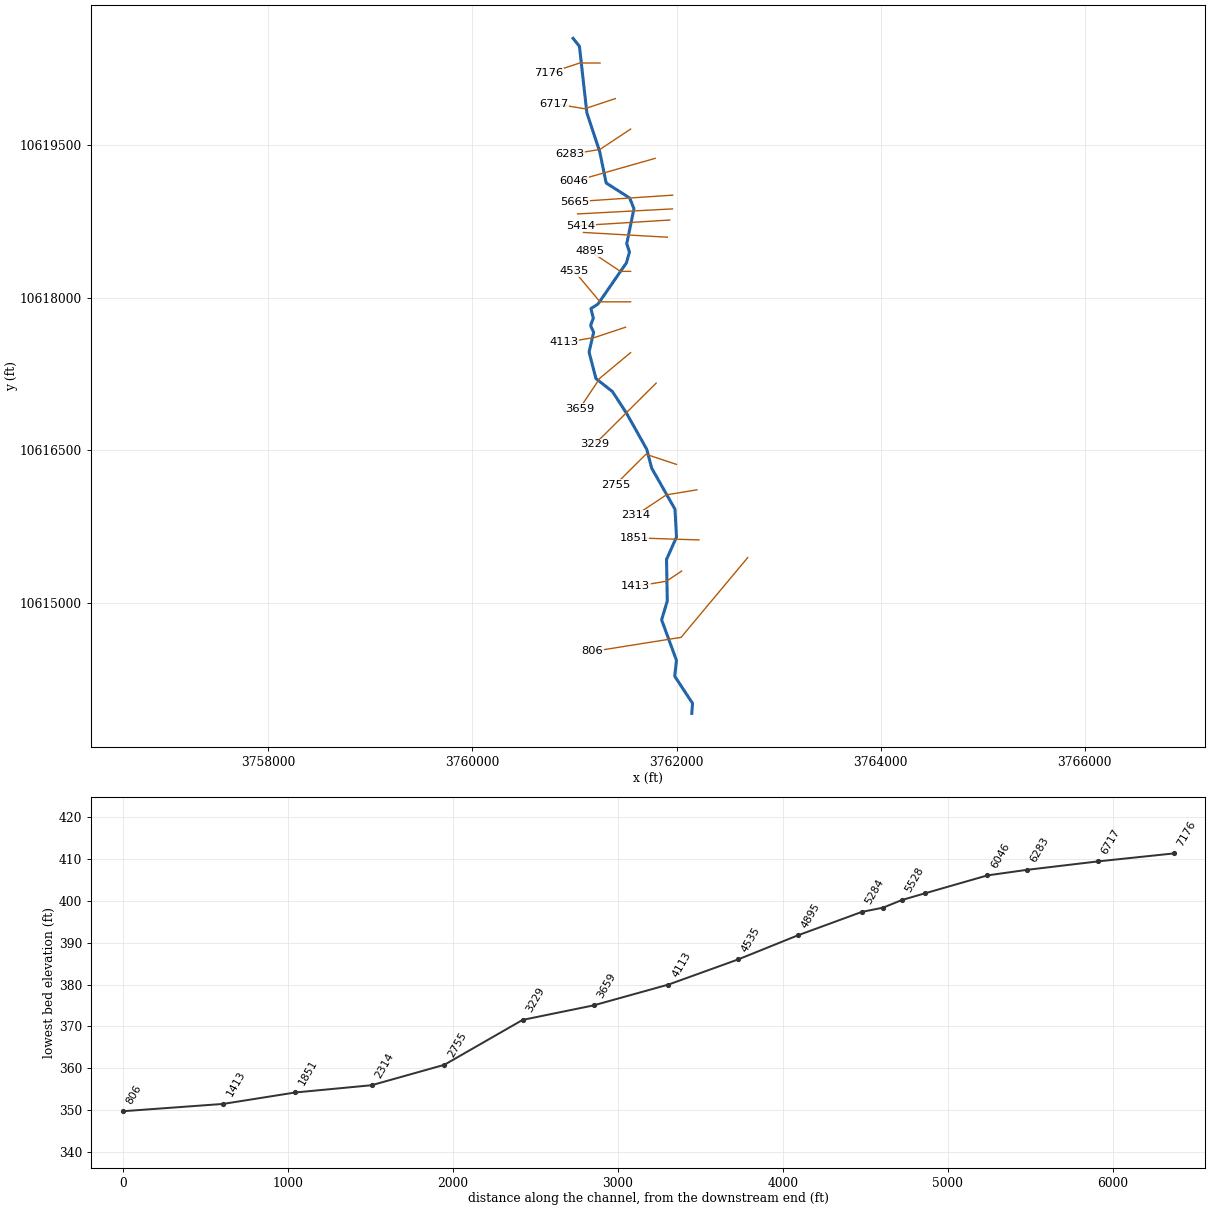
--- UNT 024 IN BOCR.prj (project) ---

Proj Title=UNT 024 IN BOCR Base Level Engineering
Current Plan=p01
Default Exp/Contr=0.3,0.1
English Units
Geom File=g01
Flow File=f01
Plan File=p01
BEGIN DESCRIPTION:
UNT 024 IN BOCR
END DESCRIPTION:

--- UNT 024 IN BOCR.p01 (plan) ---

Plan Title=Multiple Run
Short Identifier=Multiple
Geom File=g01
Flow File=f01
Subcritical Flow
K Sum by GR= 0
Std Step Tol= 0.01
Critical Tol= 0.01
Num of Std Step Trials= 20
Max Error Tol= 0.3
Flow Tol Ratio= 0.001
Split Flow NTrial= 30
Split Flow Tol= 0.02
Split Flow Ratio= 0.02
Log Output Level= 0
Friction Slope Method= 1
Unsteady Friction Slope Method= 2
Unsteady Bridges Friction Slope Method= 1
Parabolic Critical Depth
Global Vel Dist=  1 , 1 , 1
Global Log Level= 0
CheckData=True
Encroach Param= -1, 0, 0, 0
BEGIN DESCRIPTION:
Multiple Run
END DESCRIPTION:

--- UNT 024 IN BOCR.f01 (steady flow) ---

Flow Title=Multiple
Number of Profiles=7
Profile Names=10-year,25-year,50-year,1pct_min,100-year,1pct_plu,500-year
River Rch & RM= UNT 024 IN BOCR,Reach-1,7176
     746    1029    1267    1147    1551    2098    2334
Boundary for River Rch & Prof#=UNT 024 IN BOCR,Reach-1,1
Up Type=0
Dn Type=3
Dn Slope=0.005
Boundary for River Rch & Prof#=UNT 024 IN BOCR,Reach-1,2
Up Type=0
Dn Type=3
Dn Slope=0.005
Boundary for River Rch & Prof#=UNT 024 IN BOCR,Reach-1,3
Up Type=0
Dn Type=3
Dn Slope=0.005
Boundary for River Rch & Prof#=UNT 024 IN BOCR,Reach-1,4
Up Type=0
Dn Type=3
Dn Slope=0.005
Boundary for River Rch & Prof#=UNT 024 IN BOCR,Reach-1,5
Up Type=0
Dn Type=3
Dn Slope=0.005
Boundary for River Rch & Prof#=UNT 024 IN BOCR,Reach-1,6
Up Type=0
Dn Type=3
Dn Slope=0.005
Boundary for River Rch & Prof#=UNT 024 IN BOCR,Reach-1,7
Up Type=0
Dn Type=3
Dn Slope=0.005

--- UNT 024 IN BOCR.g01 (geometry) ---

Geom Title=Existing Conditions

River Reach=UNT 024 IN BOCR,Reach-1
Reach XY= 30
      3760985.54     10620553.31      3761048.00     10620475.00
      3761120.75     10619820.00      3761246.50     10619439.00
      3761309.75     10619130.00      3761540.57     10618981.67
      3761582.12     10618876.58      3761511.42     10618531.40
      3761538.50     10618451.00      3761508.50     10618344.00
      3761229.50     10617938.00      3761160.75     10617894.00
      3761183.75     10617800.00      3761157.25     10617727.00
      3761187.25     10617660.00      3761142.25     10617466.00
      3761209.75     10617205.00      3761371.50     10617077.00
      3761508.25     10616866.00      3761707.75     10616509.00
      3761756.00     10616323.00      3761984.50     10615919.00
      3761999.25     10615645.00      3761901.50     10615425.00
      3761909.00     10615016.00      3761853.25     10614831.00
      3761999.00     10614431.00      3761981.75     10614276.00
      3762156.25     10614009.00      3762149.00     10613910.00

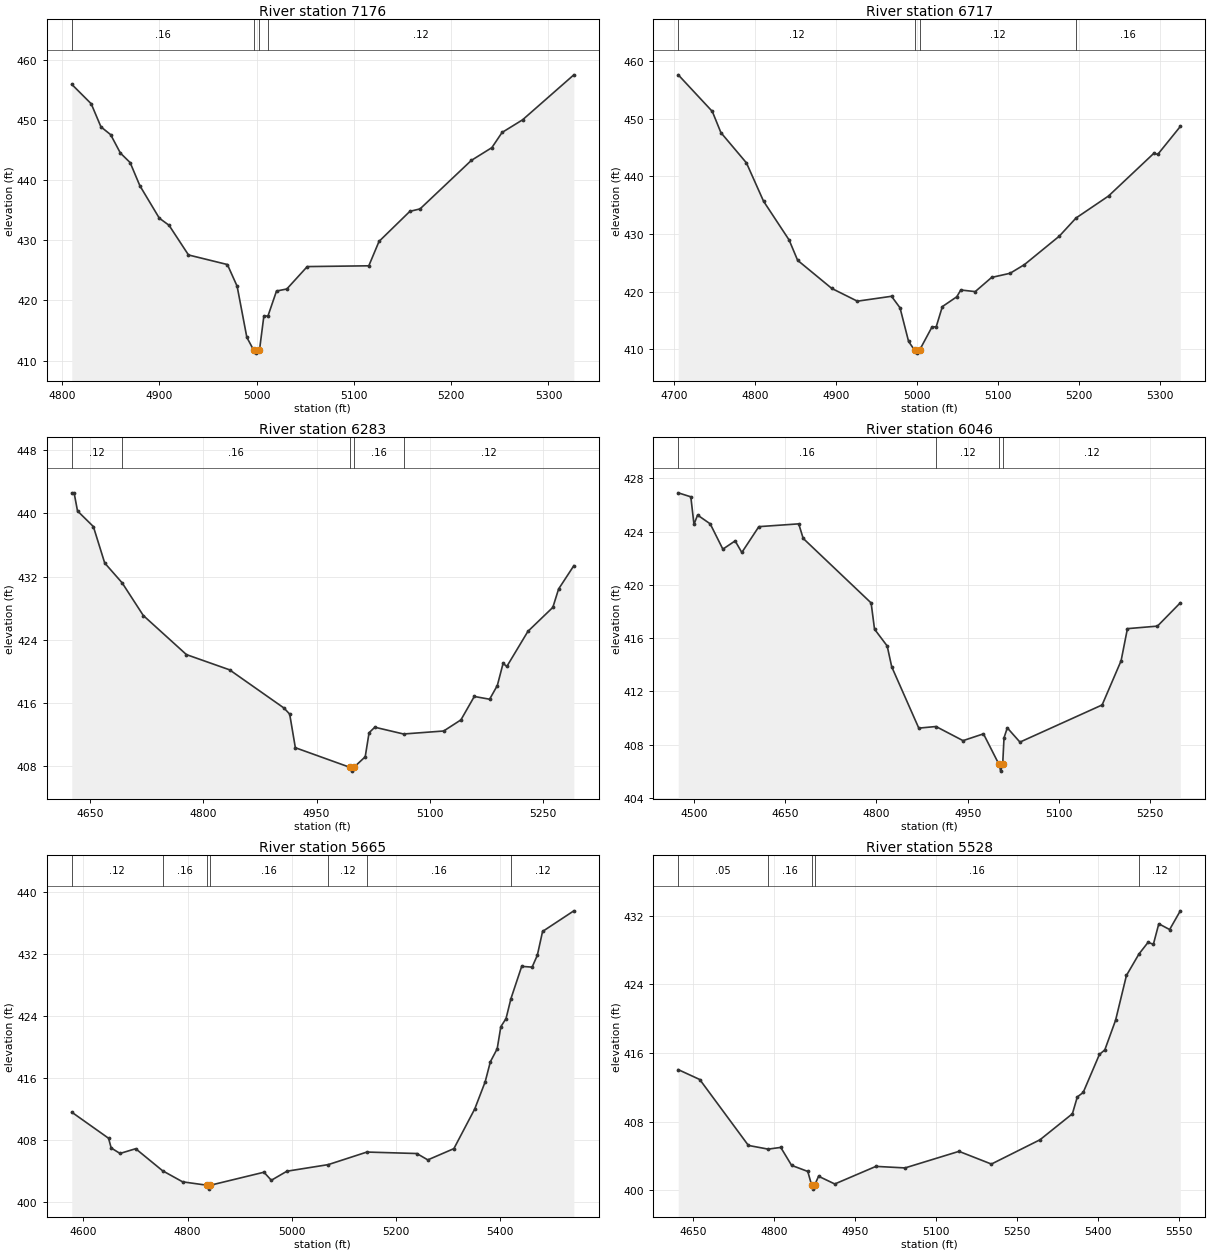
Type RM Length L Ch R = 1,7176,459,459,459
BEGIN DESCRIPTION:
UNT 024 IN BOCR 15.0
END DESCRIPTION:
XS GIS Cut Line= 3
      3761249.59     10620310.19      3761049.61     10620310.19
      3760749.62     10620210.19
#Sta/Elev= 30
  4809.9  455.88  4829.9  452.65  4839.9  448.82  4849.9  447.52  4859.9  444.47
  4869.9  442.89  4879.9  439.05  4899.9  433.66  4909.9  432.48  4929.9  427.55
  4969.9  425.96  4979.9  422.36  4989.9  413.87  4996.9  411.75  4999.6  411.25
  5002.9  411.75  5007.4  417.41  5011.6  417.41  5020.4  421.56  5031.0  421.90
  5052.0  425.62  5115.3  425.75  5125.8  429.80  5157.5  434.79  5168.0  435.20
  5220.7  443.25  5241.8  445.37  5252.3  447.89  5273.4  449.99  5326.1  457.46
#Mann=4,-1,0
  4809.9    0.16       0  4996.9    0.07       0  5002.9    0.16       0
  5011.6    0.12       0
Bank Sta=4996.9,5002.9
Exp/Cntr=0.3,0.1

Type RM Length L Ch R = 1,6717,434,434,434
BEGIN DESCRIPTION:
UNT 024 IN BOCR 14.0
END DESCRIPTION:
XS GIS Cut Line= 3
      3761399.58     10619960.18      3761099.61     10619860.19
      3760799.64     10619910.18
#Sta/Elev= 30
  4705.4  457.62  4747.5  451.27  4758.1  447.60  4789.7  442.34  4810.8  435.70
  4842.4  428.97  4852.9  425.45  4895.1  420.57  4926.7  418.36  4968.9  419.21
  4979.4  417.21  4990.0  411.37  4997.5  409.85  5000.3  409.35  5003.5  409.85
  5019.0  413.91  5024.1  413.91  5031.7  417.42  5049.5  419.12  5054.5  420.30
  5072.3  420.02  5092.6  422.48  5115.4  423.20  5133.1  424.70  5176.2  429.64
  5196.9  432.79  5237.0  436.60  5292.8  443.98  5297.9  443.83  5325.7  448.66
#Mann=4,-1,0
  4705.4    0.12       0  4997.5    0.07       0  5003.5    0.12       0
  5196.9    0.16       0
Bank Sta=4997.5,5003.5
Exp/Cntr=0.3,0.1

Type RM Length L Ch R = 1,6283,237,237,237
BEGIN DESCRIPTION:
UNT 024 IN BOCR 13.0
END DESCRIPTION:
XS GIS Cut Line= 3
      3761549.65     10619660.21      3761249.61     10619460.19
      3760949.65     10619410.19
#Sta/Elev= 30
  4625.9  442.62  4629.0  442.62  4633.5  440.32  4654.5  438.34  4669.5  433.72
  4692.6  431.20  4720.6  427.06  4777.7  422.10  4834.8  420.17  4906.9  415.32
  4914.4  414.55  4921.9  410.29  4993.6  407.82  4996.4  407.32  4999.6  407.82
  5014.4  409.14  5019.5  412.19  5027.1  412.89  5065.1  412.03  5118.3  412.41
  5141.1  413.82  5158.8  416.79  5179.1  416.44  5189.3  418.18  5196.9  420.98
  5201.9  420.60  5229.8  425.05  5262.8  428.09  5270.4  430.42  5290.6  433.38
#Mann=5,-1,0
  4625.9    0.12       0  4692.6    0.16       0  4993.6    0.07       0
  4999.6    0.16       0  5065.1    0.12       0
Bank Sta=4993.6,4999.6
Exp/Cntr=0.3,0.1

Type RM Length L Ch R = 1,6046,381,381,381
BEGIN DESCRIPTION:
Mapping XS e3fd97eb
END DESCRIPTION:
XS GIS Cut Line= 2
      3761790.16     10619372.12      3760995.94     10619145.57
#Sta/Elev= 30
  4473.9  426.91  4494.6  426.61  4499.8  424.54  4505.7  425.24  4526.5  424.58
  4547.3  422.68  4567.5  423.30  4578.5  422.43  4606.5  424.37  4672.1  424.58
  4679.4  423.49  4791.2  418.64  4796.8  416.67  4817.6  415.41  4825.1  413.84
  4869.6  409.24  4897.9  409.36  4942.4  408.30  4976.0  408.81  5001.6  406.51
  5004.3  406.01  5007.6  406.51  5009.8  408.51  5015.2  409.26  5036.0  408.19
  5171.2  410.98  5202.4  414.30  5212.8  416.71  5262.2  416.90  5299.8  418.65
#Mann=4,-1,0
  4473.9    0.16       0  4897.9    0.12       0  5001.6    0.07       0
  5007.6    0.12       0
Bank Sta=5001.6,5007.6
Exp/Cntr=0.3,0.1

Type RM Length L Ch R = 1,5665,137,137,137
BEGIN DESCRIPTION:
Mapping XS 8e5f53fc
END DESCRIPTION:
XS GIS Cut Line= 2
      3761962.10     10619010.15      3760999.60     10618945.12
#Sta/Elev= 30
  4577.5  411.63  4648.2  408.27  4653.2  407.02  4670.2  406.31  4700.3  406.92
  4752.0  404.08  4790.5  402.65  4837.6  402.21  4840.3  401.71  4843.6  402.21
  4946.8  403.89  4960.9  402.85  4990.9  404.02  5070.3  404.87  5144.6  406.49
  5240.5  406.30  5261.6  405.48  5311.7  406.93  5351.8  412.05  5371.8  415.54
  5381.8  418.13  5394.9  419.80  5401.9  422.65  5411.9  423.70  5421.3  426.26
  5442.0  430.43  5462.0  430.33  5472.0  431.85  5482.1  434.93  5542.2  437.59
#Mann=7,-1,0
  4577.5    0.12       0  4752.0    0.16       0  4837.6    0.07       0
  4843.6    0.16       0  5070.3    0.12       0  5144.6    0.16       0
  5421.3    0.12       0
Bank Sta=4837.6,4843.6
Exp/Cntr=0.3,0.1

Type RM Length L Ch R = 1,5528,114,114,114
BEGIN DESCRIPTION:
UNT 024 IN BOCR 12.0
END DESCRIPTION:
XS GIS Cut Line= 2
      3761959.49     10618874.74      3761029.80     10618825.26
#Sta/Elev= 30
  4622.1  414.07  4662.0  412.92  4752.2  405.24  4788.8  404.81  4812.2  405.01
  4832.3  402.92  4862.3  402.21  4869.3  400.65  4872.1  400.15  4875.3  400.65
  4882.3  401.65  4912.4  400.75  4988.7  402.80  5042.6  402.62  5142.7  404.55
  5202.8  403.07  5292.9  405.90  5353.0  408.93  5362.1  410.89  5373.0  411.41
  5403.1  415.84  5413.1  416.37  5433.1  419.83  5453.2  425.04  5476.4  427.54
  5493.2  428.89  5503.2  428.68  5513.2  431.06  5533.3  430.39  5553.1  432.57
#Mann=5,-1,0
  4622.1    0.05       0  4788.8    0.16       0  4869.3    0.07       0
  4875.3    0.16       0  5476.4    0.12       0
Bank Sta=4869.3,4875.3
Exp/Cntr=0.3,0.1

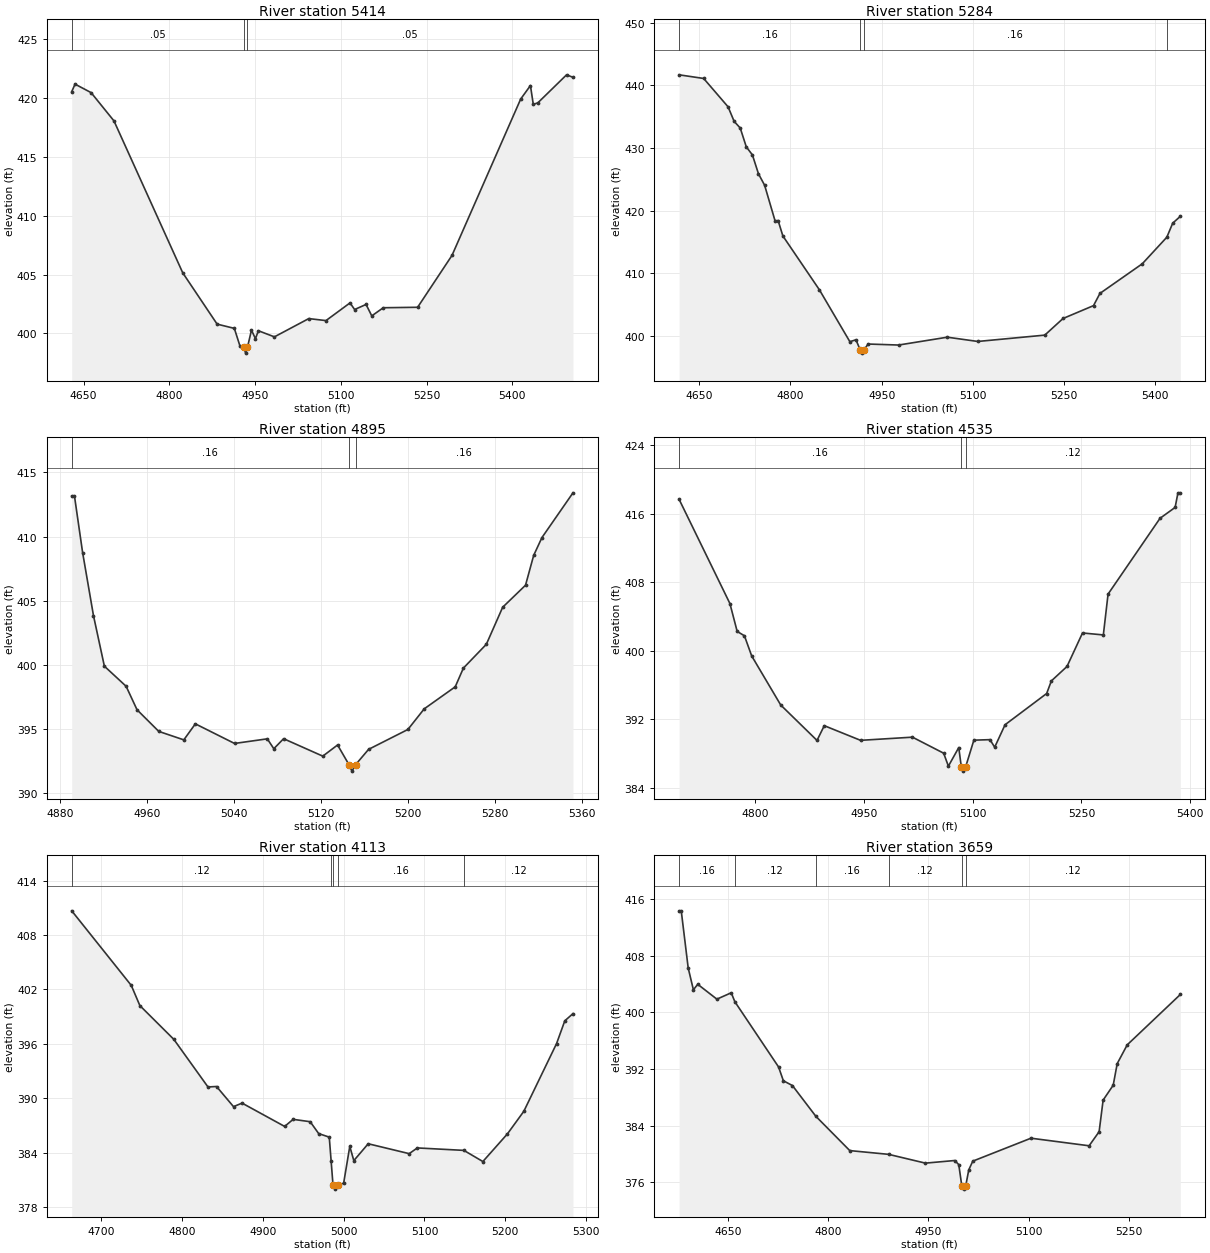
Type RM Length L Ch R = 1,5414,130,130,130
BEGIN DESCRIPTION:
UNT 024 IN BOCR 11.0
END DESCRIPTION:
XS GIS Cut Line= 2
      3761933.41     10618765.36      3761058.42     10618710.67
#Sta/Elev= 30
  4629.2  420.51  4635.0  421.15  4663.1  420.43  4703.1  418.03  4823.4  405.14
  4883.5  400.79  4913.6  400.43  4923.6  398.91  4930.6  398.83  4933.3  398.33
  4936.6  398.83  4943.6  400.28  4950.6  399.55  4955.6  400.23  4983.7  399.71
  5043.8  401.26  5073.9  401.09  5115.9  402.59  5124.0  402.03  5144.0  402.46
  5154.0  401.49  5174.1  402.18  5234.2  402.22  5294.3  406.62  5414.5  419.89
  5431.5  421.03  5436.5  419.43  5444.6  419.57  5494.7  421.94  5505.9  421.73
#Mann=3,-1,0
  4629.2    0.05       0  4930.6    0.04       0  4936.6    0.05       0
Bank Sta=4930.6,4936.6
Exp/Cntr=0.3,0.1

Type RM Length L Ch R = 1,5284,389,389,389
BEGIN DESCRIPTION:
Mapping XS 62d78b8a
END DESCRIPTION:
XS GIS Cut Line= 2
      3761909.94     10618596.09      3761087.07     10618642.96
#Sta/Elev= 30
  4616.9  441.66  4657.3  441.08  4697.4  436.56  4707.4  434.24  4717.4  433.18
  4727.4  430.17  4737.4  428.90  4747.4  425.88  4757.5  424.06  4774.7  418.38
  4779.7  418.43  4787.5  415.98  4847.6  407.39  4897.7  399.12  4907.7  399.43
  4914.7  397.80  4917.5  397.30  4920.7  397.80  4927.7  398.75  4977.8  398.59
  5057.9  399.84  5108.0  399.16  5218.2  400.17  5248.2  402.82  5298.3  404.87
  5308.9  406.82  5378.5  411.54  5418.9  415.78  5428.5  418.01  5441.1  419.11
#Mann=4,-1,0
  4616.9    0.16       0  4914.7    0.07       0  4920.7    0.16       0
  5418.9    0.05       0
Bank Sta=4914.7,4920.7
Exp/Cntr=0.3,0.1

Type RM Length L Ch R = 1,4895,360,360,360
BEGIN DESCRIPTION:
UNT 024 IN BOCR 10.0
END DESCRIPTION:
XS GIS Cut Line= 3
      3761549.65     10618260.19      3761449.61     10618260.19
      3761149.61     10618460.19
#Sta/Elev= 30
  4891.0  413.17  4893.5  413.17  4901.0  408.75  4911.0  403.82  4921.0  399.88
  4941.0  398.31  4951.0  396.48  4971.0  394.79  4994.0  394.13  5004.6  395.38
  5040.6  393.85  5070.7  394.21  5076.7  393.44  5085.7  394.22  5121.7  392.86
  5135.3  393.73  5145.8  392.19  5148.5  391.69  5151.8  392.19  5163.8  393.39
  5199.9  394.94  5214.9  396.55  5243.4  398.27  5250.9  399.73  5272.0  401.59
  5287.0  404.48  5308.0  406.20  5315.5  408.53  5323.1  409.92  5351.6  413.41
#Mann=3,-1,0
  4891.0    0.16       0  5145.8    0.07       0  5151.8    0.16       0
Bank Sta=5145.8,5151.8
Exp/Cntr=0.3,0.1

Type RM Length L Ch R = 1,4535,422,422,422
BEGIN DESCRIPTION:
UNT 024 IN BOCR 9.0
END DESCRIPTION:
XS GIS Cut Line= 3
      3761549.65     10617960.19      3761249.61     10617960.19
      3760999.58     10618260.22
#Sta/Elev= 30
  4695.6  417.67  4765.6  405.52  4775.6  402.27  4785.6  401.76  4795.6  399.41
  4835.6  393.69  4885.6  389.56  4895.6  391.28  4945.6  389.57  5017.1  389.94
  5060.1  388.07  5066.6  386.56  5080.9  388.73  5084.4  386.48  5087.2  385.98
  5090.4  386.48  5101.7  389.59  5123.9  389.65  5130.4  388.77  5144.7  391.39
  5202.0  395.03  5208.5  396.50  5230.0  398.18  5251.4  402.09  5280.1  401.86
  5286.6  406.62  5358.2  415.46  5379.0  416.73  5382.9  418.43  5386.2  418.43
#Mann=3,-1,0
  4695.6    0.16       0  5084.4    0.07       0  5090.4    0.12       0
Bank Sta=5084.4,5090.4
Exp/Cntr=0.3,0.1

Type RM Length L Ch R = 1,4113,454,454,454
BEGIN DESCRIPTION:
UNT 024 IN BOCR 8.0
END DESCRIPTION:
XS GIS Cut Line= 3
      3761499.57     10617710.18      3761199.61     10617610.19
      3760899.63     10617560.19
#Sta/Elev= 30
  4663.5  410.66  4737.2  402.44  4747.8  400.22  4789.9  396.49  4832.1  391.25
  4842.7  391.30  4863.7  389.08  4874.3  389.47  4927.0  386.90  4937.5  387.68
  4958.6  387.42  4969.1  386.11  4982.2  385.72  4984.5  383.11  4986.8  380.49
  4989.6  379.99  4992.8  380.49  5000.0  380.64  5007.6  384.70  5012.6  383.13
  5030.4  384.99  5081.1  383.90  5091.2  384.53  5148.8  384.26  5172.3  383.03
  5202.7  386.08  5223.0  388.57  5263.5  396.03  5273.7  398.54  5283.8  399.33
#Mann=5,-1,0
  4663.5    0.12       0  4984.5    0.16       0  4986.8    0.07       0
  4992.8    0.16       0  5148.8    0.12       0
Bank Sta=4986.8,4992.8
Exp/Cntr=0.3,0.1

Type RM Length L Ch R = 1,3659,430,430,430
BEGIN DESCRIPTION:
UNT 024 IN BOCR 7.0
END DESCRIPTION:
XS GIS Cut Line= 3
      3761549.57     10617460.16      3761249.61     10617210.19
      3761049.62     10616910.20
#Sta/Elev= 30
  4576.4  414.32  4579.6  414.32  4590.0  406.26  4597.8  403.17  4604.3  403.95
  4633.0  401.85  4654.5  402.75  4659.9  401.49  4725.4  392.28  4732.6  390.33
  4746.2  389.65  4781.3  385.31  4832.1  380.47  4890.3  379.94  4945.4  378.70
  4989.4  379.07  4995.4  378.49  4999.9  375.53  5002.7  375.03  5005.9  375.53
  5010.4  377.75  5016.4  378.98  5103.6  382.22  5190.7  381.15  5205.7  383.14
  5211.7  387.60  5226.8  389.70  5232.8  392.75  5247.8  395.40  5327.4  402.51
#Mann=6,-1,0
  4576.4    0.16       0  4659.9    0.12       0  4781.3    0.16       0
  4890.3    0.12       0  4999.9    0.07       0  5005.9    0.12       0
Bank Sta=4999.9,5005.9
Exp/Cntr=0.3,0.1

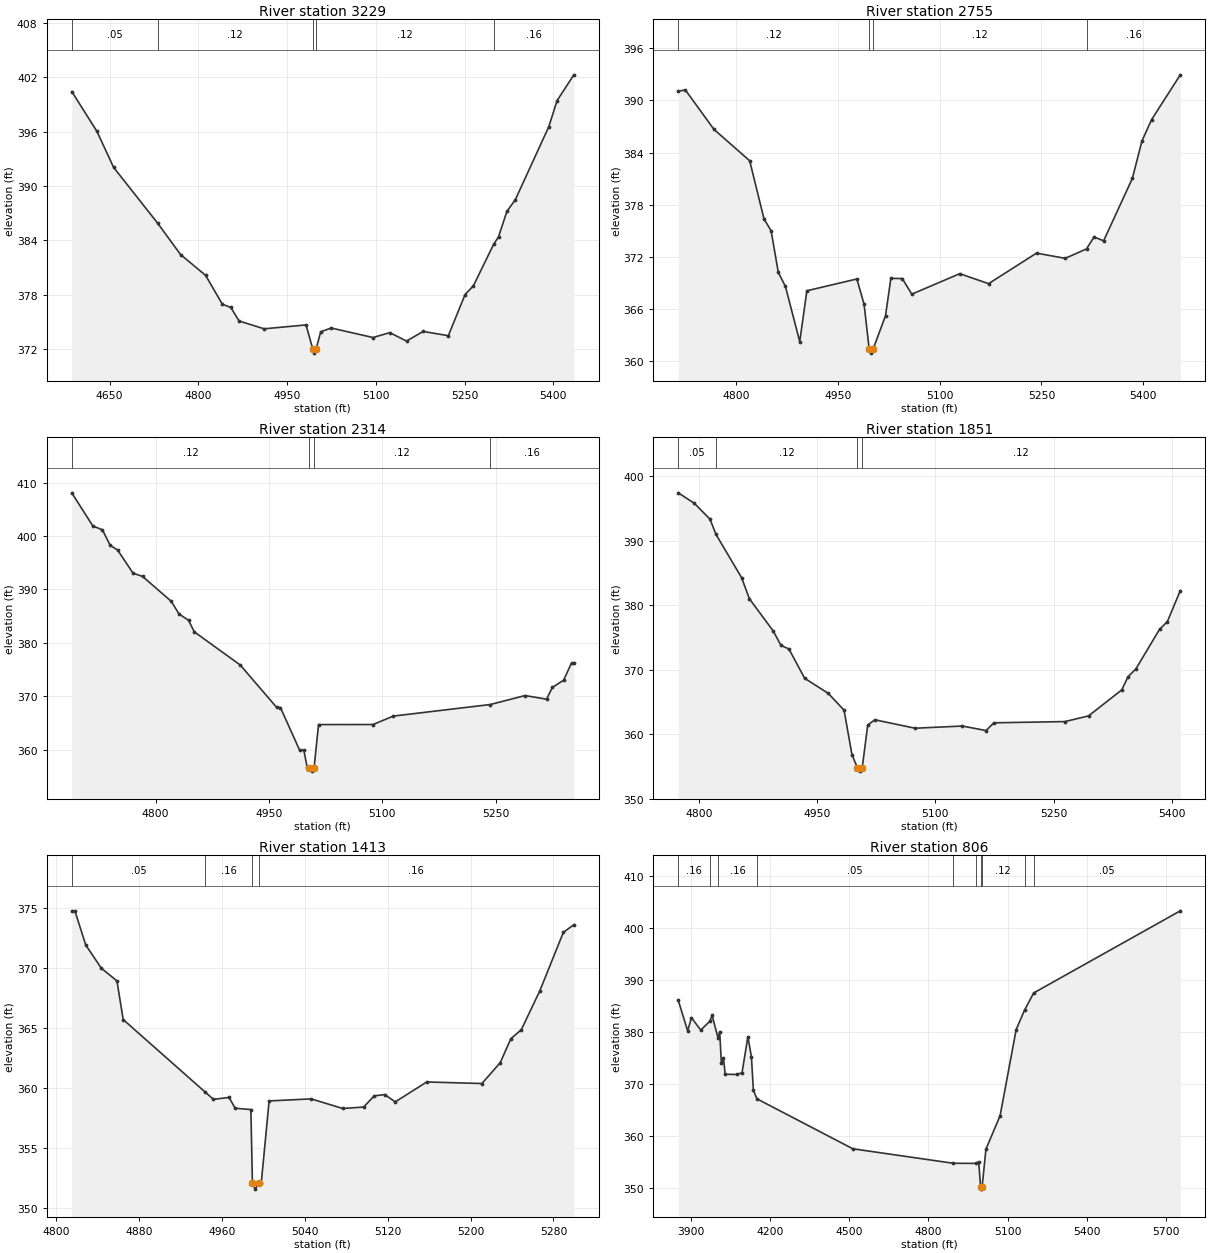
Type RM Length L Ch R = 1,3229,474,474,474
BEGIN DESCRIPTION:
UNT 024 IN BOCR 6.0
END DESCRIPTION:
XS GIS Cut Line= 3
      3761799.59     10617160.16      3761499.61     10616860.19
      3761199.61     10616560.18
#Sta/Elev= 30
  4586.2  400.41  4628.6  396.03  4656.9  392.05  4731.4  385.89  4770.0  382.44
  4812.4  380.14  4840.7  376.96  4854.9  376.61  4869.0  375.11  4911.4  374.25
  4982.1  374.68  4993.3  372.07  4996.0  371.57  4999.3  372.07  5006.9  373.92
  5024.6  374.34  5095.3  373.29  5123.6  373.83  5151.9  372.90  5180.1  373.96
  5222.6  373.49  5250.8  378.02  5265.0  379.00  5299.1  383.56  5307.4  384.39
  5321.6  387.20  5335.7  388.47  5392.3  396.52  5406.4  399.41  5434.7  402.25
#Mann=5,-1,0
  4586.2    0.05       0  4731.4    0.12       0  4993.3    0.07       0
  4999.3    0.12       0  5299.1    0.16       0
Bank Sta=4993.3,4999.3
Exp/Cntr=0.3,0.1

Type RM Length L Ch R = 1,2755,441,441,441
BEGIN DESCRIPTION:
UNT 024 IN BOCR 5.0
END DESCRIPTION:
XS GIS Cut Line= 3
      3761999.62     10616360.19      3761699.61     10616460.19
      3761399.61     10616160.19
#Sta/Elev= 30
  4714.3  391.07  4724.8  391.22  4767.0  386.67  4819.7  383.05  4840.8  376.34
  4851.3  374.98  4861.9  370.17  4872.4  368.56  4893.5  362.19  4904.0  368.06
  4977.8  369.42  4988.4  366.50  4995.9  361.37  4998.7  360.87  5001.9  361.37
  5020.0  365.18  5027.9  369.49  5044.7  369.47  5058.8  367.67  5129.5  370.03
  5172.0  368.88  5242.7  372.40  5285.1  371.80  5316.5  372.89  5327.5  374.26
  5341.7  373.82  5384.1  381.02  5398.2  385.33  5412.4  387.79  5454.8  392.96
#Mann=4,-1,0
  4714.3    0.12       0  4995.9    0.07       0  5001.9    0.12       0
  5316.5    0.16       0
Bank Sta=4995.9,5001.9
Exp/Cntr=0.3,0.1

Type RM Length L Ch R = 1,2314,463,463,463
BEGIN DESCRIPTION:
UNT 024 IN BOCR 4.0
END DESCRIPTION:
XS GIS Cut Line= 3
      3762199.62     10616110.19      3761899.61     10616060.19
      3761599.61     10615860.19
#Sta/Elev= 30
  4689.0  408.07  4716.9  401.87  4729.6  401.15  4739.7  398.27  4749.8  397.35
  4770.1  393.04  4782.8  392.42  4820.8  387.76  4830.9  385.42  4843.6  384.21
  4851.2  382.06  4912.0  375.86  4960.2  367.93  4965.3  367.88  4990.6  359.94
  4996.2  359.94  5000.7  356.68  5003.7  356.50  5006.4  356.00  5009.7  356.50
  5015.7  364.71  5087.8  364.72  5114.8  366.30  5243.0  368.46  5289.1  370.14
  5317.6  369.46  5325.2  371.65  5340.2  373.02  5350.7  376.26  5353.7  376.26
#Mann=4,-1,0
  4689.0    0.12       0  5003.7    0.07       0  5009.7    0.12       0
  5243.0    0.16       0
Bank Sta=5003.7,5009.7
Exp/Cntr=0.3,0.1

Type RM Length L Ch R = 1,1851,438,438,438
BEGIN DESCRIPTION:
UNT 024 IN BOCR 3.0
END DESCRIPTION:
XS GIS Cut Line= 2
      3762219.90     10615616.92      3761583.24     10615637.71
#Sta/Elev= 30
  4773.8  397.41  4794.1  395.80  4814.1  393.33  4821.7  390.96  4854.1  384.28
  4864.1  380.98  4894.2  376.02  4904.2  373.75  4914.2  373.21  4934.2  368.66
  4964.2  366.32  4984.2  363.71  4994.2  356.82  5001.2  354.77  5004.0  354.27
  5007.2  354.77  5014.2  361.40  5023.2  362.23  5074.3  360.92  5134.3  361.26
  5164.3  360.56  5174.3  361.76  5264.4  361.95  5294.4  362.83  5336.5  366.86
  5344.4  368.89  5354.4  370.11  5384.4  376.24  5394.4  377.45  5410.8  382.26
#Mann=4,-1,0
  4773.8    0.05       0  4821.7    0.12       0  5001.2    0.07       0
  5007.2    0.12       0
Bank Sta=5001.2,5007.2
Exp/Cntr=0.3,0.1

Type RM Length L Ch R = 1,1413,607,607,607
BEGIN DESCRIPTION:
UNT 024 IN BOCR 2.0
END DESCRIPTION:
XS GIS Cut Line= 3
      3762049.60     10615310.18      3761899.61     10615210.19
      3761599.61     10615160.19
#Sta/Elev= 30
  4815.3  374.73  4818.3  374.73  4828.8  371.88  4843.8  369.95  4858.9  368.89
  4864.9  365.67  4944.1  359.62  4952.0  359.02  4967.0  359.18  4973.0  358.28
  4988.1  358.17  4989.6  352.04  4992.3  351.54  4995.6  352.04  4998.1  352.04
  5005.7  358.89  5046.3  359.06  5076.7  358.26  5096.9  358.38  5107.1  359.31
  5117.2  359.42  5127.4  358.81  5157.8  360.47  5211.0  360.34  5228.7  362.08
  5238.9  364.07  5249.0  364.82  5266.8  368.05  5289.6  372.94  5299.7  373.57
#Mann=4,-1,0
  4815.3    0.05       0  4944.1    0.16       0  4989.6    0.07       0
  4995.6    0.16       0
Bank Sta=4989.6,4995.6
Exp/Cntr=0.3,0.1

Type RM Length L Ch R = 1,806,0,0,0
BEGIN DESCRIPTION:
UNT 024 IN BOCR 1.0
END DESCRIPTION:
XS GIS Cut Line= 3
      3762697.16     10615442.98      3762044.36     10614658.22
      3761176.28     10614519.33
#Sta/Elev= 30
  3853.3  386.12  3889.0  380.24  3903.3  382.77  3938.5  380.38  3973.5  382.13
  3981.4  383.23  4003.9  378.86  4010.1  380.06  4016.6  374.00  4024.4  375.04
  4030.9  371.89  4073.9  371.85  4094.7  372.16  4116.8  379.11  4130.1  375.30
  4137.7  368.83  4151.0  367.17  4513.9  357.56  4894.5  354.77  4980.2  354.75
  4990.3  355.05  4997.4  350.30  5000.2  349.80  5003.4  350.30  5017.7  357.49
  5071.3  363.93  5132.1  380.48  5163.7  384.21  5198.4  387.53  5753.2  403.32
#Mann=10,-1,0
  3853.3    0.16       0  3973.5    0.05       0  4003.9    0.16       0
  4151.0    0.05       0  4894.5    0.16       0  4980.2    0.12       0
  4997.4    0.07       0  5003.4    0.12       0  5163.7    0.16       0
  5198.4    0.05       0
Bank Sta=4997.4,5003.4
Exp/Cntr=0.3,0.1

Chan Stop Cuts=-1