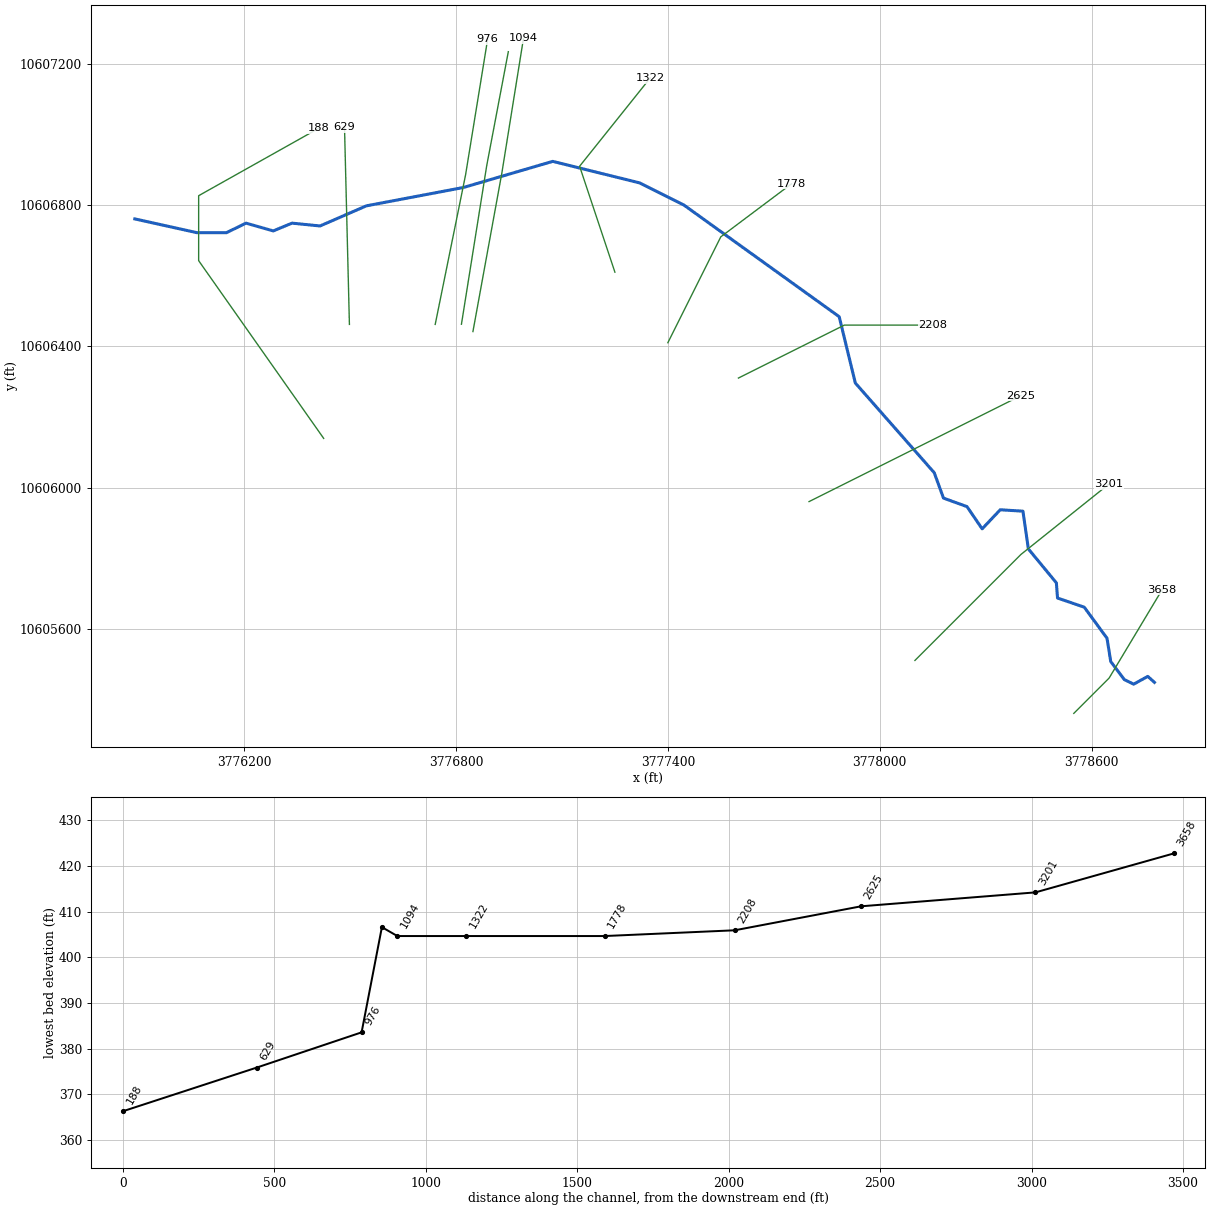
--- UNT 028 IN BOCR.prj (project) ---

Proj Title=UNT 028 IN BOCR Base Level Engineering
Current Plan=p01
Default Exp/Contr=0.3,0.1
English Units
Geom File=g01
Flow File=f01
Plan File=p01
Y Axis Title=Elevation
X Axis Title(PF)=Main Channel Distance
X Axis Title(XS)=Station
BEGIN DESCRIPTION:
UNT 028 IN BOCR
END DESCRIPTION:
DSS Export Rating Curves= 0
DSS Export Rating Curve Sorted= 0
DSS Export Volume Flow Curves= 0
DXF OffsetX= 0
DXF OffsetY= 0
DXF ScaleX= 1
DXF ScaleY= 10

--- UNT 028 IN BOCR.p01 (plan) ---

Plan Title=Multiple Run
Short Identifier=Multiple
Geom File=g01
Flow File=f01
Subcritical Flow
K Sum by GR= 0
Std Step Tol= 0.01
Critical Tol= 0.01
Num of Std Step Trials= 20
Max Error Tol= 0.3
Flow Tol Ratio= 0.001
Split Flow NTrial= 30
Split Flow Tol= 0.02
Split Flow Ratio= 0.02
Log Output Level= 0
Friction Slope Method= 1
Unsteady Friction Slope Method= 2
Unsteady Bridges Friction Slope Method= 1
Parabolic Critical Depth
Global Vel Dist=  1 , 1 , 1
Global Log Level= 0
CheckData=True
Encroach Param= -1, 0, 0, 0
BEGIN DESCRIPTION:
Multiple Run
END DESCRIPTION:

--- UNT 028 IN BOCR.f01 (steady flow) ---

Flow Title=Multiple
Program Version=4.10
Number of Profiles= 7
Profile Names=10-year,25-year,50-year,1pct_min,100-year,1pct_plu,500-year
River Rch & RM=UNT 028 IN BOCR,Reach-1         ,3658
     592     809     991     894    1209    1635    1806
Boundary for River Rch & Prof#=UNT 028 IN BOCR,Reach-1         , 1
Up Type= 0
Dn Type= 3
Dn Slope=0.02
Boundary for River Rch & Prof#=UNT 028 IN BOCR,Reach-1         , 2
Up Type= 0
Dn Type= 3
Dn Slope=0.02
Boundary for River Rch & Prof#=UNT 028 IN BOCR,Reach-1         , 3
Up Type= 0
Dn Type= 3
Dn Slope=0.02
Boundary for River Rch & Prof#=UNT 028 IN BOCR,Reach-1         , 4
Up Type= 0
Dn Type= 3
Dn Slope=0.02
Boundary for River Rch & Prof#=UNT 028 IN BOCR,Reach-1         , 5
Up Type= 0
Dn Type= 3
Dn Slope=0.02
Boundary for River Rch & Prof#=UNT 028 IN BOCR,Reach-1         , 6
Up Type= 0
Dn Type= 3
Dn Slope=0.02
Boundary for River Rch & Prof#=UNT 028 IN BOCR,Reach-1         , 7
Up Type= 0
Dn Type= 3
Dn Slope=0.02
DSS Import GetInterval= 0
DSS Import GetPeak= 0
DSS Import FillOption= 0

--- UNT 028 IN BOCR.g01 (geometry) ---

Geom Title=Existing Conditions
Program Version=4.10

River Reach=UNT 028 IN BOCR ,Reach-1
Reach XY= 30
      3778778.08     10605448.08      3778759.25       10605465.
      3778719.25       10605443.      3778692.75       10605456.
      3778654.25       10605507.      3778643.75       10605573.
      3778579.25       10605661.       3778503.5       10605687.
      3778500.25       10605730.        3778421.       10605826.
       3778405.5       10605933.      3778341.25       10605937.
        3778290.       10605883.        3778247.       10605946.
       3778180.5       10605970.      3778154.25       10606042.
      3777930.75       10606296.        3777885.       10606484.
       3777445.5       10606800.      3777319.75       10606863.
       3777073.5       10606924.       3776820.5       10606850.
       3776545.5       10606798.      3776414.25       10606741.
        3776335.       10606749.      3776281.75       10606727.
       3776204.5       10606749.      3776149.25       10606722.
       3776065.5       10606722.       3775889.5       10606761.

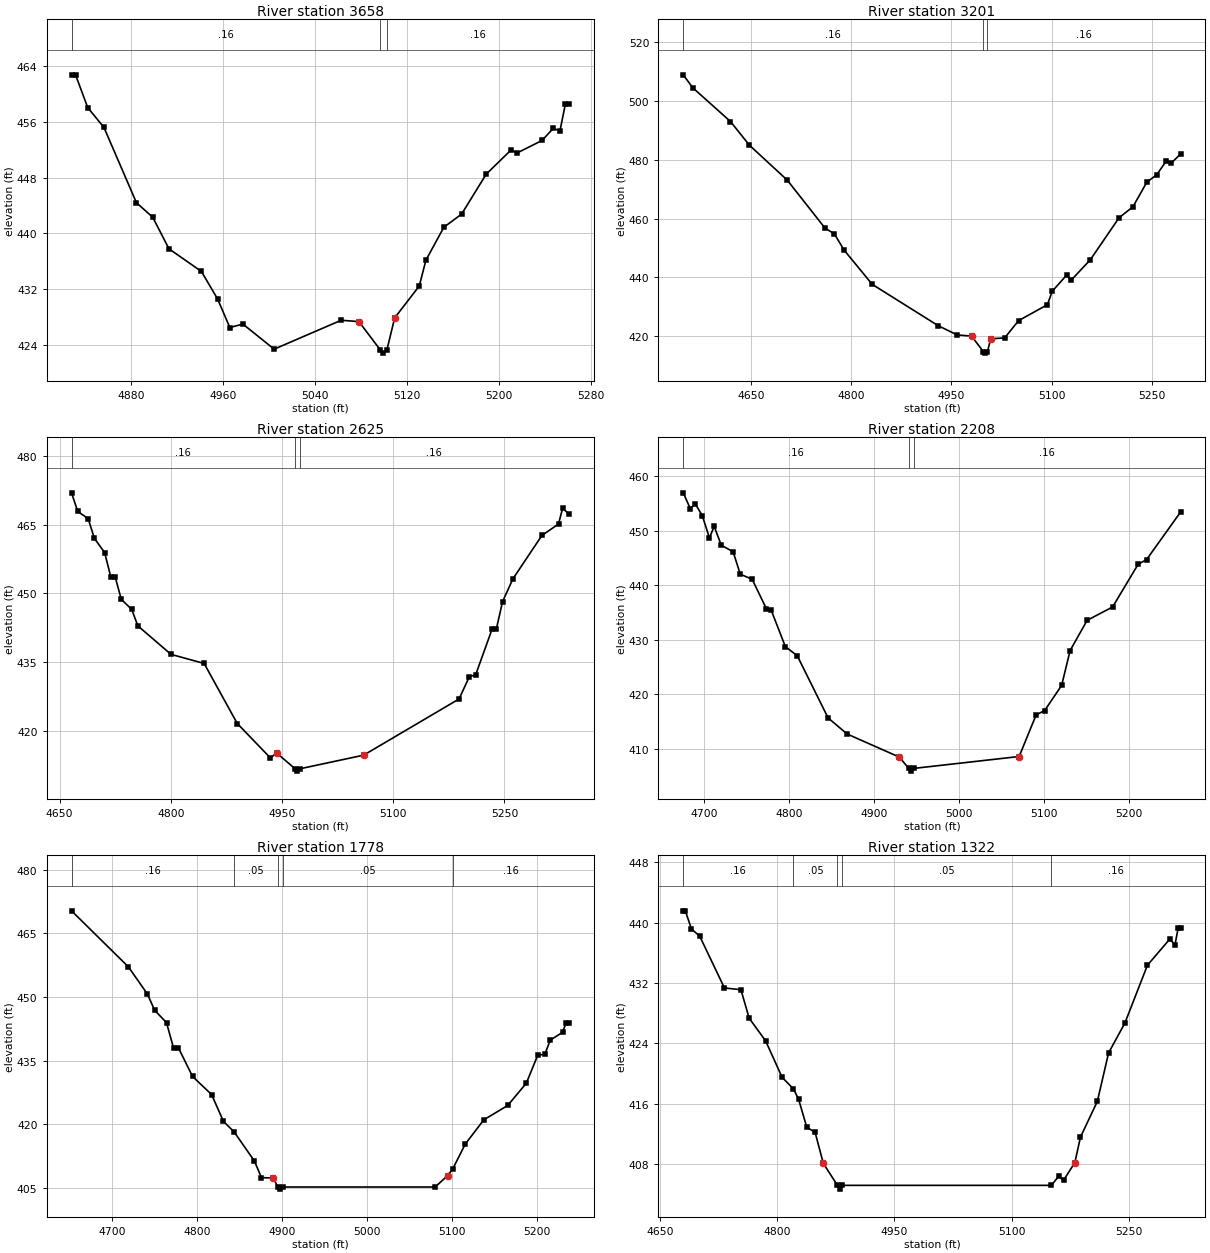
Type RM Length L Ch R = 1 ,3658    ,457,457,457
BEGIN DESCRIPTION:
UNT 028 IN BOCR 8.0
END DESCRIPTION:
XS GIS Cut Line= 3
      3778549.64     10605360.22      3778649.61     10605460.19
       3778799.6     10605710.17
#Sta/Elev= 30
  4828.2  462.75  4831.7  462.75  4842.3  458.04  4856.4   455.2  4884.7  444.38
  4898.9  442.29    4913  437.76  4941.3   434.5  4955.4  430.53    4966  426.45
  4977.4  426.94  5004.6  423.34  5062.9  427.49  5078.4   427.3  5096.8  423.27
  5099.6  422.77  5102.8  423.27  5109.5  427.83  5130.9  432.41  5136.7  436.12
  5152.3  440.85  5167.8  442.75  5189.2  448.48  5210.6  451.92  5216.4  451.55
  5237.8  453.32  5247.5  455.05  5253.4  454.71  5258.2  458.63  5261.1  458.63
#Mann= 3 ,-1 , 0
  4828.2     .16       0  5096.8     .07       0  5102.8     .16       0
Bank Sta=5078.4,5109.5
XS Rating Curve= 0 ,0
Exp/Cntr=0.3,0.1

Type RM Length L Ch R = 1 ,3201    ,576,576,576
BEGIN DESCRIPTION:
UNT 028 IN BOCR 7.0
END DESCRIPTION:
XS GIS Cut Line= 3
       3778099.6     10605510.17      3778399.61     10605810.19
      3778649.58     10606010.16
#Sta/Elev= 30
  4548.7  508.86  4562.9  504.46  4619.4  492.98  4647.7  484.94  4704.3  473.07
  4760.9  456.74    4775  454.77  4789.1  449.37  4831.6  437.61  4930.6  423.53
  4958.8  420.42  4980.2  420.04    4998  414.74  5000.7  414.24    5004  414.74
    5009  419.13  5029.8   419.4  5050.6  425.28  5093.8  430.71    5101  435.27
  5122.7   440.8  5129.1  438.99  5157.9  445.94  5201.1  460.28  5221.9  464.01
  5242.7   472.4  5257.1   474.8  5271.5  479.46  5279.5  478.93  5293.1  481.91
#Mann= 3 ,-1 , 0
  4548.7     .16       0    4998     .07       0    5004     .16       0
Bank Sta=4980.2,5009
XS Rating Curve= 0 ,0
Exp/Cntr=0.3,0.1

Type RM Length L Ch R = 1 ,2625    ,417,417,417
BEGIN DESCRIPTION:
UNT 028 IN BOCR 6.0
END DESCRIPTION:
XS GIS Cut Line= 3
       3777799.6     10605960.18      3778099.61     10606110.19
      3778399.58     10606260.17
#Sta/Elev= 30
  4666.1  471.95  4674.5  467.88  4688.5  466.33  4696.9  462.02  4710.8  458.89
  4719.2   453.5  4724.8  453.68  4733.2   448.7  4747.2  446.51  4755.6   442.9
  4800.3  436.68    4845  434.69  4889.7  421.58  4934.4  414.07  4942.8  415.15
  4967.8  411.69  4970.5  411.19  4973.8  411.69  5060.2  414.68  5188.8  426.94
  5202.8  431.83  5211.2   432.2  5233.5  442.24  5239.1  442.18  5247.5  448.19
  5261.5  453.17  5300.6  462.64    5323  465.14  5328.5  468.59  5336.9  467.35
#Mann= 3 ,-1 , 0
  4666.1     .16       0  4967.8     .07       0  4973.8     .16       0
Bank Sta=4942.8,5060.2
XS Rating Curve= 0 ,0
Exp/Cntr=0.3,0.1

Type RM Length L Ch R = 1 ,2208    ,430,430,430
BEGIN DESCRIPTION:
UNT 028 IN BOCR 5.0
END DESCRIPTION:
XS GIS Cut Line= 3
      3777599.57     10606310.17      3777899.61     10606460.19
      3778149.56     10606460.19
#Sta/Elev= 30
  4675.8  456.94  4684.2     454  4689.8  454.95  4698.2  452.76  4706.6  448.68
  4712.2  450.79  4720.6  447.33  4734.5  446.14  4742.9  442.03  4756.9   441.1
  4773.7  435.68  4779.3  435.44    4796  428.75    4810  427.08  4846.3  415.69
  4868.7  412.74  4930.2  408.51  4941.2  406.44  4943.9  405.94  4947.2  406.44
  5071.2  408.62  5091.2  416.25  5101.2  417.04  5121.2  421.64  5131.2  428.04
  5151.2  433.57  5181.2  436.02  5211.2  443.83  5221.2  444.71  5261.2  453.41
#Mann= 3 ,-1 , 0
  4675.8     .16       0  4941.2     .07       0  4947.2     .16       0
Bank Sta=4930.2,5071.2
XS Rating Curve= 0 ,0
Exp/Cntr=0.3,0.1

Type RM Length L Ch R = 1 ,1778    ,456,456,456
BEGIN DESCRIPTION:
UNT 028 IN BOCR 4.0
END DESCRIPTION:
XS GIS Cut Line= 3
      3777399.63     10606410.22      3777549.61     10606710.19
      3777749.63     10606860.21
#Sta/Elev= 30
  4651.9  470.33  4718.9   457.1  4741.3  450.67  4749.7  446.89  4763.7  443.95
    4772  437.96  4777.6  438.05  4794.4  431.25  4816.8  426.99  4830.7  420.68
  4843.5  418.12  4867.1  411.34  4875.5  407.39  4889.4  407.31  4894.8  405.18
  4897.6  404.68  4900.8  405.18    5080  405.18  5094.6  407.87  5100.9  409.54
  5115.4  415.31  5137.3  421.04  5165.4  424.42  5187.3  429.68  5200.8  436.32
  5209.1  436.46  5215.4  439.82    5230  441.68  5234.1  443.96  5237.3  443.96
#Mann= 5 ,-1 , 0
  4651.9     .16       0  4843.5     .05       0  4894.8    .033       0
  4900.8     .05       0  5100.9     .16       0
Bank Sta=4889.4,5094.6
XS Rating Curve= 0 ,0
Exp/Cntr=0.3,0.1

Type RM Length L Ch R = 1 ,1322    ,228,228,228
BEGIN DESCRIPTION:
UNT 028 IN BOCR 3.0
END DESCRIPTION:
XS GIS Cut Line= 3
      3777249.61     10606610.18      3777149.61     10606910.19
      3777349.61     10607160.19
#Sta/Elev= 30
  4679.9  441.55  4682.5  441.55  4690.4  439.15    4701  438.18  4732.6  431.33
  4753.7   431.1  4764.2  427.33  4785.3  424.32  4806.4  419.49  4820.9  417.96
  4827.5  416.58    4838  412.87  4848.6  412.21  4859.1   408.1  4877.2  405.18
  4879.9  404.68  4883.2  405.18  5151.1  405.18  5160.2  406.38  5166.6  405.86
    5181  408.19  5188.2  411.57  5209.8   416.3  5224.2  422.73  5245.1  426.69
  5273.9  434.34  5302.7  437.83  5309.1     437  5313.1  439.21  5316.3  439.21
#Mann= 5 ,-1 , 0
  4679.9     .16       0  4820.9     .05       0  4877.2    .033       0
  4883.2     .05       0  5151.1     .16       0
Bank Sta=4859.1,5181
XS Rating Curve= 0 ,0
Exp/Cntr=0.3,0.1

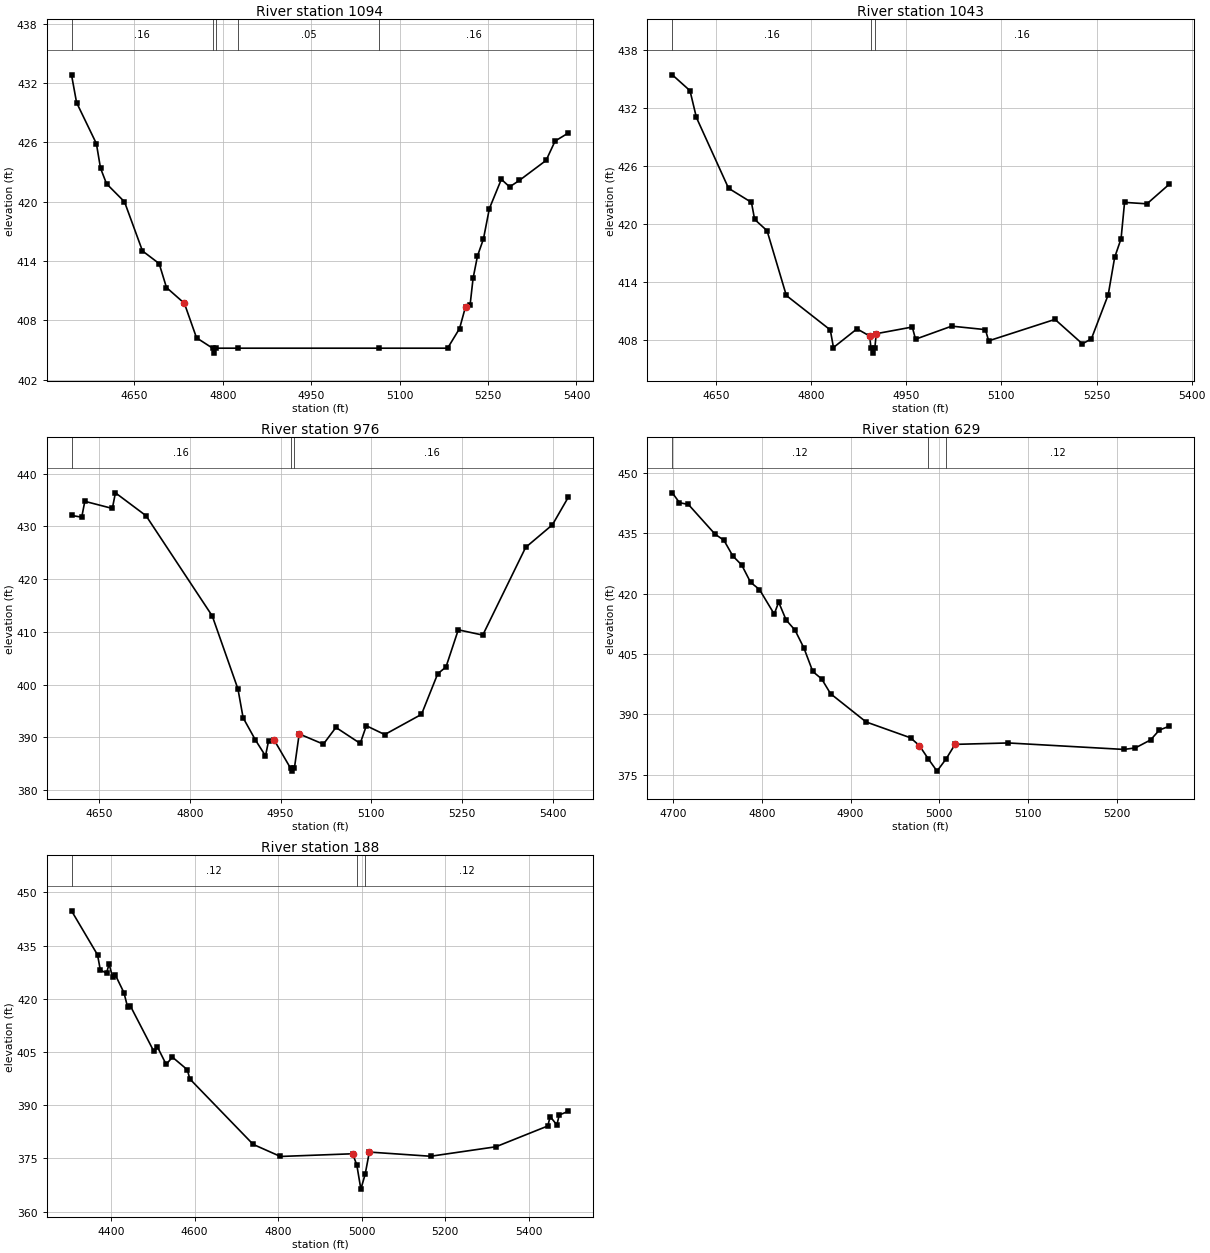
Type RM Length L Ch R = 1 ,1094    ,51,51,51
BEGIN DESCRIPTION:
Mapping XS 42e657ff
END DESCRIPTION:
XS GIS Cut Line= 3
       3776847.4     10606441.75      3776929.37     10606891.04
      3776990.64     10607272.55
#Sta/Elev= 30
  4543.3  432.84  4551.9  430.03  4585.5  425.88  4592.5   423.4  4602.7  421.82
  4633.2  419.99  4663.7  415.02    4692  413.74  4704.4  411.32  4734.8  409.72
  4755.4  406.23  4782.7  405.18  4785.4  404.68  4788.7  405.18  4825.2  405.18
  5065.5  405.18  5181.4  405.18  5201.7  407.17  5211.8  409.37  5219.6  409.57
  5224.6  412.24  5232.1  414.51  5242.2  416.23  5252.3  419.31  5272.6  422.27
  5286.6   421.5    5303  422.15  5348.5  424.18  5363.8  426.14  5386.4  426.96
#Mann= 5 ,-1 , 0
  4543.3     .16       0  4782.7    .033       0  4788.7     .16       0
  4825.2     .05       0  5065.5     .16       0
Bank Sta=4734.8,5211.8
XS Rating Curve= 0 ,0
Exp/Cntr=0.3,0.1

Type RM Length L Ch R = 1 ,1043    ,67,67,67
BEGIN DESCRIPTION:
UNT 028 IN BOCR 2.0
END DESCRIPTION:
XS GIS Cut Line= 3
      3776814.86     10606462.64      3776886.46     10606911.82
      3776947.66     10607234.72
#Sta/Elev= 30
  4581.1  435.41    4609  433.77  4619.1     431  4669.8  423.68  4705.9  422.22
  4710.9  420.46  4730.5  419.29  4760.9  412.59  4830.2  409.03  4835.2  407.21
  4872.3  409.14  4892.3   408.4  4894.4  407.13  4897.1  406.63  4900.4  407.13
  4902.7  408.64  4959.5  409.33  4964.6  408.07  5021.6  409.42  5074.8  409.06
  5079.9   407.9  5184.5  410.12  5227.7  407.59  5241.9  408.11  5268.4  412.66
  5278.6  416.53  5288.7  418.47  5294.2  422.22  5329.5  422.07  5364.6  424.09
#Mann= 3 ,-1 , 0
  4581.1     .16       0  4894.4     .07       0  4900.4     .16       0
Bank Sta=4892.3,4902.7
XS Rating Curve= 0 ,0
Exp/Cntr=0.3,0.1

Type RM Length L Ch R = 1 ,976     ,347,347,347
BEGIN DESCRIPTION:
Mapping XS 4da4014c
END DESCRIPTION:
XS GIS Cut Line= 3
      3776740.55     10606462.13      3776826.57     10606885.78
      3776889.07     10607269.93
#Sta/Elev= 30
  4604.5  432.05  4621.4  431.73  4626.5  434.73    4672  433.38  4677.1  436.34
  4727.7     432  4837.2     413  4879.7  399.15  4888.2  393.71  4908.6  389.49
  4925.2  386.48  4930.3  389.35  4939.3  389.54  4966.9   384.1  4969.6   383.6
  4972.9   384.1  4980.9  390.65  5020.9  388.71  5041.6  391.88  5081.8  388.85
  5091.9   392.2  5122.3  390.53  5183.1  394.36  5209.9  402.05  5223.6  403.34
  5243.9  410.38  5284.4  409.38  5355.3     426  5399.6  430.29    5426  435.55
#Mann= 3 ,-1 , 0
  4604.5     .16       0  4966.9     .07       0  4972.9     .16       0
Bank Sta=4939.3,4980.9
XS Rating Curve= 0 ,0
Exp/Cntr=0.3,0.1

Type RM Length L Ch R = 1 ,629     ,441,441,441
BEGIN DESCRIPTION:
Mapping XS 8d1e401a
END DESCRIPTION:
XS GIS Cut Line= 2
       3776497.5     10606462.13      3776483.61     10607021.16
#Sta/Elev= 30
  4699.4  445.03  4707.5  442.58  4717.5  442.14  4747.5  434.76  4757.5  433.24
  4767.5  429.34  4777.5   427.1  4787.5  422.79  4797.5     421  4814.1   414.9
  4819.1  417.86  4827.5  413.43  4837.5  410.91  4847.5  406.47  4857.5  400.63
  4867.5  398.78  4877.5  395.11  4917.5  388.09  4967.5  384.15  4977.5   382.2
  4987.5  378.91  4997.3  375.87  5007.6  378.93  5017.6  382.52  5077.6  382.87
  5207.6  381.26  5220.5  381.64  5237.6  383.62  5247.6  386.09  5258.6  387.02
#Mann= 3 ,-1 , 0
  4699.4     .12       0  4987.5     .07       0  5007.6     .12       0
Bank Sta=4977.5,5017.6
XS Rating Curve= 0 ,0
Exp/Cntr=0.3,0.1

Type RM Length L Ch R = 1 ,188     ,0,0,0
BEGIN DESCRIPTION:
UNT 028 IN BOCR 1.0
END DESCRIPTION:
XS GIS Cut Line= 4
      3776424.61      10606139.2      3776070.41     10606642.71
      3776070.41     10606826.74      3776410.65     10607017.69
#Sta/Elev= 30
  4305.1  444.81  4367.4   432.4  4374.1  428.11  4388.9  427.23    4395  429.79
  4403.7  426.08  4409.8  426.78  4430.7  421.72  4439.4  417.65  4445.5   418.1
  4502.2  405.19  4510.9   406.4  4531.8  401.49  4546.6  403.56  4582.3  400.01
  4588.4   397.4    4740  378.95  4805.3  375.54  4978.2   376.3  4988.2  373.15
  4997.9  366.33  5008.2  370.51  5018.2  376.78  5164.9   375.6  5321.1  378.27
  5445.5  384.14  5451.2  386.79  5467.2  384.44  5472.9  387.23  5494.9  388.29
#Mann= 3 ,-1 , 0
  4305.1     .12       0  4988.2     .07       0  5008.2     .12       0
Bank Sta=4978.2,5018.2
XS Rating Curve= 0 ,0
Exp/Cntr=0.3,0.1

Chan Stop Cuts=-1
Use User Specified Reach Order=0
Composite Channel Slope=5