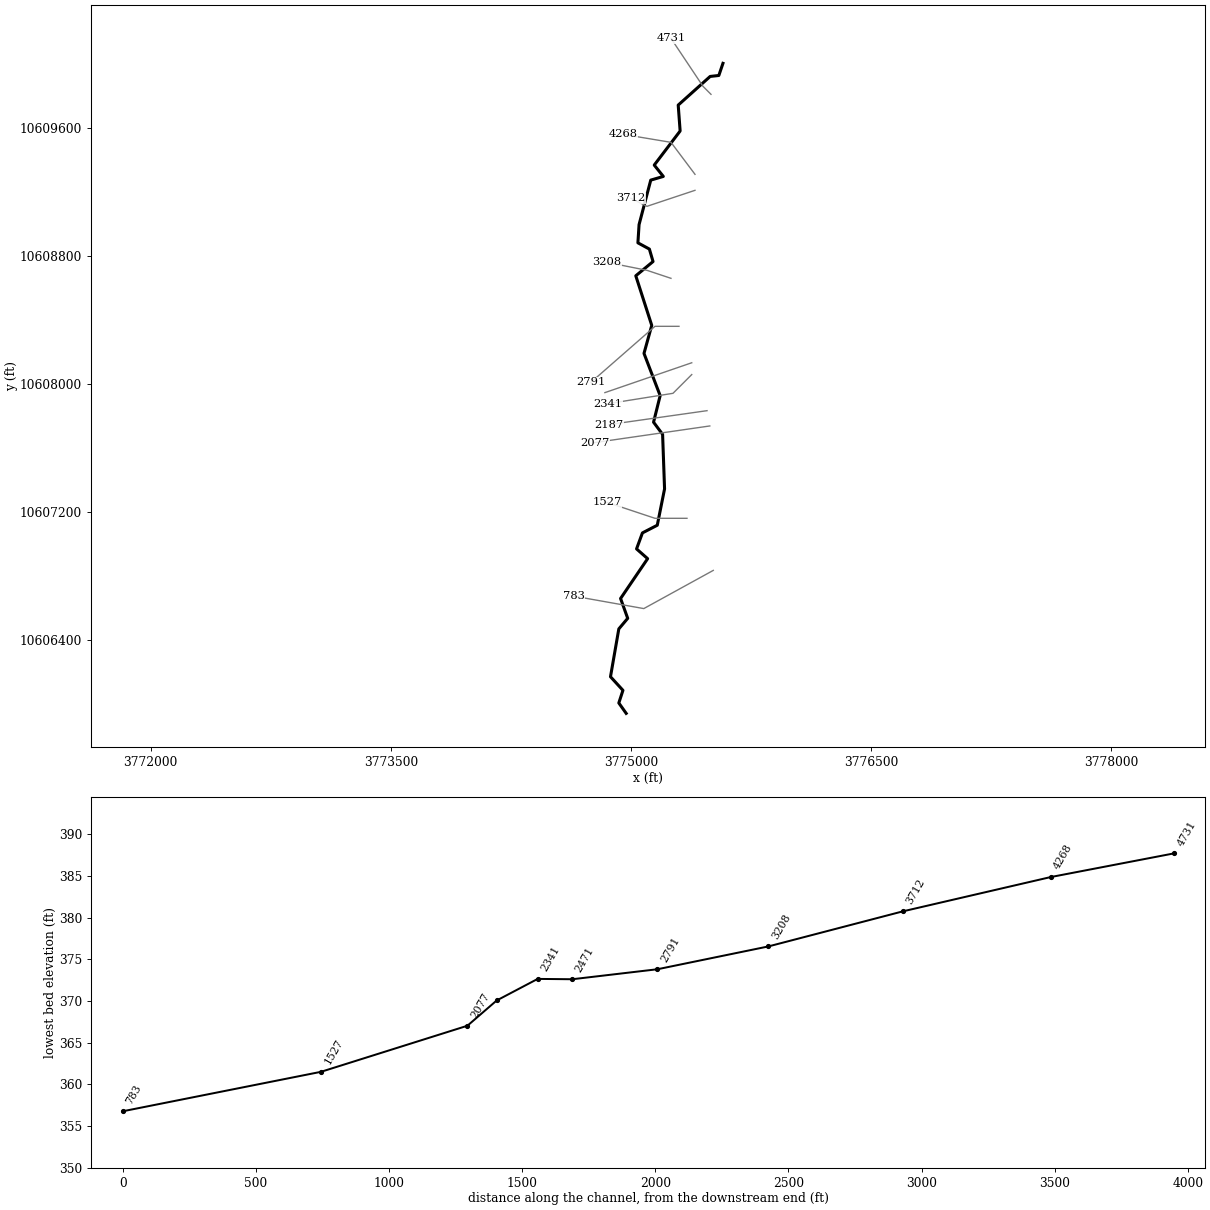
--- UNT 029 IN BOCR.prj (project) ---

Proj Title=UNT 029 IN BOCR Base Level Engineering
Current Plan=p01
Default Exp/Contr=0.3,0.1
English Units
Geom File=g01
Flow File=f01
Plan File=p01
Y Axis Title=Elevation
X Axis Title(PF)=Main Channel Distance
X Axis Title(XS)=Station
BEGIN DESCRIPTION:
UNT 029 IN BOCR
END DESCRIPTION:
DSS Export Rating Curves= 0
DSS Export Rating Curve Sorted= 0
DSS Export Volume Flow Curves= 0
DXF OffsetX= 0
DXF OffsetY= 0
DXF ScaleX= 1
DXF ScaleY= 10

--- UNT 029 IN BOCR.p01 (plan) ---

Plan Title=Multiple Run
Short Identifier=Multiple
Geom File=g01
Flow File=f01
Subcritical Flow
K Sum by GR= 0
Std Step Tol= 0.01
Critical Tol= 0.01
Num of Std Step Trials= 20
Max Error Tol= 0.3
Flow Tol Ratio= 0.001
Split Flow NTrial= 30
Split Flow Tol= 0.02
Split Flow Ratio= 0.02
Log Output Level= 0
Friction Slope Method= 1
Unsteady Friction Slope Method= 2
Unsteady Bridges Friction Slope Method= 1
Parabolic Critical Depth
Global Vel Dist=  1 , 1 , 1
Global Log Level= 0
CheckData=True
Encroach Param= -1, 0, 0, 0
BEGIN DESCRIPTION:
Multiple Run
END DESCRIPTION:

--- UNT 029 IN BOCR.f01 (steady flow) ---

Flow Title=Multiple
Number of Profiles=7
Profile Names=10-year,25-year,50-year,1pct_min,100-year,1pct_plu,500-year
River Rch & RM= UNT 029 IN BOCR,Reach-1,4731
     694     955    1174    1062    1437    1943    2157
River Rch & RM= UNT 029 IN BOCR,Reach-1,3712
     775    1070    1320    1196    1618    2188    2439
Boundary for River Rch & Prof#=UNT 029 IN BOCR,Reach-1,1
Up Type=0
Dn Type=3
Dn Slope=0.005
Boundary for River Rch & Prof#=UNT 029 IN BOCR,Reach-1,2
Up Type=0
Dn Type=3
Dn Slope=0.005
Boundary for River Rch & Prof#=UNT 029 IN BOCR,Reach-1,3
Up Type=0
Dn Type=3
Dn Slope=0.005
Boundary for River Rch & Prof#=UNT 029 IN BOCR,Reach-1,4
Up Type=0
Dn Type=3
Dn Slope=0.005
Boundary for River Rch & Prof#=UNT 029 IN BOCR,Reach-1,5
Up Type=0
Dn Type=3
Dn Slope=0.005
Boundary for River Rch & Prof#=UNT 029 IN BOCR,Reach-1,6
Up Type=0
Dn Type=3
Dn Slope=0.005
Boundary for River Rch & Prof#=UNT 029 IN BOCR,Reach-1,7
Up Type=0
Dn Type=3
Dn Slope=0.005

--- UNT 029 IN BOCR.g01 (geometry) ---

Geom Title=Existing Conditions
Program Version=4.10

River Reach=UNT 029 IN BOCR ,Reach-1
Reach XY= 30
      3775574.25       10610004.       3775548.5       10609928.
      3775494.25       10609922.      3775294.75       10609743.
      3775306.75       10609581.        3775145.       10609368.
      3775201.75       10609297.      3775123.25       10609274.
      3775050.25       10608996.        3775043.       10608882.
      3775114.75       10608843.       3775137.5       10608765.
      3775029.75       10608676.       3775129.5       10608366.
        3775081.       10608191.        3775182.       10607927.
      3775140.75       10607761.      3775197.25       10607685.
       3775209.5       10607344.        3775164.       10607117.
      3775071.25       10607069.       3775034.5       10606969.
      3775103.75       10606908.      3774934.75       10606659.
      3774979.25       10606535.      3774923.75       10606469.
      3774871.75       10606170.       3774949.5       10606085.
      3774923.75       10606006.      3774969.75       10605941.

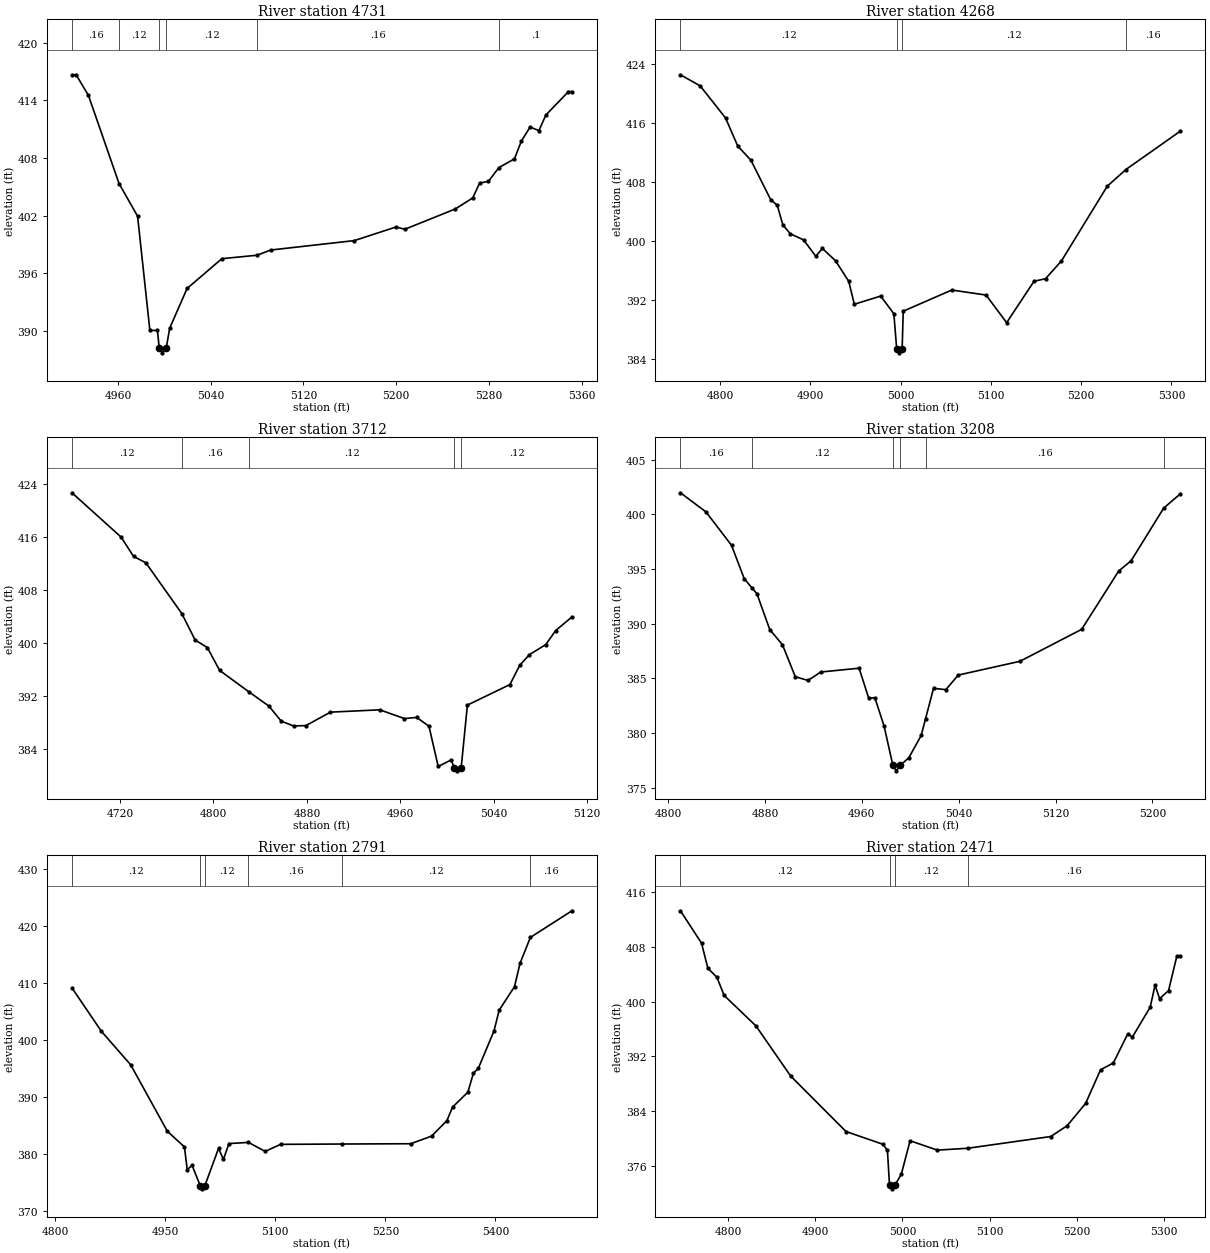
Type RM Length L Ch R = 1 ,4731    ,463,463,463
BEGIN DESCRIPTION:
UNT 029 IN BOCR 9.0
END DESCRIPTION:
XS GIS Cut Line= 3
      3775499.63     10609810.17      3775449.61     10609860.19
      3775249.61     10610160.19
#Sta/Elev= 30
  4920.3  416.65  4923.9  416.65  4934.5   414.5  4960.9  405.33  4976.9  401.93
  4987.5  390.04    4994  390.04  4995.6  388.21  4998.3  387.71  5001.6  388.21
  5004.6  390.28  5019.6  394.41  5049.6  397.51    5080  397.87  5091.7  398.41
  5163.8  399.39  5199.9  400.81  5207.4  400.57  5250.9  402.68    5266  403.83
    5272  405.39  5279.5  405.55  5288.6  406.99    5302   407.9    5308  409.76
  5315.5  411.21  5323.1  410.84  5329.1  412.46  5348.6   414.9  5351.6   414.9
#Mann= 6 ,-1 , 0
  4920.3     .16       0  4960.9     .12       0  4995.6     .07       0
  5001.6     .12       0    5080     .16       0  5288.6      .1       0
Bank Sta=4995.6,5001.6
XS Rating Curve= 0 ,0
Exp/Cntr=0.3,0.1

Type RM Length L Ch R = 1 ,4268    ,556,556,556
BEGIN DESCRIPTION:
UNT 029 IN BOCR 8.0
END DESCRIPTION:
XS GIS Cut Line= 3
      3775399.61     10609310.19      3775249.61     10609510.19
      3774949.64     10609560.18
#Sta/Elev= 30
  4755.9  422.59  4777.8  421.08  4805.9  416.73  4819.4  412.92    4834     411
  4855.9  405.65  4863.2  404.88  4869.4  402.22  4877.8  401.01  4892.4  400.19
  4905.9  397.97  4913.2  399.03  4927.8  397.36  4942.4  394.57  4948.6  391.46
  4977.8  392.57  4992.4  390.18  4995.6  385.37  4998.4  384.87  5001.6  385.37
  5002.8  390.52  5056.6  393.39  5094.6  392.71  5117.4  388.96  5147.8  394.59
  5160.5  394.92  5178.2  397.35  5228.9  407.47  5249.6  409.74    5310  414.95
#Mann= 4 ,-1 , 0
  4755.9     .12       0  4995.6     .07       0  5001.6     .12       0
  5249.6     .16       0
Bank Sta=4995.6,5001.6
XS Rating Curve= 0 ,0
Exp/Cntr=0.3,0.1

Type RM Length L Ch R = 1 ,3712    ,504,504,504
BEGIN DESCRIPTION:
UNT 029 IN BOCR 7.0
END DESCRIPTION:
XS GIS Cut Line= 3
      3775399.57     10609210.17      3775099.61     10609110.19
       3774999.6      10609160.2
#Sta/Elev= 30
  4678.9  422.67    4721  415.98  4731.6  413.08  4742.1  412.12  4772.9  404.47
  4784.3  400.48  4794.8  399.33  4805.3  395.89  4830.5  392.64  4847.5  390.51
  4858.1  388.23  4868.6  387.52  4879.1  387.57  4900.2   389.6  4942.4  389.95
  4963.5  388.63    4974   388.8  4984.5  387.48  4992.4  381.41  5003.5  382.39
  5006.1  381.25  5008.8  380.75  5012.1  381.25  5017.4  390.66  5053.8  393.76
  5062.2  396.66  5070.5  398.27  5084.5  399.78  5092.9  401.89  5106.9  403.95
#Mann= 5 ,-1 , 0
  4678.9     .12       0  4772.9     .16       0  4830.5     .12       0
  5006.1     .07       0  5012.1     .12       0
Bank Sta=5006.1,5012.1
XS Rating Curve= 0 ,0
Exp/Cntr=0.3,0.1

Type RM Length L Ch R = 1 ,3208    ,417,417,417
BEGIN DESCRIPTION:
UNT 029 IN BOCR 6.0
END DESCRIPTION:
XS GIS Cut Line= 3
      3775249.61     10608660.19      3775099.61     10608710.19
      3774849.57      10608760.2
#Sta/Elev= 30
  4810.1  401.96  4831.2  400.21  4852.3  397.16  4862.8  394.11  4869.1  393.28
  4873.3  392.73  4883.9  389.46  4894.4  388.07    4905  385.15  4915.5  384.81
    4926  385.58  4957.7  385.93  4965.6  383.21  4970.8  383.21  4978.4  380.62
  4985.6  377.05  4988.4  376.55  4991.6  377.05  4998.8  377.74    5009  379.78
  5012.6   381.3  5019.2  384.09  5029.4  383.97  5039.6   385.3  5090.6  386.56
  5141.6  389.48  5172.2  394.81  5182.4  395.74  5209.4  400.56  5223.2  401.87
#Mann= 6 ,-1 , 0
  4810.1     .16       0  4869.1     .12       0  4985.6     .07       0
  4991.6     .12       0  5012.6     .16       0  5209.4     .12       0
Bank Sta=4985.6,4991.6
XS Rating Curve= 0 ,0
Exp/Cntr=0.3,0.1

Type RM Length L Ch R = 1 ,2791    ,320,320,320
BEGIN DESCRIPTION:
UNT 029 IN BOCR 5.0
END DESCRIPTION:
XS GIS Cut Line= 3
      3775299.57     10608360.19      3775149.61     10608360.19
      3774749.59     10608010.17
#Sta/Elev= 30
  4822.8  409.09  4862.8  401.48  4902.8  395.59  4952.8  383.92  4976.1  381.17
  4979.9  377.15  4986.5  377.94  4997.8  374.31  5000.5  373.81  5003.8  374.31
  5022.6  380.92  5029.2  378.98  5036.8  381.76  5063.4  381.96  5086.2  380.38
  5107.1  381.62  5191.5  381.68  5284.6  381.73    5313  383.07  5333.9  385.79
  5341.5  388.15  5362.4  390.78    5370  394.11  5376.6  394.94    5398  401.51
  5405.1  405.17    5426  409.32  5433.6  413.42  5447.6  417.95  5504.3  422.63
#Mann= 6 ,-1 , 0
  4822.8     .12       0  4997.8     .07       0  5003.8     .12       0
  5063.4     .16       0  5191.5     .12       0  5447.6     .16       0
Bank Sta=4997.8,5003.8
XS Rating Curve= 0 ,0
Exp/Cntr=0.3,0.1

Type RM Length L Ch R = 1 ,2471    ,130,130,130
BEGIN DESCRIPTION:
Mapping XS 3e276670
END DESCRIPTION:
XS GIS Cut Line= 2
      3775379.26     10608132.43      3774836.76     10607945.81
#Sta/Elev= 30
  4745.3  413.32  4769.5  408.58  4776.7  404.93  4787.2  403.57  4795.4  400.93
  4831.9  396.47  4871.8  389.12  4935.3     381  4977.5  379.14  4982.8  378.25
  4985.2  373.11  4987.9  372.61  4991.2  373.11  4998.7  374.74  5008.8  379.65
    5040  378.28  5074.9  378.55  5170.2  380.27  5189.1  381.86  5210.2  385.11
  5227.4  390.05    5242  391.03  5258.6  395.31  5263.9  394.84  5284.3   399.2
  5289.9  402.43  5295.1  400.45  5305.4  401.64  5314.9  406.69    5319  406.69
#Mann= 4 ,-1 , 0
  4745.3     .12       0  4985.2     .07       0  4991.2     .12       0
  5074.9     .16       0
Bank Sta=4985.2,4991.2
XS Rating Curve= 0 ,0
Exp/Cntr=0.3,0.1

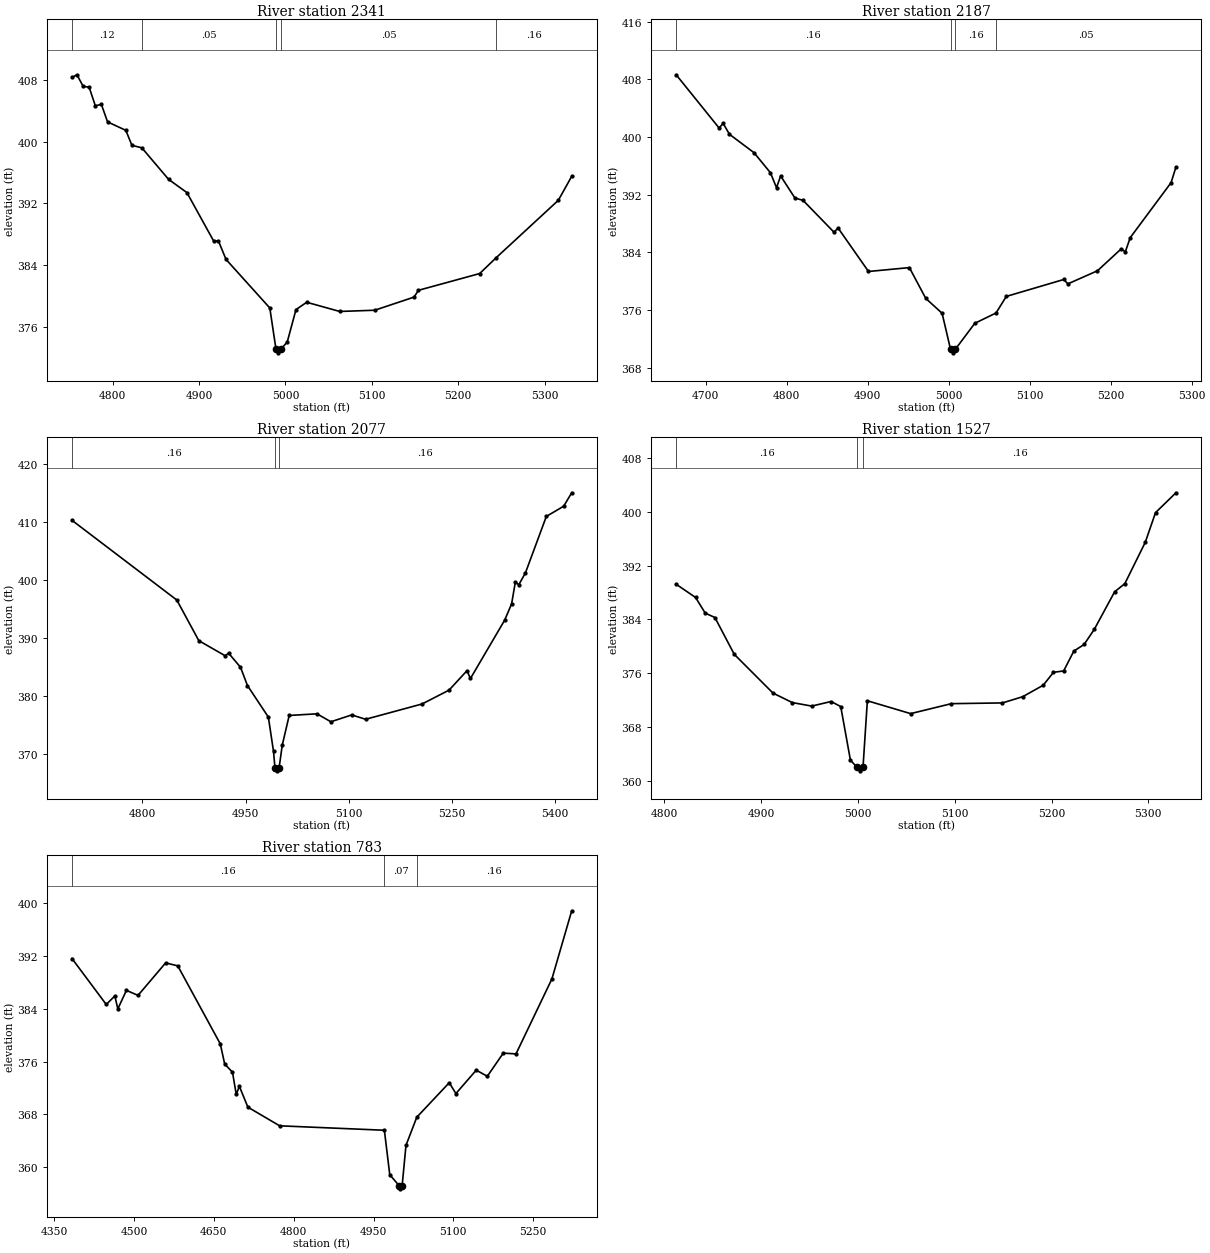
Type RM Length L Ch R = 1 ,2341    ,154,154,154
BEGIN DESCRIPTION:
UNT 029 IN BOCR 4.0
END DESCRIPTION:
XS GIS Cut Line= 3
      3775379.32     10608058.68      3775262.11     10607941.47
      3774854.33      10607876.4
#Sta/Elev= 30
  4752.8  408.33  4758.6  408.67  4765.7  407.18  4772.7  407.06  4779.8  404.67
  4786.9  404.82    4794  402.57  4815.2  401.47  4822.2  399.53  4833.7  399.21
  4864.7  395.12  4885.9  393.41  4916.8  387.15  4922.4  387.15  4931.2  384.75
  4981.9  378.46    4989  373.15  4991.7  372.65    4995  373.15  5002.1  374.06
  5012.2  378.25  5024.6   379.2  5062.9  378.01  5103.4  378.17  5148.9  379.87
    5154  380.75  5224.9  382.92  5243.7  384.94    5316  392.41  5331.5  395.52
#Mann= 5 ,-1 , 0
  4752.8     .12       0  4833.7     .05       0    4989     .04       0
    4995     .05       0  5243.7     .16       0
Bank Sta=4989,4995
XS Rating Curve= 0 ,0
Exp/Cntr=0.3,0.1

Type RM Length L Ch R = 1 ,2187    ,110,110,110
BEGIN DESCRIPTION:
UNT 029 IN BOCR 3.0
END DESCRIPTION:
XS GIS Cut Line= 2
      3775474.76     10607832.96      3774863.67     10607746.28
#Sta/Elev= 30
  4663.4  408.65  4716.4  401.26  4721.4   401.9  4729.2  400.39  4759.5  397.84
  4779.7  395.07  4787.3  392.98  4792.4  394.61    4810  391.55  4820.1  391.22
  4858.3   386.8  4863.3  387.39  4900.9  381.35  4951.4  381.89  4971.6  377.62
  4991.8  375.55  5002.2  370.56    5005  370.06  5008.2  370.56  5032.2  374.16
  5058.4  375.59  5071.1  377.89  5142.1  380.24  5147.1  379.63  5183.7  381.45
  5213.1   384.5  5218.1  384.08  5224.1  386.04  5274.6  393.68  5280.6  395.84
#Mann= 4 ,-1 , 0
  4663.4     .16       0  5002.2     .07       0  5008.2     .16       0
  5058.4     .05       0
Bank Sta=5002.2,5008.2
XS Rating Curve= 0 ,0
Exp/Cntr=0.3,0.1

Type RM Length L Ch R = 1 ,2077    ,550,550,550
BEGIN DESCRIPTION:
Mapping XS 07a0eee6
END DESCRIPTION:
XS GIS Cut Line= 2
      3775492.13     10607737.47      3774773.11     10607633.52
#Sta/Elev= 30
  4697.6  410.27    4850  396.51    4882   389.5  4920.3  386.89  4925.3  387.34
  4942.6  384.91  4952.7  381.75  4983.1  376.31  4990.6  370.38  4992.7  367.53
  4995.4  367.03  4998.7  367.53  5003.3  371.46  5013.4  376.59  5053.8  376.87
    5074   375.5  5104.3  376.68  5124.5  375.93  5206.6  378.57  5245.8  380.96
  5271.8  384.31  5276.9  382.97  5326.6  393.03  5336.7  395.84  5342.1  399.58
  5347.2  399.15  5356.9  401.22  5387.2  410.94  5412.4   412.7  5424.1  415.02
#Mann= 3 ,-1 , 0
  4697.6     .16       0  4992.7     .07       0  4998.7     .16       0
Bank Sta=4992.7,4998.7
XS Rating Curve= 0 ,0
Exp/Cntr=0.3,0.1

Type RM Length L Ch R = 1 ,1527    ,744,744,744
BEGIN DESCRIPTION:
UNT 029 IN BOCR 2.0
END DESCRIPTION:
XS GIS Cut Line= 3
      3775349.63     10607160.19      3775149.61     10607160.19
      3774849.56      10607260.2
#Sta/Elev= 30
  4812.2  389.22  4832.2  387.26  4842.2  384.93  4852.2  384.28  4872.2  378.81
  4912.2  373.05  4932.2  371.64  4952.2  371.12  4972.2   371.8  4982.2  371.05
  4992.2  363.09  4999.2     362    5002   361.5  5005.2     362  5009.7  371.91
  5054.4     370  5096.5  371.48  5149.3  371.59  5170.3  372.52  5191.4  374.22
    5202  376.14  5212.5  376.34    5223  379.29  5233.6  380.27  5244.1  382.51
  5265.2  388.11  5275.7  389.31  5296.8  395.45  5307.4  399.86  5328.5  402.81
#Mann= 3 ,-1 , 0
  4812.2     .16       0  4999.2     .07       0  5005.2     .16       0
Bank Sta=4999.2,5005.2
XS Rating Curve= 0 ,0
Exp/Cntr=0.3,0.1

Type RM Length L Ch R = 1 ,783     ,0,0,0
BEGIN DESCRIPTION:
UNT 029 IN BOCR 1.0
END DESCRIPTION:
XS GIS Cut Line= 3
      3775513.84     10606834.69      3775079.82     10606595.98
      3774643.04     10606673.82
#Sta/Elev= 30
  4383.4  391.56  4447.8  384.62  4463.9   385.9  4469.6  383.95  4485.7  386.75
  4507.5  385.99  4559.4   390.9  4582.2  390.45  4662.1  378.66  4670.4  375.61
    4685  374.39  4692.1  371.02  4697.9  372.27  4713.9  369.11  4773.6  366.29
  4970.4  365.62  4980.5  358.91  4997.8  357.27  5000.6  356.77  5003.8  357.27
    5011  363.34  5031.3  367.59  5092.3   372.8  5104.8  371.16    5143   374.7
  5163.8  373.77  5193.8  377.27  5217.7  377.15  5285.2  388.48  5322.4  398.77
#Mann= 3 ,-1 , 0
  4383.4     .16       0  4970.4     .07       0  5031.3     .16       0
Bank Sta=4997.8,5003.8
XS Rating Curve= 0 ,0
Exp/Cntr=0.3,0.1

Chan Stop Cuts=-1
Use User Specified Reach Order=0
Composite Channel Slope=5