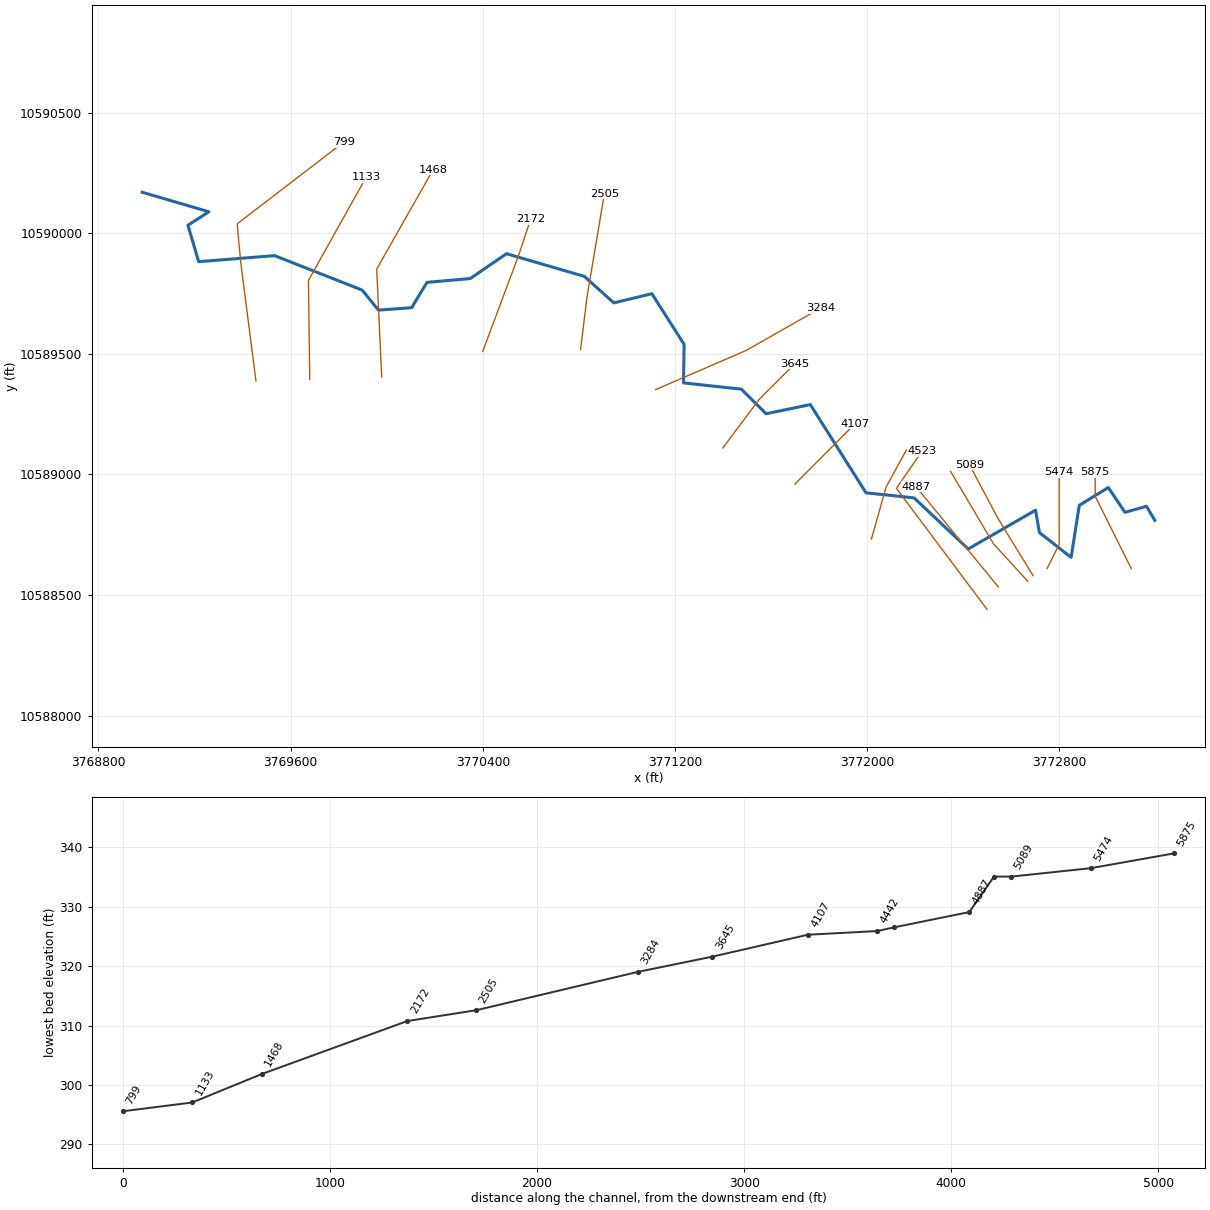
--- UNT 036 IN BOCR.prj (project) ---

Proj Title=UNT 036 IN BOCR Base Level Engineering
Current Plan=p01
Default Exp/Contr=0.3,0.1
English Units
Geom File=g01
Flow File=f01
Plan File=p01
BEGIN DESCRIPTION:
UNT 036 IN BOCR
END DESCRIPTION:

--- UNT 036 IN BOCR.p01 (plan) ---

Plan Title=Multiple Run
Short Identifier=Multiple
Geom File=g01
Flow File=f01
Subcritical Flow
K Sum by GR= 0
Std Step Tol= 0.01
Critical Tol= 0.01
Num of Std Step Trials= 20
Max Error Tol= 0.3
Flow Tol Ratio= 0.001
Split Flow NTrial= 30
Split Flow Tol= 0.02
Split Flow Ratio= 0.02
Log Output Level= 0
Friction Slope Method= 1
Unsteady Friction Slope Method= 2
Unsteady Bridges Friction Slope Method= 1
Parabolic Critical Depth
Global Vel Dist=  1 , 1 , 1
Global Log Level= 0
CheckData=True
Encroach Param= -1, 0, 0, 0
BEGIN DESCRIPTION:
Multiple Run
END DESCRIPTION:

--- UNT 036 IN BOCR.f01 (steady flow) ---

Flow Title=Multiple
Number of Profiles=7
Profile Names=10-year,25-year,50-year,1pct_min,100-year,1pct_plu,500-year
River Rch & RM= UNT 036 IN BOCR,Reach-1,5875
     456     610     736     655     886    1198    1283
River Rch & RM= UNT 036 IN BOCR,Reach-1,2505
     625     852    1041     936    1266    1712    1877
River Rch & RM= UNT 036 IN BOCR,Reach-1,1468
     782    1079    1329    1203    1626    2199    2446
Boundary for River Rch & Prof#=UNT 036 IN BOCR,Reach-1,1
Up Type=0
Dn Type=3
Dn Slope=0.005
Boundary for River Rch & Prof#=UNT 036 IN BOCR,Reach-1,2
Up Type=0
Dn Type=3
Dn Slope=0.005
Boundary for River Rch & Prof#=UNT 036 IN BOCR,Reach-1,3
Up Type=0
Dn Type=3
Dn Slope=0.005
Boundary for River Rch & Prof#=UNT 036 IN BOCR,Reach-1,4
Up Type=0
Dn Type=3
Dn Slope=0.005
Boundary for River Rch & Prof#=UNT 036 IN BOCR,Reach-1,5
Up Type=0
Dn Type=3
Dn Slope=0.005
Boundary for River Rch & Prof#=UNT 036 IN BOCR,Reach-1,6
Up Type=0
Dn Type=3
Dn Slope=0.005
Boundary for River Rch & Prof#=UNT 036 IN BOCR,Reach-1,7
Up Type=0
Dn Type=3
Dn Slope=0.005

--- UNT 036 IN BOCR.g01 (geometry) ---

Geom Title=Existing Conditions

River Reach=UNT 036 IN BOCR,Reach-1
Reach XY= 30
      3773197.83     10588809.95      3773163.25     10588868.00
      3773073.75     10588843.00      3773004.25     10588946.00
      3772883.50     10588872.00      3772849.48     10588656.24
      3772717.50     10588759.00      3772701.50     10588852.00
      3772421.00     10588691.00      3772195.75     10588903.00
      3771995.50     10588924.00      3771763.75     10589290.00
      3771579.50     10589252.00      3771476.75     10589354.00
      3771235.75     10589380.00      3771238.25     10589540.00
      3771104.00     10589750.00      3770945.50     10589712.00
      3770822.75     10589822.00      3770498.75     10589916.00
      3770348.00     10589813.00      3770167.50     10589797.00
      3770104.00     10589692.00      3769965.50     10589682.00
      3769898.00     10589765.00      3769533.25     10589908.00
      3769217.25     10589883.00      3769172.50     10590034.00
      3769259.75     10590090.00      3768982.00     10590171.00

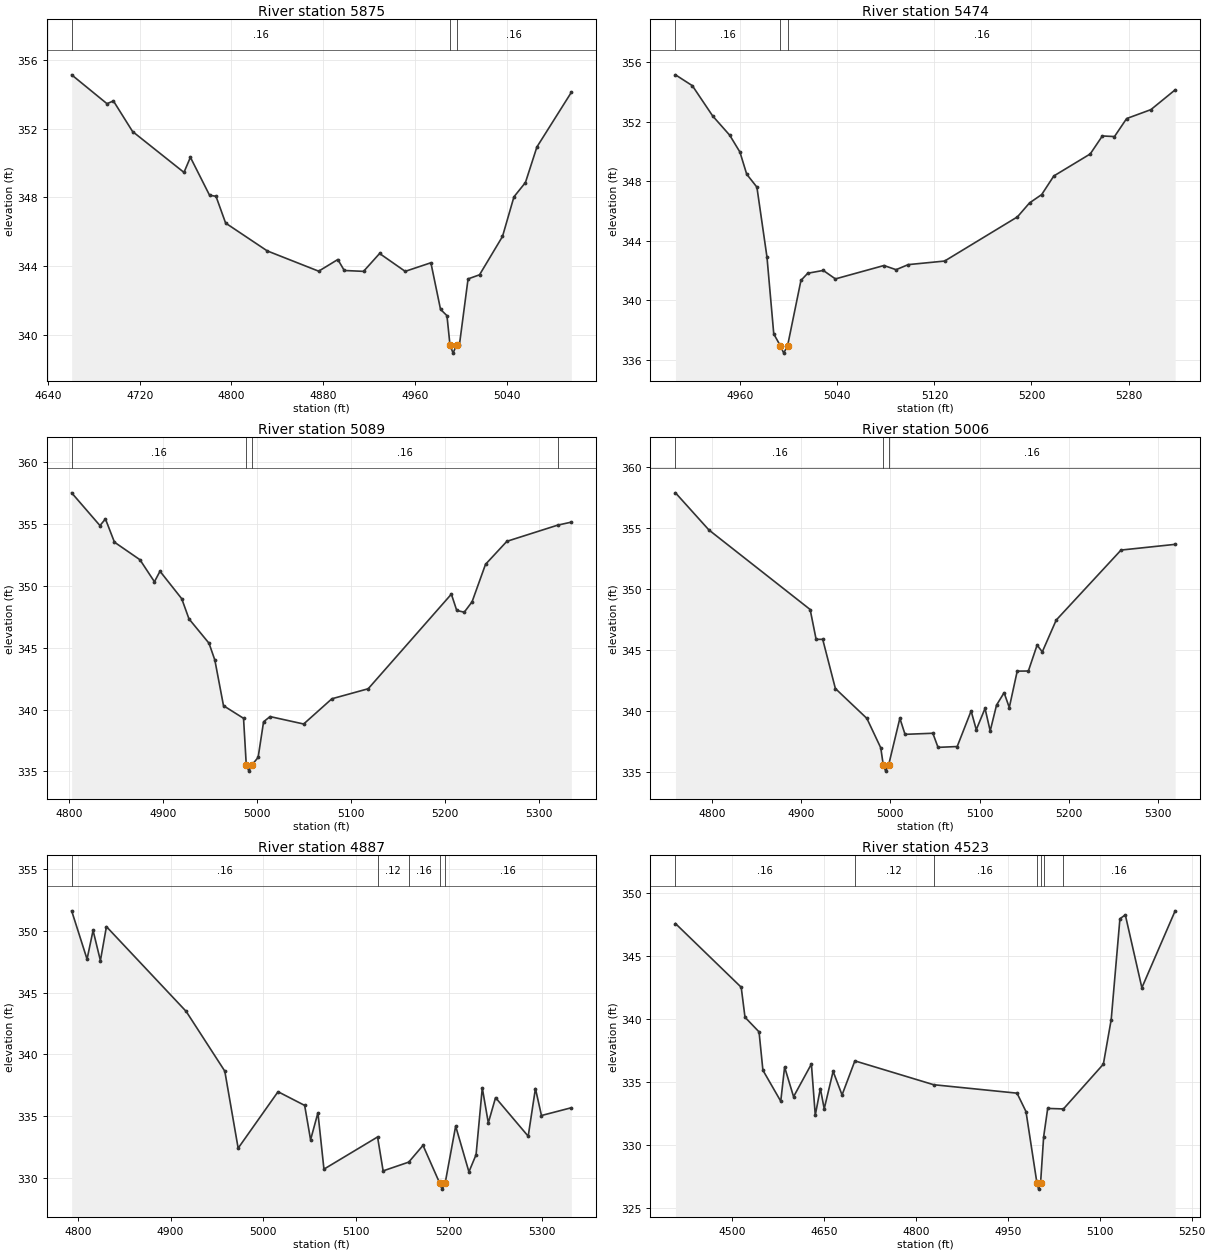
Type RM Length L Ch R = 1,5875,401,401,401
BEGIN DESCRIPTION:
UNT 036 IN BOCR 10.0
END DESCRIPTION:
XS GIS Cut Line= 3
      3773099.63     10588610.15      3772949.61     10588910.19
      3772949.61     10589010.24
#Sta/Elev= 30
  4660.7  355.13  4691.5  353.45  4697.1  353.61  4713.8  351.83  4758.6  349.45
  4764.2  350.33  4780.9  348.12  4786.5  348.06  4794.9  346.50  4831.2  344.88
  4876.0  343.70  4892.7  344.38  4898.3  343.74  4915.1  343.69  4929.1  344.73
  4951.4  343.69  4973.8  344.19  4982.2  341.48  4987.8  341.11  4990.4  339.43
  4993.1  338.93  4996.4  339.43  4998.7  339.43  5006.2  343.25  5016.2  343.49
  5036.2  345.72  5046.2  348.03  5056.2  348.86  5066.2  350.93  5096.2  354.11
#Mann=3,-1,0
  4660.7    0.16       0  4990.4    0.07       0  4996.4    0.16       0
Bank Sta=4990.4,4996.4
Exp/Cntr=0.3,0.1

Type RM Length L Ch R = 1,5474,385,385,385
BEGIN DESCRIPTION:
UNT 036 IN BOCR 9.0
END DESCRIPTION:
XS GIS Cut Line= 3
      3772749.62     10588610.21      3772799.61     10588710.19
      3772799.61     10589010.21
#Sta/Elev= 30
  4906.6  355.16  4920.5  354.43  4937.3  352.39  4951.3  351.10  4959.7  349.97
  4965.3  348.48  4973.7  347.61  4982.0  342.91  4987.6  337.74  4993.0  336.95
  4995.8  336.45  4999.0  336.95  5010.0  341.34  5015.6  341.82  5028.4  342.01
  5038.4  341.44  5078.4  342.34  5088.4  342.06  5098.4  342.40  5128.4  342.64
  5188.4  345.61  5198.4  346.55  5208.4  347.11  5218.4  348.36  5248.4  349.84
  5258.4  351.05  5268.4  351.01  5278.4  352.22  5298.4  352.82  5318.4  354.15
#Mann=3,-1,0
  4906.6    0.16       0  4993.0    0.07       0  4999.0    0.16       0
Bank Sta=4993,4999
Exp/Cntr=0.3,0.1

Type RM Length L Ch R = 1,5089,83,83,83
BEGIN DESCRIPTION:
Mapping XS ef2c77fd
END DESCRIPTION:
XS GIS Cut Line= 3
      3772690.91     10588580.50      3772545.49     10588817.06
      3772426.13     10589040.61
#Sta/Elev= 30
  4803.0  357.53  4833.1  354.88  4838.9  355.42  4848.5  353.54  4875.6  352.12
  4891.0  350.34  4896.9  351.19  4920.0  348.97  4927.7  347.34  4949.0  345.37
  4955.2  344.01  4964.4  340.32  4985.7  339.30  4988.6  335.53  4991.4  335.03
  4994.6  335.53  5001.2  336.14  5007.0  339.02  5013.9  339.44  5049.6  338.84
  5079.6  340.88  5118.2  341.69  5206.6  349.34  5212.3  348.02  5220.3  347.88
  5228.6  348.72  5242.9  351.75  5265.6  353.61  5319.7  354.92  5334.1  355.16
#Mann=4,-1,0
  4803.0    0.16       0  4988.6    0.07       0  4994.6    0.16       0
  5319.7    0.05       0
Bank Sta=4988.6,4994.6
Exp/Cntr=0.3,0.1

Type RM Length L Ch R = 1,5006,119,119,119
BEGIN DESCRIPTION:
UNT 036 IN BOCR 8.0
END DESCRIPTION:
XS GIS Cut Line= 3
      3772669.16     10588556.68      3772525.96     10588712.90
      3772348.00     10589012.40
#Sta/Elev= 30
  4759.0  357.89  4796.5  354.84  4910.0  348.31  4916.7  345.86  4924.1  345.86
  4938.3  341.82  4973.6  339.37  4989.2  336.95  4992.0  335.54  4994.7  335.04
  4998.0  335.54  5010.6  339.38  5016.4  338.06  5047.6  338.15  5053.4  336.99
  5074.9  337.06  5090.5  339.98  5096.3  338.44  5106.1  340.19  5111.9  338.34
  5119.0  340.46  5127.5  341.48  5133.3  340.26  5142.2  343.25  5154.7  343.26
  5164.5  345.39  5170.3  344.83  5185.9  347.44  5258.6  353.19  5319.3  353.66
#Mann=3,-1,0
  4759.0    0.16       0  4992.0    0.07       0  4998.0    0.16       0
Bank Sta=4992,4998
Exp/Cntr=0.3,0.1

Type RM Length L Ch R = 1,4887,364,364,364
BEGIN DESCRIPTION:
Mapping XS d8cc083c
END DESCRIPTION:
XS GIS Cut Line= 2
      3772546.44     10588533.87      3772203.62     10588949.40
#Sta/Elev= 30
  4793.3  351.64  4809.9  347.72  4816.4  350.05  4824.3  347.60  4830.8  350.36
  4916.8  343.48  4958.4  338.64  4972.8  332.39  5015.8  336.97  5044.5  335.86
  5050.9  333.07  5058.8  335.26  5065.3  330.69  5123.1  333.30  5129.1  330.55
  5156.7  331.26  5172.1  332.62  5190.0  329.57  5192.7  329.07  5196.0  329.57
  5207.3  334.18  5221.6  330.47  5229.3  331.86  5236.0  337.28  5242.5  334.44
  5250.3  336.49  5285.5  333.36  5293.3  337.23  5299.8  335.04  5332.0  335.67
#Mann=5,-1,0
  4793.3    0.16       0  5123.1    0.12       0  5156.7    0.16       0
  5190.0    0.07       0  5196.0    0.16       0
Bank Sta=5190,5196
Exp/Cntr=0.3,0.1

Type RM Length L Ch R = 1,4523,81,81,81
BEGIN DESCRIPTION:
Mapping XS 215b7790
END DESCRIPTION:
XS GIS Cut Line= 3
      3772499.51     10588440.19      3772121.93     10588942.75
      3772228.30     10589095.82
#Sta/Elev= 30
  4408.0  347.56  4515.2  342.51  4521.4  340.13  4544.3  338.97  4550.6  335.93
  4579.7  333.47  4586.0  336.18  4600.6  333.83  4629.7  336.42  4636.0  332.36
  4644.3  334.48  4650.6  332.87  4665.1  335.84  4679.7  333.97  4700.6  336.67
  4829.1  334.78  4965.1  334.11  4979.7  332.65  4997.5  327.00  5000.2  326.50
  5003.5  327.00  5008.5  330.65  5015.1  332.90  5040.8  332.86  5105.9  336.41
  5118.7  339.95  5132.9  347.94  5141.7  348.25  5168.7  342.47  5223.0  348.57
#Mann=7,-1,0
  4408.0    0.16       0  4700.6    0.12       0  4829.1    0.16       0
  4997.5    0.07       0  5003.5    0.16       0  5008.5    0.12       0
  5040.8    0.16       0
Bank Sta=4997.5,5003.5
Exp/Cntr=0.3,0.1

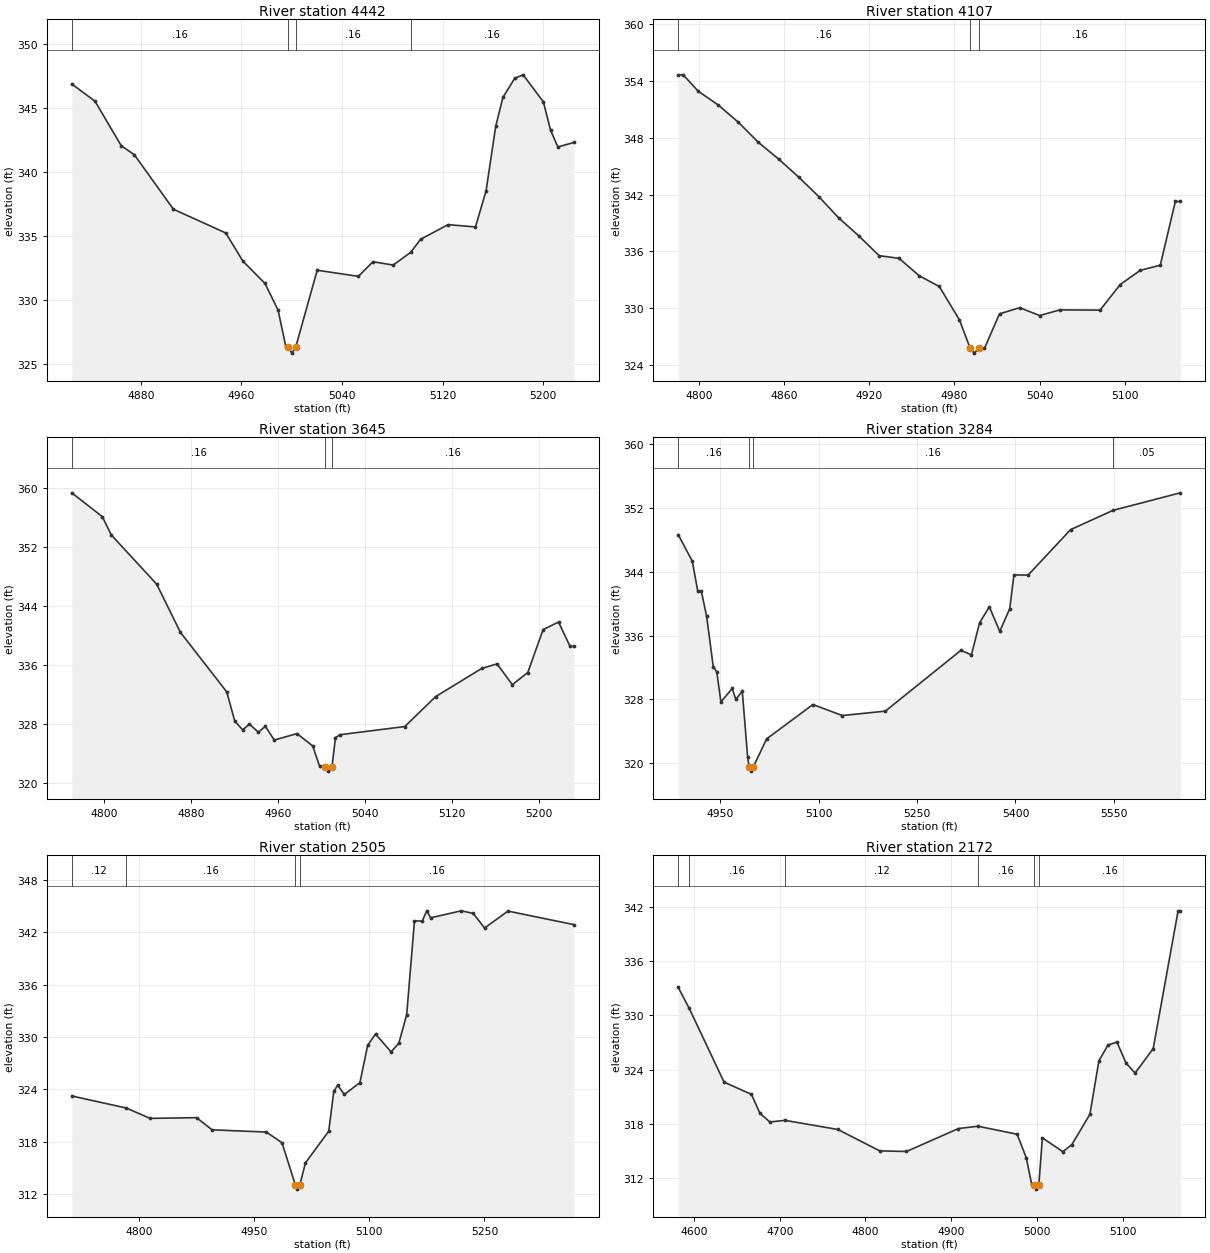
Type RM Length L Ch R = 1,4442,335,335,335
BEGIN DESCRIPTION:
UNT 036 IN BOCR 7.0
END DESCRIPTION:
XS GIS Cut Line= 3
      3772018.14     10588732.41      3772078.91     10588947.27
      3772163.55     10589101.36
#Sta/Elev= 30
  4825.2  346.85  4843.7  345.50  4864.5  342.04  4874.9  341.34  4906.0  337.09
  4947.6  335.24  4961.2  333.05  4978.8  331.31  4989.2  329.23  4995.2  326.46
  4997.3  326.38  5000.1  325.88  5003.3  326.38  5020.3  332.34  5053.0  331.86
  5064.6  333.00  5080.7  332.74  5094.6  333.73  5102.5  334.75  5124.3  335.89
  5146.1  335.71  5154.5  338.51  5162.2  343.54  5167.9  345.80  5177.3  347.29
  5184.0  347.56  5200.1  345.45  5205.8  343.25  5211.6  341.94  5224.3  342.29
#Mann=4,-1,0
  4825.2    0.16       0  4997.3    0.07       0  5003.3    0.16       0
  5094.6    0.16       0
Bank Sta=4997.3,5003.3
Exp/Cntr=0.3,0.1

Type RM Length L Ch R = 1,4107,462,462,462
BEGIN DESCRIPTION:
UNT 036 IN BOCR 6.0
END DESCRIPTION:
XS GIS Cut Line= 3
      3771699.63     10588960.21      3771849.61     10589110.19
      3771949.59     10589210.17
#Sta/Elev= 30
  4785.6  354.66  4789.1  354.66  4799.7  352.93  4813.9  351.46  4828.0  349.64
  4842.1  347.52  4856.3  345.76  4870.4  343.86  4884.6  341.79  4898.7  339.53
  4912.8  337.64  4927.0  335.56  4941.1  335.27  4955.3  333.43  4969.4  332.30
  4983.6  328.77  4991.2  325.76  4993.9  325.26  4997.2  325.76  5001.2  325.76
  5011.8  329.41  5026.0  330.06  5040.1  329.23  5054.3  329.83  5082.6  329.80
  5096.7  332.49  5110.8  334.00  5125.0  334.55  5135.6  341.28  5139.1  341.28
#Mann=3,-1,0
  4785.6    0.16       0  4991.2    0.07       0  4997.2    0.16       0
Bank Sta=4991.2,4997.2
Exp/Cntr=0.3,0.1

Type RM Length L Ch R = 1,3645,361,361,361
BEGIN DESCRIPTION:
UNT 036 IN BOCR 5.0
END DESCRIPTION:
XS GIS Cut Line= 3
      3771399.62     10589110.21      3771549.61     10589310.19
      3771699.60     10589460.18
#Sta/Elev= 30
  4770.3  359.33  4798.4  356.10  4806.7  353.61  4848.4  346.95  4870.3  340.40
  4913.0  332.31  4920.3  328.36  4927.6  327.17  4933.8  327.95  4942.1  326.84
  4948.4  327.66  4956.7  325.79  4977.6  326.66  4992.1  324.98  4998.4  322.22
  5003.7  322.07  5006.5  321.57  5009.7  322.07  5013.0  326.11  5017.1  326.51
  5076.8  327.62  5105.1  331.67  5147.6  335.50  5161.7  336.12  5175.8  333.30
  5190.0  334.95  5204.1  340.77  5218.3  341.80  5228.9  338.50  5232.4  338.50
#Mann=3,-1,0
  4770.3    0.16       0  5003.7    0.07       0  5009.7    0.16       0
Bank Sta=5003.7,5009.7
Exp/Cntr=0.3,0.1

Type RM Length L Ch R = 1,3284,779,779,779
BEGIN DESCRIPTION:
UNT 036 IN BOCR 4.0
END DESCRIPTION:
XS GIS Cut Line= 3
      3771119.83     10589352.25      3771494.86     10589513.72
      3771805.97     10589690.02
#Sta/Elev= 30
  4885.6  348.65  4907.1  345.31  4915.4  341.55  4920.9  341.54  4928.9  338.41
  4939.0  332.11  4944.4  331.44  4950.7  327.67  4968.0  329.37  4973.4  327.98
  4983.3  329.03  4991.5  320.73  4993.9  319.50  4996.7  319.00  4999.9  319.50
  5020.5  323.05  5091.1  327.35  5135.8  325.97  5201.5  326.52  5316.9  334.15
  5332.8  333.57  5345.3  337.60  5360.2  339.60  5376.1  336.52  5391.3  339.37
  5397.7  343.60  5419.3  343.58  5484.2  349.28  5548.7  351.69  5651.5  353.89
#Mann=4,-1,0
  4885.6    0.16       0  4993.9    0.07       0  4999.9    0.16       0
  5548.7    0.05       0
Bank Sta=4993.9,4999.9
Exp/Cntr=0.3,0.1

Type RM Length L Ch R = 1,2505,333,333,333
BEGIN DESCRIPTION:
UNT 036 IN BOCR 3.0
END DESCRIPTION:
XS GIS Cut Line= 3
      3770807.35     10589518.89      3770833.40     10589732.47
      3770906.32     10590164.81
#Sta/Elev= 30
  4712.8  323.25  4783.6  321.87  4814.8  320.68  4875.3  320.76  4895.4  319.37
  4966.2  319.11  4986.5  317.88  5003.8  313.07  5006.5  312.57  5009.8  313.07
  5016.9  315.57  5047.3  319.21  5053.9  323.78  5059.0  324.48  5067.6  323.42
  5087.9  324.78  5098.0  329.06  5108.2  330.35  5128.5  328.30  5138.6  329.31
  5148.8  332.58  5158.9  343.31  5169.0  343.30  5174.9  344.46  5180.0  343.67
  5219.7  344.47  5235.4  344.18  5250.2  342.50  5280.6  344.44  5366.4  342.89
#Mann=4,-1,0
  4712.8    0.12       0  4783.6    0.16       0  5003.8    0.07       0
  5009.8    0.16       0
Bank Sta=5003.8,5009.8
Exp/Cntr=0.3,0.1

Type RM Length L Ch R = 1,2172,704,704,704
BEGIN DESCRIPTION:
UNT 036 IN BOCR 2.0
END DESCRIPTION:
XS GIS Cut Line= 3
      3770399.62     10589510.21      3770549.61     10589910.19
      3770599.61     10590060.20
#Sta/Elev= 30
  4581.7  333.09  4594.6  330.76  4635.1  322.61  4667.1  321.24  4676.9  319.16
  4688.5  318.19  4706.1  318.37  4767.7  317.36  4816.6  314.99  4847.8  314.92
  4908.3  317.46  4931.1  317.72  4976.8  316.83  4987.5  314.20  4993.7  311.29
  4996.1  311.25  4998.8  310.75  5002.1  311.25  5006.2  316.43  5030.0  314.90
  5040.5  315.67  5061.6  319.04  5072.1  324.96  5082.7  326.72  5093.2  327.03
  5103.7  324.72  5114.3  323.61  5135.4  326.32  5164.4  341.58  5167.0  341.58
#Mann=6,-1,0
  4581.7    0.12       0  4594.6    0.16       0  4706.1    0.12       0
  4931.1    0.16       0  4996.1    0.07       0  5002.1    0.16       0
Bank Sta=4996.1,5002.1
Exp/Cntr=0.3,0.1

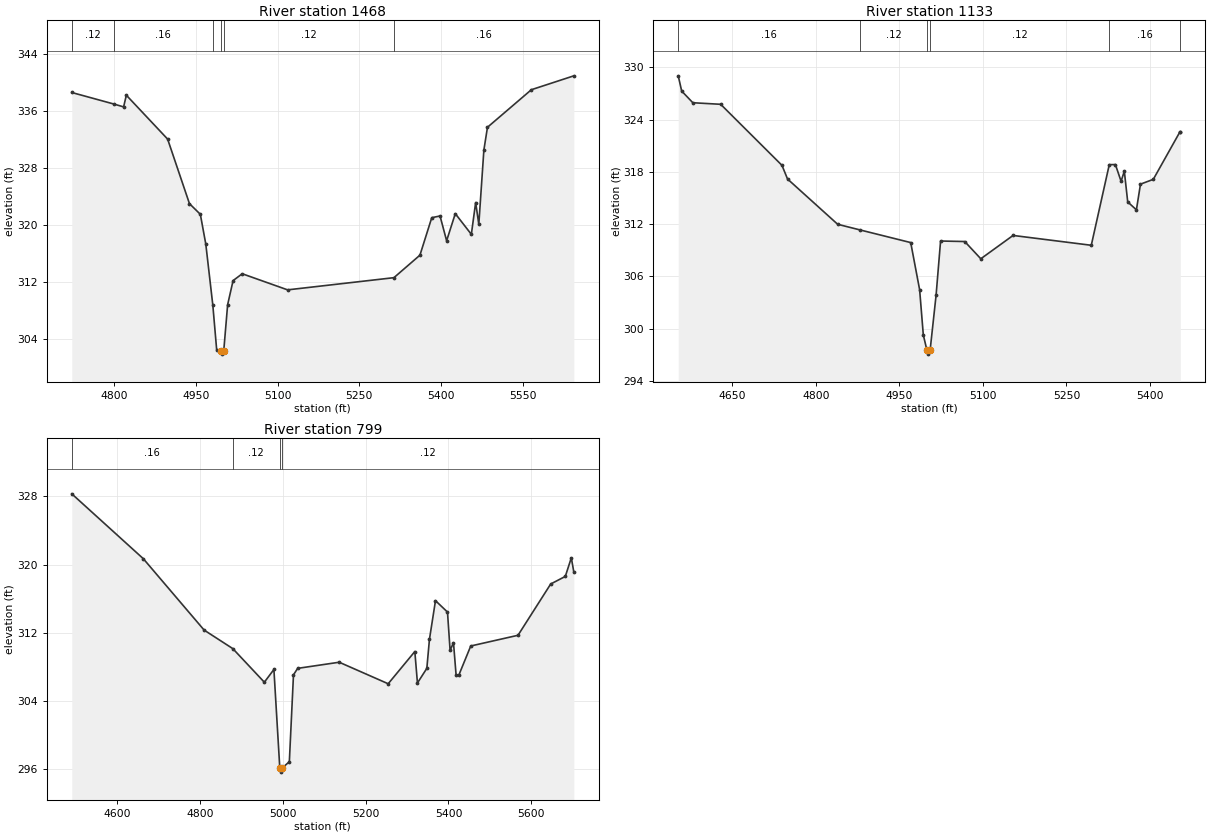
Type RM Length L Ch R = 1,1468,335,335,335
BEGIN DESCRIPTION:
UNT 036 IN BOCR 1.0
END DESCRIPTION:
XS GIS Cut Line= 3
      3769979.23     10589404.34      3769958.40     10589852.26
      3770192.76     10590263.69
#Sta/Elev= 30
  4722.1  338.55  4799.0  336.94  4817.3  336.53  4822.3  338.17  4898.1  332.01
  4938.2  322.95  4958.2  321.45  4968.2  317.27  4981.1  308.70  4988.2  302.41
  4995.2  302.33  4998.0  301.83  5001.2  302.33  5008.3  308.77  5018.3  312.15
  5035.1  313.11  5118.4  310.85  5313.6  312.56  5361.4  315.72  5383.1  320.98
  5398.3  321.22  5410.4  317.74  5426.3  321.55  5455.8  318.64  5463.7  323.11
  5469.5  320.05  5478.8  330.47  5485.4  333.67  5566.0  338.94  5644.0  340.89
#Mann=6,-1,0
  4722.1    0.12       0  4799.0    0.16       0  4981.1    0.12       0
  4995.2    0.07       0  5001.2    0.12       0  5313.6    0.16       0
Bank Sta=4995.2,5001.2
Exp/Cntr=0.3,0.1

Type RM Length L Ch R = 1,1133,334,334,334
BEGIN DESCRIPTION:
Mapping XS c97e874d
END DESCRIPTION:
XS GIS Cut Line= 3
      3769679.59     10589393.97      3769674.38     10589805.41
      3769913.98     10590232.53
#Sta/Elev= 30
  4553.1  329.02  4559.3  327.27  4579.3  325.93  4629.3  325.75  4739.3  318.74
  4749.3  317.17  4839.3  311.97  4880.2  311.31  4970.4  309.87  4986.4  304.45
  4993.0  299.26  4999.3  297.56  5002.1  297.06  5005.3  297.56  5015.9  303.80
  5024.0  310.05  5067.4  309.99  5096.2  308.01  5154.1  310.69  5294.5  309.56
  5326.8  318.82  5337.8  318.83  5348.0  316.91  5353.8  318.07  5359.9  314.54
  5375.5  313.63  5382.8  316.58  5405.8  317.13  5453.4  322.56  5454.3  322.56
#Mann=6,-1,0
  4553.1    0.16       0  4880.2    0.12       0  4999.3    0.07       0
  5005.3    0.12       0  5326.8    0.16       0  5453.4    0.12       0
Bank Sta=4999.3,5005.3
Exp/Cntr=0.3,0.1

Type RM Length L Ch R = 1,799,0,0,0
BEGIN DESCRIPTION:
Mapping XS 0e5396a6
END DESCRIPTION:
XS GIS Cut Line= 4
      3769455.63     10589388.70      3769393.13     10589873.12
      3769377.50     10590039.78      3769820.18     10590378.30
#Sta/Elev= 30
  4489.9  328.31  4662.8  320.68  4809.7  312.29  4879.0  310.11  4955.2  306.16
  4978.3  307.66  4992.5  296.09  4995.2  295.59  4998.5  296.09  5015.6  296.81
  5025.6  307.03  5035.7  307.79  5136.1  308.51  5254.4  305.98  5318.8  309.77
  5325.1  306.07  5347.8  307.79  5354.1  311.20  5368.7  315.75  5397.7  314.41
  5404.0  309.90  5412.2  310.81  5418.5  306.99  5425.3  307.02  5453.9  310.42
  5568.1  311.68  5647.1  317.71  5682.4  318.60  5696.9  320.79  5703.0  319.10
#Mann=4,-1,0
  4489.9    0.16       0  4879.0    0.12       0  4992.5    0.07       0
  4998.5    0.12       0
Bank Sta=4992.5,4998.5
Exp/Cntr=0.3,0.1

Chan Stop Cuts=-1