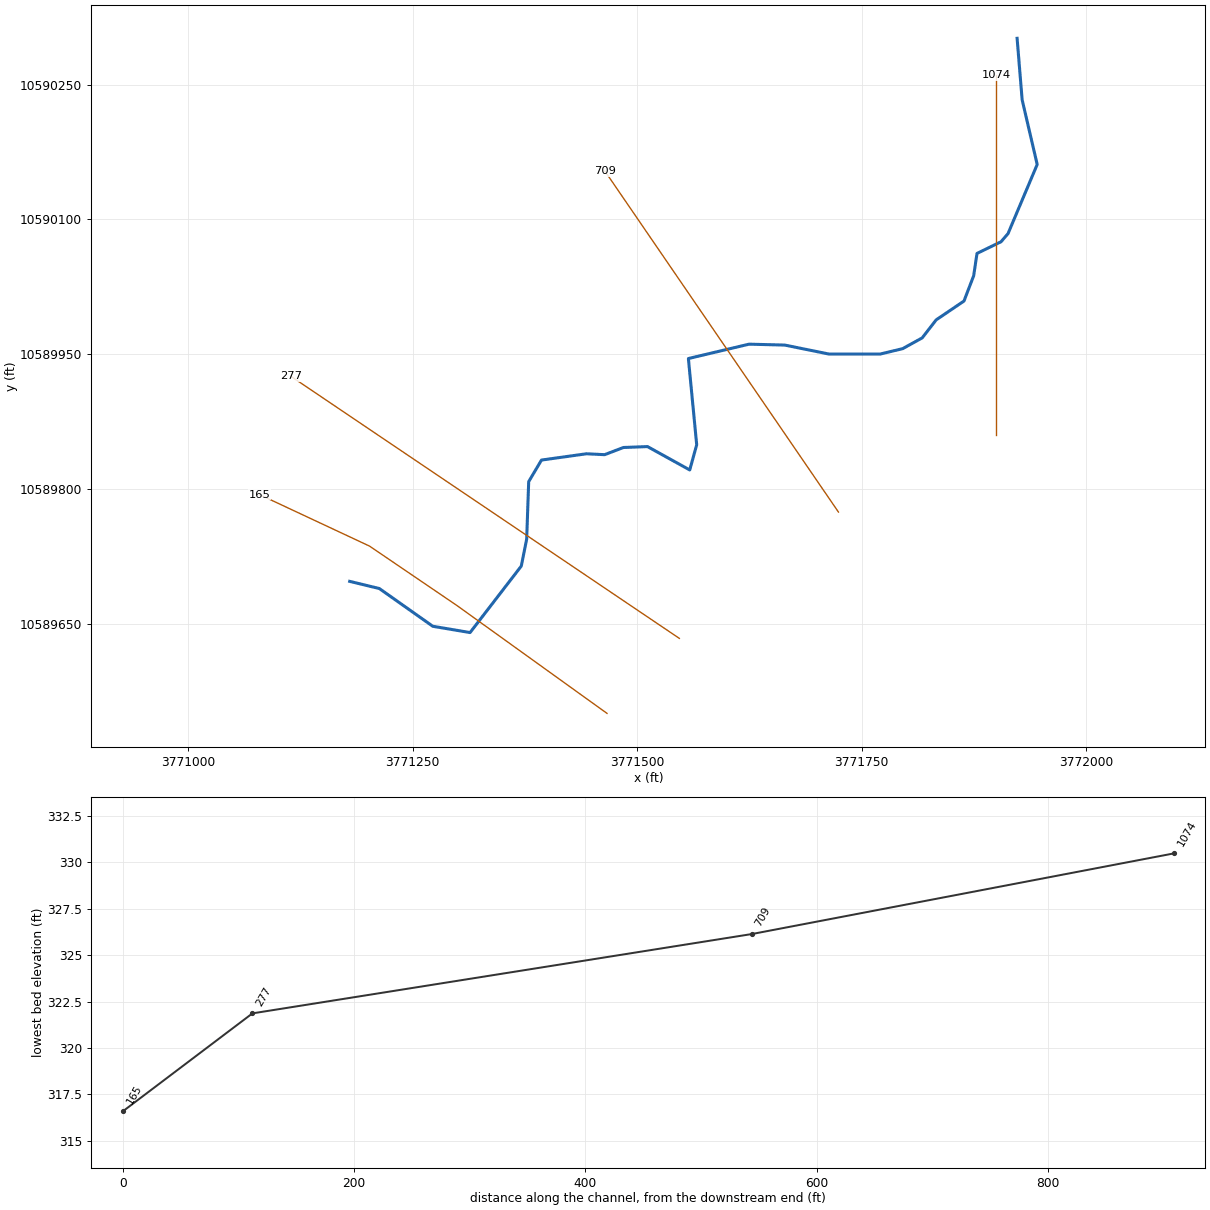
--- UNT 037 IN BOCR.prj (project) ---

Proj Title=UNT 037 IN BOCR Base Level Engineering
Current Plan=p01
Default Exp/Contr=0.3,0.1
English Units
Geom File=g01
Flow File=f01
Plan File=p01
BEGIN DESCRIPTION:
UNT 037 IN BOCR
END DESCRIPTION:

--- UNT 037 IN BOCR.p01 (plan) ---

Plan Title=Multiple Run
Short Identifier=Multiple
Geom File=g01
Flow File=f01
Subcritical Flow
K Sum by GR= 0
Std Step Tol= 0.01
Critical Tol= 0.01
Num of Std Step Trials= 20
Max Error Tol= 0.3
Flow Tol Ratio= 0.001
Split Flow NTrial= 30
Split Flow Tol= 0.02
Split Flow Ratio= 0.02
Log Output Level= 0
Friction Slope Method= 1
Unsteady Friction Slope Method= 2
Unsteady Bridges Friction Slope Method= 1
Parabolic Critical Depth
Global Vel Dist=  1 , 1 , 1
Global Log Level= 0
CheckData=True
Encroach Param= -1, 0, 0, 0
BEGIN DESCRIPTION:
Multiple Run
END DESCRIPTION:

--- UNT 037 IN BOCR.f01 (steady flow) ---

Flow Title=Multiple
Number of Profiles=7
Profile Names=10-year,25-year,50-year,1pct_min,100-year,1pct_plu,500-year
River Rch & RM= UNT 037 IN BOCR,Reach-1,1074
     237     302     353     305     412     558     562
Boundary for River Rch & Prof#=UNT 037 IN BOCR,Reach-1,1
Up Type=0
Dn Type=3
Dn Slope=0.005
Boundary for River Rch & Prof#=UNT 037 IN BOCR,Reach-1,2
Up Type=0
Dn Type=3
Dn Slope=0.005
Boundary for River Rch & Prof#=UNT 037 IN BOCR,Reach-1,3
Up Type=0
Dn Type=3
Dn Slope=0.005
Boundary for River Rch & Prof#=UNT 037 IN BOCR,Reach-1,4
Up Type=0
Dn Type=3
Dn Slope=0.005
Boundary for River Rch & Prof#=UNT 037 IN BOCR,Reach-1,5
Up Type=0
Dn Type=3
Dn Slope=0.005
Boundary for River Rch & Prof#=UNT 037 IN BOCR,Reach-1,6
Up Type=0
Dn Type=3
Dn Slope=0.005
Boundary for River Rch & Prof#=UNT 037 IN BOCR,Reach-1,7
Up Type=0
Dn Type=3
Dn Slope=0.005

--- UNT 037 IN BOCR.g01 (geometry) ---

Geom Title=Existing Conditions

River Reach=UNT 037 IN BOCR,Reach-1
Reach XY= 30
      3771922.88     10590301.42      3771928.50     10590233.00
      3771945.25     10590161.00      3771912.75     10590084.00
      3771905.00     10590075.00      3771878.25     10590062.00
      3771874.50     10590037.00      3771863.75     10590009.00
      3771832.75     10589988.00      3771817.25     10589968.00
      3771795.50     10589956.00      3771770.50     10589950.00
      3771713.50     10589950.00      3771664.25     10589960.00
      3771624.50     10589961.00      3771557.00     10589945.00
      3771566.25     10589849.00      3771558.50     10589821.00
      3771511.50     10589847.00      3771484.75     10589846.00
      3771463.75     10589838.00      3771443.50     10589839.00
      3771393.50     10589832.00      3771379.25     10589808.00
      3771377.00     10589744.00      3771371.00     10589714.00
      3771314.00     10589640.00      3771272.50     10589647.00
      3771213.00     10589689.00      3771180.00     10589697.00

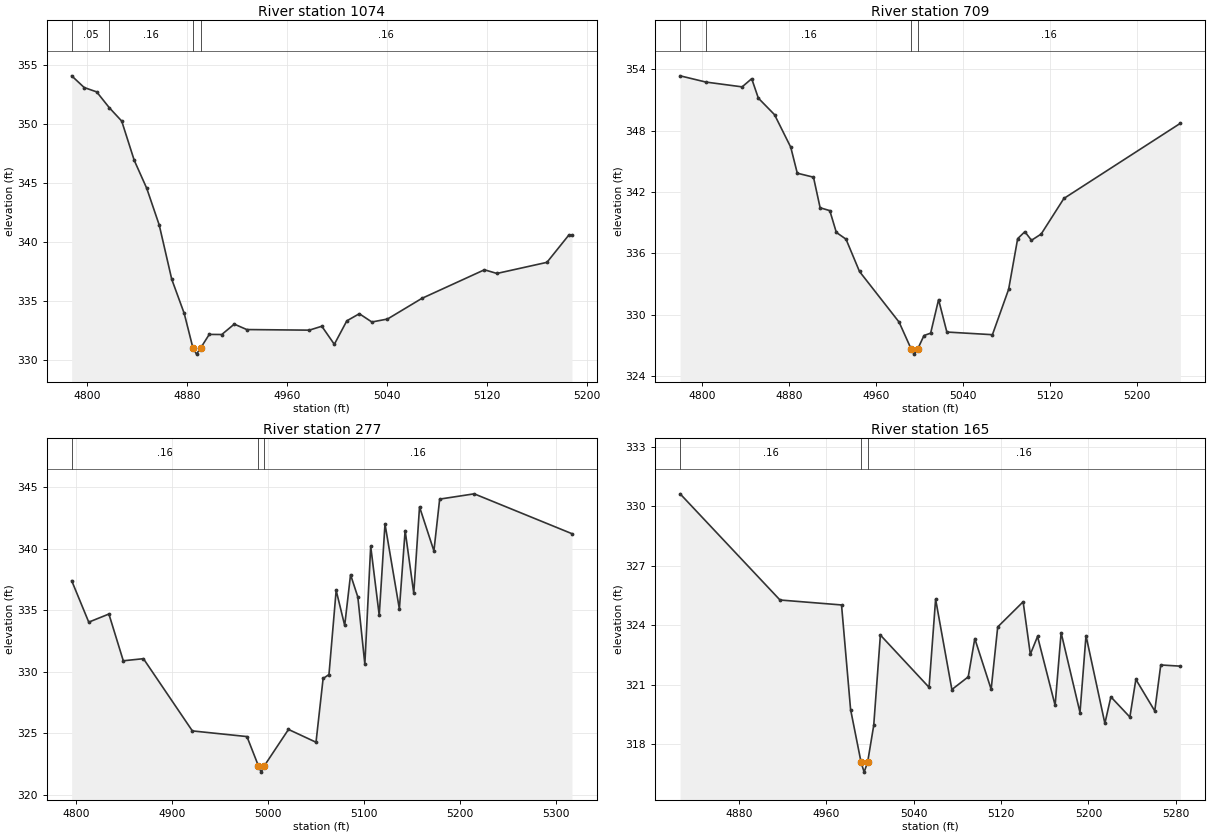
Type RM Length L Ch R = 1,1074,365,365,365
BEGIN DESCRIPTION:
UNT 037 IN BOCR 2.0
END DESCRIPTION:
XS GIS Cut Line= 3
      3771899.61     10589860.18      3771899.61     10590110.19
      3771899.61     10590260.18
#Sta/Elev= 30
  4787.8  354.05  4797.8  353.06  4807.8  352.69  4817.8  351.36  4827.8  350.22
  4837.8  346.90  4847.8  344.53  4857.8  341.42  4867.8  336.83  4877.8  333.93
  4884.8  330.99  4887.6  330.49  4890.8  330.99  4897.8  332.16  4907.8  332.15
  4917.8  333.03  4927.8  332.57  4977.8  332.52  4987.8  332.85  4997.8  331.32
  5007.8  333.31  5017.8  333.91  5027.8  333.21  5040.3  333.46  5067.8  335.21
  5117.8  337.63  5127.8  337.32  5167.8  338.26  5185.3  340.57  5187.8  340.57
#Mann=4,-1,0
  4787.8    0.05       0  4817.8    0.16       0  4884.8    0.07       0
  4890.8    0.16       0
Bank Sta=4884.8,4890.8
Exp/Cntr=0.3,0.1

Type RM Length L Ch R = 1,709,432,432,432
BEGIN DESCRIPTION:
Mapping XS 5acfce20
END DESCRIPTION:
XS GIS Cut Line= 2
      3771724.02     10589774.15      3771464.13     10590153.58
#Sta/Elev= 30
  4779.7  353.35  4803.4  352.74  4836.7  352.27  4845.5  353.07  4851.6  351.17
  4866.5  349.55  4881.4  346.37  4887.4  343.83  4902.3  343.44  4908.4  340.45
  4917.3  340.17  4923.3  338.04  4932.2  337.38  4944.6  334.22  4981.0  329.27
  4992.1  326.64  4994.8  326.14  4998.1  326.64  5003.9  327.96  5010.0  328.19
  5017.3  331.47  5024.9  328.30  5066.8  328.04  5081.7  332.48  5090.0  337.43
  5096.6  338.11  5102.7  337.27  5111.6  337.88  5132.5  341.36  5239.6  348.71
#Mann=4,-1,0
  4779.7    0.05       0  4803.4    0.16       0  4992.1    0.07       0
  4998.1    0.16       0
Bank Sta=4992.1,4998.1
Exp/Cntr=0.3,0.1

Type RM Length L Ch R = 1,277,112,112,112
BEGIN DESCRIPTION:
UNT 037 IN BOCR 1.0
END DESCRIPTION:
XS GIS Cut Line= 2
      3771546.92     10589633.53      3771114.61     10589925.21
#Sta/Elev= 30
  4795.2  337.42  4813.0  334.05  4834.0  334.71  4849.0  330.91  4870.0  331.08
  4921.0  325.21  4977.9  324.75  4989.9  322.36  4992.7  321.86  4995.9  322.36
  5021.2  325.33  5049.9  324.29  5057.3  329.47  5063.4  329.79  5070.9  336.63
  5079.8  333.78  5085.9  337.91  5093.5  336.09  5100.8  330.63  5106.9  340.22
  5115.8  334.60  5121.8  342.03  5136.8  335.12  5142.8  341.49  5151.8  336.40
  5157.8  343.42  5172.8  339.84  5178.8  344.05  5214.8  344.48  5316.7  341.24
#Mann=3,-1,0
  4795.2    0.16       0  4989.9    0.07       0  4995.9    0.16       0
Bank Sta=4989.9,4995.9
Exp/Cntr=0.3,0.1

Type RM Length L Ch R = 1,165,0,0,0
BEGIN DESCRIPTION:
Mapping XS 6307a370
END DESCRIPTION:
XS GIS Cut Line= 4
      3771466.42     10589550.05      3771299.79     10589669.82
      3771202.13     10589736.22      3771079.77     10589793.50
#Sta/Elev= 30
  4825.9  330.63  4917.4  325.27  4973.8  325.02  4982.1  319.74  4991.7  317.08
  4994.5  316.58  4997.7  317.08  5003.3  318.94  5009.4  323.50  5054.0  320.86
  5060.0  325.31  5074.9  320.75  5089.9  321.39  5095.9  323.32  5110.9  320.76
  5116.9  323.91  5140.2  325.18  5146.8  322.53  5153.4  323.43  5169.5  319.95
  5175.0  323.62  5192.3  319.59  5197.8  323.47  5215.1  319.04  5220.6  320.38
  5238.0  319.36  5243.5  321.26  5260.8  319.67  5266.3  321.99  5284.3  321.93
#Mann=3,-1,0
  4825.9    0.16       0  4991.7    0.07       0  4997.7    0.16       0
Bank Sta=4991.7,4997.7
Exp/Cntr=0.3,0.1

Chan Stop Cuts=-1