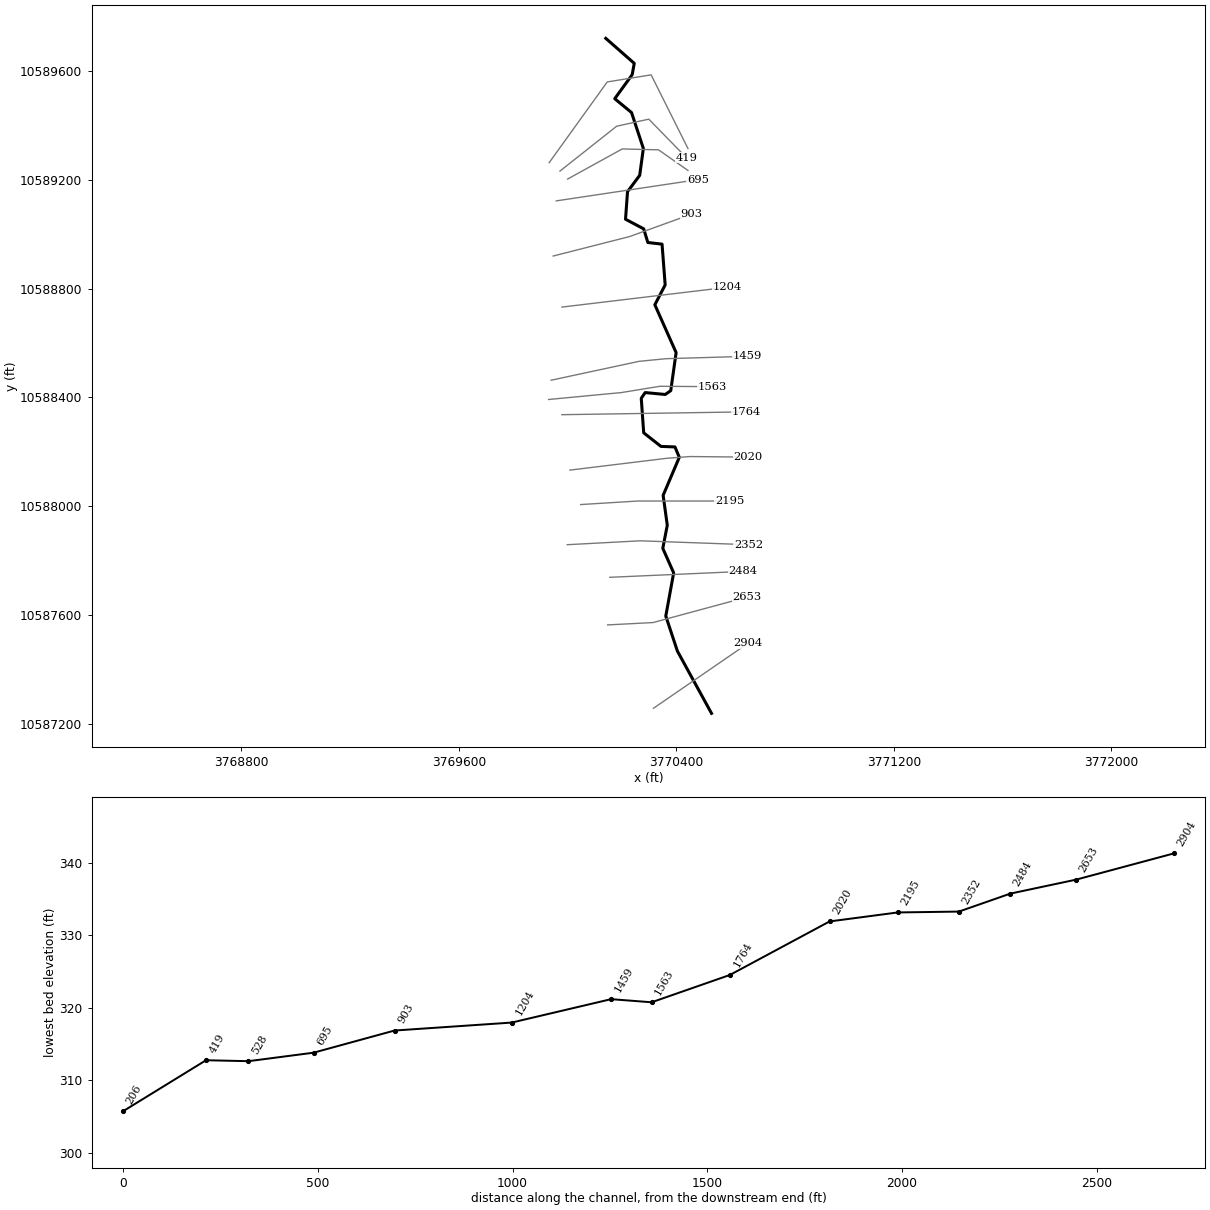
--- UNT 038 IN BOCR.prj (project) ---

Proj Title=UNT 038 IN BOCR Base Level Engineering
Current Plan=p01
Default Exp/Contr=0.3,0.1
English Units
Geom File=g01
Flow File=f01
Plan File=p01
Y Axis Title=Elevation
X Axis Title(PF)=Main Channel Distance
X Axis Title(XS)=Station
BEGIN DESCRIPTION:
UNT 038 IN BOCR
END DESCRIPTION:
DSS Export Rating Curves= 0
DSS Export Rating Curve Sorted= 0
DSS Export Volume Flow Curves= 0
DXF OffsetX= 0
DXF OffsetY= 0
DXF ScaleX= 1
DXF ScaleY= 10

--- UNT 038 IN BOCR.p01 (plan) ---

Plan Title=Multiple Run
Short Identifier=Multiple
Geom File=g01
Flow File=f01
Subcritical Flow
K Sum by GR= 0
Std Step Tol= 0.01
Critical Tol= 0.01
Num of Std Step Trials= 20
Max Error Tol= 0.3
Flow Tol Ratio= 0.001
Split Flow NTrial= 30
Split Flow Tol= 0.02
Split Flow Ratio= 0.02
Log Output Level= 0
Friction Slope Method= 1
Unsteady Friction Slope Method= 2
Unsteady Bridges Friction Slope Method= 1
Parabolic Critical Depth
Global Vel Dist=  1 , 1 , 1
Global Log Level= 0
CheckData=True
Encroach Param= -1, 0, 0, 0
BEGIN DESCRIPTION:
Multiple Run
END DESCRIPTION:

--- UNT 038 IN BOCR.f01 (steady flow) ---

Flow Title=Multiple
Number of Profiles=7
Profile Names=10-year,25-year,50-year,1pct_min,100-year,1pct_plu,500-year
River Rch & RM= UNT 038 IN BOCR,Reach-1,2904
     256     330     387     336     454     614     625
Boundary for River Rch & Prof#=UNT 038 IN BOCR,Reach-1,1
Up Type=0
Dn Type=3
Dn Slope=0.005
Boundary for River Rch & Prof#=UNT 038 IN BOCR,Reach-1,2
Up Type=0
Dn Type=3
Dn Slope=0.005
Boundary for River Rch & Prof#=UNT 038 IN BOCR,Reach-1,3
Up Type=0
Dn Type=3
Dn Slope=0.005
Boundary for River Rch & Prof#=UNT 038 IN BOCR,Reach-1,4
Up Type=0
Dn Type=3
Dn Slope=0.005
Boundary for River Rch & Prof#=UNT 038 IN BOCR,Reach-1,5
Up Type=0
Dn Type=3
Dn Slope=0.005
Boundary for River Rch & Prof#=UNT 038 IN BOCR,Reach-1,6
Up Type=0
Dn Type=3
Dn Slope=0.005
Boundary for River Rch & Prof#=UNT 038 IN BOCR,Reach-1,7
Up Type=0
Dn Type=3
Dn Slope=0.005

--- UNT 038 IN BOCR.g01 (geometry) ---

Geom Title=Existing Conditions
Program Version=4.10

River Reach=UNT 038 IN BOCR ,Reach-1
Reach XY= 30
       3770529.5       10587238.        3770404.       10587467.
      3770361.25       10587596.      3770390.25       10587755.
      3770350.25       10587845.      3770366.75       10587930.
       3770351.5       10588040.      3770410.94     10588179.78
        3770395.       10588218.       3770343.5       10588220.
        3770280.       10588270.      3770271.04     10588396.94
       3770285.5       10588418.      3770359.25       10588411.
       3770379.5       10588425.      3770399.25       10588565.
        3770321.       10588741.        3770359.       10588814.
       3770347.5       10588964.      3770295.25       10588970.
      3770280.02     10589020.21      3770213.14     10589055.61
      3770220.51     10589156.97      3770265.25       10589217.
      3770278.75       10589316.      3770235.25       10589448.
       3770173.5       10589499.      3770237.57     10589587.15
      3770245.25       10589629.       3770140.5       10589721.

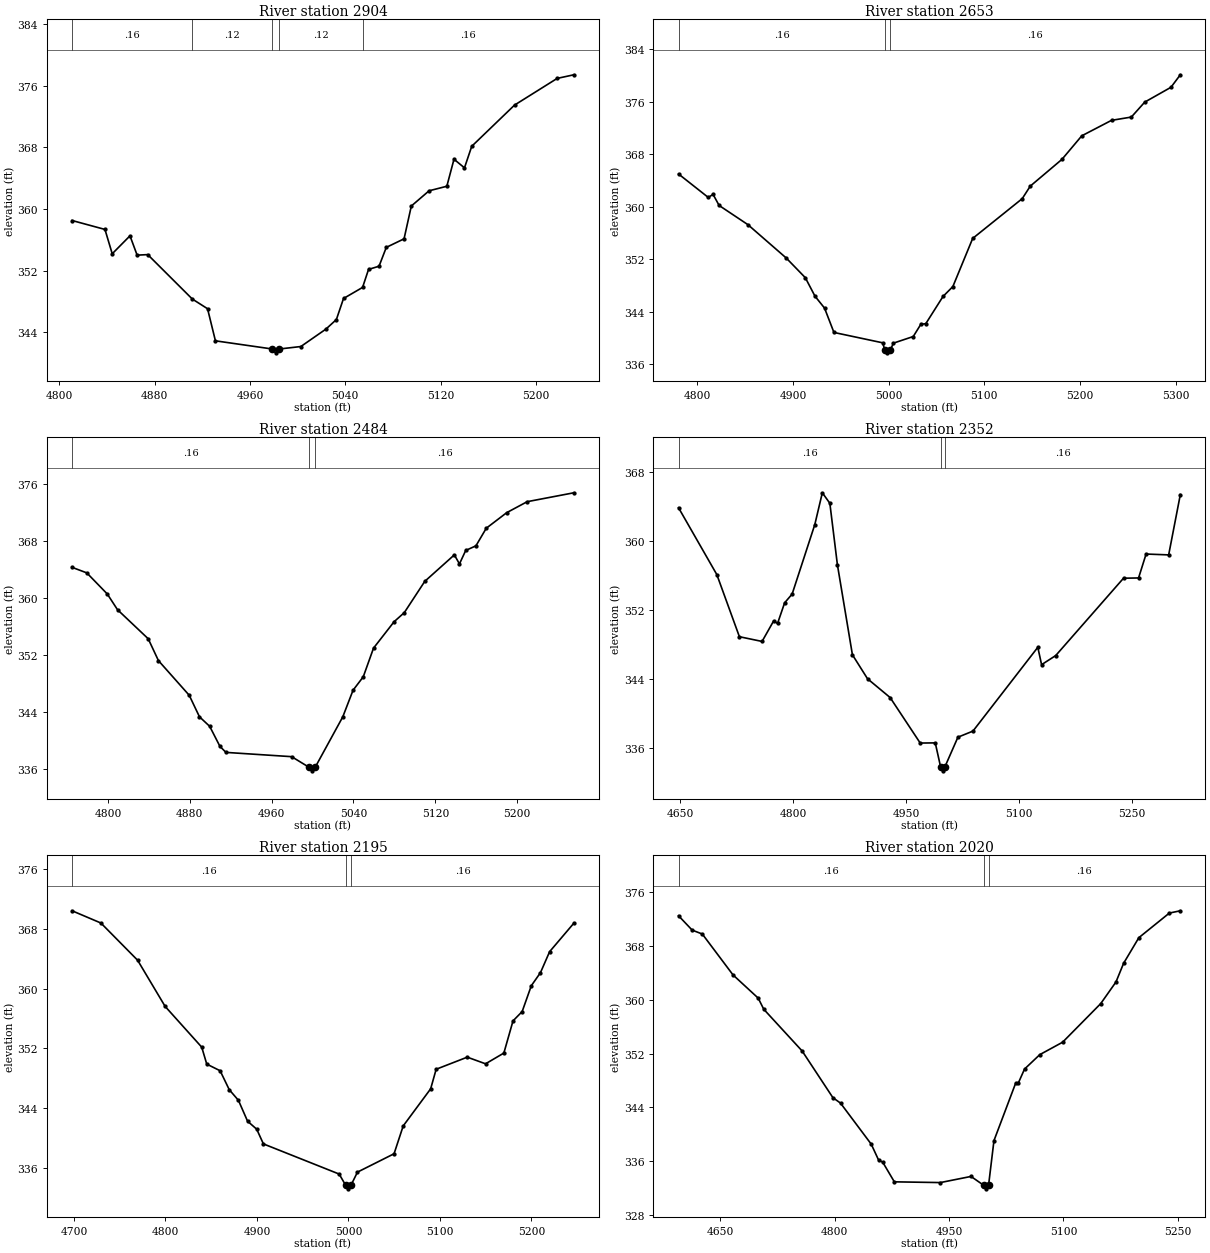
Type RM Length L Ch R = 1 ,2904    ,251,251,251
BEGIN DESCRIPTION:
UNT 038 IN BOCR 6.0
END DESCRIPTION:
XS GIS Cut Line= 2
      3770315.92     10587256.75      3770662.92     10587495.31
#Sta/Elev= 30
  4810.7  358.51  4838.3  357.35  4844.4  354.19  4859.3  356.52  4865.3  354.01
  4874.2  354.08  4911.6  348.31  4924.4  347.05    4931  342.88  4978.7  341.82
  4981.5  341.32  4984.7  341.82  5002.7  342.14  5023.7   344.4  5032.5  345.64
  5038.5  348.38  5054.5  349.82  5059.5  352.16  5068.3  352.57  5074.4  355.02
  5089.3  356.13  5095.4  360.39  5110.3  362.37  5125.2  362.96  5131.2  366.47
    5140  365.35  5146.1  368.15    5182   373.5  5217.8  376.97  5231.8  377.44
#Mann= 5 ,-1 , 0
  4810.7     .16       0  4911.6     .12       0  4978.7     .07       0
  4984.7     .12       0  5054.5     .16       0
Bank Sta=4978.7,4984.7
XS Rating Curve= 0 ,0
Exp/Cntr=0.3,0.1

Type RM Length L Ch R = 1 ,2653    ,169,169,169
BEGIN DESCRIPTION:
Mapping XS f92bc709
END DESCRIPTION:
XS GIS Cut Line= 3
      3770147.25     10587563.38      3770314.35     10587572.06
      3770659.04     10587665.28
#Sta/Elev= 30
  4780.5  364.98  4811.6   361.4  4816.6  361.87  4822.9  360.18    4853  357.25
    4893  352.17    4913  349.16  4923.1  346.34  4933.1  344.52  4942.9  340.81
  4993.8  339.23    4996   338.2  4998.7   337.7    5002   338.2  5005.1  339.18
  5025.8  340.19  5033.7  342.05  5038.9  342.15  5056.9   346.3  5067.2  347.81
  5087.9  355.15  5139.7  361.22  5148.1  363.13  5181.2  367.21  5201.9   370.8
    5233  373.16  5253.7  373.66  5267.7  375.94  5295.1   378.2  5304.9  380.11
#Mann= 3 ,-1 , 0
  4780.5     .16       0    4996     .07       0    5002     .16       0
Bank Sta=4996,5002
XS Rating Curve= 0 ,0
Exp/Cntr=0.3,0.1

Type RM Length L Ch R = 1 ,2484    ,132,132,132
BEGIN DESCRIPTION:
UNT 038 IN BOCR 5.0
END DESCRIPTION:
XS GIS Cut Line= 2
      3770155.25      10587738.5      3770645.17     10587760.18
#Sta/Elev= 30
    4765  364.35  4779.4  363.57  4799.4  360.61  4809.4   358.4  4839.4  354.32
  4849.4  351.25  4879.5  346.38  4889.5  343.36  4899.5  342.02  4909.5  339.21
  4915.4  338.36  4979.6  337.76  4996.6  336.27  4999.3  335.77  5002.6  336.27
  5029.6  343.36  5039.6  347.09  5049.6  348.98  5059.6     353  5079.7  356.71
  5089.7  357.99  5109.7  362.38  5138.6   366.1  5143.6  364.83  5149.7  366.72
  5159.7  367.37  5169.8  369.84  5189.8  372.03  5209.8  373.57  5255.4  374.82
#Mann= 3 ,-1 , 0
    4765     .16       0  4996.6     .07       0  5002.6     .16       0
Bank Sta=4996.6,5002.6
XS Rating Curve= 0 ,0
Exp/Cntr=0.3,0.1

Type RM Length L Ch R = 1 ,2352    ,157,157,157
BEGIN DESCRIPTION:
Mapping XS bf020061
END DESCRIPTION:
XS GIS Cut Line= 3
       3769998.8     10587858.41      3770267.04     10587872.74
      3770665.06     10587858.43
#Sta/Elev= 30
  4647.7  363.87  4698.6   356.1  4728.6  348.88  4758.7  348.33  4774.2  350.73
  4779.3  350.42  4788.7  352.82  4798.7  353.84  4828.8  361.91  4838.8  365.61
  4848.8  364.39  4858.8  357.27  4878.8  346.78  4898.9  343.99  4928.9  341.81
  4968.9  336.52  4988.9  336.54  4995.9  333.79  4998.7  333.29  5001.9  333.79
    5019   337.2    5039  337.91  5125.2  347.65  5130.2  345.63    5149  346.69
  5239.1  355.68  5259.1  355.71  5269.1  358.49  5299.1  358.39  5314.6   365.4
#Mann= 3 ,-1 , 0
  4647.7     .16       0  4995.9     .07       0  5001.9     .16       0
Bank Sta=4995.9,5001.9
XS Rating Curve= 0 ,0
Exp/Cntr=0.3,0.1

Type RM Length L Ch R = 1 ,2195    ,175,175,175
BEGIN DESCRIPTION:
Mapping XS 2ae2df31
END DESCRIPTION:
XS GIS Cut Line= 4
      3770048.15      10588006.1       3770259.1     10588019.12
       3770446.6     10588019.12      3770596.14     10588019.12
#Sta/Elev= 30
    4698  370.42  4729.5  368.78  4769.6   363.8  4799.7  357.61  4839.7  352.15
  4845.2  349.88  4859.8  348.99  4869.8  346.45  4879.8  345.03  4889.8  342.23
  4899.8  341.16  4907.1  339.19  4989.9  335.15  4996.9  333.67  4999.6  333.17
  5002.9  333.67  5009.9  335.41  5049.9  337.87  5059.9   341.6  5089.9  346.57
  5095.9  349.19  5129.9  350.81  5149.9  349.92  5169.9  351.36  5179.9  355.67
  5189.9  356.92  5199.9  360.38  5209.9  362.13  5219.9  364.94  5246.4  368.76
#Mann= 3 ,-1 , 0
    4698     .16       0  4996.9     .07       0  5002.9     .16       0
Bank Sta=4996.9,5002.9
XS Rating Curve= 0 ,0
Exp/Cntr=0.3,0.1

Type RM Length L Ch R = 1 ,2020    ,256,256,256
BEGIN DESCRIPTION:
Mapping XS ba7445e6
END DESCRIPTION:
XS GIS Cut Line= 4
      3770008.63     10588132.82      3770364.57     10588176.22
      3770451.38     10588182.73      3770664.04     10588180.56
#Sta/Elev= 30
    4595  372.45  4612.9  370.32  4626.2  369.74  4666.5  363.67  4699.5  360.23
  4706.8  358.58  4757.2  352.38  4797.5  345.46  4807.5  344.65  4847.8  338.56
  4857.7  336.14  4862.7  335.92  4878.1  332.97  4938.5  332.86  4978.7  333.77
  4995.7  332.43  4998.5  331.93  5001.7  332.43  5008.8  339.08  5037.2  347.59
  5040.6  347.59  5048.9   349.7  5068.9  351.84  5098.9  353.69  5148.9  359.42
  5168.9  362.63  5178.9   365.4  5198.9   369.2  5238.9  372.85  5253.3  373.19
#Mann= 3 ,-1 , 0
    4595     .16       0  4995.7     .07       0  5001.7     .16       0
Bank Sta=4995.7,5001.7
XS Rating Curve= 0 ,0
Exp/Cntr=0.3,0.1

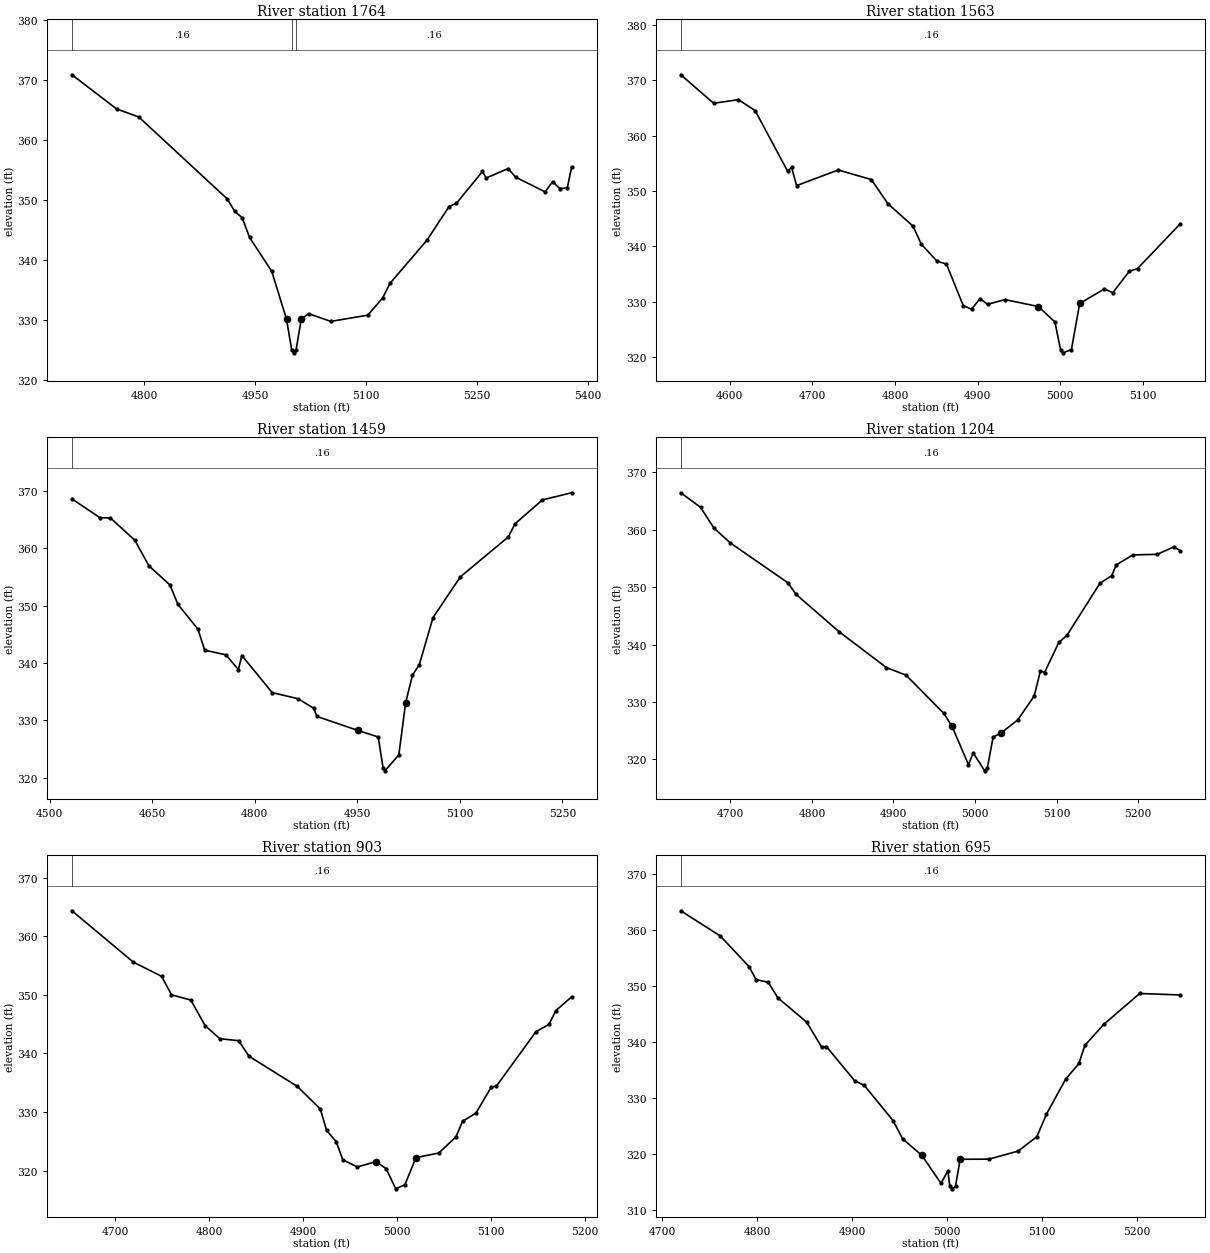
Type RM Length L Ch R = 1 ,1764    ,201,201,201
BEGIN DESCRIPTION:
Mapping XS 2c286ed7
END DESCRIPTION:
XS GIS Cut Line= 2
      3769979.23     10588336.64      3770655.45     10588347.04
#Sta/Elev= 30
    4702  370.89  4762.4   365.2  4792.4  363.86  4912.4  350.17  4922.4  348.11
  4932.4  347.06  4942.4  343.77  4972.4  338.14  4992.4  330.15  4999.4  325.04
  5002.2  324.54  5005.4  325.04  5012.4  330.16  5022.4  331.07  5052.4  329.78
  5102.4  330.82  5122.4  333.66  5132.4  336.11  5182.4   343.3  5212.4  348.92
  5222.4  349.47  5257.7  354.77  5262.7  353.68  5292.4  355.26  5302.4  353.84
  5342.5  351.37  5352.5  353.06  5362.5  351.92  5372.5  352.04  5378.3  355.47
#Mann= 3 ,-1 , 0
    4702     .16       0  4999.4     .07       0  5005.4     .16       0
Bank Sta=4992.4,5012.4
XS Rating Curve= 0 ,0
Exp/Cntr=0.3,0.1

Type RM Length L Ch R = 1 ,1563    ,104,104,104
BEGIN DESCRIPTION:
Mapping XS a363f39a
END DESCRIPTION:
XS GIS Cut Line= 5
      3769930.11     10588392.54      3770141.22     10588412.68
      3770197.53     10588417.95      3770339.83     10588441.15
      3770531.52     10588439.76
#Sta/Elev= 30
  4540.8  371.03  4580.5  365.88  4610.6  366.53  4630.7  364.56  4669.9  353.64
  4674.9  354.28  4680.9  350.99  4731.2  353.82  4771.3  352.09  4791.4  347.72
  4821.7  343.68  4831.8  340.41  4850.7  337.35  4862.2  336.81  4882.5  329.32
  4892.6  328.65  4902.7  330.55  4912.2  329.55  4933.1  330.39  4973.4  329.14
  4993.4  326.36  5000.4  321.27  5003.1  320.77  5013.4  321.36  5023.4  329.69
  5053.4  332.33  5063.4  331.62  5083.4  335.51  5093.4     336  5145.3  344.13
#Mann= 1 ,-1 , 0
  4540.8     .16       0
Bank Sta=4973.4,5023.4
XS Rating Curve= 0 ,0
Exp/Cntr=0.3,0.1

Type RM Length L Ch R = 1 ,1459    ,255,255,255
BEGIN DESCRIPTION:
Mapping XS aa8c88f6
END DESCRIPTION:
XS GIS Cut Line= 4
      3769939.52     10588463.45       3770262.9      10588532.9
      3770362.73     10588542.66      3770662.24     10588551.35
#Sta/Elev= 30
  4532.6  368.58  4573.6  365.29  4588.7  365.27  4624.7  361.35  4645.2  356.91
  4675.9  353.58  4687.5  350.21  4716.8  345.89  4726.7  342.22  4757.7  341.41
    4776  338.85  4781.1  341.29  4825.4  334.83  4863.4  333.76    4886  332.11
    4891  330.67  4950.5  328.25  4980.5   327.1  4987.6   321.7  4990.3   321.2
  5010.6  323.97  5020.6  333.04  5030.6  337.88  5040.6  339.68  5060.6  347.89
  5100.6  354.99  5170.6  361.93  5180.6  364.24  5220.6   368.4  5263.3  369.64
#Mann= 1 ,-1 , 0
  4532.6     .16       0
Bank Sta=4950.5,5020.6
XS Rating Curve= 0 ,0
Exp/Cntr=0.3,0.1

Type RM Length L Ch R = 1 ,1204    ,301,301,301
BEGIN DESCRIPTION:
Mapping XS 0965b55b
END DESCRIPTION:
XS GIS Cut Line= 2
      3769979.28     10588732.48      3770587.74     10588805.28
#Sta/Elev= 30
  4639.2  366.46  4663.4  363.92  4679.8  360.31    4700  357.71  4770.5  350.77
  4780.5  348.75  4833.1  342.26  4891.3  335.98  4915.5  334.65  4961.8  327.99
  4971.9  325.71    4992  319.06  4997.9  321.09  5011.9  317.97  5015.2  318.47
  5022.2  323.83  5032.3  324.61  5052.5  326.86  5072.6     331  5080.3   335.4
  5085.3  335.09  5102.8  340.36  5112.9  341.62  5153.2  350.66  5167.7     352
  5173.3  353.88  5193.5  355.62  5223.7  355.73  5243.8  357.03    5252  356.35
#Mann= 1 ,-1 , 0
  4639.2     .16       0
Bank Sta=4971.9,5032.3
XS Rating Curve= 0 ,0
Exp/Cntr=0.3,0.1

Type RM Length L Ch R = 1 ,903     ,208,208,208
BEGIN DESCRIPTION:
Mapping XS 86b894a7
END DESCRIPTION:
XS GIS Cut Line= 3
      3769947.12     10588920.26      3770228.18     10588991.88
      3770455.32     10589074.09
#Sta/Elev= 30
  4653.9  364.39    4719  355.64  4749.3  353.19  4759.8  350.03  4780.3  349.13
  4795.6  344.76  4811.3  342.52  4831.3  342.19  4842.2  339.54  4893.8  334.36
  4918.2   330.5  4924.8  326.85  4935.1  324.92  4942.1  321.83  4957.5  320.61
  4977.4  321.52  4988.2  320.32  4998.4  316.87  5008.2  317.58  5019.9  322.21
  5044.2  322.99  5062.4  325.74  5069.5  328.41  5083.7  329.82  5100.1  334.28
  5105.4   334.4  5147.5   343.7  5161.4  344.97  5168.8  347.34  5185.5  349.68
#Mann= 1 ,-1 , 0
  4653.9     .16       0
Bank Sta=4977.4,5019.9
XS Rating Curve= 0 ,0
Exp/Cntr=0.3,0.1

Type RM Length L Ch R = 1 ,695     ,167,167,167
BEGIN DESCRIPTION:
Mapping XS dfdc7876
END DESCRIPTION:
XS GIS Cut Line= 2
      3769958.38     10589123.09      3770479.26     10589201.22
#Sta/Elev= 30
  4719.5  363.51  4761.2  358.99  4791.5  353.52  4798.8  351.21  4811.7  350.73
  4821.9  347.94  4852.2   343.6  4867.9  339.17    4873  339.25  4902.8  333.12
  4912.9  332.31  4943.2  326.02  4953.3  322.76  4973.5  319.81  4993.8  314.79
    5001  317.04  5003.1  314.31  5005.9  313.81  5009.1  314.31    5014  319.09
  5044.3  319.12  5075.2  320.56  5094.9  323.14    5105  327.17  5125.2  333.41
  5139.2  336.22  5145.4  339.44  5165.7  343.26  5203.3  348.73  5246.2  348.46
#Mann= 1 ,-1 , 0
  4719.5     .16       0
Bank Sta=4973.5,5014
XS Rating Curve= 0 ,0
Exp/Cntr=0.3,0.1

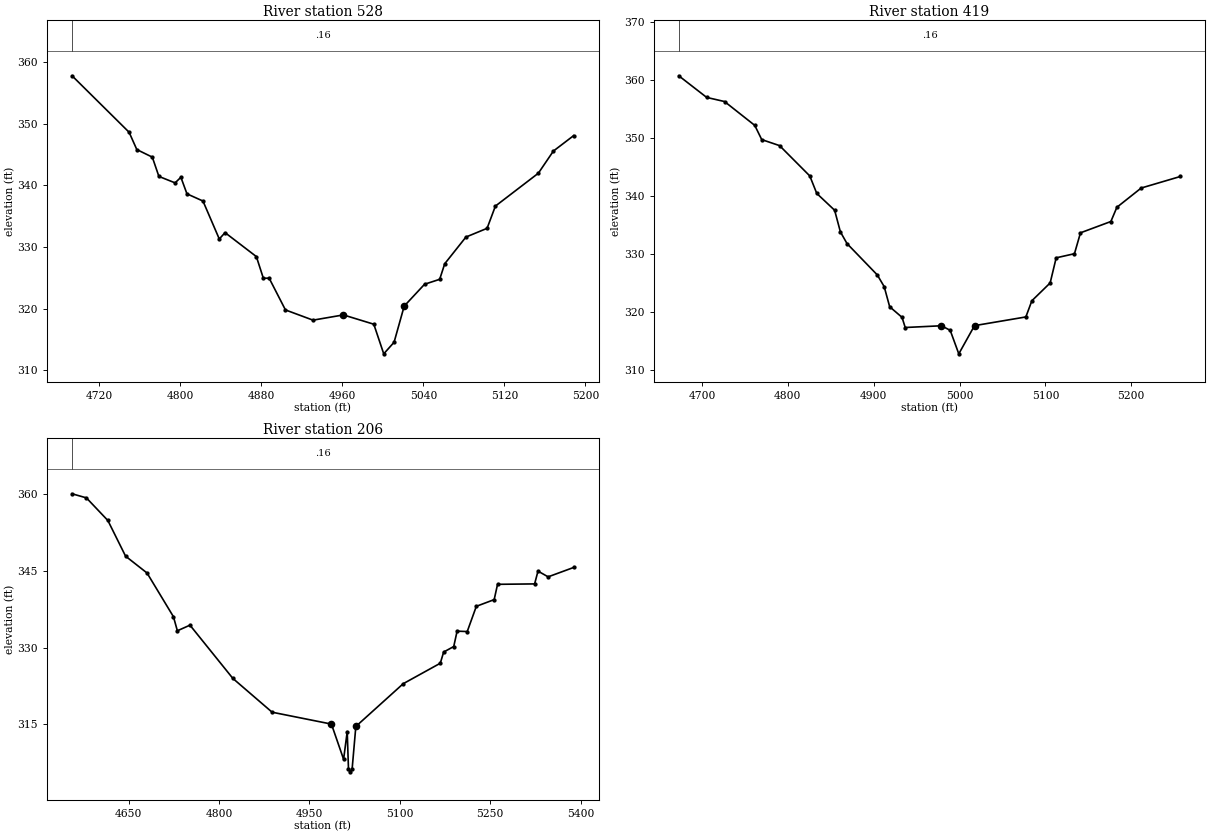
Type RM Length L Ch R = 1 ,528     ,109,109,109
BEGIN DESCRIPTION:
Mapping XS b8966f5f
END DESCRIPTION:
XS GIS Cut Line= 4
      3770000.29     10589203.46      3770201.05     10589314.15
      3770334.52     10589310.89      3770442.85     10589235.06
#Sta/Elev= 30
  4693.3  357.79  4749.6  348.62  4757.2  345.81  4772.5  344.58    4779  341.45
    4795   340.4  4800.7  341.31  4806.7  338.62  4822.5  337.45  4838.6  331.29
  4844.3  332.32  4875.2  328.43  4882.1  324.91  4887.8  324.93  4903.9  319.77
  4931.1  318.11  4961.1  318.96  4991.1  317.45  5000.9  312.64  5011.1  314.52
  5021.1  320.39  5041.2  323.94  5056.1  324.74  5061.1  327.27    5082   331.6
  5102.9  333.02  5111.1  336.63  5153.5  341.97  5168.3  345.56  5188.3  348.07
#Mann= 1 ,-1 , 0
  4693.3     .16       0
Bank Sta=4961.1,5021.1
XS Rating Curve= 0 ,0
Exp/Cntr=0.3,0.1

Type RM Length L Ch R = 1 ,419     ,213,213,213
BEGIN DESCRIPTION:
Mapping XS 1c5d1bb8
END DESCRIPTION:
XS GIS Cut Line= 4
      3769972.07     10589232.74      3770180.44      10589397.7
      3770298.71     10589423.74      3770436.54     10589282.65
#Sta/Elev= 30
    4673   360.7  4705.5  356.97  4726.3  356.26  4761.5  352.15  4769.6   349.7
  4790.4  348.66  4825.6  343.43  4833.7  340.42  4854.5  337.52  4861.2   333.8
  4868.9  331.78  4904.2  326.37  4912.2  324.36  4918.6  320.89    4933  319.06
  4936.7  317.31  4978.9  317.61  4989.1  316.82  4999.1  312.77  5017.4  317.63
  5077.2  319.13  5084.2  321.92  5105.5  324.99  5112.5  329.32  5133.8  330.03
  5140.8  333.63  5176.2  335.58  5183.2  338.03  5211.5  341.35  5257.1  343.34
#Mann= 1 ,-1 , 0
    4673     .16       0
Bank Sta=4978.9,5017.4
XS Rating Curve= 0 ,0
Exp/Cntr=0.3,0.1

Type RM Length L Ch R = 1 ,206     ,0,0,0
BEGIN DESCRIPTION:
UNT 038 IN BOCR 1.0
END DESCRIPTION:
XS GIS Cut Line= 4
      3769932.33     10589263.68       3770145.9      10589560.6
      3770307.36     10589586.64      3770442.78      10589315.8
#Sta/Elev= 30
  4556.3  360.06  4580.1  359.26  4615.7  354.84  4645.1  347.87  4680.7  344.58
  4724.5  336.04    4731  333.29  4751.9  334.39  4823.1  323.98  4888.2  317.38
  4986.6  315.06  5006.8  308.18  5012.8   313.6  5014.9  306.23  5017.6  305.73
  5020.9  306.23  5027.1   314.6  5105.7  322.95  5167.2  326.95  5172.8  329.14
  5189.5  330.21  5195.1  333.22  5211.9  333.14    5227  338.07  5256.6  339.38
  5262.2  342.37  5323.7  342.45  5329.3  344.95  5346.1  343.83  5388.4  345.66
#Mann= 1 ,-1 , 0
  4556.3     .16       0
Bank Sta=4986.6,5027.1
XS Rating Curve= 0 ,0
Exp/Cntr=0.3,0.1

Chan Stop Cuts=-1
Use User Specified Reach Order=0
Composite Channel Slope=5