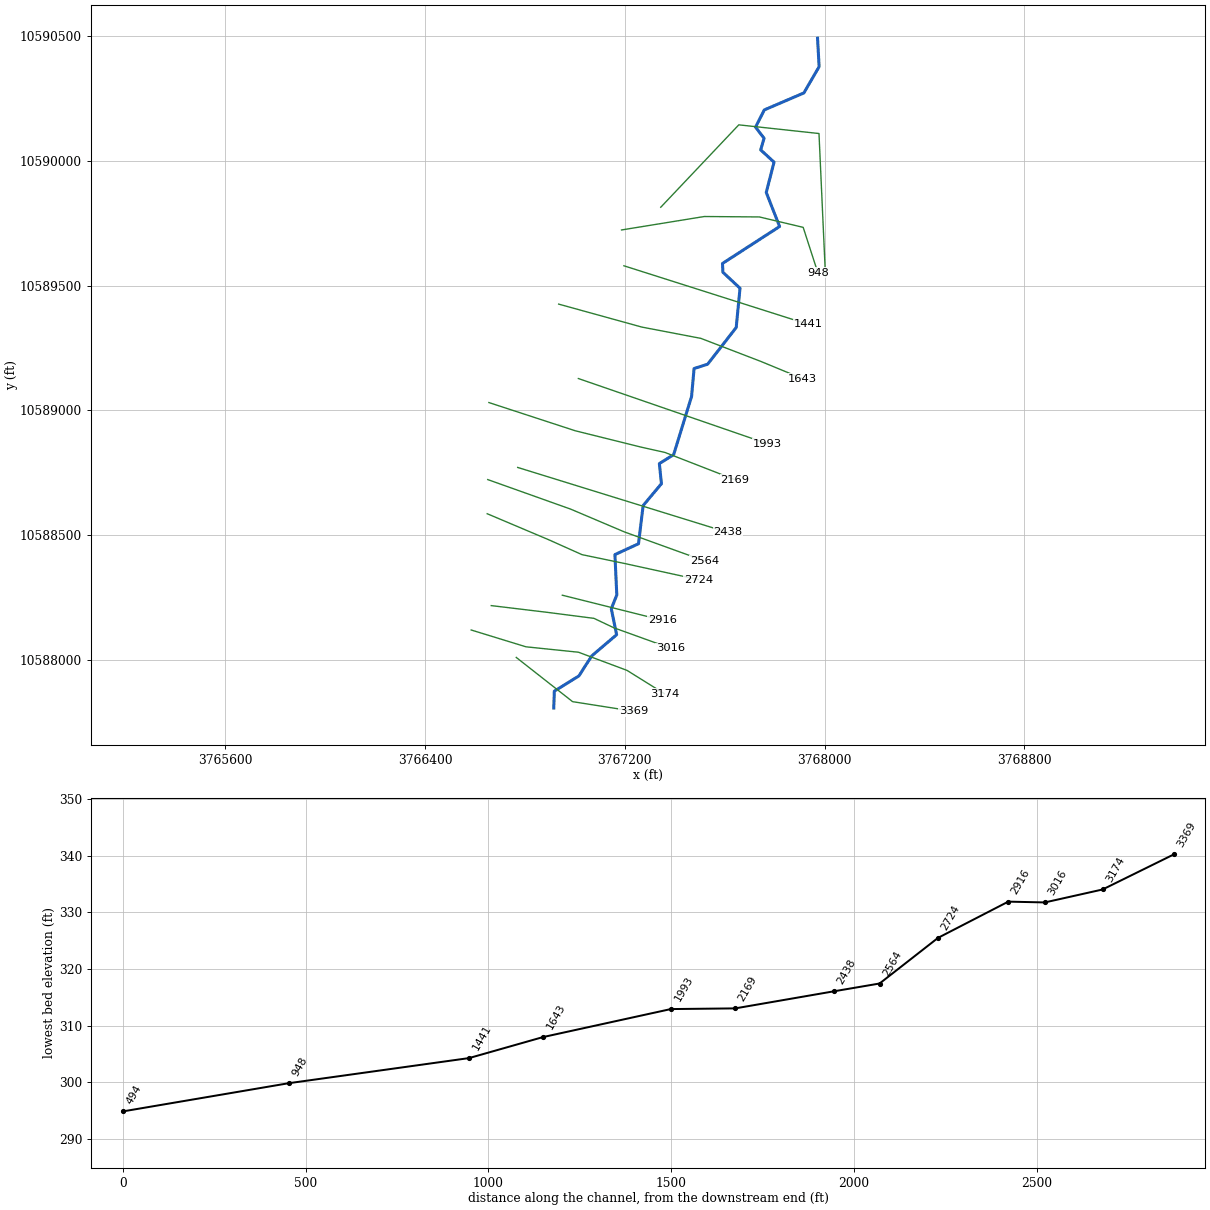
--- UNT 039 IN BOCR.prj (project) ---

Proj Title=UNT 039 IN BOCR Base Level Engineering
Current Plan=p01
Default Exp/Contr=0.3,0.1
English Units
Geom File=g01
Flow File=f01
Plan File=p01
Y Axis Title=Elevation
X Axis Title(PF)=Main Channel Distance
X Axis Title(XS)=Station
BEGIN DESCRIPTION:
UNT 039 IN BOCR
END DESCRIPTION:
DSS Export Rating Curves= 0
DSS Export Rating Curve Sorted= 0
DSS Export Volume Flow Curves= 0
DXF OffsetX= 0
DXF OffsetY= 0
DXF ScaleX= 1
DXF ScaleY= 10

--- UNT 039 IN BOCR.p01 (plan) ---

Plan Title=Multiple Run
Short Identifier=Multiple
Geom File=g01
Flow File=f01
Subcritical Flow
K Sum by GR= 0
Std Step Tol= 0.01
Critical Tol= 0.01
Num of Std Step Trials= 20
Max Error Tol= 0.3
Flow Tol Ratio= 0.001
Split Flow NTrial= 30
Split Flow Tol= 0.02
Split Flow Ratio= 0.02
Log Output Level= 0
Friction Slope Method= 1
Unsteady Friction Slope Method= 2
Unsteady Bridges Friction Slope Method= 1
Parabolic Critical Depth
Global Vel Dist=  1 , 1 , 1
Global Log Level= 0
CheckData=True
Encroach Param= -1, 0, 0, 0
BEGIN DESCRIPTION:
Multiple Run
END DESCRIPTION:

--- UNT 039 IN BOCR.f01 (steady flow) ---

Flow Title=Multiple
Number of Profiles=7
Profile Names=10-year,25-year,50-year,1pct_min,100-year,1pct_plu,500-year
River Rch & RM= UNT 039 IN BOCR,Reach-1,3369
     370     492     591     523     708     957    1018
Boundary for River Rch & Prof#=UNT 039 IN BOCR,Reach-1,1
Up Type=0
Dn Type=3
Dn Slope=0.005
Boundary for River Rch & Prof#=UNT 039 IN BOCR,Reach-1,2
Up Type=0
Dn Type=3
Dn Slope=0.005
Boundary for River Rch & Prof#=UNT 039 IN BOCR,Reach-1,3
Up Type=0
Dn Type=3
Dn Slope=0.005
Boundary for River Rch & Prof#=UNT 039 IN BOCR,Reach-1,4
Up Type=0
Dn Type=3
Dn Slope=0.005
Boundary for River Rch & Prof#=UNT 039 IN BOCR,Reach-1,5
Up Type=0
Dn Type=3
Dn Slope=0.005
Boundary for River Rch & Prof#=UNT 039 IN BOCR,Reach-1,6
Up Type=0
Dn Type=3
Dn Slope=0.005
Boundary for River Rch & Prof#=UNT 039 IN BOCR,Reach-1,7
Up Type=0
Dn Type=3
Dn Slope=0.005

--- UNT 039 IN BOCR.g01 (geometry) ---

Geom Title=Existing Conditions
Program Version=4.10

River Reach=UNT 039 IN BOCR ,Reach-1
Reach XY= 30
      3766915.36     10587808.44       3766917.5       10587876.
        3767016.       10587937.      3767067.25       10588017.
      3767167.03     10588101.96      3767145.75       10588206.
      3767167.75       10588261.      3767160.23     10588422.74
      3767254.67     10588466.14      3767273.25       10588619.
      3767346.51     10588706.59      3767338.25       10588787.
       3767395.5       10588823.      3767467.25       10589056.
      3767477.28     10589167.66       3767531.5       10589185.
        3767646.       10589332.      3767661.25       10589489.
      3767592.74     10589553.08        3767591.     10589588.23
      3767819.73     10589736.24      3767766.35     10589872.52
       3767797.5       10589994.        3767744.       10590043.
      3767757.58     10590089.57       3767723.5       10590134.
       3767758.5       10590203.        3767917.       10590271.
        3767978.       10590376.      3767971.75       10590490.

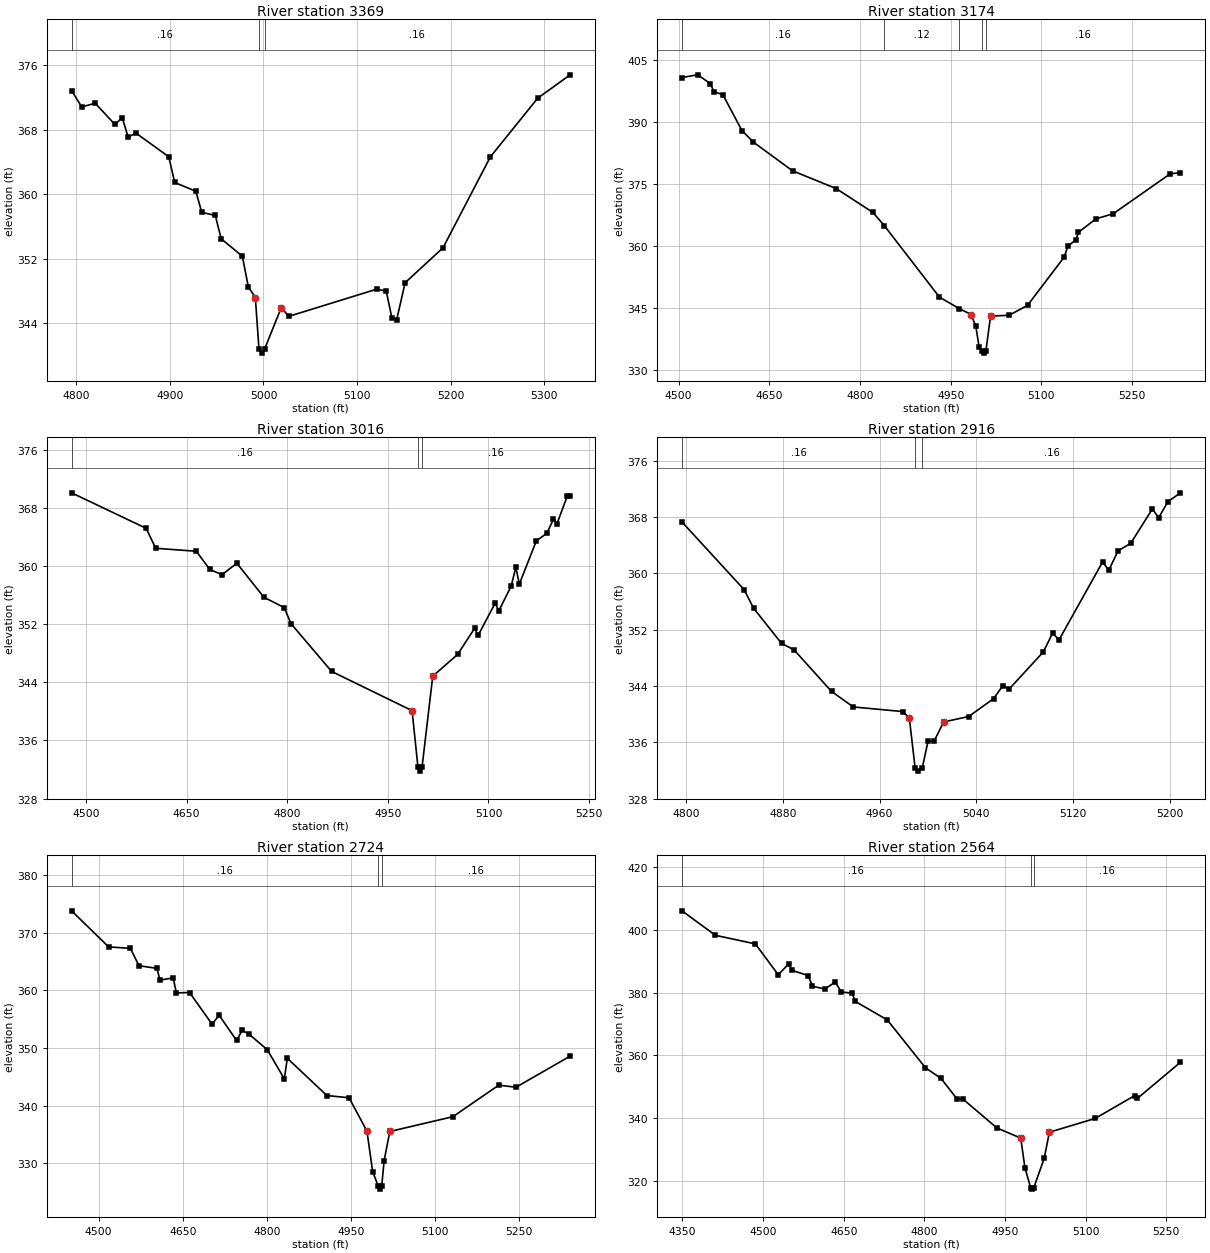
Type RM Length L Ch R = 1 ,3369    ,195,195,195
BEGIN DESCRIPTION:
UNT 039 IN BOCR 6.0
END DESCRIPTION:
XS GIS Cut Line= 3
      3766765.13     10588011.06      3766990.81     10587833.99
      3767233.87      10587795.8
#Sta/Elev= 30
  4794.9  372.84  4805.7  370.81  4820.1  371.27    4841  368.66  4849.1  369.44
  4855.4  367.05  4863.5  367.58  4898.8  364.63  4905.1  361.44  4927.7  360.35
    4934  357.74  4948.5  357.35  4954.8  354.46  4977.4   352.3  4983.8  348.51
  4991.3  347.17  4995.2  340.78    4998  340.28  5001.2  340.78    5019  345.92
  5027.1  344.84    5121  348.21  5131.2  347.98  5137.3  344.63  5142.4  344.42
  5151.4  349.01  5191.9  353.34  5242.5  364.61  5293.1  371.89  5327.8  374.79
#Mann= 3 ,-1 , 0
  4794.9     .16       0  4995.2     .07       0  5001.2     .16       0
Bank Sta=4991.3,5019
XS Rating Curve= 0 ,0
Exp/Cntr=0.3,0.1

Type RM Length L Ch R = 1 ,3174    ,158,158,158
BEGIN DESCRIPTION:
Mapping XS f7cb2dbd
END DESCRIPTION:
XS GIS Cut Line= 5
      3766584.76     10588120.89      3766803.93     10588053.62
      3767014.44     10588031.92      3767208.66     10587959.22
       3767358.4     10587865.91
#Sta/Elev= 30
  4505.4  400.79  4531.4  401.44  4552.3  399.34  4558.2   397.4  4573.2  396.61
  4604.6  387.96  4623.7  385.13  4688.3  378.21  4760.5  373.91  4821.3  368.13
    4840  364.96  4931.4  347.62    4964  344.86  4983.8  343.42  4991.6  340.52
  4996.9  335.64  5002.2  334.57  5004.9  334.07  5008.2  334.57  5015.9  343.02
  5046.8  343.24  5077.1  345.64  5137.7  357.31    5144  360.04  5157.2  361.47
    5161  363.28  5190.1  366.57  5218.8  367.81  5313.2  377.49  5330.1  377.74
#Mann= 5 ,-1 , 0
  4505.4     .16       0    4840     .12       0    4964     .16       0
  5002.2     .07       0  5008.2     .16       0
Bank Sta=4983.8,5015.9
XS Rating Curve= 0 ,0
Exp/Cntr=0.3,0.1

Type RM Length L Ch R = 1 ,3016    ,100,100,100
BEGIN DESCRIPTION:
Mapping XS 0fe39b99
END DESCRIPTION:
XS GIS Cut Line= 5
      3766665.06     10588218.55      3766890.74     10588191.42
      3767076.29     10588167.55      3767156.58     10588129.57
      3767382.25      10588048.2
#Sta/Elev= 30
  4478.6  370.12  4589.7  365.23    4604  362.48  4664.5  362.07  4684.6  359.56
  4702.8  358.84  4724.9  360.42  4765.3  355.73  4795.5  354.31  4805.6   352.1
  4866.1  345.52  4986.1  340.11  4994.9  332.28  4997.6  331.78  5000.9  332.28
  5016.9  344.86  5053.9  347.85  5079.3  351.45  5084.6  350.49    5110  354.93
  5115.3  353.85  5133.8  357.27  5140.7  359.86    5146  357.56  5171.3   363.5
    5187  364.55  5196.7  366.45    5202  365.84  5217.6  369.71  5221.7  369.71
#Mann= 3 ,-1 , 0
  4478.6     .16       0  4994.9     .07       0  5000.9     .16       0
Bank Sta=4986.1,5016.9
XS Rating Curve= 0 ,0
Exp/Cntr=0.3,0.1

Type RM Length L Ch R = 1 ,2916    ,192,192,192
BEGIN DESCRIPTION:
UNT 039 IN BOCR 5.0
END DESCRIPTION:
XS GIS Cut Line= 3
      3766949.64     10588260.18      3767149.61     10588210.19
      3767349.63     10588160.18
#Sta/Elev= 30
  4796.6   367.3  4848.1  357.67  4855.8  355.06    4879  350.05  4889.3  349.14
  4920.3  343.24  4938.3  341.03  4979.5  340.37  4984.7   339.4  4989.4  332.42
  4992.2  331.92  4995.4  332.42  5000.2  336.22  5005.3  336.22    5013   338.9
  5033.7  339.67  5054.3   342.2    5062  344.06  5067.2  343.57  5095.5  348.85
  5103.2  351.54  5108.4  350.54  5144.5  361.62  5149.6  360.44  5157.3  363.21
  5167.7  364.25  5185.7  369.16  5190.8  367.89  5198.6  370.19  5208.9  371.43
#Mann= 3 ,-1 , 0
  4796.6     .16       0  4989.4     .07       0  4995.4     .16       0
Bank Sta=4984.7,5013
XS Rating Curve= 0 ,0
Exp/Cntr=0.3,0.1

Type RM Length L Ch R = 1 ,2724    ,160,160,160
BEGIN DESCRIPTION:
Mapping XS 70d436f9
END DESCRIPTION:
XS GIS Cut Line= 5
      3766648.77     10588586.39      3766895.08     10588482.22
      3767028.54     10588422.54      3767201.07     10588386.73
      3767494.03     10588322.72
#Sta/Elev= 30
  4451.7  373.81  4517.8  367.55  4556.6   367.3    4572  364.28    4604  363.83
  4609.4  361.78  4633.1  362.18  4638.6  359.57  4662.2  359.63  4702.3  354.16
  4715.1  355.67    4746  351.34  4756.2  353.05  4767.9  352.44  4800.8  349.73
  4831.3  344.65  4836.7  348.22  4907.3  341.76  4946.9  341.37  4978.8  335.57
    4989  328.54  4999.1  326.02  5001.9  325.52  5005.1  326.02  5009.4  330.44
  5019.6  335.52  5132.2  338.09    5214  343.56  5244.8   343.2  5341.4   348.6
#Mann= 3 ,-1 , 0
  4451.7     .16       0  4999.1     .07       0  5005.1     .16       0
Bank Sta=4978.8,5019.6
XS Rating Curve= 0 ,0
Exp/Cntr=0.3,0.1

Type RM Length L Ch R = 1 ,2564    ,126,126,126
BEGIN DESCRIPTION:
Mapping XS fa5807aa
END DESCRIPTION:
XS GIS Cut Line= 4
      3766650.92     10588723.11      3766982.97     10588604.83
      3767197.81     10588513.69        3767519.     10588397.58
#Sta/Elev= 30
    4349     406  4411.3  398.21  4485.6  395.48  4528.1  385.67  4547.7  389.11
    4553  387.08  4583.8  385.42  4591.8     382  4614.7  381.14  4634.2  383.31
  4645.5  380.17  4665.7  379.83    4671  377.22    4731  371.28    4802  356.05
  4831.1  352.65  4860.8  346.11  4871.6  346.11  4934.9  336.91  4979.3  333.67
    4987  324.27  4997.6  317.94  5000.3  317.44  5003.6  317.94  5022.9  327.24
  5032.5  335.55  5117.5  339.92  5190.9  347.17  5196.2   346.3  5276.4  357.82
#Mann= 3 ,-1 , 0
    4349     .16       0  4997.6     .07       0  5003.6     .16       0
Bank Sta=4979.3,5032.5
XS Rating Curve= 0 ,0
Exp/Cntr=0.3,0.1

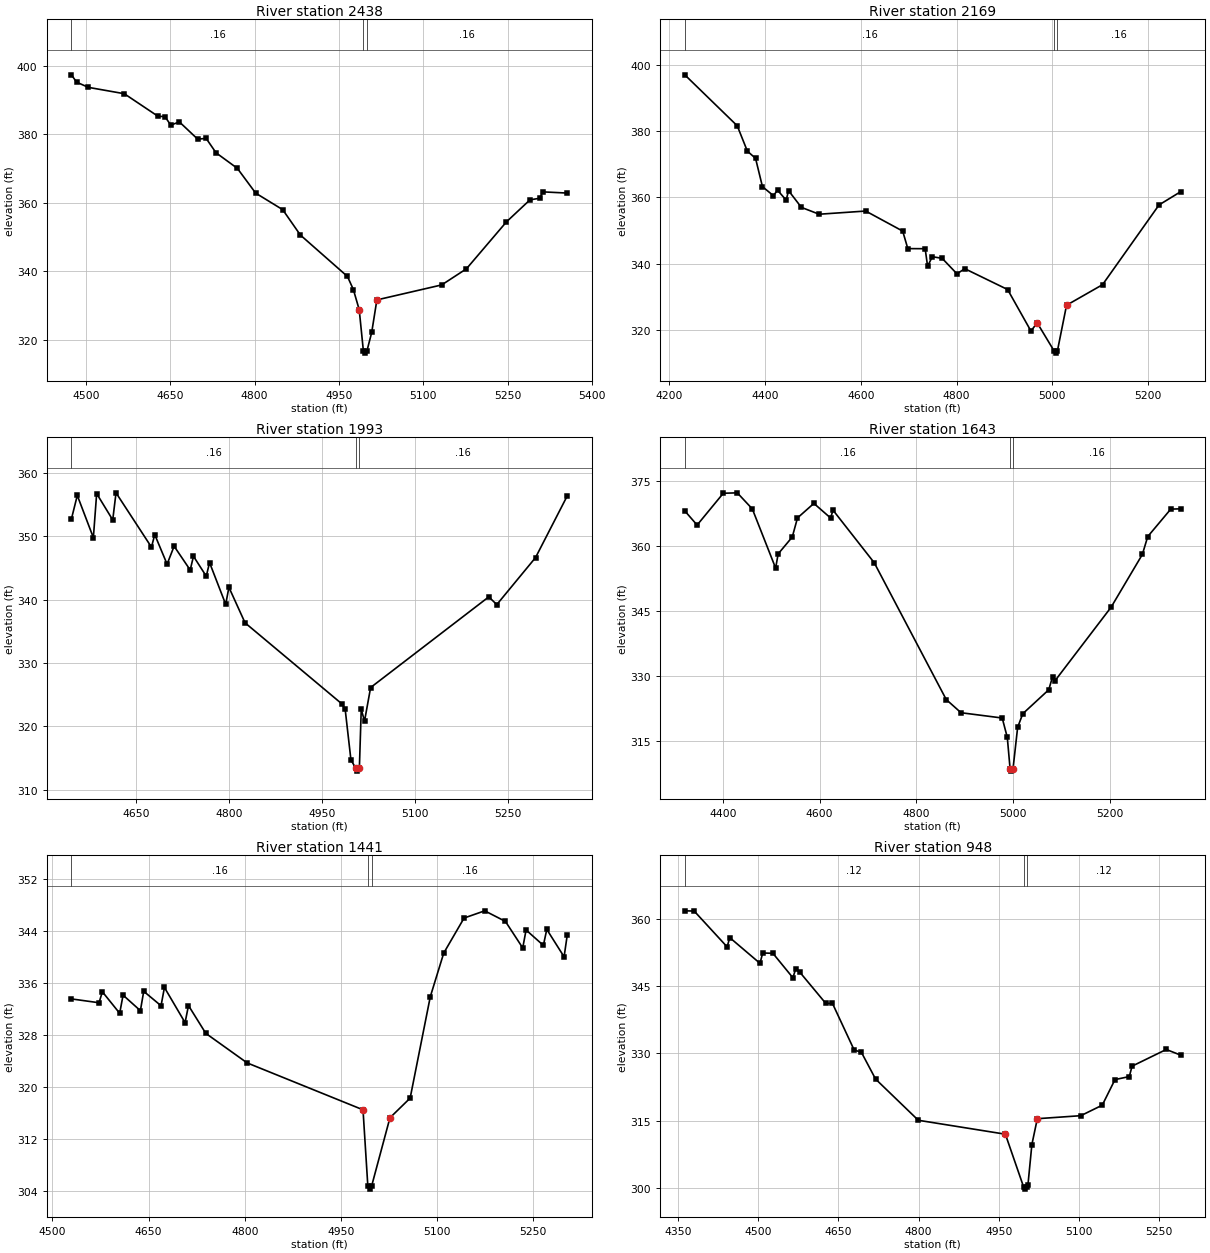
Type RM Length L Ch R = 1 ,2438    ,269,269,269
BEGIN DESCRIPTION:
Mapping XS d18d6617
END DESCRIPTION:
XS GIS Cut Line= 2
      3766770.91      10588771.7      3767612.96     10588511.28
#Sta/Elev= 30
  4474.6  397.37  4483.7  395.23  4504.6  393.71  4568.5  391.85  4628.5  385.25
  4640.7  385.18  4651.2  382.67  4666.4  383.62    4699  378.57    4714   378.8
  4731.6  374.59  4769.5  370.04  4802.1   362.8  4850.1  357.97  4881.5  350.56
  4965.2  338.45  4975.7  334.63  4986.1  328.75  4993.6  316.55  4996.4  316.05
  4999.6  316.55  5008.3  322.09  5017.5   331.6  5132.7  335.98  5176.7  340.69
  5247.8   354.4  5289.7  360.85  5307.2   361.3  5312.4  363.17    5356  362.82
#Mann= 3 ,-1 , 0
  4474.6     .16       0  4993.6     .07       0  4999.6     .16       0
Bank Sta=4986.1,5017.5
XS Rating Curve= 0 ,0
Exp/Cntr=0.3,0.1

Type RM Length L Ch R = 1 ,2169    ,176,176,176
BEGIN DESCRIPTION:
Mapping XS e524f3ea
END DESCRIPTION:
XS GIS Cut Line= 5
       3766655.5     10589031.48      3767000.98     10588918.64
      3767266.61     10588852.66      3767360.36     10588831.83
      3767641.56     10588722.47
#Sta/Elev= 30
  4232.7  396.89  4342.2  381.53  4363.3   373.9  4380.4  371.73  4394.8   363.2
  4417.6  360.49  4426.4  362.12  4444.2  359.15  4449.4  361.97  4476.1  356.95
  4513.2  354.89  4610.3  355.85  4687.5  349.81  4698.2  344.53  4734.4   344.5
  4739.5   339.2  4749.3  342.09  4769.9   341.6  4800.8  336.93  4817.1  338.48
  4906.5   332.2  4955.2  319.69  4968.2  322.17  5004.2  313.54    5007  313.04
  5010.2  313.54  5029.5  327.47  5104.6  333.66  5222.6   357.7  5267.6  361.67
#Mann= 3 ,-1 , 0
  4232.7     .16       0  5004.2     .07       0  5010.2     .16       0
Bank Sta=4968.2,5029.5
XS Rating Curve= 0 ,0
Exp/Cntr=0.3,0.1

Type RM Length L Ch R = 1 ,1993    ,350,350,350
BEGIN DESCRIPTION:
Mapping XS f98133cf
END DESCRIPTION:
XS GIS Cut Line= 2
      3767013.91     10589127.62      3767769.17     10588867.19
#Sta/Elev= 30
  4546.3  352.76  4555.7  356.46  4581.6  349.79  4586.9  356.75  4612.8  352.59
  4618.1  356.87  4675.2  348.29  4680.5  350.27  4700.4   345.6  4711.7  348.44
  4737.6  344.68  4742.9  346.85  4763.5   343.7  4768.8  345.85  4794.8  339.26
    4800  341.95    4826  336.34    4982  323.54  4987.3  322.69  4996.6  314.68
  5004.2  313.42  5006.9  312.92  5010.2  313.42  5013.2  322.67  5018.5  320.82
  5028.3  326.12  5218.7  340.44  5231.6  339.22    5294  346.64  5345.2   356.4
#Mann= 3 ,-1 , 0
  4546.3     .16       0  5004.2     .07       0  5010.2     .16       0
Bank Sta=5004.2,5010.2
XS Rating Curve= 0 ,0
Exp/Cntr=0.3,0.1

Type RM Length L Ch R = 1 ,1643    ,202,202,202
BEGIN DESCRIPTION:
Mapping XS 6c306dcc
END DESCRIPTION:
XS GIS Cut Line= 5
      3766935.01     10589425.58      3767268.34     10589333.57
      3767504.45     10589288.43      3767744.04     10589196.41
      3767912.45     10589126.96
#Sta/Elev= 30
  4321.4  368.03  4346.9  364.76    4401   372.1  4429.9   372.2    4461  368.49
  4509.2  354.82  4514.4   358.1  4543.6     362  4554.4  366.41  4588.3  369.76
  4622.7   366.4  4627.9  368.19  4713.1  356.05  4861.9  324.48  4892.5  321.44
  4977.6  320.22  4988.1  315.75  4993.9  308.46  4996.6  307.96  4999.9  308.46
  5009.5  318.08  5020.2  321.22  5073.8  326.74  5081.6  329.72  5086.9  328.85
  5202.7   345.8  5267.3  357.98  5278.4   362.1    5326  368.44  5346.4  368.51
#Mann= 3 ,-1 , 0
  4321.4     .16       0  4993.9     .07       0  4999.9     .16       0
Bank Sta=4993.9,4999.9
XS Rating Curve= 0 ,0
Exp/Cntr=0.3,0.1

Type RM Length L Ch R = 1 ,1441    ,493,493,493
BEGIN DESCRIPTION:
Mapping XS 9242c075
END DESCRIPTION:
XS GIS Cut Line= 2
      3767196.23       10589579.      3767933.24     10589344.89
#Sta/Elev= 30
  4529.8  333.53  4572.8  332.94    4578  334.63    4605  331.32  4610.3  334.11
  4637.3  331.72  4642.5   334.7  4669.5  332.48  4674.8  335.29    4707  329.88
  4712.3  332.51  4739.3  328.23  4803.8  323.68  4984.5  316.46    4992  304.75
  4994.8  304.25    4998  304.75  5026.5  315.23    5058  318.26  5089.4  333.86
  5110.4  340.59  5142.1  345.98  5174.3  347.09  5206.6  345.46  5233.6  341.38
  5238.8  344.14  5265.8  341.77  5271.1  344.23  5298.1  340.01  5303.1  343.43
#Mann= 3 ,-1 , 0
  4529.8     .16       0    4992     .07       0    4998     .16       0
Bank Sta=4984.5,5026.5
XS Rating Curve= 0 ,0
Exp/Cntr=0.3,0.1

Type RM Length L Ch R = 1 ,948     ,454,454,454
BEGIN DESCRIPTION:
Mapping XS d8aabbdb
END DESCRIPTION:
XS GIS Cut Line= 5
      3767186.72     10589722.45      3767518.34     10589776.27
      3767738.83     10589774.54      3767914.18     10589732.87
       3767973.2     10589550.58
#Sta/Elev= 30
  4362.4  361.73    4380  361.68  4441.6  353.72  4446.7  355.76  4503.2  350.05
  4508.3  352.35  4527.4  352.28  4564.8  346.84  4569.9  348.73  4578.1  348.03
  4626.4  341.13  4638.9  341.13  4679.4  330.79  4693.1  330.24  4719.6   324.3
  4799.6  315.13  4962.6  312.03  4996.7  300.31  4999.4  299.81  5002.7  300.31
  5004.8  300.67  5012.2  309.71  5022.4  315.48  5103.8  316.15    5144  318.49
  5167.8  324.18  5194.6  324.85  5199.8  327.17  5263.8  330.88  5290.7  329.63
#Mann= 3 ,-1 , 0
  4362.4     .12       0  4996.7     .07       0  5002.7     .12       0
Bank Sta=4962.6,5022.4
XS Rating Curve= 0 ,0
Exp/Cntr=0.3,0.1

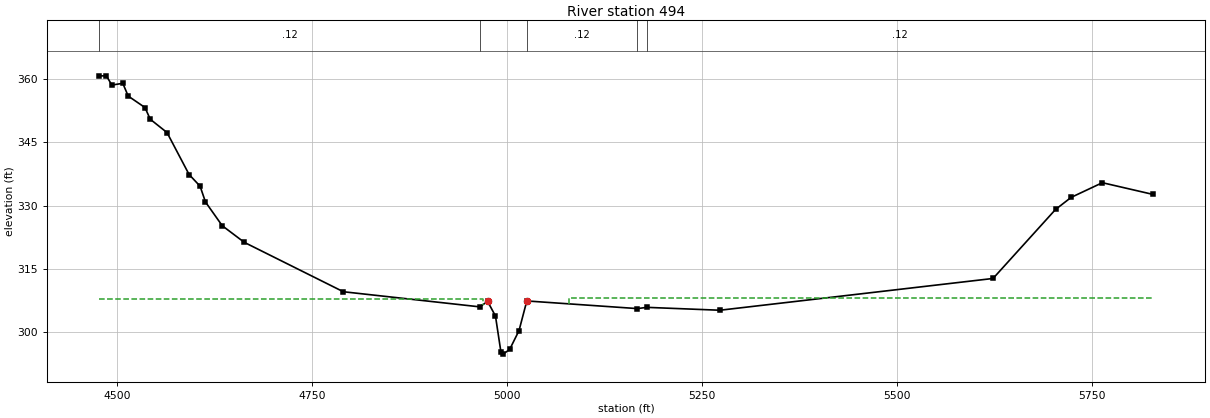
Type RM Length L Ch R = 1 ,494     ,0,0,0
BEGIN DESCRIPTION:
UNT 039 IN BOCR 1.0
END DESCRIPTION:
XS GIS Cut Line= 4
      3767343.82     10589813.37      3767656.32     10590143.23
       3767977.5     10590108.51      3768003.54     10589535.64
#Sta/Elev= 30
  4476.8  360.68  4485.9   360.7  4492.8  358.51  4506.9  358.93  4513.8  355.91
  4535.3   353.2  4542.1  350.42  4563.6  347.27  4591.9  337.34    4606  334.57
  4612.9  330.84  4634.4  325.22  4662.7  321.28  4789.7  309.59  4964.7  306.01
  4974.7   307.3  4984.8  303.85  4991.8  295.32  4994.6  294.82    5003  295.93
    5015  300.39    5025  307.41  5166.7   305.6  5179.1  305.89  5272.6  305.21
  5622.9  312.73    5703  329.06    5723  331.92  5763.1   335.4  5827.7  332.64
#Mann= 5 ,-1 , 0
  4476.8     .12       0  4964.7     .07       0    5025     .12       0
  5166.7     .12       0  5179.1     .12       0
#XS Ineff= 2 , 0
         4968.18  307.92 5079.09          308.02
Permanent Ineff=
       F       F
Bank Sta=4974.7,5025
XS Rating Curve= 0 ,0
Exp/Cntr=0.3,0.1

Chan Stop Cuts=-1
Use User Specified Reach Order=0
Composite Channel Slope=5