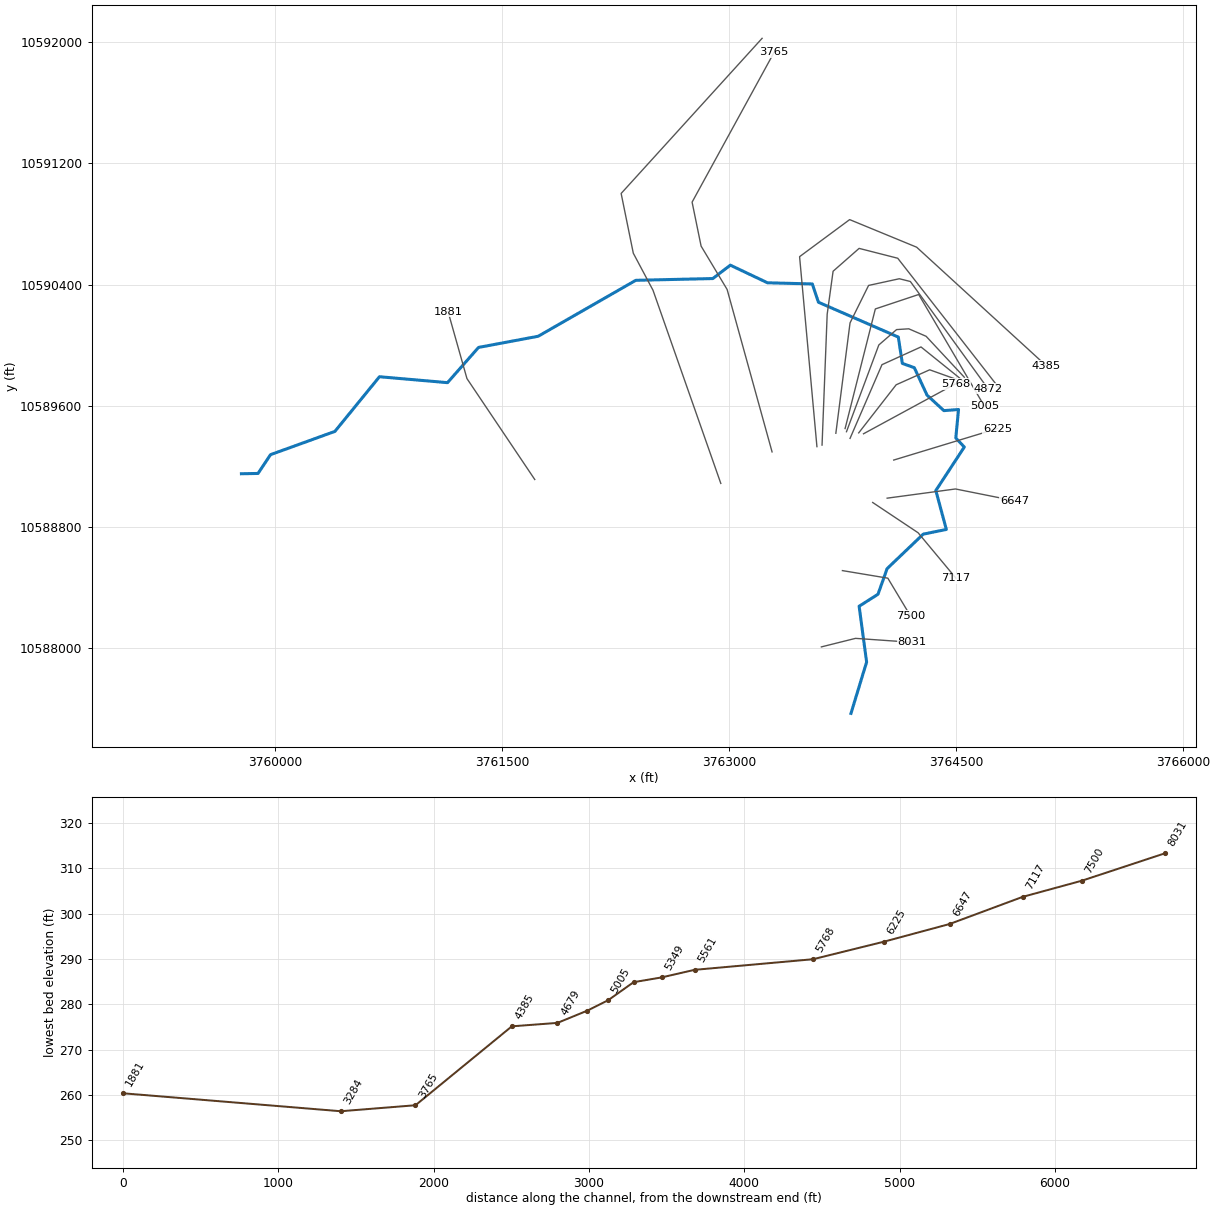
--- UNT 040 IN BOCR.prj (project) ---

Proj Title=UNT 040 IN BOCR Base Level Engineering
Current Plan=p01
Default Exp/Contr=0.3,0.1
English Units
Geom File=g01
Flow File=f01
Plan File=p01
Y Axis Title=Elevation
X Axis Title(PF)=Main Channel Distance
X Axis Title(XS)=Station
BEGIN DESCRIPTION:
UNT 040 IN BOCR
END DESCRIPTION:
DSS Export Rating Curves= 0
DSS Export Rating Curve Sorted= 0
DSS Export Volume Flow Curves= 0
DXF OffsetX= 0
DXF OffsetY= 0
DXF ScaleX= 1
DXF ScaleY= 10

--- UNT 040 IN BOCR.p01 (plan) ---

Plan Title=Multiple Run
Short Identifier=Multiple
Geom File=g01
Flow File=f01
Subcritical Flow
K Sum by GR= 0
Std Step Tol= 0.01
Critical Tol= 0.01
Num of Std Step Trials= 20
Max Error Tol= 0.3
Flow Tol Ratio= 0.001
Split Flow NTrial= 30
Split Flow Tol= 0.02
Split Flow Ratio= 0.02
Log Output Level= 0
Friction Slope Method= 1
Unsteady Friction Slope Method= 2
Unsteady Bridges Friction Slope Method= 1
Parabolic Critical Depth
Global Vel Dist=  1 , 1 , 1
Global Log Level= 0
CheckData=True
Encroach Param= -1, 0, 0, 0
BEGIN DESCRIPTION:
Multiple Run
END DESCRIPTION:

--- UNT 040 IN BOCR.f01 (steady flow) ---

Flow Title=Multiple
Number of Profiles=7
Profile Names=10-year,25-year,50-year,1pct_min,100-year,1pct_plu,500-year
River Rch & RM= UNT 040 IN BOCR,Reach-1,8031
     572     780     952     857    1159    1567    1719
Boundary for River Rch & Prof#=UNT 040 IN BOCR,Reach-1,1
Up Type=0
Dn Type=3
Dn Slope=0.005
Boundary for River Rch & Prof#=UNT 040 IN BOCR,Reach-1,2
Up Type=0
Dn Type=3
Dn Slope=0.005
Boundary for River Rch & Prof#=UNT 040 IN BOCR,Reach-1,3
Up Type=0
Dn Type=3
Dn Slope=0.005
Boundary for River Rch & Prof#=UNT 040 IN BOCR,Reach-1,4
Up Type=0
Dn Type=3
Dn Slope=0.005
Boundary for River Rch & Prof#=UNT 040 IN BOCR,Reach-1,5
Up Type=0
Dn Type=3
Dn Slope=0.005
Boundary for River Rch & Prof#=UNT 040 IN BOCR,Reach-1,6
Up Type=0
Dn Type=3
Dn Slope=0.005
Boundary for River Rch & Prof#=UNT 040 IN BOCR,Reach-1,7
Up Type=0
Dn Type=3
Dn Slope=0.005

--- UNT 040 IN BOCR.g01 (geometry) ---

Geom Title=Existing Conditions
Program Version=4.10

River Reach=UNT 040 IN BOCR ,Reach-1
Reach XY= 30
      3763806.25       10587567.       3763909.5       10587906.
      3763859.98     10588274.58      3763984.75       10588354.
      3764044.75       10588523.       3764283.5       10588751.
      3764436.25       10588782.      3764366.75       10589039.
      3764554.82     10589326.43      3764498.57     10589386.33
      3764516.79     10589574.35      3764419.92     10589567.05
       3764308.8     10589669.11      3764224.61     10589850.55
      3764145.52     10589879.01      3764118.75       10590053.
      3763591.25       10590283.      3763550.81      10590403.9
      3763254.93     10590411.49      3763009.15     10590528.03
       3762893.7     10590439.49      3762384.61     10590427.87
      3761739.83     10590058.24      3761345.74     10589984.46
      3761140.87     10589751.82      3760691.22     10589790.88
      3760396.95     10589429.77       3759971.5       10589276.
        3759889.       10589152.       3759779.5       10589150.

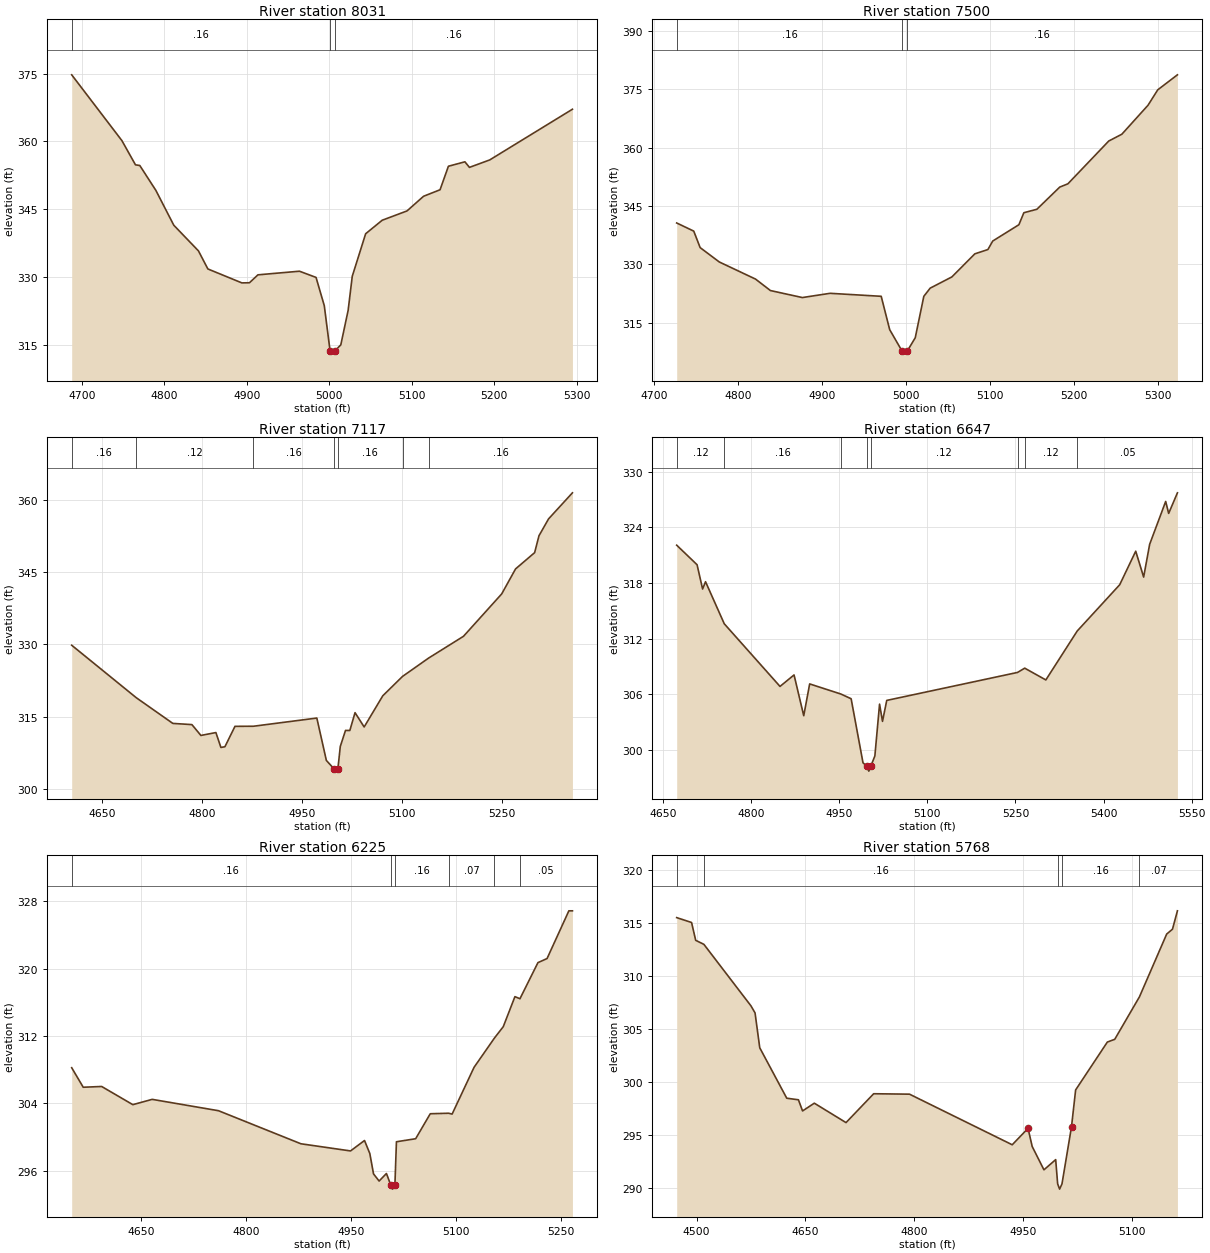
Type RM Length L Ch R = 1 ,8031    ,531,531,531
BEGIN DESCRIPTION:
UNT 040 IN BOCR 6.0
END DESCRIPTION:
XS GIS Cut Line= 3
      3763610.64     10588006.17      3763836.29     10588062.58
      3764209.59     10588036.53
#Sta/Elev= 30
  4687.9  374.71  4748.7  360.19  4765.2  354.83  4770.4  354.69  4789.9  349.19
  4811.6   341.5  4841.5  335.83  4852.9  331.84  4894.1  328.76  4903.3  328.79
  4913.6  330.54  4963.9  331.34    4984  329.97    4994  323.72    5001  313.75
  5003.8  313.25    5007  313.75    5014  315.08  5022.9   322.7  5027.9  330.23
  5044.1  339.61  5064.2   342.6  5094.2  344.65  5114.3  347.89  5134.3  349.33
  5144.4  354.52  5164.4   355.5  5169.9  354.27  5194.5  355.92  5294.7  367.11
#Mann= 3 ,-1 , 0
  4687.9     .16       0    5001     .07       0    5007     .16       0
Bank Sta=5001,5007
XS Rating Curve= 0 ,0
Exp/Cntr=0.3,0.1

Type RM Length L Ch R = 1 ,7500    ,383,383,383
BEGIN DESCRIPTION:
UNT 040 IN BOCR 5.0
END DESCRIPTION:
XS GIS Cut Line= 3
      3763749.63     10588510.19      3764049.61     10588460.19
      3764199.63     10588210.16
#Sta/Elev= 30
  4726.9  340.65  4747.2  338.56  4754.8  334.33  4777.6  330.64  4820.7  326.25
  4838.4  323.31  4876.4  321.51  4909.4   322.6  4970.2  321.83  4980.3  313.27
  4995.1  307.75  4997.8  307.25  5001.1  307.75  5010.7  311.19  5020.9  321.83
  5028.5  323.93  5054.3  326.81  5081.6  332.73  5097.1  333.83  5102.9  336.02
    5134   340.2  5139.9  343.28  5155.4  344.17  5182.6  349.86  5192.3   350.7
  5240.9  361.68  5256.5  363.43  5287.6  370.86  5299.2  374.82  5322.6  378.67
#Mann= 3 ,-1 , 0
  4726.9     .16       0  4995.1     .07       0  5001.1     .16       0
Bank Sta=4995.1,5001.1
XS Rating Curve= 0 ,0
Exp/Cntr=0.3,0.1

Type RM Length L Ch R = 1 ,7117    ,470,470,470
BEGIN DESCRIPTION:
UNT 040 IN BOCR 4.0
END DESCRIPTION:
XS GIS Cut Line= 3
      3763949.61     10588960.19      3764249.61     10588760.19
      3764499.63     10588460.16
#Sta/Elev= 30
  4604.8  329.81  4701.6  318.92  4756.5  313.58  4785.1  313.33  4798.6  311.08
  4821.1  311.68  4828.6  308.59  4834.6  308.73  4849.7  312.97  4877.4  312.99
  4972.5  314.69  4986.8  305.89  4998.1  304.17  5000.9  303.67  5004.1  304.17
  5007.7   308.8  5015.5  312.12    5022  312.11  5029.8  315.81  5043.5  312.84
  5071.4  319.31    5101  323.33    5140  327.13  5192.5  331.67  5249.8  340.47
  5270.6  345.66  5299.2  349.04  5305.7  352.54  5320.1  356.05  5355.9  361.46
#Mann= 7 ,-1 , 0
  4604.8     .16       0  4701.6     .12       0  4877.4     .16       0
  4998.1     .07       0  5004.1     .16       0    5101     .12       0
    5140     .16       0
Bank Sta=4998.1,5004.1
XS Rating Curve= 0 ,0
Exp/Cntr=0.3,0.1

Type RM Length L Ch R = 1 ,6647    ,422,422,422
BEGIN DESCRIPTION:
UNT 040 IN BOCR 3.0
END DESCRIPTION:
XS GIS Cut Line= 3
      3764045.23     10588988.72      3764496.59     10589049.48
      3764885.95     10588971.61
#Sta/Elev= 30
  4673.3  322.07    4708  319.96  4717.4  317.34  4722.4  318.13  4754.3  313.59
  4849.2  306.83  4873.1  308.07  4889.6  303.67  4899.7   307.1  4952.8  306.01
  4970.3   305.5  4990.5  298.59  4997.6  298.19  5000.4  297.69  5003.6  298.19
  5010.7  299.33  5018.7  304.92  5023.7  303.06  5030.9  305.32  5253.6  308.34
  5265.8   308.8  5301.8  307.53  5355.2  312.81  5427.5   317.8  5454.8  321.42
  5468.3  318.63  5478.5  322.16  5505.8  326.79  5510.9   325.5  5525.8  327.72
#Mann= 8 ,-1 , 0
  4673.3     .12       0  4754.3     .16       0  4952.8     .12       0
  4997.6     .07       0  5003.6     .12       0  5253.6     .07       0
  5265.8     .12       0  5355.2     .05       0
Bank Sta=4997.6,5003.6
XS Rating Curve= 0 ,0
Exp/Cntr=0.3,0.1

Type RM Length L Ch R = 1 ,6225    ,457,457,457
BEGIN DESCRIPTION:
UNT 040 IN BOCR 2.0
END DESCRIPTION:
XS GIS Cut Line= 2
      3764088.59     10589240.45      3764774.35     10589448.78
#Sta/Elev= 30
  4550.3  308.23  4566.8  305.91  4593.2     306  4637.8  303.84  4665.5  304.47
  4760.4  303.12  4878.4  299.19  4949.4  298.34  4969.4  299.58    4977  298.03
  4982.3  295.61  4990.3  294.76  5000.8  295.66  5006.9   294.3  5009.7   293.8
  5012.9   294.3  5015.1  299.43  5042.6  299.79  5063.5  302.76  5089.7  302.82
  5094.8  302.72  5126.2  308.28  5155.4  311.76    5168  313.11  5184.7  316.68
  5191.9  316.43  5217.6  320.72  5230.7  321.21  5261.9  326.88    5267  326.88
#Mann= 6 ,-1 , 0
  4550.3     .16       0  5006.9     .07       0  5012.9     .16       0
  5089.7     .07       0  5155.4     .16       0  5191.9     .05       0
Bank Sta=5006.9,5012.9
XS Rating Curve= 0 ,0
Exp/Cntr=0.3,0.1

Type RM Length L Ch R = 1 ,5768    ,763,763,763
BEGIN DESCRIPTION:
Mapping XS f6350efe
END DESCRIPTION:
XS GIS Cut Line= 2
      3763888.99     10589414.08      3764495.57     10589743.37
#Sta/Elev= 30
  4472.6  315.52  4493.1  315.06  4498.8  313.38  4510.1     313  4574.9  307.21
  4580.6  306.54  4587.1  303.25  4624.3   298.5  4640.4  298.35  4646.1   297.3
  4662.3  298.03    4706   296.2  4744.1  298.92  4793.5  298.88  4935.1  294.11
  4956.9  295.66  4962.6  293.95  4978.8  291.75    4995  292.71  4997.7  290.43
  5000.4  289.93  5003.7  290.43  5016.8  295.81  5022.5  299.28  5066.2  303.79
  5076.4  304.05  5110.5  308.06    5148  313.97    5156  314.43  5162.8  316.16
#Mann= 5 ,-1 , 0
  4472.6     .12       0  4510.1     .16       0  4997.7     .07       0
  5003.7     .16       0  5110.5     .07       0
Bank Sta=4956.9,5016.8
XS Rating Curve= 0 ,0
Exp/Cntr=0.3,0.1

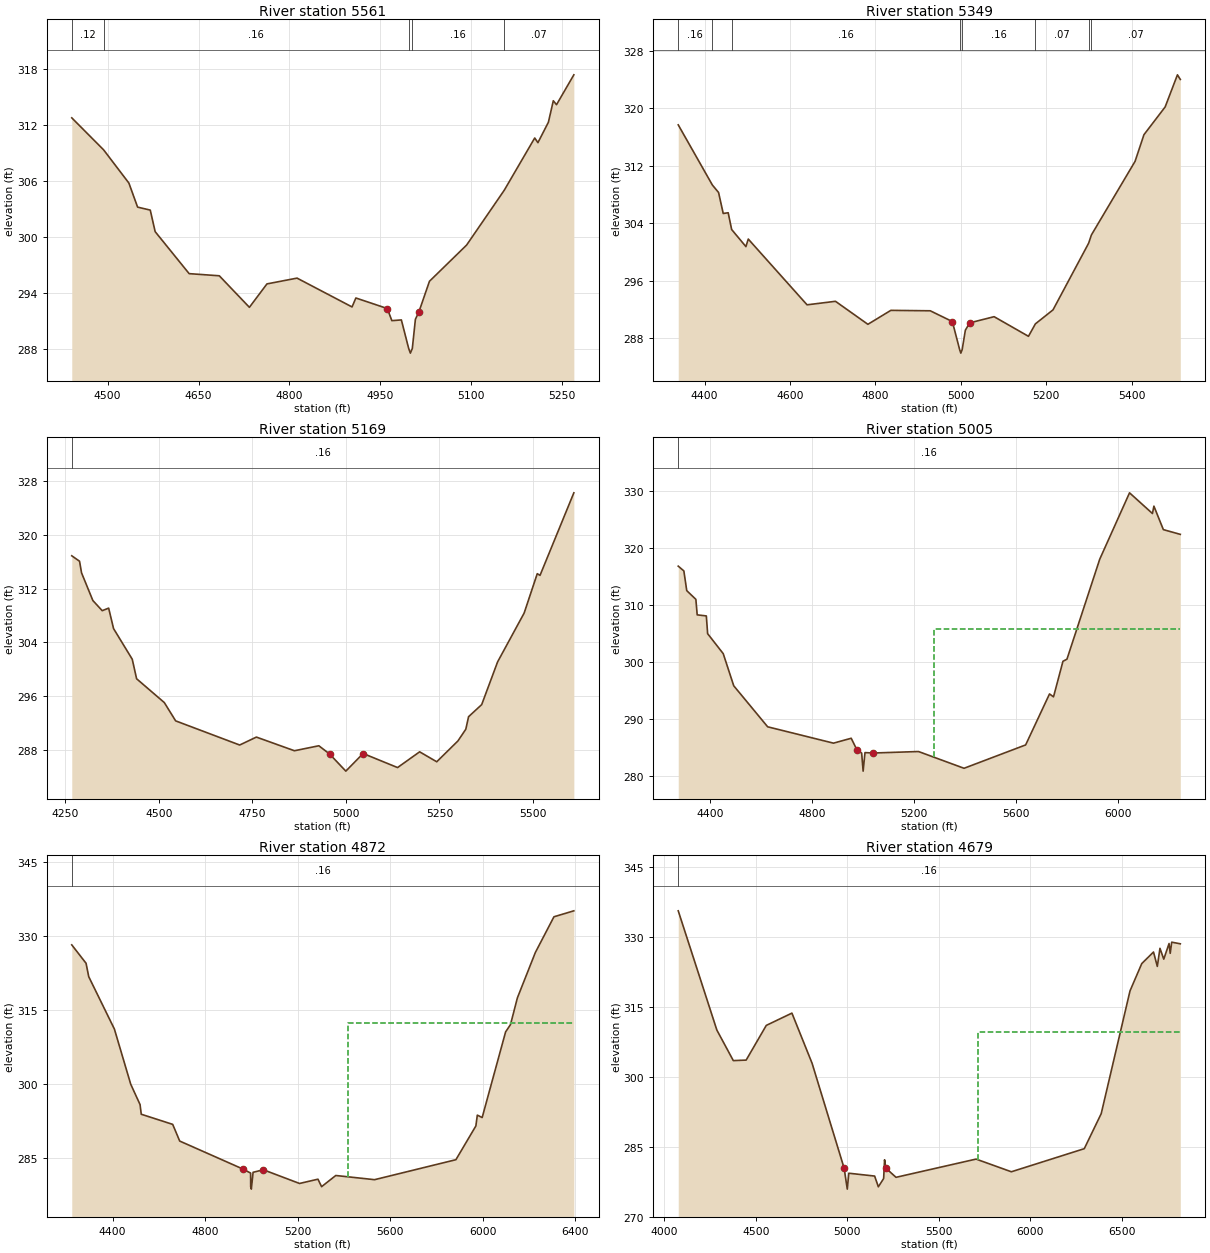
Type RM Length L Ch R = 1 ,5561    ,212,212,212
BEGIN DESCRIPTION:
Mapping XS 85af1fda
END DESCRIPTION:
XS GIS Cut Line= 4
      3763857.31     10589420.01      3764104.72     10589737.74
      3764326.08      10589836.7      3764499.14     10589774.71
#Sta/Elev= 30
  4440.7  312.81  4493.4  309.37    4535  305.82  4549.4  303.24  4570.3  302.92
  4578.4  300.61  4634.5  296.11  4684.3  295.88    4734   292.5    4763  295.01
  4812.7  295.63  4903.5  292.54  4909.8   293.5  4961.7  292.37  4969.2  291.07
  4984.9  291.15    4997  288.09  4999.8  287.59    5003  288.09  5008.1  291.22
  5013.6  291.96  5031.3  295.29  5092.6  299.17  5154.8  305.05  5205.1  310.65
  5210.4  310.15  5227.7  312.34  5235.8  314.64  5241.1  314.22  5269.7  317.42
#Mann= 5 ,-1 , 0
  4440.7     .12       0  4493.4     .16       0    4997     .07       0
    5003     .16       0  5154.8     .07       0
Bank Sta=4961.7,5013.6
XS Rating Curve= 0 ,0
Exp/Cntr=0.3,0.1

Type RM Length L Ch R = 1 ,5349    ,180,180,180
BEGIN DESCRIPTION:
Mapping XS 6ccf2af7
END DESCRIPTION:
XS GIS Cut Line= 4
      3763800.03     10589383.56      3764010.97     10589870.55
      3764268.78     10589987.74      3764550.06     10589761.16
#Sta/Elev= 30
  4338.4  317.68  4418.3  309.31  4432.8  308.27  4443.7  305.35  4455.3  305.45
  4463.4  303.12  4496.8  300.74  4502.3  301.79  4639.9  292.64  4706.4  293.13
  4782.3  289.93    4836  291.87  4928.3  291.81    4980  290.31    4997  286.42
  4999.8  285.92    5003  286.42  5010.4  289.11  5020.6  290.13  5077.7  290.99
  5158.1  288.26  5174.3  289.99  5215.6  291.94  5298.9  301.21  5305.4  302.36
  5407.6   312.6  5428.4  316.31    5478  320.17  5506.8  324.64  5513.5     324
#Mann= 8 ,-1 , 0
  4338.4     .16       0  4418.3     .12       0  4463.4     .16       0
    4997     .07       0    5003     .16       0  5174.3     .07       0
  5298.9     .16       0  5305.4     .07       0
Bank Sta=4980,5020.6
XS Rating Curve= 0 ,0
Exp/Cntr=0.3,0.1

Type RM Length L Ch R = 1 ,5169    ,164,164,164
BEGIN DESCRIPTION:
Mapping XS 8ea57b15
END DESCRIPTION:
XS GIS Cut Line= 6
      3763776.58     10589427.81      3763990.14     10590000.76
      3764107.33     10590102.33      3764188.05     10590107.53
      3764302.64     10590058.05      3764554.91     10589787.58
#Sta/Elev= 30
  4267.2  316.88    4288  316.07  4293.3  314.35  4323.6  310.23  4348.6  308.72
  4365.8   309.1  4378.9  306.06  4428.9   301.5  4440.5   298.6  4514.6  295.06
  4544.9  292.34  4716.1  288.75  4760.7  289.93  4862.4   287.9  4927.7  288.64
  4956.3  287.42  4999.8  284.87    5046  287.49  5138.1   285.4  5197.1  287.74
  5242.8  286.26  5299.5  289.36  5320.5   291.1  5327.9  292.96    5363  294.76
  5405.5  301.11  5476.4  308.36  5511.5  314.22  5518.9  313.97  5609.3  326.24
#Mann= 1 ,-1 , 0
  4267.2     .16       0
Bank Sta=4956.3,5046
XS Rating Curve= 0 ,0
Exp/Cntr=0.3,0.1

Type RM Length L Ch R = 1 ,5005    ,133,133,133
BEGIN DESCRIPTION:
UNT 040 IN BOCR 1.0
END DESCRIPTION:
XS GIS Cut Line= 4
      3763767.42     10589448.74      3763967.08     10590238.72
      3764253.54     10590334.21      3764687.56     10589596.37
#Sta/Elev= 30
  4273.3  316.87  4295.4  316.03  4306.8  312.57  4342.6  311.04  4347.8  308.32
  4383.7  308.13  4388.8  305.02  4450.1  301.51  4491.4  295.87  4624.7  288.67
  4883.3   285.8    4953  286.66  4976.2  284.55    4994  284.07  4999.8  280.89
  5007.1  284.14  5040.2  284.07  5217.3  284.33  5396.4  281.39  5638.4  285.49
  5732.2  294.44  5747.9  293.93    5785  300.17  5800.7  300.54  5929.5  318.09
  6046.6  329.74  6136.6  326.11  6142.4   327.4  6179.5  323.28  6246.1  322.45
#Mann= 1 ,-1 , 0
  4273.3     .16       0
#XS Ineff= 2 , 0
                         5278.41          305.91
Permanent Ineff=
       F       F
Bank Sta=4976.2,5040.2
XS Rating Curve= 0 ,0
Exp/Cntr=0.3,0.1

Type RM Length L Ch R = 1 ,4872    ,193,193,193
BEGIN DESCRIPTION:
Mapping XS 98c0958e
END DESCRIPTION:
XS GIS Cut Line= 6
      3763706.28     10589417.43      3763800.03      10590146.6
      3763922.43     10590393.99      3764125.55     10590438.26
      3764198.47     10590420.03      3764711.52     10589711.66
#Sta/Elev= 30
  4223.6  328.25  4285.4  324.51    4297  321.78  4407.9  311.14  4478.4  299.94
  4518.8  295.79    4524  293.83  4659.9  291.77  4690.2  288.38  4963.6  282.69
  4996.7  281.87    4997  279.11  4999.8  278.61  5007.4  282.03    5052  282.54
  5208.2  279.76  5287.8  280.63  5303.5  279.11  5364.9  281.38  5532.6  280.53
  5884.1  284.59  5970.4  291.45  5976.7  293.65  5997.6  293.16    6099  310.57
    6120  312.04  6149.8  317.47  6227.5   326.7  6307.9  333.96  6393.9  335.17
#Mann= 1 ,-1 , 0
  4223.6     .16       0
#XS Ineff= 2 , 0
                         5417.61           312.4
Permanent Ineff=
       F       F
Bank Sta=4963.6,5052
XS Rating Curve= 0 ,0
Exp/Cntr=0.3,0.1

Type RM Length L Ch R = 1 ,4679    ,294,294,294
BEGIN DESCRIPTION:
Mapping XS 697e7d8f
END DESCRIPTION:
XS GIS Cut Line= 6
      3763615.14     10589339.29      3763648.99     10590203.89
      3763688.05     10590487.74      3763859.93     10590638.78
      3764115.14     10590573.68      3764792.23     10589706.49
#Sta/Elev= 30
  4075.8  335.56  4286.9     310  4376.9  303.45    4447  303.56  4557.1     311
  4697.2  313.63  4807.3  302.89  4982.5   280.4  4999.8   275.9    5008  279.31
  5149.3   278.7  5169.5   276.4  5198.5  278.17  5203.6  282.19  5209.9  280.42
  5266.1  278.43  5703.8  282.34  5896.6  279.62  6295.1  284.57  6387.7  292.08
  6545.1   318.4  6609.3  324.25  6673.5  326.73  6694.3  323.65  6708.8  327.52
  6729.6   325.2  6758.5  328.55  6764.9  326.45    6773  328.84    6820  328.49
#Mann= 1 ,-1 , 0
  4075.8     .16       0
#XS Ineff= 2 , 0
                         5713.07           309.6
Permanent Ineff=
       F       F
Bank Sta=4982.5,5209.9
XS Rating Curve= 0 ,0
Exp/Cntr=0.3,0.1

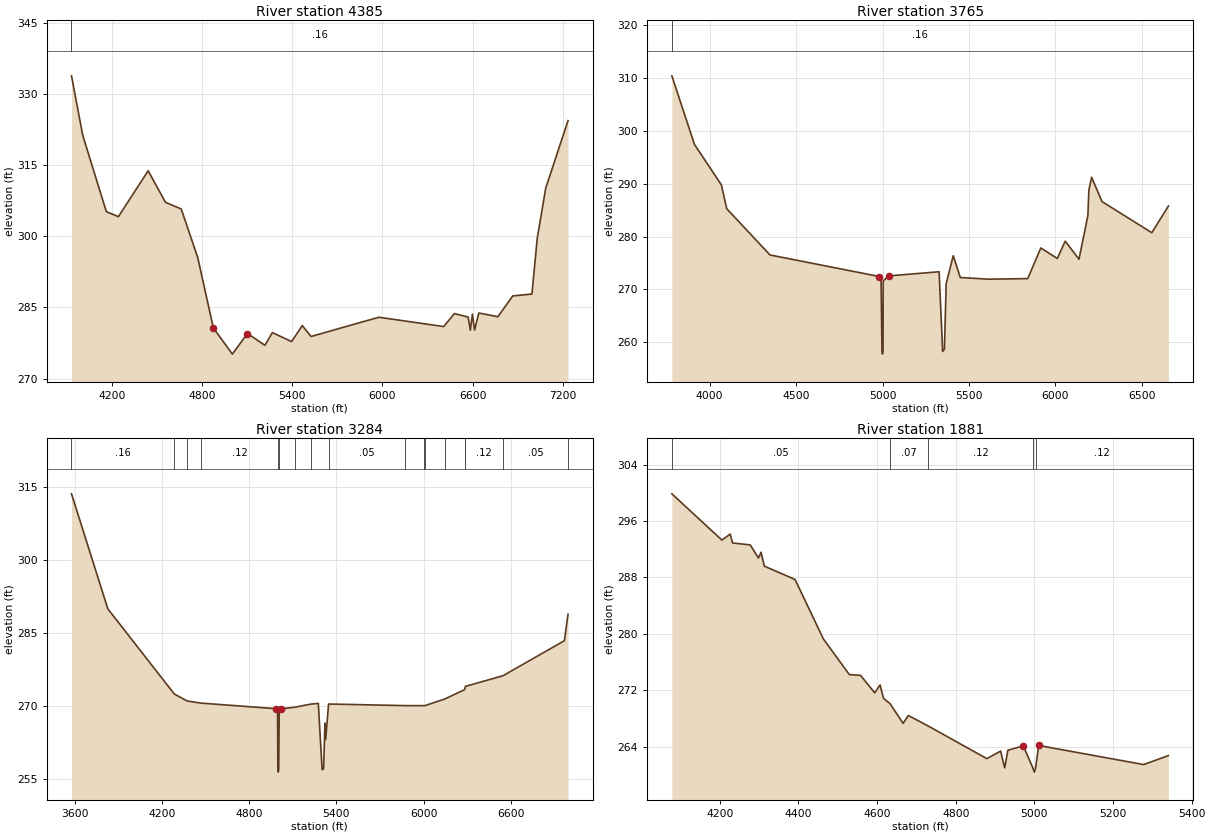
Type RM Length L Ch R = 1 ,4385    ,620,620,620
BEGIN DESCRIPTION:
Mapping XS 23788488
END DESCRIPTION:
XS GIS Cut Line= 5
      3763581.28     10589328.91       3763466.7      10590584.1
      3763797.43     10590828.89      3764240.14      10590646.6
      3765094.41     10589865.03
#Sta/Elev= 30
    3928  333.83    4003  321.28  4160.2  305.18  4240.6  304.13  4438.9  313.81
  4554.1  307.16  4659.4  305.74  4769.6  295.46  4873.2  280.67  4999.8  275.14
  5100.3  279.49  5216.9  277.01  5266.7  279.68  5394.6  277.79  5465.7  281.16
  5524.1  278.86  5976.3  282.92  6408.3  280.95  6479.2  283.69  6571.1  282.95
  6585.3   280.2  6599.5  283.57  6613.7   280.2    6642  283.81  6769.2  283.03
  6868.4  287.42    6996  287.81  7031.2  299.54  7087.9  310.16  7236.5  324.38
#Mann= 1 ,-1 , 0
    3928     .16       0
Bank Sta=4873.2,5100.3
XS Rating Curve= 0 ,0
Exp/Cntr=0.3,0.1

Type RM Length L Ch R = 1 ,3765    ,481,481,481
BEGIN DESCRIPTION:
Mapping XS e53e79b0
END DESCRIPTION:
XS GIS Cut Line= 5
      3763284.89     10589294.38      3762988.01     10590367.28
      3762816.14     10590653.74      3762756.63     10590944.34
      3763298.28     10591933.89
#Sta/Elev= 30
  3781.7  310.45  3912.2  297.47  4067.9  289.81    4099  285.29  4349.2  276.53
  4982.5  272.44  4991.6   272.1    4997  258.25  4999.8  257.75    5003  258.25
  5003.9   271.6    5035  272.56  5327.4  273.35  5347.8  258.25  5358.1  258.69
  5368.3  271.09  5409.1  276.39  5449.9  272.26  5612.1  271.94  5840.1  272.05
  5915.6  277.86  6011.1  275.86  6056.7  279.14  6136.5  275.72  6187.8  283.99
  6193.5  288.77  6209.6  291.24  6269.4  286.64  6557.7  280.74  6653.7   285.8
#Mann= 1 ,-1 , 0
  3781.7     .16       0
Bank Sta=4982.5,5035
XS Rating Curve= 0 ,0
Exp/Cntr=0.3,0.1

Type RM Length L Ch R = 1 ,3284    ,1403,1403,1403
BEGIN DESCRIPTION:
Mapping XS 446d1adf
END DESCRIPTION:
XS GIS Cut Line= 5
      3762946.33     10589086.07      3762498.43     10590362.07
      3762368.22     10590606.87      3762287.88     10591001.63
      3763219.03     10592026.42
#Sta/Elev= 30
  3576.9   313.5    3827  289.91  4284.8  272.44  4373.6  271.01  4469.6  270.58
  4984.7  269.44  4995.1  269.17    4997  256.93  4999.8  256.43    5003  256.93
  5006.6   269.4  5017.3   269.4  5111.9  269.73  5222.4  270.37  5275.5  270.52
  5301.7  256.93  5311.9  257.11    5321  266.48  5326.1  263.09  5346.1   270.4
  5870.9  270.07  6004.9  270.06  6008.2  270.06    6146  271.43  6282.9  273.36
  6287.2  274.01  6546.6   276.2  6968.9  283.38  6992.7  288.54    6994   288.8
#Mann= 17 ,-1 , 0
  3576.9     .16       0  4284.8     .12       0  4373.6     .16       0
  4469.6     .12       0    4997     .07       0    5003     .12       0
  5111.9     .05       0  5222.4     .12       0  5346.1     .05       0
  5870.9     .07       0  6004.9     .12       0  6008.2     .07       0
    6146     .12       0  6282.9     .07       0  6287.2     .12       0
  6546.6     .05       0  6992.7     .16       0
Bank Sta=4984.7,5017.3
XS Rating Curve= 0 ,0
Exp/Cntr=0.3,0.1

Type RM Length L Ch R = 1 ,1881    ,0,0,0
BEGIN DESCRIPTION:
Mapping XS b9899974
END DESCRIPTION:
XS GIS Cut Line= 3
      3761717.19     10589112.05      3761269.26     10589778.74
      3761144.43     10590220.87
#Sta/Elev= 30
  4078.3  299.85  4205.5  293.29  4226.5  294.14  4232.7  292.88  4277.5  292.61
  4298.5  290.75    4305  291.57  4313.5  289.59  4391.5  287.71  4463.5  279.28
  4529.5  274.22    4558  274.11  4594.1  271.63  4607.6  272.75  4616.5  270.85
  4633.2  270.09  4666.4   267.3  4679.6  268.42  4729.8  266.94  4879.3   262.3
  4914.2  263.37  4924.6  260.99  4932.6  263.49  4971.8  264.11    4997  260.89
  4999.8  260.39    5003  260.89    5011  264.17  5277.9  261.46  5340.9  262.74
#Mann= 5 ,-1 , 0
  4078.3     .05       0  4633.2     .07       0  4729.8     .12       0
    4997     .07       0    5003     .12       0
Bank Sta=4971.8,5011
XS Rating Curve= 0 ,0
Exp/Cntr=0.3,0.1

Chan Stop Cuts=-1
Use User Specified Reach Order=0
Composite Channel Slope=5