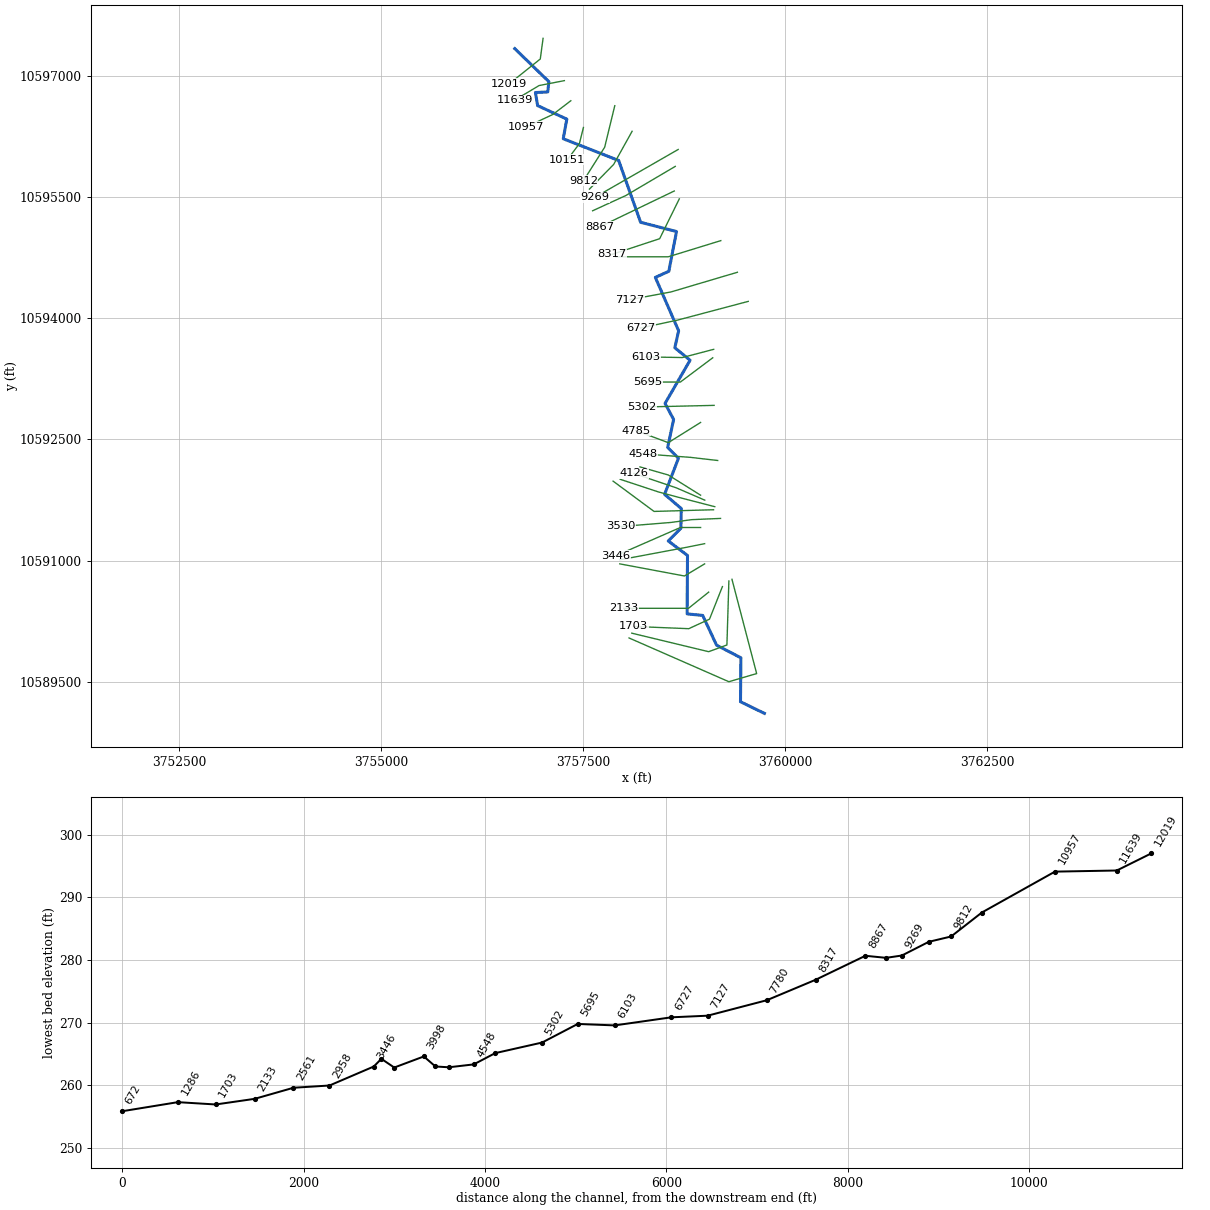
--- UNT 041 IN BOCR.prj (project) ---

Proj Title=UNT 041 IN BOCR Base Level Engineering
Current Plan=p01
Default Exp/Contr=0.3,0.1
English Units
Geom File=g01
Flow File=f01
Plan File=p01
Y Axis Title=Elevation
X Axis Title(PF)=Main Channel Distance
X Axis Title(XS)=Station
BEGIN DESCRIPTION:
UNT 041 IN BOCR
END DESCRIPTION:
DSS Export Rating Curves= 0
DSS Export Rating Curve Sorted= 0
DSS Export Volume Flow Curves= 0
DXF OffsetX= 0
DXF OffsetY= 0
DXF ScaleX= 1
DXF ScaleY= 10

--- UNT 041 IN BOCR.p01 (plan) ---

Plan Title=Multiple Run
Short Identifier=Multiple
Geom File=g01
Flow File=f01
Subcritical Flow
K Sum by GR= 0
Std Step Tol= 0.01
Critical Tol= 0.01
Num of Std Step Trials= 20
Max Error Tol= 0.3
Flow Tol Ratio= 0.001
Split Flow NTrial= 30
Split Flow Tol= 0.02
Split Flow Ratio= 0.02
Log Output Level= 0
Friction Slope Method= 1
Unsteady Friction Slope Method= 2
Unsteady Bridges Friction Slope Method= 1
Parabolic Critical Depth
Global Vel Dist=  1 , 1 , 1
Global Log Level= 0
CheckData=True
Encroach Param= -1, 0, 0, 0
BEGIN DESCRIPTION:
Multiple Run
END DESCRIPTION:

--- UNT 041 IN BOCR.f01 (steady flow) ---

Flow Title=Multiple
Number of Profiles=7
Profile Names=10-year,25-year,50-year,1pct_min,100-year,1pct_plu,500-year
River Rch & RM= UNT 041 IN BOCR,Reach-1,12019
     674     927    1139    1030    1393    1884    2090
River Rch & RM= UNT 041 IN BOCR,Reach-1,9269
     744    1025    1262    1142    1545    2089    2323
River Rch & RM= UNT 041 IN BOCR,Reach-1,7780
    1030    1436    1780    1620    2190    2962    3330
Boundary for River Rch & Prof#=UNT 041 IN BOCR,Reach-1,1
Up Type=0
Dn Type=3
Dn Slope=0.005
Boundary for River Rch & Prof#=UNT 041 IN BOCR,Reach-1,2
Up Type=0
Dn Type=3
Dn Slope=0.005
Boundary for River Rch & Prof#=UNT 041 IN BOCR,Reach-1,3
Up Type=0
Dn Type=3
Dn Slope=0.005
Boundary for River Rch & Prof#=UNT 041 IN BOCR,Reach-1,4
Up Type=0
Dn Type=3
Dn Slope=0.005
Boundary for River Rch & Prof#=UNT 041 IN BOCR,Reach-1,5
Up Type=0
Dn Type=3
Dn Slope=0.005
Boundary for River Rch & Prof#=UNT 041 IN BOCR,Reach-1,6
Up Type=0
Dn Type=3
Dn Slope=0.005
Boundary for River Rch & Prof#=UNT 041 IN BOCR,Reach-1,7
Up Type=0
Dn Type=3
Dn Slope=0.005

--- UNT 041 IN BOCR.g01 (geometry) ---

Geom Title=Existing Conditions
Program Version=4.10

River Reach=UNT 041 IN BOCR ,Reach-1
Reach XY= 30
      3756650.24     10597336.06      3757071.75       10596928.
      3757058.75       10596800.      3756905.75       10596793.
        3756933.       10596631.      3757294.25       10596464.
        3757250.       10596221.      3757935.75       10595952.
       3758207.5       10595187.      3758651.75       10595073.
       3758556.5       10594581.       3758389.5       10594505.
        3758678.       10593844.      3758630.75       10593635.
      3758819.25       10593480.        3758510.       10592946.
      3758615.75       10592747.      3758542.25       10592401.
      3758675.75       10592267.        3758504.       10591821.
      3758710.25       10591645.        3758706.       10591401.
       3758549.5       10591244.      3758787.75       10591064.
        3758783.       10590341.        3758976.       10590322.
      3759147.25       10589954.      3759448.25       10589798.
       3759443.5       10589254.        3759739.       10589110.

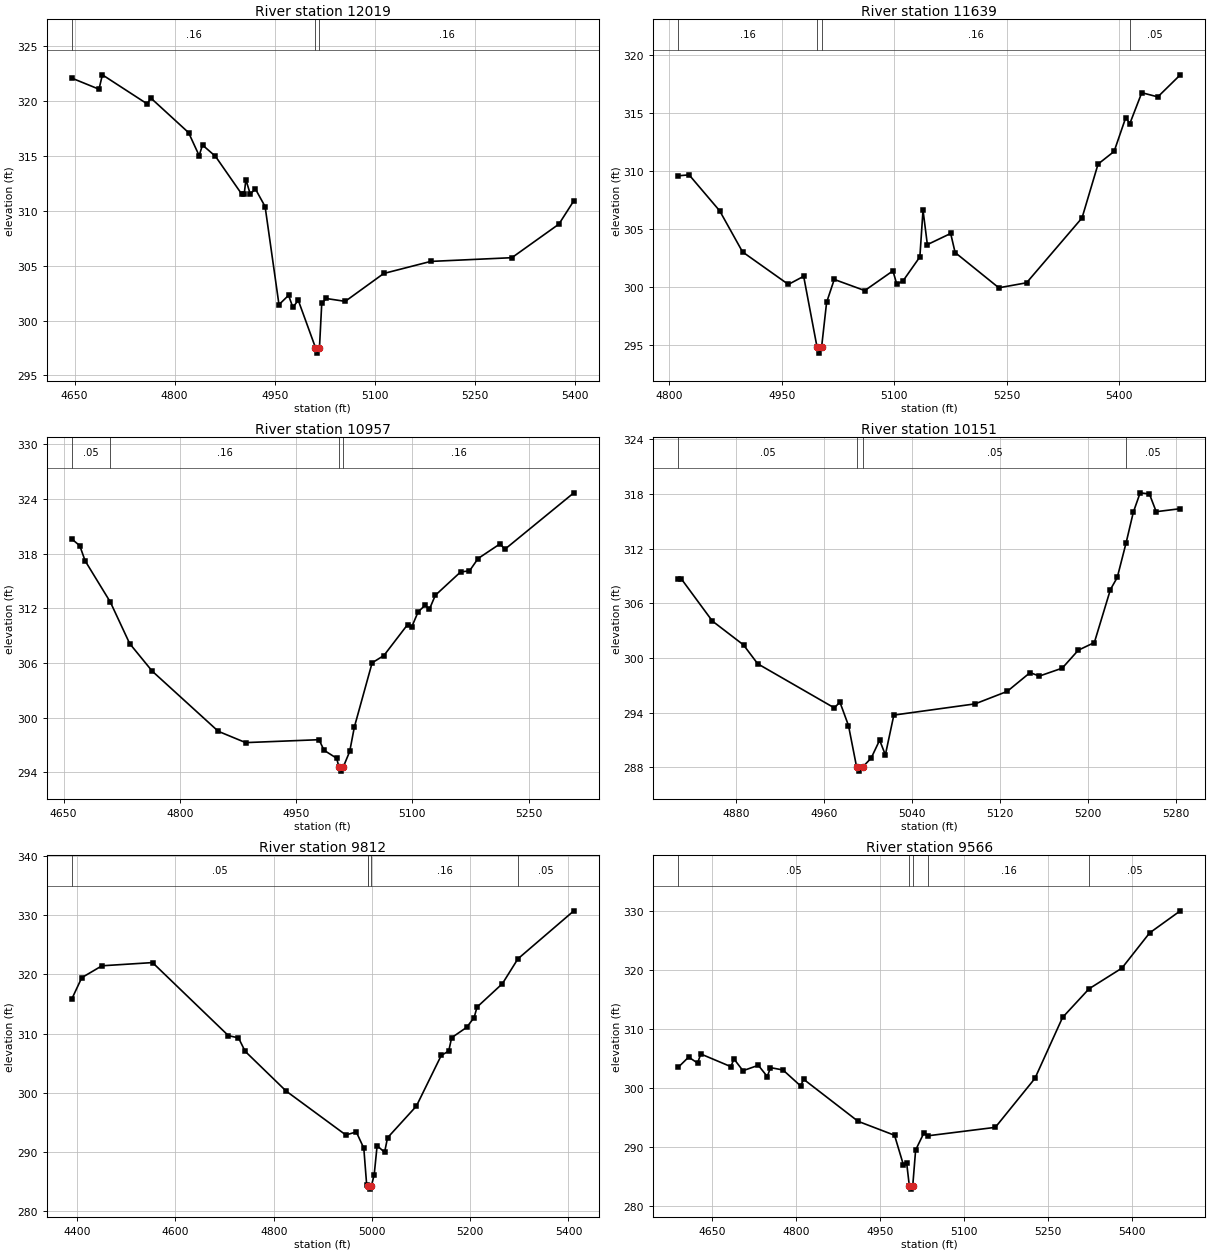
Type RM Length L Ch R = 1 ,12019   ,380,380,380
BEGIN DESCRIPTION:
UNT 041 IN BOCR 22.0
END DESCRIPTION:
XS GIS Cut Line= 3
      3757000.36     10597463.65      3756965.63     10597207.54
      3756579.34     10596899.38
#Sta/Elev= 30
  4645.8   322.1  4686.6  321.09  4691.7   322.4  4759.1  319.74  4764.2  320.29
  4820.9  317.13  4836.7  315.04  4841.8     316  4861.2  314.97  4900.4  311.54
  4904.3  311.54  4906.8  312.85  4913.2  311.55  4921.2  311.98  4935.6  310.39
  4956.4  301.45  4970.8   302.3  4977.2   301.2  4985.3  301.85  5011.1  297.53
  5013.8  297.03  5017.1  297.53  5020.5  301.56  5027.1  302.01  5055.7  301.75
  5113.4  304.29  5183.8  305.39  5305.5  305.73    5376  308.79  5398.4  310.92
#Mann= 3 ,-1 , 0
  4645.8     .16       0  5011.1     .07       0  5017.1     .16       0
Bank Sta=5011.1,5017.1
XS Rating Curve= 0 ,0
Exp/Cntr=0.3,0.1

Type RM Length L Ch R = 1 ,11639   ,682,682,682
BEGIN DESCRIPTION:
UNT 041 IN BOCR 21.0
END DESCRIPTION:
XS GIS Cut Line= 3
      3757263.85     10596940.24      3756951.37     10596879.48
      3756649.69     10596699.34
#Sta/Elev= 30
  4811.9  309.58  4826.4  309.66  4867.2  306.56  4897.7  303.02  4958.8  300.22
  4979.2  300.92  4997.1   294.8  4999.9   294.3  5003.1   294.8  5009.8  298.67
    5020  300.65  5060.7  299.69  5098.3  301.39  5103.4  300.24  5111.7  300.52
  5134.2  302.59  5138.4  306.62  5144.2  303.65  5175.3  304.61  5181.2  302.97
  5239.5  299.93  5276.5  300.36  5350.5  305.95  5371.9  310.59  5393.3  311.68
  5408.8  314.59  5414.3  314.08  5430.2  316.74  5451.6  316.38  5481.6  318.28
#Mann= 4 ,-1 , 0
  4811.9     .16       0  4997.1     .07       0  5003.1     .16       0
  5414.3     .05       0
Bank Sta=4997.1,5003.1
XS Rating Curve= 0 ,0
Exp/Cntr=0.3,0.1

Type RM Length L Ch R = 1 ,10957   ,806,806,806
BEGIN DESCRIPTION:
UNT 041 IN BOCR 20.0
END DESCRIPTION:
XS GIS Cut Line= 3
      3757343.27     10596691.08      3757121.88     10596521.78
       3756787.7     10596365.54
#Sta/Elev= 30
  4660.6   319.6  4670.9  318.87  4677.8  317.21  4710.4  312.67  4735.3  308.12
  4764.3   305.1  4849.6  298.49  4884.9  297.25  4979.5  297.57    4986  296.41
  5002.3  295.53    5005  294.62  5007.8  294.12    5011  294.62  5019.1  296.28
  5025.1  298.96    5048  306.01  5063.2  306.81  5093.7   310.2  5099.2  309.97
  5107.4  311.61  5116.5  312.33    5122  311.91  5129.5  313.42  5162.2  315.99
  5173.6   316.1  5184.7  317.46  5213.4  319.09  5218.9  318.45  5308.2  324.67
#Mann= 4 ,-1 , 0
  4660.6     .05       0  4710.4     .16       0    5005     .07       0
    5011     .16       0
Bank Sta=5005,5011
XS Rating Curve= 0 ,0
Exp/Cntr=0.3,0.1

Type RM Length L Ch R = 1 ,10151   ,339,339,339
BEGIN DESCRIPTION:
UNT 041 IN BOCR 19.0
END DESCRIPTION:
XS GIS Cut Line= 3
      3757499.62     10596360.24      3757449.61     10596160.19
      3757299.61     10595960.19
#Sta/Elev= 30
  4827.4  308.72    4830  308.72  4858.4  304.06  4886.7  301.44  4899.6  299.37
  4969.2  294.53  4974.3  295.16  4982.1  292.59  4989.4  288.09  4992.1  287.59
  4995.4  288.09  5002.7  289.02  5010.4  290.99  5015.6  289.37  5023.3  293.74
  5097.1  294.97  5126.3  296.34  5147.1   298.4  5155.5  298.02  5176.3  298.89
  5190.9  300.86  5205.5   301.7  5220.1  307.52  5226.3  308.84  5234.4  312.67
  5240.9     316  5247.1  318.13  5255.5  318.01  5261.7  316.06  5283.6  316.39
#Mann= 4 ,-1 , 0
  4827.4     .05       0  4989.4     .07       0  4995.4     .05       0
  5234.4     .05       0
Bank Sta=4989.4,4995.4
XS Rating Curve= 0 ,0
Exp/Cntr=0.3,0.1

Type RM Length L Ch R = 1 ,9812    ,246,246,246
BEGIN DESCRIPTION:
UNT 041 IN BOCR 18.0
END DESCRIPTION:
XS GIS Cut Line= 3
      3757887.58     10596629.97      3757762.57     10596116.03
      3757498.69     10595699.39
#Sta/Elev= 30
  4388.9  315.82  4409.3  319.43  4450.4  321.43  4553.3  321.97  4707.7  309.65
  4728.3  309.27  4741.8  307.01  4825.3   300.3  4946.9  292.89  4968.1  293.41
  4983.4  290.67  4989.3  284.43  4992.3  284.28  4992.8  284.26  4995.5  283.76
  4998.8  284.26  5004.6  286.22  5010.5  291.09  5025.7  289.97  5031.7  292.42
  5090.5  297.77    5141   306.3  5156.3  307.06  5162.2   309.3  5192.7  311.04
    5208   312.7  5213.9  314.46  5265.6  318.42  5297.1   322.6    5411   330.7
#Mann= 5 ,-1 , 0
  4388.9     .05       0  4992.3     .16       0  4992.8     .07       0
  4998.8     .16       0  5297.1     .05       0
Bank Sta=4992.8,4998.8
XS Rating Curve= 0 ,0
Exp/Cntr=0.3,0.1

Type RM Length L Ch R = 1 ,9566    ,297,297,297
BEGIN DESCRIPTION:
Mapping XS ccb355db
END DESCRIPTION:
XS GIS Cut Line= 3
      3758102.32     10596313.79      3757873.14     10595902.31
       3757574.1     10595598.07
#Sta/Elev= 30
  4588.9  303.52  4607.5  305.24  4623.5  304.23  4629.2  305.77  4682.9  303.63
  4688.6  304.92  4704.6  302.94  4732.1  303.85  4748.1  301.95  4753.8  303.46
  4776.2  303.06  4807.5  300.38  4813.2  301.48  4910.4  294.38  4975.6  292.02
  4991.6  286.97  4997.3  287.31  5002.1  283.41  5004.8  282.91  5008.1  283.41
  5013.3  289.52    5028  292.39    5036  291.94  5155.8  293.36  5226.6  301.64
    5276  311.95  5323.3  316.79  5382.1  320.29  5431.6  326.24  5486.5  329.98
#Mann= 5 ,-1 , 0
  4588.9     .05       0  5002.1     .03       0  5008.1     .05       0
    5036     .16       0  5323.3     .05       0
Bank Sta=5002.1,5008.1
XS Rating Curve= 0 ,0
Exp/Cntr=0.3,0.1

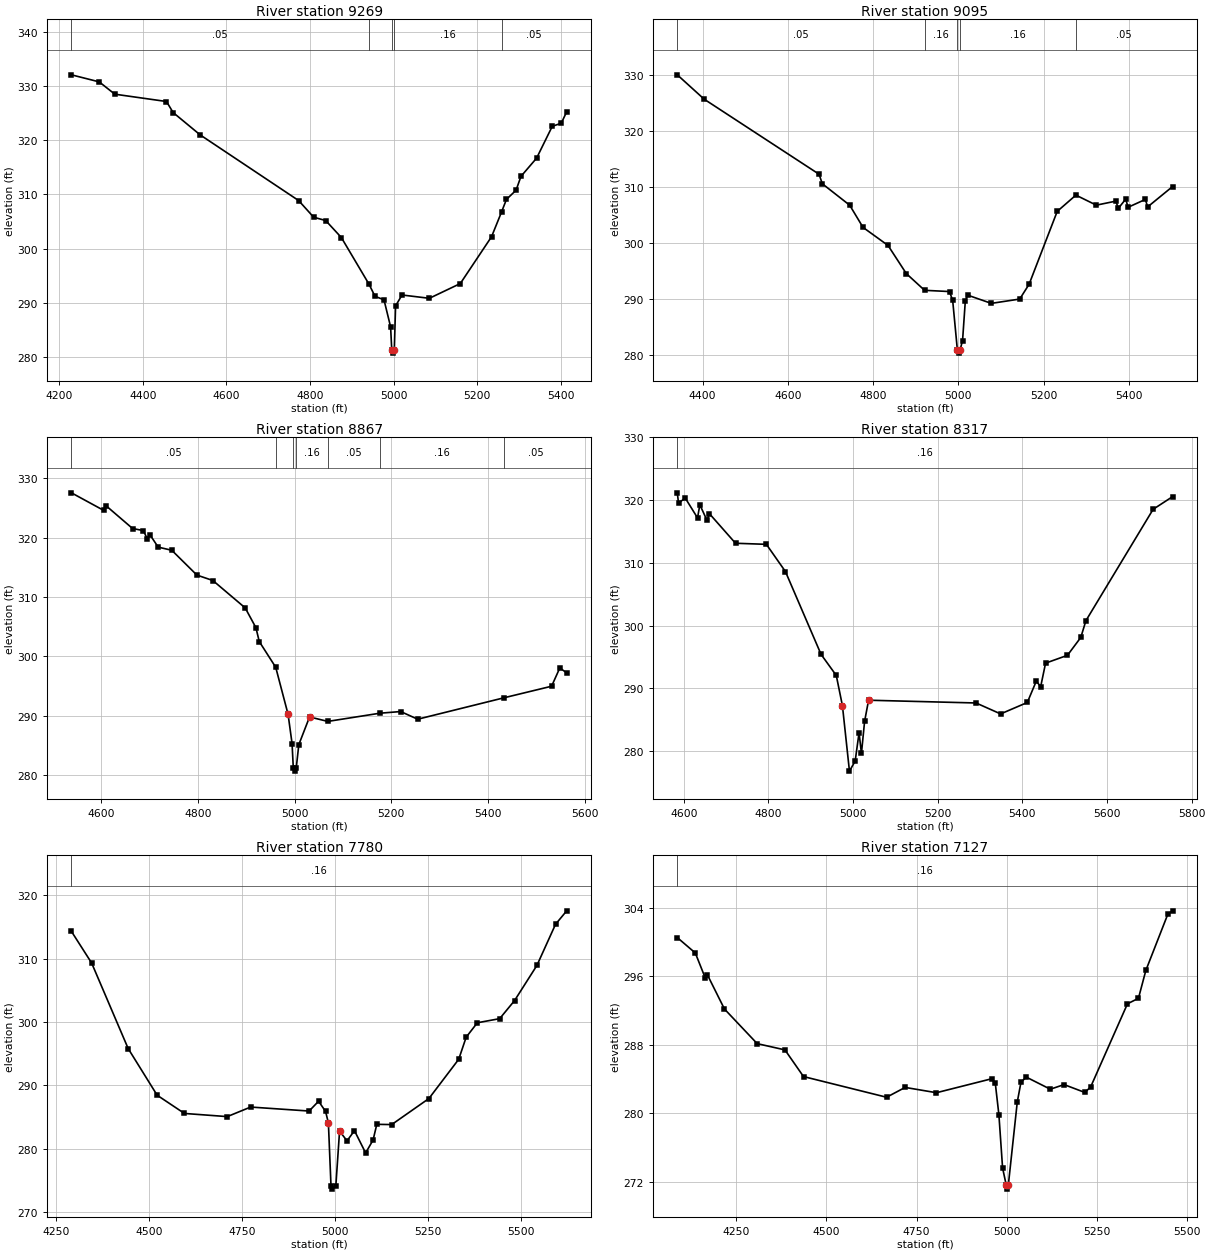
Type RM Length L Ch R = 1 ,9269    ,174,174,174
BEGIN DESCRIPTION:
UNT 041 IN BOCR 17.0
END DESCRIPTION:
XS GIS Cut Line= 2
      3758672.29     10596088.26      3757644.53     10595497.99
#Sta/Elev= 30
  4229.1  332.04  4295.6  330.74  4332.9  328.47  4456.6  327.12  4472.4  325.09
  4537.1  320.97  4772.9  308.85  4808.8  305.78  4837.6  305.17    4875  302.04
  4941.3  293.42  4955.5   291.2  4977.1  290.55  4992.9  285.56  4995.7  281.22
  4998.4  280.72  5001.7  281.22  5004.8  289.43  5020.2  291.44  5085.6  290.83
  5159.7  293.55  5234.5  302.19  5258.7  306.81  5270.1  309.07  5293.1  310.76
  5304.9  313.32  5342.3  316.68  5379.7  322.54  5401.3  323.12  5414.3  325.23
#Mann= 5 ,-1 , 0
  4229.1     .05       0  4941.3     .16       0  4995.7     .07       0
  5001.7     .16       0  5258.7     .05       0
Bank Sta=4995.7,5001.7
XS Rating Curve= 0 ,0
Exp/Cntr=0.3,0.1

Type RM Length L Ch R = 1 ,9095    ,228,228,228
BEGIN DESCRIPTION:
Mapping XS 0ef695b5
END DESCRIPTION:
XS GIS Cut Line= 3
      3758636.14     10595878.86      3758026.79      10595519.5
      3757613.67     10595329.83
#Sta/Elev= 30
  4340.7  330.02  4403.8  325.67  4673.3  312.28  4680.9  310.58  4745.2  306.75
  4776.5  302.79  4835.1  299.57    4878  294.55  4920.9  291.56  4979.4  291.34
  4986.8  289.75  4997.9  280.85  5000.6  280.35  5003.9  280.85    5010   282.6
  5016.5  289.72  5022.3  290.69  5077.5  289.23  5144.1     290  5166.1  292.64
  5232.1  305.65  5275.9  308.55  5323.8  306.76  5369.8  307.48  5375.3  306.18
  5392.8  307.84  5398.3  306.38  5438.8  307.78  5444.3  306.45  5502.7  310.08
#Mann= 5 ,-1 , 0
  4340.7     .05       0  4920.9     .16       0  4997.9     .07       0
  5003.9     .16       0  5275.9     .05       0
Bank Sta=4997.9,5003.9
XS Rating Curve= 0 ,0
Exp/Cntr=0.3,0.1

Type RM Length L Ch R = 1 ,8867    ,550,550,550
BEGIN DESCRIPTION:
UNT 041 IN BOCR 16.0
END DESCRIPTION:
XS GIS Cut Line= 2
      3758623.66     10595574.36      3757700.03     10595129.91
#Sta/Elev= 30
    4538  327.53  4604.4  324.59  4609.9  325.34  4664.6  321.52  4686.8  321.18
  4694.9   319.8  4700.5  320.47  4717.5  318.39  4745.7  317.86  4797.7  313.68
  4830.7  312.77  4897.6  308.16  4919.8  304.83  4926.7   302.5  4960.8  298.16
  4986.4  290.23  4994.6  285.33  4997.2  281.18  4999.9  280.68  5003.2  281.18
  5008.6  285.14  5030.8   289.8  5068.6  289.05  5176.4  290.43  5219.4  290.71
  5254.6  289.42  5433.4  293.03  5531.7  294.97  5548.8  298.06    5563  297.21
#Mann= 7 ,-1 , 0
    4538     .05       0  4960.8     .16       0  4997.2     .07       0
  5003.2     .16       0  5068.6     .05       0  5176.4     .16       0
  5433.4     .05       0
Bank Sta=4986.4,5030.8
XS Rating Curve= 0 ,0
Exp/Cntr=0.3,0.1

Type RM Length L Ch R = 1 ,8317    ,537,537,537
BEGIN DESCRIPTION:
UNT 041 IN BOCR 15.0
END DESCRIPTION:
XS GIS Cut Line= 3
      3758686.18     10595477.14      3758443.12     10594984.09
      3757853.68     10594789.92
#Sta/Elev= 30
  4584.6  321.15  4587.5  319.53  4603.5  320.31  4632.4  317.16  4637.9  319.25
  4654.8  316.76  4660.4  317.84  4722.2  313.12  4795.1  312.95  4840.1  308.62
  4924.3  295.43  4960.3  292.07  4974.8  287.26  4991.4  276.84  5004.9  278.44
  5014.1  282.96  5019.7  279.65  5027.2  284.77  5036.6  288.13  5290.6  287.69
  5348.6  285.95  5411.7  287.77  5432.8  291.16  5443.3   290.3  5454.8  294.03
  5506.5  295.28  5538.1  298.13  5550.1  300.79    5709  318.53  5754.9  320.54
#Mann= 1 ,-1 , 0
  4584.6     .16       0
Bank Sta=4974.8,5036.6
XS Rating Curve= 0 ,0
Exp/Cntr=0.3,0.1

Type RM Length L Ch R = 1 ,7780    ,653,653,653
BEGIN DESCRIPTION:
UNT 041 IN BOCR 14.0
END DESCRIPTION:
XS GIS Cut Line= 3
      3759199.64      10594960.2      3758549.61     10594760.19
      3757899.62     10594760.19
#Sta/Elev= 30
    4292  314.31  4346.3  309.31  4444.4  295.79  4522.2  288.42  4595.5  285.54
  4710.5  285.04  4773.3  286.55  4930.3  285.92  4955.8  287.47  4974.6  285.85
  4982.1  284.03  4989.1  274.08  4991.9  273.58  5002.1  274.11  5012.1  282.75
  5032.1  281.21  5052.1  282.82  5082.1   279.3  5102.1  281.34  5112.1  283.82
  5152.1  283.78  5252.1   287.9  5332.1   294.1  5352.1  297.59  5382.1  299.87
  5442.1  300.52  5482.1  303.38  5542.1  308.93  5592.1  315.43  5622.1  317.56
#Mann= 1 ,-1 , 0
    4292     .16       0
Bank Sta=4982.1,5012.1
XS Rating Curve= 0 ,0
Exp/Cntr=0.3,0.1

Type RM Length L Ch R = 1 ,7127    ,400,400,400
BEGIN DESCRIPTION:
UNT 041 IN BOCR 13.0
END DESCRIPTION:
XS GIS Cut Line= 3
      3759404.89     10594568.66      3758584.56      10594325.6
      3758076.75     10594230.11
#Sta/Elev= 30
  4086.9  300.54  4136.8  298.74  4164.9  295.76  4170.1   296.2  4217.6  292.18
  4308.3  288.13  4385.2   287.4  4436.6  284.28  4666.8  281.86  4718.2  283.01
    4805  282.39  4957.7  284.02  4967.9  283.54    4978  279.81  4988.2  273.59
  4998.2  271.61  5000.9  271.11  5004.2  271.61  5028.9   281.3  5039.1   283.6
  5053.7  284.22  5120.5   282.8  5158.6  283.34  5216.2  282.42  5232.4  283.08
  5334.2  292.79  5364.7  293.44  5385.1  296.69  5446.1  303.28  5459.2  303.67
#Mann= 1 ,-1 , 0
  4086.9     .16       0
Bank Sta=4998.2,5004.2
XS Rating Curve= 0 ,0
Exp/Cntr=0.3,0.1

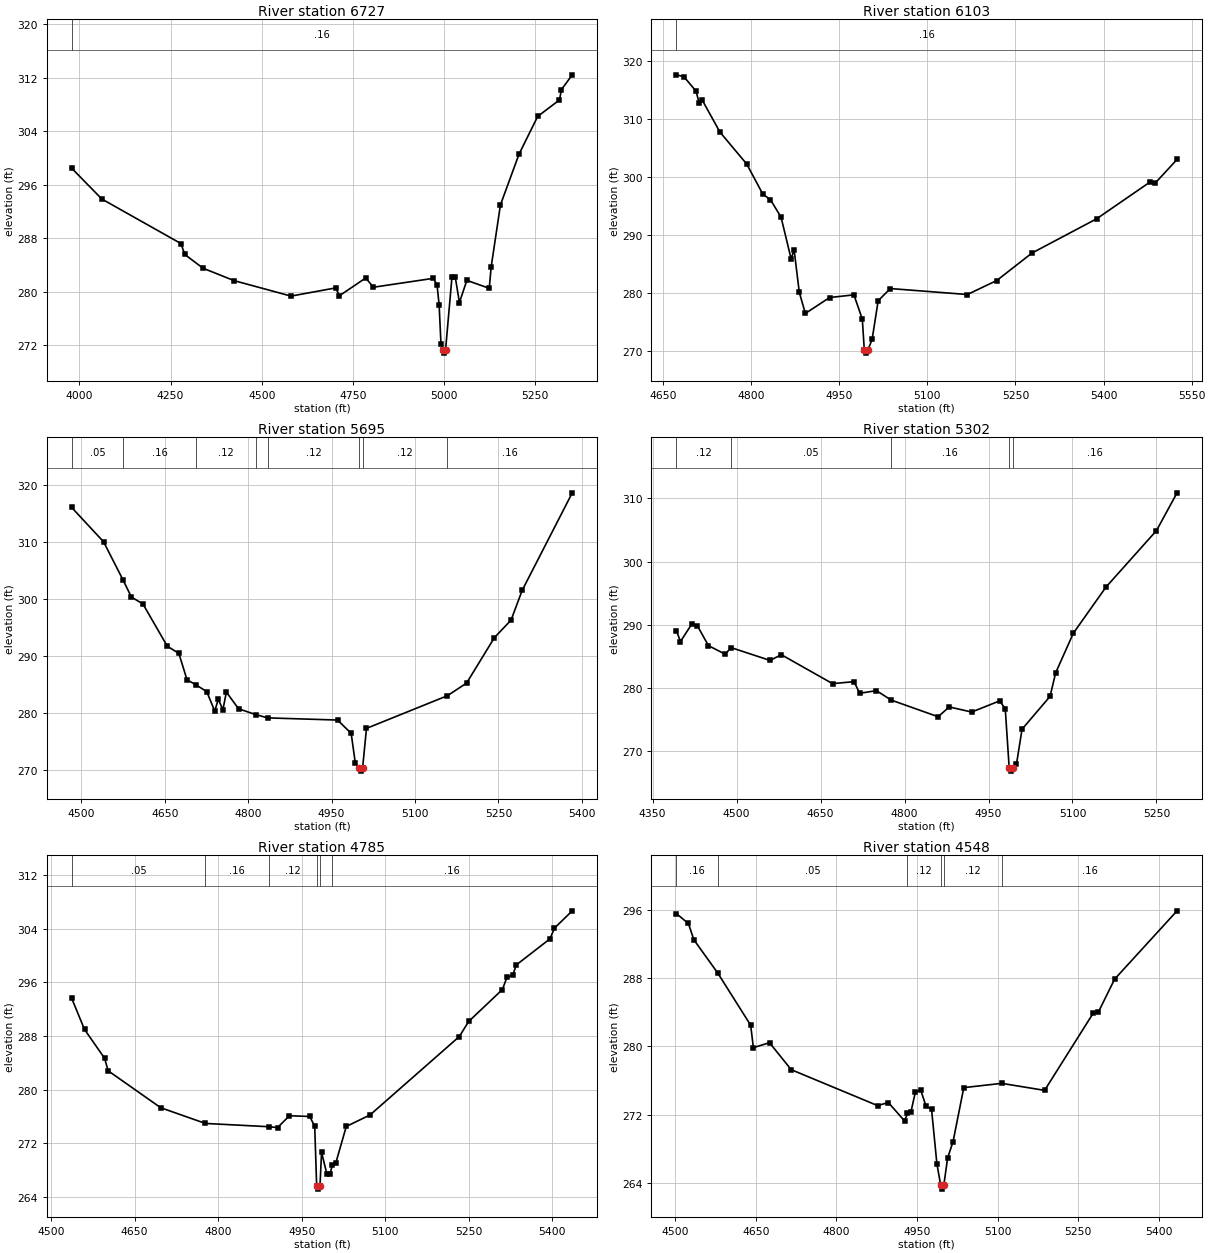
Type RM Length L Ch R = 1 ,6727    ,624,624,624
BEGIN DESCRIPTION:
UNT 041 IN BOCR 12.0
END DESCRIPTION:
XS GIS Cut Line= 3
      3759539.41     10594208.41      3758671.36     10593978.38
      3758206.97     10593878.56
#Sta/Elev= 30
  3978.8  298.47  4061.4  293.87  4278.6  287.21  4288.9  285.59  4339.1  283.53
  4424.7  281.67  4580.4  279.37  4702.8  280.59  4713.1  279.42  4785.5  282.08
  4806.1  280.69  4970.7  282.02  4980.9  281.02  4986.6  278.08  4991.7  272.22
  4998.3  271.35  5001.1  270.85  5004.3  271.35  5021.8  282.19  5030.8  282.24
  5042.3  278.41  5062.7  281.72  5124.1  280.53  5129.5  283.78  5154.8  292.99
  5205.9  300.58    5257  306.21  5316.8  308.67  5321.9   310.2  5351.8  312.42
#Mann= 1 ,-1 , 0
  3978.8     .16       0
Bank Sta=4998.3,5004.3
XS Rating Curve= 0 ,0
Exp/Cntr=0.3,0.1

Type RM Length L Ch R = 1 ,6103    ,408,408,408
BEGIN DESCRIPTION:
UNT 041 IN BOCR 11.0
END DESCRIPTION:
XS GIS Cut Line= 3
      3759111.85       10593615.      3758723.85     10593513.44
      3758272.69     10593521.22
#Sta/Elev= 30
  4672.9  317.66  4685.6  317.33  4706.2  314.83  4711.5  312.79  4716.7   313.3
  4746.8  307.77  4792.4  302.25  4819.9  297.04  4832.8  296.08  4850.9  293.07
    4868  285.88  4873.2  287.38    4882  280.06  4892.3  276.42  4933.6  279.17
    4975  279.63  4989.3  275.43  4992.7  270.06  4995.4  269.56  4998.7  270.06
    5006  271.95  5016.3  278.62    5037  280.72  5168.2  279.69  5218.2  282.11
  5278.2  286.86  5388.3  292.78  5478.3  299.07  5488.3  298.98  5525.2  303.04
#Mann= 1 ,-1 , 0
  4672.9     .16       0
Bank Sta=4992.7,4998.7
XS Rating Curve= 0 ,0
Exp/Cntr=0.3,0.1

Type RM Length L Ch R = 1 ,5695    ,393,393,393
BEGIN DESCRIPTION:
UNT 041 IN BOCR 10.0
END DESCRIPTION:
XS GIS Cut Line= 3
      3759099.59     10593510.17      3758699.61     10593210.19
      3758299.59     10593210.19
#Sta/Elev= 30
  4482.7  315.99    4540  309.98    4575  303.29    4590   300.3  4610.8  299.08
  4654.6  291.68  4675.4  290.42    4690   285.8  4705.7  284.94  4725.4  283.73
    4740  280.31  4746.2   282.4  4754.6  280.56  4760.8  283.64  4782.7  280.72
  4813.7  279.69  4835.3  279.12  4960.8  278.74  4985.2  276.41  4992.7  271.15
  4999.7  270.29  5002.4  269.79  5005.7  270.29  5012.7  277.28  5158.1     283
  5192.7  285.22  5242.7  293.18  5272.7  296.26  5292.7  301.48  5382.7  318.56
#Mann= 8 ,-1 , 0
  4482.7     .05       0    4575     .16       0  4705.7     .12       0
  4813.7     .16       0  4835.3     .12       0  4999.7     .07       0
  5005.7     .12       0  5158.1     .16       0
Bank Sta=4999.7,5005.7
XS Rating Curve= 0 ,0
Exp/Cntr=0.3,0.1

Type RM Length L Ch R = 1 ,5302    ,517,517,517
BEGIN DESCRIPTION:
UNT 041 IN BOCR 9.0
END DESCRIPTION:
XS GIS Cut Line= 2
      3759116.74     10592921.59      3758222.78      10592900.8
#Sta/Elev= 30
  4392.6  289.03  4399.7  287.33  4419.7  290.07  4429.7  289.86  4449.7  286.68
  4479.8  285.32  4489.8  286.38  4559.8  284.34  4579.8  285.25  4671.4  280.67
  4709.8  280.98  4719.8  279.14  4749.8  279.56    4776  278.07  4859.9  275.43
  4879.9  276.98  4919.9  276.17  4969.9  277.94  4979.9  276.69  4986.9  267.32
  4989.6  266.82  4992.9  267.32  4999.9   267.9  5009.9  273.46  5059.9  278.65
  5069.9  282.37  5101.5  288.65  5159.9  295.96    5250  304.89  5286.8  310.87
#Mann= 5 ,-1 , 0
  4392.6     .12       0  4489.8     .05       0    4776     .16       0
  4986.9     .07       0  4992.9     .16       0
Bank Sta=4986.9,4992.9
XS Rating Curve= 0 ,0
Exp/Cntr=0.3,0.1

Type RM Length L Ch R = 1 ,4785    ,237,237,237
BEGIN DESCRIPTION:
UNT 041 IN BOCR 8.0
END DESCRIPTION:
XS GIS Cut Line= 3
      3758949.65     10592710.21      3758549.61     10592460.19
      3758149.65     10592610.17
#Sta/Elev= 30
    4537  293.62    4560  288.98    4596  284.68  4602.5   282.8  4696.8  277.29
  4777.1  274.94    4891  274.45  4906.7  274.32    4928  276.09  4964.5  275.98
  4973.4   274.5  4976.9  265.63  4979.6  265.13  4982.9  265.63  4985.7  270.63
  4995.2  267.41  5001.1  267.38  5004.9  268.75  5011.4  269.07  5030.1  274.49
  5072.8  276.21    5233  287.91  5249.9  290.17  5310.5  294.94  5318.5  296.74
  5329.1  297.08  5335.4  298.61  5395.9  302.51  5403.9   304.1  5435.9  306.69
#Mann= 6 ,-1 , 0
    4537     .05       0  4777.1     .16       0    4891     .12       0
  4976.9     .07       0  4982.9     .12       0  5004.9     .16       0
Bank Sta=4976.9,4982.9
XS Rating Curve= 0 ,0
Exp/Cntr=0.3,0.1

Type RM Length L Ch R = 1 ,4548    ,275,275,275
BEGIN DESCRIPTION:
Mapping XS 9d6940f4
END DESCRIPTION:
XS GIS Cut Line= 3
      3759161.65     10592239.34      3758823.06     10592278.41
      3758233.69     10592321.74
#Sta/Elev= 30
  4502.4  295.51  4524.6  294.37  4534.7  292.47    4579   288.6  4640.5  282.48
  4645.5  279.86  4675.6  280.44  4715.9  277.29  4876.8  273.09  4896.8  273.45
  4926.9   271.3  4932.4  272.18  4938.8  272.34    4947  274.67    4957  274.91
    4967  272.99  4977.1   272.7  4987.1  266.31  4994.1  263.83  4996.9  263.33
  5000.1  263.83  5007.1  266.97  5017.2  268.88  5037.2  275.19  5107.8  275.69
  5187.6  274.87  5277.9  283.87  5287.9  284.04    5318  287.87  5434.2  295.85
#Mann= 6 ,-1 , 0
  4502.4     .16       0    4579     .05       0  4932.4     .12       0
  4994.1     .07       0  5000.1     .12       0  5107.8     .16       0
Bank Sta=4994.1,5000.1
XS Rating Curve= 0 ,0
Exp/Cntr=0.3,0.1

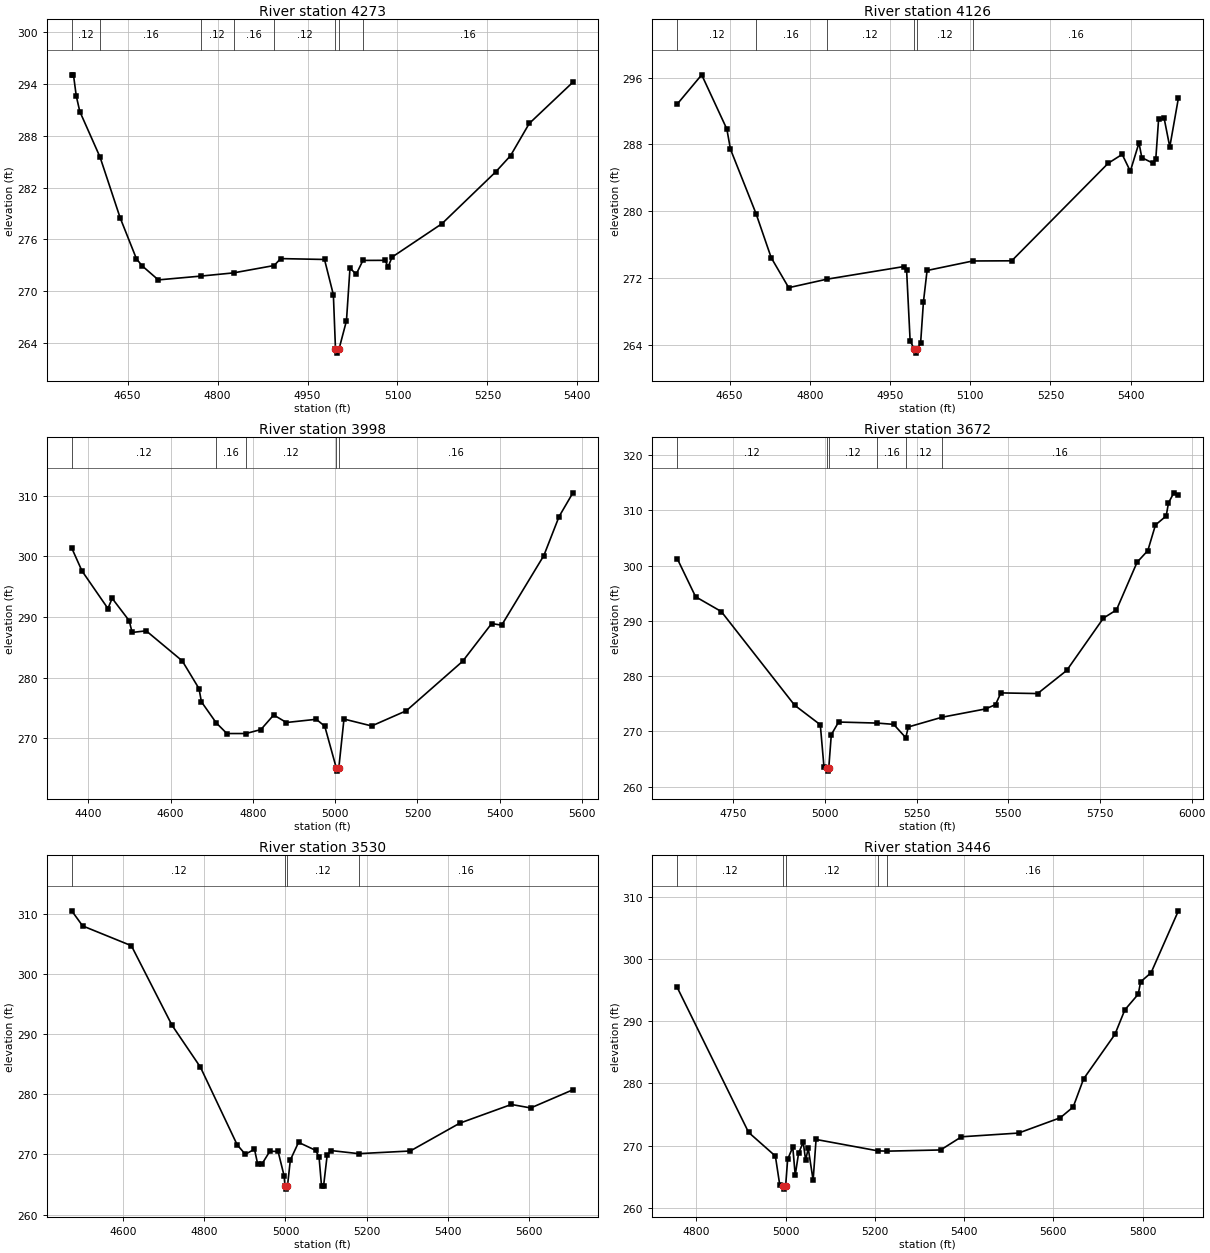
Type RM Length L Ch R = 1 ,4273    ,147,147,147
BEGIN DESCRIPTION:
UNT 041 IN BOCR 7.0
END DESCRIPTION:
XS GIS Cut Line= 3
      3758949.57     10591810.21      3758549.61     10592060.19
      3758199.57      10592160.2
#Sta/Elev= 30
  4556.8  295.02  4559.7  295.02  4564.4  292.56  4570.3  290.78  4604.1   285.5
  4637.5  278.51  4664.7  273.77  4674.1  272.96  4701.2  271.33  4772.2  271.77
  4826.6  272.14  4894.3  272.99  4905.2  273.79  4978.3  273.69  4993.1  269.61
  4996.6  263.37  4999.3  262.87  5002.6  263.37  5014.9   266.6  5020.8   272.7
  5031.1  271.98  5042.4  273.58  5079.2  273.59  5084.4  272.84  5090.9  273.96
  5174.1  277.82  5263.8  283.81  5288.5  285.68  5319.7   289.4  5392.5  294.17
#Mann= 8 ,-1 , 0
  4556.8     .12       0  4604.1     .16       0  4772.2     .12       0
  4826.6     .16       0  4894.3     .12       0  4996.6     .07       0
  5002.6     .12       0  5042.4     .16       0
Bank Sta=4996.6,5002.6
XS Rating Curve= 0 ,0
Exp/Cntr=0.3,0.1

Type RM Length L Ch R = 1 ,4126    ,128,128,128
BEGIN DESCRIPTION:
Mapping XS 90a00db4
END DESCRIPTION:
XS GIS Cut Line= 3
        3759001.      10591748.9      3758649.45      10591900.8
      3758124.44      10592078.7
#Sta/Elev= 30
    4552  292.83  4597.8  296.34  4644.8  289.85  4651.6  287.43  4699.5   279.7
  4727.8  274.43  4760.5  270.84  4831.3  271.85  4975.8  273.37    4981  272.96
  4987.6  264.49  4995.1   263.5  4997.9     263  5001.1   263.5  5007.2  264.19
  5012.5  269.14  5019.3   272.9  5104.8  274.04  5177.6  274.06  5358.1  285.75
  5384.2  286.81  5399.4  284.79  5415.6  288.19  5420.9  286.42  5441.6  285.76
    5447  286.23  5452.3  291.02  5462.7  291.12  5473.2   287.7  5489.3  293.54
#Mann= 6 ,-1 , 0
    4552     .12       0  4699.5     .16       0  4831.3     .12       0
  4995.1     .07       0  5001.1     .12       0  5104.8     .16       0
Bank Sta=4995.1,5001.1
XS Rating Curve= 0 ,0
Exp/Cntr=0.3,0.1

Type RM Length L Ch R = 1 ,3998    ,326,326,326
BEGIN DESCRIPTION:
Mapping XS 90886db0
END DESCRIPTION:
XS GIS Cut Line= 4
      3759124.83     10591667.97      3758671.27     10591785.16
      3758428.21     10591850.26      3757955.13     10592006.51
#Sta/Elev= 30
  4359.5   301.4  4384.4  297.62  4447.5  291.42  4457.8   293.1  4499.2  289.41
  4506.3  287.47  4540.5  287.74  4628.2  282.78  4668.9  278.21  4674.7  276.04
    4711  272.54  4736.7   270.8  4782.7   270.8  4819.3  271.45  4850.4  273.86
  4881.4  272.62  4953.9  273.15  4974.6  272.01  5002.7   265.1  5005.4   264.6
  5008.7   265.1  5021.3  273.19  5088.6  272.05  5172.9  274.56  5309.8  282.72
  5380.3  288.94  5404.6  288.67  5507.2  300.16  5544.2  306.59  5577.8   310.5
#Mann= 5 ,-1 , 0
  4359.5     .12       0    4711     .16       0  4782.7     .12       0
  5002.7     .07       0  5008.7     .16       0
Bank Sta=5002.7,5008.7
XS Rating Curve= 0 ,0
Exp/Cntr=0.3,0.1

Type RM Length L Ch R = 1 ,3672    ,142,142,142
BEGIN DESCRIPTION:
UNT 041 IN BOCR 6.0
END DESCRIPTION:
XS GIS Cut Line= 3
      3759109.78     10591629.92      3758373.68     10591609.09
       3757866.7     10591984.11
#Sta/Elev= 30
  4596.9  301.28  4647.1  294.37  4717.1   291.7  4917.2  274.75  4987.2  271.22
  4997.2   263.6  5004.2  263.33    5007  262.83  5010.2  263.33  5017.2  269.43
  5037.2  271.71  5142.7  271.52  5187.3  271.29  5220.3  268.88  5227.3  270.82
  5319.2  272.58  5437.9  274.08  5465.1  274.86  5479.7  276.98  5579.9  276.86
  5659.3  281.04  5759.5  290.51    5795  291.99  5851.3  300.62  5880.5  302.72
  5901.4  307.36  5930.6  308.98  5936.9  311.35  5951.5  313.17  5963.9  312.74
#Mann= 6 ,-1 , 0
  4596.9     .12       0  5004.2     .07       0  5010.2     .12       0
  5142.7     .16       0  5220.3     .12       0  5319.2     .16       0
Bank Sta=5004.2,5010.2
XS Rating Curve= 0 ,0
Exp/Cntr=0.3,0.1

Type RM Length L Ch R = 1 ,3530    ,84,84,84
BEGIN DESCRIPTION:
Mapping XS 232367c7
END DESCRIPTION:
XS GIS Cut Line= 4
      3759196.49     10591522.57      3758840.54     10591507.38
      3758582.29     10591472.66      3757965.95     10591422.74
#Sta/Elev= 30
  4473.2   310.5  4500.1  307.99  4620.2   304.7  4720.3  291.48  4790.4   284.5
  4880.9   271.6    4901  270.01  4923.6  270.86  4931.3  268.45  4941.4  268.33
  4961.6  270.53  4981.8  270.48  4996.5  266.47  4998.9  264.72  5001.7  264.22
  5004.9  264.72    5012  269.06  5032.2     272  5074.3  270.67  5082.7  269.59
  5088.9  264.73  5093.9  264.73  5102.8   269.9  5112.8  270.63  5180.4  270.12
  5307.5  270.56  5429.6  275.19  5556.7   278.3  5604.4  277.72  5708.4  280.74
#Mann= 4 ,-1 , 0
  4473.2     .12       0  4998.9     .07       0  5004.9     .12       0
  5180.4     .16       0
Bank Sta=4998.9,5004.9
XS Rating Curve= 0 ,0
Exp/Cntr=0.3,0.1

Type RM Length L Ch R = 1 ,3446    ,488,488,488
BEGIN DESCRIPTION:
UNT 041 IN BOCR 5.0
END DESCRIPTION:
XS GIS Cut Line= 3
      3758949.64     10591410.19      3758699.61     10591410.19
      3757899.64      10591060.2
#Sta/Elev= 30
  4757.2  295.44  4917.2  272.12  4977.2  268.31  4987.2  263.58  4994.2  263.49
    4997  262.99  5000.2  263.49  5004.7  267.77  5016.2  269.76  5021.7  265.22
  5029.1  268.74  5039.6  270.54    5045  267.64  5050.9  269.56  5061.8   264.4
  5068.4  270.98  5206.7  269.15  5227.6   269.1  5347.5  269.29  5394.3  271.41
  5522.2  272.01  5615.7  274.47  5644.6   276.2    5668  280.73  5738.2  287.89
  5760.4  291.83  5790.4  294.35  5795.8  296.34  5819.2   297.8  5880.4  307.76
#Mann= 5 ,-1 , 0
  4757.2     .12       0  4994.2     .07       0  5000.2     .12       0
  5206.7      .1       0  5227.6     .16       0
Bank Sta=4994.2,5000.2
XS Rating Curve= 0 ,0
Exp/Cntr=0.3,0.1

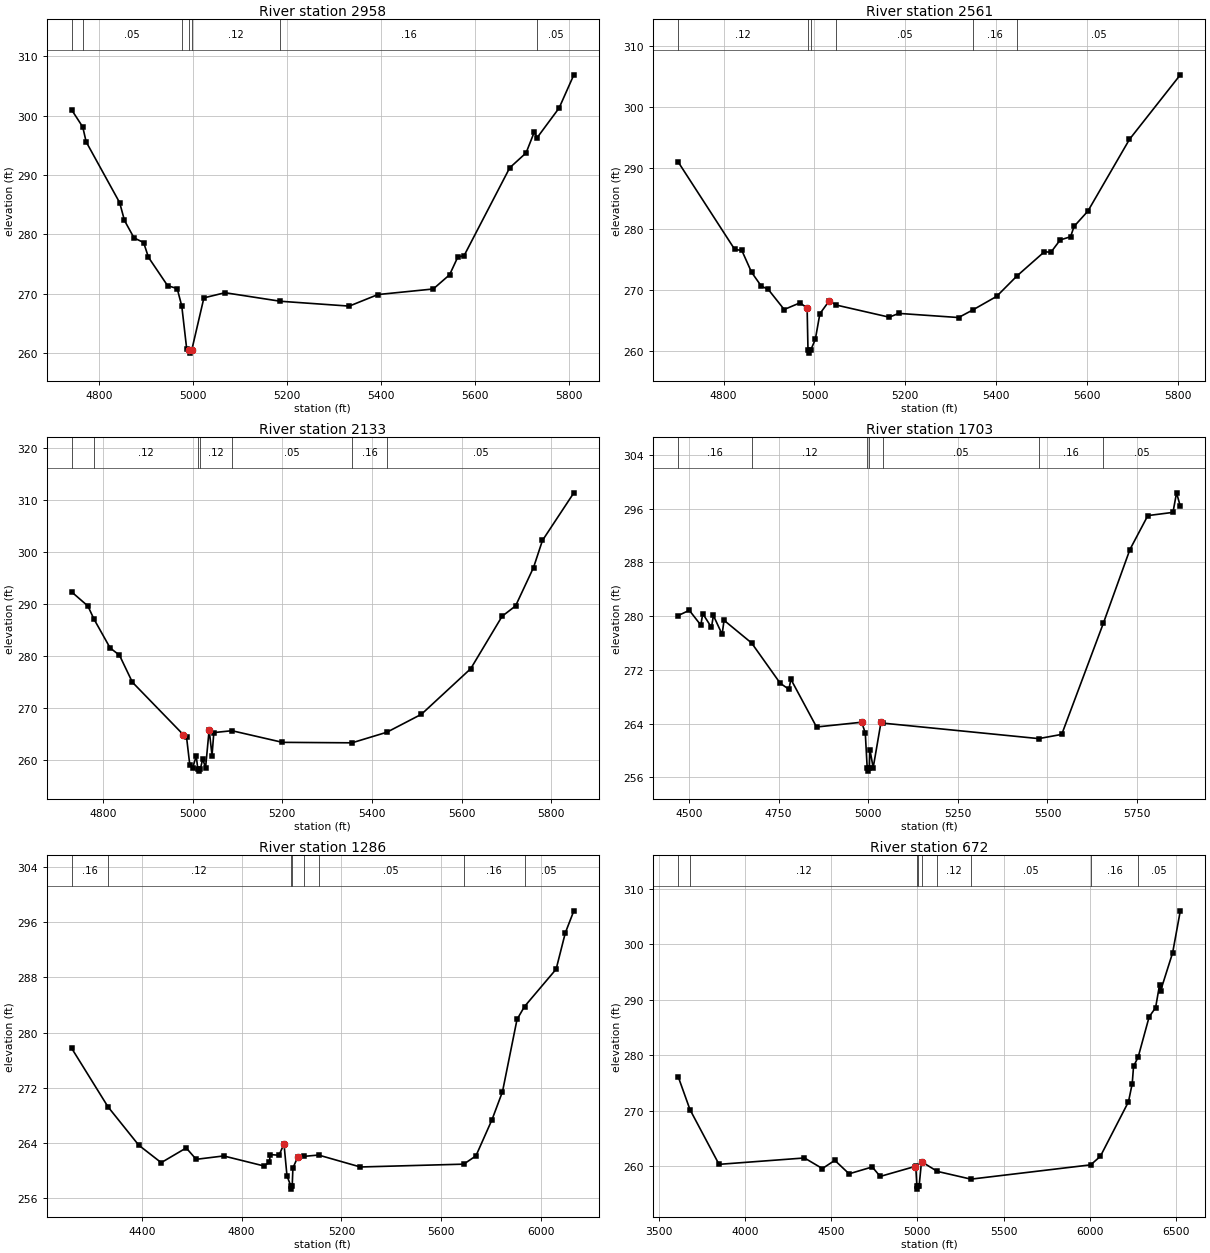
Type RM Length L Ch R = 1 ,2958    ,397,397,397
BEGIN DESCRIPTION:
UNT 041 IN BOCR 4.0
END DESCRIPTION:
XS GIS Cut Line= 3
      3758999.64     10591210.19      3758749.61     10591160.19
      3757949.63     10591010.19
#Sta/Elev= 30
  4742.1  300.96  4765.5   298.1  4772.7   295.6  4844.1  285.33  4854.3  282.33
  4874.7  279.39  4895.1  278.61  4905.3  276.13  4946.1  271.34  4966.5  270.85
  4976.3   267.9  4986.9  260.58  4991.5  260.46  4994.3  259.96  4997.5  260.46
  5023.4  269.28  5068.3  270.15  5186.1  268.71  5332.8  267.89  5393.9  269.84
  5511.7  270.78  5546.5  273.18  5564.3  276.23    5577  276.35  5674.5  291.22
  5709.3  293.73  5727.1  297.32  5732.5  296.26  5779.6   301.3    5811   306.9
#Mann= 7 ,-1 , 0
  4742.1     .12       0  4765.5     .05       0  4976.3     .12       0
  4991.5     .07       0  4997.5     .12       0  5186.1     .16       0
  5732.5     .05       0
Bank Sta=4991.5,4997.5
XS Rating Curve= 0 ,0
Exp/Cntr=0.3,0.1

Type RM Length L Ch R = 1 ,2561    ,428,428,428
BEGIN DESCRIPTION:
UNT 041 IN BOCR 3.0
END DESCRIPTION:
XS GIS Cut Line= 3
      3758999.64     10590960.21      3758749.61     10590810.19
      3757949.63     10590960.18
#Sta/Elev= 30
    4700     291  4824.4  276.64    4840  276.48  4861.4   272.9  4882.7  270.63
  4898.3  270.06  4933.3  266.77  4968.3  267.87  4983.8     267  4985.7   260.1
  4988.4   259.6  4991.7   260.1  5001.8  261.85  5011.9  266.08  5032.3  268.17
    5048   267.5  5164.5  265.51  5185.7  266.13  5317.2  265.45  5348.7   266.7
  5401.1  268.93  5445.6  272.27  5506.2  276.26  5520.6  276.18    5541   278.2
  5563.9  278.73  5571.5  280.42    5602  282.94  5693.6  294.74  5805.5  305.34
#Mann= 6 ,-1 , 0
    4700     .12       0  4985.7     .07       0  4991.7     .12       0
    5048     .05       0  5348.7     .16       0  5445.6     .05       0
Bank Sta=4983.8,5032.3
XS Rating Curve= 0 ,0
Exp/Cntr=0.3,0.1

Type RM Length L Ch R = 1 ,2133    ,430,430,430
BEGIN DESCRIPTION:
UNT 041 IN BOCR 2.0
END DESCRIPTION:
XS GIS Cut Line= 3
      3759049.59     10590610.17      3758799.61     10590410.19
      3757999.64     10590410.19
#Sta/Elev= 30
  4730.3  292.31  4766.3  289.61  4779.7  287.12  4815.9  281.54  4836.7  280.15
  4865.5  274.95  4979.2  264.84  4986.4  264.34  4993.6  259.04    5000  258.47
    5008  260.73  5011.4  258.33  5014.2  257.83  5017.4  258.33  5022.4  260.18
  5028.8  258.48  5036.8  265.81  5043.2  260.83  5047.2  265.25  5087.7  265.61
  5200.4  263.37  5355.4  263.28  5433.3  265.32  5510.4  268.78  5620.4  277.56
  5690.4  287.65  5720.4  289.64  5760.4  297.02  5780.4  302.25  5850.4  311.41
#Mann= 7 ,-1 , 0
  4730.3     .16       0  4779.7     .12       0  5011.4     .07       0
  5017.4     .12       0  5087.7     .05       0  5355.4     .16       0
  5433.3     .05       0
Bank Sta=4979.2,5036.8
XS Rating Curve= 0 ,0
Exp/Cntr=0.3,0.1

Type RM Length L Ch R = 1 ,1703    ,417,417,417
BEGIN DESCRIPTION:
Mapping XS 6195937c
END DESCRIPTION:
XS GIS Cut Line= 4
      3759219.78     10590678.84      3759060.07      10590276.1
      3758803.13     10590158.04      3758119.11     10590185.82
#Sta/Elev= 30
  4469.9  280.09  4500.7  280.87  4532.9  278.67  4538.3  280.37  4562.6  278.33
    4568   280.1  4592.3  277.29  4597.7  279.38  4674.5  276.01  4754.4  270.01
  4778.7  269.11  4784.1  270.61  4855.7   263.5  4981.7  264.21  4991.7   262.6
    4997  257.43  4999.8  256.93    5003  257.43  5004.7  260.13  5013.7  257.43
  5035.7  264.26  5040.2  264.08  5475.6  261.77  5539.7   262.4  5655.9  278.96
  5729.9  289.92  5779.9  294.97    5850  295.45    5860  298.36  5870.5  296.36
#Mann= 7 ,-1 , 0
  4469.9     .16       0  4674.5     .12       0    4997     .07       0
    5003     .12       0  5040.2     .05       0  5475.6     .16       0
  5655.9     .05       0
Bank Sta=4981.7,5035.7
XS Rating Curve= 0 ,0
Exp/Cntr=0.3,0.1

Type RM Length L Ch R = 1 ,1286    ,614,614,614
BEGIN DESCRIPTION:
Mapping XS e29377bc
END DESCRIPTION:
XS GIS Cut Line= 4
      3759299.66     10590748.33      3759275.35     10589956.65
      3759049.66     10589873.32       3758098.3     10590102.48
#Sta/Elev= 30
  4119.9  277.69    4265  269.23  4388.2  263.67  4478.2  261.14  4578.3  263.27
  4618.3  261.62  4728.3  262.11  4888.4  260.67  4911.9  261.16  4914.5  262.31
  4950.2  262.21    4970  263.86    4982  259.22    4997   257.8  4999.8   257.3
    5003   257.8  5005.7  260.35  5024.7  261.92  5050.5  262.05  5108.4  262.24
    5276  260.51    5690  260.92  5738.9  262.12  5803.4  267.38  5845.3  271.43
  5903.5   281.9  5933.5  283.77  6060.1  289.18  6096.9  294.44  6131.1  297.64
#Mann= 8 ,-1 , 0
  4119.9     .16       0    4265     .12       0    4997     .07       0
    5003     .12       0  5050.5     .07       0  5108.4     .05       0
    5690     .16       0  5933.5     .05       0
Bank Sta=4970,5024.7
XS Rating Curve= 0 ,0
Exp/Cntr=0.3,0.1

Type RM Length L Ch R = 1 ,672     ,0,0,0
BEGIN DESCRIPTION:
UNT 041 IN BOCR 1.0
END DESCRIPTION:
XS GIS Cut Line= 4
      3759337.85     10590769.16      3759643.41     10589602.48
      3759299.66     10589501.79      3758064.09     10590043.22
#Sta/Elev= 30
  3612.1  276.11  3680.2  270.19  3848.8  260.32  4344.5  261.47  4448.4  259.56
  4520.7  261.04  4603.4  258.61  4737.8  259.85  4783.9  258.14    4985  259.93
  4990.2  259.97    4997  256.35  4999.8  255.85    5003  256.35  5009.6  256.35
  5023.6   260.8  5115.3  259.05  5310.4  257.65  6005.5  260.23  6061.5  261.77
  6224.5   271.6  6246.3  274.89    6254     278  6280.7  279.66  6344.6  286.93
  6381.8  288.56  6405.1  292.74  6410.6  291.59  6480.7  298.47  6525.3  306.04
#Mann= 9 ,-1 , 0
  3612.1     .16       0  3680.2     .12       0    4997     .07       0
    5003     .12       0  5023.6     .05       0  5115.3     .12       0
  5310.4     .05       0  6005.5     .16       0  6280.7     .05       0
Bank Sta=4985,5023.6
XS Rating Curve= 0 ,0
Exp/Cntr=0.3,0.1

Chan Stop Cuts=-1
Use User Specified Reach Order=0
Composite Channel Slope=5