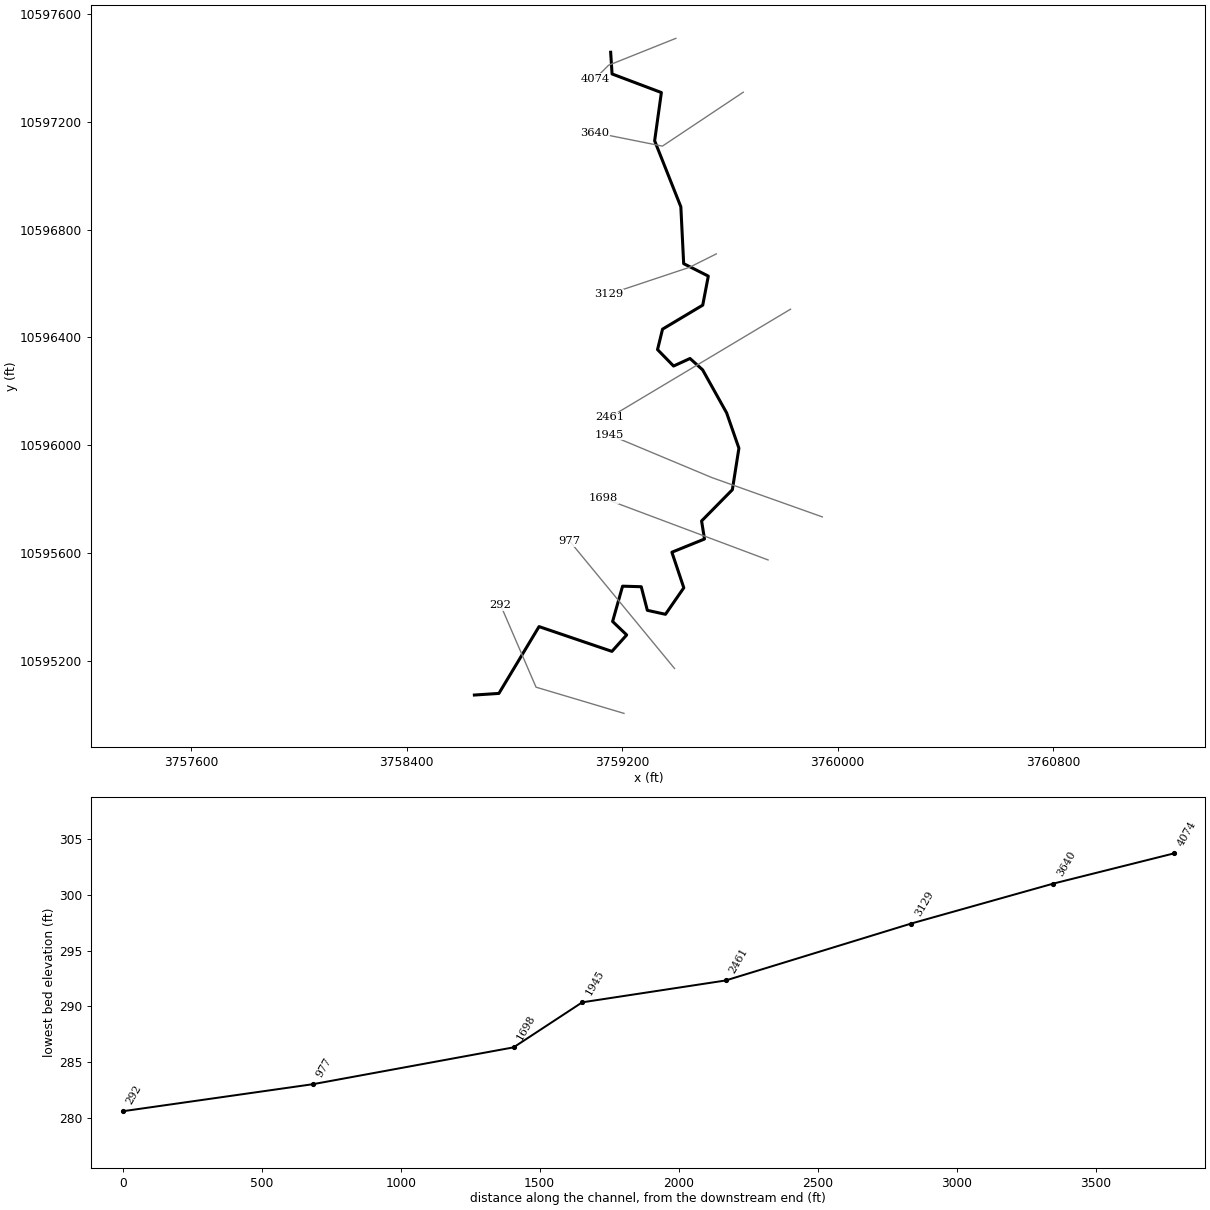
--- UNT 042 IN BOCR.prj (project) ---

Proj Title=UNT 042 IN BOCR Base Level Engineering
Current Plan=p01
Default Exp/Contr=0.3,0.1
English Units
Geom File=g01
Flow File=f01
Plan File=p01
Y Axis Title=Elevation
X Axis Title(PF)=Main Channel Distance
X Axis Title(XS)=Station
BEGIN DESCRIPTION:
UNT 042 IN BOCR
END DESCRIPTION:
DSS Export Rating Curves= 0
DSS Export Rating Curve Sorted= 0
DSS Export Volume Flow Curves= 0
DXF OffsetX= 0
DXF OffsetY= 0
DXF ScaleX= 1
DXF ScaleY= 10

--- UNT 042 IN BOCR.p01 (plan) ---

Plan Title=Multiple Run
Short Identifier=Multiple
Geom File=g01
Flow File=f01
Subcritical Flow
K Sum by GR= 0
Std Step Tol= 0.01
Critical Tol= 0.01
Num of Std Step Trials= 20
Max Error Tol= 0.3
Flow Tol Ratio= 0.001
Split Flow NTrial= 30
Split Flow Tol= 0.02
Split Flow Ratio= 0.02
Log Output Level= 0
Friction Slope Method= 1
Unsteady Friction Slope Method= 2
Unsteady Bridges Friction Slope Method= 1
Parabolic Critical Depth
Global Vel Dist=  1 , 1 , 1
Global Log Level= 0
CheckData=True
Encroach Param= -1, 0, 0, 0
BEGIN DESCRIPTION:
Multiple Run
END DESCRIPTION:

--- UNT 042 IN BOCR.f01 (steady flow) ---

Flow Title=Multiple
Number of Profiles=7
Profile Names=10-year,25-year,50-year,1pct_min,100-year,1pct_plu,500-year
River Rch & RM= UNT 042 IN BOCR,Reach-1,4074
     254     328     388     339     458     620     639
River Rch & RM= UNT 042 IN BOCR,Reach-1,1945
     387     514     618     548     741    1002    1065
Boundary for River Rch & Prof#=UNT 042 IN BOCR,Reach-1,1
Up Type=0
Dn Type=3
Dn Slope=0.005
Boundary for River Rch & Prof#=UNT 042 IN BOCR,Reach-1,2
Up Type=0
Dn Type=3
Dn Slope=0.005
Boundary for River Rch & Prof#=UNT 042 IN BOCR,Reach-1,3
Up Type=0
Dn Type=3
Dn Slope=0.005
Boundary for River Rch & Prof#=UNT 042 IN BOCR,Reach-1,4
Up Type=0
Dn Type=3
Dn Slope=0.005
Boundary for River Rch & Prof#=UNT 042 IN BOCR,Reach-1,5
Up Type=0
Dn Type=3
Dn Slope=0.005
Boundary for River Rch & Prof#=UNT 042 IN BOCR,Reach-1,6
Up Type=0
Dn Type=3
Dn Slope=0.005
Boundary for River Rch & Prof#=UNT 042 IN BOCR,Reach-1,7
Up Type=0
Dn Type=3
Dn Slope=0.005

--- UNT 042 IN BOCR.g01 (geometry) ---

Geom Title=Existing Conditions
Program Version=4.10

River Reach=UNT 042 IN BOCR ,Reach-1
Reach XY= 30
      3759157.54     10597458.51      3759162.75       10597378.
      3759345.75       10597309.      3759320.75       10597130.
        3759418.       10596885.       3759428.5       10596674.
      3759519.93     10596627.77      3759499.25       10596520.
       3759350.1     10596430.91       3759331.5       10596355.
        3759391.       10596294.        3759452.       10596322.
      3759498.75       10596280.        3759588.       10596120.
       3759633.5       10595989.      3759609.25       10595835.
        3759495.       10595719.      3759505.75       10595652.
      3759384.75       10595603.        3759429.       10595471.
      3759360.93     10595372.63      3759293.66     10595387.38
        3759271.       10595475.      3759201.75       10595477.
      3759164.75       10595346.        3759217.       10595296.
      3759162.25       10595235.      3758891.75       10595327.
      3758742.75       10595079.      3758651.75       10595073.

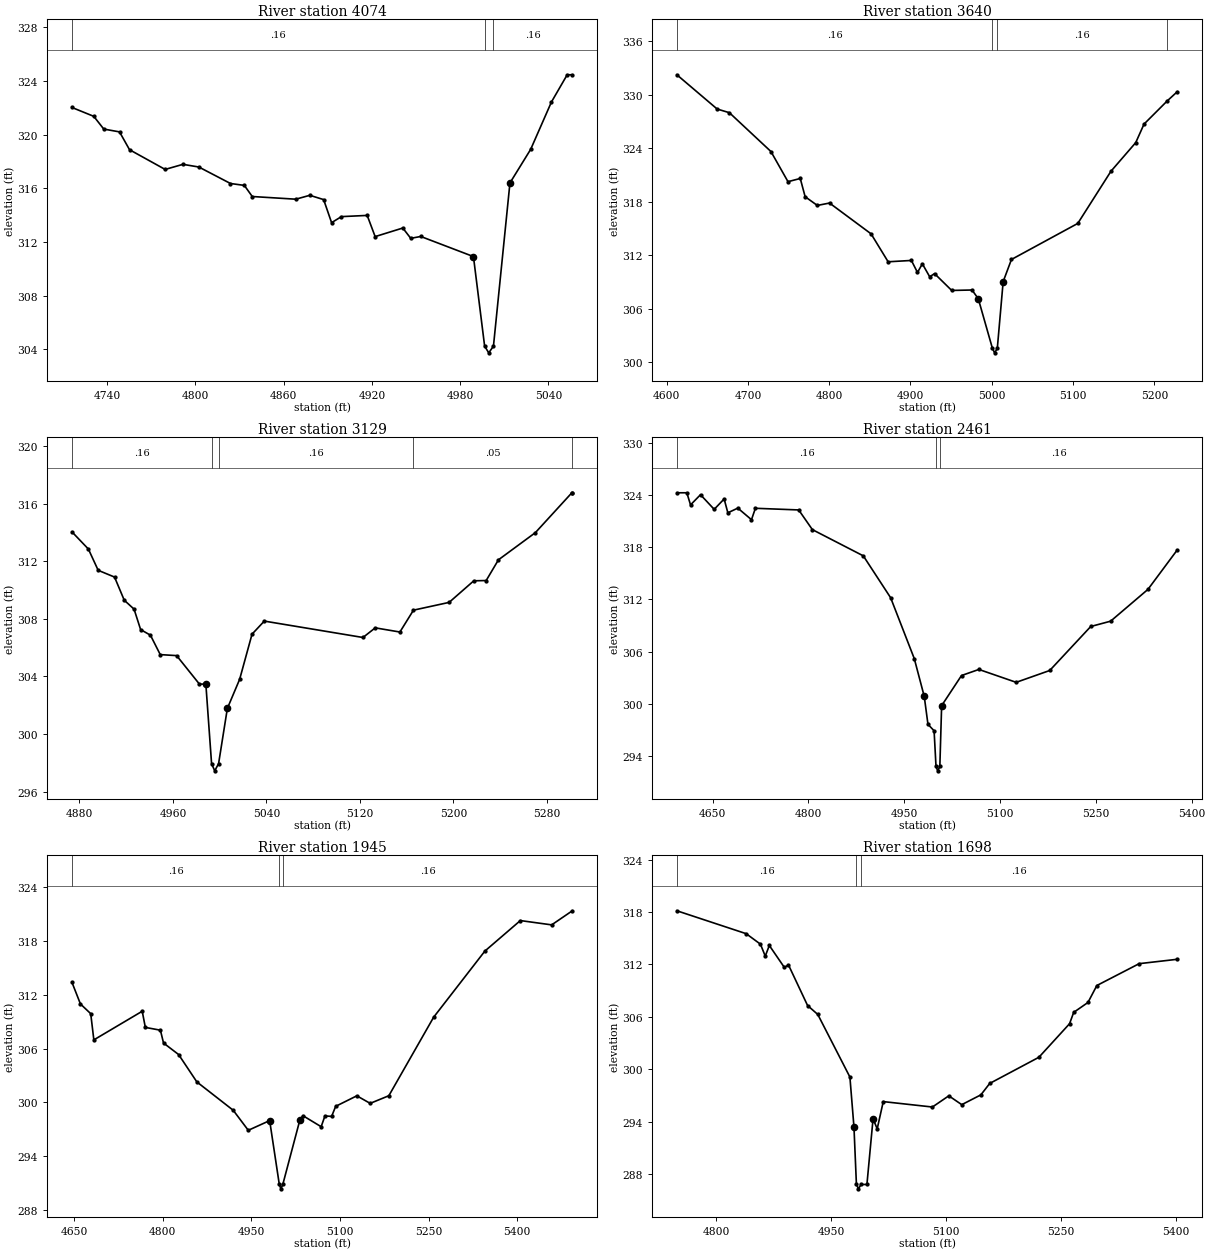
Type RM Length L Ch R = 1 ,4074    ,434,434,434
BEGIN DESCRIPTION:
UNT 042 IN BOCR 8.0
END DESCRIPTION:
XS GIS Cut Line= 3
      3759399.62     10597510.19      3759149.61     10597410.19
       3759099.6     10597360.18
#Sta/Elev= 30
  4716.2  322.03    4731  321.37  4737.8  320.42  4748.5  320.21  4755.3  318.88
  4779.5  317.41  4791.6  317.79  4802.4  317.59  4823.9  316.36  4833.3  316.22
  4838.7  315.39  4868.3  315.19  4877.8  315.48  4887.2  315.16  4892.6  313.44
  4899.3  313.89  4916.8  313.98  4922.2   312.4    4941  313.04  4946.4  312.27
  4953.2  312.41    4989  310.91  4996.6  304.23  4999.4  303.73  5002.6  304.23
  5013.8   316.4  5027.9  318.91    5042  322.44  5052.7  324.47  5056.2  324.47
#Mann= 3 ,-1 , 0
  4716.2     .16       0  4996.6     .07       0  5002.6     .16       0
Bank Sta=4989,5013.8
XS Rating Curve= 0 ,0
Exp/Cntr=0.3,0.1

Type RM Length L Ch R = 1 ,3640    ,511,511,511
BEGIN DESCRIPTION:
UNT 042 IN BOCR 7.0
END DESCRIPTION:
XS GIS Cut Line= 3
      3759649.64     10597310.21      3759349.61     10597110.19
      3759099.65     10597160.18
#Sta/Elev= 30
  4612.6  332.26  4662.2  328.41  4677.2     328  4728.3  323.64  4749.3  320.25
  4764.4  320.61  4770.4  318.56  4785.4  317.58  4800.4  317.85  4851.5  314.39
  4872.5  311.25  4901.1   311.4  4908.6  310.05  4914.6  311.02  4923.6  309.57
  4929.6  309.92  4950.7  308.03  4975.7  308.08  4983.4   307.1  5000.8  301.52
  5003.5  301.02  5006.8  301.52    5014  309.02  5024.2  311.51  5105.8  315.56
  5146.6  321.42  5177.1  324.64  5187.3  326.72  5215.9  329.33  5228.1  330.35
#Mann= 4 ,-1 , 0
  4612.6     .16       0  5000.8     .07       0  5006.8     .16       0
  5215.9     .05       0
Bank Sta=4983.4,5014
XS Rating Curve= 0 ,0
Exp/Cntr=0.3,0.1

Type RM Length L Ch R = 1 ,3129    ,668,668,668
BEGIN DESCRIPTION:
UNT 042 IN BOCR 6.0
END DESCRIPTION:
XS GIS Cut Line= 3
      3759549.62      10596710.2      3759449.61     10596660.19
      3759149.65      10596560.2
#Sta/Elev= 30
  4873.7  314.05  4887.7  312.86  4896.1  311.38  4910.1  310.91  4918.4   309.3
  4926.8  308.68  4932.4  307.26  4940.8  306.87  4949.2  305.52  4963.2  305.45
  4982.7  303.47  4988.2  303.47  4993.1  297.94  4995.8  297.44  4999.1  297.94
  5006.6  301.78  5017.1   303.8  5027.7  306.94  5038.2  307.85  5122.6  306.71
  5133.1  307.38  5154.2  307.09  5165.8  308.61  5196.3  309.15  5217.4  310.65
    5228  310.67  5238.5  312.11  5270.1     314  5301.3  316.77  5301.7  316.77
#Mann= 5 ,-1 , 0
  4873.7     .16       0  4993.1     .07       0  4999.1     .16       0
  5165.8     .05       0  5301.3     .16       0
Bank Sta=4988.2,5006.6
XS Rating Curve= 0 ,0
Exp/Cntr=0.3,0.1

Type RM Length L Ch R = 1 ,2461    ,516,516,516
BEGIN DESCRIPTION:
UNT 042 IN BOCR 5.0
END DESCRIPTION:
XS GIS Cut Line= 2
      3759825.11     10596504.95      3759152.99     10596103.07
#Sta/Elev= 30
  4594.2  324.25  4609.8  324.25  4615.6  322.86  4631.2  324.03  4652.6  322.35
  4668.2  323.54    4674  321.95  4689.6  322.49    4711  321.16  4717.1  322.47
  4784.9  322.28  4806.3  320.02    4886  317.01  4928.8   312.2  4965.8  305.21
  4981.4  300.87  4987.2  297.67  4996.8  296.93  4999.8  292.83  5002.5  292.33
  5005.8  292.83  5008.6  299.81  5039.7  303.27  5066.9  303.97  5125.3  302.49
  5177.8  303.85    5242   308.9  5273.1  309.51  5331.5  313.16  5377.3  317.68
#Mann= 3 ,-1 , 0
  4594.2     .16       0  4999.8     .07       0  5005.8     .16       0
Bank Sta=4981.4,5008.6
XS Rating Curve= 0 ,0
Exp/Cntr=0.3,0.1

Type RM Length L Ch R = 1 ,1945    ,247,247,247
BEGIN DESCRIPTION:
UNT 042 IN BOCR 4.0
END DESCRIPTION:
XS GIS Cut Line= 3
       3759943.1      10595734.1       3759533.4     10595879.92
        3759153.       10596039.
#Sta/Elev= 30
  4646.3  313.36  4660.6  310.96    4678  309.88  4683.3  306.96  4765.2  310.15
  4770.5  308.35    4796  308.04  4801.3  306.61  4826.8  305.33  4857.7  302.28
  4919.3  299.12  4944.8  296.89    4981  297.97  4997.3  290.87    5000  290.37
  5003.3  290.87    5032     298  5037.3  298.52  5068.2  297.29  5074.6  298.49
  5085.9  298.44  5092.8  299.56  5128.6  300.73  5151.2  299.89  5182.8  300.74
  5258.7  309.49  5345.4  316.85  5405.5  320.25  5458.5  319.77  5493.5  321.34
#Mann= 3 ,-1 , 0
  4646.3     .16       0  4997.3     .07       0  5003.3     .16       0
Bank Sta=4981,5032
XS Rating Curve= 0 ,0
Exp/Cntr=0.3,0.1

Type RM Length L Ch R = 1 ,1698    ,721,721,721
BEGIN DESCRIPTION:
Mapping XS 85583e69
END DESCRIPTION:
XS GIS Cut Line= 2
       3759741.7     10595574.38      3759130.65     10595803.52
#Sta/Elev= 30
  4748.9  318.14  4839.3  315.52  4857.9  314.32  4864.2  312.95  4869.5  314.17
  4889.1  311.66  4894.5  311.94  4919.4   307.3  4932.7  306.28  4974.6  299.12
  4979.9  293.39  4983.1  286.83  4985.8  286.33  4989.1  286.83  4996.8  286.83
  5004.8  294.35  5010.2  293.19  5018.1  296.31  5082.2  295.69  5103.6  296.97
  5120.5  295.96  5145.4  297.08    5157  298.39  5221.1  301.38  5261.1  305.22
  5266.5  306.52  5285.1  307.65  5296.7  309.59  5351.9  312.09  5401.5  312.59
#Mann= 3 ,-1 , 0
  4748.9     .16       0  4983.1     .07       0  4989.1     .16       0
Bank Sta=4979.9,5004.8
XS Rating Curve= 0 ,0
Exp/Cntr=0.3,0.1

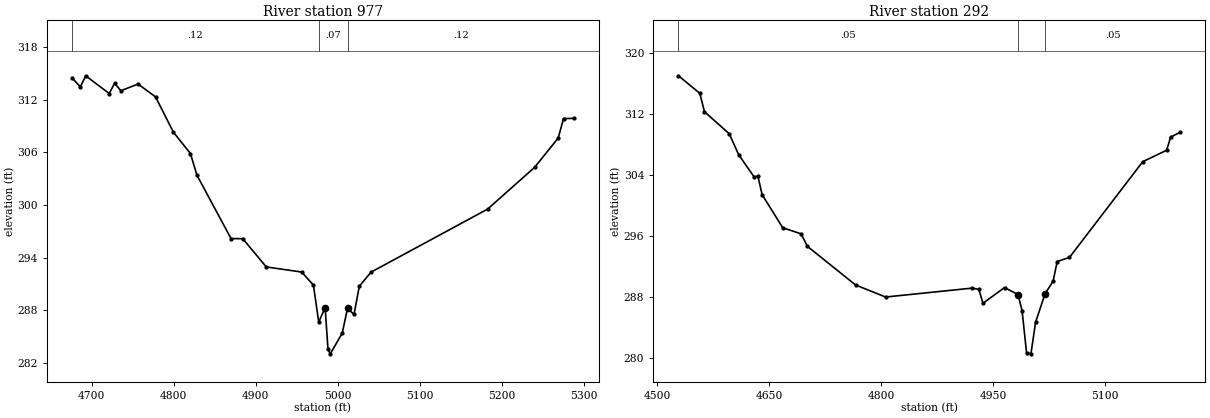
Type RM Length L Ch R = 1 ,977     ,685,685,685
BEGIN DESCRIPTION:
Mapping XS 5f25e235
END DESCRIPTION:
XS GIS Cut Line= 2
      3759394.52     10595171.58      3759005.59     10595643.85
#Sta/Elev= 30
    4676  314.47  4686.1  313.44  4692.6  314.71  4721.3  312.69  4727.8  313.85
  4735.6  313.01  4756.5  313.77  4777.8   312.3  4799.5  308.29  4820.3  305.85
  4828.2  303.39  4869.8  296.16  4884.1  296.15  4912.8  292.93  4955.9  292.35
  4970.2  290.87  4976.7  286.65  4984.5   288.3    4988  283.53  4990.8  283.03
  5005.4   285.4  5011.8  288.21  5019.7  287.52  5026.2  290.74  5040.5  292.34
  5182.6  299.52  5239.9  304.28  5268.6  307.61  5275.1  309.83  5287.8  309.86
#Mann= 3 ,-1 , 0
    4676     .12       0  4976.7     .07       0  5011.8     .12       0
Bank Sta=4984.5,5011.8
XS Rating Curve= 0 ,0
Exp/Cntr=0.3,0.1

Type RM Length L Ch R = 1 ,292     ,0,0,0
BEGIN DESCRIPTION:
UNT 042 IN BOCR 1.0
END DESCRIPTION:
XS GIS Cut Line= 3
      3759206.98     10595004.93      3758880.62     10595102.15
      3758749.22     10595406.46
#Sta/Elev= 30
  4528.5  316.96  4557.1  314.66  4563.3  312.26  4596.5  309.38  4609.2  306.62
  4629.7  303.75  4634.9  303.82  4640.5  301.41  4668.1  297.09  4692.7  296.29
  4701.2  294.65  4765.7   289.6  4805.9  288.03  4921.4  289.19  4930.7  289.04
  4936.2  287.21  4965.1  289.27  4983.2  288.35  4988.6  286.25  4994.6  280.75
 5000.45   280.6  5006.7  284.74  5019.4  288.46  5030.2  290.11  5035.6  292.67
  5052.1  293.21  5150.1  305.72  5182.1  307.22  5187.6  308.94  5200.5  309.59
#Mann= 3 , 0 , 0
  4528.5     .05       0  4983.2     .03       0  5019.4     .05       0
Bank Sta=4983.2,5019.4
XS Rating Curve= 0 ,0
Exp/Cntr=0.3,0.1

Chan Stop Cuts=-1
Use User Specified Reach Order=0
Composite Channel Slope=5