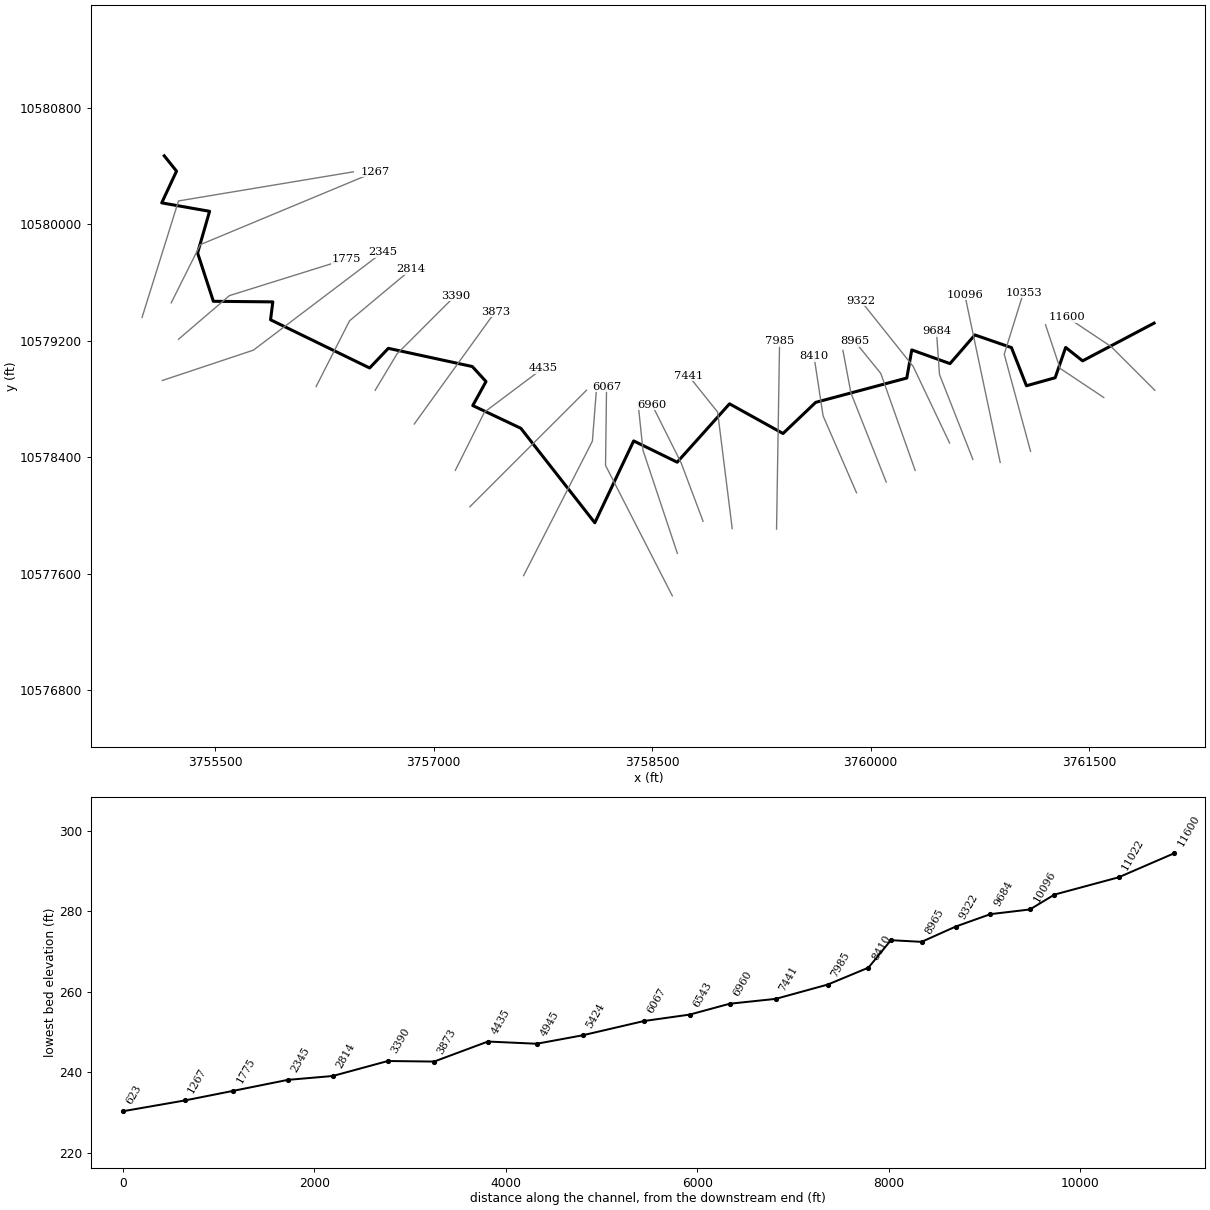
--- UNT 044 IN BOCR.prj (project) ---

Proj Title=UNT 044 IN BOCR Base Level Engineering
Current Plan=p01
Default Exp/Contr=0.3,0.1
English Units
Geom File=g01
Flow File=f01
Plan File=p01
Y Axis Title=Elevation
X Axis Title(PF)=Main Channel Distance
X Axis Title(XS)=Station
BEGIN DESCRIPTION:
UNT 044 IN BOCR
END DESCRIPTION:
DSS Export Rating Curves= 0
DSS Export Rating Curve Sorted= 0
DSS Export Volume Flow Curves= 0
DXF OffsetX= 0
DXF OffsetY= 0
DXF ScaleX= 1
DXF ScaleY= 10

--- UNT 044 IN BOCR.p01 (plan) ---

Plan Title=Multiple Run
Short Identifier=Multiple
Geom File=g01
Flow File=f01
Subcritical Flow
K Sum by GR= 0
Std Step Tol= 0.01
Critical Tol= 0.01
Num of Std Step Trials= 20
Max Error Tol= 0.3
Flow Tol Ratio= 0.001
Split Flow NTrial= 30
Split Flow Tol= 0.02
Split Flow Ratio= 0.02
Log Output Level= 0
Friction Slope Method= 1
Unsteady Friction Slope Method= 2
Unsteady Bridges Friction Slope Method= 1
Parabolic Critical Depth
Global Vel Dist=  1 , 1 , 1
Global Log Level= 0
CheckData=True
Encroach Param= -1, 0, 0, 0
BEGIN DESCRIPTION:
Multiple Run
END DESCRIPTION:

--- UNT 044 IN BOCR.f01 (steady flow) ---

Flow Title=Multiple
Program Version=4.10
Number of Profiles= 7
Profile Names=10-year,25-year,50-year,1pct_min,100-year,1pct_plu,500-year
River Rch & RM=UNT 044 IN BOCR,Reach-1         ,11600
     708     976    1201    1088    1471    1990    2215
River Rch & RM=UNT 044 IN BOCR,Reach-1         ,7985
     913    1270    1574    1432    1937    2620    2946
River Rch & RM=UNT 044 IN BOCR,Reach-1         ,2345
    1103    1551    1934    1770    2394    3237    3683
River Rch & RM=UNT 044 IN BOCR,Reach-1         ,1267
    1103    1551    1934    1770    2394    3237    3683
Boundary for River Rch & Prof#=UNT 044 IN BOCR,Reach-1         , 1
Up Type= 0
Dn Type= 3
Dn Slope=0.005
Boundary for River Rch & Prof#=UNT 044 IN BOCR,Reach-1         , 2
Up Type= 0
Dn Type= 3
Dn Slope=0.005
Boundary for River Rch & Prof#=UNT 044 IN BOCR,Reach-1         , 3
Up Type= 0
Dn Type= 3
Dn Slope=0.005
Boundary for River Rch & Prof#=UNT 044 IN BOCR,Reach-1         , 4
Up Type= 0
Dn Type= 3
Dn Slope=0.005
Boundary for River Rch & Prof#=UNT 044 IN BOCR,Reach-1         , 5
Up Type= 0
Dn Type= 3
Dn Slope=0.005
Boundary for River Rch & Prof#=UNT 044 IN BOCR,Reach-1         , 6
Up Type= 0
Dn Type= 3
Dn Slope=0.005
Boundary for River Rch & Prof#=UNT 044 IN BOCR,Reach-1         , 7
Up Type= 0
Dn Type= 3
Dn Slope=0.005
DSS Import GetInterval= 0
DSS Import GetPeak= 0
DSS Import FillOption= 0

--- UNT 044 IN BOCR.g01 (geometry) ---

Geom Title=Existing Conditions
Program Version=4.10

River Reach=UNT 044 IN BOCR ,Reach-1
Reach XY= 30
      3761944.97     10579321.05      3761454.25       10579062.
        3761338.       10579154.        3761266.       10578946.
        3761069.       10578891.        3760966.       10579153.
        3760715.       10579240.      3760544.25       10579043.
        3760282.       10579137.      3760247.75       10578944.
      3759622.75       10578777.      3759398.25       10578563.
      3759031.25       10578767.        3758672.       10578366.
       3758373.5       10578512.      3758106.75       10577950.
        3757599.       10578599.      3757269.25       10578755.
        3757360.       10578920.        3757266.       10579023.
      3756689.75       10579148.       3756561.5       10579013.
       3755881.5       10579344.        3755897.       10579467.
        3755489.       10579471.      3755380.75       10579803.
        3755463.       10580089.       3755134.5       10580147.
      3755236.25       10580365.        3755152.       10580470.

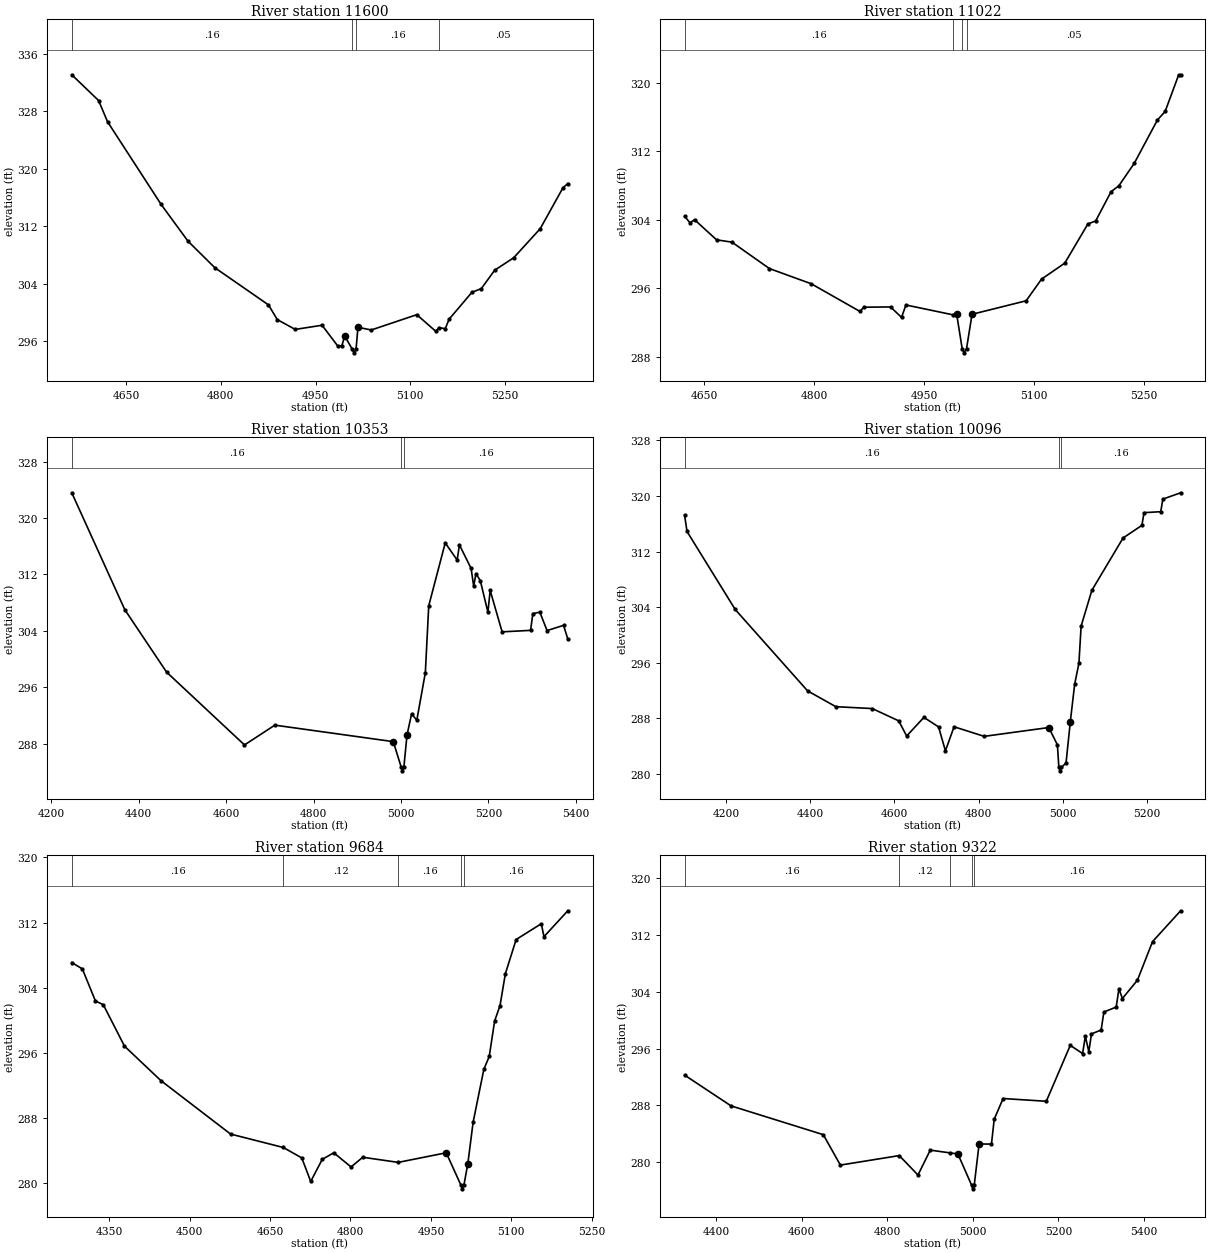
Type RM Length L Ch R = 1 ,11600   ,578,578,578
BEGIN DESCRIPTION:
UNT 044 IN BOCR 22.0
END DESCRIPTION:
XS GIS Cut Line= 3
      3761949.61     10578860.19      3761649.61     10579160.19
      3761349.62     10579360.18
#Sta/Elev= 30
  4564.3  333.09  4606.7  329.51  4620.9  326.55  4705.7  315.04  4748.1  309.94
  4790.6  306.24  4875.4  301.07  4889.6  299.01  4917.8  297.65  4960.3  298.23
    4985  295.36  4991.6  295.36  4996.1  296.74  5008.1  294.89  5010.8  294.39
  5014.1  294.89  5017.1  297.95  5038.1  297.57  5110.2   299.7  5140.3  297.38
  5145.2  297.89  5155.3  297.76  5161.3  299.07  5197.4  302.81  5212.4  303.34
  5233.4  305.89  5263.5  307.62  5305.5  311.67  5341.6  317.38  5349.1  317.94
#Mann= 4 ,-1 , 0
  4564.3     .16       0  5008.1     .07       0  5014.1     .16       0
  5145.2     .05       0
Bank Sta=4996.1,5017.1
XS Rating Curve= 0 ,0
Exp/Cntr=0.3,0.1

Type RM Length L Ch R = 1 ,11022   ,669,669,669
BEGIN DESCRIPTION:
UNT 044 IN BOCR 21.0
END DESCRIPTION:
XS GIS Cut Line= 3
      3761599.62     10578810.18      3761299.61     10579010.19
      3761199.61     10579310.19
#Sta/Elev= 30
  4623.4  304.41  4630.9  303.64  4636.9  304.02    4667  301.66    4688  301.39
  4739.1   298.3  4796.2  296.52  4862.3   293.3  4868.3  293.78  4904.4  293.81
  4919.4  292.59  4925.4  294.04  4989.4  292.89  4994.5  293.04  5002.1  288.94
  5004.8  288.44  5008.1  288.94  5015.6  292.95  5089.4  294.53  5110.5  297.07
  5142.1  298.93  5173.7  303.52  5184.3  303.87  5205.3  307.29  5215.9  307.98
    5237  310.62  5268.6  315.69  5279.1  316.68  5297.6  320.97  5300.2  320.97
#Mann= 4 ,-1 , 0
  4623.4     .16       0  4989.4     .05       0  5002.1    .035       0
  5008.1     .05       0
Bank Sta=4994.5,5015.6
XS Rating Curve= 0 ,0
Exp/Cntr=0.3,0.1

Type RM Length L Ch R = 1 ,10353   ,257,257,257
BEGIN DESCRIPTION:
UNT 044 IN BOCR 20.0
END DESCRIPTION:
XS GIS Cut Line= 3
      3761097.07     10578440.93       3760916.5     10579107.64
      3761048.44     10579531.24
#Sta/Elev= 30
  4247.1  323.58  4368.4     307  4463.9  298.15  4642.1  287.82  4711.5  290.63
  4982.4  288.29  5000.6  284.65  5003.4  284.15  5006.6  284.65  5013.8  289.23
  5024.3  292.24  5036.2  291.32  5055.7  298.06  5063.5  307.56  5101.2  316.47
  5128.5  314.04  5133.7  316.19  5160.4  312.85  5166.3  310.34  5171.5  312.11
  5181.4  311.13  5198.8  306.65    5204  309.73  5231.3  303.86  5296.4  304.07
  5301.6  306.45  5317.6  306.65  5334.1  304.04  5371.9  304.78  5381.5  302.85
#Mann= 3 ,-1 , 0
  4247.1     .16       0  5000.6     .07       0  5006.6     .16       0
Bank Sta=4982.4,5013.8
XS Rating Curve= 0 ,0
Exp/Cntr=0.3,0.1

Type RM Length L Ch R = 1 ,10096   ,412,412,412
BEGIN DESCRIPTION:
UNT 044 IN BOCR 19.0
END DESCRIPTION:
XS GIS Cut Line= 2
      3760888.73     10578364.58       3760645.9     10579516.26
#Sta/Elev= 30
  4102.2   317.2  4107.9  314.88  4222.3  303.66  4394.1  291.95    4461  289.68
  4547.4  289.41  4610.3  287.64  4629.1  285.46    4670  288.14  4704.8  286.77
  4721.1  283.33  4741.6  286.79  4813.1  285.41  4966.4  286.68  4986.8  284.19
  4990.3  280.95    4993  280.45  4996.3  280.95  5007.3  281.58  5017.5  287.53
  5027.7  292.88  5037.9  295.94  5043.1  301.28  5068.6  306.42  5142.7  313.95
  5187.3  315.76  5192.4  317.59    5232  317.73  5237.1  319.54  5279.2  320.45
#Mann= 3 ,-1 , 0
  4102.2     .16       0  4990.3     .07       0  4996.3     .16       0
Bank Sta=4966.4,5017.5
XS Rating Curve= 0 ,0
Exp/Cntr=0.3,0.1

Type RM Length L Ch R = 1 ,9684    ,362,362,362
BEGIN DESCRIPTION:
UNT 044 IN BOCR 18.0
END DESCRIPTION:
XS GIS Cut Line= 3
      3760701.23     10578385.41      3760472.06     10578968.75
       3760451.3     10579266.29
#Sta/Elev= 30
  4280.3  307.09    4300  306.31  4324.4  302.37  4339.1  301.91  4378.6  296.82
  4446.6  292.58  4576.4  286.02  4674.8  284.37  4709.2  283.09  4725.9   280.2
  4747.4  282.91  4768.9  283.72  4801.1  281.98    4823  283.17  4889.1  282.54
  4978.6  283.72  5005.7  279.79  5008.5  279.29  5011.7  279.79  5018.9  282.38
  5028.8  287.49  5048.8  293.98  5058.8  295.55  5068.9  299.92  5078.9  301.79
  5088.9  305.72    5109  309.92  5155.9  311.86  5160.9  310.27  5205.3  313.45
#Mann= 5 ,-1 , 0
  4280.3     .16       0  4674.8     .12       0  4889.1     .16       0
  5005.7     .07       0  5011.7     .16       0
Bank Sta=4978.6,5018.9
XS Rating Curve= 0 ,0
Exp/Cntr=0.3,0.1

Type RM Length L Ch R = 1 ,9322    ,357,357,357
BEGIN DESCRIPTION:
Mapping XS ac6228c6
END DESCRIPTION:
XS GIS Cut Line= 3
      3760541.42     10578497.77      3760291.41     10579023.84
        3759932.     10579474.39
#Sta/Elev= 30
  4326.7  292.25  4435.2  287.91  4650.7  283.85  4690.6  279.56  4828.2   280.9
  4871.9  278.16  4900.6  281.67  4946.8  281.28  4965.1  281.14  4997.3  276.71
  5000.1  276.21  5003.3  276.71  5014.7  282.54  5043.6  282.52    5050  286.03
  5070.8  288.95  5171.7  288.56  5227.7  296.45  5256.5  295.29  5262.9  297.73
    5271  295.56  5277.3  298.07  5299.8  298.61  5306.2  301.15    5335  301.85
  5341.4  304.44  5349.4  303.05  5384.6  305.64  5419.9  311.08  5485.5  315.43
#Mann= 5 ,-1 , 0
  4326.7     .16       0  4828.2     .12       0  4946.8     .16       0
  4997.3     .07       0  5003.3     .16       0
Bank Sta=4965.1,5014.7
XS Rating Curve= 0 ,0
Exp/Cntr=0.3,0.1

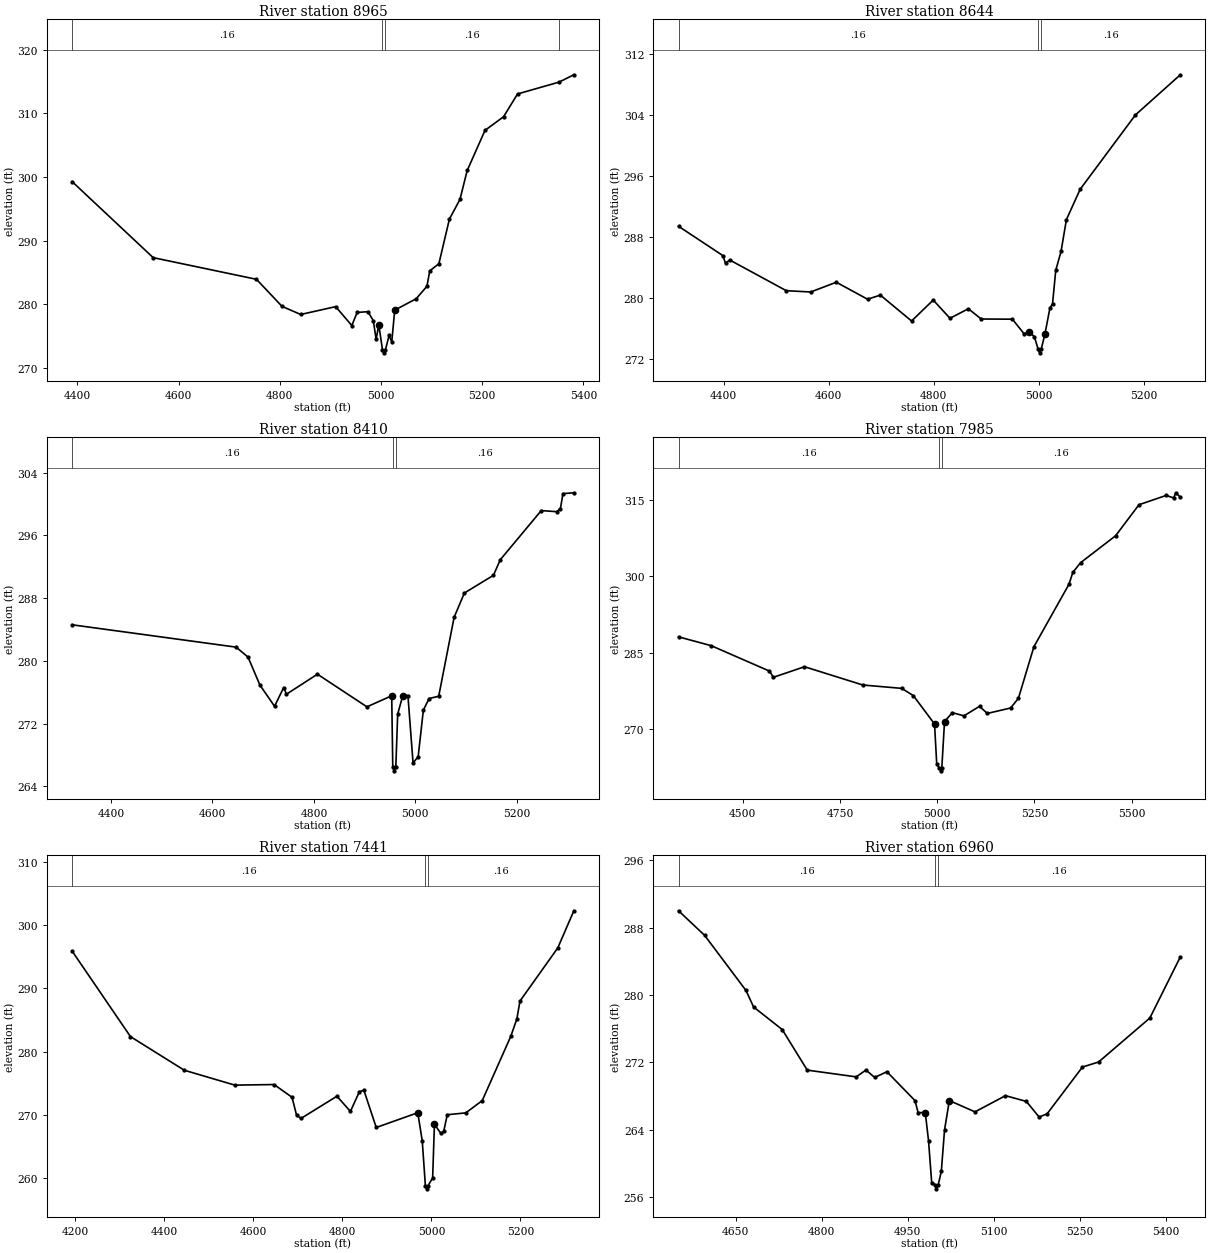
Type RM Length L Ch R = 1 ,8965    ,321,321,321
BEGIN DESCRIPTION:
UNT 044 IN BOCR 17.0
END DESCRIPTION:
XS GIS Cut Line= 3
      3760305.39     10578309.04      3760069.28      10578975.7
      3759889.84     10579196.55
#Sta/Elev= 30
  4389.4  299.28  4549.7  287.34  4753.9  283.94  4804.4  279.69  4841.3  278.42
  4910.4  279.65  4942.3  276.69  4952.9  278.74  4974.1  278.86  4984.7  277.47
  4990.4  274.56  4995.7  276.75  5002.9   272.9  5005.7   272.4  5008.9   272.9
    5016  275.13  5021.3  274.12  5027.1   279.1  5069.6  280.89  5090.8  282.85
  5096.4  285.27  5114.4  286.38  5135.2  293.39    5156  296.47  5170.4  301.02
  5205.6  307.32  5242.2  309.45  5269.9  313.03  5351.9  314.89  5381.2  316.04
#Mann= 4 ,-1 , 0
  4389.4     .16       0  5002.9     .07       0  5008.9     .16       0
  5351.9     .05       0
Bank Sta=4995.7,5027.1
XS Rating Curve= 0 ,0
Exp/Cntr=0.3,0.1

Type RM Length L Ch R = 1 ,8644    ,234,234,234
BEGIN DESCRIPTION:
Mapping XS 6bad7a33
END DESCRIPTION:
XS GIS Cut Line= 3
      3760106.53     10578229.52      3759864.32     10578841.55
      3759809.63     10579133.26
#Sta/Elev= 30
  4314.2  289.43  4398.3  285.59  4403.6  284.59  4411.7     285  4519.3  280.97
  4565.8   280.8  4614.5  282.08  4673.9  279.85  4698.3  280.39  4757.7  276.99
  4798.9  279.74  4830.8  277.35  4865.9   278.6  4890.2  277.25  4949.6  277.23
    4972   275.3  4981.2  275.58  4991.4  274.93  4998.5  273.31  5001.3  272.81
  5004.5  273.31  5011.7  275.33    5021   278.7    5026  279.24  5032.1  283.64
  5042.2  286.13  5052.4   290.3  5078.6  294.29  5183.8  304.05  5269.2  309.32
#Mann= 3 ,-1 , 0
  4314.2     .16       0  4998.5     .07       0  5004.5     .16       0
Bank Sta=4981.2,5011.7
XS Rating Curve= 0 ,0
Exp/Cntr=0.3,0.1

Type RM Length L Ch R = 1 ,8410    ,425,425,425
BEGIN DESCRIPTION:
UNT 044 IN BOCR 16.0
END DESCRIPTION:
XS GIS Cut Line= 3
       3759902.6     10578156.28      3759673.45     10578684.03
      3759610.95     10579093.74
#Sta/Elev= 30
    4323  284.61  4646.6  281.76  4670.1  280.49  4693.5  276.93  4722.4  274.22
  4740.4  276.61  4745.9  275.76    4807  278.31  4904.6  274.15  4953.5  275.56
  4955.6  266.49  4958.3  265.99  4961.6  266.49  4965.3  273.23  4975.4  275.59
  4985.5  275.58  4995.6     267  5005.7  267.79  5015.9  273.72  5027.2  275.21
  5046.2   275.5  5076.6  285.56  5096.8  288.66  5154.2  290.92  5167.6   292.9
  5248.5  299.17  5278.9  299.03  5286.2   299.4  5291.3  301.33  5312.8  301.44
#Mann= 3 ,-1 , 0
    4323     .16       0  4955.6     .07       0  4961.6     .16       0
Bank Sta=4953.5,4975.4
XS Rating Curve= 0 ,0
Exp/Cntr=0.3,0.1

Type RM Length L Ch R = 1 ,7985    ,544,544,544
BEGIN DESCRIPTION:
UNT 044 IN BOCR 15.0
END DESCRIPTION:
XS GIS Cut Line= 2
        3759354.      10577906.3      3759374.81     10579196.53
#Sta/Elev= 30
  4334.7   288.1  4418.6  286.37  4568.6  281.37  4578.6  280.15  4658.6  282.23
  4808.7  278.64  4908.7  277.98  4938.7  276.54    4993  270.98  4998.7  263.08
  5005.7  262.28  5008.4  261.78  5011.7  262.28  5018.7  271.45  5038.7  273.21
  5068.7  272.58  5108.7  274.46  5128.7  273.05  5188.7  274.13  5208.7  276.02
  5248.7  286.18  5338.7  298.42  5348.7  300.77  5368.7  302.67  5458.7  307.96
  5518.7  314.05  5588.8  315.88  5608.1  315.38  5613.1   316.4  5625.1  315.55
#Mann= 3 ,-1 , 0
  4334.7     .16       0  5005.7     .07       0  5011.7     .16       0
Bank Sta=4993,5018.7
XS Rating Curve= 0 ,0
Exp/Cntr=0.3,0.1

Type RM Length L Ch R = 1 ,7441    ,481,481,481
BEGIN DESCRIPTION:
UNT 044 IN BOCR 14.0
END DESCRIPTION:
XS GIS Cut Line= 3
      3759049.61     10577910.21      3758949.61     10578710.19
      3758749.59     10578960.22
#Sta/Elev= 30
  4193.4  295.94  4324.4  282.37  4445.3  277.03  4558.7  274.67  4646.9  274.76
  4687.2  272.74  4697.3   269.9  4707.4  269.39    4788  272.91  4818.2   270.5
  4838.4  273.63  4848.4  273.87  4876.2  267.95  4969.4  270.29  4979.5  265.81
  4986.5  258.72  4989.3  258.22  4992.5  258.72  5002.8  259.94  5006.8  268.46
  5021.2  267.02  5027.6  267.32  5035.6  269.97  5077.2  270.27  5114.1  272.21
  5178.1  282.39  5191.7  285.13  5198.9  288.01  5283.7  296.43  5319.8  302.32
#Mann= 3 ,-1 , 0
  4193.4     .16       0  4986.5     .07       0  4992.5     .16       0
Bank Sta=4969.4,5006.8
XS Rating Curve= 0 ,0
Exp/Cntr=0.3,0.1

Type RM Length L Ch R = 1 ,6960    ,417,417,417
BEGIN DESCRIPTION:
UNT 044 IN BOCR 13.0
END DESCRIPTION:
XS GIS Cut Line= 3
      3758849.61     10577960.19      3758699.61     10578360.19
      3758499.62     10578760.18
#Sta/Elev= 30
  4550.6  289.99    4596  287.08  4668.1  280.54  4681.4  278.58  4731.3   275.9
  4774.9  271.09  4860.3  270.29  4877.2   271.1  4892.4  270.22  4913.7   270.9
  4962.7  267.47    4968  266.06  4980.6  266.04  4986.2  262.74  4991.8   257.7
  4997.2  257.51  4999.9  257.01  5003.2  257.51  5008.5  259.07  5014.1  263.98
  5022.5  267.48  5067.2  266.14  5120.3  268.06  5156.7  267.38    5179  265.52
    5193  265.92  5254.5  271.46  5282.5  272.05  5371.9  277.27    5425  284.52
#Mann= 3 ,-1 , 0
  4550.6     .16       0  4997.2     .07       0  5003.2     .16       0
Bank Sta=4980.6,5022.5
XS Rating Curve= 0 ,0
Exp/Cntr=0.3,0.1

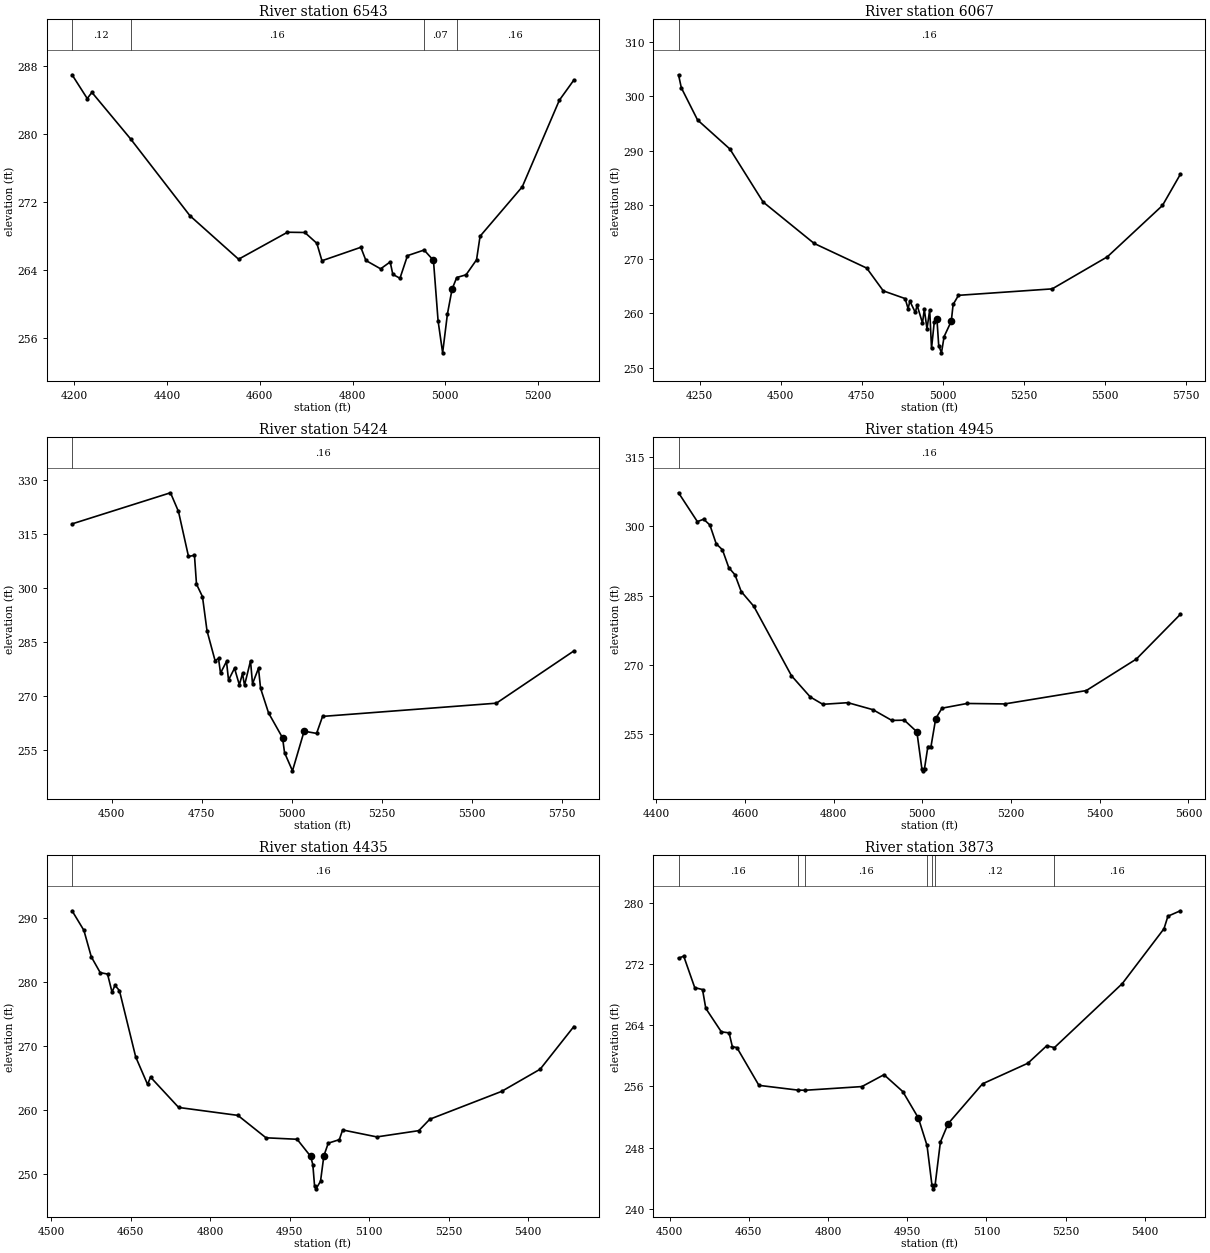
Type RM Length L Ch R = 1 ,6543    ,476,476,476
BEGIN DESCRIPTION:
UNT 044 IN BOCR 12.0
END DESCRIPTION:
XS GIS Cut Line= 3
      3758673.44     10577739.61      3758437.34     10578447.92
      3758402.61     10578781.29
#Sta/Elev= 30
  4195.3  286.98    4228  284.19  4238.1  284.91  4321.7  279.43  4449.4  270.42
  4554.3  265.31  4659.7  268.48  4697.1  268.45    4723  267.18    4734  265.13
  4817.8  266.71  4828.8  265.16  4860.5  264.18  4881.1  264.99  4886.8  263.53
  4902.2  263.07  4918.4  265.73  4954.3  266.39  4974.4  265.17  4984.4  258.06
  4994.2  254.31  5004.5  258.87  5014.6   261.8  5024.6  263.16  5044.7  263.48
  5067.3  265.24  5074.9  268.01  5165.9  273.82  5245.8  283.99  5277.1  286.36
#Mann= 4 ,-1 , 0
  4195.3     .12       0  4321.7     .16       0  4954.3     .07       0
  5024.6     .16       0
Bank Sta=4974.4,5014.6
XS Rating Curve= 0 ,0
Exp/Cntr=0.3,0.1

Type RM Length L Ch R = 1 ,6067    ,643,643,643
BEGIN DESCRIPTION:
UNT 044 IN BOCR 11.0
END DESCRIPTION:
XS GIS Cut Line= 3
      3758638.74      10577447.9      3758180.39     10578343.75
      3758187.33     10578885.31
#Sta/Elev= 30
  4184.7  303.97  4193.3  301.57  4243.4  295.64  4343.2  290.28  4445.6  280.52
  4602.9  272.89  4765.2  268.34  4816.3  264.14  4883.7  262.72  4892.8  260.87
  4898.4  262.24    4915  260.17  4920.7  261.48  4937.2  258.22  4942.9  260.72
  4951.1  257.14  4959.5  260.65  4965.1  253.55  4973.6  258.43  4981.7  259.01
  4987.3  254.06  4995.8  252.72  5003.9  255.71  5026.1  258.56  5031.7  261.63
  5048.3  263.32  5337.4  264.51  5507.5  270.42  5677.5  279.88  5732.6  285.62
#Mann= 1 ,-1 , 0
  4184.7     .16       0
Bank Sta=4981.7,5026.1
XS Rating Curve= 0 ,0
Exp/Cntr=0.3,0.1

Type RM Length L Ch R = 1 ,5424    ,479,479,479
BEGIN DESCRIPTION:
UNT 044 IN BOCR 10.0
END DESCRIPTION:
XS GIS Cut Line= 3
      3757617.87     10577586.78      3758090.11     10578510.42
      3758117.89     10578864.57
#Sta/Elev= 30
  4389.9  317.75    4663  326.39  4685.2   321.2    4713  308.71  4729.6  309.02
  4735.2  301.01  4751.8  297.54  4764.4  288.06  4786.8  279.76  4796.3   280.4
  4801.9   276.3  4818.5  279.55  4824.1  274.37  4840.7  277.66  4854.2  273.03
  4862.9  276.21  4868.5   272.9  4885.1  279.69  4890.7  273.36  4907.3  277.65
    4913   272.1  4935.2  265.24    4974  258.34  4979.6   254.2  5001.6  249.16
  5033.9  260.17  5068.5  259.56  5085.1  264.28  5567.5  267.95  5782.5  282.46
#Mann= 1 ,-1 , 0
  4389.9     .16       0
Bank Sta=4974,5033.9
XS Rating Curve= 0 ,0
Exp/Cntr=0.3,0.1

Type RM Length L Ch R = 1 ,4945    ,510,510,510
BEGIN DESCRIPTION:
UNT 044 IN BOCR 9.0
END DESCRIPTION:
XS GIS Cut Line= 3
      3757249.59     10578060.17      3757649.61     10578460.19
      3758049.61     10578860.19
#Sta/Elev= 30
  4450.4  307.28  4492.9  301.03    4507  301.56  4521.1   300.3  4535.3  296.24
  4549.4  294.93  4563.6  291.09  4577.7  289.51  4591.8  285.88  4620.1   282.7
    4705  267.66  4747.4  263.06  4775.7  261.47  4832.3  261.82  4888.8   260.3
  4931.3  257.98  4959.5  258.03  4987.8  255.51    4999  247.56  5001.7  247.06
    5005  247.56  5012.6  252.32  5019.6  252.32  5030.3  258.38  5044.4  260.63
    5101  261.65  5185.8  261.55  5369.7  264.44  5482.8  271.28  5581.8  280.95
#Mann= 1 ,-1 , 0
  4450.4     .16       0
Bank Sta=4987.8,5030.3
XS Rating Curve= 0 ,0
Exp/Cntr=0.3,0.1

Type RM Length L Ch R = 1 ,4435    ,562,562,562
BEGIN DESCRIPTION:
UNT 044 IN BOCR 8.0
END DESCRIPTION:
XS GIS Cut Line= 3
      3757149.63     10578310.23      3757349.61     10578710.19
      3757749.63     10579010.21
#Sta/Elev= 30
  4539.3  291.14  4561.6  288.08  4575.6  283.93  4592.4  281.46  4606.3  281.23
  4614.7  278.41  4620.3  279.46  4628.7  278.65  4659.4  268.26  4681.8  263.96
  4687.4   265.1  4740.5  260.35  4852.3  259.11  4905.4   255.6  4964.1  255.37
  4989.6   252.7  4993.8  251.38    4997  248.11  4999.8  247.61  5008.3   248.8
  5014.6  252.78  5022.9  254.76  5043.8  255.31    5050  256.83  5114.6  255.74
  5193.8  256.72  5214.6  258.51    5350  262.86  5422.9  266.34  5486.5  273.02
#Mann= 1 ,-1 , 0
  4539.3     .16       0
Bank Sta=4989.6,5014.6
XS Rating Curve= 0 ,0
Exp/Cntr=0.3,0.1

Type RM Length L Ch R = 1 ,3873    ,483,483,483
BEGIN DESCRIPTION:
UNT 044 IN BOCR 7.0
END DESCRIPTION:
XS GIS Cut Line= 2
      3756867.92     10578628.51      3757423.43     10579399.29
#Sta/Elev= 30
  4517.1  272.74  4526.9  273.01  4547.8  268.89  4562.5  268.65  4568.7  266.19
  4598.1  263.13  4612.8  262.99    4619  261.19  4627.6  261.07  4669.3  256.14
  4742.9  255.52    4757   255.5  4864.3  255.98  4906.1  257.53  4941.7  255.33
  4971.2  251.88  4987.6  248.29  4996.9  243.13  4999.7  242.63  5002.9  243.13
  5012.9  248.73  5027.6  251.14  5092.7  256.34  5178.6  259.03  5214.1   261.3
  5228.8  261.07  5357.4  269.43  5436.3  276.59  5443.7  278.22  5467.2  278.93
#Mann= 7 ,-1 , 0
  4517.1     .16       0  4742.9     .12       0    4757     .16       0
  4987.6     .12       0  4996.9     .07       0  5002.9     .12       0
  5228.8     .16       0
Bank Sta=4971.2,5027.6
XS Rating Curve= 0 ,0
Exp/Cntr=0.3,0.1

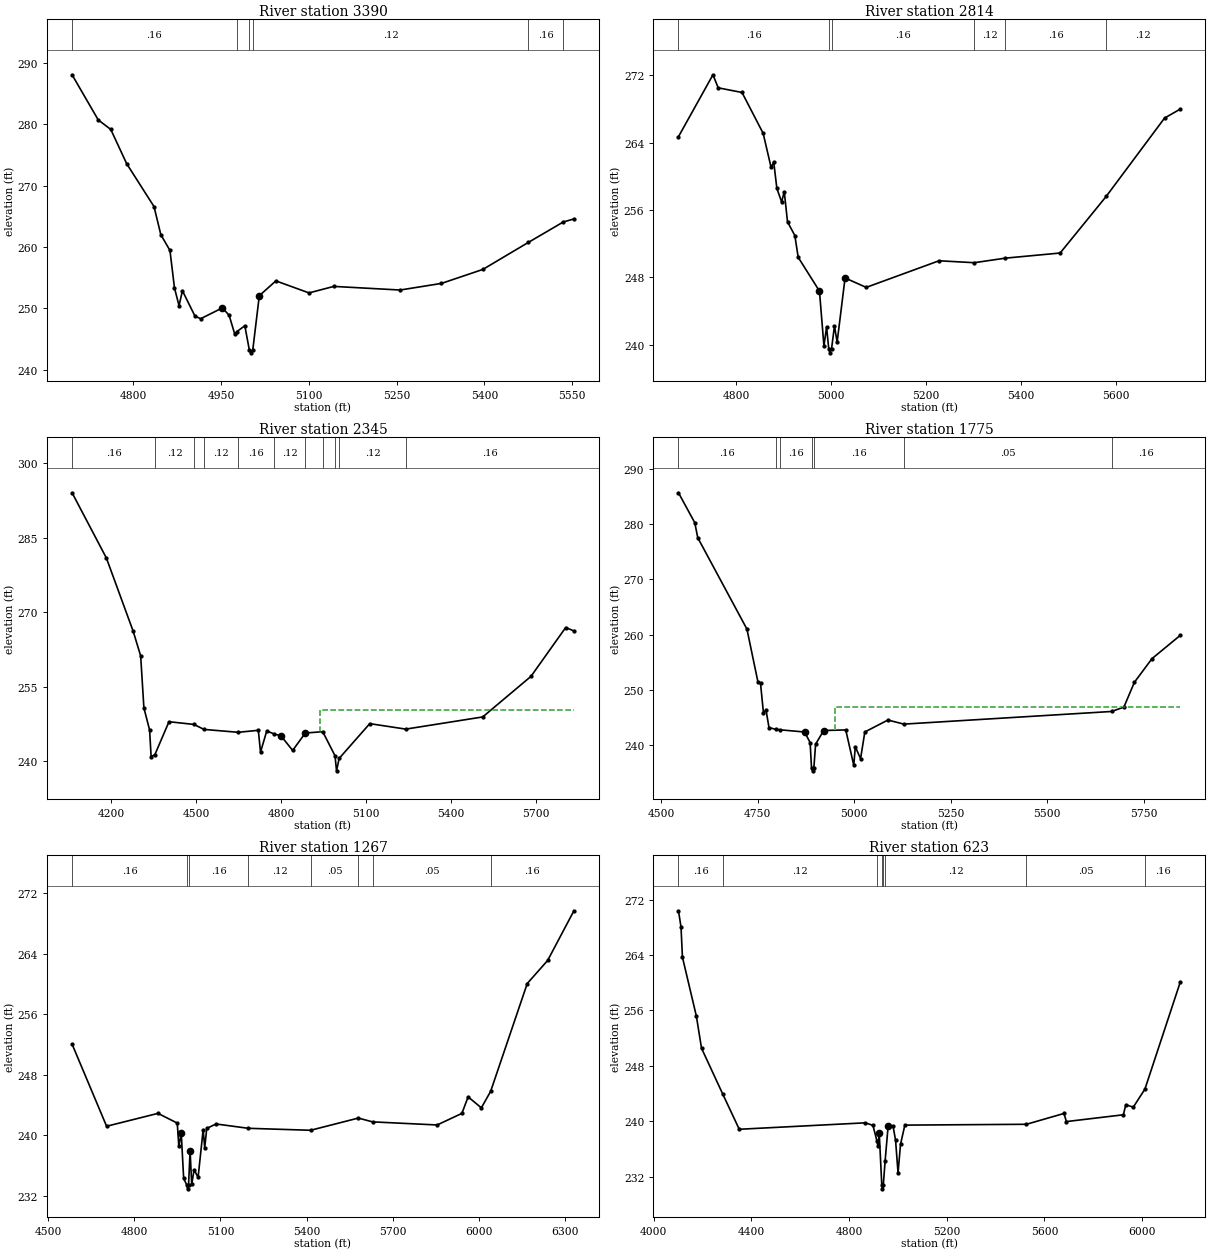
Type RM Length L Ch R = 1 ,3390    ,576,576,576
BEGIN DESCRIPTION:
UNT 044 IN BOCR 6.0
END DESCRIPTION:
XS GIS Cut Line= 3
       3756599.6     10578860.18      3756749.61     10579110.19
      3757149.58     10579510.16
#Sta/Elev= 30
  4695.8   288.1  4740.5  280.74  4761.9  279.19  4789.1   273.6  4835.8  266.61
  4847.4  262.03    4863  259.46  4870.7  253.36  4878.5  250.46  4884.3  252.89
  4905.7  248.76  4915.4  248.33  4952.4  250.09    4964  248.91  4973.8  245.78
  4977.1  246.22  4990.9  247.18  4998.5  243.27  5001.2  242.77  5004.5  243.27
  5015.6  252.08  5043.9   254.5  5100.5  252.54  5142.9   253.6  5256.1  253.01
  5326.8  254.09  5397.5  256.37  5475.3  260.78  5534.8   264.1    5553   264.6
#Mann= 6 ,-1 , 0
  4695.8     .16       0  4977.1     .12       0  4998.5     .07       0
  5004.5     .12       0  5475.3     .16       0  5534.8     .12       0
Bank Sta=4952.4,5015.6
XS Rating Curve= 0 ,0
Exp/Cntr=0.3,0.1

Type RM Length L Ch R = 1 ,2814    ,469,469,469
BEGIN DESCRIPTION:
UNT 044 IN BOCR 5.0
END DESCRIPTION:
XS GIS Cut Line= 3
      3756194.28     10578885.43      3756423.45     10579336.81
      3756845.84     10579689.96
#Sta/Elev= 30
    4679   264.7  4751.6  272.05  4762.7   270.5  4812.8  269.95  4857.3   265.1
    4874  261.06  4879.6  261.68  4886.2  258.56  4896.2  256.96  4901.8  258.17
  4908.6  254.59  4924.1  252.96  4931.1  250.38  4975.9  246.37  4985.3  239.85
  4990.9   242.1  4995.4  239.54  4998.1  239.04  5001.4  239.54  5007.5  242.24
  5013.1   240.3  5029.8  247.93  5074.3  246.81  5227.7  249.97  5301.9  249.74
  5367.1  250.28  5482.7  250.89  5579.7  257.61  5702.6  266.91  5735.8  267.98
#Mann= 6 ,-1 , 0
    4679     .16       0  4995.4     .07       0  5001.4     .16       0
  5301.9     .12       0  5367.1     .16       0  5579.7     .12       0
Bank Sta=4975.9,5029.8
XS Rating Curve= 0 ,0
Exp/Cntr=0.3,0.1

Type RM Length L Ch R = 1 ,2345    ,570,570,570
BEGIN DESCRIPTION:
UNT 044 IN BOCR 4.0
END DESCRIPTION:
XS GIS Cut Line= 3
      3755138.76      10578927.1      3755763.72     10579135.42
      3756652.64     10579809.06
#Sta/Elev= 30
  4061.6  294.06  4182.9  280.93  4277.7  266.17  4304.1  261.22  4315.5  250.76
  4335.7  246.29    4341  240.96  4354.1  241.31  4404.2  247.97  4492.9  247.42
  4527.6  246.42    4649  245.84    4720  246.24  4727.8  241.85  4749.8  246.11
  4776.6  245.49  4799.8  245.14  4841.4  242.19  4885.1  245.61    4886  245.69
  4947.7  245.96  4991.2  241.11  4996.5  238.08  5005.8  240.58  5113.9  247.58
  5241.3  246.48  5513.3  248.93  5683.9   257.1  5806.6  266.93  5835.7  266.25
#Mann= 11 ,-1 , 0
  4061.6     .16       0  4354.1     .12       0  4492.9     .16       0
  4527.6     .12       0    4649     .16       0  4776.6     .12       0
    4886     .16       0  4947.7     .12       0  4991.2     .07       0
  5005.8     .12       0  5241.3     .16       0
#XS Ineff= 2 , 0
                         4939.77          250.24
Permanent Ineff=
       F       F
Bank Sta=4799.8,4885.1
XS Rating Curve= 0 ,0
Exp/Cntr=0.3,0.1

Type RM Length L Ch R = 1 ,1775    ,508,508,508
BEGIN DESCRIPTION:
UNT 044 IN BOCR 3.0
END DESCRIPTION:
XS GIS Cut Line= 3
      3755249.62      10579210.2      3755599.61     10579510.19
       3756399.6     10579760.19
#Sta/Elev= 30
  4545.4   285.7  4587.6  280.28  4595.3  277.56  4722.6  261.02  4751.2  251.41
  4757.8  251.17  4765.4  245.82    4772  246.36  4779.7  243.19  4797.7  242.85
    4807  242.79  4871.9  242.38  4886.2  240.46  4889.8  235.85  4892.5  235.35
  4895.8  235.85  4900.4  240.18  4921.3  242.65  4978.4  242.76  4999.2  236.35
  5003.1   239.7  5016.8  237.56  5027.8  242.39  5087.6  244.55  5128.8  243.81
  5666.6   246.1  5698.4  246.89  5725.6  251.38  5771.2  255.67  5844.5  259.89
#Mann= 7 ,-1 , 0
  4545.4     .16       0  4797.7     .12       0    4807     .16       0
  4889.8     .07       0  4895.8     .16       0  5128.8     .05       0
  5666.6     .16       0
#XS Ineff= 2 , 0
                            4950           246.9
Permanent Ineff=
       F       F
Bank Sta=4871.9,4921.3
XS Rating Curve= 0 ,0
Exp/Cntr=0.3,0.1

Type RM Length L Ch R = 1 ,1267    ,644,644,644
BEGIN DESCRIPTION:
UNT 044 IN BOCR 2.0
END DESCRIPTION:
XS GIS Cut Line= 3
      3755199.61     10579460.19      3755399.61     10579860.19
       3756599.6     10580360.18
#Sta/Elev= 30
  4583.4  252.05  4703.6  241.21  4882.5  242.91  4949.6  241.63  4955.1  238.56
  4963.5   240.3  4971.9  234.32  4982.9  233.45  4985.6  232.95  4988.9  233.45
  4994.3  237.96  4999.9  233.55  5008.3  235.47  5022.2  234.47  5039.8  240.76
  5045.2  238.37  5052.3  240.93  5084.8  241.51  5197.2  240.94  5413.9  240.68
  5579.9  242.29  5629.6  241.79  5854.5  241.38  5940.6  242.91  5962.3  245.09
  6008.3  243.64  6040.7  245.82  6168.1  260.05  6239.1  263.09  6330.6  269.65
#Mann= 8 ,-1 , 0
  4583.4     .16       0  4982.9     .07       0  4988.9     .16       0
  5197.2     .12       0  5413.9     .05       0  5579.9     .07       0
  5629.6     .05       0  6040.7     .16       0
Bank Sta=4963.5,4994.3
XS Rating Curve= 0 ,0
Exp/Cntr=0.3,0.1

Type RM Length L Ch R = 1 ,623     ,0,0,0
BEGIN DESCRIPTION:
UNT 044 IN BOCR 1.0
END DESCRIPTION:
XS GIS Cut Line= 3
      3754999.62     10579360.21      3755249.61     10580160.19
      3756449.63     10580360.19
#Sta/Elev= 30
  4101.7  270.38  4112.1  268.04  4117.9  263.69    4175  255.18    4196  250.56
  4282.4  243.99  4350.5  238.87  4866.5   239.8  4897.9  239.43  4914.1  237.21
  4918.3  236.45  4923.6  238.35  4934.2  230.78    4937  230.28  4940.2  230.78
  4947.9  234.36  4960.1  239.36  4980.4  239.28  4990.5   237.3  5000.7  232.56
  5010.8   236.7  5028.5  239.47  5526.3  239.59  5679.9  241.15    5690  239.98
  5923.2  240.96  5933.3  242.41  5963.8  242.06  6011.4  244.66  6156.4  260.12
#Mann= 8 ,-1 , 0
  4101.7     .16       0  4282.4     .12       0  4914.1     .16       0
  4934.2     .07       0  4940.2     .16       0  4947.9     .12       0
  5526.3     .05       0  6011.4     .16       0
Bank Sta=4923.6,4960.1
XS Rating Curve= 0 ,0
Exp/Cntr=0.3,0.1

Chan Stop Cuts=-1
Use User Specified Reach Order=0
Composite Channel Slope=5