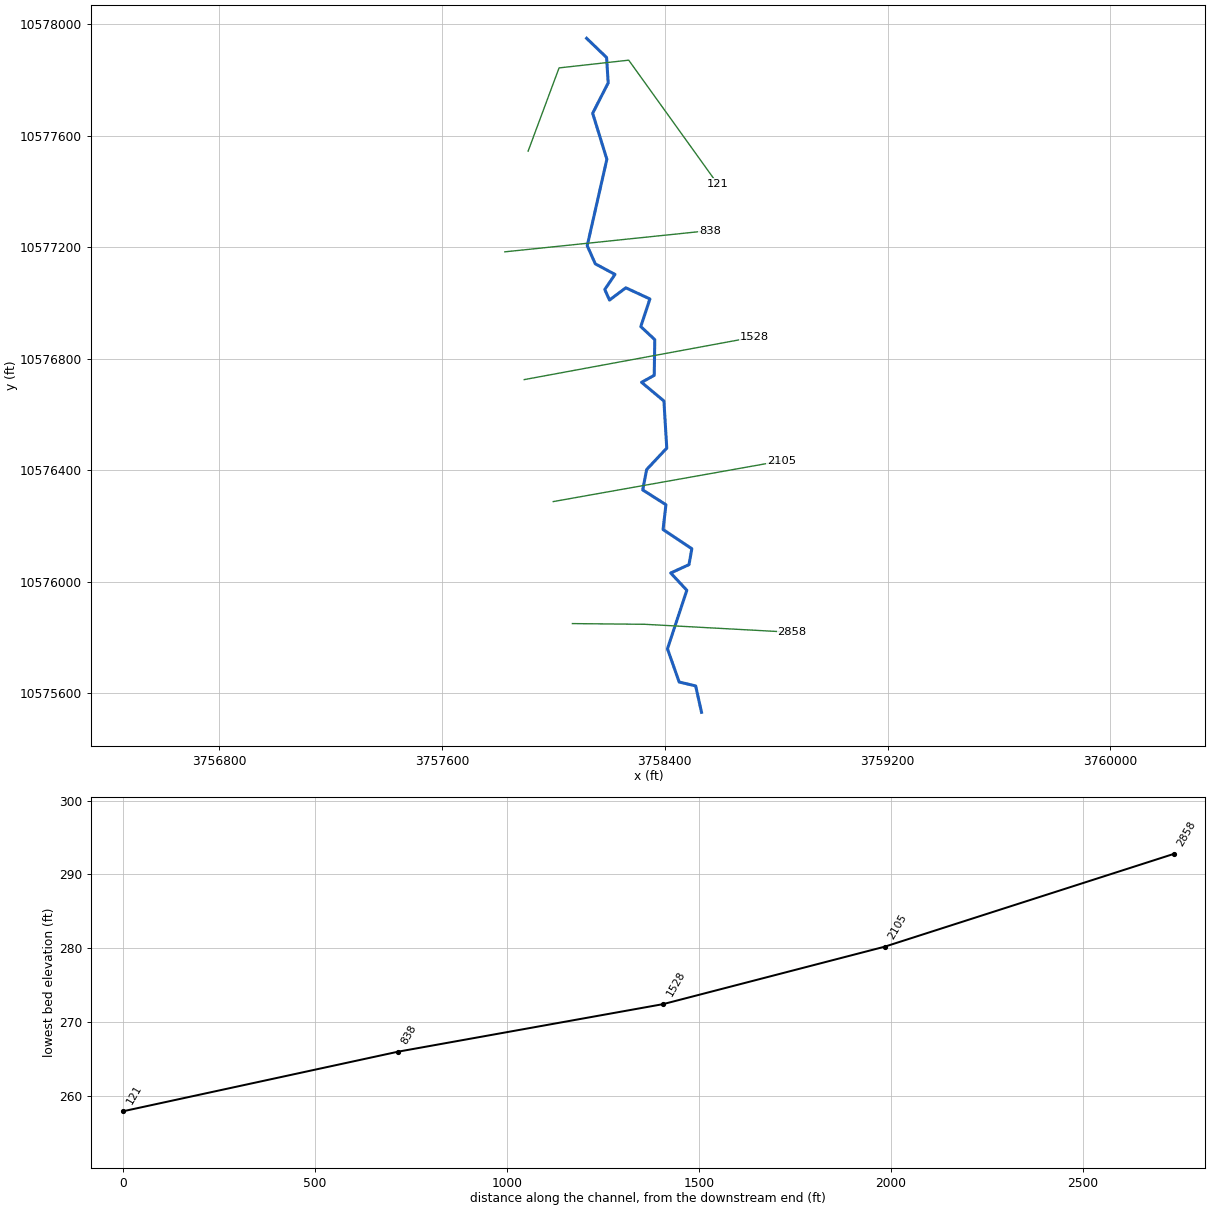
--- UNT 045 IN BOCR.prj (project) ---

Proj Title=UNT 045 IN BOCR Base Level Engineering
Current Plan=p01
Default Exp/Contr=0.3,0.1
English Units
Geom File=g01
Flow File=f01
Plan File=p01
Y Axis Title=Elevation
X Axis Title(PF)=Main Channel Distance
X Axis Title(XS)=Station
BEGIN DESCRIPTION:
UNT 045 IN BOCR
END DESCRIPTION:
DSS Export Rating Curves= 0
DSS Export Rating Curve Sorted= 0
DSS Export Volume Flow Curves= 0
DXF OffsetX= 0
DXF OffsetY= 0
DXF ScaleX= 1
DXF ScaleY= 10

--- UNT 045 IN BOCR.p01 (plan) ---

Plan Title=Multiple Run
Short Identifier=Multiple
Geom File=g01
Flow File=f01
Subcritical Flow
K Sum by GR= 0
Std Step Tol= 0.01
Critical Tol= 0.01
Num of Std Step Trials= 20
Max Error Tol= 0.3
Flow Tol Ratio= 0.001
Split Flow NTrial= 30
Split Flow Tol= 0.02
Split Flow Ratio= 0.02
Log Output Level= 0
Friction Slope Method= 1
Unsteady Friction Slope Method= 2
Unsteady Bridges Friction Slope Method= 1
Parabolic Critical Depth
Global Vel Dist=  1 , 1 , 1
Global Log Level= 0
CheckData=True
Encroach Param= -1, 0, 0, 0
BEGIN DESCRIPTION:
Multiple Run
END DESCRIPTION:

--- UNT 045 IN BOCR.f01 (steady flow) ---

Flow Title=Multiple
Program Version=4.10
Number of Profiles= 7
Profile Names=10-year,25-year,50-year,1pct_min,100-year,1pct_plu,500-year
River Rch & RM=UNT 045 IN BOCR,Reach-1         ,2858
     719     935    1101     752    1274    1797    1691
Boundary for River Rch & Prof#=UNT 045 IN BOCR,Reach-1         , 1
Up Type= 0
Dn Type= 3
Dn Slope=0.01
Boundary for River Rch & Prof#=UNT 045 IN BOCR,Reach-1         , 2
Up Type= 0
Dn Type= 3
Dn Slope=0.01
Boundary for River Rch & Prof#=UNT 045 IN BOCR,Reach-1         , 3
Up Type= 0
Dn Type= 3
Dn Slope=0.01
Boundary for River Rch & Prof#=UNT 045 IN BOCR,Reach-1         , 4
Up Type= 0
Dn Type= 3
Dn Slope=0.01
Boundary for River Rch & Prof#=UNT 045 IN BOCR,Reach-1         , 5
Up Type= 0
Dn Type= 3
Dn Slope=0.01
Boundary for River Rch & Prof#=UNT 045 IN BOCR,Reach-1         , 6
Up Type= 0
Dn Type= 3
Dn Slope=0.01
Boundary for River Rch & Prof#=UNT 045 IN BOCR,Reach-1         , 7
Up Type= 0
Dn Type= 3
Dn Slope=0.01
DSS Import GetInterval= 0
DSS Import GetPeak= 0
DSS Import FillOption= 0

--- UNT 045 IN BOCR.g01 (geometry) ---

Geom Title=Existing Conditions
Program Version=4.10

River Reach=UNT 045 IN BOCR ,Reach-1
Reach XY= 30
      3758532.07     10575532.34        3758511.       10575627.
      3758451.75       10575641.      3758409.75       10575760.
      3758479.25       10575970.       3758421.5       10576032.
        3758487.       10576062.      3758497.25       10576119.
        3758394.       10576188.      3758404.25       10576277.
        3758321.       10576330.        3758335.       10576403.
      3758407.25       10576480.        3758397.       10576649.
      3758316.75       10576716.      3758362.25       10576741.
      3758364.25       10576869.        3758314.       10576916.
      3758346.75       10577015.      3758260.25       10577055.
      3758201.75       10577011.      3758184.75       10577049.
       3758221.5       10577103.      3758150.75       10577141.
      3758121.75       10577206.      3758192.25       10577516.
      3758141.25       10577681.        3758197.       10577790.
      3758191.25       10577881.       3758119.5       10577950.

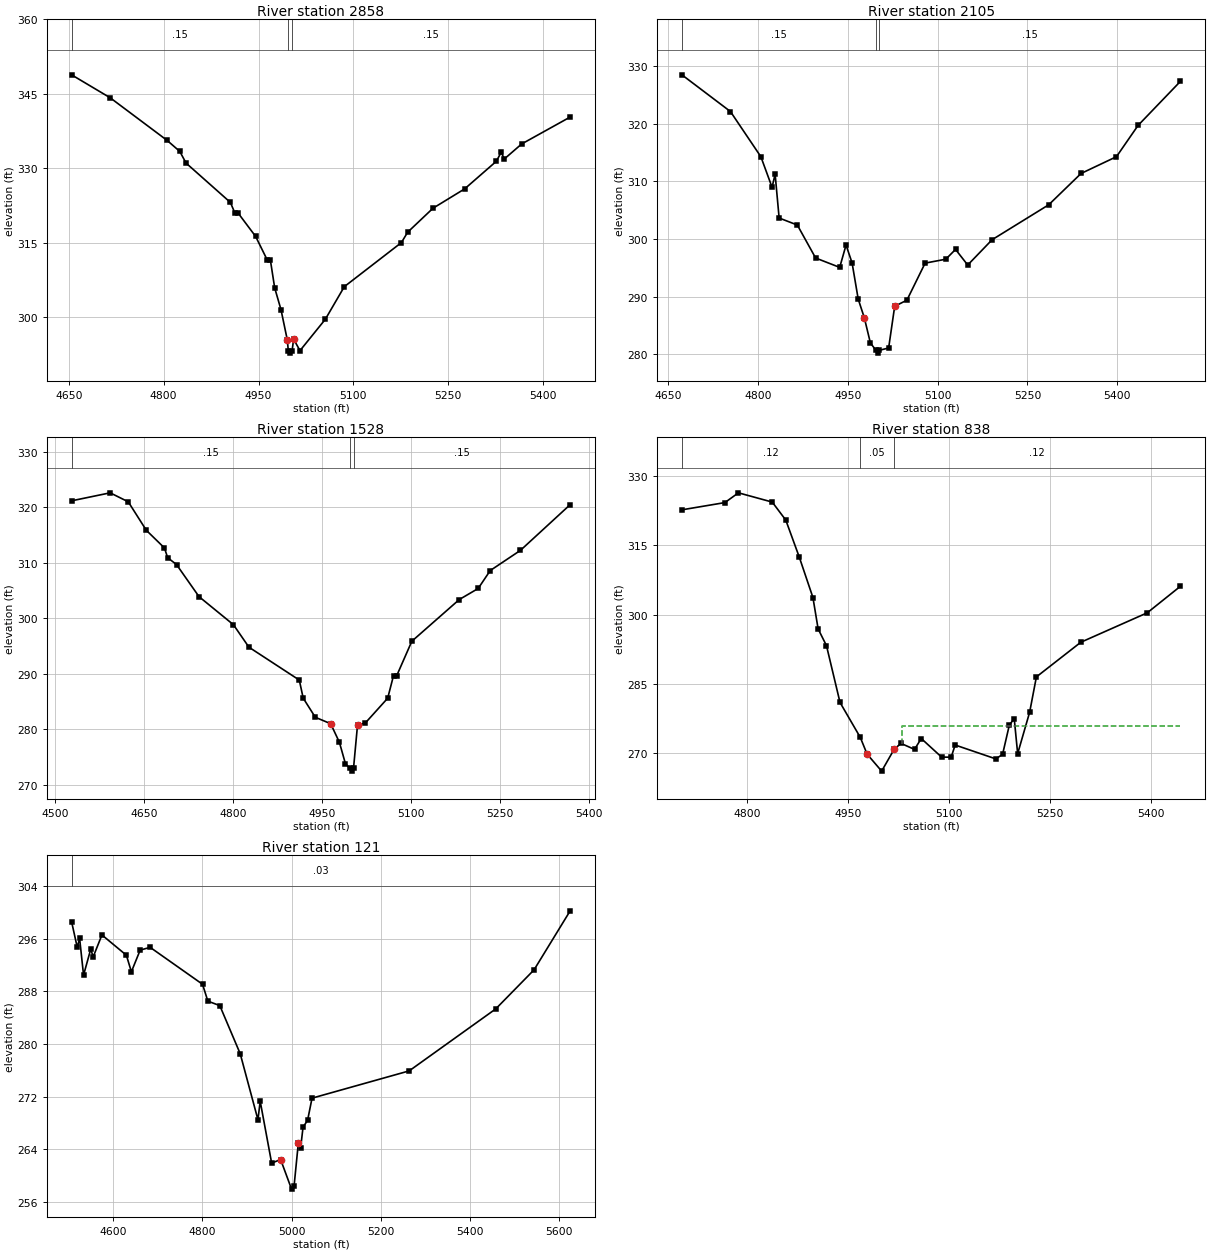
Type RM Length L Ch R = 1 ,2858    ,753,753,753
BEGIN DESCRIPTION:
UNT 045 IN BOCR 5.0
END DESCRIPTION:
XS GIS Cut Line= 3
      3758068.63      10575850.6        3758329.       10575848.
      3758856.15     10575819.43
#Sta/Elev= 30
  4654.4  348.81  4715.4  344.19  4805.4  335.61  4825.4   333.4  4835.4  331.04
  4905.4  323.13  4912.6  320.99  4917.6  320.99  4945.4  316.27  4963.6  311.57
  4968.6  311.59  4975.5  305.92  4985.5  301.52  4995.5  295.41    4997  293.28
  4999.8  292.78    5003  293.28  5005.5  295.58  5015.5  293.28  5055.6   299.6
  5085.6  306.16  5175.8  315.03  5185.8  317.13  5225.8  321.95  5275.9  325.85
    5326  331.41  5333.6  333.22  5338.6  331.87    5366  334.89  5442.7  340.31
#Mann= 3 ,-1 , 0
  4654.4     .15       0    4997     .05       0    5003     .15       0
Bank Sta=4995.5,5005.5
XS Rating Curve= 0 ,0
Exp/Cntr=0.3,0.1

Type RM Length L Ch R = 1 ,2105    ,577,577,577
BEGIN DESCRIPTION:
Mapping XS 490e2bb7
END DESCRIPTION:
XS GIS Cut Line= 2
      3757999.87      10576288.2      3758819.29     10576434.03
#Sta/Elev= 30
  4673.2  328.51  4754.2  322.14    4805   314.3  4823.7  308.99  4828.8  311.27
  4835.5  303.66  4865.9  302.44  4896.4  296.72  4936.6  295.09  4947.2  298.97
  4957.3  295.86  4967.5  289.59  4977.7  286.35  4987.8  281.99    4997  280.71
  4999.8  280.21    5003  280.71  5018.3   281.1  5028.4  288.34  5048.8   289.4
  5079.2  295.83  5113.7  296.51    5130  298.21  5150.3   295.5    5191  299.89
  5285.6  305.96  5339.5  311.39  5398.6   314.3  5434.7  319.73  5505.5  327.39
#Mann= 3 ,-1 , 0
  4673.2     .15       0    4997     .05       0    5003     .15       0
Bank Sta=4977.7,5028.4
XS Rating Curve= 0 ,0
Exp/Cntr=0.3,0.1

Type RM Length L Ch R = 1 ,1528    ,690,690,690
BEGIN DESCRIPTION:
Mapping XS 209f3ba3
END DESCRIPTION:
XS GIS Cut Line= 2
      3757895.68      10576725.7      3758722.08     10576878.48
#Sta/Elev= 30
  4527.8  321.17  4592.8  322.61  4623.3  320.99  4653.8  315.85  4684.3  312.67
  4689.7  310.92  4704.7  309.67  4742.6  303.89  4800.6  298.83  4826.7  294.78
  4911.6  288.85  4918.2  285.59  4938.6  282.14  4964.5  280.98  4979.2  277.63
  4989.4  273.76    4997  272.93  4999.8  272.43    5003  272.93  5009.8  280.79
  5022.5  281.06  5060.6  285.58  5070.4  289.64  5075.5  289.56  5101.3  295.85
  5181.3  303.37  5213.1  305.36  5233.5   308.6  5284.3  312.23  5368.2  320.48
#Mann= 3 ,-1 , 0
  4527.8     .15       0    4997     .05       0    5003     .15       0
Bank Sta=4964.5,5009.8
XS Rating Curve= 0 ,0
Exp/Cntr=0.3,0.1

Type RM Length L Ch R = 1 ,838     ,717,717,717
BEGIN DESCRIPTION:
Mapping XS c69f7b54
END DESCRIPTION:
XS GIS Cut Line= 2
      3757826.18     10577184.03      3758562.33     10577260.42
#Sta/Elev= 30
  4703.3  322.73  4767.1   324.3  4787.2  326.42  4837.4  324.41  4857.5   320.5
  4877.7  312.39  4897.8  303.68  4905.5  296.87  4917.9  293.23    4938   280.9
  4968.1  273.31  4978.2  269.68  4999.8  265.99  5018.4  270.75  5028.5  272.01
  5048.6  270.71  5058.6  273.07  5088.8  269.03    5103  269.02  5108.9  271.66
  5169.2  268.65  5179.3  269.62  5189.3  275.97  5196.6  277.41  5201.7  269.78
  5219.5  278.79  5229.5  286.45  5295.4  293.97  5394.1  300.37  5443.4  306.14
#Mann= 3 ,-1 , 0
  4703.3     .12       0  4968.1     .05       0  5018.4     .12       0
#XS Ineff= 2 , 0
                         5029.55          275.86
Permanent Ineff=
       F       F
Bank Sta=4978.2,5018.4
XS Rating Curve= 0 ,0
Exp/Cntr=0.3,0.1

Type RM Length L Ch R = 1 ,121     ,0,0,0
BEGIN DESCRIPTION:
UNT 045 IN BOCR 1.0
END DESCRIPTION:
XS GIS Cut Line= 4
      3757909.54     10577545.11      3758020.67     10577843.75
      3758270.67     10577871.53       3758590.1     10577427.11
#Sta/Elev= 30
  4506.8  298.62  4519.4  294.74  4524.8  296.07  4533.6  290.49  4549.8  294.47
  4555.1  293.25  4574.8  296.61  4629.6  293.52  4640.8     291  4660.5   294.3
  4682.9  294.72  4800.3   289.1  4812.2  286.53    4839  285.85  4884.8  278.51
  4924.5  268.47  4929.5   271.3  4955.2  261.87  4975.3  262.42  4999.8  257.91
  5005.5  258.41    5015  264.92  5020.1  264.16  5025.6  267.36  5035.7  268.37
  5045.7  271.76  5263.4  275.91  5457.5  285.35  5543.4   291.3  5624.3  300.28
#Mann= 1 ,-1 , 0
  4506.8     .03       0
Bank Sta=4975.3,5015
XS Rating Curve= 0 ,0
Exp/Cntr=0.3,0.1

Chan Stop Cuts=-1
Use User Specified Reach Order=0
Composite Channel Slope=5