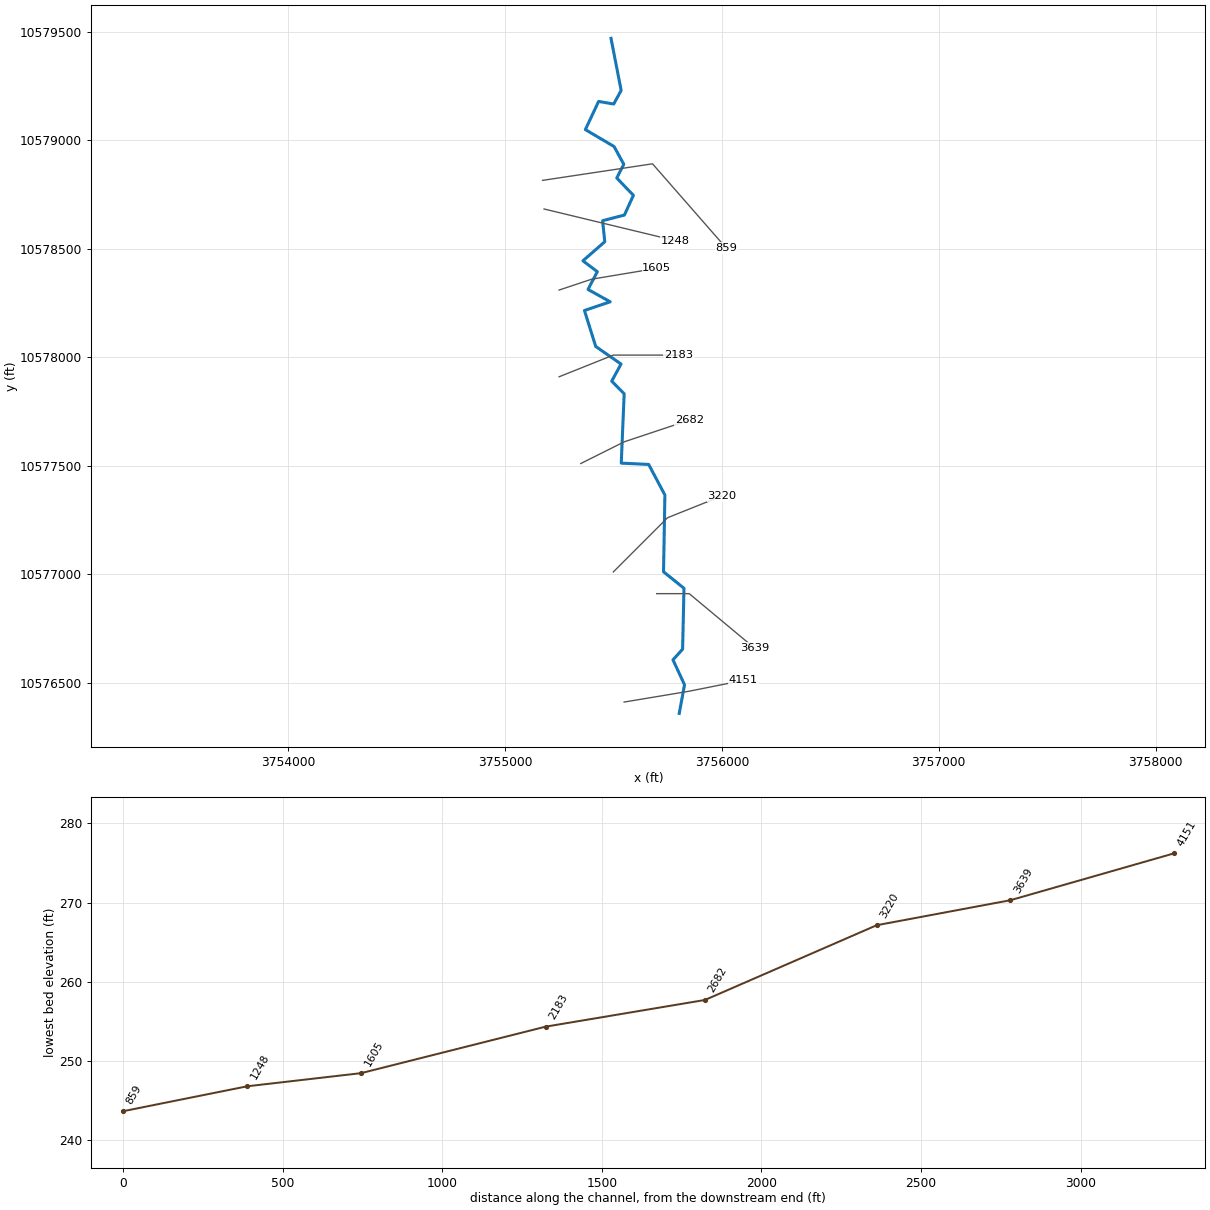
--- UNT 046 IN BOCR.prj (project) ---

Proj Title=UNT 046 IN BOCR Base Level Engineering
Current Plan=p01
Default Exp/Contr=0.3,0.1
English Units
Geom File=g01
Flow File=f01
Plan File=p01
Y Axis Title=Elevation
X Axis Title(PF)=Main Channel Distance
X Axis Title(XS)=Station
BEGIN DESCRIPTION:
UNT 046 IN BOCR
END DESCRIPTION:
DSS Export Rating Curves= 0
DSS Export Rating Curve Sorted= 0
DSS Export Volume Flow Curves= 0
DXF OffsetX= 0
DXF OffsetY= 0
DXF ScaleX= 1
DXF ScaleY= 10

--- UNT 046 IN BOCR.p01 (plan) ---

Plan Title=Multiple Run
Short Identifier=Multiple
Geom File=g01
Flow File=f01
Subcritical Flow
K Sum by GR= 0
Std Step Tol= 0.01
Critical Tol= 0.01
Num of Std Step Trials= 20
Max Error Tol= 0.3
Flow Tol Ratio= 0.001
Split Flow NTrial= 30
Split Flow Tol= 0.02
Split Flow Ratio= 0.02
Log Output Level= 0
Friction Slope Method= 1
Unsteady Friction Slope Method= 2
Unsteady Bridges Friction Slope Method= 1
Parabolic Critical Depth
Global Vel Dist=  1 , 1 , 1
Global Log Level= 0
CheckData=True
Encroach Param= -1, 0, 0, 0
BEGIN DESCRIPTION:
Multiple Run
END DESCRIPTION:

--- UNT 046 IN BOCR.f01 (steady flow) ---

Flow Title=Multiple
Program Version=4.10
Number of Profiles= 7
Profile Names=10-year,25-year,50-year,1pct_min,100-year,1pct_plu,500-year
River Rch & RM=UNT 046 IN BOCR,Reach-1         ,4151
     375     497     596     526     712     963    1019
Boundary for River Rch & Prof#=UNT 046 IN BOCR,Reach-1         , 1
Up Type= 0
Dn Type= 3
Dn Slope=0.008
Boundary for River Rch & Prof#=UNT 046 IN BOCR,Reach-1         , 2
Up Type= 0
Dn Type= 3
Dn Slope=0.008
Boundary for River Rch & Prof#=UNT 046 IN BOCR,Reach-1         , 3
Up Type= 0
Dn Type= 3
Dn Slope=0.008
Boundary for River Rch & Prof#=UNT 046 IN BOCR,Reach-1         , 4
Up Type= 0
Dn Type= 3
Dn Slope=0.008
Boundary for River Rch & Prof#=UNT 046 IN BOCR,Reach-1         , 5
Up Type= 0
Dn Type= 3
Dn Slope=0.008
Boundary for River Rch & Prof#=UNT 046 IN BOCR,Reach-1         , 6
Up Type= 0
Dn Type= 3
Dn Slope=0.008
Boundary for River Rch & Prof#=UNT 046 IN BOCR,Reach-1         , 7
Up Type= 0
Dn Type= 3
Dn Slope=0.008
DSS Import GetInterval= 0
DSS Import GetPeak= 0
DSS Import FillOption= 0

--- UNT 046 IN BOCR.g01 (geometry) ---

Geom Title=Existing Conditions
Program Version=4.10

River Reach=UNT 046 IN BOCR ,Reach-1
Reach XY= 30
      3755803.75       10576358.        3755828.       10576490.
      3755774.75       10576605.      3755819.25       10576654.
       3755825.5       10576935.      3755731.25       10577011.
       3755737.5       10577365.      3755662.75       10577506.
      3755536.25       10577512.      3755549.75       10577832.
      3755492.25       10577890.      3755535.25       10577969.
       3755418.5       10578050.       3755366.5       10578216.
       3755485.5       10578256.        3755383.       10578313.
        3755426.       10578395.       3755359.5       10578445.
      3755460.25       10578533.      3755450.25       10578630.
      3755550.75       10578656.      3755592.25       10578747.
       3755515.5       10578827.        3755548.       10578890.
      3755503.25       10578972.      3755370.75       10579050.
      3755431.75       10579180.       3755501.5       10579168.
      3755535.75       10579231.        3755489.       10579471.

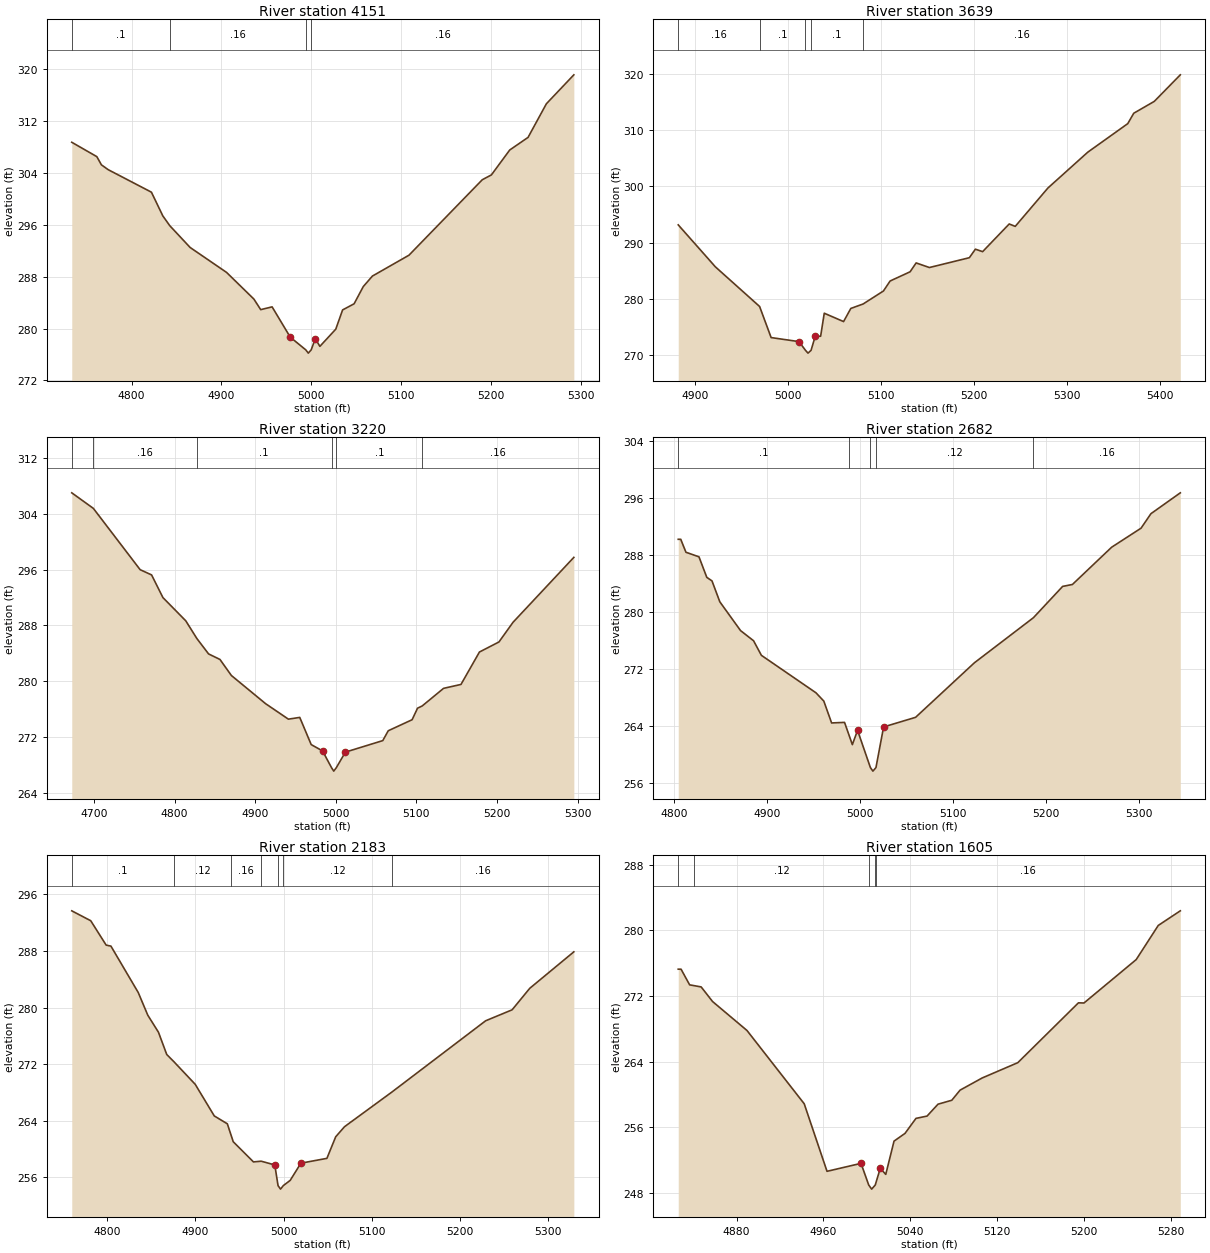
Type RM Length L Ch R = 1 ,4151    ,512,512,512
BEGIN DESCRIPTION:
UNT 046 IN BOCR 7.0
END DESCRIPTION:
XS GIS Cut Line= 3
      3755549.58     10576410.18      3755849.61     10576460.19
      3756099.59     10576510.19
#Sta/Elev= 30
  4733.3  308.66  4761.2  306.45  4766.3  305.19  4773.9  304.44    4822  300.98
  4834.7  297.33  4842.4  295.83  4865.1  292.47  4905.7  288.63  4936.1  284.53
  4943.7   282.9  4956.4  283.33  4976.6  278.67  4993.9  276.71  4996.7  276.21
  4999.9  276.71  5004.5  278.43  5009.6  277.25  5027.3   279.9  5034.9  282.86
  5047.7   283.8  5057.9  286.45  5068.1  288.07  5108.8  291.28  5190.4  302.89
  5200.6  303.64    5221  307.47  5241.4  309.41  5261.8  314.58  5292.4  319.04
#Mann= 4 ,-1 , 0
  4733.3      .1       0  4842.4     .16       0  4993.9     .07       0
  4999.9     .16       0
Bank Sta=4976.6,5004.5
XS Rating Curve= 0 ,0
Exp/Cntr=0.3,0.1

Type RM Length L Ch R = 1 ,3639    ,419,419,419
BEGIN DESCRIPTION:
UNT 046 IN BOCR 6.0
END DESCRIPTION:
XS GIS Cut Line= 3
      3755699.61     10576910.19      3755849.61     10576910.19
       3756149.6      10576660.2
#Sta/Elev= 30
  4881.5  293.15  4921.5  285.67  4969.1  278.61  4981.5  273.07  5011.5  272.35
  5018.5   270.8  5021.2   270.3  5024.5   270.8    5029  273.31  5034.8  273.31
  5038.7  277.41  5059.5  275.92  5067.3  278.26  5080.6  279.06  5102.4  281.37
  5109.6  283.15  5131.1  284.79  5137.6  286.37  5151.9  285.55  5194.9   287.3
  5201.4  288.82  5209.2  288.38  5237.8  293.31  5244.3  292.88  5279.5  299.72
  5322.4   306.1  5365.4  311.18  5371.9  313.04    5394  315.15    5422  319.88
#Mann= 5 ,-1 , 0
  4881.5     .16       0  4969.1      .1       0  5018.5     .07       0
  5024.5      .1       0  5080.6     .16       0
Bank Sta=5011.5,5029
XS Rating Curve= 0 ,0
Exp/Cntr=0.3,0.1

Type RM Length L Ch R = 1 ,3220    ,538,538,538
BEGIN DESCRIPTION:
UNT 046 IN BOCR 5.0
END DESCRIPTION:
XS GIS Cut Line= 3
      3755499.63     10577010.21      3755749.61     10577260.19
      3755999.63      10577360.2
#Sta/Elev= 30
  4672.5  306.98  4699.3  304.75  4757.3  295.98  4771.5  295.23  4785.6  291.98
  4813.9  288.66  4827.7  286.12  4842.2  283.92  4856.3  283.13  4870.5  280.83
  4912.9   276.8  4941.2  274.58  4955.3  274.83  4969.5  270.94  4983.6  270.03
  4994.7  267.64  4997.5  267.14  5000.7  267.64  5011.9  269.86  5058.3  271.51
  5065.1  272.92  5094.7   274.5  5101.4  276.15  5107.2  276.47  5133.7  278.99
  5155.3  279.55  5178.2  284.19  5202.4  285.63  5219.9  288.45  5295.3  297.74
#Mann= 6 ,-1 , 0
  4672.5      .1       0  4699.3     .16       0  4827.7      .1       0
  4994.7     .07       0  5000.7      .1       0  5107.2     .16       0
Bank Sta=4983.6,5011.9
XS Rating Curve= 0 ,0
Exp/Cntr=0.3,0.1

Type RM Length L Ch R = 1 ,2682    ,499,499,499
BEGIN DESCRIPTION:
UNT 046 IN BOCR 4.0
END DESCRIPTION:
XS GIS Cut Line= 3
      3755349.65     10577510.21      3755549.61     10577610.19
      3755849.62     10577710.19
#Sta/Elev= 30
  4804.4  290.23  4807.1  290.23  4812.7  288.41  4826.7  287.77  4835.1  284.89
  4840.7  284.39  4849.1  281.46  4871.4  277.42  4885.4  275.99  4893.8  273.95
  4952.5  268.69  4960.9  267.53  4969.3  264.46  4983.2  264.54  4987.8  262.83
  4991.6  261.42  4997.2  263.42    5011   258.2  5013.7   257.7    5017   258.2
  5025.2   263.9  5059.6  265.25  5122.8   272.9  5186.3  279.23  5217.7  283.62
  5228.2  283.89  5270.4  289.12    5302  291.79  5312.6  293.82  5344.2  296.75
#Mann= 5 ,-1 , 0
  4804.4      .1       0  4987.8     .12       0    5011     .07       0
    5017     .12       0  5186.3     .16       0
Bank Sta=4997.2,5025.2
XS Rating Curve= 0 ,0
Exp/Cntr=0.3,0.1

Type RM Length L Ch R = 1 ,2183    ,578,578,578
BEGIN DESCRIPTION:
UNT 046 IN BOCR 3.0
END DESCRIPTION:
XS GIS Cut Line= 3
      3755249.61     10577910.19      3755499.61     10578010.19
      3755799.65     10578010.19
#Sta/Elev= 30
  4759.8  293.69  4781.3  292.29  4798.8  288.84  4804.2   288.7  4835.2  282.13
    4846  278.93  4858.1  276.52  4867.5  273.37  4875.7  272.34  4899.8  269.15
  4921.4  264.68  4936.2  263.57  4940.5  261.94  4942.9  261.03  4965.8  258.18
  4974.6  258.28    4990  257.75  4993.7  254.83  4996.5  254.33  4999.7  254.83
  5007.5  255.57  5019.6     258  5049.1  258.68  5059.1  261.74  5069.1  263.16
  5122.9  268.07  5229.1  278.14  5259.1  279.69  5279.1  282.73  5329.1  287.89
#Mann= 7 ,-1 , 0
  4759.8      .1       0  4875.7     .12       0  4940.5     .16       0
  4974.6     .12       0  4993.7     .07       0  4999.7     .12       0
  5122.9     .16       0
Bank Sta=4990,5019.6
XS Rating Curve= 0 ,0
Exp/Cntr=0.3,0.1

Type RM Length L Ch R = 1 ,1605    ,357,357,357
BEGIN DESCRIPTION:
UNT 046 IN BOCR 2.0
END DESCRIPTION:
XS GIS Cut Line= 3
       3755249.6     10578310.19      3755399.61     10578360.19
      3755699.65      10578410.2
#Sta/Elev= 30
  4826.3  275.26  4828.9  275.26  4836.8  273.35    4841  273.25  4847.4   273.1
  4857.9  271.32  4889.6  267.79  4942.3  258.86  4963.3  250.63  4994.6   251.6
  5001.7  248.96  5004.4  248.46  5007.7  248.96  5008.5  249.31  5012.3  250.98
  5017.4  250.26    5025  254.31  5035.1  255.25  5045.2  257.08  5055.4  257.36
  5065.5  258.81  5078.2  259.29  5085.8  260.52  5106.1     262    5139  263.87
  5194.8  271.16  5199.9  271.14    5248  276.43  5268.3  280.59  5288.6  282.37
#Mann= 5 ,-1 , 0
  4826.3      .1       0    4841     .12       0  5001.7     .07       0
  5007.7     .12       0  5008.5     .16       0
Bank Sta=4994.6,5012.3
XS Rating Curve= 0 ,0
Exp/Cntr=0.3,0.1

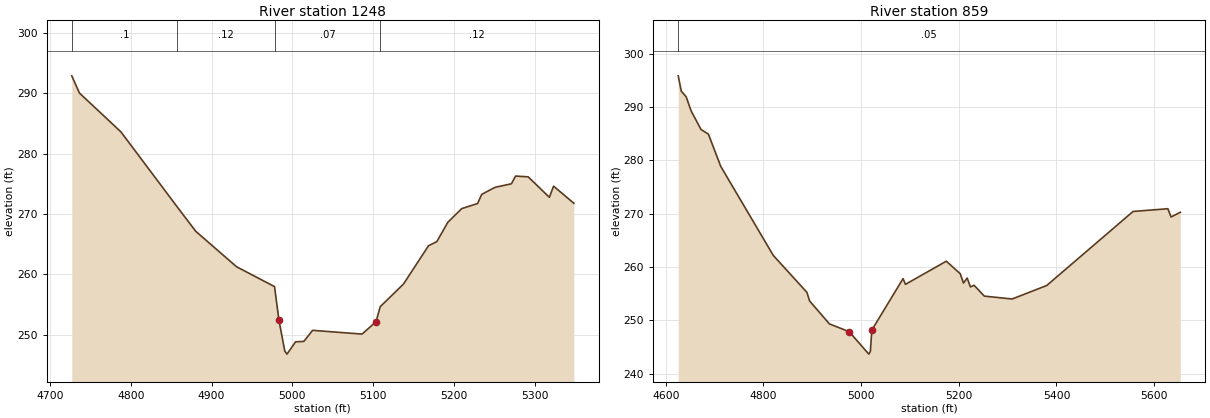
Type RM Length L Ch R = 1 ,1248    ,389,389,389
BEGIN DESCRIPTION:
Mapping XS 0689d3d0
END DESCRIPTION:
XS GIS Cut Line= 2
      3755180.36     10578684.04      3755784.51     10578538.21
#Sta/Elev= 30
    4727  292.89  4736.5  290.04  4787.9   283.6  4857.5  271.19  4880.5  267.14
    4931  261.27    4978  257.98  4983.4  252.47  4990.7   247.3  4993.4   246.8
    5004  248.84  5014.3  248.91  5025.1  250.74  5086.3  250.12  5103.7  252.17
  5108.8  254.65  5137.7  258.42  5168.6  264.75  5178.9  265.43  5192.6  268.65
  5209.7   270.9  5229.3  271.74  5234.5  273.26  5250.9  274.42  5271.2  275.01
  5276.4  276.29    5292  276.16  5318.2  272.77  5323.4  274.62  5348.5  271.79
#Mann= 4 ,-1 , 0
    4727      .1       0  4857.5     .12       0    4978     .07       0
  5108.8     .12       0
Bank Sta=4983.4,5103.7
XS Rating Curve= 0 ,0
Exp/Cntr=0.3,0.1

Type RM Length L Ch R = 1 ,859     ,0,0,0
BEGIN DESCRIPTION:
UNT 046 IN BOCR 1.0
END DESCRIPTION:
XS GIS Cut Line= 3
      3755173.46     10578815.98      3755680.39     10578892.37
      3756019.95      10578504.3
#Sta/Elev= 30
  4625.4  295.85  4631.6  292.98  4641.7  291.91  4651.8  289.27  4672.1  285.78
  4687.2  284.92  4712.5  278.86  4820.1  262.16    4889  255.23  4894.5  253.62
    4935  249.32  4975.5  247.86  5015.7  243.65  5018.9  244.15  5021.9  248.16
  5085.8  257.81  5090.8  256.74  5174.5  261.08    5203  258.73  5209.6  256.98
  5217.2  257.92  5223.8  256.26  5231.4  256.56  5252.3  254.53  5309.3  253.99
  5380.1  256.52    5557  270.41  5628.2  270.92  5634.8  269.37  5653.7  270.26
#Mann= 1 ,-1 , 0
  4625.4     .05       0
Bank Sta=4975.5,5021.9
XS Rating Curve= 0 ,0
Exp/Cntr=0.3,0.1

Chan Stop Cuts=-1
Use User Specified Reach Order=0
Composite Channel Slope=5