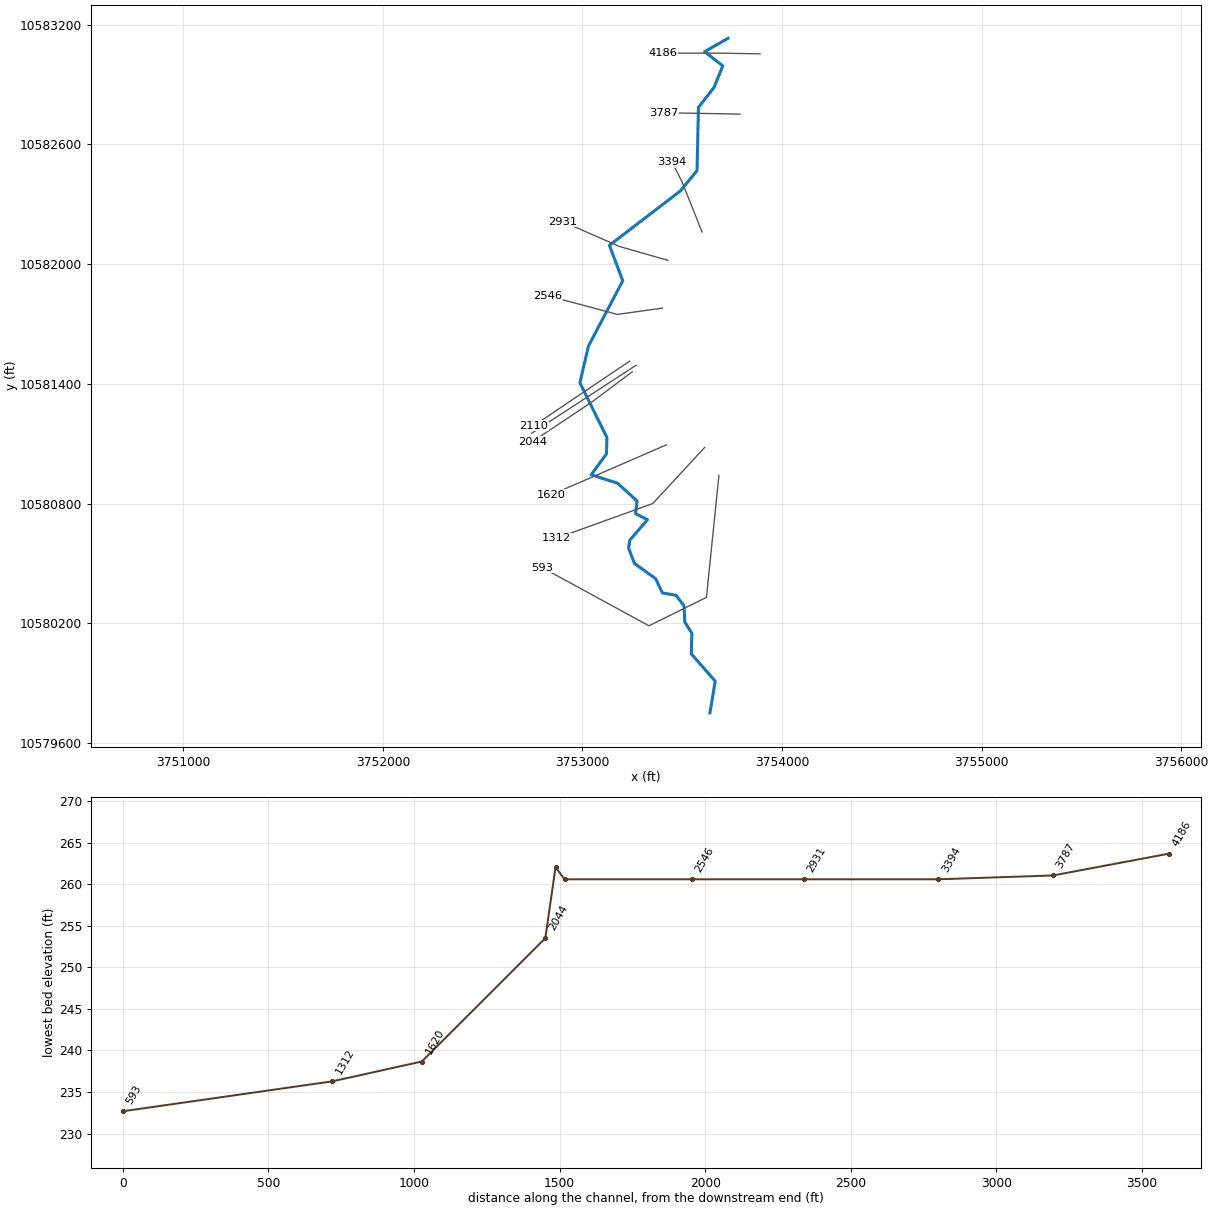
--- UNT 047 IN BOCR.prj (project) ---

Proj Title=UNT 047 IN BOCR Base Level Engineering
Current Plan=p01
Default Exp/Contr=0.3,0.1
English Units
Geom File=g01
Flow File=f01
Plan File=p01
BEGIN DESCRIPTION:
UNT 047 IN BOCR
END DESCRIPTION:

--- UNT 047 IN BOCR.p01 (plan) ---

Plan Title=Multiple Run
Short Identifier=Multiple
Geom File=g01
Flow File=f01
Subcritical Flow
K Sum by GR= 0
Std Step Tol= 0.01
Critical Tol= 0.01
Num of Std Step Trials= 20
Max Error Tol= 0.3
Flow Tol Ratio= 0.001
Split Flow NTrial= 30
Split Flow Tol= 0.02
Split Flow Ratio= 0.02
Log Output Level= 0
Friction Slope Method= 1
Unsteady Friction Slope Method= 2
Unsteady Bridges Friction Slope Method= 1
Parabolic Critical Depth
Global Vel Dist=  1 , 1 , 1
Global Log Level= 0
CheckData=True
Encroach Param= -1, 0, 0, 0
BEGIN DESCRIPTION:
Multiple Run
END DESCRIPTION:

--- UNT 047 IN BOCR.f01 (steady flow) ---

Flow Title=Multiple
Number of Profiles=7
Profile Names=10-year,25-year,50-year,1pct_min,100-year,1pct_plu,500-year
River Rch & RM= UNT 047 IN BOCR,Reach-1,4186
     342     444     524     455     615     832     851
Boundary for River Rch & Prof#=UNT 047 IN BOCR,Reach-1,1
Up Type=0
Dn Type=3
Dn Slope=0.005
Boundary for River Rch & Prof#=UNT 047 IN BOCR,Reach-1,2
Up Type=0
Dn Type=3
Dn Slope=0.005
Boundary for River Rch & Prof#=UNT 047 IN BOCR,Reach-1,3
Up Type=0
Dn Type=3
Dn Slope=0.005
Boundary for River Rch & Prof#=UNT 047 IN BOCR,Reach-1,4
Up Type=0
Dn Type=3
Dn Slope=0.005
Boundary for River Rch & Prof#=UNT 047 IN BOCR,Reach-1,5
Up Type=0
Dn Type=3
Dn Slope=0.005
Boundary for River Rch & Prof#=UNT 047 IN BOCR,Reach-1,6
Up Type=0
Dn Type=3
Dn Slope=0.005
Boundary for River Rch & Prof#=UNT 047 IN BOCR,Reach-1,7
Up Type=0
Dn Type=3
Dn Slope=0.005

--- UNT 047 IN BOCR.g01 (geometry) ---

Geom Title=Existing Conditions

River Reach=UNT 047 IN BOCR,Reach-1
Reach XY= 30
      3753729.38     10583131.03      3753612.25     10583064.00
      3753703.25     10582993.00      3753659.50     10582885.00
      3753581.25     10582785.00      3753574.25     10582468.00
      3753490.16     10582365.75      3753135.25     10582094.00
      3753202.00     10581916.00      3753030.25     10581589.00
      3752987.25     10581405.00      3753122.75     10581131.00
      3753120.50     10581049.00      3753043.75     10580944.00
      3753175.75     10580902.00      3753273.75     10580813.00
      3753266.25     10580749.00      3753326.00     10580719.00
      3753237.25     10580616.00      3753231.50     10580576.00
      3753260.25     10580500.00      3753366.50     10580424.00
      3753400.75     10580352.00      3753469.25     10580340.00
      3753509.00     10580287.00      3753513.00     10580206.00
      3753548.50     10580150.00      3753545.50     10580047.00
      3753665.25     10579910.00      3753638.75     10579751.00

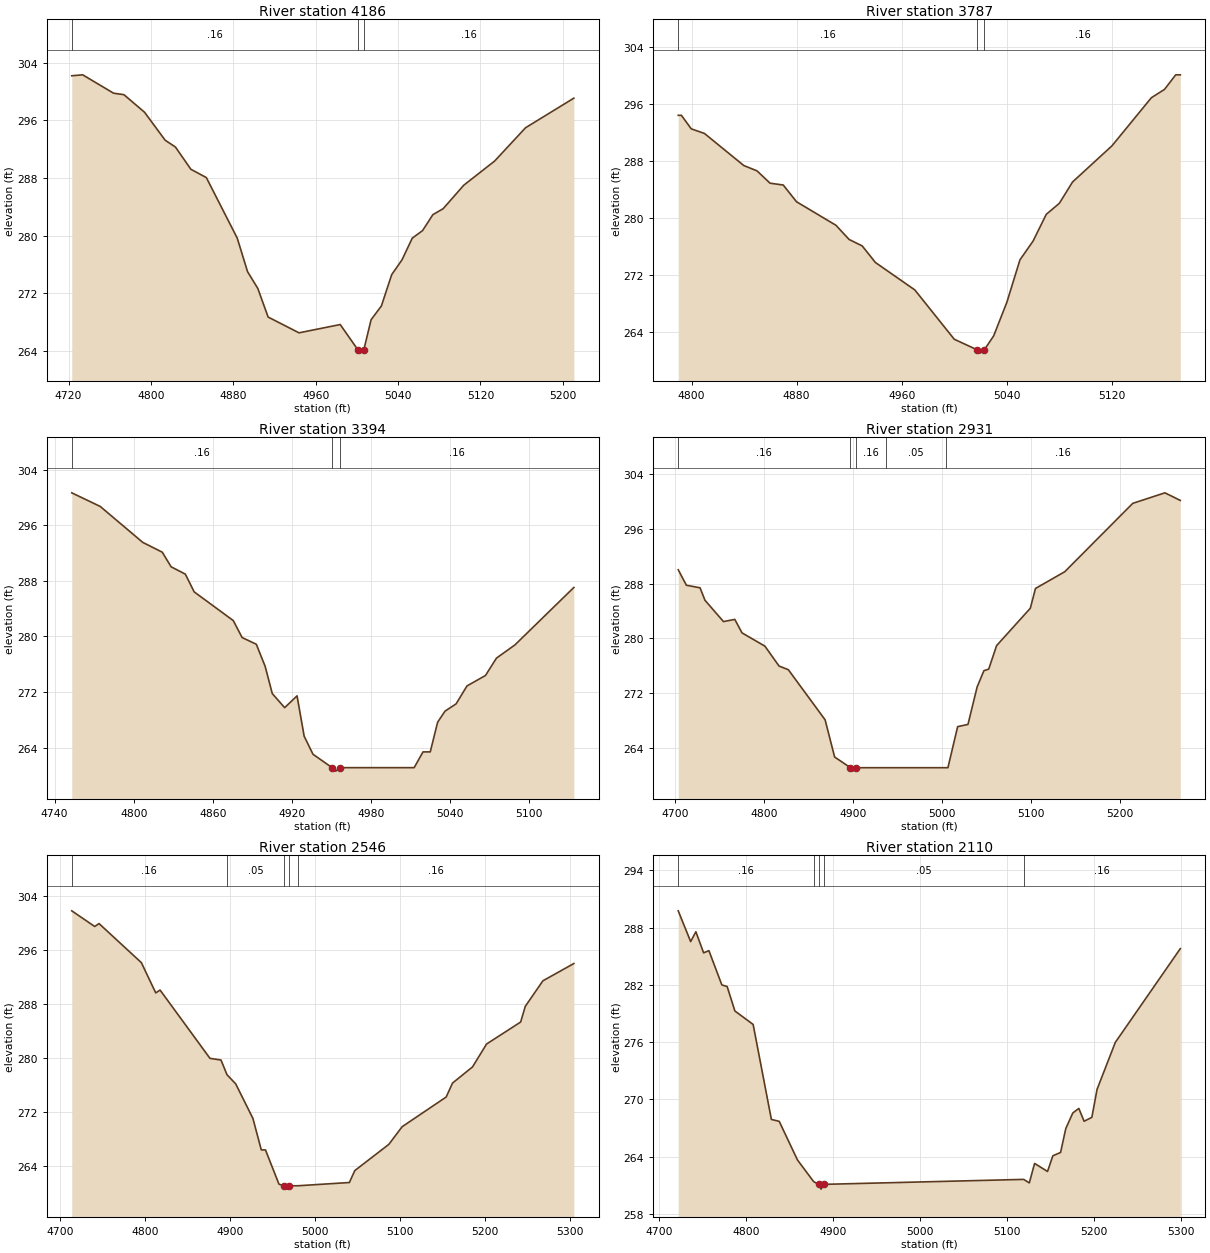
Type RM Length L Ch R = 1,4186,399,399,399
BEGIN DESCRIPTION:
UNT 047 IN BOCR 8.0
END DESCRIPTION:
XS GIS Cut Line= 3
      3753890.25     10583053.29      3753678.48     10583056.76
      3753402.68     10583056.76
#Sta/Elev= 30
  4723.1  302.21  4733.7  302.34  4763.7  299.79  4773.8  299.58  4793.8  297.14
  4813.8  293.26  4823.8  292.31  4838.8  289.22  4853.8  288.07  4883.8  279.66
  4893.8  275.01  4903.8  272.67  4913.8  268.70  4943.8  266.51  4983.8  267.66
  5000.8  264.19  5003.5  263.69  5006.8  264.19  5013.8  268.33  5023.8  270.24
  5033.8  274.59  5043.8  276.64  5053.8  279.66  5063.8  280.71  5073.8  282.92
  5083.8  283.75  5103.8  287.01  5133.8  290.37  5163.8  294.99  5210.7  299.10
#Mann=3,-1,0
  4723.1    0.16       0  5000.8    0.07       0  5006.8    0.16       0
Bank Sta=5000.8,5006.8
Exp/Cntr=0.3,0.1

Type RM Length L Ch R = 1,3787,393,393,393
BEGIN DESCRIPTION:
UNT 047 IN BOCR 7.0
END DESCRIPTION:
XS GIS Cut Line= 2
      3753789.54     10582751.21      3753407.61     10582758.15
#Sta/Elev= 30
  4789.9  294.43  4792.3  294.43  4799.8  292.53  4809.8  291.89  4839.8  287.38
  4849.8  286.64  4859.8  284.90  4869.8  284.65  4879.9  282.30  4909.9  279.00
  4919.9  277.01  4929.9  276.10  4939.9  273.78  4969.9  269.93  4999.9  263.01
  5016.9  261.56  5019.6  261.06  5022.9  261.56  5029.9  263.48  5039.9  268.18
  5049.9  274.15  5059.9  276.79  5069.9  280.53  5079.9  282.09  5089.9  285.07
  5119.9  290.15  5149.9  296.90  5159.9  298.07  5168.4  300.11  5171.9  300.11
#Mann=3,-1,0
  4789.9    0.16       0  5016.9    0.07       0  5022.9    0.16       0
Bank Sta=5016.9,5022.9
Exp/Cntr=0.3,0.1

Type RM Length L Ch R = 1,3394,463,463,463
BEGIN DESCRIPTION:
UNT 047 IN BOCR 6.0
END DESCRIPTION:
XS GIS Cut Line= 3
      3753599.63     10582160.15      3753499.61     10582410.19
      3753449.61     10582510.18
#Sta/Elev= 30
  4753.0  300.68  4774.6  298.72  4806.9  293.54  4821.7  292.13  4828.4  290.03
  4839.2  288.97  4845.9  286.42  4875.6  282.28  4882.3  279.84  4893.1  278.87
  4899.8  275.68  4905.2  271.77  4914.6  269.74  4924.0  271.44  4929.4  265.63
  4936.1  263.03  4950.6  261.10  4953.4  260.60  4956.6  261.10  5012.9  261.10
  5019.6  263.37  5025.1  263.37  5030.7  267.64  5036.3  269.24  5044.7  270.28
  5053.0  272.87  5067.0  274.37  5075.4  276.88  5089.4  278.78  5134.1  287.05
#Mann=3,-1,0
  4753.0    0.16       0  4950.6    0.07       0  4956.6    0.16       0
Bank Sta=4950.6,4956.6
Exp/Cntr=0.3,0.1

Type RM Length L Ch R = 1,2931,385,385,385
BEGIN DESCRIPTION:
UNT 047 IN BOCR 5.0
END DESCRIPTION:
XS GIS Cut Line= 3
      3753428.48     10582018.57      3753185.42     10582088.01
      3752900.74     10582213.00
#Sta/Elev= 30
  4703.8  290.03  4713.0  287.77  4728.3  287.40  4733.8  285.58  4754.6  282.46
  4767.3  282.78  4775.4  280.81  4801.1  278.87  4817.0  275.96  4827.4  275.43
  4868.7  268.10  4879.4  262.66  4897.2  261.10  4900.0  260.60  4903.2  261.10
  4936.9  261.10  5004.8  261.10  5006.6  261.10  5017.5  267.10  5029.1  267.43
  5039.4  272.91  5047.0  275.28  5052.4  275.51  5061.2  278.94  5099.1  284.41
  5104.9  287.30  5137.7  289.74  5214.1  299.74  5250.2  301.28  5267.5  300.17
#Mann=5,-1,0
  4703.8    0.16       0  4897.2   0.033       0  4903.2    0.16       0
  4936.9    0.05       0  5004.8    0.16       0
Bank Sta=4897.2,4903.2
Exp/Cntr=0.3,0.1

Type RM Length L Ch R = 1,2546,436,436,436
BEGIN DESCRIPTION:
UNT 047 IN BOCR 4.0
END DESCRIPTION:
XS GIS Cut Line= 3
      3753400.71     10581778.99      3753175.01     10581747.73
      3752824.47     10581841.44
#Sta/Elev= 30
  4713.5  301.84  4740.5  299.52  4745.6  299.95  4795.4  294.16  4812.3  289.68
  4817.4  290.10  4876.1  279.98  4889.1  279.73  4896.1  277.56  4906.4  276.19
  4926.6  271.09  4936.5  266.41  4941.4  266.41  4957.3  261.33  4963.3  261.10
  4966.1  260.60  4969.3  261.10  4979.8  261.10  5040.1  261.58  5046.5  263.35
  5086.5  267.23  5102.2  269.85  5154.0  274.25  5161.5  276.32  5185.0  278.71
  5201.5  282.10  5241.6  285.36  5247.1  287.69  5267.8  291.47  5304.2  294.03
#Mann=5,-1,0
  4713.5    0.16       0  4896.1    0.05       0  4963.3    0.07       0
  4969.3    0.05       0  4979.8    0.16       0
Bank Sta=4963.3,4969.3
Exp/Cntr=0.3,0.1

Type RM Length L Ch R = 1,2110,31,31,31
BEGIN DESCRIPTION:
Mapping XS 0ad4dfe3
END DESCRIPTION:
XS GIS Cut Line= 2
      3753236.16     10581513.34      3752757.01     10581190.44
#Sta/Elev= 30
  4721.8  289.75  4736.1  286.53  4742.1  287.56  4751.0  285.35  4757.1  285.58
  4772.0  281.99  4778.1  281.82  4787.0  279.26  4808.0  277.85  4829.0  267.90
  4838.0  267.70  4859.0  263.66  4877.6  261.39  4883.5  261.10  4886.2  260.60
  4889.5  261.10  5119.4  261.62  5125.8  261.25  5131.9  263.29  5146.8  262.45
  5152.9  264.09  5161.8  264.44  5167.8  266.94  5175.9  268.58  5182.8  269.05
  5188.9  267.71  5197.8  268.12  5203.8  271.05  5224.8  275.97  5299.6  285.79
#Mann=5,-1,0
  4721.8    0.16       0  4877.6    0.05       0  4883.5   0.033       0
  4889.5    0.05       0  5119.4    0.16       0
Bank Sta=4883.5,4889.5
Exp/Cntr=0.3,0.1

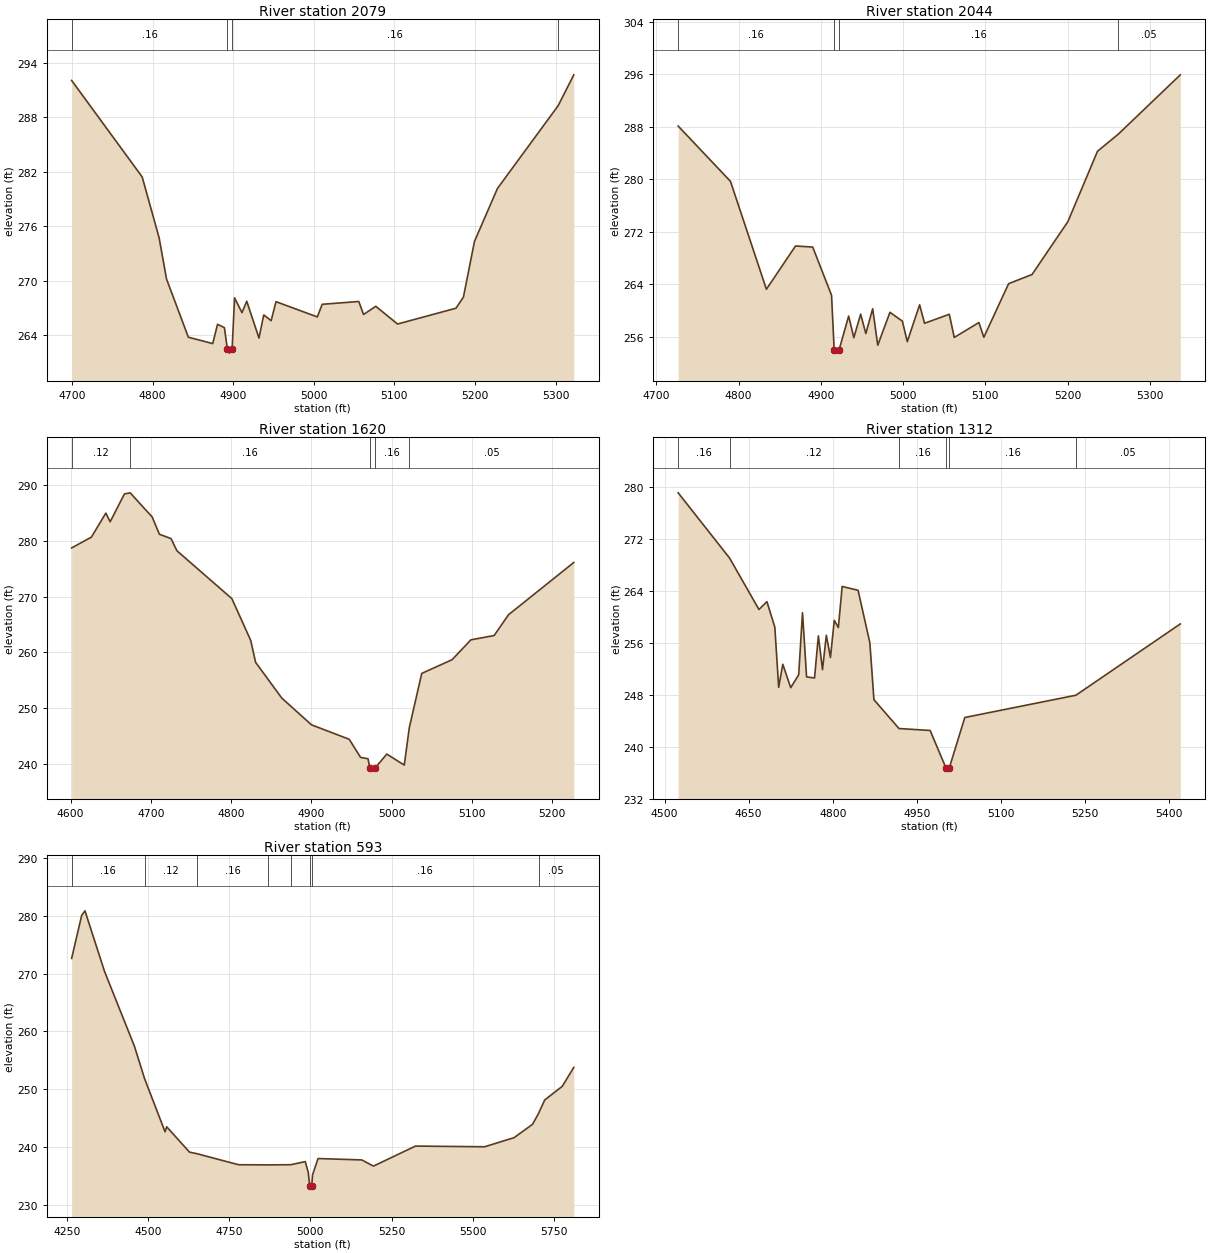
Type RM Length L Ch R = 1,2079,35,35,35
BEGIN DESCRIPTION:
Mapping XS 07a81d27
END DESCRIPTION:
XS GIS Cut Line= 2
      3753268.39     10581492.58      3752746.34     10581152.77
#Sta/Elev= 30
  4699.7  292.05  4787.2  281.44  4808.2  274.75  4817.4  270.21  4844.5  263.81
  4874.7  263.11  4880.7  265.23  4889.2  264.86  4892.8  262.56  4895.6  262.06
  4898.8  262.56  4901.8  268.14  4911.0  266.51  4916.9  267.77  4932.1  263.72
  4938.0  266.26  4947.2  265.63  4953.2  267.72  5004.5  266.04  5010.5  267.43
  5055.9  267.74  5061.8  266.31  5077.0  267.21  5104.0  265.26  5176.5  267.00
  5185.7  268.22  5199.4  274.34  5227.9  280.17  5303.2  289.27  5322.6  292.67
#Mann=4,-1,0
  4699.7    0.16       0  4892.8    0.07       0  4898.8    0.16       0
  5303.2    0.05       0
Bank Sta=4892.8,4898.8
Exp/Cntr=0.3,0.1

Type RM Length L Ch R = 1,2044,424,424,424
BEGIN DESCRIPTION:
UNT 047 IN BOCR 3.0
END DESCRIPTION:
XS GIS Cut Line= 3
      3753249.63     10581460.21      3753049.61     10581310.19
      3752749.59     10581110.18
#Sta/Elev= 30
  4726.5  288.12  4790.1  279.70  4833.8  263.25  4869.2  269.85  4890.1  269.68
  4913.0  262.34  4916.2  254.02  4919.0  253.52  4922.2  254.02  4933.8  259.17
  4940.1  255.88  4948.4  259.46  4954.7  256.50  4963.0  260.28  4969.2  254.73
  4984.0  259.74  4999.1  258.40  5005.1  255.27  5020.1  260.88  5026.1  258.07
  5056.2  259.44  5062.2  255.91  5092.2  258.18  5098.2  255.94  5128.3  264.10
  5156.8  265.50  5200.4  273.56  5236.4  284.28  5261.7  286.89  5337.1  295.93
#Mann=4,-1,0
  4726.5    0.16       0  4916.2    0.07       0  4922.2    0.16       0
  5261.7    0.05       0
Bank Sta=4916.2,4922.2
Exp/Cntr=0.3,0.1

Type RM Length L Ch R = 1,1620,308,308,308
BEGIN DESCRIPTION:
UNT 047 IN BOCR 2.0
END DESCRIPTION:
XS GIS Cut Line= 2
      3753419.96     10581093.75      3752845.75     10580844.69
#Sta/Elev= 30
  4601.3  278.76  4625.9  280.69  4643.9  285.00  4649.3  283.45  4667.1  288.45
  4674.3  288.65  4701.7  284.31  4710.7  281.21  4725.2  280.43  4732.5  278.25
  4801.0  269.65  4824.5  262.15  4830.6  258.21  4863.3  251.78  4900.3  246.98
  4947.3  244.39  4961.4  241.14  4970.7  240.89  4973.2  239.17  4975.9  238.67
  4979.2  239.17  4994.1  241.73  5015.9  239.76  5022.2  246.48  5037.7  256.22
  5075.5  258.68  5099.0  262.25  5127.9  263.02  5145.9  266.76  5227.2  276.14
#Mann=5,-1,0
  4601.3    0.12       0  4674.3    0.16       0  4973.2    0.07       0
  4979.2    0.16       0  5022.2    0.05       0
Bank Sta=4973.2,4979.2
Exp/Cntr=0.3,0.1

Type RM Length L Ch R = 1,1312,719,719,719
BEGIN DESCRIPTION:
Mapping XS 386fdb2a
END DESCRIPTION:
XS GIS Cut Line= 3
      3753612.50     10581081.06      3753352.09     10580799.82
      3752869.46     10580626.21
#Sta/Elev= 30
  4524.2  279.14  4615.9  269.10  4668.4  261.17  4682.6  262.38  4696.7  258.45
  4703.6  249.18  4710.9  252.74  4725.1  249.13  4739.3  251.12  4746.1  260.68
  4753.4  250.79  4767.6  250.63  4774.4  257.11  4781.8  251.90  4788.6  257.20
  4796.0  253.79  4802.8  259.50  4810.1  258.39  4816.9  264.72  4845.3  264.13
  4866.3  256.05  4873.6  247.28  4918.3  242.84  4973.9  242.54  5002.1  236.78
  5004.9  236.28  5008.1  236.78  5035.8  244.54  5234.1  247.97  5420.4  258.95
#Mann=6,-1,0
  4524.2    0.16       0  4615.9    0.12       0  4918.3    0.16       0
  5002.1    0.07       0  5008.1    0.16       0  5234.1    0.05       0
Bank Sta=5002.1,5008.1
Exp/Cntr=0.3,0.1

Type RM Length L Ch R = 1,593,0,0,0
BEGIN DESCRIPTION:
UNT 047 IN BOCR 1.0
END DESCRIPTION:
XS GIS Cut Line= 4
      3753683.86     10580940.96      3753621.36     10580329.87
      3753333.17     10580187.50      3752798.46     10580479.16
#Sta/Elev= 30
  4265.4  272.67  4296.3  280.13  4306.4  280.91  4366.7  270.39  4458.4  257.47
  4489.7  251.84  4552.8  242.61  4557.8  243.48  4628.1  239.09  4650.9  238.82
  4778.8  236.91  4870.5  236.88  4939.6  236.91  4984.1  237.45  4993.2  235.62
  4997.9  233.18  5000.7  232.68  5003.9  233.18  5006.5  235.14  5023.4  237.98
  5158.0  237.74  5193.9  236.67  5323.2  240.14  5535.8  240.02  5626.6  241.60
  5683.6  243.93  5701.8  245.80  5720.9  248.14  5774.7  250.49  5810.2  253.78
#Mann=8,-1,0
  4265.4    0.16       0  4489.7    0.12       0  4650.9    0.16       0
  4870.5    0.12       0  4939.6    0.16       0  4997.9    0.07       0
  5003.9    0.16       0  5701.8    0.05       0
Bank Sta=4997.9,5003.9
Exp/Cntr=0.3,0.1

Chan Stop Cuts=-1