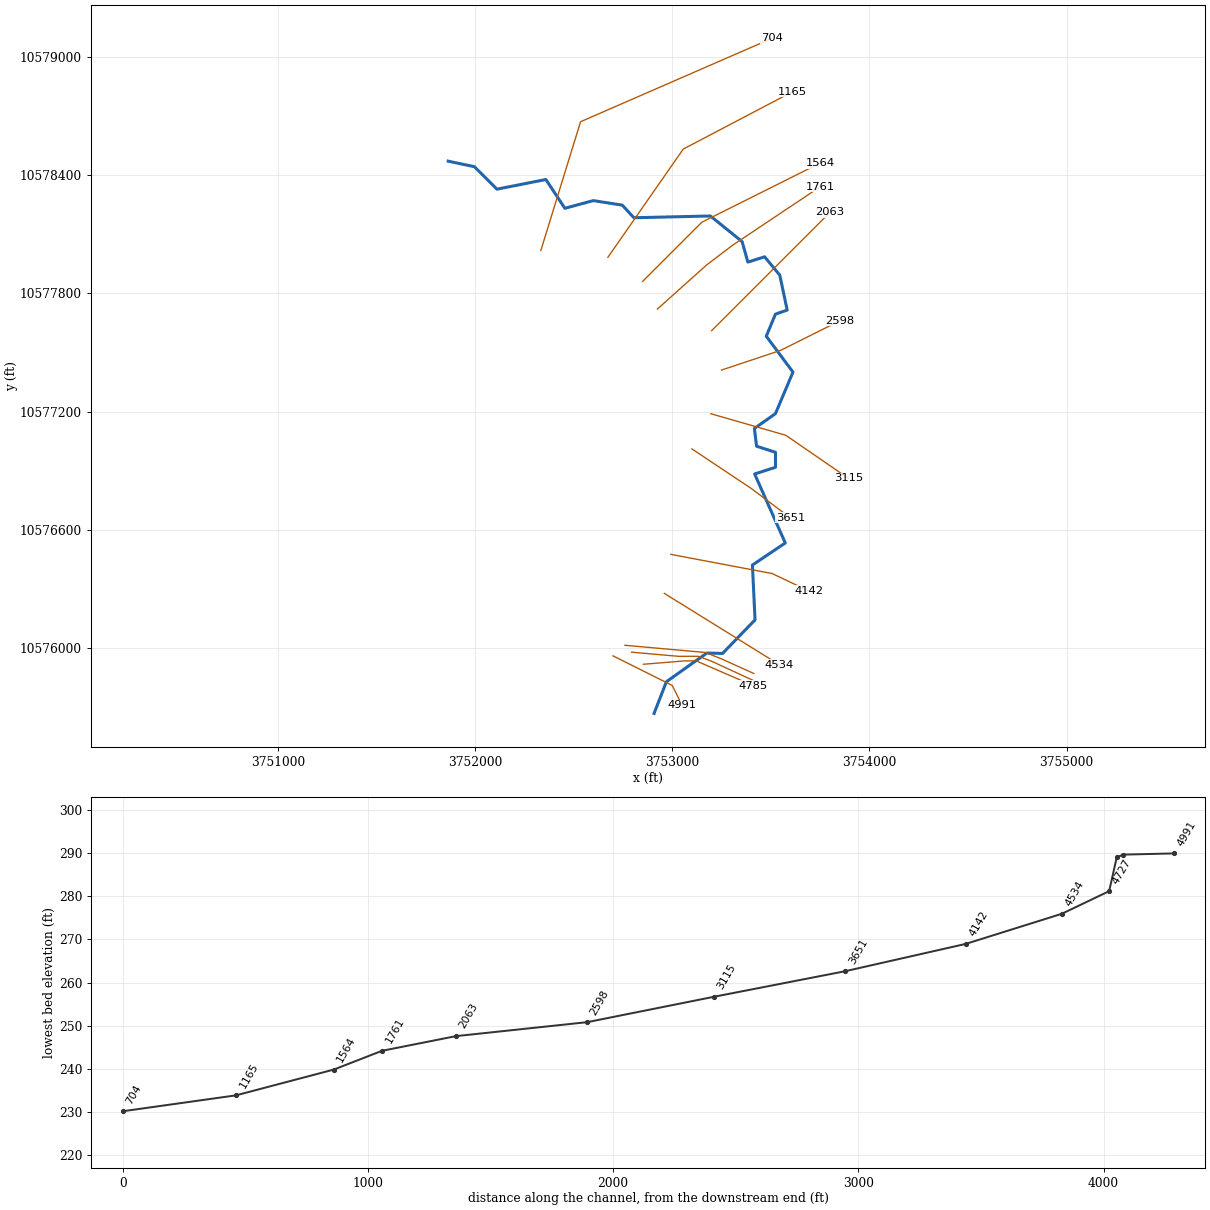
--- UNT 048 IN BOCR.prj (project) ---

Proj Title=UNT 048 IN BOCR Base Level Engineering
Current Plan=p01
Default Exp/Contr=0.3,0.1
English Units
Geom File=g01
Flow File=f01
Plan File=p01
BEGIN DESCRIPTION:
UNT 048 IN BOCR
END DESCRIPTION:

--- UNT 048 IN BOCR.p01 (plan) ---

Plan Title=Multiple Run
Short Identifier=Multiple
Geom File=g01
Flow File=f01
Subcritical Flow
K Sum by GR= 0
Std Step Tol= 0.01
Critical Tol= 0.01
Num of Std Step Trials= 20
Max Error Tol= 0.3
Flow Tol Ratio= 0.001
Split Flow NTrial= 30
Split Flow Tol= 0.02
Split Flow Ratio= 0.02
Log Output Level= 0
Friction Slope Method= 1
Unsteady Friction Slope Method= 2
Unsteady Bridges Friction Slope Method= 1
Parabolic Critical Depth
Global Vel Dist=  1 , 1 , 1
Global Log Level= 0
CheckData=True
Encroach Param= -1, 0, 0, 0
BEGIN DESCRIPTION:
Multiple Run
END DESCRIPTION:

--- UNT 048 IN BOCR.f01 (steady flow) ---

Flow Title=Multiple
Number of Profiles=7
Profile Names=10-year,25-year,50-year,1pct_min,100-year,1pct_plu,500-year
River Rch & RM= UNT 048 IN BOCR,Reach-1,4991
     413     552     665     591     800    1081    1158
Boundary for River Rch & Prof#=UNT 048 IN BOCR,Reach-1,1
Up Type=0
Dn Type=3
Dn Slope=0.005
Boundary for River Rch & Prof#=UNT 048 IN BOCR,Reach-1,2
Up Type=0
Dn Type=3
Dn Slope=0.005
Boundary for River Rch & Prof#=UNT 048 IN BOCR,Reach-1,3
Up Type=0
Dn Type=3
Dn Slope=0.005
Boundary for River Rch & Prof#=UNT 048 IN BOCR,Reach-1,4
Up Type=0
Dn Type=3
Dn Slope=0.005
Boundary for River Rch & Prof#=UNT 048 IN BOCR,Reach-1,5
Up Type=0
Dn Type=3
Dn Slope=0.005
Boundary for River Rch & Prof#=UNT 048 IN BOCR,Reach-1,6
Up Type=0
Dn Type=3
Dn Slope=0.005
Boundary for River Rch & Prof#=UNT 048 IN BOCR,Reach-1,7
Up Type=0
Dn Type=3
Dn Slope=0.005

--- UNT 048 IN BOCR.g01 (geometry) ---

Geom Title=Existing Conditions

River Reach=UNT 048 IN BOCR,Reach-1
Reach XY= 30
      3752907.66     10575668.49      3752970.00     10575829.00
      3753175.05     10575974.53      3753255.00     10575972.65
      3753419.75     10576143.00      3753406.50     10576421.00
      3753573.25     10576533.00      3753417.75     10576883.00
      3753523.50     10576917.00      3753523.50     10576993.00
      3753427.50     10577024.00      3753416.50     10577114.00
      3753523.25     10577189.00      3753612.25     10577400.00
      3753476.75     10577582.00      3753523.25     10577694.00
      3753582.89     10577714.55      3753545.25     10577892.00
      3753468.25     10577985.00      3753383.50     10577958.00
      3753354.25     10578062.00      3753193.25     10578192.00
      3752805.00     10578183.00      3752746.25     10578247.00
      3752599.00     10578270.00      3752455.00     10578231.00
      3752358.50     10578377.00      3752110.25     10578328.00
      3751996.00     10578442.00      3751863.25     10578470.00

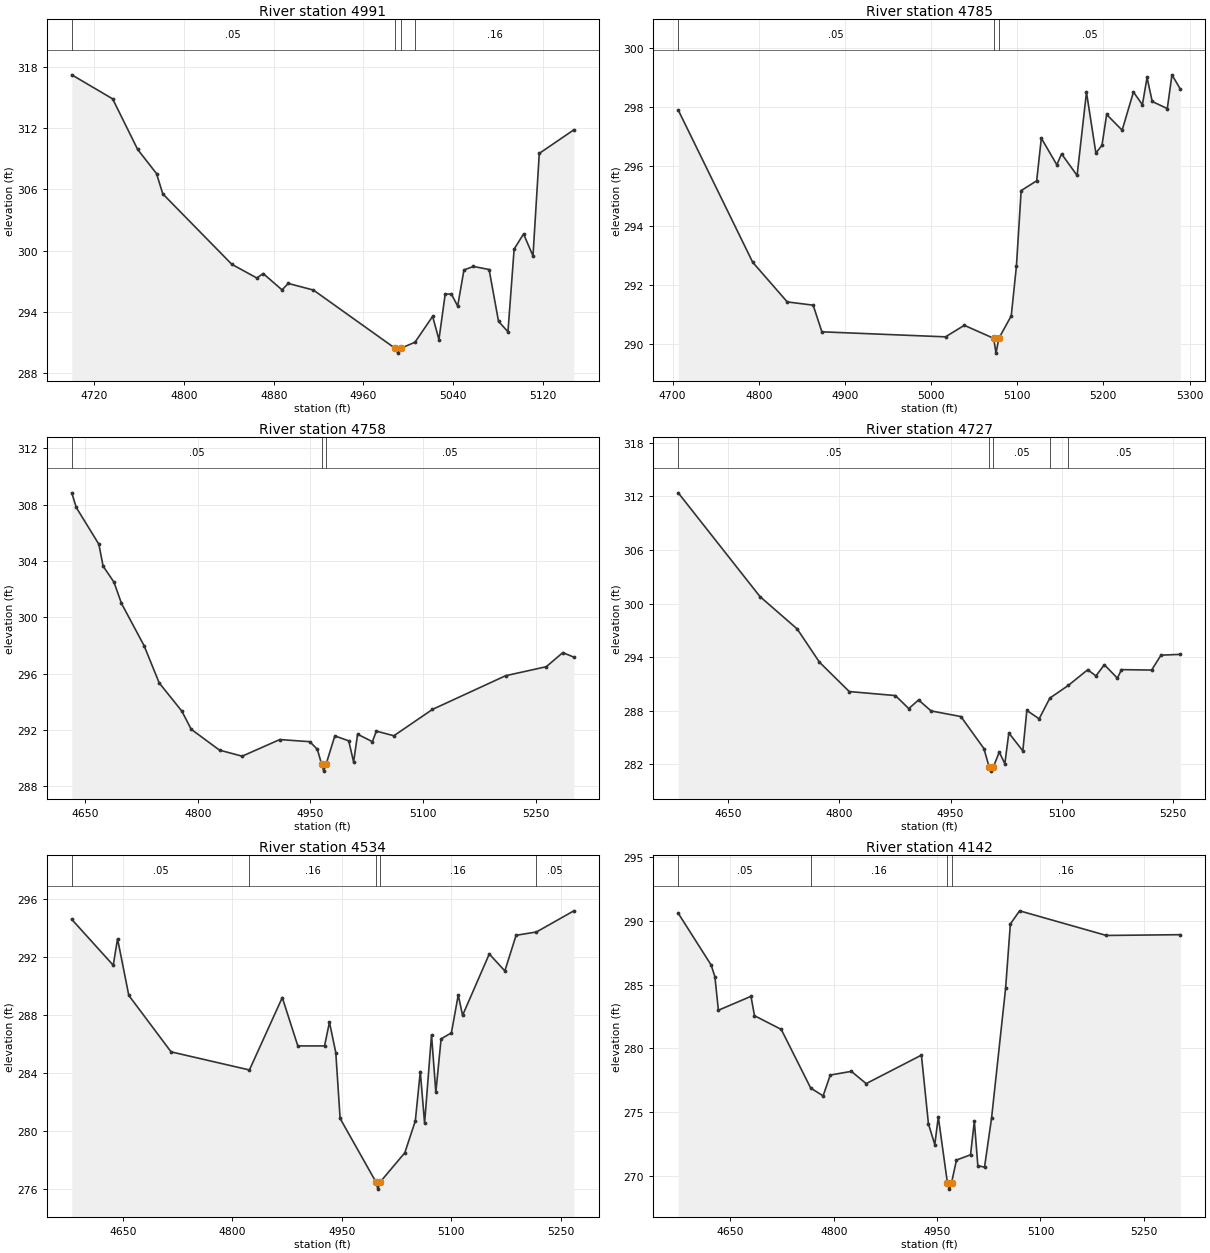
Type RM Length L Ch R = 1,4991,206,206,206
BEGIN DESCRIPTION:
UNT 048 IN BOCR 9.0
END DESCRIPTION:
XS GIS Cut Line= 3
      3752699.58     10575960.21      3752999.61     10575810.19
      3753049.63     10575710.14
#Sta/Elev= 30
  4700.1  317.20  4736.5  314.85  4758.8  309.90  4775.6  307.54  4781.2  305.55
  4842.7  298.66  4865.0  297.32  4870.6  297.76  4887.4  296.16  4893.0  296.79
  4915.4  296.14  4987.8  290.47  4990.6  289.97  4993.8  290.47  5005.9  291.04
  5021.6  293.57  5027.2  291.29  5032.8  295.75  5038.3  295.75  5043.9  294.57
  5049.5  298.11  5057.9  298.45  5071.9  298.15  5080.3  293.08  5088.7  292.06
  5094.2  300.15  5102.6  301.63  5111.0  299.48  5116.6  309.51  5147.4  311.82
#Mann=4,-1,0
  4700.1    0.05       0  4987.8    0.04       0  4993.8    0.05       0
  5005.9    0.16       0
Bank Sta=4987.8,4993.8
Exp/Cntr=0.3,0.1

Type RM Length L Ch R = 1,4785,27,27,27
BEGIN DESCRIPTION:
Mapping XS 3183afc7
END DESCRIPTION:
XS GIS Cut Line= 4
      3752853.50     10575917.70      3753060.56     10575934.62
      3753121.76     10575934.62      3753409.53     10575809.62
#Sta/Elev= 30
  4706.6  297.90  4793.0  292.76  4833.1  291.42  4863.2  291.31  4873.3  290.41
  5016.8  290.24  5038.6  290.63  5072.7  290.19  5075.4  289.69  5078.7  290.19
  5093.1  290.95  5099.1  292.63  5104.6  295.18  5122.6  295.51  5128.0  296.95
  5146.0  296.05  5151.5  296.42  5169.5  295.69  5180.4  298.50  5191.3  296.45
  5198.4  296.71  5203.8  297.75  5221.8  297.22  5234.9  298.51  5245.3  298.08
  5250.7  299.00  5256.7  298.19  5274.2  297.95  5279.6  299.09  5289.3  298.61
#Mann=3,-1,0
  4706.6    0.05       0  5072.7    0.04       0  5078.7    0.05       0
Bank Sta=5072.7,5078.7
Exp/Cntr=0.3,0.1

Type RM Length L Ch R = 1,4758,31,31,31
BEGIN DESCRIPTION:
Mapping XS 71b40d0b
END DESCRIPTION:
XS GIS Cut Line= 5
      3752793.67     10575978.89      3753030.61     10575958.06
      3753132.17     10575958.06      3753198.58     10575933.32
      3753432.98     10575825.24
#Sta/Elev= 30
  4632.3  308.83  4638.3  307.79  4668.4  305.18  4674.0  303.63  4688.5  302.49
  4698.5  300.98  4728.6  297.98  4748.7  295.34  4778.8  293.34  4791.3  292.05
  4829.0  290.57  4859.1  290.14  4909.2  291.32  4949.2  291.17  4959.2  290.63
  4964.9  289.58  4967.7  289.08  4970.9  289.58  4982.5  291.58  5001.0  291.23
  5007.5  289.73  5012.8  291.70  5032.5  291.17  5037.8  291.92  5061.1  291.59
  5112.5  293.46  5209.8  295.85  5264.0  296.49  5286.0  297.49  5300.7  297.17
#Mann=3,-1,0
  4632.3    0.05       0  4964.9    0.04       0  4970.9    0.05       0
Bank Sta=4964.9,4970.9
Exp/Cntr=0.3,0.1

Type RM Length L Ch R = 1,4727,193,193,193
BEGIN DESCRIPTION:
Mapping XS fde36a50
END DESCRIPTION:
XS GIS Cut Line= 5
      3752759.77     10576014.05      3753048.84     10575988.01
      3753167.33     10575977.59      3753249.36     10575945.04
      3753413.41     10575870.83
#Sta/Elev= 30
  4582.5  312.41  4692.8  300.78  4743.0  297.15  4773.1  293.42  4813.3  290.13
  4875.6  289.68  4893.6  288.22  4906.8  289.19  4923.7  287.96  4963.9  287.33
  4995.0  283.74  5001.9  281.71  5004.7  281.21  5007.9  281.71  5015.7  283.35
  5023.2  282.04  5028.6  285.49  5047.5  283.48  5052.9  288.01  5069.5  287.08
  5084.0  289.40  5108.7  290.81  5135.1  292.58  5146.1  291.88  5157.5  293.14
  5175.1  291.63  5180.6  292.59  5221.3  292.54  5233.9  294.21  5260.0  294.30
#Mann=5,-1,0
  4582.5    0.05       0  5001.9    0.04       0  5007.9    0.05       0
  5084.0    0.16       0  5108.7    0.05       0
Bank Sta=5001.9,5007.9
Exp/Cntr=0.3,0.1

Type RM Length L Ch R = 1,4534,392,392,392
BEGIN DESCRIPTION:
UNT 048 IN BOCR 8.0
END DESCRIPTION:
XS GIS Cut Line= 2
      3752959.72     10576277.25      3753544.07     10575914.85
#Sta/Elev= 30
  4580.1  294.59  4636.9  291.42  4642.8  293.25  4658.2  289.34  4716.1  285.44
  4823.4  284.19  4868.4  289.19  4889.7  285.85  4926.3  285.85  4933.0  287.49
  4941.7  285.38  4947.6  280.84  4996.6  276.46  4999.3  275.96  5002.6  276.46
  5036.2  278.47  5050.6  280.67  5057.4  284.08  5063.3  280.51  5072.8  286.62
  5078.7  282.64  5085.9  286.34  5100.0  286.75  5109.4  289.37  5115.3  287.96
  5151.9  292.20  5173.2  291.03  5188.6  293.49  5216.5  293.72  5267.7  295.18
#Mann=5,-1,0
  4580.1    0.05       0  4823.4    0.16       0  4996.6    0.07       0
  5002.6    0.16       0  5216.5    0.05       0
Bank Sta=4996.6,5002.6
Exp/Cntr=0.3,0.1

Type RM Length L Ch R = 1,4142,491,491,491
BEGIN DESCRIPTION:
UNT 048 IN BOCR 7.0
END DESCRIPTION:
XS GIS Cut Line= 3
      3752992.72     10576475.16      3753506.60     10576377.94
      3753692.38     10576289.39
#Sta/Elev= 30
  4574.2  290.59  4621.9  286.54  4627.4  285.62  4632.5  282.99  4679.8  284.08
  4684.9  282.56  4723.7  281.49  4766.5  276.89  4784.5  276.28  4794.9  277.91
  4825.5  278.20  4847.0  277.24  4927.2  279.47  4937.4  274.08  4946.6  272.46
  4951.7  274.63  4964.9  269.47  4967.7  268.97  4970.9  269.47  4978.1  271.25
  4998.5  271.66  5004.0  274.29  5009.1  270.81  5018.8  270.69  5029.0  274.53
  5049.4  284.71  5056.3  289.75  5069.7  290.78  5195.6  288.85  5303.0  288.91
#Mann=4,-1,0
  4574.2    0.05       0  4766.5    0.16       0  4964.9    0.07       0
  4970.9    0.16       0
Bank Sta=4964.9,4970.9
Exp/Cntr=0.3,0.1

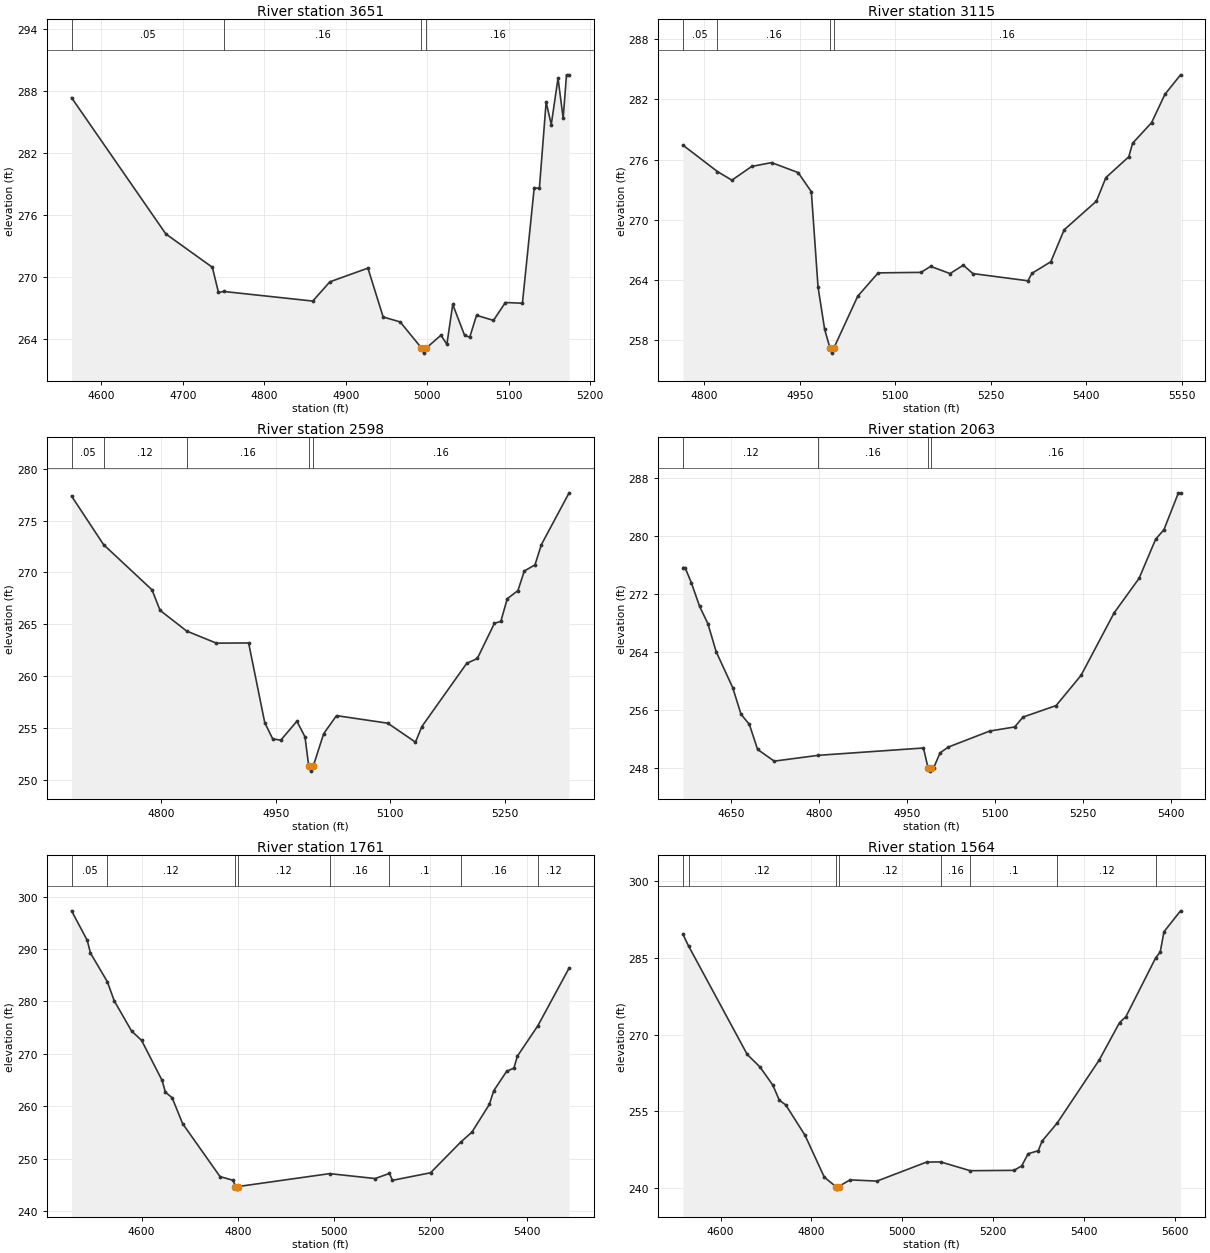
Type RM Length L Ch R = 1,3651,536,536,536
BEGIN DESCRIPTION:
UNT 048 IN BOCR 6.0
END DESCRIPTION:
XS GIS Cut Line= 3
      3753099.61     10577010.19      3753399.61     10576810.19
      3753599.64     10576660.16
#Sta/Elev= 30
  4563.5  287.37  4679.2  274.18  4736.3  270.95  4743.8  268.51  4750.0  268.61
  4859.5  267.68  4880.5  269.54  4927.2  270.87  4945.9  266.14  4966.8  265.66
  4992.9  263.14  4995.7  262.64  4998.9  263.14  5016.8  264.37  5024.1  263.50
  5031.3  267.35  5045.9  264.35  5052.2  264.19  5060.5  266.30  5081.3  265.81
  5095.9  267.54  5116.8  267.47  5131.3  278.66  5137.6  278.58  5145.9  286.94
  5152.2  284.77  5160.5  289.26  5166.8  285.37  5170.9  289.58  5174.1  289.58
#Mann=4,-1,0
  4563.5    0.05       0  4750.0    0.16       0  4992.9    0.07       0
  4998.9    0.16       0
Bank Sta=4992.9,4998.9
Exp/Cntr=0.3,0.1

Type RM Length L Ch R = 1,3115,517,517,517
BEGIN DESCRIPTION:
UNT 048 IN BOCR 5.0
END DESCRIPTION:
XS GIS Cut Line= 3
      3753195.82     10577188.71      3753576.05     10577079.33
      3753893.77     10576860.57
#Sta/Elev= 30
  4766.6  277.43  4820.7  274.80  4843.4  273.94  4874.6  275.31  4905.8  275.69
  4947.4  274.70  4968.2  272.79  4978.7  263.30  4989.1  259.07  4997.5  257.20
  5000.3  256.70  5003.5  257.20  5041.1  262.38  5073.1  264.70  5140.5  264.75
  5155.5  265.35  5186.0  264.63  5206.9  265.47  5221.8  264.63  5308.4  263.91
  5314.5  264.65  5344.3  265.81  5365.2  268.99  5415.9  271.85  5430.8  274.20
  5466.7  276.27  5472.7  277.62  5502.5  279.67  5523.5  282.50  5548.0  284.44
#Mann=4,-1,0
  4766.6    0.05       0  4820.7    0.16       0  4997.5    0.07       0
  5003.5    0.16       0
Bank Sta=4997.5,5003.5
Exp/Cntr=0.3,0.1

Type RM Length L Ch R = 1,2598,535,535,535
BEGIN DESCRIPTION:
UNT 048 IN BOCR 4.0
END DESCRIPTION:
XS GIS Cut Line= 3
      3753249.61     10577410.19      3753549.61     10577510.19
      3753849.58     10577660.17
#Sta/Elev= 30
  4682.6  277.38  4724.5  272.69  4788.0  268.32  4798.5  266.34  4833.4  264.34
  4872.3  263.17  4914.5  263.19  4935.6  255.50  4946.1  253.91  4956.7  253.81
  4977.7  255.63  4988.3  254.12  4993.2  251.31  4995.9  250.81  4999.2  251.31
  5012.8  254.43  5029.6  256.17  5096.7  255.44  5133.0  253.61  5141.4  255.12
  5200.1  261.22  5214.0  261.69  5236.4  265.09  5244.8  265.28  5253.2  267.46
  5267.2  268.25  5275.5  270.14  5289.5  270.73  5297.9  272.69  5334.2  277.69
#Mann=5,-1,0
  4682.6    0.05       0  4724.5    0.12       0  4833.4    0.16       0
  4993.2    0.07       0  4999.2    0.16       0
Bank Sta=4993.2,4999.2
Exp/Cntr=0.3,0.1

Type RM Length L Ch R = 1,2063,302,302,302
BEGIN DESCRIPTION:
UNT 048 IN BOCR 3.0
END DESCRIPTION:
XS GIS Cut Line= 3
      3753199.58     10577610.16      3753499.61     10577910.19
      3753799.63     10578210.21
#Sta/Elev= 30
  4567.9  275.63  4571.5  275.63  4582.1  273.56  4596.2  270.30  4610.4  267.90
  4624.5  264.04  4652.8  259.07  4666.9  255.41  4681.1  254.02  4695.2  250.56
  4723.5  248.95  4798.8  249.75  4978.1  250.76  4985.7  248.07  4988.4  247.57
  4991.7  248.07  4995.7  248.07  5006.3  250.08  5020.5  250.89  5091.2  253.10
  5133.6  253.66  5147.8  255.02  5204.3  256.61  5246.8  260.77  5303.3  269.40
  5345.8  274.15  5374.0  279.54  5388.2  280.86  5412.9  285.94  5416.5  285.94
#Mann=4,-1,0
  4567.9    0.12       0  4798.8    0.16       0  4985.7    0.07       0
  4991.7    0.16       0
Bank Sta=4985.7,4991.7
Exp/Cntr=0.3,0.1

Type RM Length L Ch R = 1,1761,197,197,197
BEGIN DESCRIPTION:
Mapping XS a57c2485
END DESCRIPTION:
XS GIS Cut Line= 4
      3752924.43     10577719.74      3753174.41     10577943.69
      3753304.62     10578042.65      3753749.02     10578339.49
#Sta/Elev= 30
  4454.5  297.29  4487.1  291.66  4493.8  289.22  4528.8  283.77  4543.2  280.11
  4579.1  274.36  4600.0  272.56  4642.6  264.91  4649.4  262.68  4663.5  261.60
  4685.2  256.67  4763.0  246.55  4790.1  245.85  4794.8  244.66  4797.5  244.16
  4800.8  244.66  4990.7  247.12  5085.1  246.18  5114.8  247.16  5121.1  245.84
  5200.2  247.28  5262.5  253.10  5286.3  255.06  5322.4  260.33  5331.4  262.93
  5358.4  266.66  5373.4  267.27  5380.6  269.54  5423.1  275.34  5488.1  286.37
#Mann=8,-1,0
  4454.5    0.05       0  4528.8    0.12       0  4794.8    0.07       0
  4800.8    0.12       0  4990.7    0.16       0  5114.8     0.1       0
  5262.5    0.16       0  5423.1    0.12       0
Bank Sta=4794.8,4800.8
Exp/Cntr=0.3,0.1

Type RM Length L Ch R = 1,1564,399,399,399
BEGIN DESCRIPTION:
UNT 048 IN BOCR 2.0
END DESCRIPTION:
XS GIS Cut Line= 3
      3752849.63     10577860.21      3753149.61     10578160.19
      3753749.65     10578460.21
#Sta/Elev= 30
  4517.3  289.58  4529.5  287.33  4658.7  266.12  4687.0  263.65  4715.3  260.09
  4729.4  257.17  4743.5  256.26  4786.0  250.31  4828.4  242.13  4853.7  240.30
  4856.4  239.80  4859.7  240.30  4885.0  241.61  4944.3  241.37  5053.3  245.08
  5084.2  245.12  5149.5  243.40  5246.2  243.47  5263.0  244.37  5276.9  246.71
  5299.3  247.31  5307.7  249.19  5340.8  252.70  5433.5  265.04  5478.2  272.34
  5492.2  273.50  5557.9  285.03  5567.6  286.10  5576.0  290.10  5612.4  294.18
#Mann=8,-1,0
  4517.3    0.05       0  4529.5    0.12       0  4853.7    0.07       0
  4859.7    0.12       0  5084.2    0.16       0  5149.5     0.1       0
  5340.8    0.12       0  5557.9    0.16       0
Bank Sta=4853.7,4859.7
Exp/Cntr=0.3,0.1

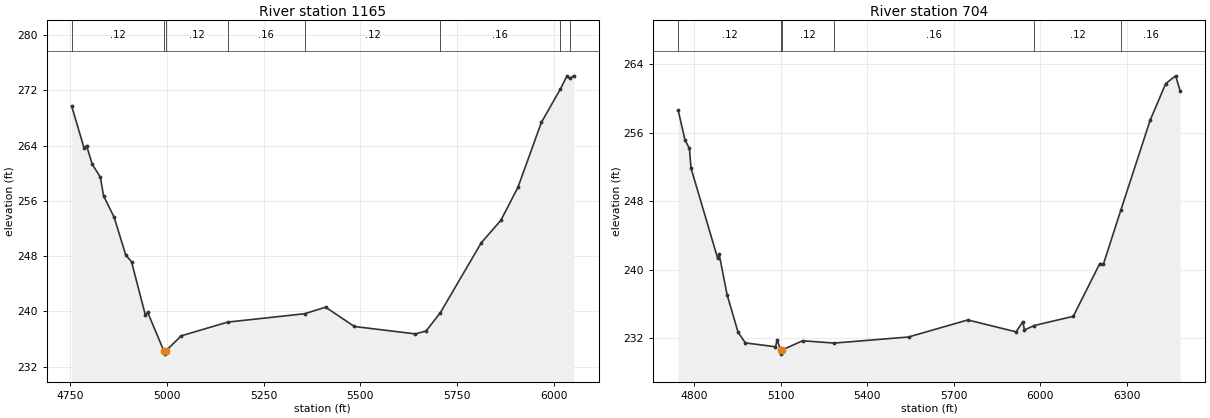
Type RM Length L Ch R = 1,1165,461,461,461
BEGIN DESCRIPTION:
Mapping XS 847551e2
END DESCRIPTION:
XS GIS Cut Line= 3
      3752673.43     10577982.62      3753055.39     10578531.25
      3753610.98     10578822.94
#Sta/Elev= 30
  4754.8  269.73  4787.1  263.61  4793.2  264.01  4808.0  261.30  4828.9  259.44
  4837.1  256.75  4864.7  253.60  4894.4  248.17  4909.3  247.20  4945.0  239.48
  4951.1  239.86  4992.5  234.32  4995.3  233.82  4998.5  234.32  5037.5  236.47
  5157.8  238.46  5356.4  239.67  5410.2  240.62  5484.5  237.82  5641.9  236.75
  5669.6  237.18  5706.1  239.80  5812.1  249.96  5862.5  253.19  5906.6  257.98
  5967.1  267.37  6015.7  272.16  6033.2  274.10  6039.7  273.73  6050.8  274.11
#Mann=8,-1,0
  4754.8    0.12       0  4992.5    0.07       0  4998.5    0.12       0
  5157.8    0.16       0  5356.4    0.12       0  5706.1    0.16       0
  6015.7    0.12       0  6039.7    0.16       0
Bank Sta=4992.5,4998.5
Exp/Cntr=0.3,0.1

Type RM Length L Ch R = 1,704,0,0,0
BEGIN DESCRIPTION:
UNT 048 IN BOCR 1.0
END DESCRIPTION:
XS GIS Cut Line= 3
      3752333.18     10578017.39      3752534.56     10578670.14
      3753505.67     10579093.27
#Sta/Elev= 30
  4744.2  258.63  4768.1  255.13  4783.4  254.14  4789.0  251.84  4881.3  241.34
  4886.6  241.80  4914.0  237.09  4951.9  232.73  4977.4  231.45  5082.0  231.00
  5087.8  231.77  5099.9  230.64  5102.7  230.14  5105.9  230.64  5176.2  231.70
  5286.1  231.43  5543.7  232.14  5749.2  234.13  5916.9  232.74  5940.3  233.93
  5945.8  232.96  5979.7  233.48  6115.2  234.55  6207.3  240.71  6219.8  240.64
  6280.4  246.96  6381.8  257.42  6436.1  261.72  6470.4  262.62  6486.6  260.81
#Mann=6,-1,0
  4744.2    0.12       0  5099.9    0.07       0  5105.9    0.12       0
  5286.1    0.16       0  5979.7    0.12       0  6280.4    0.16       0
Bank Sta=5099.9,5105.9
Exp/Cntr=0.3,0.1

Chan Stop Cuts=-1