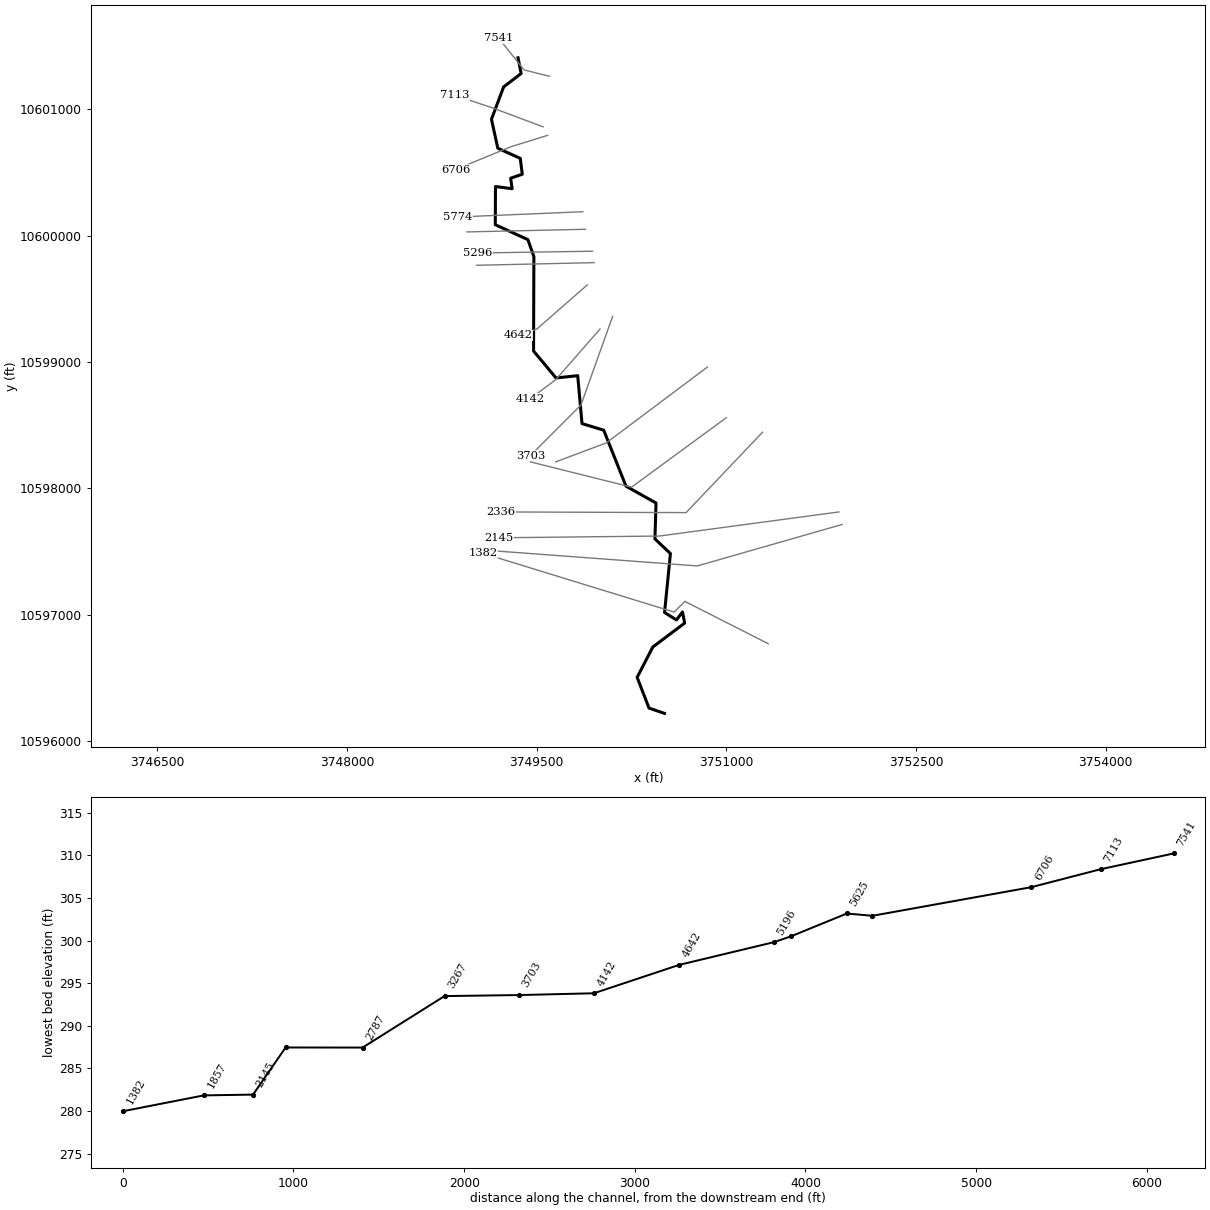
--- UNT 050 IN BOCR.prj (project) ---

Proj Title=UNT 050 IN BOCR Base Level Engineering
Current Plan=p01
Default Exp/Contr=0.3,0.1
English Units
Geom File=g01
Flow File=f01
Plan File=p01
Y Axis Title=Elevation
X Axis Title(PF)=Main Channel Distance
X Axis Title(XS)=Station
BEGIN DESCRIPTION:
UNT 050 IN BOCR
END DESCRIPTION:
DSS Export Rating Curves= 0
DSS Export Rating Curve Sorted= 0
DSS Export Volume Flow Curves= 0
DXF OffsetX= 0
DXF OffsetY= 0
DXF ScaleX= 1
DXF ScaleY= 10

--- UNT 050 IN BOCR.p01 (plan) ---

Plan Title=Multiple Run
Short Identifier=Multiple
Geom File=g01
Flow File=f01
Subcritical Flow
K Sum by GR= 0
Std Step Tol= 0.01
Critical Tol= 0.01
Num of Std Step Trials= 20
Max Error Tol= 0.3
Flow Tol Ratio= 0.001
Split Flow NTrial= 30
Split Flow Tol= 0.02
Split Flow Ratio= 0.02
Log Output Level= 0
Friction Slope Method= 1
Unsteady Friction Slope Method= 2
Unsteady Bridges Friction Slope Method= 1
Parabolic Critical Depth
Global Vel Dist=  1 , 1 , 1
Global Log Level= 0
CheckData=True
Encroach Param= -1, 0, 0, 0
BEGIN DESCRIPTION:
Multiple Run
END DESCRIPTION:

--- UNT 050 IN BOCR.f01 (steady flow) ---

Flow Title=Multiple
Program Version=4.10
Number of Profiles= 7
Profile Names=10-year,25-year,50-year,1pct_min,100-year,1pct_plu,500-year
River Rch & RM=UNT 050 IN BOCR,Reach-1         ,7541
     672     918    1124    1011    1367    1849    2031
River Rch & RM=UNT 050 IN BOCR,Reach-1         ,6706
     838    1155    1422    1286    1739    2351    2609
Boundary for River Rch & Prof#=UNT 050 IN BOCR,Reach-1         , 1
Up Type= 0
Dn Type= 3
Dn Slope=0.005
Boundary for River Rch & Prof#=UNT 050 IN BOCR,Reach-1         , 2
Up Type= 0
Dn Type= 3
Dn Slope=0.005
Boundary for River Rch & Prof#=UNT 050 IN BOCR,Reach-1         , 3
Up Type= 0
Dn Type= 3
Dn Slope=0.005
Boundary for River Rch & Prof#=UNT 050 IN BOCR,Reach-1         , 4
Up Type= 0
Dn Type= 3
Dn Slope=0.005
Boundary for River Rch & Prof#=UNT 050 IN BOCR,Reach-1         , 5
Up Type= 0
Dn Type= 3
Dn Slope=0.005
Boundary for River Rch & Prof#=UNT 050 IN BOCR,Reach-1         , 6
Up Type= 0
Dn Type= 3
Dn Slope=0.005
Boundary for River Rch & Prof#=UNT 050 IN BOCR,Reach-1         , 7
Up Type= 0
Dn Type= 3
Dn Slope=0.005
DSS Import GetInterval= 0
DSS Import GetPeak= 0
DSS Import FillOption= 0

--- UNT 050 IN BOCR.g01 (geometry) ---

Geom Title=Existing Conditions

River Reach=UNT 050 IN BOCR,Reach-1
Reach XY= 30
      3749351.75     10601406.00      3749376.25     10601282.00
      3749237.75     10601176.00      3749141.50     10600920.00
      3749191.75     10600691.00      3749369.25     10600611.00
      3749385.25     10600485.00      3749293.25     10600454.00
      3749305.00     10600371.00      3749173.25     10600388.00
      3749171.75     10600086.00      3749429.25     10599968.00
      3749477.00     10599835.00      3749474.50     10599087.00
      3749652.00     10598874.00      3749823.75     10598892.00
      3749857.75     10598513.00      3750029.25     10598461.00
      3750205.50     10598018.00      3750443.00     10597885.00
      3750434.50     10597601.00      3750557.00     10597485.00
      3750510.50     10597019.00      3750604.75     10596960.00
      3750652.75     10597023.00      3750669.50     10596935.00
      3750417.75     10596746.00      3750293.75     10596506.00
      3750387.50     10596263.00      3750509.75     10596221.00

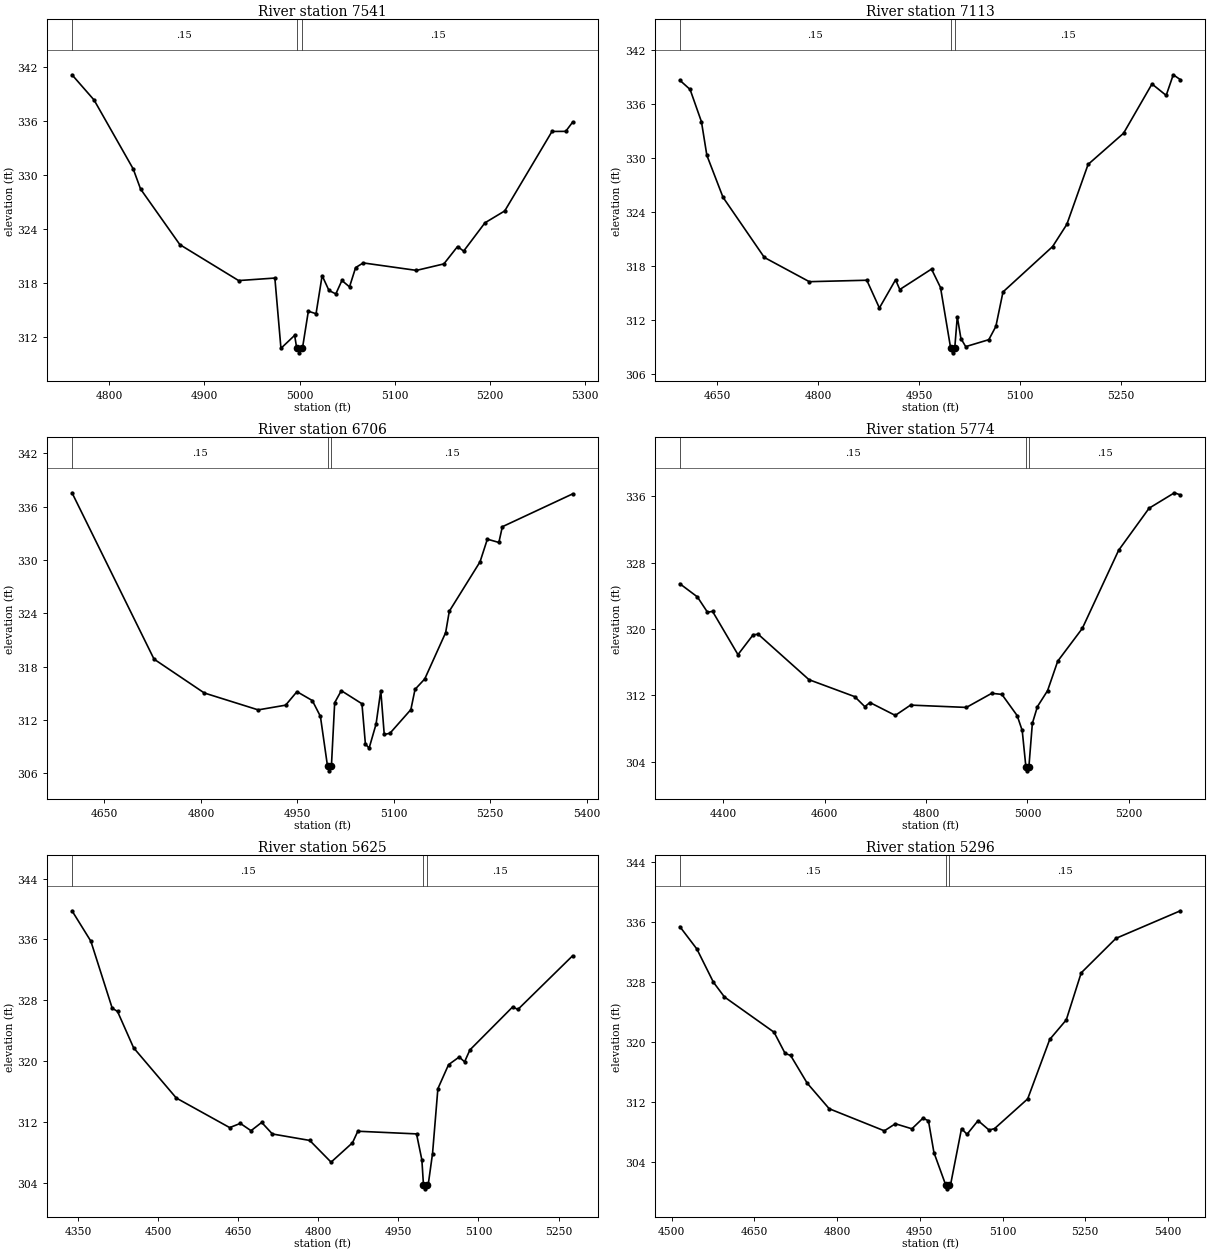
Type RM Length L Ch R = 1,7541,428,428,428
BEGIN DESCRIPTION:
UNT 050 IN BOCR 12.0
END DESCRIPTION:
XS GIS Cut Line= 3
      3749599.58     10601260.20      3749399.61     10601310.19
      3749199.60     10601560.20
#Sta/Elev= 30
  4760.7  341.09  4783.9  338.29  4825.1  330.63  4832.8  328.41  4874.1  322.24
  4935.9  318.25  4974.0  318.53  4980.4  310.73  4994.8  312.17  4997.0  310.73
  4999.8  310.23  5003.0  310.73  5009.2  314.85  5017.3  314.57  5023.7  318.80
  5030.9  317.15  5038.1  316.77  5044.5  318.26  5052.5  317.55  5058.9  319.69
  5066.9  320.21  5122.9  319.38  5151.7  320.10  5166.1  322.03  5172.5  321.52
  5194.9  324.66  5215.7  325.98  5265.4  334.80  5279.8  334.81  5287.0  335.82
#Mann=3,-1,0
  4760.7    0.15       0  4997.0    0.05       0  5003.0    0.15       0
Bank Sta=4997,5003
Exp/Cntr=0.3,0.1

Type RM Length L Ch R = 1,7113,407,407,407
BEGIN DESCRIPTION:
UNT 050 IN BOCR 11.0
END DESCRIPTION:
XS GIS Cut Line= 3
      3749549.65     10600860.17      3749149.61     10601010.19
      3748849.58     10601110.20
#Sta/Elev= 30
  4594.7  338.64  4609.9  337.62  4626.8  334.03  4634.8  330.31  4658.8  325.65
  4720.2  318.97  4787.0  316.28  4872.4  316.44  4891.1  313.36  4915.1  316.49
  4921.4  315.41  4968.5  317.68  4981.9  315.63  4997.0  308.88  4999.8  308.38
  5003.0  308.88  5006.8  312.39  5012.2  309.97  5019.3  309.07  5053.6  309.84
  5064.1  311.31  5074.7  315.14  5148.4  320.18  5169.5  322.64  5201.1  329.30
  5253.8  332.76  5296.0  338.23  5317.1  336.96  5327.6  339.25  5338.2  338.71
#Mann=3,-1,0
  4594.7    0.15       0  4997.0    0.05       0  5003.0    0.15       0
Bank Sta=4997,5003
Exp/Cntr=0.3,0.1

Type RM Length L Ch R = 1,6706,932,932,932
BEGIN DESCRIPTION:
UNT 050 IN BOCR 10.0
END DESCRIPTION:
XS GIS Cut Line= 3
      3749586.25     10600792.99      3749294.62     10600702.72
      3748857.09     10600522.15
#Sta/Elev= 30
  4599.5  337.56  4727.1  318.84  4805.3  315.03  4889.1  313.13  4931.8  313.66
  4949.4  315.18  4973.3  314.18  4985.9  312.40  4997.0  306.77  4999.8  306.27
  5003.0  306.77  5008.1  313.94  5018.4  315.29  5050.5  313.82  5055.9  309.28
  5061.7  308.83  5072.5  311.54  5079.8  315.30  5085.2  310.36  5094.1  310.50
  5126.6  313.16  5133.1  315.44  5148.2  316.61  5180.7  321.82  5186.4  324.23
  5234.2  329.79  5245.6  332.34  5263.5  331.97  5268.9  333.74  5378.1  337.43
#Mann=3,-1,0
  4599.5    0.15       0  4997.0    0.05       0  5003.0    0.15       0
Bank Sta=4997,5003
Exp/Cntr=0.3,0.1

Type RM Length L Ch R = 1,5774,149,149,149
BEGIN DESCRIPTION:
Mapping XS a7e1e163
END DESCRIPTION:
XS GIS Cut Line= 2
      3749864.07     10600188.83      3748877.95     10600147.17
#Sta/Elev= 30
  4314.7  325.45  4349.2  323.87  4369.2  322.02  4379.2  322.12  4429.3  316.91
  4459.3  319.31  4469.3  319.36  4569.4  313.89  4659.5  311.85  4679.5  310.64
  4689.5  311.14  4739.5  309.59  4769.6  310.83  4879.7  310.55  4929.7  312.25
  4949.7  312.12  4979.8  309.57  4989.8  307.77  4997.0  303.41  4999.8  302.91
  5003.0  303.41  5009.8  308.63  5019.8  310.65  5039.8  312.57  5059.8  316.12
  5108.3  320.07  5179.9  329.48  5240.0  334.55  5290.0  336.41  5301.7  336.15
#Mann=3,-1,0
  4314.7    0.15       0  4997.0    0.05       0  5003.0    0.15       0
Bank Sta=4997,5003
Exp/Cntr=0.3,0.1

Type RM Length L Ch R = 1,5625,329,329,329
BEGIN DESCRIPTION:
UNT 050 IN BOCR 9.0
END DESCRIPTION:
XS GIS Cut Line= 2
      3749884.94     10600049.94      3748947.37     10600029.11
#Sta/Elev= 30
  4338.5  339.77  4373.8  335.77  4413.8  326.96  4423.8  326.52  4453.9  321.74
  4533.9  315.13  4633.9  311.24  4653.9  311.79  4673.9  310.83  4693.9  311.92
  4713.9  310.40  4783.9  309.55  4823.9  306.69  4864.0  309.24  4874.0  310.76
  4984.0  310.41  4994.0  306.99  4997.0  303.68  4999.8  303.18  5003.0  303.68
  5005.8  303.68  5014.0  307.83  5024.0  316.36  5044.0  319.52  5064.0  320.53
  5074.0  319.89  5084.0  321.46  5164.0  327.11  5174.0  326.79  5276.3  333.84
#Mann=3,-1,0
  4338.5    0.15       0  4997.0    0.05       0  5003.0    0.15       0
Bank Sta=4997,5003
Exp/Cntr=0.3,0.1

Type RM Length L Ch R = 1,5296,100,100,100
BEGIN DESCRIPTION:
UNT 050 IN BOCR 8.0
END DESCRIPTION:
XS GIS Cut Line= 2
      3749940.47     10599876.33      3749032.67     10599862.47
#Sta/Elev= 30
  4514.7  335.38  4545.6  332.40  4575.6  327.98  4595.6  326.02  4685.6  321.33
  4705.6  318.51  4715.6  318.24  4745.6  314.56  4785.6  311.15  4885.6  308.21
  4905.6  309.15  4935.6  308.48  4955.6  309.89  4965.6  309.55  4975.6  305.31
  4997.0  300.99  4999.8  300.49  5003.0  300.99  5005.6  300.99  5025.6  308.50
  5035.6  307.75  5055.6  309.57  5075.6  308.31  5085.6  308.51  5145.6  312.46
  5185.6  320.37  5215.6  322.97  5242.7  329.23  5305.7  333.82  5422.6  337.49
#Mann=3,-1,0
  4514.7    0.15       0  4997.0    0.05       0  5003.0    0.15       0
Bank Sta=4997,5003
Exp/Cntr=0.3,0.1

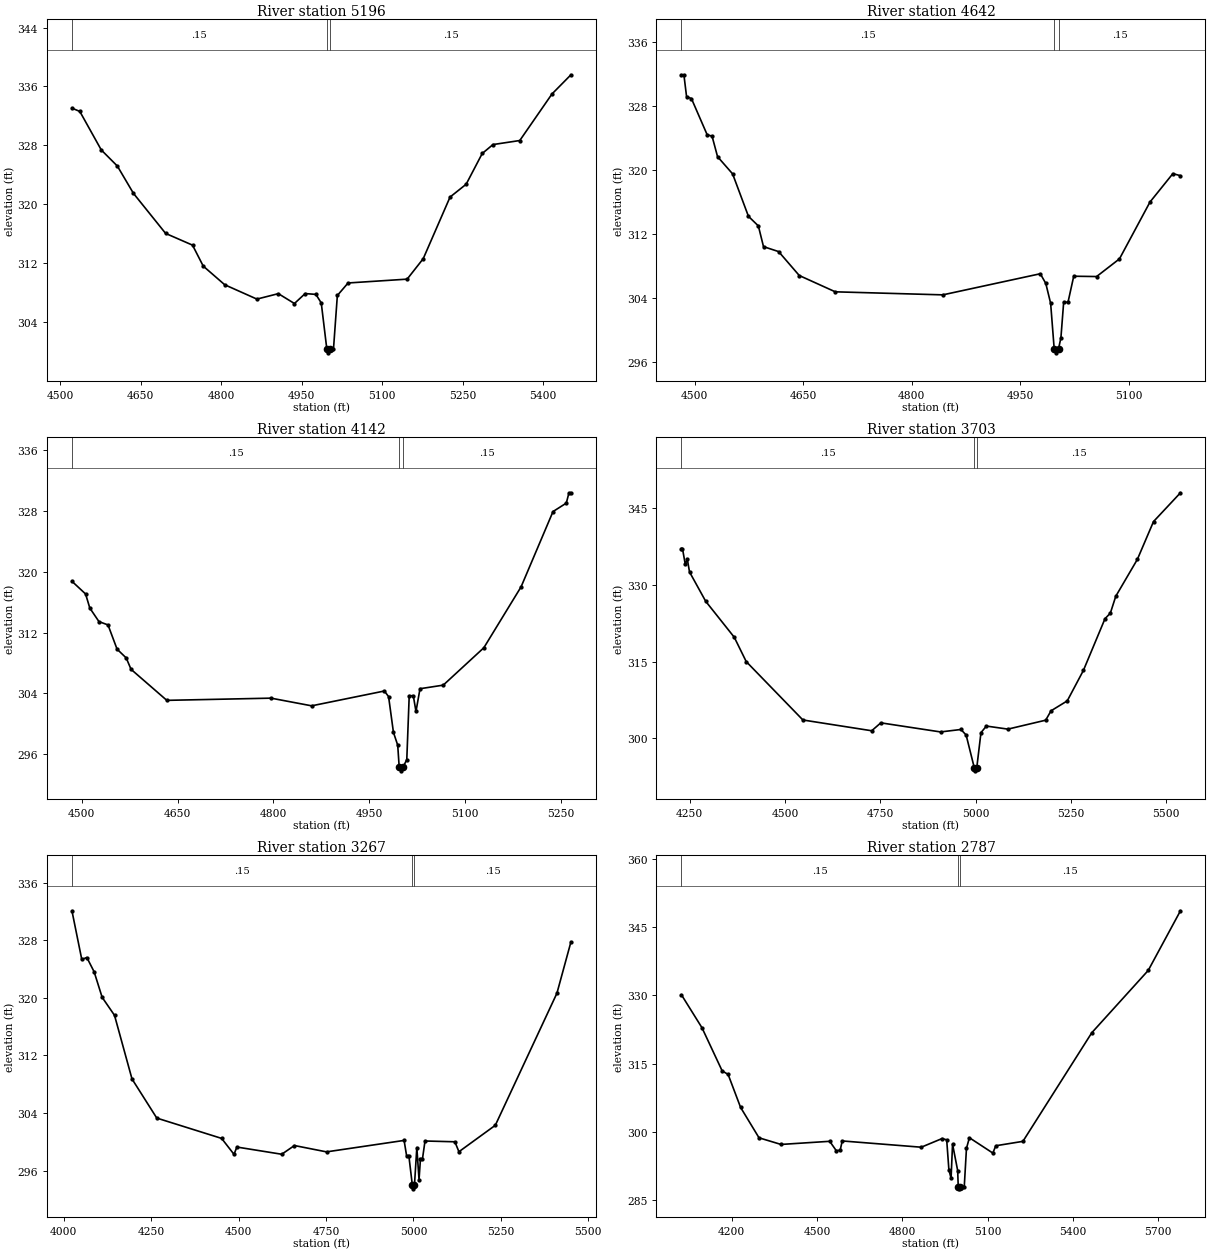
Type RM Length L Ch R = 1,5196,554,554,554
BEGIN DESCRIPTION:
Mapping XS 1dd2f829
END DESCRIPTION:
XS GIS Cut Line= 2
      3749954.31     10599786.05      3749024.24     10599765.23
#Sta/Elev= 30
  4521.8  333.05  4536.5  332.60  4576.5  327.37  4606.5  325.18  4636.5  321.47
  4696.5  316.03  4746.6  314.44  4766.6  311.59  4806.6  309.06  4866.6  307.11
  4906.6  307.85  4936.6  306.51  4956.6  307.86  4976.6  307.75  4986.6  306.59
  4997.0  300.31  4999.8  299.81  5003.0  300.31  5009.4  300.33  5016.6  307.60
  5036.6  309.30  5146.7  309.82  5176.7  312.60  5226.7  320.97  5256.7  322.71
  5286.7  326.89  5306.7  328.10  5356.7  328.65  5416.7  334.97  5452.1  337.58
#Mann=3,-1,0
  4521.8    0.15       0  4997.0    0.05       0  5003.0    0.15       0
Bank Sta=4997,5003
Exp/Cntr=0.3,0.1

Type RM Length L Ch R = 1,4642,500,500,500
BEGIN DESCRIPTION:
UNT 050 IN BOCR 7.0
END DESCRIPTION:
XS GIS Cut Line= 3
      3749899.63     10599610.21      3749499.61     10599260.19
      3749349.66     10599210.20
#Sta/Elev= 30
  4481.9  331.92  4485.3  331.92  4489.0  329.18  4495.7  328.95  4517.5  324.41
  4524.2  324.25  4531.8  321.68  4552.6  319.53  4574.5  314.22  4588.2  313.02
  4595.3  310.43  4616.2  309.81  4644.7  306.82  4694.5  304.78  4843.1  304.40
  4977.8  307.04  4985.4  305.83  4992.1  303.34  4997.0  297.65  4999.8  297.15
  5003.0  297.65  5006.3  299.04  5010.1  303.48  5016.1  303.48  5024.0  306.73
  5055.6  306.69  5087.2  308.90  5129.4  316.01  5161.0  319.56  5171.5  319.30
#Mann=3,-1,0
  4481.9    0.15       0  4997.0    0.05       0  5003.0    0.15       0
Bank Sta=4997,5003
Exp/Cntr=0.3,0.1

Type RM Length L Ch R = 1,4142,439,439,439
BEGIN DESCRIPTION:
UNT 050 IN BOCR 6.0
END DESCRIPTION:
XS GIS Cut Line= 3
      3749999.62     10599260.20      3749649.61     10598860.19
      3749449.63     10598710.20
#Sta/Elev= 30
  4484.5  318.75  4505.9  317.08  4512.5  315.23  4526.8  313.45  4541.0  313.01
  4555.2  309.82  4569.5  308.67  4577.1  307.17  4633.1  303.09  4796.3  303.38
  4859.9  302.37  4973.8  304.32  4980.4  303.58  4988.0  298.88  4994.7  297.19
  4997.0  294.32  4999.8  293.82  5003.0  294.32  5008.9  295.28  5012.7  303.70
  5019.1  303.70  5023.3  301.63  5029.6  304.62  5066.0  305.09  5129.6  310.01
  5187.9  318.02  5237.9  327.92  5258.7  329.03  5262.9  330.39  5266.0  330.39
#Mann=3,-1,0
  4484.5    0.15       0  4997.0    0.05       0  5003.0    0.15       0
Bank Sta=4997,5003
Exp/Cntr=0.3,0.1

Type RM Length L Ch R = 1,3703,436,436,436
BEGIN DESCRIPTION:
UNT 050 IN BOCR 5.0
END DESCRIPTION:
XS GIS Cut Line= 3
      3750099.61     10599360.19      3749849.61     10598660.19
      3749449.60     10598260.18
#Sta/Elev= 30
  4228.5  337.15  4231.2  337.15  4238.6  334.04  4243.9  335.06  4249.7  332.56
  4292.2  326.81  4367.1  319.77  4398.4  315.01  4547.1  303.57  4727.6  301.46
  4751.5  303.01  4908.1  301.23  4961.7  301.71  4975.3  300.62  4997.0  294.11
  4999.8  293.61  5003.0  294.11  5014.2  301.09  5028.4  302.38  5084.9  301.78
  5183.9  303.53  5198.1  305.37  5240.5  307.31  5282.9  313.28  5339.5  323.40
  5353.6  324.50  5367.8  327.80  5424.4  335.02  5466.8  342.43  5537.5  348.07
#Mann=3,-1,0
  4228.5    0.15       0  4997.0    0.05       0  5003.0    0.15       0
Bank Sta=4997,5003
Exp/Cntr=0.3,0.1

Type RM Length L Ch R = 1,3267,480,480,480
BEGIN DESCRIPTION:
UNT 050 IN BOCR 4.0
END DESCRIPTION:
XS GIS Cut Line= 3
      3750849.58     10598960.17      3750049.61     10598360.19
      3749649.57     10598210.18
#Sta/Elev= 30
  4023.4  332.08  4051.5  325.34  4066.1  325.59  4086.9  323.61  4109.8  320.07
  4145.2  317.57  4195.2  308.74  4266.1  303.31  4451.5  300.49  4486.9  298.28
  4495.2  299.29  4623.4  298.29  4659.8  299.50  4751.5  298.62  4973.4  300.21
  4980.7  298.04  4986.9  298.11  4997.0  293.99  4999.8  293.49  5003.0  293.99
  5009.8  299.22  5016.1  294.77  5020.2  297.67  5026.0  297.67  5033.2  300.13
  5118.6  300.02  5130.2  298.64  5234.3  302.31  5410.5  320.64  5450.6  327.77
#Mann=3,-1,0
  4023.4    0.15       0  4997.0    0.05       0  5003.0    0.15       0
Bank Sta=4997,5003
Exp/Cntr=0.3,0.1

Type RM Length L Ch R = 1,2787,451,451,451
BEGIN DESCRIPTION:
UNT 050 IN BOCR 3.0
END DESCRIPTION:
XS GIS Cut Line= 3
      3750999.63     10598560.21      3750249.61     10598010.19
      3749449.62     10598210.19
#Sta/Elev= 30
  4023.7  330.15  4095.9  322.90  4166.9  313.41  4187.8  312.63  4231.7  305.37
  4296.5  298.68  4373.8  297.22  4545.1  297.91  4568.2  295.84  4581.8  295.94
  4589.1  297.99  4867.0  296.61  4940.3  298.52  4956.4  298.23  4964.1  291.67
  4971.8  289.77  4977.0  297.29  4995.0  291.47  4997.0  287.95  4999.8  287.45
  5003.0  287.95  5018.2  287.95  5025.9  296.34  5036.2  298.70  5118.7  295.32
  5129.0  296.93  5224.4  297.90  5466.6  321.80  5665.0  335.51  5778.4  348.64
#Mann=3,-1,0
  4023.7    0.15       0  4997.0    0.05       0  5003.0    0.15       0
Bank Sta=4997,5003
Exp/Cntr=0.3,0.1

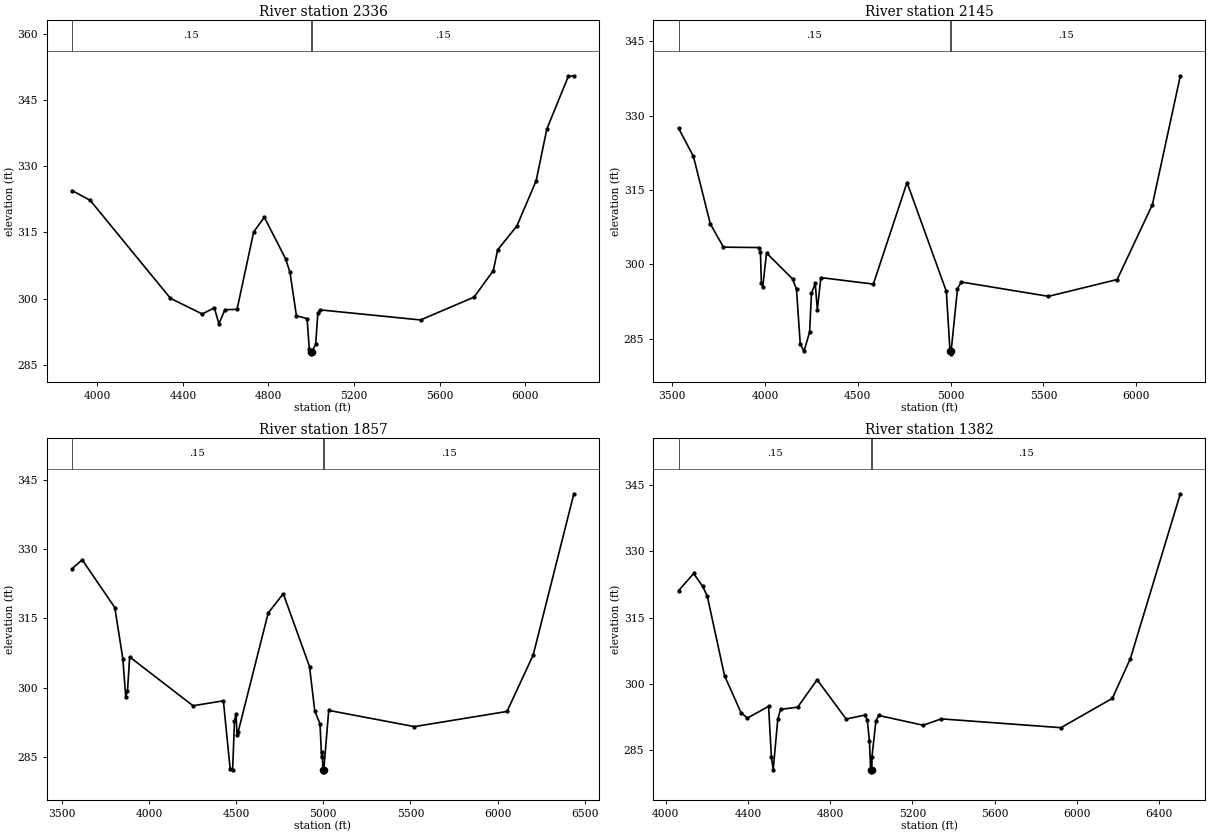
Type RM Length L Ch R = 1,2336,191,191,191
BEGIN DESCRIPTION:
Mapping XS 018815d9
END DESCRIPTION:
XS GIS Cut Line= 3
      3751285.15     10598444.43      3750680.97     10597809.00
      3749213.39     10597814.21
#Sta/Elev= 30
  3882.5  324.51  3967.3  322.29  4342.2  300.06  4490.7  296.50  4547.3  297.91
  4568.4  294.27  4596.7  297.48  4653.3  297.55  4731.0  315.12  4780.7  318.46
  4880.7  308.97  4900.7  305.94  4930.7  296.10  4980.7  295.46  4990.7  288.60
  4997.0  287.96  4999.8  287.46  5003.0  287.96  5020.7  289.64  5030.7  296.64
  5040.7  297.44  5510.7  295.15  5760.7  300.33  5850.7  306.36  5870.7  311.05
  5960.7  316.47  6050.7  326.73  6100.7  338.48  6200.7  350.40  6226.9  350.56
#Mann=3,-1,0
  3882.5    0.15       0  4997.0    0.05       0  5003.0    0.15       0
Bank Sta=4997,5003
Exp/Cntr=0.3,0.1

Type RM Length L Ch R = 1,2145,288,288,288
BEGIN DESCRIPTION:
UNT 050 IN BOCR 2.0
END DESCRIPTION:
XS GIS Cut Line= 3
      3751889.32     10597814.21      3750470.27     10597623.64
      3749199.43     10597609.75
#Sta/Elev= 30
  3534.8  327.45  3615.2  321.74  3706.0  308.14  3776.7  303.45  3968.4  303.37
  3975.8  302.44  3980.9  296.27  3988.5  295.48  4008.7  302.28  4150.0  297.00
  4170.2  294.93  4190.3  283.94  4210.5  282.43  4240.8  286.34  4250.9  294.16
  4271.1  296.12  4282.5  290.80  4301.3  297.31  4584.1  296.00  4765.5  316.49
  4977.2  294.53  4997.0  282.43  4999.8  281.93  5003.0  282.43  5037.3  295.06
  5057.3  296.42  5527.3  293.53  5897.3  296.92  6087.3  312.05  6237.5  338.02
#Mann=3,-1,0
  3534.8    0.15       0  4997.0    0.05       0  5003.0    0.15       0
Bank Sta=4997,5003
Exp/Cntr=0.3,0.1

Type RM Length L Ch R = 1,1857,475,475,475
BEGIN DESCRIPTION:
Mapping XS c951c105
END DESCRIPTION:
XS GIS Cut Line= 3
      3751915.32     10597715.25      3750769.51     10597387.13
      3749087.22     10597512.13
#Sta/Elev= 30
  3558.7  325.76  3616.7  327.70  3803.9  317.36  3850.1  306.28  3866.3  298.10
  3876.7  299.37  3889.1  306.69  4252.7  296.13  4426.7  297.20  4465.7  282.47
  4480.0  282.34  4490.4  292.82  4499.5  294.41  4504.7  289.90  4511.2  290.43
  4683.9  316.20  4770.5  320.35  4920.9  304.61  4951.0  295.02  4981.1  292.24
  4990.2  285.02  4995.2  286.17  4997.0  282.34  4999.8  281.84  5003.0  282.34
  5031.2  295.13  5522.6  291.62  6054.1  294.90  6204.2  307.11  6437.5  341.97
#Mann=3,-1,0
  3558.7    0.15       0  4997.0    0.05       0  5003.0    0.15       0
Bank Sta=4997,5003
Exp/Cntr=0.3,0.1

Type RM Length L Ch R = 1,1382,0,0,0
BEGIN DESCRIPTION:
UNT 050 IN BOCR 1.0
END DESCRIPTION:
XS GIS Cut Line= 4
      3751330.39     10596772.07      3750671.13     10597106.84
      3750586.29     10597022.17      3749073.48     10597487.11
#Sta/Elev= 30
  4062.1  321.08  4135.6  324.99  4180.1  322.04  4202.3  319.79  4285.8  301.82
  4365.8  293.44  4397.1  292.19  4500.4  294.84  4514.0  283.31  4522.8  280.48
  4545.2  291.98  4558.5  294.15  4641.9  294.66  4736.5  300.88  4878.0  291.96
  4970.6  292.88  4980.7  291.66  4991.1  286.96  4997.0  280.48  4999.8  279.98
  5003.0  280.48  5003.3  283.35  5022.5  291.48  5036.0  292.78  5252.7  290.55
  5340.8  292.00  5923.1  290.00  6173.3  296.66  6260.7  305.66  6504.0  343.08
#Mann=3,-1,0
  4062.1    0.15       0  4997.0    0.05       0  5003.0    0.15       0
Bank Sta=4997,5003
Exp/Cntr=0.3,0.1

Chan Stop Cuts=-1