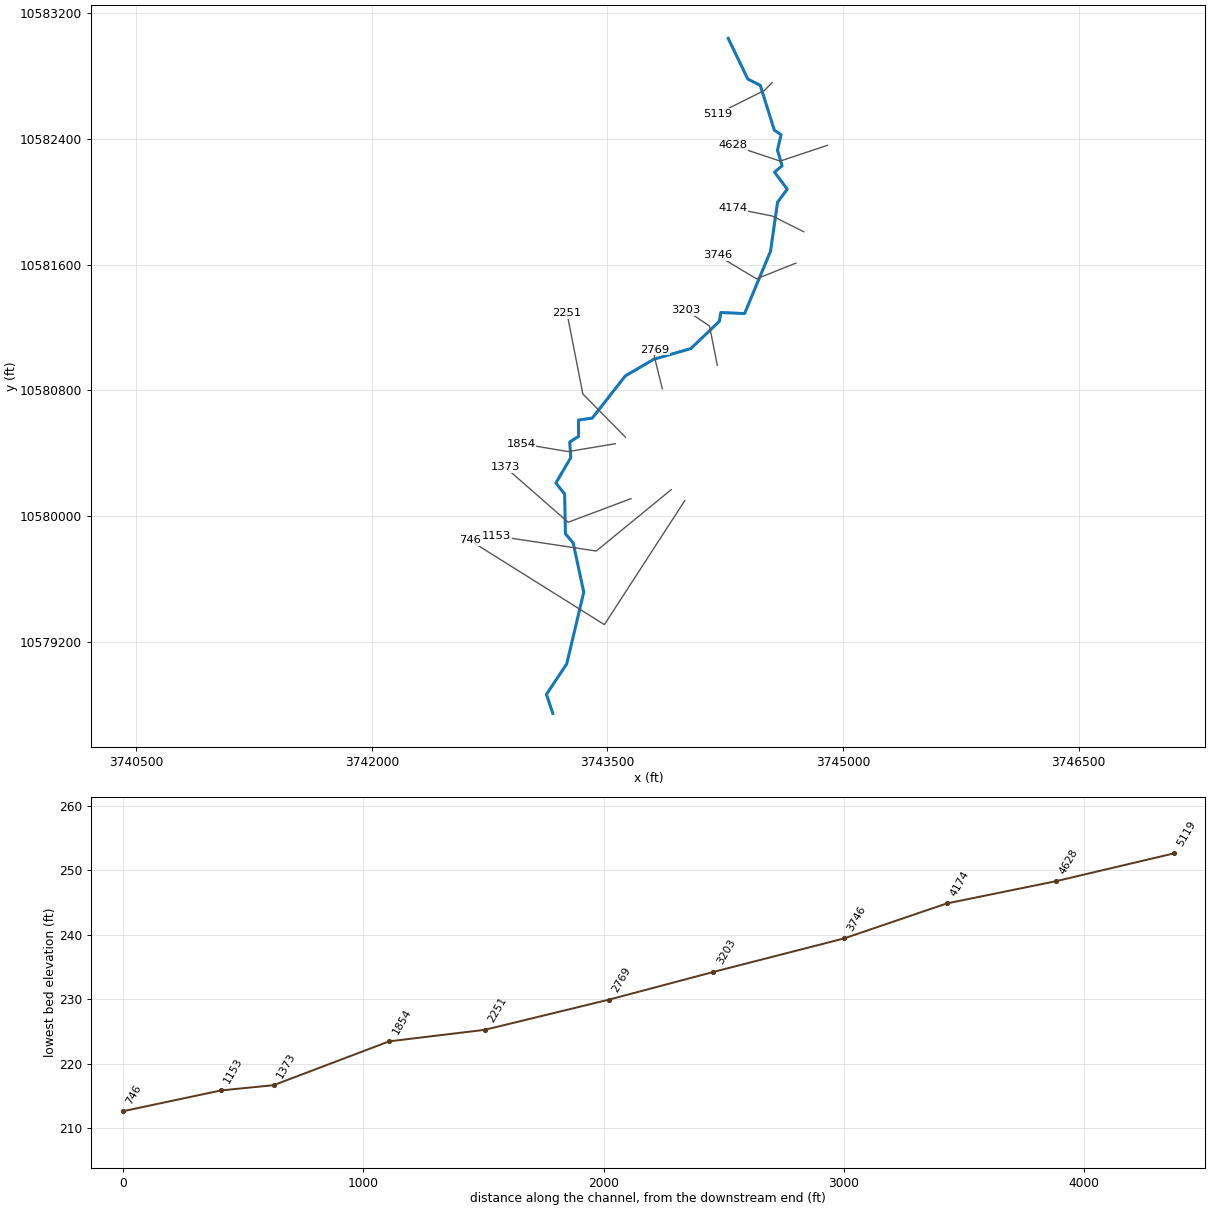
--- UNT 051 IN BOCR.prj (project) ---

Proj Title=UNT 051 IN BOCR Base Level Engineering
Current Plan=p01
Default Exp/Contr=0.3,0.1
English Units
Geom File=g01
Flow File=f01
Plan File=p01
Y Axis Title=Elevation
X Axis Title(PF)=Main Channel Distance
X Axis Title(XS)=Station
BEGIN DESCRIPTION:
UNT 051 IN BOCR
END DESCRIPTION:
DSS File=dss
DSS Export Rating Curves= 0
DSS Export Rating Curve Sorted= 0
DSS Export Volume Flow Curves= 0
DXF OffsetX= 0
DXF OffsetY= 0
DXF ScaleX= 1
DXF ScaleY= 10

--- UNT 051 IN BOCR.p01 (plan) ---

Plan Title=Multiple Run
Program Version=4.10
Short Identifier=Multiple Run
Geom File=g01
Flow File=f01
Subcritical Flow
K Sum by GR= 0
Std Step Tol= 0.01
Critical Tol= 0.01
Num of Std Step Trials= 20
Max Error Tol= 0.3
Flow Tol Ratio= 0.001
Split Flow NTrial= 30
Split Flow Tol= 0.02
Split Flow Ratio= 0.02
Log Output Level= 0
Friction Slope Method= 1
Unsteady Friction Slope Method= 2
Unsteady Bridges Friction Slope Method= 1
Parabolic Critical Depth
Global Vel Dist= 1 , 1 , 1
Global Log Level= 0
CheckData=True
Encroach Param=-1 ,0,0, 0
BEGIN DESCRIPTION:
Multiple Run
END DESCRIPTION:
Computation Interval=1HOUR
Output Interval=1HOUR
Run HTab= 0
Run UNet= 0
Run PostProcess= 0
Run WQNet= 0
UNET Theta= 1
UNET Theta Warmup= 1
UNET ZTol= 0.02
UNET ZSATol= 0.05
UNET MxIter= 20
UNET MaxInSteps= 0
UNET DtIC= 0
UNET DtMin= 0
UNET MaxCRTS= 20
UNET WFStab= 2
UNET SFStab= 1
UNET WFX= 1
UNET SFX= 1
UNET DSS MLevel= 4
UNET DZMax Abort= 100
UNET Convert EG Bridges= 0
UNET Use Existing IB Tables=-1
UNET Froude Reduction=False
UNET Froude Limit= 1
UNET Froude Power= 10
UNET Time Slicing=0,0, 5
UNET Junction Losses=0
Instantaneous Interval=1HOUR
DSS File=dss
Write IC File= 0
Write IC File at Sim End=0
Echo Input=False
Echo Parameters=False
Echo Output=False
Write Detailed= 0
WQ AD Non Conservative
WQ ULTIMATE=-1
WQ Max Comp Step=1HOUR
WQ Output Interval=15MIN
WQ Output Selected Increments= 0
WQ Output face flow=0
WQ Output face velocity=0
WQ Output face area=0
WQ Output face dispersion=0
WQ Output cell volume=0
WQ Output cell surface area=0
WQ Output cell continuity=0
WQ Output cumulative cell continuity=0
WQ Output face conc=0
WQ Output face dconc_dx=0
WQ Output face courant=0
WQ Output face peclet=0
WQ Output face adv mass=0
WQ Output face disp mass=0
WQ Output cell mass=0
WQ Output cell source sink temp=0
WQ Output cell source sink nsm=0
WQ Output MaxMinRange=-1
WQ Daily Max Min Mean=-1
WQ Daily Range=0
WQ Daily Time=0
WQ Create Restart=0
WQ Fixed Restart=0
WQ System Summary=0
WQ Use Fixed Temperature=0
Sorting and Armoring Iterations= 10
XS Update Threshold= 0.02
Hydraulics Update Threshold= 0.02
Energy Slope Method= 1
Volume Change Method= 0
XS Weighting Method= 0
Number of US Weighted Cross Sections= 1
Number of DS Weighted Cross Sections= 1
Upstream XS Weight=0.25
Main XS Weight=0.5
Downstream XS Weight=0.25
Number of DS XS's Weighted with US Boundary= 1
Upstream Boundary Weight= 1
Weight of XSs Associated with US Boundary= 0
Number of US XS's Weighted with DS Boundary= 1
Downstream Boundary Weight= 0.5
Weight of XSs Associated with DS Boundary= 0.5
Sediment Output Level= 4
Mass or Volume Output= 0
Output Increment Type= 1
Profile and TS Output Increment= 10
XS Output Flag= 0
XS Output Increment= 10
Disregard all LS=0
Disregard all Conn=0
Disregard all Breaches=0
Disregard all Pumps=0

--- UNT 051 IN BOCR.f01 (steady flow) ---

Flow Title=Multiple
Program Version=4.10
Number of Profiles= 7
Profile Names=10-year,25-year,50-year,1pct_min,100-year,1pct_plu,500-year
River Rch & RM=UNT 051 IN BOCR,Reach-1         ,5119
     431     576     696     619     837    1131    1213
River Rch & RM=UNT 051 IN BOCR,Reach-1         ,1854
     648     889    1090     984    1331    1800    1988
Boundary for River Rch & Prof#=UNT 051 IN BOCR,Reach-1         , 1
Up Type= 0
Dn Type= 3
Dn Slope=0.005
Boundary for River Rch & Prof#=UNT 051 IN BOCR,Reach-1         , 2
Up Type= 0
Dn Type= 3
Dn Slope=0.005
Boundary for River Rch & Prof#=UNT 051 IN BOCR,Reach-1         , 3
Up Type= 0
Dn Type= 3
Dn Slope=0.005
Boundary for River Rch & Prof#=UNT 051 IN BOCR,Reach-1         , 4
Up Type= 0
Dn Type= 3
Dn Slope=0.005
Boundary for River Rch & Prof#=UNT 051 IN BOCR,Reach-1         , 5
Up Type= 0
Dn Type= 3
Dn Slope=0.005
Boundary for River Rch & Prof#=UNT 051 IN BOCR,Reach-1         , 6
Up Type= 0
Dn Type= 3
Dn Slope=0.005
Boundary for River Rch & Prof#=UNT 051 IN BOCR,Reach-1         , 7
Up Type= 0
Dn Type= 3
Dn Slope=0.005
DSS Import GetInterval= 0
DSS Import GetPeak= 0
DSS Import FillOption= 0

--- UNT 051 IN BOCR.g01 (geometry) ---

Geom Title=Existing Conditions
Program Version=4.10

River Reach=UNT 051 IN BOCR ,Reach-1
Reach XY= 30
      3744268.74     10583041.81      3744393.25       10582783.
      3744473.25       10582742.       3744562.5       10582457.
       3744605.5       10582428.       3744582.5       10582330.
        3744612.       10582230.      3744563.75       10582190.
        3744645.       10582081.       3744583.5       10581999.
      3744538.25       10581686.      3744373.25       10581289.
      3744221.75       10581296.      3744212.75       10581240.
      3744030.75       10581066.        3743795.       10580998.
      3743613.75       10580892.      3743402.75       10580623.
        3743315.       10580611.      3743316.25       10580507.
       3743259.5       10580471.       3743266.5       10580372.
       3743171.5       10580210.      3743227.25       10580140.
      3743232.25       10579887.      3743281.75       10579828.
        3743349.       10579515.       3743240.5       10579058.
      3743111.25       10578864.      3743151.75       10578743.

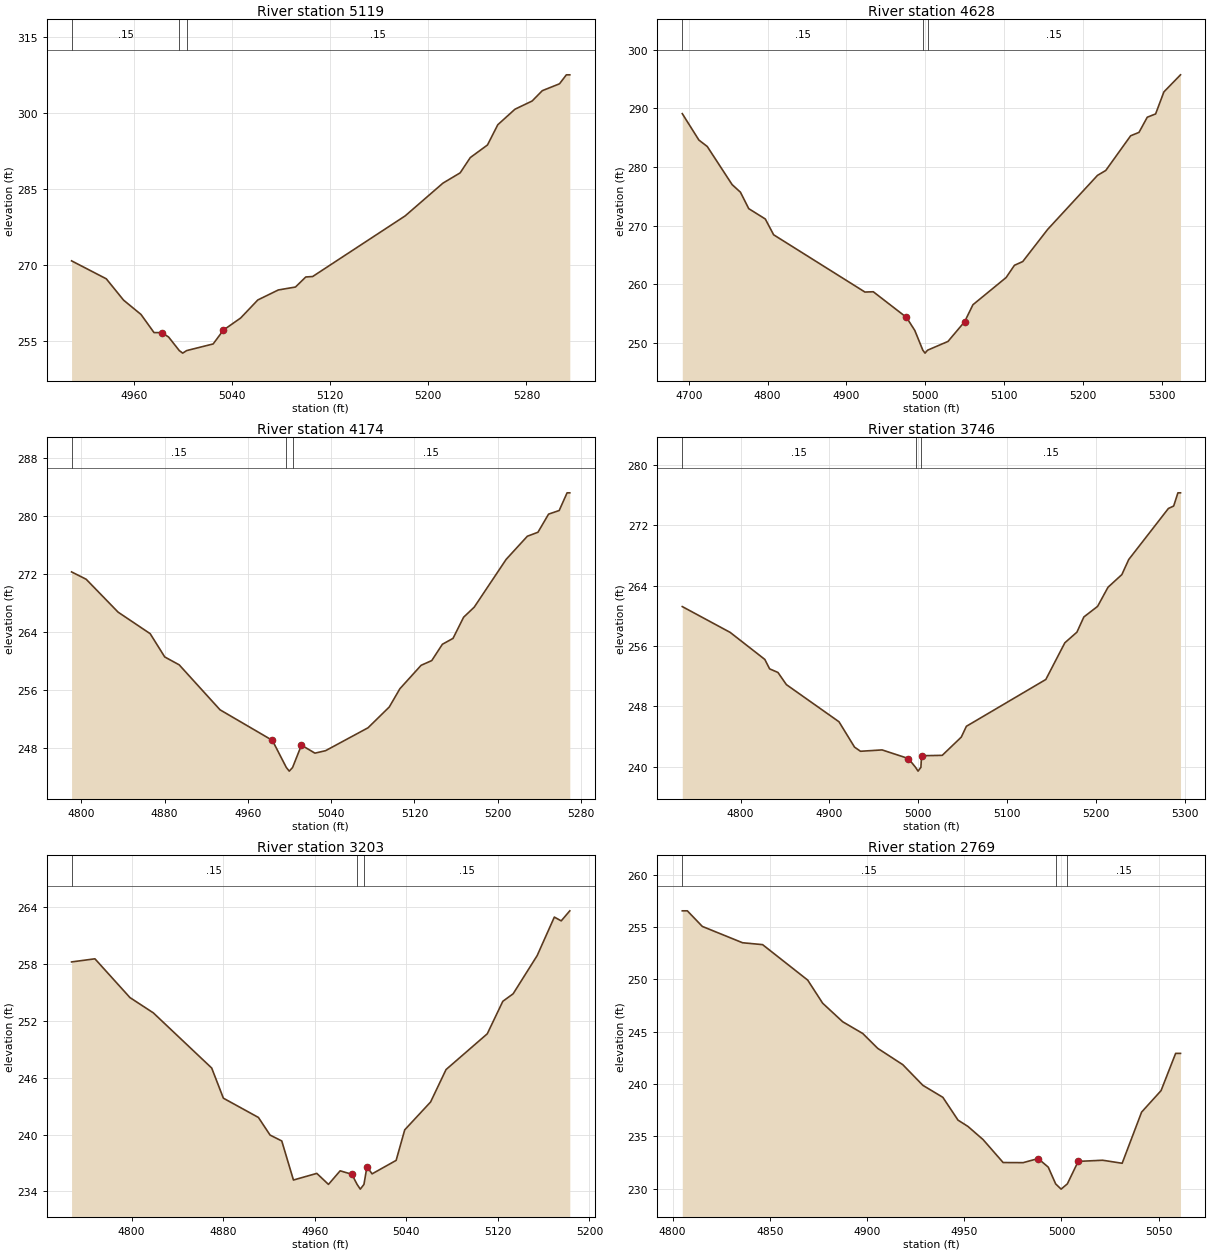
Type RM Length L Ch R = 1 ,5119    ,491,491,491
BEGIN DESCRIPTION:
UNT 051 IN BOCR 10.0
END DESCRIPTION:
XS GIS Cut Line= 3
       3744549.6     10582760.18      3744499.61     10582710.19
      3744199.61     10582560.19
#Sta/Elev= 30
  4909.2  270.81  4937.5  267.27  4951.6  263.06  4965.8  260.24  4976.4  256.67
  4982.7  256.67  4988.3  255.79    4997  253.12  4999.8  252.62    5003  253.12
  5024.6  254.43    5033  257.17    5047  259.54    5061   263.1  5077.7  265.07
  5091.7  265.65  5100.1  267.63  5105.7  267.72  5181.1  279.67  5211.9  286.13
  5225.9  288.15  5234.2  291.17  5248.2  293.65  5256.6  297.64  5270.6   300.7
  5284.6  302.32  5292.9  304.36  5306.9  305.71  5312.5  307.48  5315.3  307.48
#Mann= 3 ,-1 , 0
  4909.2     .15       0    4997     .05       0    5003     .15       0
Bank Sta=4982.7,5033
XS Rating Curve= 0 ,0
Exp/Cntr=0.3,0.1

Type RM Length L Ch R = 1 ,4628    ,454,454,454
BEGIN DESCRIPTION:
UNT 051 IN BOCR 9.0
END DESCRIPTION:
XS GIS Cut Line= 3
      3744899.64      10582360.2      3744599.61     10582260.19
       3744299.6     10582360.19
#Sta/Elev= 30
  4691.6  289.09  4712.7  284.59  4723.3   283.5  4754.9     277  4765.4  275.72
    4776  272.91    4797  271.15  4807.6  268.46  4923.5  258.71  4934.1  258.76
  4976.2   254.4  4986.8  252.17    4997  248.81  4999.8  248.31    5003  248.81
  5028.9   250.3    5050  253.65  5060.6  256.55  5102.7  261.18  5113.3  263.27
  5123.8   263.9  5155.4  269.37  5218.7  278.58  5229.2  279.41  5260.8  285.32
  5271.4   285.9  5281.9  288.48  5292.5  289.04    5303  292.79  5324.1   295.7
#Mann= 3 ,-1 , 0
  4691.6     .15       0    4997     .05       0    5003     .15       0
Bank Sta=4976.2,5050
XS Rating Curve= 0 ,0
Exp/Cntr=0.3,0.1

Type RM Length L Ch R = 1 ,4174    ,428,428,428
BEGIN DESCRIPTION:
UNT 051 IN BOCR 8.0
END DESCRIPTION:
XS GIS Cut Line= 3
      3744749.62     10581810.18      3744549.61     10581910.19
      3744299.58     10581960.19
#Sta/Elev= 30
  4790.7  272.34  4804.7  271.33  4835.4  266.79  4866.2  263.82  4880.2  260.61
  4894.1  259.52  4933.3  253.32  4983.6   249.1    4997  245.36  4999.8  244.86
    5003  245.36  5011.5  248.44  5024.5  247.34  5034.7  247.68  5075.5  250.84
  5095.9  253.71  5106.1  256.23  5126.5  259.46  5136.7  260.11  5146.9  262.36
  5157.1  263.17  5167.3  266.09  5177.5  267.48  5208.1  274.06  5228.5  277.26
  5238.7  277.81  5248.9  280.31  5259.1  280.81  5266.7  283.25  5269.3  283.25
#Mann= 3 ,-1 , 0
  4790.7     .15       0    4997     .05       0    5003     .15       0
Bank Sta=4983.6,5011.5
XS Rating Curve= 0 ,0
Exp/Cntr=0.3,0.1

Type RM Length L Ch R = 1 ,3746    ,543,543,543
BEGIN DESCRIPTION:
UNT 051 IN BOCR 7.0
END DESCRIPTION:
XS GIS Cut Line= 3
      3744699.64      10581610.2      3744449.61     10581510.19
      3744199.64     10581660.17
#Sta/Elev= 30
  4734.4  261.23  4788.3  257.81  4827.3  254.23  4832.7  252.98  4842.1   252.5
  4851.6  250.89  4910.8  245.97  4928.3  242.61    4935  242.06  4959.3  242.24
  4988.9   241.1    4997  239.93  4999.8  239.43    5003  239.93  5003.7  241.47
    5027  241.52  5048.4  243.93  5054.2  245.37  5143.6  251.57    5165  256.43
  5178.6  257.84  5186.4  259.85  5201.9  261.26  5213.6  263.79  5229.2  265.47
  5236.9  267.46  5281.6  274.23  5287.5  274.55  5292.3   276.3  5295.2   276.3
#Mann= 3 ,-1 , 0
  4734.4     .15       0    4997     .05       0    5003     .15       0
Bank Sta=4988.9,5003.7
XS Rating Curve= 0 ,0
Exp/Cntr=0.3,0.1

Type RM Length L Ch R = 1 ,3203    ,434,434,434
BEGIN DESCRIPTION:
UNT 051 IN BOCR 6.0
END DESCRIPTION:
XS GIS Cut Line= 3
      3744199.61     10580960.17      3744149.61     10581210.19
      3743999.65     10581310.16
#Sta/Elev= 30
  4747.6   258.2    4768  258.53  4798.6  254.44    4819  252.83    4870  247.01
  4880.2  243.83  4910.8   241.8    4921  239.94  4931.2  239.32  4941.4   235.2
  4961.8   235.9    4972  234.74  4982.2  236.17  4992.4  235.81    4997  234.74
  4999.8  234.24    5003  234.74  5005.6   236.6  5010.1  235.85  5031.1  237.27
  5038.6  240.49  5061.2  243.43  5074.7  246.85  5110.7  250.62  5124.3  254.05
  5133.3  254.84  5154.3  258.87  5169.3  262.93  5175.3  262.53  5182.8  263.59
#Mann= 3 ,-1 , 0
  4747.6     .15       0    4997     .05       0    5003     .15       0
Bank Sta=4992.4,5005.6
XS Rating Curve= 0 ,0
Exp/Cntr=0.3,0.1

Type RM Length L Ch R = 1 ,2769    ,518,518,518
BEGIN DESCRIPTION:
UNT 051 IN BOCR 5.0
END DESCRIPTION:
XS GIS Cut Line= 3
      3743849.62     10580810.15      3743799.61     10581010.19
      3743799.61      10581060.2
#Sta/Elev= 30
    4805  256.54  4807.6  256.54  4815.3  255.05    4836  253.49  4846.3  253.31
  4869.5  249.92  4877.2  247.71  4887.5  245.94  4897.8  244.82  4905.5   243.4
  4918.4  241.84  4928.7  239.87    4939  238.72  4946.8  236.54  4951.9  235.94
  4959.7  234.68    4970  232.49  4980.3  232.48    4988  232.87  4993.2  232.05
    4997  230.45  4999.8  229.95    5003  230.45  5008.6   232.6  5021.2  232.71
  5031.2  232.42  5041.2  237.31  5051.2  239.36  5058.7  242.92  5061.2  242.92
#Mann= 3 ,-1 , 0
    4805     .15       0    4997     .05       0    5003     .15       0
Bank Sta=4988,5008.6
XS Rating Curve= 0 ,0
Exp/Cntr=0.3,0.1

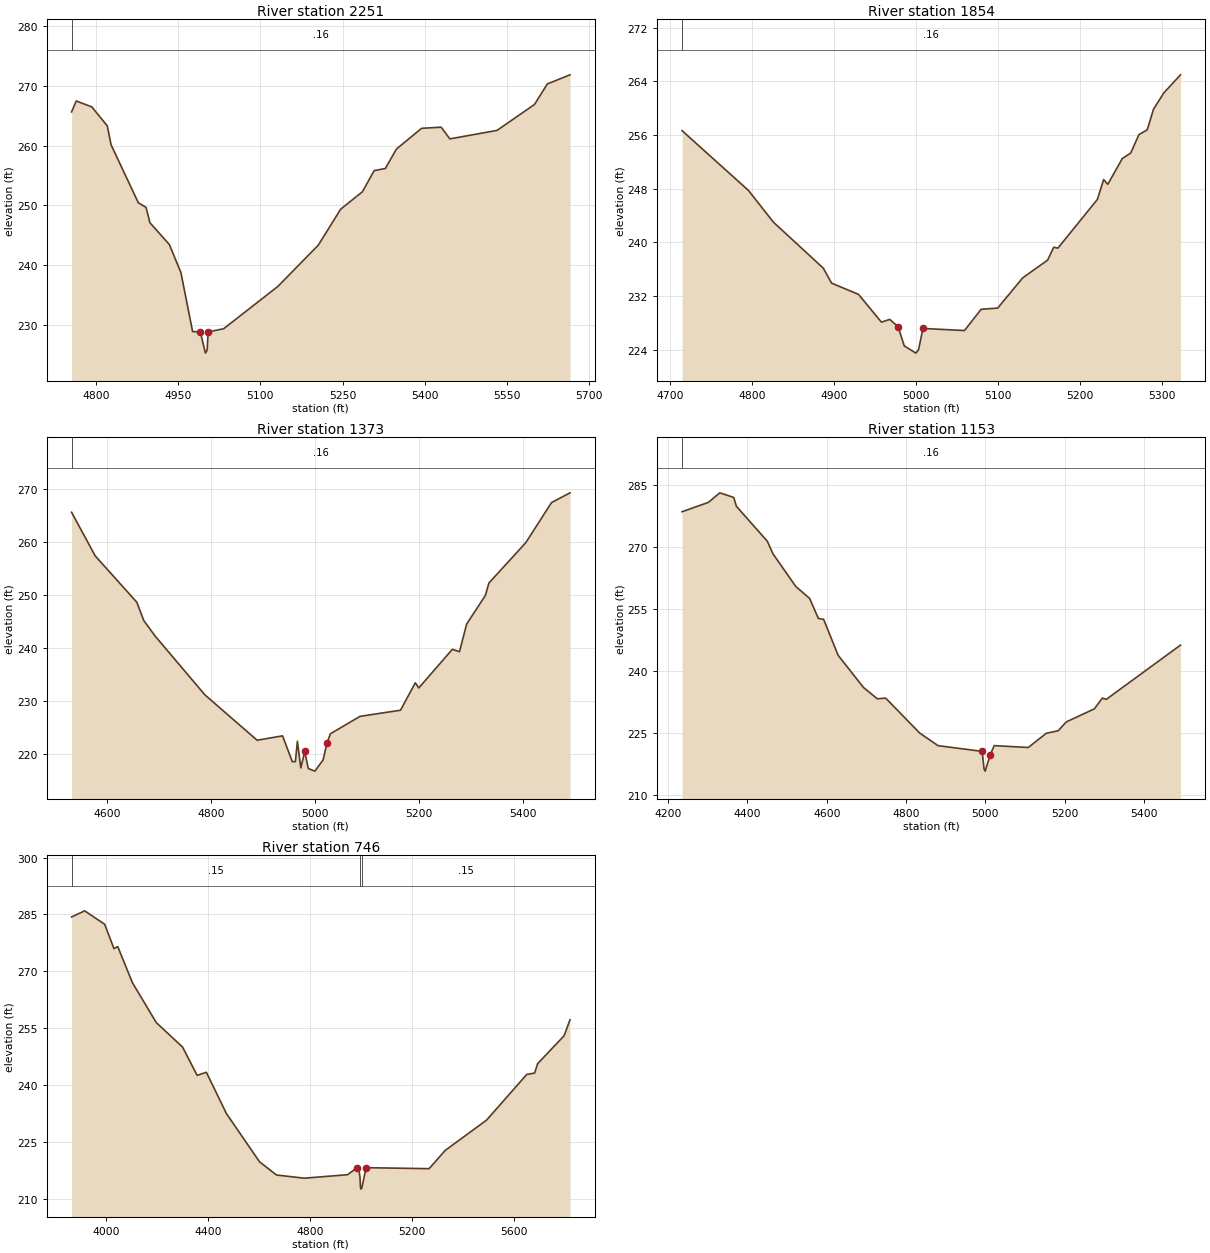
Type RM Length L Ch R = 1 ,2251    ,397,397,397
BEGIN DESCRIPTION:
UNT 051 IN BOCR 4.0
END DESCRIPTION:
XS GIS Cut Line= 3
      3743614.06     10580502.61      3743343.23     10580776.91
      3743242.54     10581290.76
#Sta/Elev= 30
  4755.7  265.62  4764.2  267.45  4792.5  266.47  4820.8  263.29  4827.8  260.11
  4877.4  250.43  4891.5  249.65  4898.6  247.08    4934  243.44  4955.1  238.75
  4976.4  228.87  4990.5  228.83  4999.8  225.26    5003  225.76  5004.7  228.81
    5033  229.34  5131.9  236.42  5205.7  243.33  5246.4  249.34  5286.1  252.26
  5307.6   255.8  5327.9  256.15  5348.3  259.42  5394.1  262.88  5429.8  263.07
  5445.6  261.11  5531.7  262.53    5600  266.87  5623.5  270.31  5664.8  271.83
#Mann= 1 ,-1 , 0
  4755.7     .16       0
Bank Sta=4990.5,5004.7
XS Rating Curve= 0 ,0
Exp/Cntr=0.3,0.1

Type RM Length L Ch R = 1 ,1854    ,481,481,481
BEGIN DESCRIPTION:
UNT 051 IN BOCR 3.0
END DESCRIPTION:
XS GIS Cut Line= 3
      3743549.62     10580460.19      3743249.61     10580410.19
      3742949.59     10580460.19
#Sta/Elev= 30
  4714.4  256.66  4795.5  247.74  4825.9  243.01  4886.8  236.15  4896.9  233.92
  4929.8  232.24  4957.7   228.1  4967.9  228.51    4978  227.42  4985.6  224.55
  4999.8  223.48    5003  223.98  5008.4  227.16  5059.1  226.85  5079.4  230.02
  5099.6   230.2  5130.1   234.7  5160.5  237.35  5168.1  239.28  5173.1  239.14
  5221.3  246.41  5228.9  249.37    5234  248.66  5251.7  252.51  5261.9  253.31
    5272  256.08  5282.1  256.78  5289.7  259.84  5302.4   262.3  5322.7  264.99
#Mann= 1 ,-1 , 0
  4714.4     .16       0
Bank Sta=4978,5008.4
XS Rating Curve= 0 ,0
Exp/Cntr=0.3,0.1

Type RM Length L Ch R = 1 ,1373    ,220,220,220
BEGIN DESCRIPTION:
UNT 051 IN BOCR 2.0
END DESCRIPTION:
XS GIS Cut Line= 3
      3743649.59     10580110.18      3743249.61     10579960.19
       3742849.6     10580310.19
#Sta/Elev= 30
  4531.8  265.55  4577.2  257.32  4657.3  248.56  4670.6  245.12  4692.9  242.13
  4788.1  231.09  4888.7  222.51  4937.6  223.34  4956.3  218.47  4962.3  218.47
  4966.1  222.31  4972.7  217.29  4980.3  220.39    4987  217.18  4999.8  216.68
  5015.5  218.78    5023  221.98  5029.7  223.74  5086.6  227.02  5164.5  228.18
  5192.9  233.36  5199.6  232.38  5264.1  239.67  5277.9  239.23  5291.6  244.43
  5327.7  249.85  5334.4  252.18  5405.5  259.82  5454.9  267.38  5490.5  269.22
#Mann= 1 ,-1 , 0
  4531.8     .16       0
Bank Sta=4980.3,5023
XS Rating Curve= 0 ,0
Exp/Cntr=0.3,0.1

Type RM Length L Ch R = 1 ,1153    ,407,407,407
BEGIN DESCRIPTION:
Mapping XS 7ad7a3d2
END DESCRIPTION:
XS GIS Cut Line= 3
      3743905.75     10580167.55       3743428.3     10579776.91
      3742794.65     10579872.39
#Sta/Elev= 30
  4234.9  278.64  4301.4  280.91  4330.1  283.22  4365.3  282.11    4372  279.96
    4450  271.51  4464.3  268.46  4521.8  260.56  4556.9  257.65  4578.8  252.82
  4592.1   252.6  4628.7   243.9  4692.6  236.12  4727.8  233.36  4748.6  233.54
  4834.7  225.07  4880.8  222.03  4992.1  220.64    4997  216.36  4999.8  215.86
  5012.3  219.72  5022.4  222.03  5108.5  221.58  5153.9  225.02  5184.2  225.64
  5204.4  227.77  5275.2  230.93  5295.4  233.52  5305.3  233.23  5492.6  246.36
#Mann= 1 ,-1 , 0
  4234.9     .16       0
Bank Sta=4992.1,5012.3
XS Rating Curve= 0 ,0
Exp/Cntr=0.3,0.1

Type RM Length L Ch R = 1 ,746     ,0,0,0
BEGIN DESCRIPTION:
UNT 051 IN BOCR 1.0
END DESCRIPTION:
XS GIS Cut Line= 3
      3743992.53     10580098.09      3743480.38     10579308.16
      3742621.95     10579845.76
#Sta/Elev= 30
  3864.4  284.34  3915.6  285.96  3994.1  282.43  4030.4  276.02  4045.5  276.53
  4102.9  267.03  4196.5  256.51  4299.3  250.09  4356.7  242.61  4392.9  243.42
  4471.4  232.56  4601.3  219.84  4667.9  216.36  4776.6  215.52  4946.7  216.44
  4983.2  218.27  4989.1  218.78  4995.5  215.57    4997  213.14  4999.8  212.64
    5003  213.14  5019.1  218.29  5266.1  218.03  5329.8  222.87  5491.1  230.79
  5649.2  242.86  5679.9  243.22  5691.7  245.69  5795.4  253.04  5818.7  257.26
#Mann= 3 ,-1 , 0
  3864.4     .15       0    4997     .05       0    5003     .15       0
Bank Sta=4983.2,5019.1
XS Rating Curve= 0 ,0
Exp/Cntr=0.3,0.1

Chan Stop Cuts=-1
Use User Specified Reach Order=0
Composite Channel Slope=5