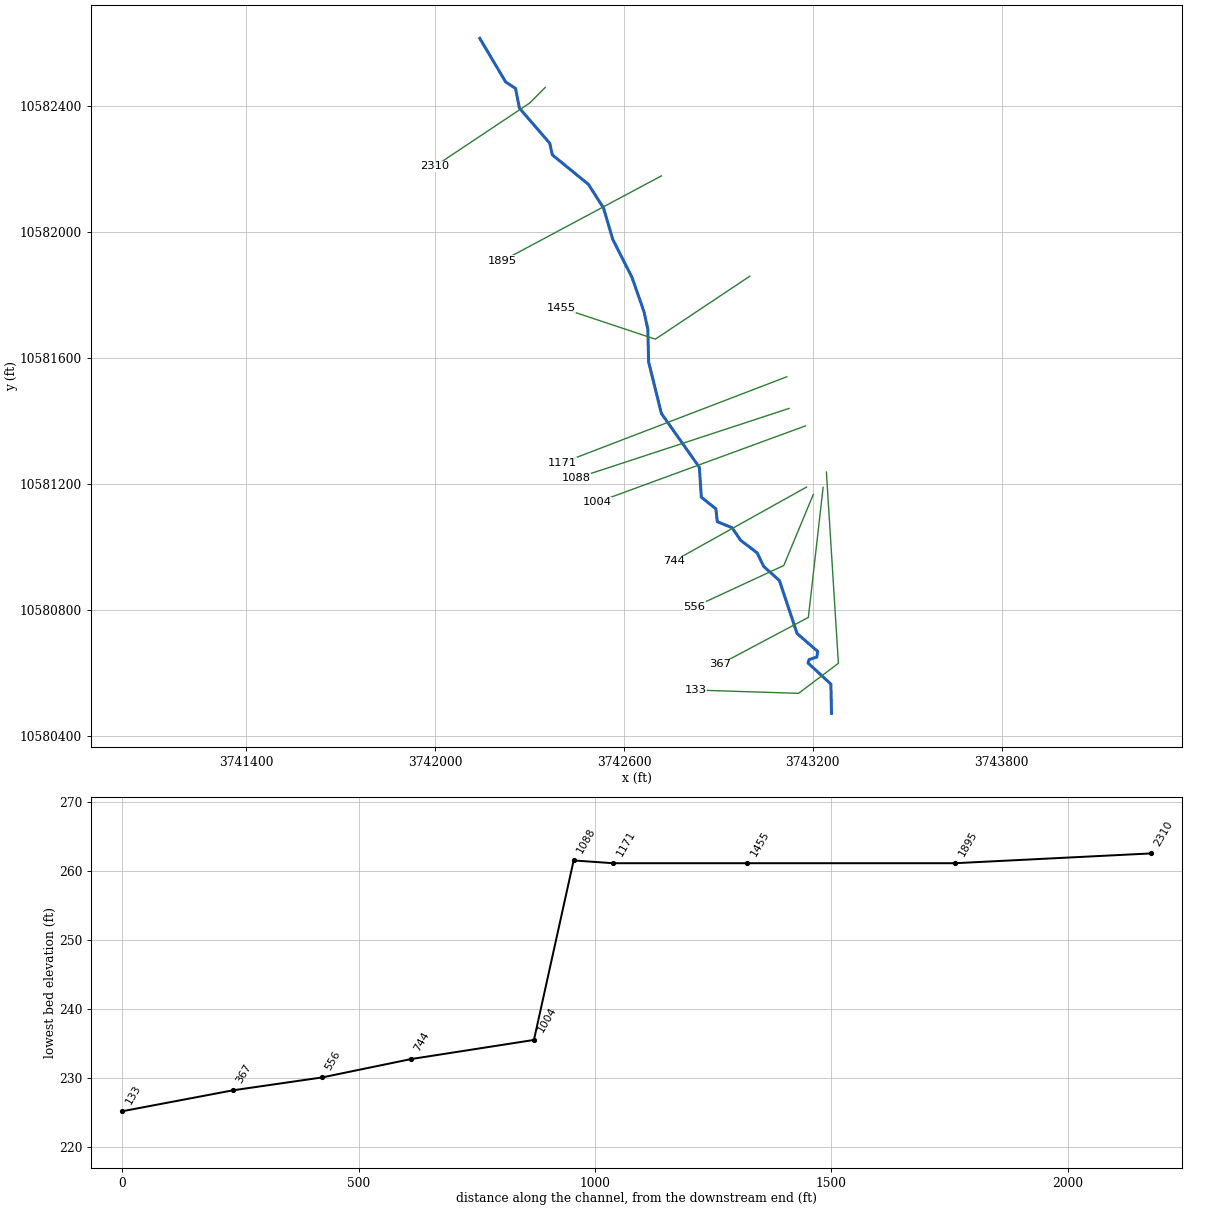
--- UNT 052 IN BOCR.prj (project) ---

Proj Title=UNT 052 IN BOCR Base Level Engineering
Current Plan=p01
Default Exp/Contr=0.3,0.1
English Units
Geom File=g01
Flow File=f01
Plan File=p01
Y Axis Title=Elevation
X Axis Title(PF)=Main Channel Distance
X Axis Title(XS)=Station
BEGIN DESCRIPTION:
UNT 052 IN BOCR
END DESCRIPTION:
DSS Export Rating Curves= 0
DSS Export Rating Curve Sorted= 0
DSS Export Volume Flow Curves= 0
DXF OffsetX= 0
DXF OffsetY= 0
DXF ScaleX= 1
DXF ScaleY= 10

--- UNT 052 IN BOCR.p01 (plan) ---

Plan Title=Multiple Run
Short Identifier=Multiple
Geom File=g01
Flow File=f01
Subcritical Flow
K Sum by GR= 0
Std Step Tol= 0.01
Critical Tol= 0.01
Num of Std Step Trials= 20
Max Error Tol= 0.3
Flow Tol Ratio= 0.001
Split Flow NTrial= 30
Split Flow Tol= 0.02
Split Flow Ratio= 0.02
Log Output Level= 0
Friction Slope Method= 1
Unsteady Friction Slope Method= 2
Unsteady Bridges Friction Slope Method= 1
Parabolic Critical Depth
Global Vel Dist=  1 , 1 , 1
Global Log Level= 0
CheckData=True
Encroach Param= -1, 0, 0, 0
BEGIN DESCRIPTION:
Multiple Run
END DESCRIPTION:

--- UNT 052 IN BOCR.f01 (steady flow) ---

Flow Title=Multiple
Program Version=4.10
Number of Profiles= 7
Profile Names=10-year,25-year,50-year,1pct_min,100-year,1pct_plu,500-year
River Rch & RM=UNT 052 IN BOCR,Reach-1         ,2310
     322     426     509     450     609     823     871
Boundary for River Rch & Prof#=UNT 052 IN BOCR,Reach-1         , 1
Up Type= 0
Dn Type= 3
Dn Slope=0.01
Boundary for River Rch & Prof#=UNT 052 IN BOCR,Reach-1         , 2
Up Type= 0
Dn Type= 3
Dn Slope=0.01
Boundary for River Rch & Prof#=UNT 052 IN BOCR,Reach-1         , 3
Up Type= 0
Dn Type= 3
Dn Slope=0.01
Boundary for River Rch & Prof#=UNT 052 IN BOCR,Reach-1         , 4
Up Type= 0
Dn Type= 3
Dn Slope=0.01
Boundary for River Rch & Prof#=UNT 052 IN BOCR,Reach-1         , 5
Up Type= 0
Dn Type= 3
Dn Slope=0.01
Boundary for River Rch & Prof#=UNT 052 IN BOCR,Reach-1         , 6
Up Type= 0
Dn Type= 3
Dn Slope=0.01
Boundary for River Rch & Prof#=UNT 052 IN BOCR,Reach-1         , 7
Up Type= 0
Dn Type= 3
Dn Slope=0.01
DSS Import GetInterval= 0
DSS Import GetPeak= 0
DSS Import FillOption= 0

--- UNT 052 IN BOCR.g01 (geometry) ---

Geom Title=Existing Conditions
Program Version=4.10

River Reach=UNT 052 IN BOCR ,Reach-1
Reach XY= 30
      3742141.65     10582616.33      3742223.75       10582478.
      3742255.25       10582457.        3742268.       10582394.
        3742364.       10582283.      3742372.25       10582246.
      3742487.25       10582152.        3742535.       10582077.
       3742564.5       10581977.      3742625.25       10581857.
       3742663.5       10581748.      3742675.75       10581692.
      3742678.25       10581588.        3742719.       10581424.
       3742839.5       10581253.      3742845.75       10581158.
        3742892.       10581121.       3742896.5       10581080.
       3742943.5       10581061.      3742970.75       10581021.
      3743023.25       10580981.        3743044.       10580938.
        3743094.       10580893.        3743150.       10580725.
       3743215.5       10580668.        3743213.       10580650.
       3743188.5       10580642.        3743185.       10580631.
       3743257.5       10580564.       3743259.5       10580471.

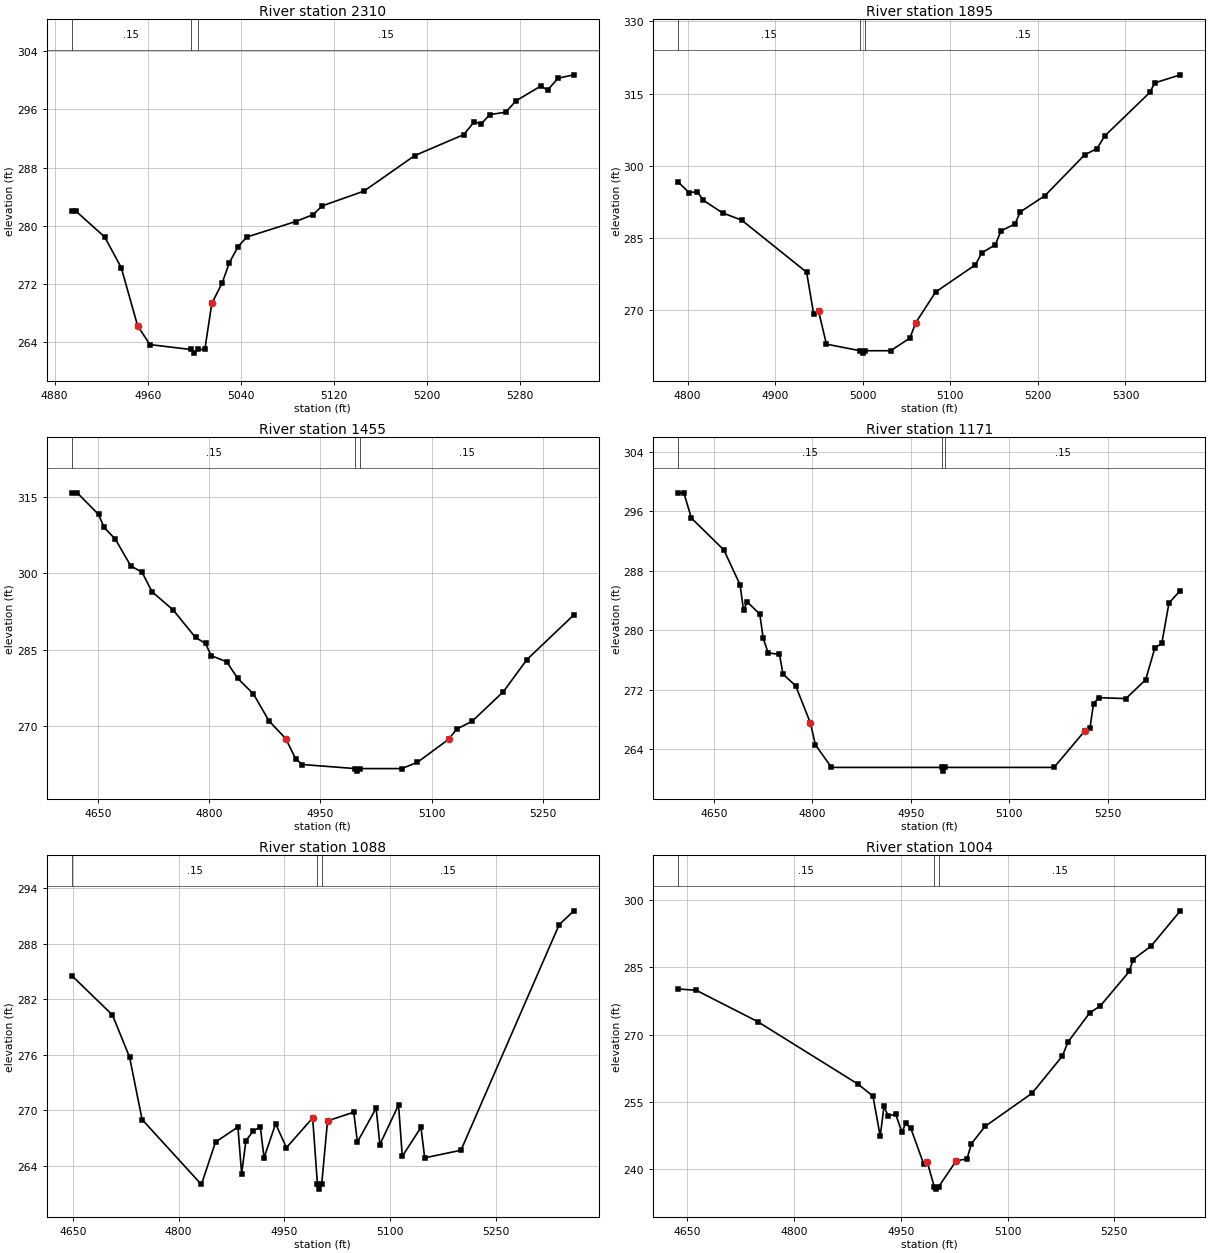
Type RM Length L Ch R = 1 ,2310    ,415,415,415
BEGIN DESCRIPTION:
UNT 052 IN BOCR 5.0
END DESCRIPTION:
XS GIS Cut Line= 3
      3742349.63     10582460.21      3742299.61     10582410.19
      3741999.61     10582210.19
#Sta/Elev= 30
  4894.7  282.02  4898.3  282.02    4923  278.47  4937.2  274.26  4951.3  266.25
  4961.9  263.68    4997  263.01  4999.8  262.51    5003  263.01    5009  263.01
    5015  269.34    5024  272.19    5030  274.92  5037.6  277.16  5045.1  278.47
  5087.1   280.6  5102.2  281.56  5109.7  282.74  5145.7  284.78  5189.3  289.66
  5231.4  292.54  5240.4   294.3  5246.4  294.01  5253.9   295.3  5267.4  295.62
  5276.4  297.19  5297.5  299.21  5303.5  298.68  5312.5   300.3    5326  300.76
#Mann= 3 ,-1 , 0
  4894.7     .15       0    4997     .05       0    5003     .15       0
Bank Sta=4951.3,5015
XS Rating Curve= 0 ,0
Exp/Cntr=0.3,0.1

Type RM Length L Ch R = 1 ,1895    ,440,440,440
BEGIN DESCRIPTION:
UNT 052 IN BOCR 4.0
END DESCRIPTION:
XS GIS Cut Line= 2
      3742718.87     10582179.19       3742213.3     10581909.09
#Sta/Elev= 30
  4789.4  296.62  4801.7  294.44  4811.2  294.61    4818  292.83    4840  290.22
  4861.9   288.7    4936  277.89    4944  269.21  4949.7  269.74  4958.6  262.95
    4997  261.59  4999.8  261.09    5003  261.59  5031.8  261.59  5053.8   264.2
  5060.7  267.44  5083.3  273.79  5128.7  279.44  5135.9  281.91  5151.4  283.59
  5157.9  286.48    5174  287.93  5179.8  290.41  5208.1   293.8  5253.4  302.27
  5267.6  303.58  5276.1  306.15  5327.8  315.23  5333.4  317.21  5362.6  318.89
#Mann= 3 ,-1 , 0
  4789.4     .15       0    4997     .05       0    5003     .15       0
Bank Sta=4949.7,5060.7
XS Rating Curve= 0 ,0
Exp/Cntr=0.3,0.1

Type RM Length L Ch R = 1 ,1455    ,284,284,284
BEGIN DESCRIPTION:
UNT 052 IN BOCR 3.0
END DESCRIPTION:
XS GIS Cut Line= 3
      3742999.61     10581860.19      3742699.61     10581660.19
       3742399.6     10581760.19
#Sta/Elev= 30
  4614.9  315.82  4622.4   315.8    4651  311.56  4658.5  309.01  4673.5  306.73
  4694.5  301.43  4709.6  300.22  4723.1  296.36  4751.6  292.78  4781.7  287.37
  4795.2   286.2  4802.7  283.81  4823.7  282.59  4838.7  279.31  4859.8  276.26
  4880.8  270.96  4903.3  267.48  4916.9  263.44  4925.9  262.39    4997  261.59
  4999.8  261.09    5003  261.59  5059.8  261.59  5080.9  262.83    5123  267.36
  5133.6  269.33  5154.7  270.91  5196.8  276.73  5228.4  283.02  5291.7  291.82
#Mann= 3 ,-1 , 0
  4614.9     .15       0    4997     .05       0    5003     .15       0
Bank Sta=4903.3,5123
XS Rating Curve= 0 ,0
Exp/Cntr=0.3,0.1

Type RM Length L Ch R = 1 ,1171    ,83,83,83
BEGIN DESCRIPTION:
Mapping XS 93da44ac
END DESCRIPTION:
XS GIS Cut Line= 2
      3743117.56     10581540.81      3742403.47     10581266.96
#Sta/Elev= 30
  4595.9  298.43  4604.4  298.46    4616  295.06  4665.4  290.79  4690.1  286.11
  4695.4  282.68  4700.8  283.83  4720.1  282.18  4725.4   278.9  4732.9  276.97
  4750.1  276.76  4755.5  274.12  4774.8  272.54  4797.2  267.56  4804.8  264.64
  4829.3  261.59    4997  261.59  4999.8  261.09    5003  261.59  5168.4  261.59
  5214.9  266.46  5223.1  266.93  5228.5  270.12  5236.3  270.96  5277.8  270.83
  5307.9  273.36    5322  277.65  5332.5  278.24  5343.4  283.66  5360.7  285.34
#Mann= 3 ,-1 , 0
  4595.9     .15       0    4997     .05       0    5003     .15       0
Bank Sta=4797.2,5214.9
XS Rating Curve= 0 ,0
Exp/Cntr=0.3,0.1

Type RM Length L Ch R = 1 ,1088    ,84,84,84
BEGIN DESCRIPTION:
UNT 052 IN BOCR 2.0
END DESCRIPTION:
XS GIS Cut Line= 2
      3743124.47      10581440.1       3742447.4     10581217.88
#Sta/Elev= 30
  4648.3  284.56    4706   280.3  4730.3  275.76  4748.1  269.01  4832.3  261.99
  4852.3  266.57  4884.1   268.2  4889.4  263.15  4895.5  266.73    4906  267.78
  4915.9   268.2  4921.2  264.88  4937.6  268.55    4953  265.97  4990.2  269.18
    4997  261.99  4999.8  261.49    5003  261.99  5011.3  268.86  5048.5   269.8
  5053.7  266.58  5080.3  270.24  5085.6  266.31  5112.1  270.58  5117.4  265.03
  5143.9  268.16  5149.2  264.87  5200.7  265.69  5340.1  290.06  5360.9  291.55
#Mann= 3 ,-1 , 0
  4648.3     .15       0    4997     .05       0    5003     .15       0
Bank Sta=4990.2,5011.3
XS Rating Curve= 0 ,0
Exp/Cntr=0.3,0.1

Type RM Length L Ch R = 1 ,1004    ,260,260,260
BEGIN DESCRIPTION:
Mapping XS cbe70469
END DESCRIPTION:
XS GIS Cut Line= 2
      3743176.57     10581384.55      3742513.97     10581141.71
#Sta/Elev= 30
  4637.1   280.2  4662.4  279.91  4748.6  272.92  4889.5  258.97  4910.8  256.26
    4921  247.29  4926.3  254.01  4932.1  251.83  4942.7  252.22  4951.5   248.2
  4956.8  250.17    4964  249.07    4982  241.13  4987.3  241.44    4997  235.98
  4999.8  235.48    5003  235.98  5027.9  241.82    5043  242.24  5049.2  245.62
  5068.2  249.48  5134.5  256.92    5177  265.21  5184.9  268.34  5215.4  274.86
  5230.3  276.41  5271.1  284.11  5276.4  286.78  5301.6  289.76  5342.8  297.66
#Mann= 3 ,-1 , 0
  4637.1     .15       0    4997     .05       0    5003     .15       0
Bank Sta=4987.3,5027.9
XS Rating Curve= 0 ,0
Exp/Cntr=0.3,0.1

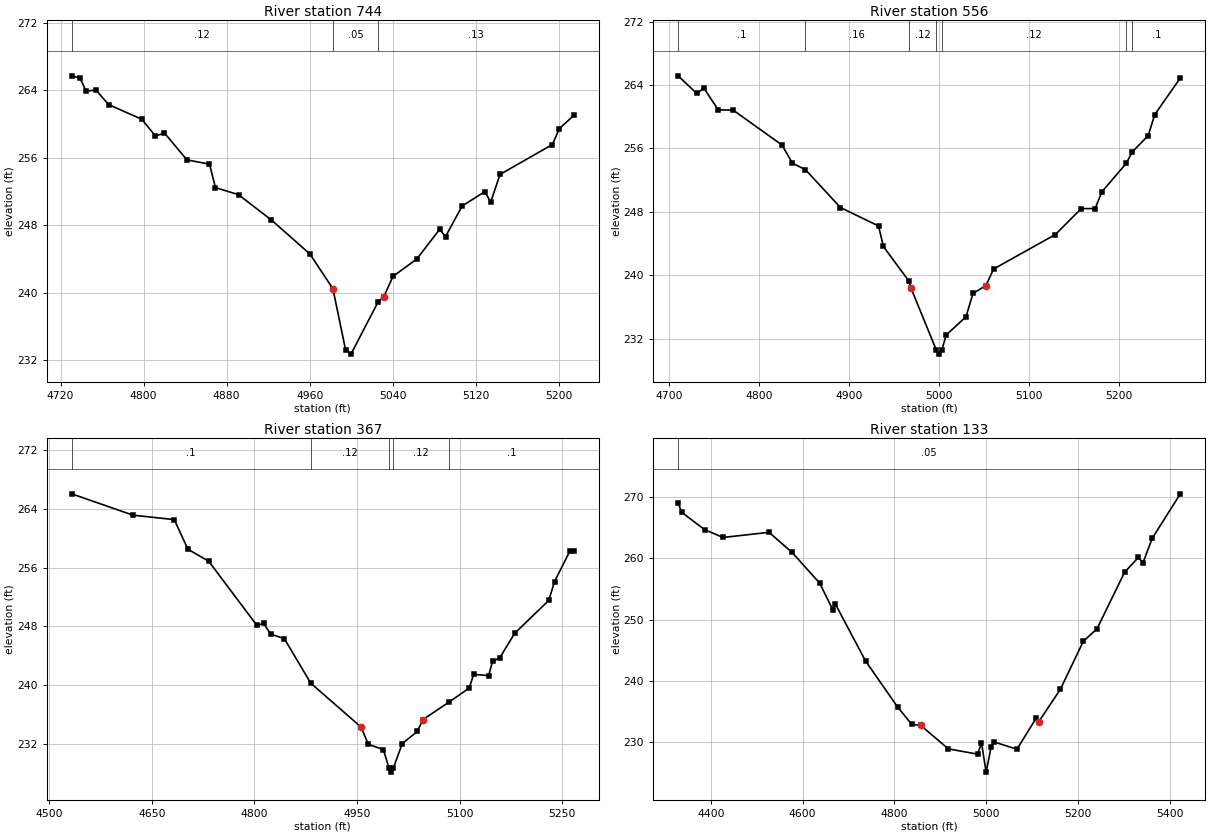
Type RM Length L Ch R = 1 ,744     ,188,188,188
BEGIN DESCRIPTION:
Mapping XS 83c63103
END DESCRIPTION:
XS GIS Cut Line= 2
      3743180.08     10581190.13      3742757.49     10580954.59
#Sta/Elev= 30
  4730.7  265.71  4738.9  265.42  4744.6  263.89  4754.1  264.03  4766.3   262.3
  4798.3  260.56  4811.4  258.57  4820.1  258.93  4841.8  255.74  4863.5  255.24
  4869.2  252.46  4891.5  251.61  4922.9  248.64  4960.2  244.59  4982.4  240.46
  4994.6  233.21  4999.8  232.71  5025.8  238.87  5031.5  239.54  5040.3  241.93
  5063.2  243.99  5085.2   247.5  5090.9  246.65  5106.9  250.28  5128.7  251.97
  5134.4  250.74  5143.4  254.02  5193.8  257.56  5200.6  259.46  5214.5  261.02
#Mann= 3 ,-1 , 0
  4730.7     .12       0  4982.4     .05       0  5025.8     .13       0
Bank Sta=4982.4,5031.5
XS Rating Curve= 0 ,0
Exp/Cntr=0.3,0.1

Type RM Length L Ch R = 1 ,556     ,189,189,189
BEGIN DESCRIPTION:
Mapping XS ed133e79
END DESCRIPTION:
XS GIS Cut Line= 3
      3743201.56     10581166.61      3743107.82     10580940.94
      3742823.89     10580809.36
#Sta/Elev= 30
  4710.4  265.16  4731.1  262.94    4739  263.61  4754.9  260.87  4771.5  260.83
  4825.6  256.44  4837.3  254.14  4851.7  253.32  4890.6  248.54  4932.8  246.22
  4938.2  243.63  4966.3  239.29  4968.9  238.36    4997  230.55  4999.8  230.05
    5003  230.55  5007.9  232.46  5029.9  234.77  5037.6  237.71    5052   238.7
  5060.5  240.79  5129.1  245.14  5157.7  248.41  5173.2  248.41  5180.6  250.52
  5207.6   254.1  5214.4  255.57    5232  257.61  5239.4  260.28  5267.7  264.89
#Mann= 7 ,-1 , 0
  4710.4      .1       0  4851.7     .16       0  4966.3     .12       0
    4997     .07       0    5003     .12       0  5207.6     .16       0
  5214.4      .1       0
Bank Sta=4968.9,5052
XS Rating Curve= 0 ,0
Exp/Cntr=0.3,0.1

Type RM Length L Ch R = 1 ,367     ,234,234,234
BEGIN DESCRIPTION:
Mapping XS 0846dded
END DESCRIPTION:
XS GIS Cut Line= 3
      3743232.82     10581189.22      3743185.94     10580776.01
      3742904.68      10580626.7
#Sta/Elev= 30
  4532.8  266.04  4622.4  263.14  4682.8  262.53  4702.9  258.49  4733.1  256.88
  4803.6  248.15  4813.6  248.42  4823.7  246.96  4843.8  246.34  4882.5  240.27
    4956  234.31  4966.6  231.96  4988.6  231.25    4997  228.68  4999.8  228.18
    5003  228.68  5016.2  232.06  5038.2  233.71  5046.4  235.32  5085.2  237.75
  5114.3  239.63  5120.5  241.48  5142.5  241.31  5148.3  243.27  5158.8  243.74
  5180.8  247.09  5230.4  251.53  5238.9  254.11  5261.5  258.29  5267.1  258.29
#Mann= 5 ,-1 , 0
  4532.8      .1       0  4882.5     .12       0    4997     .07       0
    5003     .12       0  5085.2      .1       0
Bank Sta=4956,5046.4
XS Rating Curve= 0 ,0
Exp/Cntr=0.3,0.1

Type RM Length L Ch R = 1 ,133     ,0,0,0
BEGIN DESCRIPTION:
UNT 052 IN BOCR 1.0
END DESCRIPTION:
XS GIS Cut Line= 4
      3743243.24     10581237.79      3743281.43     10580630.17
      3743154.69     10580534.69      3742828.35      10580545.1
#Sta/Elev= 30
  4328.8  269.07  4336.4  267.55  4386.5  264.71  4426.6  263.43  4526.8  264.27
  4576.9     261    4637     256  4665.8  251.64  4670.8  252.65  4737.2  243.27
  4807.3  235.74  4837.4  232.97  4857.4  232.76  4917.6  228.94  4981.4  228.08
  4989.7  229.94  4999.8  225.15  5010.6  229.23  5016.8  230.08  5066.8  228.88
  5109.2     234  5114.2  233.35  5161.4  238.64  5211.4  246.48  5241.5  248.55
  5301.5  257.77  5331.5  260.17  5341.5   259.3  5361.5  263.27  5422.8  270.55
#Mann= 1 ,-1 , 0
  4328.8     .05       0
Bank Sta=4857.4,5114.2
XS Rating Curve= 0 ,0
Exp/Cntr=0.3,0.1

Chan Stop Cuts=-1
Use User Specified Reach Order=0
Composite Channel Slope=5