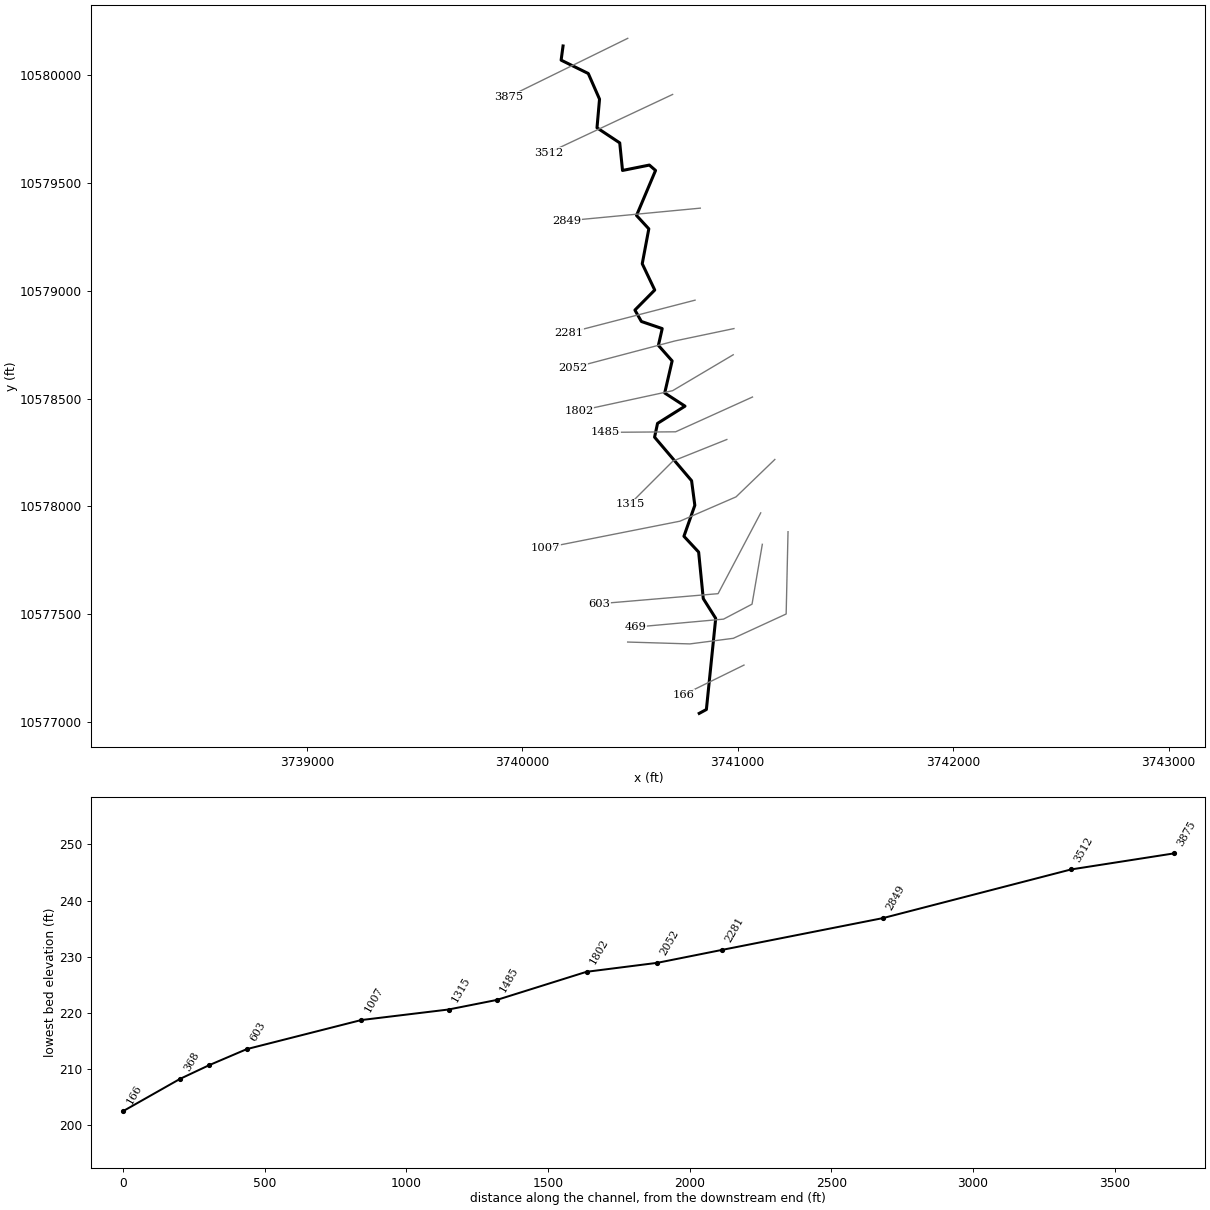
--- UNT 053 IN BOCR.prj (project) ---

Proj Title=UNT 053 IN BOCR Base Level Engineering
Current Plan=p01
Default Exp/Contr=0.3,0.1
English Units
Geom File=g01
Flow File=f01
Plan File=p01
BEGIN DESCRIPTION:
UNT 053 IN BOCR
END DESCRIPTION:

--- UNT 053 IN BOCR.p01 (plan) ---

Plan Title=Multiple Run
Short Identifier=Multiple
Geom File=g01
Flow File=f01
Subcritical Flow
K Sum by GR= 0
Std Step Tol= 0.01
Critical Tol= 0.01
Num of Std Step Trials= 20
Max Error Tol= 0.3
Flow Tol Ratio= 0.001
Split Flow NTrial= 30
Split Flow Tol= 0.02
Split Flow Ratio= 0.02
Log Output Level= 0
Friction Slope Method= 1
Unsteady Friction Slope Method= 2
Unsteady Bridges Friction Slope Method= 1
Parabolic Critical Depth
Global Vel Dist=  1 , 1 , 1
Global Log Level= 0
CheckData=True
Encroach Param= -1, 0, 0, 0
BEGIN DESCRIPTION:
Multiple Run
END DESCRIPTION:

--- UNT 053 IN BOCR.f01 (steady flow) ---

Flow Title=Multiple
Number of Profiles=7
Profile Names=10-year,25-year,50-year,1pct_min,100-year,1pct_plu,500-year
River Rch & RM= UNT 053 IN BOCR,Reach-1,3875
     319     419     498     438     592     800     836
Boundary for River Rch & Prof#=UNT 053 IN BOCR,Reach-1,1
Up Type=0
Dn Type=3
Dn Slope=0.005
Boundary for River Rch & Prof#=UNT 053 IN BOCR,Reach-1,2
Up Type=0
Dn Type=3
Dn Slope=0.005
Boundary for River Rch & Prof#=UNT 053 IN BOCR,Reach-1,3
Up Type=0
Dn Type=3
Dn Slope=0.005
Boundary for River Rch & Prof#=UNT 053 IN BOCR,Reach-1,4
Up Type=0
Dn Type=3
Dn Slope=0.005
Boundary for River Rch & Prof#=UNT 053 IN BOCR,Reach-1,5
Up Type=0
Dn Type=3
Dn Slope=0.005
Boundary for River Rch & Prof#=UNT 053 IN BOCR,Reach-1,6
Up Type=0
Dn Type=3
Dn Slope=0.005
Boundary for River Rch & Prof#=UNT 053 IN BOCR,Reach-1,7
Up Type=0
Dn Type=3
Dn Slope=0.005

--- UNT 053 IN BOCR.g01 (geometry) ---

Geom Title=Existing Conditions

River Reach=UNT 053 IN BOCR,Reach-1
Reach XY= 30
      3740189.43     10580136.82      3740180.50     10580071.00
      3740306.50     10580009.00      3740358.75     10579890.00
      3740347.00     10579757.00      3740452.50     10579687.00
      3740465.50     10579559.00      3740590.00     10579584.00
      3740618.75     10579559.00      3740530.50     10579350.00
      3740587.50     10579288.00      3740557.00     10579126.00
      3740615.00     10579004.00      3740523.00     10578911.00
      3740553.00     10578858.00      3740649.75     10578825.00
      3740632.00     10578747.00      3740695.75     10578675.00
      3740661.25     10578526.00      3740755.50     10578465.00
      3740628.00     10578385.00      3740614.25     10578321.00
      3740786.00     10578119.00      3740801.08     10578004.68
      3740750.50     10577861.00      3740818.75     10577787.68
      3740840.25     10577571.79      3740898.00     10577480.00
      3740854.75     10577057.00      3740821.50     10577039.00

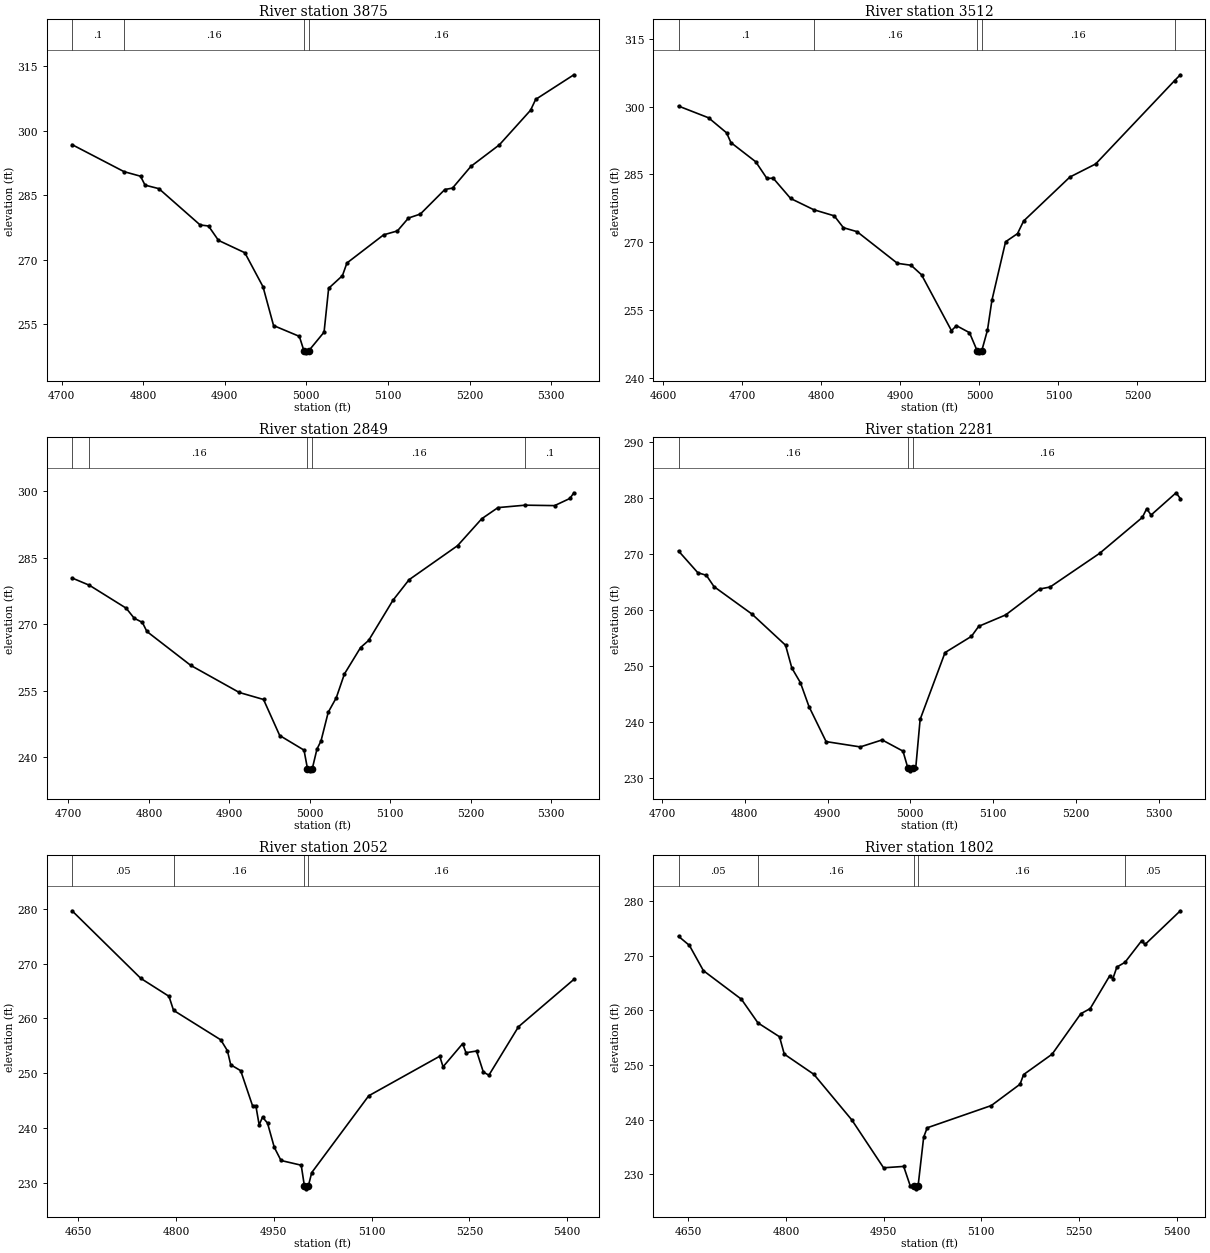
Type RM Length L Ch R = 1,3875,363,363,363
BEGIN DESCRIPTION:
UNT 053 IN BOCR 7.0
END DESCRIPTION:
XS GIS Cut Line= 2
      3740489.68     10580172.24      3739937.63     10579901.42
#Sta/Elev= 30
  4712.9  296.78  4776.6  290.50  4796.8  289.44  4802.3  287.37  4819.3  286.55
  4869.8  278.12  4880.1  277.87  4892.3  274.53  4924.6  271.66  4946.9  263.75
  4959.8  254.74  4991.4  252.23  4997.0  248.90  4999.8  248.40  5003.0  248.90
  5021.7  253.21  5027.3  263.39  5044.2  266.33  5049.7  269.27  5094.7  275.82
  5111.6  276.73  5125.1  279.72  5139.7  280.65  5169.7  286.35  5179.1  286.68
  5201.6  291.72  5236.5  296.73  5274.7  304.76  5281.0  307.29  5327.8  313.01
#Mann=4,-1,0
  4712.9     0.1       0  4776.6    0.16       0  4997.0    0.07       0
  5003.0    0.16       0
Bank Sta=4997,5003
Exp/Cntr=0.3,0.1

Type RM Length L Ch R = 1,3512,663,663,663
BEGIN DESCRIPTION:
UNT 053 IN BOCR 6.0
END DESCRIPTION:
XS GIS Cut Line= 2
      3740698.01     10579911.82      3740123.11     10579641.69
#Sta/Elev= 30
  4619.1  300.10  4657.1  297.51  4679.9  294.19  4685.4  292.03  4716.8  287.79
  4731.0  284.10  4738.9  284.16  4761.0  279.67  4790.2  277.19  4816.2  275.83
  4827.8  273.21  4845.1  272.33  4896.2  265.33  4913.5  264.90  4926.7  262.80
  4964.6  250.45  4970.9  251.55  4987.4  250.00  4997.0  246.04  4999.8  245.54
  5003.0  246.04  5010.2  250.58  5015.8  257.16  5033.1  270.10  5048.2  271.90
  5055.9  274.68  5114.5  284.41  5147.1  287.30  5247.1  305.74  5254.3  307.02
#Mann=5,-1,0
  4619.1     0.1       0  4790.2    0.16       0  4997.0    0.07       0
  5003.0    0.16       0  5247.1     0.1       0
Bank Sta=4997,5003
Exp/Cntr=0.3,0.1

Type RM Length L Ch R = 1,2849,568,568,568
BEGIN DESCRIPTION:
UNT 053 IN BOCR 5.0
END DESCRIPTION:
XS GIS Cut Line= 2
      3740826.48     10579384.06      3740205.77     10579325.11
#Sta/Elev= 30
  4704.5  280.45  4726.1  278.80  4771.7  273.63  4781.7  271.36  4791.8  270.42
  4797.5  268.36  4852.0  260.70  4912.3  254.58  4942.4  253.00  4962.5  244.86
  4992.7  241.56  4997.0  237.38  4999.8  236.88  5003.0  237.38  5008.8  241.80
  5013.8  243.62  5022.8  250.12  5032.8  253.39  5042.9  258.76  5063.0  264.74
  5073.0  266.34  5103.2  275.41  5123.2  280.05  5183.5  287.75  5213.6  293.84
  5233.7  296.35  5267.5  296.90  5304.1  296.80  5323.1  298.42  5328.0  299.70
#Mann=5,-1,0
  4704.5    0.05       0  4726.1    0.16       0  4997.0    0.07       0
  5003.0    0.16       0  5267.5     0.1       0
Bank Sta=4997,5003
Exp/Cntr=0.3,0.1

Type RM Length L Ch R = 1,2281,229,229,229
BEGIN DESCRIPTION:
UNT 053 IN BOCR 4.0
END DESCRIPTION:
XS GIS Cut Line= 2
      3740802.18     10578956.97      3740215.22     10578805.05
#Sta/Elev= 30
  4719.9  270.46  4743.2  266.58  4753.5  266.12  4762.8  264.09  4808.6  259.20
  4849.2  253.64  4856.8  249.57  4867.2  246.94  4877.5  242.69  4898.2  236.43
  4939.5  235.48  4965.9  236.73  4991.1  234.73  4997.0  231.71  4999.8  231.21
  5003.0  231.71  5006.5  231.71  5011.8  240.38  5041.9  252.32  5073.8  255.22
  5082.6  257.01  5115.1  259.04  5156.4  263.67  5168.9  264.03  5228.7  270.04
  5280.3  276.45  5285.6  278.02  5290.8  276.87  5321.1  280.85  5326.2  279.81
#Mann=3,-1,0
  4719.9    0.16       0  4997.0    0.07       0  5003.0    0.16       0
Bank Sta=4997,5003
Exp/Cntr=0.3,0.1

Type RM Length L Ch R = 1,2052,250,250,250
BEGIN DESCRIPTION:
Mapping XS ec877cb5
END DESCRIPTION:
XS GIS Cut Line= 3
      3740982.73     10578825.09      3740709.29     10578767.80
      3740235.38     10578642.81
#Sta/Elev= 30
  4640.7  279.62  4746.1  267.29  4789.3  264.02  4796.3  261.46  4868.7  256.08
  4878.9  254.10  4884.0  251.53  4899.3  250.45  4917.4  244.07  4922.5  244.07
  4927.6  240.57  4932.8  241.97  4940.4  240.90  4950.8  236.47  4961.1  234.07
  4992.1  233.21  4997.0  229.40  4999.8  228.90  5003.0  229.40  5008.2  231.86
  5095.6  245.87  5204.5  253.09  5209.6  251.16  5239.6  255.37  5244.8  253.73
  5261.0  254.04  5271.4  250.20  5279.9  249.63  5325.3  258.47  5410.2  267.10
#Mann=4,-1,0
  4640.7    0.05       0  4796.3    0.16       0  4997.0    0.07       0
  5003.0    0.16       0
Bank Sta=4997,5003
Exp/Cntr=0.3,0.1

Type RM Length L Ch R = 1,1802,317,317,317
BEGIN DESCRIPTION:
UNT 053 IN BOCR 3.0
END DESCRIPTION:
XS GIS Cut Line= 3
      3740979.32     10578703.52      3740698.05     10578536.84
      3740264.30     10578443.15
#Sta/Elev= 30
  4635.1  273.60  4651.8  271.93  4673.3  267.30  4731.7  262.06  4757.1  257.72
  4790.2  255.18  4797.5  252.00  4842.9  248.30  4901.4  239.91  4950.0  231.16
  4980.9  231.41  4991.1  227.80  4997.0  227.80  4999.8  227.30  5003.0  227.80
  5011.6  236.77  5017.0  238.49  5115.5  242.57  5159.6  246.48  5165.1  248.25
  5208.9  251.99  5253.0  259.41  5267.4  260.35  5297.2  266.33  5302.3  265.86
  5308.3  267.96  5320.8  268.83  5346.4  272.79  5351.6  272.10  5405.8  278.28
#Mann=5,-1,0
  4635.1    0.05       0  4757.1    0.16       0  4997.0    0.07       0
  5003.0    0.16       0  5320.8    0.05       0
Bank Sta=4997,5003
Exp/Cntr=0.3,0.1

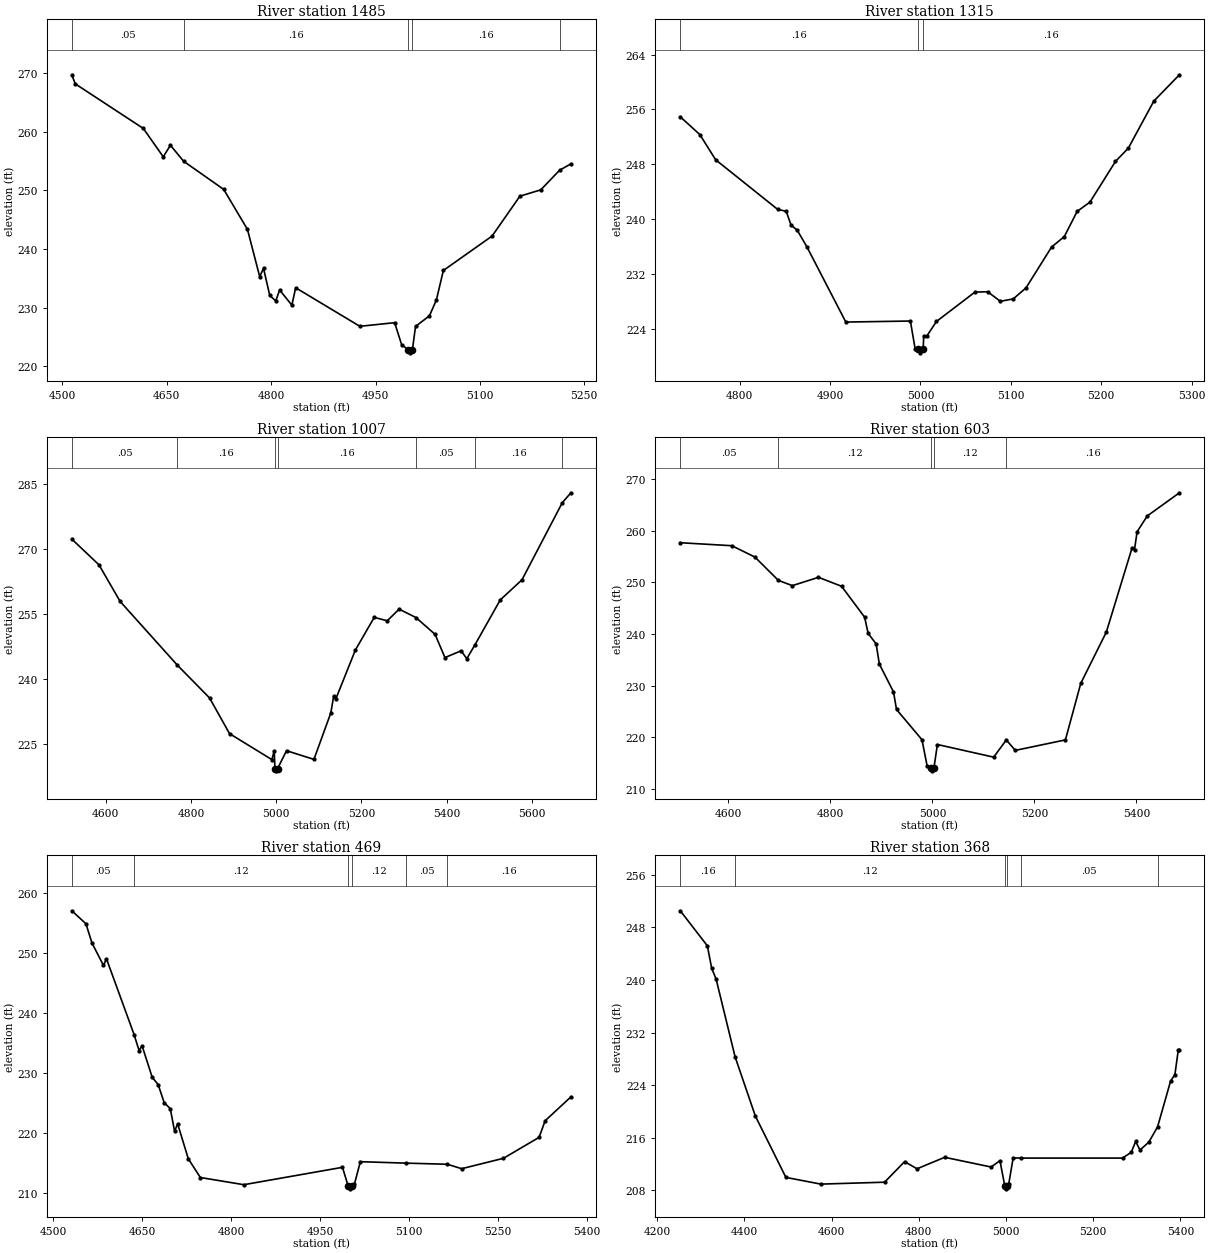
Type RM Length L Ch R = 1,1485,170,170,170
BEGIN DESCRIPTION:
Mapping XS 05621fc2
END DESCRIPTION:
XS GIS Cut Line= 3
      3741068.69     10578507.39      3740711.90     10578345.92
      3740386.34     10578343.32
#Sta/Elev= 30
  4513.6  269.67  4518.5  268.13  4616.4  260.52  4645.0  255.69  4655.3  257.66
  4674.3  254.93  4731.9  250.13  4766.0  243.32  4783.6  235.26  4789.1  236.69
  4798.0  232.07  4806.7  231.12  4812.2  232.99  4829.8  230.41  4835.3  233.37
  4927.5  226.80  4977.5  227.42  4987.5  223.69  4997.0  222.78  4999.8  222.28
  5003.0  222.78  5007.5  226.78  5027.5  228.59  5037.5  231.30  5047.5  236.32
  5117.5  242.18  5157.5  248.98  5187.5  250.06  5214.5  253.40  5230.8  254.49
#Mann=5,-1,0
  4513.6    0.05       0  4674.3    0.16       0  4997.0    0.07       0
  5003.0    0.16       0  5214.5    0.05       0
Bank Sta=4997,5003
Exp/Cntr=0.3,0.1

Type RM Length L Ch R = 1,1315,308,308,308
BEGIN DESCRIPTION:
UNT 053 IN BOCR 2.0
END DESCRIPTION:
XS GIS Cut Line= 3
      3740949.63     10578310.20      3740699.61     10578210.19
      3740499.63     10578010.21
#Sta/Elev= 30
  4734.4  254.93  4756.0  252.35  4773.5  248.68  4842.1  241.46  4851.6  241.18
  4856.9  239.17  4863.7  238.44  4874.4  236.02  4917.5  225.06  4988.9  225.21
  4994.3  221.08  4997.0  221.08  4999.8  220.58  5003.0  221.08  5003.7  223.05
  5007.2  223.05  5017.8  225.15  5060.3  229.42  5074.4  229.47  5088.5  228.08
  5102.7  228.43  5116.8  230.03  5145.1  235.98  5159.2  237.50  5173.4  241.17
  5187.5  242.51  5215.8  248.44  5230.0  250.37  5258.2  257.22  5286.5  261.05
#Mann=3,-1,0
  4734.4    0.16       0  4997.0    0.07       0  5003.0    0.16       0
Bank Sta=4997,5003
Exp/Cntr=0.3,0.1

Type RM Length L Ch R = 1,1007,404,404,404
BEGIN DESCRIPTION:
Mapping XS 3b8cf82f
END DESCRIPTION:
XS GIS Cut Line= 4
      3741172.47     10578217.50      3740992.37     10578043.91
      3740731.96     10577931.06      3740106.93     10577807.36
#Sta/Elev= 30
  4520.3  272.33  4584.0  266.38  4633.7  257.90  4768.2  243.13  4843.5  235.57
  4890.4  227.31  4989.8  221.29  4995.2  223.36  4997.0  219.20  4999.8  218.70
  5003.0  219.20  5024.1  223.36  5088.4  221.35  5128.0  232.10  5134.6  235.91
  5139.7  235.32  5185.8  246.69  5229.9  254.21  5260.5  253.43  5288.3  256.12
  5327.7  254.18  5372.7  250.28  5395.8  244.91  5433.8  246.48  5447.1  244.65
  5466.4  247.90  5525.6  258.26  5576.5  262.90  5671.3  280.78  5691.4  283.05
#Mann=7,-1,0
  4520.3    0.05       0  4768.2    0.16       0  4997.0    0.07       0
  5003.0    0.16       0  5327.7    0.05       0  5466.4    0.16       0
  5671.3    0.05       0
Bank Sta=4997,5003
Exp/Cntr=0.3,0.1

Type RM Length L Ch R = 1,603,134,134,134
BEGIN DESCRIPTION:
UNT 053 IN BOCR 1.0
END DESCRIPTION:
XS GIS Cut Line= 3
      3741106.96     10577969.64      3740909.03     10577594.62
      3740356.96     10577547.75
#Sta/Elev= 30
  4506.0  257.69  4607.1  257.11  4652.4  254.90  4698.3  250.39  4725.6  249.38
  4776.8  250.99  4822.0  249.26  4867.2  243.28  4874.1  240.14  4889.8  238.09
  4896.1  234.19  4923.8  228.81  4929.7  225.40  4979.6  219.55  4989.7  214.49
  4997.0  214.02  4999.8  213.52  5003.0  214.02  5009.8  218.62  5120.1  216.17
  5144.9  219.50  5162.5  217.48  5260.7  219.51  5290.8  230.46  5340.9  240.39
  5391.1  256.62  5396.1  256.35  5401.2  259.81  5421.2  262.88  5484.1  267.36
#Mann=5,-1,0
  4506.0    0.05       0  4698.3    0.12       0  4997.0    0.07       0
  5003.0    0.12       0  5144.9    0.16       0
Bank Sta=4997,5003
Exp/Cntr=0.3,0.1

Type RM Length L Ch R = 1,469,101,101,101
BEGIN DESCRIPTION:
Mapping XS 597d3061
END DESCRIPTION:
XS GIS Cut Line= 4
      3741114.34     10577823.67      3741066.59     10577545.86
      3740934.21     10577476.42      3740526.24     10577439.53
#Sta/Elev= 30
  4531.5  257.01  4555.3  254.85  4565.5  251.63  4584.8  247.90  4589.9  249.00
  4636.4  236.37  4644.8  233.70  4649.9  234.49  4666.9  229.25  4677.1  227.99
  4687.2  224.99  4697.4  224.02  4704.7  220.23  4709.8  221.48  4727.8  215.64
  4748.1  212.52  4821.3  211.32  4987.6  214.22  4997.0  211.13  4999.8  210.63
  5003.0  211.13  5007.7  211.42  5017.7  215.16  5093.8  214.92  5164.2  214.73
  5188.4  213.99  5258.7  215.72  5318.9  219.22  5329.0  221.98  5372.5  225.97
#Mann=6,-1,0
  4531.5    0.05       0  4636.4    0.12       0  4997.0    0.07       0
  5003.0    0.12       0  5093.8    0.05       0  5164.2    0.16       0
Bank Sta=4997,5003
Exp/Cntr=0.3,0.1

Type RM Length L Ch R = 1,368,202,202,202
BEGIN DESCRIPTION:
Mapping XS a7cbae06
END DESCRIPTION:
XS GIS Cut Line= 5
      3741233.69     10577882.22      3741225.01     10577500.29
      3740979.79     10577387.44      3740777.96     10577361.40
      3740489.36     10577370.08
#Sta/Elev= 30
  4253.3  250.54  4315.3  245.21  4325.3  241.78  4335.4  240.15  4378.9  228.32
  4425.4  219.30  4495.4  209.97  4575.4  208.95  4721.6  209.24  4767.5  212.37
  4796.0  211.28  4859.4  213.03  4965.9  211.55  4986.1  212.52  4997.0  208.73
  4999.8  208.23  5003.0  208.73  5006.3  208.99  5016.4  212.94  5034.4  212.91
  5267.2  212.91  5287.2  213.80  5297.2  215.44  5307.2  214.14  5327.2  215.32
  5347.5  217.67  5377.2  224.61  5387.2  225.62  5394.9  229.34  5397.5  229.34
#Mann=6,-1,0
  4253.3    0.16       0  4378.9    0.12       0  4997.0    0.07       0
  5003.0    0.12       0  5034.4    0.05       0  5347.5    0.12       0
Bank Sta=4997,5003
Exp/Cntr=0.3,0.1

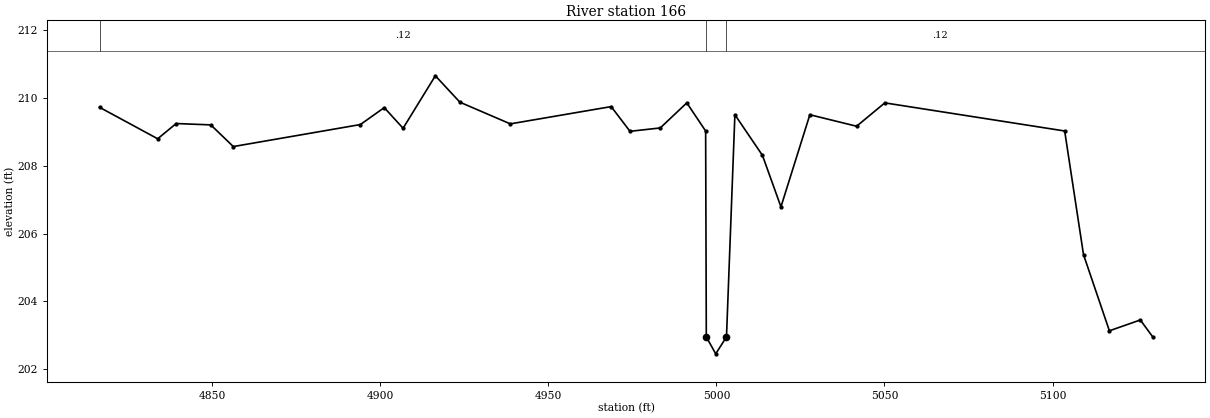
Type RM Length L Ch R = 1,166,0,0,0
BEGIN DESCRIPTION:
Mapping XS 34a7707f
END DESCRIPTION:
XS GIS Cut Line= 2
      3741029.31     10577263.19      3740748.05     10577125.16
#Sta/Elev= 30
  4816.5  209.73  4833.8  208.80  4839.3  209.25  4849.6  209.21  4856.3  208.57
  4894.1  209.22  4901.2  209.72  4906.8  209.11  4916.4  210.66  4923.7  209.88
  4938.7  209.24  4968.7  209.75  4974.3  209.02  4983.3  209.12  4991.2  209.86
  4996.8  209.03  4997.0  202.95  4999.8  202.45  5003.0  202.95  5005.5  209.51
  5013.7  208.31  5019.2  206.79  5027.8  209.51  5041.7  209.17  5050.1  209.86
  5103.6  209.03  5109.2  205.38  5116.9  203.13  5126.1  203.45  5129.8  202.95
#Mann=3,-1,0
  4816.5    0.12       0  4997.0    0.07       0  5003.0    0.12       0
Bank Sta=4997,5003
Exp/Cntr=0.3,0.1

Chan Stop Cuts=-1