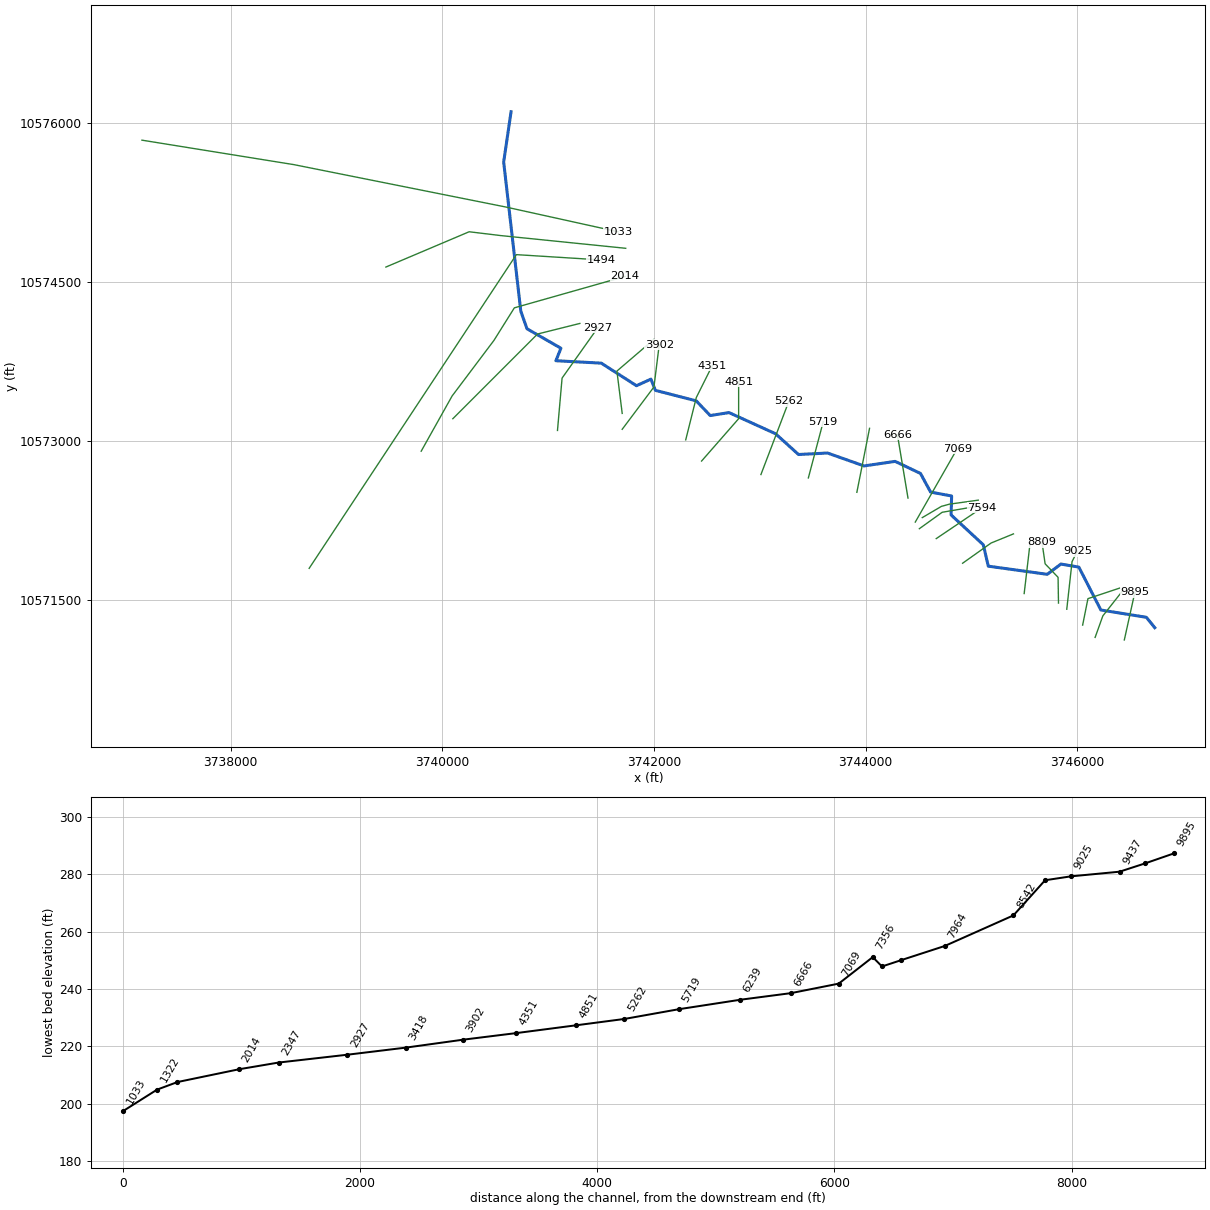
--- UNT 054 IN BOCR.prj (project) ---

Proj Title=UNT 054 IN BOCR Base Level Engineering
Current Plan=p01
Default Exp/Contr=0.3,0.1
English Units
Geom File=g01
Flow File=f01
Plan File=p01
Y Axis Title=Elevation
X Axis Title(PF)=Main Channel Distance
X Axis Title(XS)=Station
BEGIN DESCRIPTION:
UNT 054 IN BOCR
END DESCRIPTION:
DSS Export Rating Curves= 0
DSS Export Rating Curve Sorted= 0
DSS Export Volume Flow Curves= 0
DXF OffsetX= 0
DXF OffsetY= 0
DXF ScaleX= 1
DXF ScaleY= 10

--- UNT 054 IN BOCR.p01 (plan) ---

Plan Title=Multiple Run
Short Identifier=Multiple
Geom File=g01
Flow File=f01
Subcritical Flow
K Sum by GR= 0
Std Step Tol= 0.01
Critical Tol= 0.01
Num of Std Step Trials= 20
Max Error Tol= 0.3
Flow Tol Ratio= 0.001
Split Flow NTrial= 30
Split Flow Tol= 0.02
Split Flow Ratio= 0.02
Log Output Level= 0
Friction Slope Method= 1
Unsteady Friction Slope Method= 2
Unsteady Bridges Friction Slope Method= 1
Parabolic Critical Depth
Global Vel Dist=  1 , 1 , 1
Global Log Level= 0
CheckData=True
Encroach Param= -1, 0, 0, 0
BEGIN DESCRIPTION:
Multiple Run
END DESCRIPTION:

--- UNT 054 IN BOCR.f01 (steady flow) ---

Flow Title=Multiple
Number of Profiles=7
Profile Names=10-year,25-year,50-year,1pct_min,100-year,1pct_plu,500-year
River Rch & RM= UNT 054 IN BOCR,Reach-1,9895
     391     524     634     566     765    1035    1117
River Rch & RM= UNT 054 IN BOCR,Reach-1,7069
    1018    1435    1794    1647    2227    3012    3449
Boundary for River Rch & Prof#=UNT 054 IN BOCR,Reach-1,1
Up Type=0
Dn Type=3
Dn Slope=0.005
Boundary for River Rch & Prof#=UNT 054 IN BOCR,Reach-1,2
Up Type=0
Dn Type=3
Dn Slope=0.005
Boundary for River Rch & Prof#=UNT 054 IN BOCR,Reach-1,3
Up Type=0
Dn Type=3
Dn Slope=0.005
Boundary for River Rch & Prof#=UNT 054 IN BOCR,Reach-1,4
Up Type=0
Dn Type=3
Dn Slope=0.005
Boundary for River Rch & Prof#=UNT 054 IN BOCR,Reach-1,5
Up Type=0
Dn Type=3
Dn Slope=0.005
Boundary for River Rch & Prof#=UNT 054 IN BOCR,Reach-1,6
Up Type=0
Dn Type=3
Dn Slope=0.005
Boundary for River Rch & Prof#=UNT 054 IN BOCR,Reach-1,7
Up Type=0
Dn Type=3
Dn Slope=0.005

--- UNT 054 IN BOCR.g01 (geometry) ---

Geom Title=Existing Conditions
Program Version=4.10

River Reach=UNT 054 IN BOCR ,Reach-1
Reach XY= 30
        3746731.       10571236.       3746651.5       10571334.
      3746221.53     10571402.83      3746013.75       10571808.
       3745844.5       10571837.        3745715.       10571740.
        3745158.       10571817.      3745111.43     10572018.65
      3744806.75      10572301.1      3744811.75       10572480.
      3744613.25       10572517.       3744517.5       10572693.
        3744278.       10572807.       3743984.5       10572764.
        3743639.       10572886.      3743365.25       10572872.
       3743148.5       10573068.       3742708.5       10573268.
        3742531.       10573240.      3742398.75       10573379.
        3742013.       10573478.        3741971.       10573584.
      3741834.25       10573522.        3741502.       10573735.
      3741073.25       10573758.       3741120.5       10573876.
        3740800.       10574060.       3740741.5       10574226.
      3740579.75       10575635.       3740649.5       10576110.

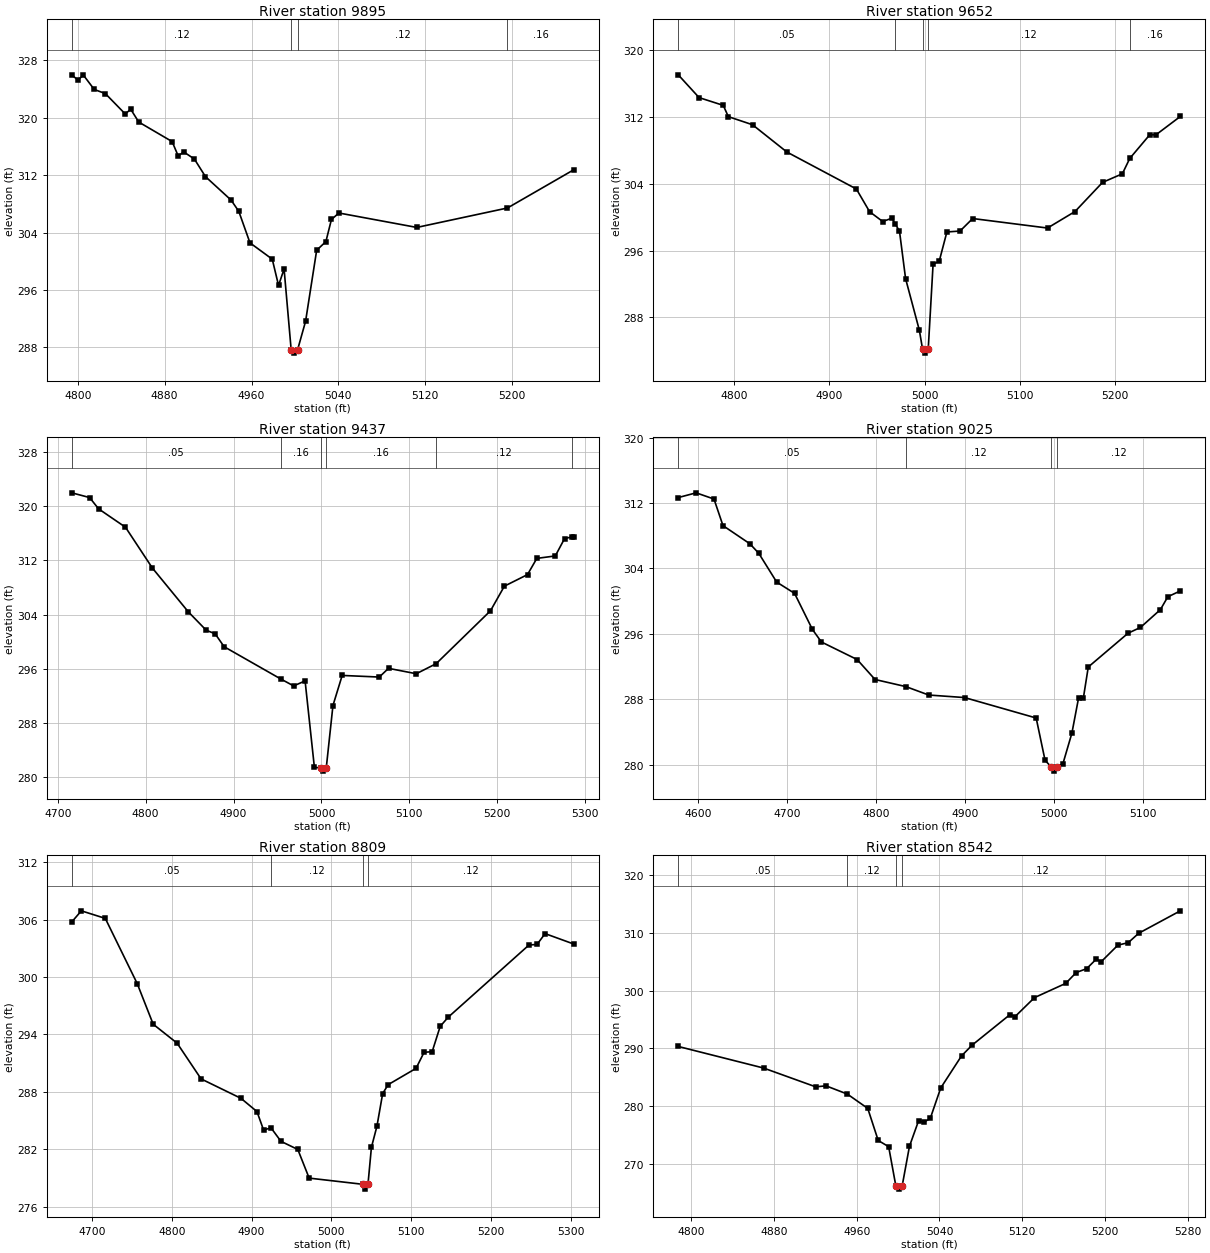
Type RM Length L Ch R = 1 ,9895    ,243,243,243
BEGIN DESCRIPTION:
UNT 054 IN BOCR 19.0
END DESCRIPTION:
XS GIS Cut Line= 2
      3746443.35     10571119.98      3746543.18     10571571.37
#Sta/Elev= 30
  4794.5  325.97  4800.1  325.24  4805.2  325.93  4815.2  323.93  4825.4  323.36
  4843.7  320.52  4848.8  321.17  4856.2  319.39  4886.9  316.67  4892.5  314.67
  4897.6  315.23  4907.4  314.24  4917.6  311.79  4941.2  308.52  4948.3  306.95
  4958.6  302.56  4979.1  300.29  4984.9  296.63    4990  298.92  4996.5   287.7
  4999.3   287.2  5002.5   287.7  5009.8  291.64    5020  301.53  5028.5  302.74
  5033.6  305.82  5040.5  306.72  5112.2  304.71  5195.7  307.42  5256.8  312.75
#Mann= 4 ,-1 , 0
  4794.5     .12       0  4996.5     .07       0  5002.5     .12       0
  5195.7     .16       0
Bank Sta=4996.5,5002.5
XS Rating Curve= 0 ,0
Exp/Cntr=0.3,0.1

Type RM Length L Ch R = 1 ,9652    ,215,215,215
BEGIN DESCRIPTION:
Mapping XS 0736e470
END DESCRIPTION:
XS GIS Cut Line= 3
      3746167.41     10571144.06      3746240.34     10571347.21
      3746433.05     10571592.01
#Sta/Elev= 30
  4741.3  317.07  4763.2  314.34  4788.6  313.41  4793.9  312.06  4819.3  311.09
  4855.4  307.82  4928.4  303.39  4942.3  300.67  4956.1  299.49  4965.7  299.89
  4969.5  299.15  4973.7  298.34  4980.1  292.65  4994.6  286.45  4997.9  284.22
  5000.7  283.72  5003.9  284.22    5009  294.38  5015.4  294.72  5023.5  298.24
  5037.3  298.35  5050.6  299.85  5129.2  298.71  5158.1  300.69    5187  304.18
  5207.8  305.21  5215.6  307.05  5236.7   309.9  5243.1  309.88  5268.7  312.08
#Mann= 5 ,-1 , 0
  4741.3     .05       0  4969.5     .12       0  4997.9     .07       0
  5003.9     .12       0  5215.6     .16       0
Bank Sta=4997.9,5003.9
XS Rating Curve= 0 ,0
Exp/Cntr=0.3,0.1

Type RM Length L Ch R = 1 ,9437    ,412,412,412
BEGIN DESCRIPTION:
UNT 054 IN BOCR 18.0
END DESCRIPTION:
XS GIS Cut Line= 3
      3746049.62     10571260.23      3746099.61     10571510.19
      3746399.58     10571610.18
#Sta/Elev= 30
    4716  322.01  4736.3  321.31  4746.5  319.64  4777.1  316.92  4807.7  310.88
  4848.5  304.41  4868.9  301.68  4879.1  301.15  4889.3  299.24  4953.8  294.46
  4968.4  293.44  4981.4  294.18    4992  281.37  4999.5  281.33  5002.3  280.83
  5005.5  281.33  5013.1  290.54  5023.6  294.99  5065.8  294.75  5076.3  296.04
  5107.9  295.24  5130.5  296.73  5192.3  304.56  5208.1   308.2  5234.4  309.91
    5245  312.31    5266  312.67  5276.6  315.25  5285.4  315.49  5287.1  315.49
#Mann= 6 ,-1 , 0
    4716     .05       0  4953.8     .16       0  4999.5     .07       0
  5005.5     .16       0  5130.5     .12       0  5285.4     .16       0
Bank Sta=4999.5,5005.5
XS Rating Curve= 0 ,0
Exp/Cntr=0.3,0.1

Type RM Length L Ch R = 1 ,9025    ,216,216,216
BEGIN DESCRIPTION:
UNT 054 IN BOCR 17.0
END DESCRIPTION:
XS GIS Cut Line= 3
      3745899.61     10571410.19      3745949.61     10571860.19
      3745999.62     10571960.22
#Sta/Elev= 30
  4577.8  312.67  4597.9  313.25    4618  312.49  4628.1  309.24  4658.3  307.02
  4668.3  305.86  4688.5  302.33  4708.6  300.95  4728.7  296.53  4738.8     295
    4779  292.85  4799.1  290.41  4833.8  289.54  4859.5  288.51  4899.8   288.2
  4980.3   285.7  4990.3  280.52  4997.4   279.7  5000.1   279.2  5003.4   279.7
  5010.4  280.11  5020.5  283.86    5028  288.16  5033.4  288.16  5038.9  291.94
  5083.7  296.08  5097.6  296.78    5120  298.96  5128.4  300.54  5142.4  301.25
#Mann= 4 ,-1 , 0
  4577.8     .05       0  4833.8     .12       0  4997.4     .07       0
  5003.4     .12       0
Bank Sta=4997.4,5003.4
XS Rating Curve= 0 ,0
Exp/Cntr=0.3,0.1

Type RM Length L Ch R = 1 ,8809    ,267,267,267
BEGIN DESCRIPTION:
Mapping XS 9e39a019
END DESCRIPTION:
XS GIS Cut Line= 4
      3745821.36     10571468.22      3745817.45     10571711.75
      3745695.05     10571839.36      3745665.19     10572045.83
#Sta/Elev= 30
  4674.7  305.75  4686.7  306.91  4716.7  306.12  4756.7  299.31  4776.7  295.07
  4806.7  293.09  4836.7  289.36  4886.7  287.33  4906.7  285.95    4915  284.02
  4924.3  284.25  4936.8  282.84  4957.9  281.99  4972.1     279  5039.8  278.35
  5042.6  277.85  5045.8  278.35  5050.1  282.21    5057  284.41  5064.2  287.83
  5071.1  288.76    5106  290.46  5116.1  292.14  5126.2   292.2  5136.3  294.85
  5146.4  295.81  5247.5  303.34  5257.6   303.4  5267.7  304.53  5303.7  303.44
#Mann= 4 ,-1 , 0
  4674.7     .05       0  4924.3     .12       0  5039.8     .07       0
  5045.8     .12       0
Bank Sta=5039.8,5045.8
XS Rating Curve= 0 ,0
Exp/Cntr=0.3,0.1

Type RM Length L Ch R = 1 ,8542    ,578,578,578
BEGIN DESCRIPTION:
UNT 054 IN BOCR 16.0
END DESCRIPTION:
XS GIS Cut Line= 2
      3745497.16     10571558.31      3745553.59     10572040.12
#Sta/Elev= 30
  4787.6  290.35    4870  286.61  4920.4  283.35  4930.4  283.52    4951  282.09
  4970.7  279.61  4980.8  274.05  4990.9  272.97  4997.9  266.11  5000.7  265.61
  5003.9  266.11    5011  273.04  5019.8  277.46  5024.8  277.21  5031.1  277.87
  5041.2  283.15  5061.3  288.71  5071.4  290.56  5108.1  295.87  5113.1  295.54
  5131.8  298.82    5162  301.29  5172.1  303.17  5182.2  303.84  5191.3  305.46
  5196.4  305.07  5212.4  307.92  5222.4  308.35  5232.5  309.98  5272.7  313.87
#Mann= 4 ,-1 , 0
  4787.6     .05       0    4951     .12       0  4997.9     .07       0
  5003.9     .12       0
Bank Sta=4997.9,5003.9
XS Rating Curve= 0 ,0
Exp/Cntr=0.3,0.1

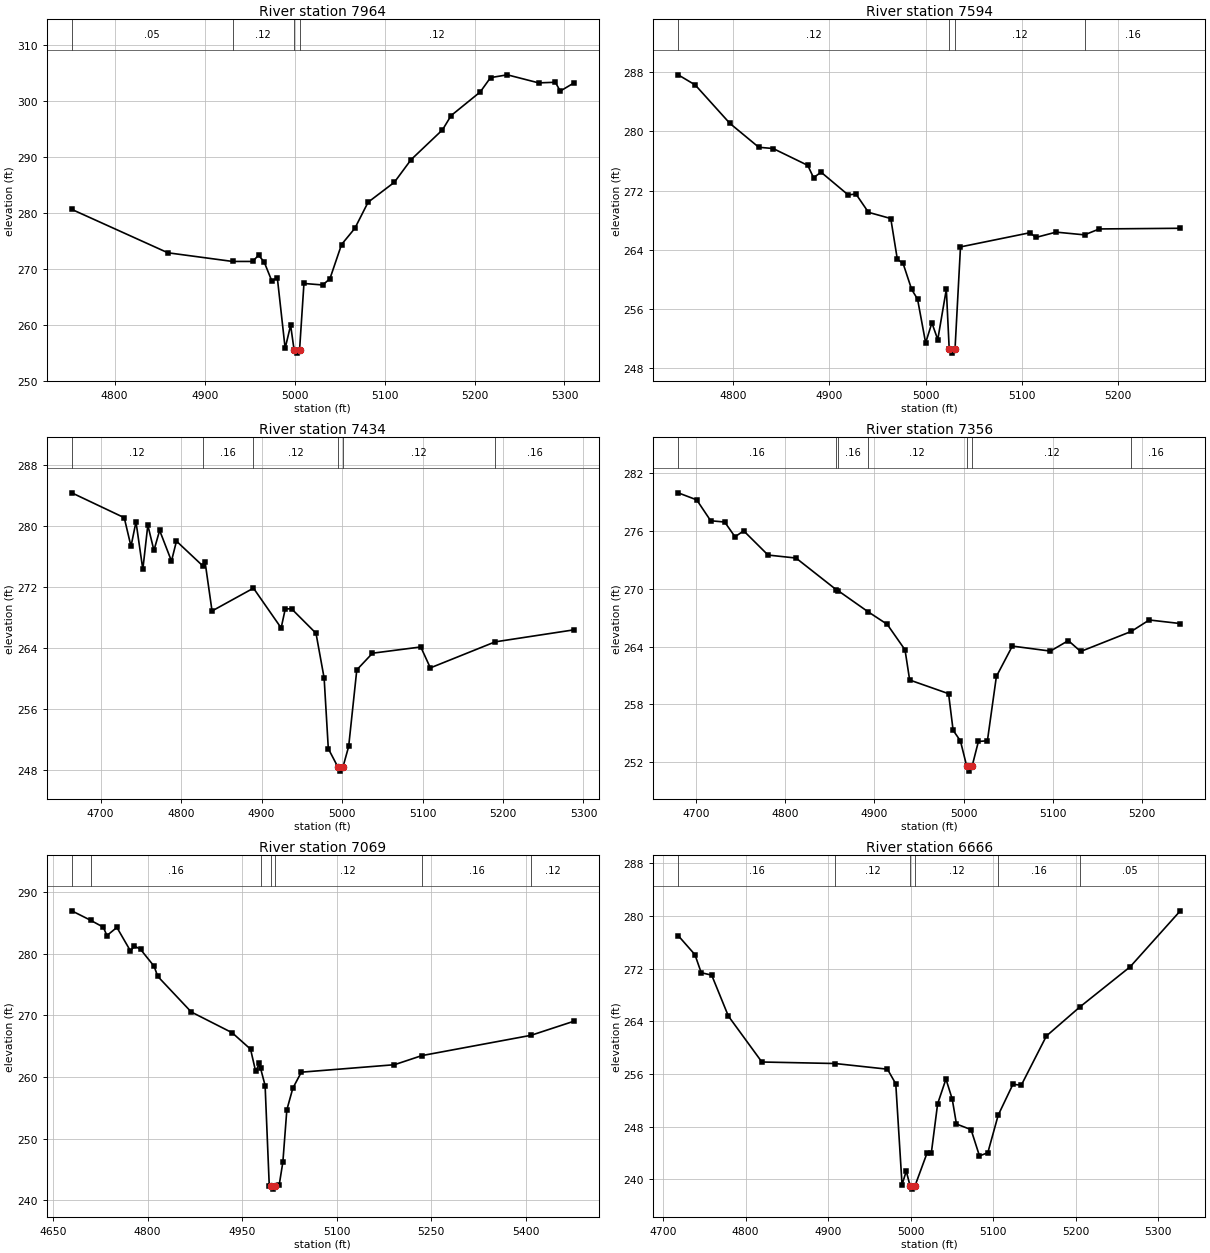
Type RM Length L Ch R = 1 ,7964    ,370,370,370
BEGIN DESCRIPTION:
UNT 054 IN BOCR 15.0
END DESCRIPTION:
XS GIS Cut Line= 3
      3744915.59      10571844.8      3745184.66     10572035.75
      3745395.99     10572122.01
#Sta/Elev= 30
  4752.3  280.68  4859.1  272.92    4931  271.37  4953.4  271.37  4959.9  272.48
  4966.1   271.3  4974.7  267.87  4980.8  268.46  4989.5  255.83  4995.6  259.95
  4999.5  255.47  5002.2  254.97  5005.5  255.47  5010.4  267.43  5031.3  267.16
  5039.3  268.29  5052.2   274.4    5067   277.3  5081.7  281.96  5110.9  285.53
  5129.5  289.58  5164.4  294.91    5174  297.46  5206.4  301.69  5217.8  304.25
  5236.5  304.75  5271.3  303.31  5289.9  303.42  5295.3  301.84  5310.5   303.3
#Mann= 4 ,-1 , 0
  4752.3     .05       0    4931     .12       0  4999.5     .07       0
  5005.5     .12       0
Bank Sta=4999.5,5005.5
XS Rating Curve= 0 ,0
Exp/Cntr=0.3,0.1

Type RM Length L Ch R = 1 ,7594    ,160,160,160
BEGIN DESCRIPTION:
UNT 054 IN BOCR 14.0
END DESCRIPTION:
XS GIS Cut Line= 2
      3744666.56     10572077.51      3745098.86     10572369.19
#Sta/Elev= 30
    4743  287.65  4760.7  286.28  4796.7  281.08  4826.7  277.85  4841.6  277.68
  4877.6   275.4  4883.6  273.73  4891.4  274.48  4919.6   271.4  4927.6  271.53
  4940.6  269.05  4963.8  268.21  4970.6   262.7  4976.6  262.13  4985.5  258.61
  4991.6  257.31    5000  251.39  5006.5  254.09  5012.6  251.83  5021.5  258.64
  5024.5   250.5  5027.3     250  5030.5   250.5  5036.2  264.37  5108.4  266.29
  5114.5  265.65  5135.5  266.37    5165     266  5180.4   266.8  5264.5  266.89
#Mann= 4 ,-1 , 0
    4743     .12       0  5024.5     .07       0  5030.5     .12       0
    5165     .16       0
Bank Sta=5024.5,5030.5
XS Rating Curve= 0 ,0
Exp/Cntr=0.3,0.1

Type RM Length L Ch R = 1 ,7434    ,78,78,78
BEGIN DESCRIPTION:
Mapping XS b2983bb4
END DESCRIPTION:
XS GIS Cut Line= 3
       3744506.7     10572170.88      3744722.83     10572326.25
      3745075.48     10572386.86
#Sta/Elev= 30
  4664.1   284.4  4729.3  281.13  4737.7  277.37  4743.9  280.59  4752.4  274.33
  4758.6  280.15  4766.2  276.83  4773.3  279.46    4788  275.43  4794.2  278.05
  4826.6  274.83  4829.8  275.28  4838.4  268.87  4889.9  271.87  4924.3  266.64
  4929.4  269.14  4937.2  269.16  4967.6  265.94  4977.7  260.06  4982.9  250.77
    4995  248.32  4997.8  247.82    5001  248.32  5008.2  251.07  5018.3  261.13
  5037.8  263.32  5097.8  264.14  5109.7  261.39  5190.2  264.81  5288.1  266.39
#Mann= 6 ,-1 , 0
  4664.1     .12       0  4826.6     .16       0  4889.9     .12       0
    4995     .07       0    5001     .12       0  5190.2     .16       0
Bank Sta=4995,5001
XS Rating Curve= 0 ,0
Exp/Cntr=0.3,0.1

Type RM Length L Ch R = 1 ,7356    ,287,287,287
BEGIN DESCRIPTION:
Mapping XS fcd2a925
END DESCRIPTION:
XS GIS Cut Line= 4
       3744534.6     10572275.87      3744715.18     10572381.79
      3744789.84     10572402.62      3745064.13     10572440.82
#Sta/Elev= 30
  4679.6  279.97  4700.4  279.24  4716.1  277.07  4731.8  276.94  4743.4  275.41
  4753.2  276.02  4780.5  273.51  4811.9   273.2    4857  269.92  4859.2  269.81
  4892.4  267.65  4914.3  266.32  4934.3  263.67  4939.5  260.54  4983.2  259.12
  4988.3  255.32  4996.5  254.22  5003.6  251.58  5006.4  251.08  5009.6  251.58
  5016.7  254.16  5026.8  254.23  5036.9  260.91  5054.8  264.06  5097.5  263.54
  5117.7  264.63  5131.5   263.5  5188.3  265.58  5208.5  266.77  5243.4   266.4
#Mann= 7 ,-1 , 0
  4679.6     .16       0    4857     .12       0  4859.2     .16       0
  4892.4     .12       0  5003.6     .07       0  5009.6     .12       0
  5188.3     .16       0
Bank Sta=5003.6,5009.6
XS Rating Curve= 0 ,0
Exp/Cntr=0.3,0.1

Type RM Length L Ch R = 1 ,7069    ,403,403,403
BEGIN DESCRIPTION:
UNT 054 IN BOCR 13.0
END DESCRIPTION:
XS GIS Cut Line= 2
      3744468.64     10572233.76      3744864.11     10572925.84
#Sta/Elev= 30
  4679.5  286.96  4709.4  285.43  4729.5  284.31  4735.3  282.95  4751.1  284.27
  4772.7  280.45    4779  281.25  4788.6  280.72  4810.2  277.97  4815.9  276.34
  4869.2  270.56    4934   267.2  4963.3  264.53  4971.4  260.93  4977.2  262.21
  4979.1  261.47  4986.4  258.64    4993  242.39  4995.8  242.34  4998.5  241.84
  5001.8  242.34  5008.8  242.53  5014.6  246.23  5020.9  254.69  5030.4   258.2
  5043.9   260.8  5191.7  262.01  5235.3  263.49  5408.6  266.78  5476.6  269.06
#Mann= 7 ,-1 , 0
  4679.5     .12       0  4709.4     .16       0  4979.1     .12       0
  4995.8     .07       0  5001.8     .12       0  5235.3     .16       0
  5408.6     .12       0
Bank Sta=4995.8,5001.8
XS Rating Curve= 0 ,0
Exp/Cntr=0.3,0.1

Type RM Length L Ch R = 1 ,6666    ,427,427,427
BEGIN DESCRIPTION:
UNT 054 IN BOCR 12.0
END DESCRIPTION:
XS GIS Cut Line= 3
      3744399.61     10572460.18      3744349.61     10572760.19
      3744299.61     10573060.21
#Sta/Elev= 30
  4718.3     277  4738.6  274.11  4746.2  271.37  4758.9     271  4779.1  264.79
  4819.7  257.82  4908.4  257.59  4971.8  256.73  4981.9  254.51  4989.5  239.19
  4994.6  241.27  4999.2  239.03  5001.9  238.53  5005.2  239.03  5019.9  244.04
    5025  244.04  5032.6  251.47  5042.7  255.23  5050.3  252.19  5055.4  248.41
  5073.1  247.56  5083.3  243.57  5093.4  244.05    5106  249.76  5123.8  254.43
    5134  254.31  5164.4  261.77  5204.8  266.16  5265.8  272.26  5326.6  280.76
#Mann= 6 ,-1 , 0
  4718.3     .16       0  4908.4     .12       0  4999.2     .07       0
  5005.2     .12       0    5106     .16       0  5204.8     .05       0
Bank Sta=4999.2,5005.2
XS Rating Curve= 0 ,0
Exp/Cntr=0.3,0.1

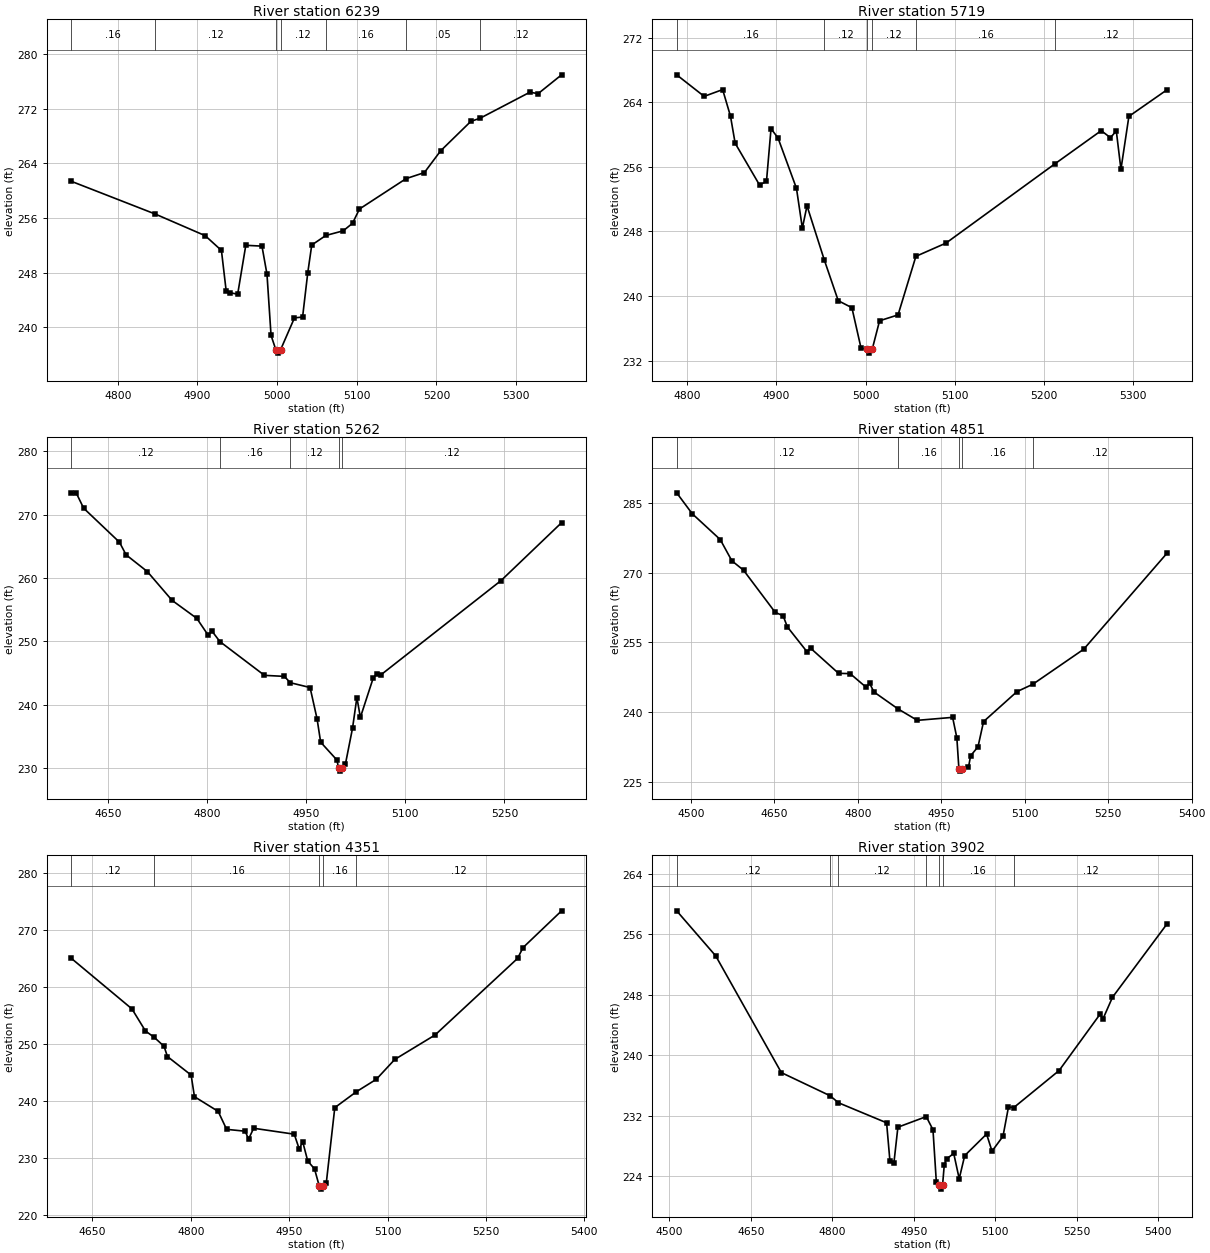
Type RM Length L Ch R = 1 ,6239    ,520,520,520
BEGIN DESCRIPTION:
Mapping XS 2b129373
END DESCRIPTION:
XS GIS Cut Line= 2
      3743916.56     10572515.03      3744036.34     10573119.17
#Sta/Elev= 30
  4741.3  261.39  4847.1  256.58  4909.7  253.42  4930.1  251.26  4936.1  245.29
  4941.2  245.06  4950.5  244.86  4960.7  252.01    4981  251.89  4987.3  247.78
  4992.4  238.83  4998.4  236.73  5001.2  236.23  5004.4  236.73  5021.8  241.39
    5032  241.51  5038.5  247.99  5043.5  252.05  5061.2  253.45    5083  254.13
  5094.7  255.23  5103.4  257.32    5162  261.77  5184.9  262.65  5205.3  265.83
  5243.2  270.14  5255.1  270.62  5317.5  274.42  5327.7   274.2  5357.2  276.96
#Mann= 7 ,-1 , 0
  4741.3     .16       0  4847.1     .12       0  4998.4     .07       0
  5004.4     .12       0  5061.2     .16       0    5162     .05       0
  5255.1     .12       0
Bank Sta=4998.4,5004.4
XS Rating Curve= 0 ,0
Exp/Cntr=0.3,0.1

Type RM Length L Ch R = 1 ,5719    ,457,457,457
BEGIN DESCRIPTION:
Mapping XS 3cdc0f95
END DESCRIPTION:
XS GIS Cut Line= 2
      3743458.22     10572650.45      3743598.84     10573181.65
#Sta/Elev= 30
  4788.4  267.42  4819.2  264.75  4839.9  265.59  4848.7  262.29  4853.9  258.94
  4881.2  253.77    4889  254.21  4894.1  260.74  4901.9   259.6  4922.6  253.35
  4929.2  248.42  4934.4  251.18  4953.9  244.43  4969.4  239.42  4984.7  238.55
    4995  233.51  5001.5  233.42  5004.2  232.92  5007.5  233.42  5015.7  236.93
  5036.4  237.66  5056.4  244.92  5090.1  246.56  5212.3   256.4    5264   260.5
  5274.3  259.63  5280.9  260.46  5286.1  255.71    5295  262.27  5337.9  265.58
#Mann= 6 ,-1 , 0
  4788.4     .16       0  4953.9     .12       0  5001.5     .07       0
  5007.5     .12       0  5056.4     .16       0  5212.3     .12       0
Bank Sta=5001.5,5007.5
XS Rating Curve= 0 ,0
Exp/Cntr=0.3,0.1

Type RM Length L Ch R = 1 ,5262    ,411,411,411
BEGIN DESCRIPTION:
UNT 054 IN BOCR 9.0
END DESCRIPTION:
XS GIS Cut Line= 2
      3743010.17     10572682.43      3743274.47     10573375.65
#Sta/Elev= 30
  4594.6  273.39  4602.3  273.45  4613.6  271.03  4667.8  265.66  4677.8  263.67
  4709.9  261.03  4747.4  256.48  4784.8  253.64  4802.2  250.95  4807.6  251.65
  4819.7  249.98  4887.1  244.65  4917.2  244.49  4926.2  243.49  4956.1  242.73
  4966.7  237.78  4972.1  234.11  4996.8  231.28  4999.1  230.04  5001.9  229.54
  5005.1  230.04  5009.6  230.67  5020.3  236.31  5026.9  241.15  5032.2  238.02
  5051.6  244.23    5057   244.9  5063.1  244.72    5245  259.61  5336.5  268.74
#Mann= 5 ,-1 , 0
  4594.6     .12       0  4819.7     .16       0  4926.2     .12       0
  4999.1     .07       0  5005.1     .12       0
Bank Sta=4999.1,5005.1
XS Rating Curve= 0 ,0
Exp/Cntr=0.3,0.1

Type RM Length L Ch R = 1 ,4851    ,500,500,500
BEGIN DESCRIPTION:
UNT 054 IN BOCR 8.0
END DESCRIPTION:
XS GIS Cut Line= 3
      3742449.59     10572810.17      3742799.61     10573210.19
      3742799.61     10573560.15
#Sta/Elev= 30
  4474.5  287.15  4502.5  282.65  4552.8   277.1  4573.7  272.53  4594.6  270.52
  4651.5  261.46  4665.8  260.71  4673.4  258.33  4708.5  253.01  4715.1  253.75
  4765.4  248.34  4786.3  248.27  4814.8  245.36  4821.4  246.16    4829  244.33
    4872  240.71  4906.9  238.23  4970.4  238.87    4978  234.48  4981.7  227.81
  4984.4  227.31  4987.7  227.81  4998.9  228.12  5002.7   230.6    5016  232.54
    5026  237.96    5086   244.4  5114.5  245.99    5206  253.52    5356  274.21
#Mann= 5 ,-1 , 0
  4474.5     .12       0    4872     .16       0  4981.7     .07       0
  4987.7     .16       0  5114.5     .12       0
Bank Sta=4981.7,4987.7
XS Rating Curve= 0 ,0
Exp/Cntr=0.3,0.1

Type RM Length L Ch R = 1 ,4351    ,449,449,449
BEGIN DESCRIPTION:
UNT 054 IN BOCR 7.0
END DESCRIPTION:
XS GIS Cut Line= 3
      3742299.61     10573010.19      3742399.61     10573410.19
       3742549.6     10573710.17
#Sta/Elev= 30
  4617.6  265.11  4710.4  256.21    4731  252.34  4744.3  251.23  4759.3  249.66
  4764.5  247.86  4800.6  244.61  4805.7  240.82  4841.8  238.25  4854.7   235.1
    4883  234.77  4888.2  233.39  4895.9  235.29  4957.8  234.25  4965.5  231.62
  4970.6  232.96  4978.4  229.54  4988.7  228.17    4996  225.12  4998.7  224.62
    5002  225.12  5006.7  225.76  5019.6   238.9  5052.5  241.69    5083  243.88
    5111  247.35  5172.5  251.64  5298.2  265.06  5306.6  266.96  5365.3   273.4
#Mann= 5 ,-1 , 0
  4617.6     .12       0  4744.3     .16       0    4996     .07       0
    5002     .16       0  5052.5     .12       0
Bank Sta=4996,5002
XS Rating Curve= 0 ,0
Exp/Cntr=0.3,0.1

Type RM Length L Ch R = 1 ,3902    ,484,484,484
BEGIN DESCRIPTION:
UNT 054 IN BOCR 6.0
END DESCRIPTION:
XS GIS Cut Line= 3
       3741699.6     10573110.17      3741999.61     10573510.19
       3742049.6     10573910.16
#Sta/Elev= 30
  4513.3  259.12  4585.2  253.16    4706  237.73  4795.7  234.67  4811.2  233.74
  4899.8  231.09    4906  225.98  4913.3  225.81  4920.6  230.51  4972.8  231.91
  4985.2  230.17  4991.4  223.23  4996.8  222.82  4999.5  222.32  5002.8  222.82
    5006  225.53  5010.2  226.31  5023.4  227.04  5033.5  223.69  5043.6  226.75
  5083.9   229.6  5093.9  227.34  5114.1  229.31  5124.2  233.18  5133.9   233.1
  5217.4     238    5293  245.47    5298   244.8  5315.7  247.69  5416.4  257.42
#Mann= 7 ,-1 , 0
  4513.3     .12       0  4795.7     .16       0  4811.2     .12       0
  4972.8     .16       0  4996.8     .07       0  5002.8     .16       0
  5133.9     .12       0
Bank Sta=4996.8,5002.8
XS Rating Curve= 0 ,0
Exp/Cntr=0.3,0.1

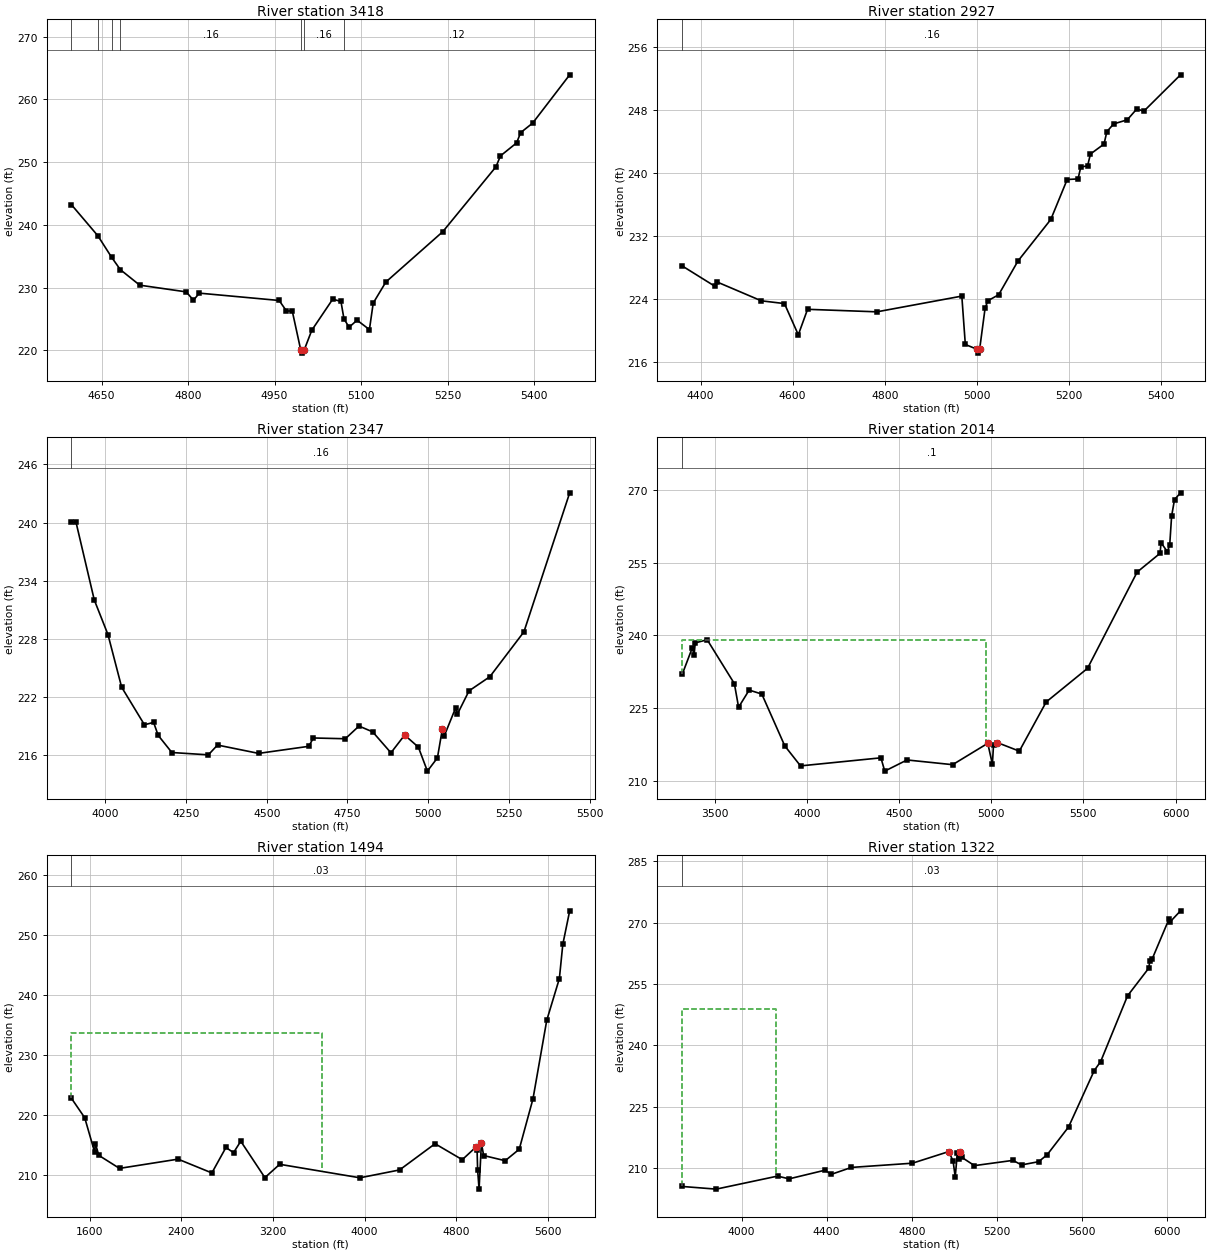
Type RM Length L Ch R = 1 ,3418    ,491,491,491
BEGIN DESCRIPTION:
UNT 054 IN BOCR 5.0
END DESCRIPTION:
XS GIS Cut Line= 3
       3741699.6     10573260.23      3741649.61     10573660.19
      3741999.57     10573960.16
#Sta/Elev= 30
  4597.7   243.2  4643.5  238.25  4667.3  234.83  4682.5  232.85  4716.1  230.38
  4796.7  229.31  4809.3  227.98  4819.4  229.11  4957.9  227.94  4970.5  226.27
  4980.6  226.26  4995.3  220.05    4998  219.55  5001.3  220.05  5014.5   223.2
  5050.7  228.14    5065   227.8  5070.3     225  5079.2  223.68    5093   224.8
  5114.4   223.3    5121  227.53  5142.9  230.88  5241.7  238.91  5333.9  249.25
  5341.6  250.98  5369.6  253.05  5376.7  254.69  5397.5  256.21  5461.7   263.9
#Mann= 7 ,-1 , 0
  4597.7     .12       0  4643.5     .16       0  4667.3     .12       0
  4682.5     .16       0  4995.3     .07       0  5001.3     .16       0
  5070.3     .12       0
Bank Sta=4995.3,5001.3
XS Rating Curve= 0 ,0
Exp/Cntr=0.3,0.1

Type RM Length L Ch R = 1 ,2927    ,580,580,580
BEGIN DESCRIPTION:
UNT 054 IN BOCR 4.0
END DESCRIPTION:
XS GIS Cut Line= 3
      3741088.17     10573099.14      3741131.57     10573593.91
      3741470.14     10574071.38
#Sta/Elev= 30
  4360.4  228.17  4430.4  225.62  4435.4  226.15  4532.1  223.74  4582.3  223.39
  4612.4  219.42  4632.5  222.66  4783.1  222.34  4967.5  224.34  4975.1  218.19
  5000.2  217.59  5002.9  217.09  5006.2  217.59    5018  222.79  5024.1  223.75
  5047.5  224.51  5089.3  228.79  5160.7  234.08  5196.3  239.16  5219.8  239.24
  5225.9  240.74  5240.7  240.91  5246.8   242.4  5276.3  243.67  5282.5  245.25
  5297.2  246.23  5326.8  246.75  5347.7  248.15  5362.5  247.83  5442.4  252.47
#Mann= 1 ,-1 , 0
  4360.4     .16       0
Bank Sta=5000.2,5006.2
XS Rating Curve= 0 ,0
Exp/Cntr=0.3,0.1

Type RM Length L Ch R = 1 ,2347    ,333,333,333
BEGIN DESCRIPTION:
UNT 054 IN BOCR 3.0
END DESCRIPTION:
XS GIS Cut Line= 3
      3740099.63     10573210.21      3740899.61     10574010.19
      3741299.66      10574110.2
#Sta/Elev= 30
  3894.8  240.01  3908.9  240.04  3965.5  232.02  4007.9  228.45  4050.3  223.02
    4121  219.14  4149.3  219.39  4163.5  218.05  4205.9  216.28    4319  216.04
  4347.3  217.05  4474.6  216.19  4630.2  216.92  4644.3  217.78  4743.3   217.7
  4785.7  219.01  4828.1  218.41  4884.7  216.25  4927.1  218.08  4969.6  216.84
  4997.6  214.36  5028.7  215.73  5044.2  218.75  5049.3  217.95  5085.4  220.91
  5090.6  220.24  5126.6  222.64  5191.1   224.1  5296.7  228.73  5438.5  243.07
#Mann= 1 ,-1 , 0
  3894.8     .16       0
Bank Sta=4927.1,5044.2
XS Rating Curve= 0 ,0
Exp/Cntr=0.3,0.1

Type RM Length L Ch R = 1 ,2014    ,520,520,520
BEGIN DESCRIPTION:
Mapping XS 8e6087f3
END DESCRIPTION:
XS GIS Cut Line= 5
      3739800.61     10572903.42      3740092.27     10573424.24
       3740488.1     10573950.28      3740680.81     10574257.57
      3741726.12       10574554.
#Sta/Elev= 30
  3322.4  231.99  3376.6  237.41  3386.9  236.01  3392.6  238.45  3457.7   239.1
  3605.2  230.06  3628.1  225.19  3685.5  228.73  3754.2  227.91  3878.9  217.23
  3964.3  213.11  4400.8  214.77  4421.4  212.03  4542.4  214.33    4790  213.36
  4980.7  217.76  5005.8  213.45  5011.9  217.42  5032.7  217.91  5151.9  216.15
  5297.9  226.28  5522.2  233.21  5791.5  253.04  5916.1  256.91  5921.3   259.1
  5955.3  257.25  5968.2  258.55  5978.6  264.57  5994.4  267.98  6026.9  269.37
#Mann= 1 ,-1 , 0
  3322.4      .1       0
#XS Ineff= 2 , 0
         4973.72  239.02
Permanent Ineff=
       F       F
Bank Sta=4980.7,5032.7
XS Rating Curve= 0 ,0
Exp/Cntr=0.3,0.1

Type RM Length L Ch R = 1 ,1494    ,172,172,172
BEGIN DESCRIPTION:
UNT 054 IN BOCR 2.0
END DESCRIPTION:
XS GIS Cut Line= 3
      3738742.15     10571796.52      3740699.61     10574760.19
      3741499.59     10574710.19
#Sta/Elev= 30
  1439.1  222.71  1554.9  219.48  1642.2  213.71  1648.2  215.15  1678.3   213.2
  1858.9  211.03  2370.6  212.57  2665.9  210.27    2789  214.52  2855.3  213.65
  2918.4  215.56  3129.2  209.49  3258.6  211.71  3959.9  209.46  4306.1  210.77
  4616.1  215.14  4853.9  212.48  4977.3  214.66  4983.3  214.09  4987.9   210.8
  5000.6  207.57  5020.9   215.2    5041  213.17  5228.8  212.31  5351.6  214.22
  5471.8  222.64    5592  235.73  5702.2  242.68  5732.3   248.4  5792.4  253.98
#Mann= 1 ,-1 , 0
  1439.1     .03       0
#XS Ineff= 2 , 0
         3628.43  233.59
Permanent Ineff=
       F       F
Bank Sta=4977.3,5020.9
XS Rating Curve= 0 ,0
Exp/Cntr=0.3,0.1

Type RM Length L Ch R = 1 ,1322    ,289,289,289
BEGIN DESCRIPTION:
Mapping XS c390b922
END DESCRIPTION:
XS GIS Cut Line= 4
      3739467.31     10574643.01      3740253.73     10574976.32
      3740555.81     10574939.86      3741732.92     10574820.07
#Sta/Elev= 30
  3721.4  205.58  3880.8  204.93  4169.2  208.11  4223.5  207.44  4392.6  209.56
  4421.7  208.54  4516.4  210.23  4803.1  211.26  4974.1   214.1  4994.2  211.77
  5004.2  207.92  5014.3  213.78    5022  212.17  5027.1  214.08  5034.4  212.71
  5094.7  210.67  5275.6  211.95  5315.8  210.84  5396.3  211.63  5436.5  213.34
    5537  220.11  5657.6  233.88  5687.8  236.08  5814.1  252.13  5913.8  258.88
  5918.9  260.69    5929  261.02  6008.4   270.8  6013.4  270.14    6063  272.88
#Mann= 1 ,-1 , 0
  3721.4     .03       0
#XS Ineff= 2 , 0
         4163.08  249.02
Permanent Ineff=
       F       F
Bank Sta=4974.1,5027.1
XS Rating Curve= 0 ,0
Exp/Cntr=0.3,0.1

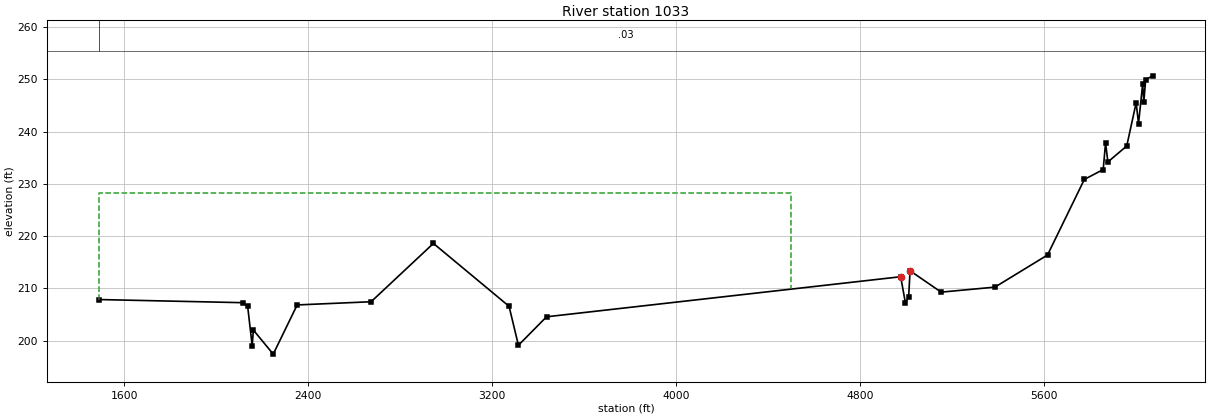
Type RM Length L Ch R = 1 ,1033    ,0,0,0
BEGIN DESCRIPTION:
UNT 054 IN BOCR 1.0
END DESCRIPTION:
XS GIS Cut Line= 5
      3737162.31     10575841.67      3738599.61     10575610.19
      3738698.84     10575590.34      3740599.61     10575210.19
        3741660.     10574976.32
#Sta/Elev= 30
  1491.1  207.85  2116.4  207.25  2136.6  206.54  2156.3  199.03  2161.4  202.01
  2247.8   197.4  2351.9  206.82  2673.4  207.43  2944.4   218.6  3273.3  206.56
    3314   199.1  3436.4  204.55  4976.3  212.22  4996.8  207.23  5010.9  208.33
  5017.2  213.36  5152.3  209.27  5386.1  210.23  5614.8  216.38    5775  230.85
    5857  232.75  5867.2  237.85  5877.4   234.2  5959.4  237.26  6000.3  245.53
  6010.6  241.52  6028.6  249.17  6033.7  245.63  6041.3  249.96  6072.4  250.69
#Mann= 1 ,-1 , 0
  1491.1     .03       0
#XS Ineff= 2 , 0
       0    4500  228.33               0
Permanent Ineff=
       F       F
Bank Sta=4976.3,5017.2
XS Rating Curve= 0 ,0
Exp/Cntr=0.3,0.1

Chan Stop Cuts=-1
Use User Specified Reach Order=0
Composite Channel Slope=5