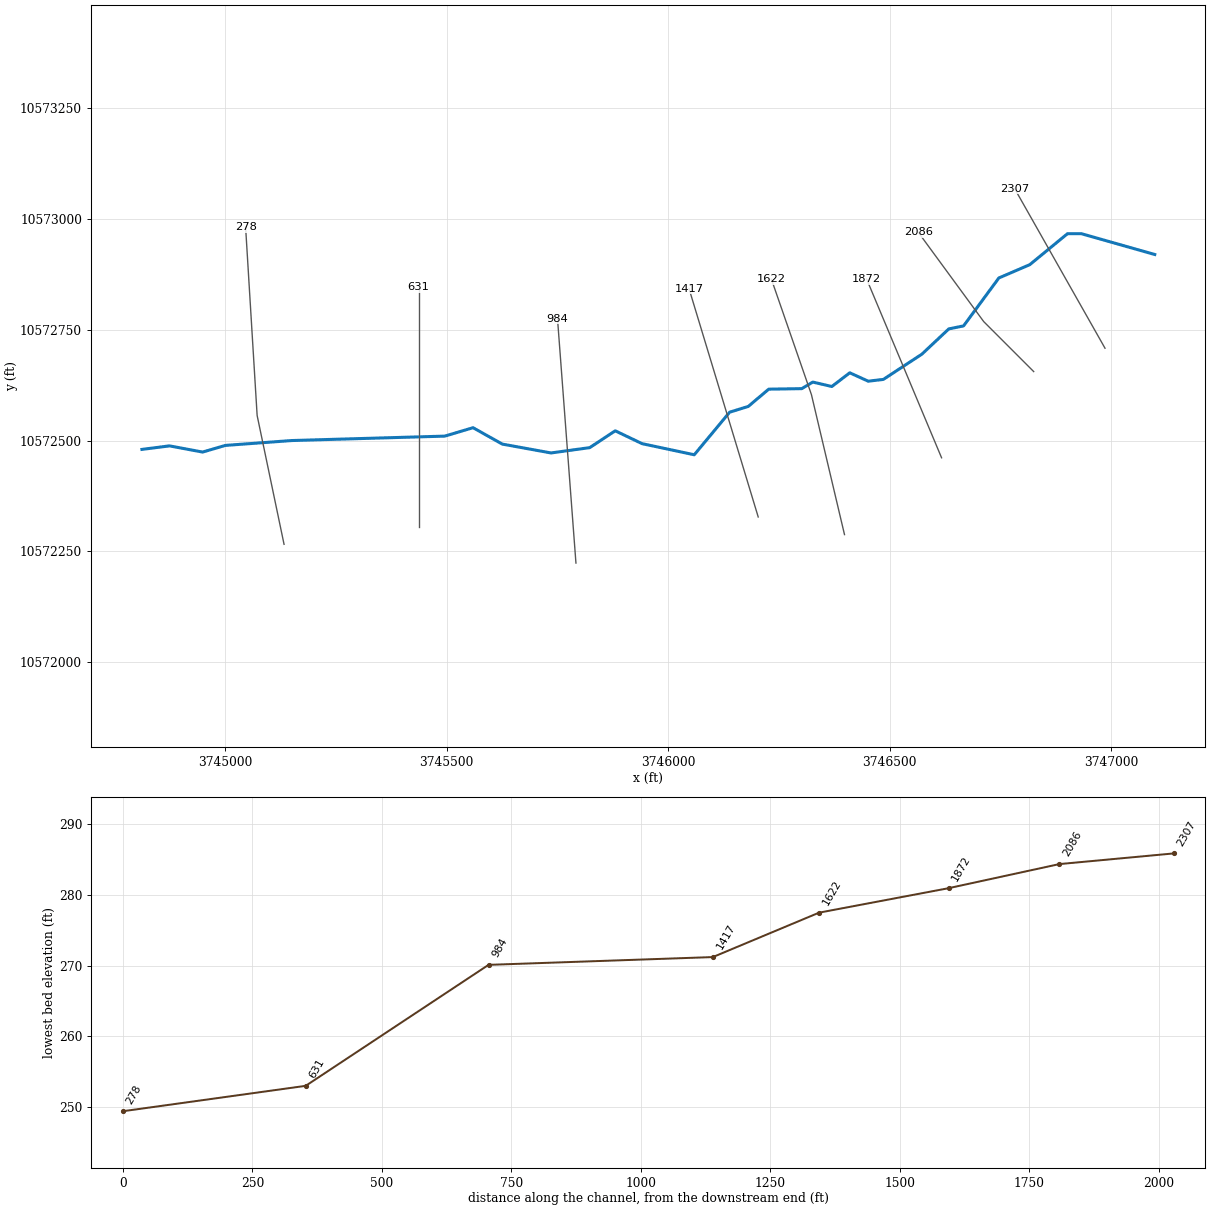
--- UNT 055 IN BOCR.prj (project) ---

Proj Title=UNT 055 IN BOCR Base Level Engineering
Current Plan=p01
Default Exp/Contr=0.3,0.1
English Units
Geom File=g01
Flow File=f01
Plan File=p01
Y Axis Title=Elevation
X Axis Title(PF)=Main Channel Distance
X Axis Title(XS)=Station
BEGIN DESCRIPTION:
UNT 055 IN BOCR
END DESCRIPTION:
DSS Export Rating Curves= 0
DSS Export Rating Curve Sorted= 0
DSS Export Volume Flow Curves= 0
DXF OffsetX= 0
DXF OffsetY= 0
DXF ScaleX= 1
DXF ScaleY= 10

--- UNT 055 IN BOCR.p01 (plan) ---

Plan Title=Multiple Run
Short Identifier=Multiple
Geom File=g01
Flow File=f01
Subcritical Flow
K Sum by GR= 0
Std Step Tol= 0.01
Critical Tol= 0.01
Num of Std Step Trials= 20
Max Error Tol= 0.3
Flow Tol Ratio= 0.001
Split Flow NTrial= 30
Split Flow Tol= 0.02
Split Flow Ratio= 0.02
Log Output Level= 0
Friction Slope Method= 1
Unsteady Friction Slope Method= 2
Unsteady Bridges Friction Slope Method= 1
Parabolic Critical Depth
Global Vel Dist=  1 , 1 , 1
Global Log Level= 0
CheckData=True
Encroach Param= -1, 0, 0, 0
BEGIN DESCRIPTION:
Multiple Run
END DESCRIPTION:

--- UNT 055 IN BOCR.f01 (steady flow) ---

Flow Title=Multiple
Number of Profiles=7
Profile Names=10-year,25-year,50-year,1pct_min,100-year,1pct_plu,500-year
River Rch & RM= UNT 055 IN BOCR,Reach-1,2307
     368     489     589     523     707     956    1021
Boundary for River Rch & Prof#=UNT 055 IN BOCR,Reach-1,1
Up Type=0
Dn Type=3
Dn Slope=0.005
Boundary for River Rch & Prof#=UNT 055 IN BOCR,Reach-1,2
Up Type=0
Dn Type=3
Dn Slope=0.005
Boundary for River Rch & Prof#=UNT 055 IN BOCR,Reach-1,3
Up Type=0
Dn Type=3
Dn Slope=0.005
Boundary for River Rch & Prof#=UNT 055 IN BOCR,Reach-1,4
Up Type=0
Dn Type=3
Dn Slope=0.005
Boundary for River Rch & Prof#=UNT 055 IN BOCR,Reach-1,5
Up Type=0
Dn Type=3
Dn Slope=0.005
Boundary for River Rch & Prof#=UNT 055 IN BOCR,Reach-1,6
Up Type=0
Dn Type=3
Dn Slope=0.005
Boundary for River Rch & Prof#=UNT 055 IN BOCR,Reach-1,7
Up Type=0
Dn Type=3
Dn Slope=0.005

--- UNT 055 IN BOCR.g01 (geometry) ---

Geom Title=Existing Conditions
Program Version=4.10

River Reach=UNT 055 IN BOCR ,Reach-1
Reach XY= 30
      3747098.26       10572920.       3746932.5       10572967.
      3746901.25       10572967.        3746816.       10572897.
      3746746.25       10572867.      3746666.65     10572758.85
      3746633.25       10572752.       3746572.5       10572695.
       3746485.5       10572638.      3746451.25       10572634.
       3746409.7     10572652.95      3746369.25       10572622.
      3746326.25       10572632.      3746301.37     10572617.18
      3746226.75       10572616.       3746180.5       10572577.
       3746138.5       10572564.      3746058.66     10572467.88
      3745940.75       10572493.      3745880.25       10572522.
      3745822.75       10572484.      3745735.25       10572472.
      3745625.25       10572492.      3745559.25       10572529.
       3745495.5       10572510.      3745149.75       10572500.
        3745000.       10572489.      3744948.75       10572474.
        3744874.       10572488.      3744811.75       10572480.

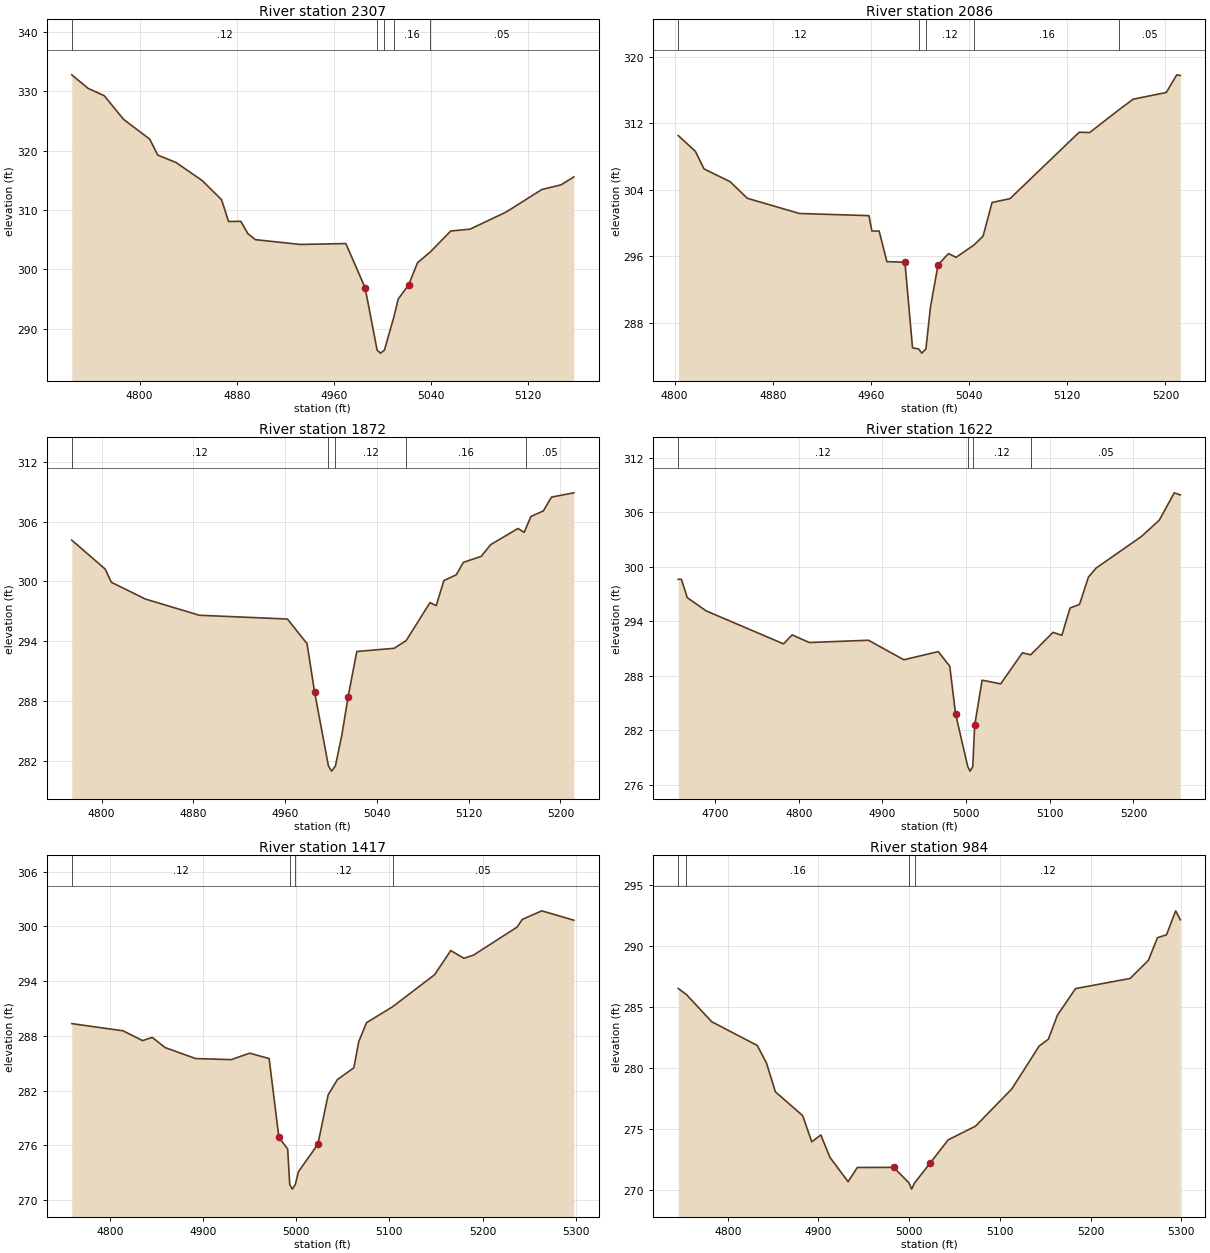
Type RM Length L Ch R = 1 ,2307    ,221,221,221
BEGIN DESCRIPTION:
UNT 055 IN BOCR 5.0
END DESCRIPTION:
XS GIS Cut Line= 2
       3746985.9     10572708.46       3746781.9     10573068.71
#Sta/Elev= 30
    4744  332.81  4757.5  330.52  4770.8  329.29  4786.7   325.3  4808.3  321.96
  4814.9  319.27    4830  318.02  4851.6  314.97  4867.5  311.75  4873.3  308.07
  4883.4   308.1  4889.2  306.03  4895.4  305.01  4932.4   304.2    4970  304.35
  4985.9  296.89  4995.8  286.37  4998.6  285.87  5001.8  286.37  5009.6  291.97
  5013.2     295  5021.8   297.4  5029.1  301.12  5039.5  302.91  5056.5  306.47
  5072.4  306.78  5102.2  309.67  5131.6  313.47  5147.5  314.26    5158   315.6
#Mann= 5 ,-1 , 0
    4744     .12       0  4995.8     .07       0  5001.8     .12       0
  5009.6     .16       0  5039.5     .05       0
Bank Sta=4985.9,5021.8
XS Rating Curve= 0 ,0
Exp/Cntr=0.3,0.1

Type RM Length L Ch R = 1 ,2086    ,214,214,214
BEGIN DESCRIPTION:
Mapping XS 47460dcd
END DESCRIPTION:
XS GIS Cut Line= 3
       3746824.9     10572655.72      3746712.06     10572768.55
      3746564.58     10572969.83
#Sta/Elev= 30
    4803  310.52    4817  308.62    4824  306.51  4845.3  304.97  4859.4  302.97
  4901.8  301.15  4958.4  300.89  4960.8  299.04  4966.7  299.04    4973  295.36
  4987.7  295.29  4993.9     285  4998.8  284.86  5001.5  284.36  5004.8  284.86
  5008.5  289.86  5014.7  294.98  5023.2  296.32  5029.4  295.88  5043.9  297.35
  5051.4  298.43  5058.7  302.47  5073.3  302.93  5129.7  310.92  5138.2  310.88
  5162.2  313.63  5173.7  314.89  5200.7   315.7  5209.2  317.82  5212.1  317.74
#Mann= 5 ,-1 , 0
    4803     .12       0  4998.8     .07       0  5004.8     .12       0
  5043.9     .16       0  5162.2     .05       0
Bank Sta=4987.7,5014.7
XS Rating Curve= 0 ,0
Exp/Cntr=0.3,0.1

Type RM Length L Ch R = 1 ,1872    ,250,250,250
BEGIN DESCRIPTION:
UNT 055 IN BOCR 4.0
END DESCRIPTION:
XS GIS Cut Line= 2
      3746616.97     10572461.06       3746447.7      10572864.7
#Sta/Elev= 30
    4774  304.14  4803.1  301.24  4808.5  299.91  4838.1  298.23  4885.2   296.6
    4962  296.22  4979.1  293.75  4985.7  288.88  4997.8  281.45  5000.5  280.95
  5003.8  281.45  5009.5   284.6  5014.9  288.41  5022.5  292.96    5055  293.28
  5065.5  294.05  5086.3  297.87  5091.7  297.56  5098.4  300.08  5109.2  300.66
  5115.4  301.91  5130.9  302.51  5139.2  303.69    5163  305.31  5168.4  304.92
  5170.2  305.41  5174.3  306.52  5185.1  307.07  5192.2  308.46  5211.7  308.89
#Mann= 5 ,-1 , 0
    4774     .12       0  4997.8     .07       0  5003.8     .12       0
  5065.5     .16       0  5170.2     .05       0
Bank Sta=4985.7,5014.9
XS Rating Curve= 0 ,0
Exp/Cntr=0.3,0.1

Type RM Length L Ch R = 1 ,1622    ,205,205,205
BEGIN DESCRIPTION:
Mapping XS 577329fb
END DESCRIPTION:
XS GIS Cut Line= 3
      3746397.82     10572287.69      3746323.18     10572603.62
      3746232.91     10572863.99
#Sta/Elev= 30
  4655.9  298.61  4659.7  298.61  4666.7  296.59  4689.3  295.13  4781.8   291.5
    4792  292.49  4812.6  291.65  4883.3   291.9  4925.6  289.75  4966.7  290.65
  4980.5  289.04  4987.5  283.76    5002  277.99  5004.8  277.49    5008  277.99
  5010.3  282.55  5019.2   287.5  5041.4   287.1  5067.3  290.51  5077.3   290.3
  5103.9  292.77  5114.5  292.44  5124.3  295.45  5135.6  295.84  5146.2  298.84
  5155.4  299.84  5209.7  303.33  5230.9  305.11  5248.9  308.13  5256.1   307.9
#Mann= 4 ,-1 , 0
  4655.9     .12       0    5002     .07       0    5008     .12       0
  5077.3     .05       0
Bank Sta=4987.5,5010.3
XS Rating Curve= 0 ,0
Exp/Cntr=0.3,0.1

Type RM Length L Ch R = 1 ,1417    ,433,433,433
BEGIN DESCRIPTION:
Mapping XS 19cf1323
END DESCRIPTION:
XS GIS Cut Line= 2
      3746203.02     10572327.48      3746046.76     10572843.12
#Sta/Elev= 30
  4759.1  289.35  4814.2  288.56  4835.1  287.49  4845.5  287.84  4859.1  286.73
    4892  285.52  4930.2   285.4    4950  286.11  4970.9  285.52  4981.4  276.87
  4990.8  275.61    4993  271.71  4995.8  271.21    4999  271.71  5002.3  273.11
  5023.2  276.13  5034.2  281.53  5044.1  283.21  5061.8  284.51  5067.1  287.38
  5075.4  289.45  5103.3  291.19  5148.5  294.71  5165.8  297.36  5179.9  296.51
  5190.3  296.86  5236.9  299.92  5242.6  300.77  5263.5  301.71  5297.9  300.68
#Mann= 4 ,-1 , 0
  4759.1     .12       0    4993     .07       0    4999     .12       0
  5103.3     .05       0
Bank Sta=4981.4,5023.2
XS Rating Curve= 0 ,0
Exp/Cntr=0.3,0.1

Type RM Length L Ch R = 1 ,984     ,353,353,353
BEGIN DESCRIPTION:
Mapping XS 2db5b22c
END DESCRIPTION:
XS GIS Cut Line= 2
      3745791.55     10572223.38      3745749.89     10572775.32
#Sta/Elev= 30
  4745.4  286.52  4754.5  286.02  4782.3   283.8  4832.5  281.86  4842.6  280.44
  4852.5  278.07  4882.6  276.12  4892.6  273.98  4902.6  274.54  4912.7   272.7
  4932.7  270.72  4942.8  271.88  4982.9  271.89  4999.9  270.61  5002.7  270.11
  5005.9  270.61    5023  272.23    5043  274.14  5073.1  275.26  5113.2  278.31
  5143.3  281.81  5153.4  282.37  5163.4  284.33  5183.4  286.51  5243.6  287.34
  5263.7  288.82  5273.7  290.67  5283.7  290.91  5293.8  292.87  5298.9  292.14
#Mann= 4 ,-1 , 0
  4745.4     .12       0  4754.5     .16       0  4999.9     .07       0
  5005.9     .12       0
Bank Sta=4982.9,5023
XS Rating Curve= 0 ,0
Exp/Cntr=0.3,0.1

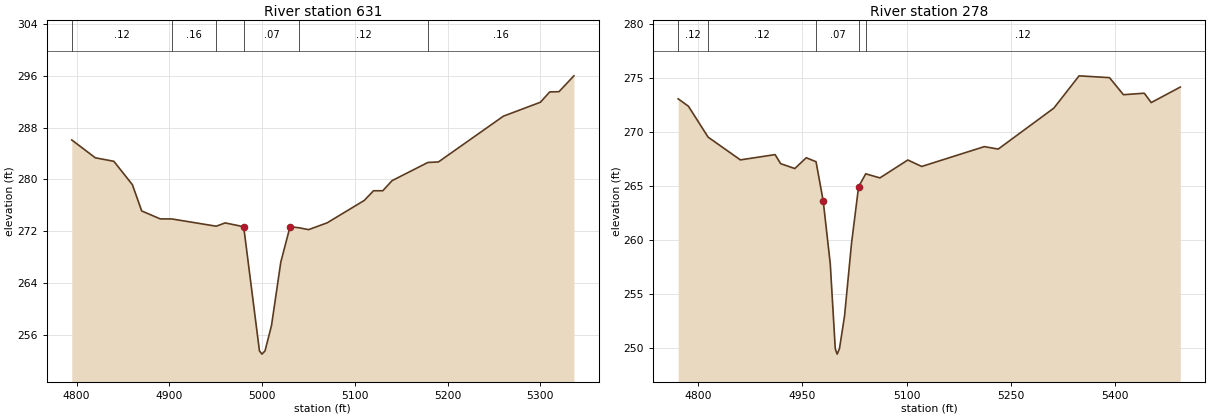
Type RM Length L Ch R = 1 ,631     ,353,353,353
BEGIN DESCRIPTION:
Mapping XS 1208a75d
END DESCRIPTION:
XS GIS Cut Line= 2
       3745436.4      10572304.8       3745436.4      10572846.3
#Sta/Elev= 30
  4794.8   286.1  4820.2  283.34  4840.2   282.8  4860.2  279.18  4870.2  275.13
  4890.2   273.9  4902.8  273.89  4950.6  272.77  4960.2  273.28  4980.2  272.69
  4997.2   253.5  4999.9     253  5003.2   253.5  5010.2  257.42  5020.2  267.21
  5030.2   272.7  5040.2  272.52  5050.2  272.24  5070.2  273.29  5110.2  276.75
  5120.2  278.25  5130.2  278.25  5140.2  279.81  5178.8  282.62  5190.2   282.7
  5260.2  289.77  5300.2  291.93  5310.2  293.52  5320.2  293.56  5336.3  296.01
#Mann= 6 ,-1 , 0
  4794.8     .12       0  4902.8     .16       0  4950.6     .12       0
  4980.2     .07       0  5040.2     .12       0  5178.8     .16       0
Bank Sta=4980.2,5030.2
XS Rating Curve= 0 ,0
Exp/Cntr=0.3,0.1

Type RM Length L Ch R = 1 ,278     ,0,0,0
BEGIN DESCRIPTION:
UNT 055 IN BOCR 1.0
END DESCRIPTION:
XS GIS Cut Line= 3
      3745132.59     10572265.75      3745071.82     10572556.59
      3745045.77     10572981.97
#Sta/Elev= 30
    4771  273.07  4785.8  272.38  4814.1  269.52  4860.6  267.41  4910.6   267.9
  4918.6  267.06    4939  266.61  4955.5  267.61  4969.6  267.24  4979.9  263.61
  4990.1  257.77  4997.3  249.91    5000  249.41  5003.3  249.91  5010.6  252.92
  5020.7  259.68  5030.9  264.93  5041.2  266.12  5061.6  265.74  5101.8   267.4
  5121.8   266.8    5212  268.64    5232  268.41  5312.2  272.21  5348.5   275.2
  5392.3  275.03  5412.4  273.45  5442.4  273.59  5452.4  272.72  5494.3  274.16
#Mann= 5 ,-1 , 0
    4771     .12       0  4814.1     .12       0  4969.6     .07       0
  5030.9     .12       0  5041.2     .12       0
Bank Sta=4979.9,5030.9
XS Rating Curve= 0 ,0
Exp/Cntr=0.3,0.1

Chan Stop Cuts=-1
Use User Specified Reach Order=0
Composite Channel Slope=5