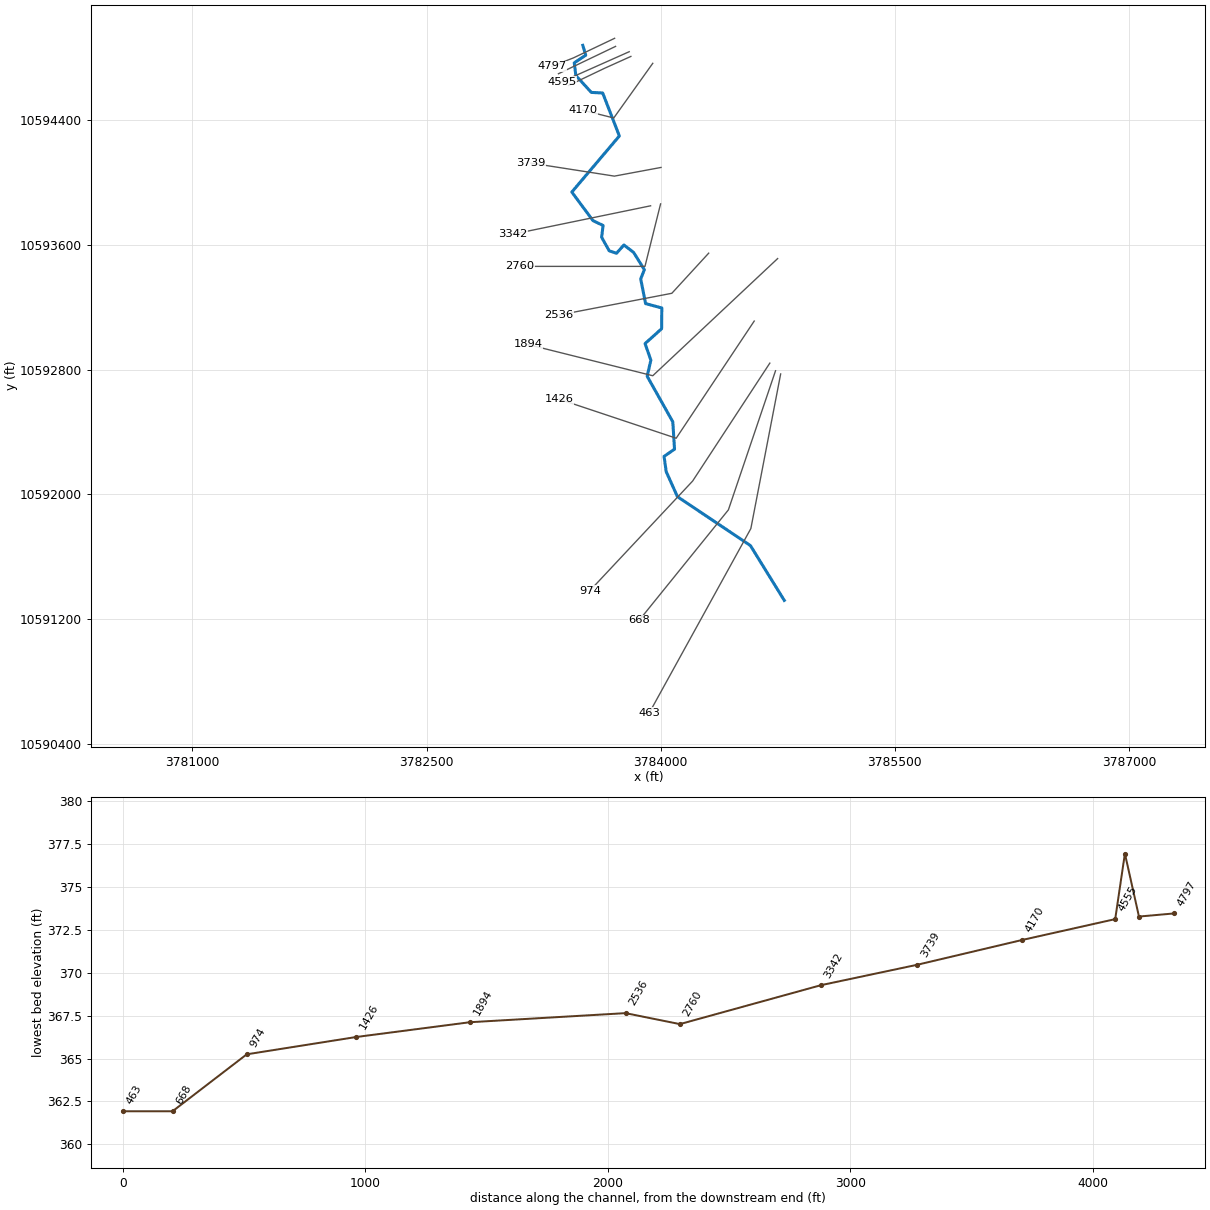
--- UNT 058 IN BOCR.prj (project) ---

Proj Title=UNT 058 IN BOCR Base Level Engineering
Current Plan=p01
Default Exp/Contr=0.3,0.1
English Units
Geom File=g01
Flow File=f01
Plan File=p01
Y Axis Title=Elevation
X Axis Title(PF)=Main Channel Distance
X Axis Title(XS)=Station
BEGIN DESCRIPTION:
UNT 058 IN BOCR
END DESCRIPTION:
DSS Export Rating Curves= 0
DSS Export Rating Curve Sorted= 0
DSS Export Volume Flow Curves= 0
DXF OffsetX= 0
DXF OffsetY= 0
DXF ScaleX= 1
DXF ScaleY= 10

--- UNT 058 IN BOCR.p01 (plan) ---

Plan Title=Multiple Run
Short Identifier=Multiple
Geom File=g01
Flow File=f01
Subcritical Flow
K Sum by GR= 0
Std Step Tol= 0.01
Critical Tol= 0.01
Num of Std Step Trials= 20
Max Error Tol= 0.3
Flow Tol Ratio= 0.001
Split Flow NTrial= 30
Split Flow Tol= 0.02
Split Flow Ratio= 0.02
Log Output Level= 0
Friction Slope Method= 1
Unsteady Friction Slope Method= 2
Unsteady Bridges Friction Slope Method= 1
Parabolic Critical Depth
Global Vel Dist=  1 , 1 , 1
Global Log Level= 0
CheckData=True
Encroach Param= -1, 0, 0, 0
BEGIN DESCRIPTION:
Multiple Run
END DESCRIPTION:

--- UNT 058 IN BOCR.f01 (steady flow) ---

Flow Title=Multiple
Number of Profiles=7
Profile Names=10-year,25-year,50-year,1pct_min,100-year,1pct_plu,500-year
River Rch & RM= UNT 058 IN BOCR,Reach-1,4797
     952    1332    1657    1515    2049    2771    3143
Boundary for River Rch & Prof#=UNT 058 IN BOCR,Reach-1,1
Up Type=0
Dn Type=3
Dn Slope=0.005
Boundary for River Rch & Prof#=UNT 058 IN BOCR,Reach-1,2
Up Type=0
Dn Type=3
Dn Slope=0.005
Boundary for River Rch & Prof#=UNT 058 IN BOCR,Reach-1,3
Up Type=0
Dn Type=3
Dn Slope=0.005
Boundary for River Rch & Prof#=UNT 058 IN BOCR,Reach-1,4
Up Type=0
Dn Type=3
Dn Slope=0.005
Boundary for River Rch & Prof#=UNT 058 IN BOCR,Reach-1,5
Up Type=0
Dn Type=3
Dn Slope=0.005
Boundary for River Rch & Prof#=UNT 058 IN BOCR,Reach-1,6
Up Type=0
Dn Type=3
Dn Slope=0.005
Boundary for River Rch & Prof#=UNT 058 IN BOCR,Reach-1,7
Up Type=0
Dn Type=3
Dn Slope=0.005

--- UNT 058 IN BOCR.g01 (geometry) ---

Geom Title=Existing Conditions
Program Version=4.10

River Reach=UNT 058 IN BOCR ,Reach-1
Reach XY= 30
      3783501.25       10594875.        3783520.       10594812.
       3783446.5       10594763.      3783456.75       10594682.
      3783555.75       10594574.      3783628.75       10594570.
       3783735.5       10594295.        3783431.       10593936.
       3783566.5       10593753.      3783631.25       10593722.
        3783622.       10593646.       3783670.5       10593560.
        3783717.       10593544.      3783764.75       10593597.
      3783827.25       10593549.      3783895.75       10593439.
      3783872.25       10593380.       3783903.5       10593222.
       3784007.5       10593194.      3784006.25       10593061.
      3783900.25       10592966.       3783937.5       10592860.
      3783913.75       10592757.        3784078.       10592465.
        3784089.       10592290.        3784022.       10592244.
      3784035.75       10592146.      3784107.75       10591986.
      3784575.25       10591673.      3784792.25       10591322.

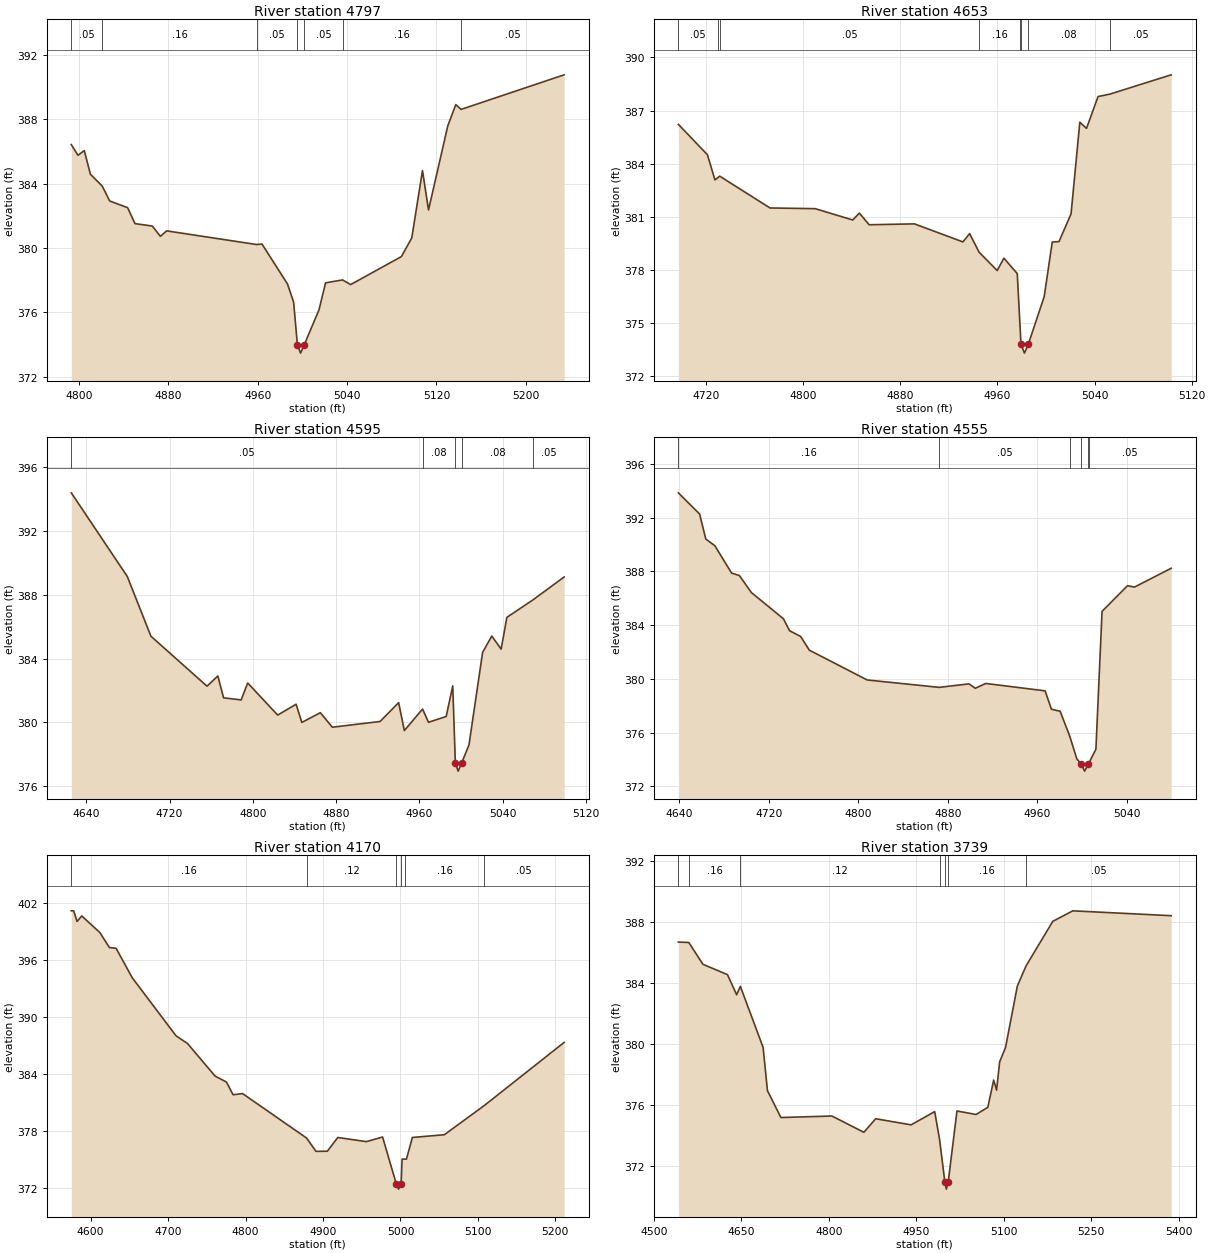
Type RM Length L Ch R = 1 ,4797    ,144,144,144
BEGIN DESCRIPTION:
Mapping XS a4b127b8
END DESCRIPTION:
XS GIS Cut Line= 3
      3783705.09     10594920.13      3783441.93     10594795.14
      3783302.78      10594740.3
#Sta/Elev= 30
  4793.3  386.42  4799.3  385.76  4804.9  386.05  4810.4  384.58    4821  383.84
  4827.6  382.92  4843.7   382.5  4850.3  381.51  4865.8  381.36    4873  380.72
  4878.6  381.06  4959.2  380.21  4963.9  380.24  4986.7  377.76  4992.2  376.63
  4995.6  373.96  4998.4  373.46  5001.6  373.96  5014.9  376.15  5020.8  377.83
    5036  378.01  5043.2  377.72  5088.6  379.46  5097.9  380.62  5107.5  384.81
  5112.9  382.36  5130.1  387.58  5137.3  388.91    5142  388.61  5234.2  390.76
#Mann= 7 ,-1 , 0
  4793.3     .05       0    4821     .16       0  4959.2     .05       0
  4995.6     .04       0  5001.6     .05       0    5036     .16       0
    5142     .05       0
Bank Sta=4995.6,5001.6
XS Rating Curve= 0 ,0
Exp/Cntr=0.3,0.1

Type RM Length L Ch R = 1 ,4653    ,58,58,58
BEGIN DESCRIPTION:
Mapping XS b0a34317
END DESCRIPTION:
XS GIS Cut Line= 2
      3783711.21     10594868.42      3783345.29     10594693.45
#Sta/Elev= 30
  4697.5  386.22  4721.4   384.5  4727.6  383.08  4729.7  383.19  4731.5  383.29
  4772.9  381.49  4810.1  381.45    4841  380.81  4846.5   381.2  4854.5  380.54
  4891.8  380.59  4931.7  379.57  4937.2  380.04    4945  378.99  4959.9  377.95
  4965.4  378.65  4976.4  377.78  4978.7  374.81  4979.5  373.78  4982.3  373.28
  4985.5  373.78  4998.6  376.48  5005.2  379.56  5010.8  379.59  5020.7  381.16
  5027.9  386.34  5033.4  385.99  5042.9  387.79  5052.7  387.93  5103.1  389.02
#Mann= 8 ,-1 , 0
  4697.5     .05       0  4729.7     .16       0  4731.5     .05       0
    4945     .16       0  4978.7     .08       0  4979.5     .07       0
  4985.5     .08       0  5052.7     .05       0
Bank Sta=4979.5,4985.5
XS Rating Curve= 0 ,0
Exp/Cntr=0.3,0.1

Type RM Length L Ch R = 1 ,4595    ,40,40,40
BEGIN DESCRIPTION:
Mapping XS fd99e9f1
END DESCRIPTION:
XS GIS Cut Line= 2
      3783798.75     10594834.42      3783366.09     10594642.05
#Sta/Elev= 30
  4625.6  394.38  4679.4  389.14  4702.1   385.4    4756  382.27  4766.4  382.91
  4771.9  381.54  4788.8  381.41  4795.1  382.47  4823.9  380.46  4841.6  381.14
  4847.1     380  4864.9  380.61  4876.4   379.7  4922.3  380.06  4940.1  381.24
  4945.6  379.49  4963.1  380.84  4968.8  380.01  4985.8  380.37  4992.1  382.29
  4994.6  377.45  4997.3  376.95  5000.6  377.45  5007.7  378.59  5020.8  384.39
  5029.6  385.41  5038.6  384.59  5044.1  386.58  5069.5  387.69  5099.1  389.11
#Mann= 5 ,-1 , 0
  4625.6     .05       0  4963.1     .08       0  4994.6     .07       0
  5000.6     .08       0  5069.5     .05       0
Bank Sta=4994.6,5000.6
XS Rating Curve= 0 ,0
Exp/Cntr=0.3,0.1

Type RM Length L Ch R = 1 ,4555    ,385,385,385
BEGIN DESCRIPTION:
Mapping XS 39854a60
END DESCRIPTION:
XS GIS Cut Line= 3
       3783809.3     10594804.18      3783641.23     10594728.47
      3783409.98     10594618.05
#Sta/Elev= 30
  4639.1  393.86  4658.1  392.28  4663.6  390.42  4671.7  389.92  4686.7  387.88
  4693.6   387.7  4704.4  386.43    4733  384.48  4738.5  383.59  4748.4  383.16
  4756.2  382.14  4807.9  379.92  4872.2  379.37    4899  379.63  4904.5   379.3
  4913.9  379.66    4967  379.11  4972.6  377.74  4980.4  377.59  4988.9  375.76
  4995.3  374.05  4999.5  373.63  5002.3  373.13  5005.5  373.63  5006.1  373.73
  5012.4  374.76  5017.9  385.03  5040.6  386.94  5046.9  386.84  5079.7  388.24
#Mann= 6 ,-1 , 0
  4639.1     .16       0  4872.2     .05       0  4988.9     .08       0
  4999.5     .07       0  5005.5     .08       0  5006.1     .05       0
Bank Sta=4999.5,5005.5
XS Rating Curve= 0 ,0
Exp/Cntr=0.3,0.1

Type RM Length L Ch R = 1 ,4170    ,431,431,431
BEGIN DESCRIPTION:
UNT 058 IN BOCR 9.0
END DESCRIPTION:
XS GIS Cut Line= 3
      3783949.62     10594760.21      3783699.61     10594410.19
       3783499.6     10594460.19
#Sta/Elev= 30
    4575  401.22  4578.1  401.22  4582.4   400.1  4588.5  400.68  4611.9  398.93
  4624.2  397.35  4632.8  397.28  4653.7  394.17  4710.2  388.06    4725  387.25
  4760.6  383.82  4775.3  383.19  4783.9  381.85  4796.2  381.97  4878.8  377.29
  4890.9  375.89  4905.6   375.9  4919.1  377.35    4956  376.91  4976.9   377.4
  4994.8  372.41  4997.5  371.91  5000.8  372.41  5002.1  375.07  5005.6  375.07
  5007.7  375.07  5015.4  377.35  5056.7  377.64  5108.5  380.73  5211.3  387.36
#Mann= 6 ,-1 , 0
    4575     .16       0  4878.8     .12       0  4994.8     .07       0
  5000.8     .12       0  5005.6     .16       0  5108.5     .05       0
Bank Sta=4994.8,5000.8
XS Rating Curve= 0 ,0
Exp/Cntr=0.3,0.1

Type RM Length L Ch R = 1 ,3739    ,397,397,397
BEGIN DESCRIPTION:
UNT 058 IN BOCR 8.0
END DESCRIPTION:
XS GIS Cut Line= 3
      3784002.41     10594093.54      3783703.76     10594037.98
      3783168.99     10594121.32
#Sta/Elev= 30
  4542.2  386.69  4560.1  386.66  4584.3  385.23  4626.4  384.55  4642.1  383.23
  4648.5  383.78  4687.5  379.77  4694.9  376.94    4718  375.17  4805.5  375.27
  4860.3   374.2  4880.5  375.09  4941.3  374.69  4981.7  375.56  4990.1  373.72
    4999  370.97  5001.7  370.47    5005  370.97  5019.9   375.6  5052.6  375.37
  5072.8  375.84  5082.8  377.63  5087.8  376.97  5093.1  378.83  5103.2  379.77
  5123.4   383.8  5138.3  385.12  5184.2  388.05  5218.5  388.74  5387.2  388.42
#Mann= 7 ,-1 , 0
  4542.2     .05       0  4560.1     .16       0  4648.5     .12       0
  4990.1     .16       0    4999     .07       0    5005     .16       0
  5138.3     .05       0
Bank Sta=4999,5005
XS Rating Curve= 0 ,0
Exp/Cntr=0.3,0.1

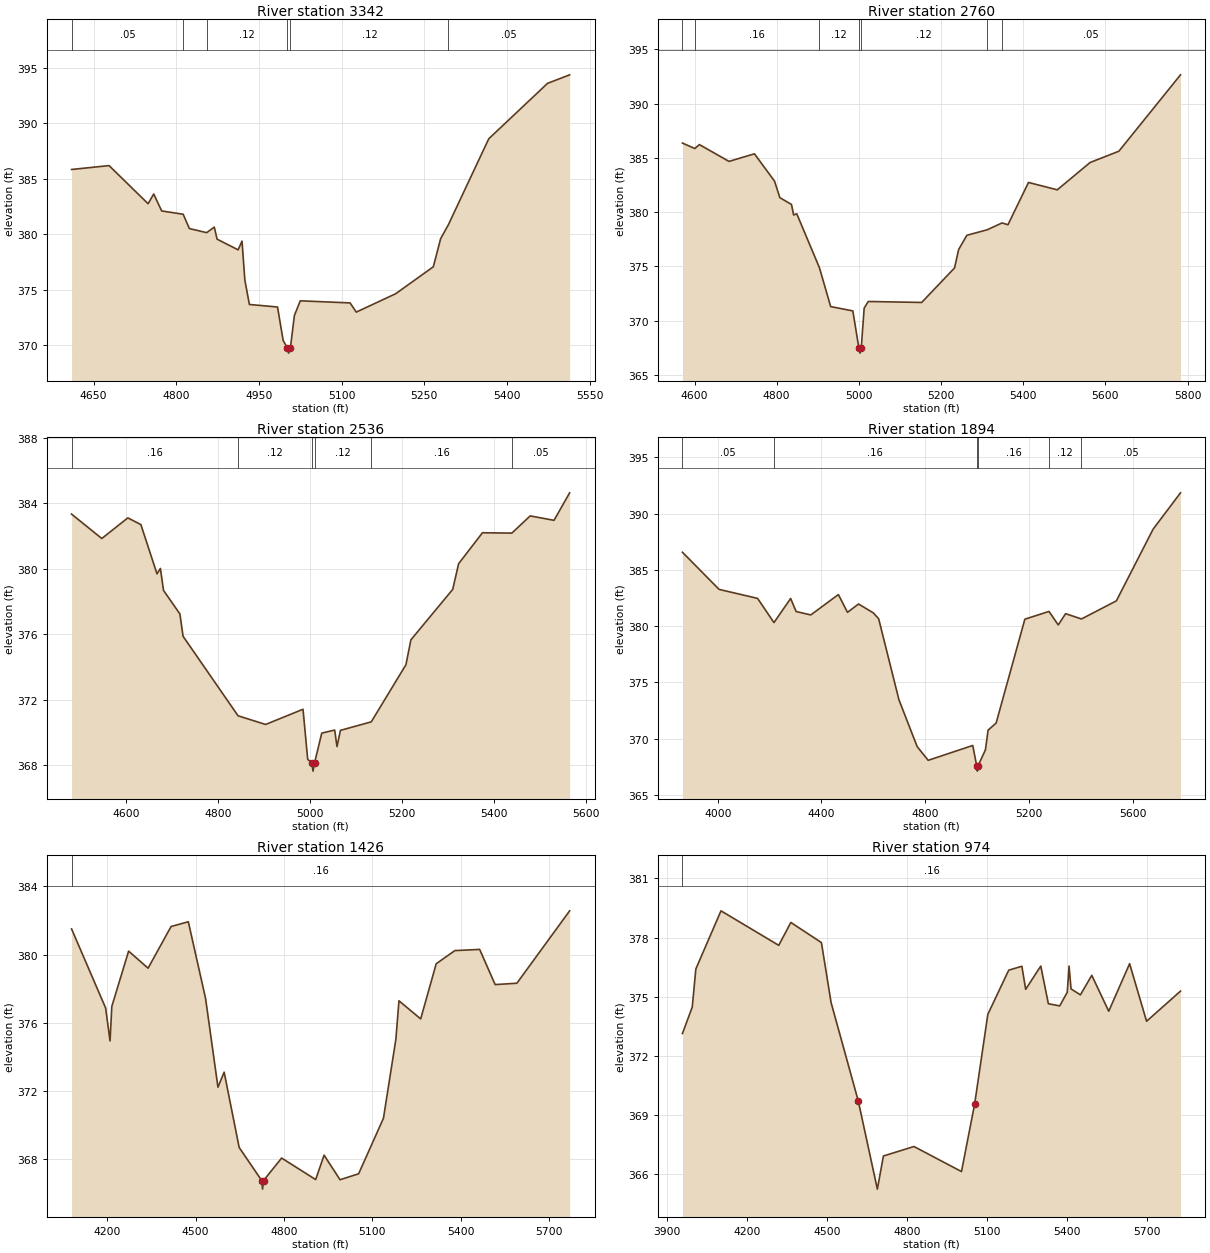
Type RM Length L Ch R = 1 ,3342    ,582,582,582
BEGIN DESCRIPTION:
UNT 058 IN BOCR 7.0
END DESCRIPTION:
XS GIS Cut Line= 2
      3783935.68     10593847.97      3783050.35     10593665.69
#Sta/Elev= 30
  4609.9  385.85  4677.9   386.2  4748.8  382.76    4759  383.64  4773.4  382.11
  4812.4  381.81  4823.7  380.52  4855.1  380.15  4868.9  380.65    4874  379.56
  4912.2   378.6  4919.2  379.39  4924.4  375.87  4932.6  373.67  4983.7  373.44
  4993.9  370.42  5001.1  369.78  5003.8  369.28  5007.1  369.78  5014.3  372.68
    5025     374  5115.4  373.81  5126.6  372.98  5198.1  374.64  5266.4  377.07
  5279.7  379.61  5293.7  380.86    5367  388.62  5473.7  393.62  5513.8  394.39
#Mann= 6 ,-1 , 0
  4609.9     .05       0  4812.4     .16       0  4855.1     .12       0
  5001.1     .07       0  5007.1     .12       0  5293.7     .05       0
Bank Sta=5001.1,5007.1
XS Rating Curve= 0 ,0
Exp/Cntr=0.3,0.1

Type RM Length L Ch R = 1 ,2760    ,224,224,224
BEGIN DESCRIPTION:
UNT 058 IN BOCR 6.0
END DESCRIPTION:
XS GIS Cut Line= 3
      3783999.62     10593860.22      3783899.61     10593460.19
      3783099.66     10593460.19
#Sta/Elev= 30
  4570.6  386.37  4600.7  385.87  4611.9  386.23    4684  384.68  4745.9  385.38
  4794.8  382.86  4807.7  381.34  4836.1  380.71  4841.2  379.74  4848.9  379.85
  4904.1  374.88  4931.4   371.3  4985.4   370.9  4999.9  367.51  5002.7  367.01
  5005.9  367.51  5012.9  371.15  5022.9  371.77  5152.9  371.68  5232.9  374.86
  5242.9  376.56  5262.9  377.87  5312.5  378.38  5348.6  379.01  5362.9  378.84
  5412.9  382.74  5482.9  382.06  5562.9  384.58  5632.9  385.62  5782.9  392.66
#Mann= 7 ,-1 , 0
  4570.6     .05       0  4600.7     .16       0  4904.1     .12       0
  4999.9     .07       0  5005.9     .12       0  5312.5     .16       0
  5348.6     .05       0
Bank Sta=4999.9,5005.9
XS Rating Curve= 0 ,0
Exp/Cntr=0.3,0.1

Type RM Length L Ch R = 1 ,2536    ,642,642,642
BEGIN DESCRIPTION:
UNT 058 IN BOCR 5.0
END DESCRIPTION:
XS GIS Cut Line= 3
      3784307.92     10593544.91      3784071.82     10593287.98
      3783349.59     10593149.09
#Sta/Elev= 30
  4480.9  383.35  4546.7  381.86  4603.4  383.12  4631.8  382.71  4666.9   379.7
  4674.3  380.03  4681.1  378.69  4716.8  377.25  4723.6  375.89  4843.4  371.03
  4903.4   370.5  4984.8  371.43    4995  368.37  5003.9  368.15  5006.6  367.65
  5009.9  368.15  5025.6  369.97  5053.7  370.16  5058.8  369.15  5066.3  370.14
  5133.4  370.66  5208.9  374.15  5219.7  375.67  5310.7  378.75  5323.6  380.32
  5375.5  382.21  5439.5  382.19  5479.4  383.24  5531.3  382.97  5565.3  384.65
#Mann= 6 ,-1 , 0
  4480.9     .16       0  4843.4     .12       0  5003.9     .07       0
  5009.9     .12       0  5133.4     .16       0  5439.5     .05       0
Bank Sta=5003.9,5009.9
XS Rating Curve= 0 ,0
Exp/Cntr=0.3,0.1

Type RM Length L Ch R = 1 ,1894    ,468,468,468
BEGIN DESCRIPTION:
UNT 058 IN BOCR 4.0
END DESCRIPTION:
XS GIS Cut Line= 3
      3784749.61     10593510.19      3783949.61     10592760.19
      3783149.61     10592960.19
#Sta/Elev= 30
  3863.7  386.57  4005.1  383.27  4153.6  382.47  4216.7  380.32  4281.1  382.46
  4302.3   381.3  4358.8     381  4465.2  382.81  4500.4  381.23  4542.9  381.97
  4599.6  381.19  4620.6  380.66  4698.7  373.47  4769.1   369.3  4811.6  368.08
  4983.5   369.4  4998.5  367.62  5001.3  367.12  5004.5  367.62  5032.4  369.01
  5042.7  370.76  5073.7  371.39  5184.5  380.62  5277.6  381.31  5313.3  380.11
  5341.7  381.11  5402.9  380.64  5537.5  382.25  5679.2  388.62  5784.9  391.85
#Mann= 6 ,-1 , 0
  3863.7     .05       0  4216.7     .16       0  4998.5     .07       0
  5004.5     .16       0  5277.6     .12       0  5402.9     .05       0
Bank Sta=4998.5,5004.5
XS Rating Curve= 0 ,0
Exp/Cntr=0.3,0.1

Type RM Length L Ch R = 1 ,1426    ,452,452,452
BEGIN DESCRIPTION:
UNT 058 IN BOCR 3.0
END DESCRIPTION:
XS GIS Cut Line= 3
      3784599.62     10593110.21      3784099.61     10592360.19
       3783349.6     10592610.19
#Sta/Elev= 30
  4078.4   381.5  4194.1  376.87  4209.1  374.94  4215.1  376.96  4272.2   380.2
  4338.3   379.2  4416.4  381.64    4475  381.92  4533.6  377.43  4575.7  372.23
  4596.7  373.11  4647.8   368.7  4724.4  366.76  4727.2  366.26  4730.4  366.76
    4792  368.08  4907.7  366.82  4936.2  368.25  4990.4  366.81  5053.6  367.16
  5137.9  370.41  5180.1  375.04  5190.6  377.29  5264.4  376.23  5317.1  379.46
  5380.4  380.23  5464.7   380.3  5517.4  378.24  5591.2  378.32  5770.4  382.56
#Mann= 1 ,-1 , 0
  4078.4     .16       0
Bank Sta=4724.4,4730.4
XS Rating Curve= 0 ,0
Exp/Cntr=0.3,0.1

Type RM Length L Ch R = 1 ,974     ,306,306,306
BEGIN DESCRIPTION:
UNT 058 IN BOCR 2.0
END DESCRIPTION:
XS GIS Cut Line= 3
       3784699.6       10592841.      3784204.83     10592085.82
      3783546.26     10591383.93
#Sta/Elev= 30
  3958.7  373.14  3995.5  374.48  4008.9  376.41  4103.1  379.36  4319.4  377.61
  4364.7  378.77  4479.2  377.75  4515.4  374.71  4617.2  369.72  4688.7  365.25
  4711.4  366.93  4825.9  367.41  5003.8  366.14  5053.1  369.57  5102.4  374.11
  5180.6  376.35  5229.9  376.55  5244.1  375.38  5300.7  376.56  5329.1  374.65
  5371.6  374.54  5399.9  375.23  5406.7  376.56    5414   375.4  5449.2   375.1
  5491.7  376.09  5555.2  374.27  5633.4  376.68  5696.9  373.76    5824  375.29
#Mann= 1 ,-1 , 0
  3958.7     .16       0
Bank Sta=4617.2,5053.1
XS Rating Curve= 0 ,0
Exp/Cntr=0.3,0.1

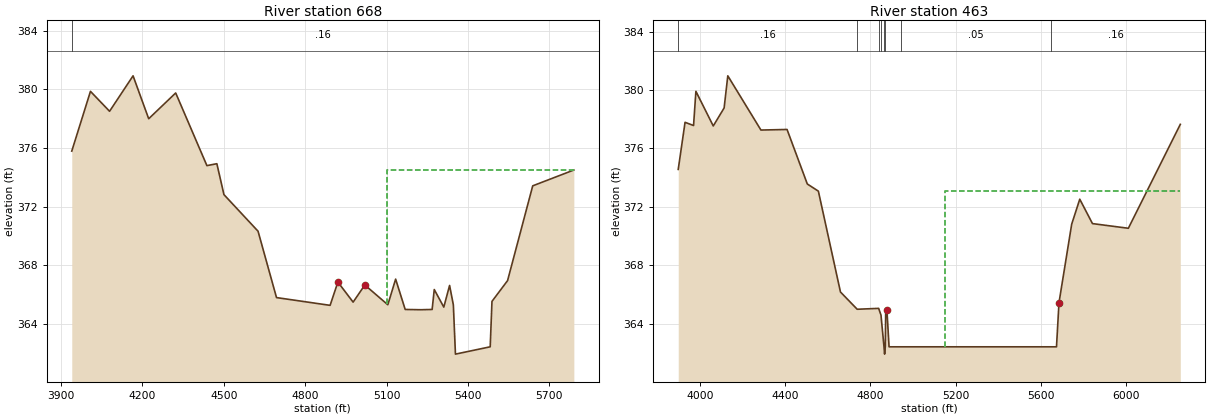
Type RM Length L Ch R = 1 ,668     ,205,205,205
BEGIN DESCRIPTION:
Mapping XS 0aa36027
END DESCRIPTION:
XS GIS Cut Line= 3
      3784736.18      10592792.1       3784434.1     10591901.49
      3783861.98     10591194.15
#Sta/Elev= 30
  3940.1  375.79    4009  379.87  4079.4  378.51    4166  380.93  4223.6     378
  4323.1  379.76  4438.1   374.8  4474.8  374.93  4500.9  372.82  4626.6  370.32
  4694.6  365.79  4892.1  365.26  4920.8  366.85  4976.9  365.48  5020.1  366.65
  5104.8   365.3  5133.6  367.05  5168.8  364.98  5226.3  364.96  5268.1  364.98
  5275.9  366.34  5311.1  365.14  5332.4  366.62  5346.3  365.29    5354  361.93
  5482.1  362.43  5488.6  365.53  5546.1  366.95  5638.8  373.42  5790.3   374.5
#Mann= 1 ,-1 , 0
  3940.1     .16       0
#XS Ineff= 2 , 0
       0                    5100       0  374.49
Permanent Ineff=
       F       F
Bank Sta=4920.8,5020.1
XS Rating Curve= 0 ,0
Exp/Cntr=0.3,0.1

Type RM Length L Ch R = 1 ,463     ,0,0,0
BEGIN DESCRIPTION:
UNT 058 IN BOCR 1.0
END DESCRIPTION:
XS GIS Cut Line= 3
      3784769.06     10592771.58      3784578.09       10591782.
      3783927.05     10590601.46
#Sta/Elev= 30
  3897.9  374.57  3929.9  377.79  3969.8  377.57  3980.8  379.91  4062.3  377.54
  4113.2  378.77  4130.5  380.97    4286  377.26  4408.5   377.3  4503.6  373.57
  4555.5  373.08  4659.2  366.18  4737.7     365  4838.4  365.06  4849.3   364.6
  4863.5  362.43  4866.3  361.93  4869.5  362.43  4871.6  365.04    4877  364.98
  4887.2  362.43  4943.5  362.43    5647  362.43  5672.9  362.43  5684.6  365.45
  5744.2  370.82  5782.1  372.53  5841.7  370.86  6010.1  370.54  6253.9  377.65
#Mann= 8 ,-1 , 0
  3897.9     .16       0  4737.7     .12       0  4838.4     .16       0
  4849.3     .07       0  4863.5    .035       0  4869.5     .07       0
  4943.5     .05       0    5647     .16       0
#XS Ineff= 2 , 0
       0                    5150       0  373.11
Permanent Ineff=
       F       F
Bank Sta=4877,5684.6
XS Rating Curve= 0 ,0
Exp/Cntr=0.3,0.1

Chan Stop Cuts=-1
Use User Specified Reach Order=0
Composite Channel Slope=5