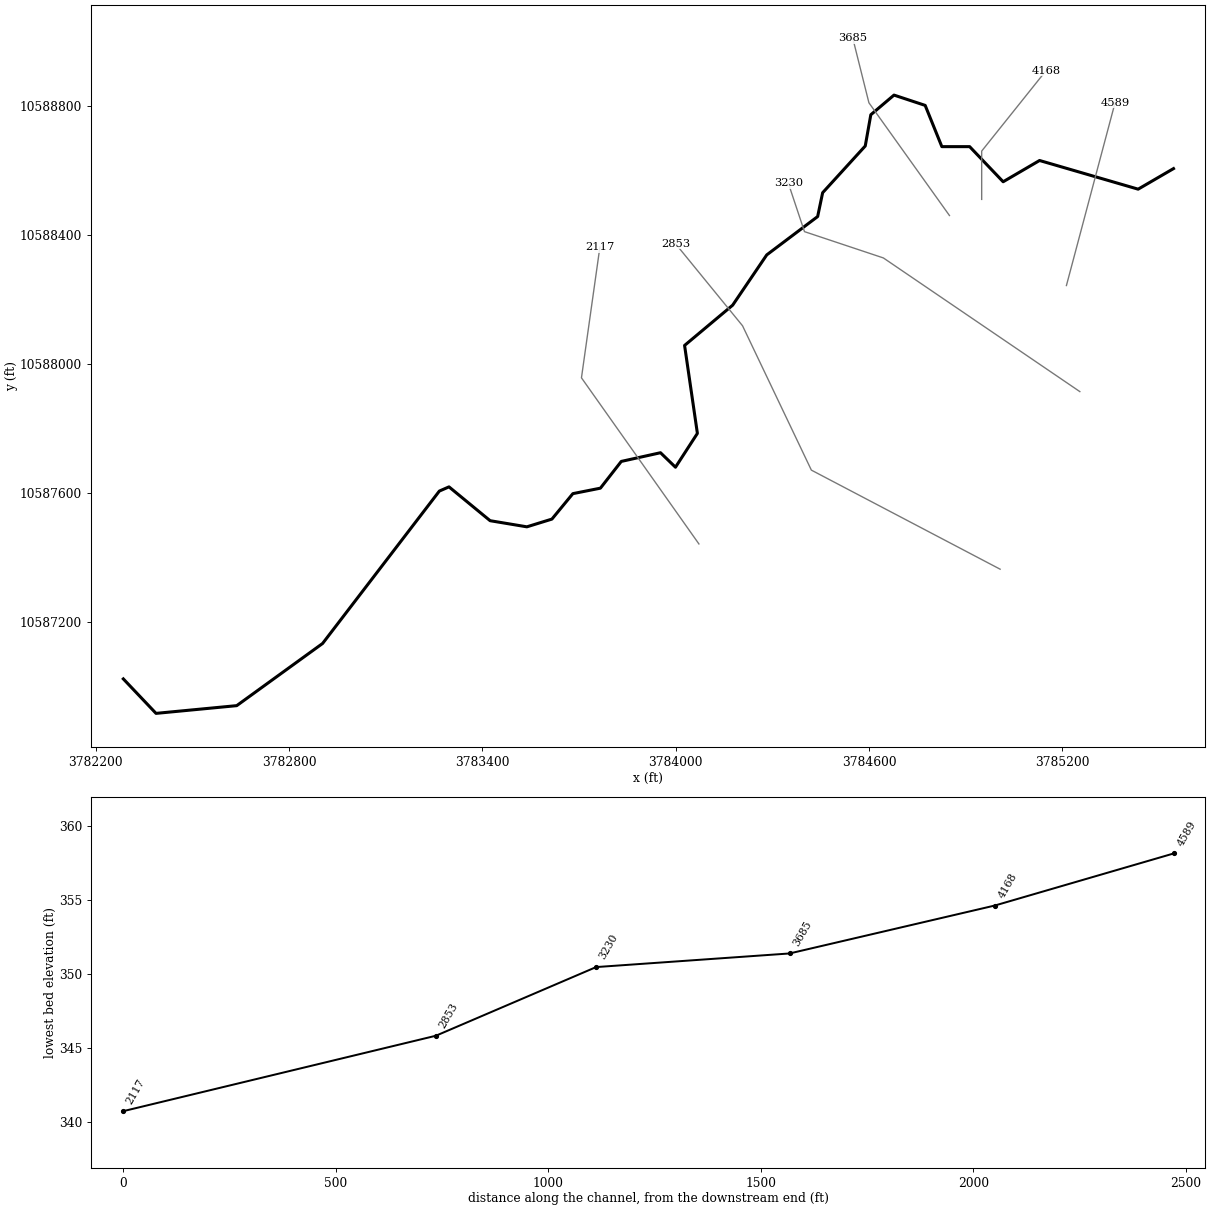
--- UNT 059 IN BOCR.prj (project) ---

Proj Title=UNT 059 IN BOCR Base Level Engineering
Current Plan=p01
Default Exp/Contr=0.3,0.1
English Units
Geom File=g01
Flow File=f01
Plan File=p01
BEGIN DESCRIPTION:
UNT 059 IN BOCR
END DESCRIPTION:

--- UNT 059 IN BOCR.p01 (plan) ---

Plan Title=Multiple Run
Short Identifier=Multiple
Geom File=g01
Flow File=f01
Subcritical Flow
K Sum by GR= 0
Std Step Tol= 0.01
Critical Tol= 0.01
Num of Std Step Trials= 20
Max Error Tol= 0.3
Flow Tol Ratio= 0.001
Split Flow NTrial= 30
Split Flow Tol= 0.02
Split Flow Ratio= 0.02
Log Output Level= 0
Friction Slope Method= 1
Unsteady Friction Slope Method= 2
Unsteady Bridges Friction Slope Method= 1
Parabolic Critical Depth
Global Vel Dist=  1 , 1 , 1
Global Log Level= 0
CheckData=True
Encroach Param= -1, 0, 0, 0
BEGIN DESCRIPTION:
Multiple Run
END DESCRIPTION:

--- UNT 059 IN BOCR.f01 (steady flow) ---

Flow Title=Multiple
Number of Profiles=7
Profile Names=10-year,25-year,50-year,1pct_min,100-year,1pct_plu,500-year
River Rch & RM= UNT 059 IN BOCR,Reach-1,4589
     561     753     910     809    1094    1480    1586
Boundary for River Rch & Prof#=UNT 059 IN BOCR,Reach-1,1
Up Type=0
Dn Type=3
Dn Slope=0.005
Boundary for River Rch & Prof#=UNT 059 IN BOCR,Reach-1,2
Up Type=0
Dn Type=3
Dn Slope=0.005
Boundary for River Rch & Prof#=UNT 059 IN BOCR,Reach-1,3
Up Type=0
Dn Type=3
Dn Slope=0.005
Boundary for River Rch & Prof#=UNT 059 IN BOCR,Reach-1,4
Up Type=0
Dn Type=3
Dn Slope=0.005
Boundary for River Rch & Prof#=UNT 059 IN BOCR,Reach-1,5
Up Type=0
Dn Type=3
Dn Slope=0.005
Boundary for River Rch & Prof#=UNT 059 IN BOCR,Reach-1,6
Up Type=0
Dn Type=3
Dn Slope=0.005
Boundary for River Rch & Prof#=UNT 059 IN BOCR,Reach-1,7
Up Type=0
Dn Type=3
Dn Slope=0.005

--- UNT 059 IN BOCR.g01 (geometry) ---

Geom Title=Existing Conditions

River Reach=UNT 059 IN BOCR,Reach-1
Reach XY= 30
      3785545.00     10588605.86      3785435.25     10588542.00
      3785129.25     10588631.00      3785016.25     10588565.00
      3784912.25     10588674.00      3784826.00     10588674.00
      3784774.25     10588802.00      3784677.50     10588834.00
      3784605.50     10588773.00      3784588.25     10588676.00
      3784456.00     10588531.00      3784440.50     10588457.00
      3784282.50     10588338.00      3784176.75     10588182.00
      3784027.50     10588057.00      3784067.25     10587784.00
      3783999.25     10587679.00      3783952.75     10587724.00
      3783831.00     10587697.00      3783766.25     10587614.00
      3783680.75     10587597.00      3783615.75     10587518.00
      3783538.00     10587494.00      3783424.00     10587513.00
      3783296.32     10587618.00      3783266.37     10587604.98
      3782904.00     10587132.00      3782637.50     10586939.00
      3782387.00     10586915.00      3782285.50     10587022.00

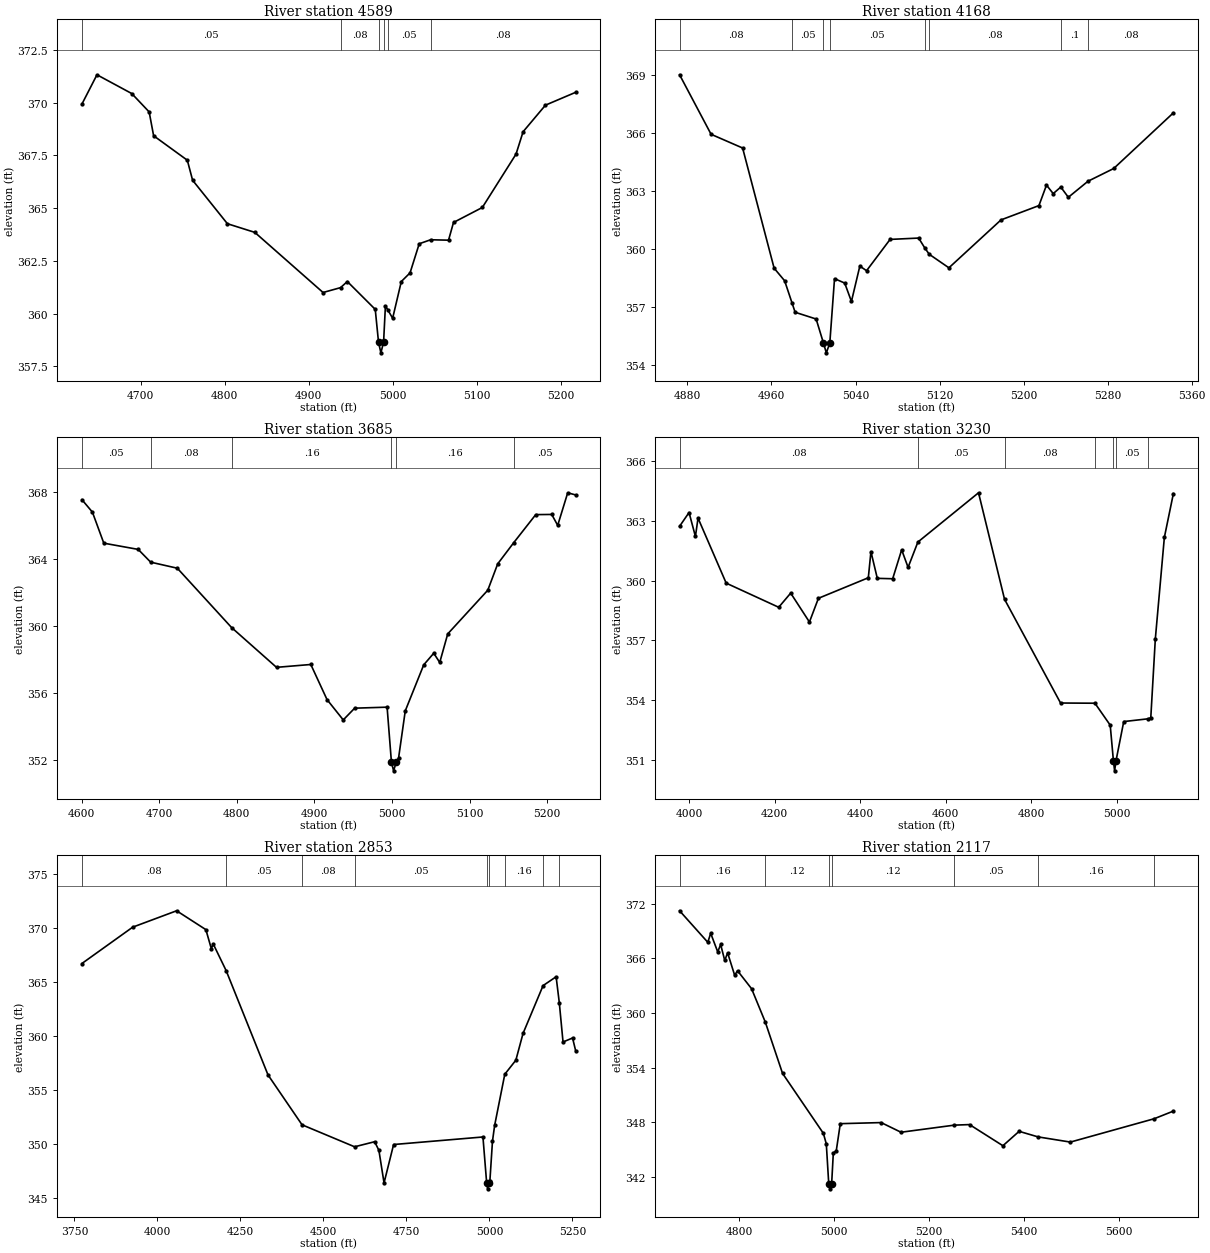
Type RM Length L Ch R = 1,4589,421,421,421
BEGIN DESCRIPTION:
UNT 059 IN BOCR 5.0
END DESCRIPTION:
XS GIS Cut Line= 2
      3785212.63     10588242.92      3785363.69     10588810.67
#Sta/Elev= 30
  4630.3  369.93  4648.2  371.32  4689.6  370.43  4710.3  369.56  4715.6  368.43
  4755.7  367.27  4762.0  366.32  4803.4  364.26  4836.0  363.85  4917.2  361.00
  4938.0  361.23  4946.1  361.52  4979.3  360.20  4983.2  358.64  4986.0  358.14
  4989.2  358.64  4991.4  360.37  4994.3  360.17  5000.0  359.78  5010.3  361.52
  5020.7  361.93  5031.6  363.31  5045.2  363.50  5066.5  363.48  5072.4  364.32
  5106.7  365.03  5146.8  367.56  5155.2  368.62  5181.8  369.88  5217.8  370.49
#Mann=6,-1,0
  4630.3    0.05       0  4938.0    0.08       0  4983.2    0.04       0
  4989.2    0.08       0  4994.3    0.05       0  5045.2    0.08       0
Bank Sta=4983.2,4989.2
Exp/Cntr=0.3,0.1

Type RM Length L Ch R = 1,4168,483,483,483
BEGIN DESCRIPTION:
UNT 059 IN BOCR 4.0
END DESCRIPTION:
XS GIS Cut Line= 3
      3784949.61     10588510.23      3784949.61     10588660.19
      3785149.60     10588910.18
#Sta/Elev= 30
  4872.5  369.01  4902.5  365.93  4932.5  365.22  4962.5  359.00  4972.5  358.35
  4979.5  357.21  4982.5  356.72  5002.5  356.37  5009.5  355.12  5012.2  354.62
  5015.5  355.12  5020.0  358.46  5029.7  358.23  5036.1  357.28  5044.1  359.11
  5050.5  358.87  5072.9  360.49  5100.1  360.56  5105.9  360.05  5110.2  359.72
  5128.9  359.02  5178.5  361.50  5214.6  362.24  5221.8  363.30  5228.2  362.86
  5235.4  363.20  5242.6  362.67  5261.3  363.50  5285.8  364.16  5342.6  367.04
#Mann=8,-1,0
  4872.5    0.08       0  4979.5    0.05       0  5009.5    0.04       0
  5015.5    0.05       0  5105.9    0.16       0  5110.2    0.08       0
  5235.4     0.1       0  5261.3    0.08       0
Bank Sta=5009.5,5015.5
Exp/Cntr=0.3,0.1

Type RM Length L Ch R = 1,3685,455,455,455
BEGIN DESCRIPTION:
UNT 059 IN BOCR 3.0
END DESCRIPTION:
XS GIS Cut Line= 3
      3784849.59     10588460.22      3784599.61     10588810.19
      3784549.62     10589010.15
#Sta/Elev= 30
  4600.5  367.52  4614.0  366.78  4628.7  364.93  4673.0  364.56  4689.1  363.80
  4723.4  363.44  4793.3  359.91  4851.2  357.54  4895.4  357.71  4916.3  355.62
  4937.2  354.41  4951.9  355.11  4993.7  355.17  4999.3  351.88  5002.1  351.38
  5005.3  351.88  5008.5  352.15  5017.1  354.95  5040.9  357.69  5053.8  358.38
  5061.5  357.83  5071.8  359.53  5123.4  362.13  5136.2  363.70  5157.0  364.97
  5185.2  366.63  5205.8  366.64  5213.5  365.99  5226.4  367.93  5236.7  367.80
#Mann=6,-1,0
  4600.5    0.05       0  4689.1    0.08       0  4793.3    0.16       0
  4999.3    0.07       0  5005.3    0.16       0  5157.0    0.05       0
Bank Sta=4999.3,5005.3
Exp/Cntr=0.3,0.1

Type RM Length L Ch R = 1,3230,377,377,377
BEGIN DESCRIPTION:
UNT 059 IN BOCR 2.0
END DESCRIPTION:
XS GIS Cut Line= 4
      3785254.26     10587913.70      3784644.52     10588328.55
      3784399.61     10588410.19      3784349.59     10588560.23
#Sta/Elev= 30
  3978.0  362.72  4000.1  363.41  4015.0  362.21  4021.1  363.13  4086.9  359.87
  4209.6  358.66  4237.6  359.37  4281.4  357.92  4302.4  359.11  4419.0  360.14
  4425.1  361.45  4440.0  360.11  4475.9  360.09  4496.9  361.54  4511.9  360.66
  4534.8  361.93  4676.5  364.40  4737.3  359.06  4868.2  353.86  4948.5  353.85
  4984.2  352.75  4991.7  350.96  4994.5  350.46  4997.7  350.96  5015.8  352.93
  5073.4  353.07  5079.0  353.12  5089.6  357.07  5110.7  362.16  5131.8  364.36
#Mann=7,-1,0
  3978.0    0.08       0  4534.8    0.05       0  4737.3    0.08       0
  4948.5    0.05       0  4991.7    0.04       0  4997.7    0.05       0
  5073.4    0.16       0
Bank Sta=4991.7,4997.7
Exp/Cntr=0.3,0.1

Type RM Length L Ch R = 1,2853,736,736,736
BEGIN DESCRIPTION:
Mapping XS de60b1d8
END DESCRIPTION:
XS GIS Cut Line= 5
      3785006.84     10587362.50      3784420.97     10587670.02
      3784402.32     10587709.16      3784207.43     10588117.94
      3783999.12     10588373.12
#Sta/Elev= 30
  3772.7  366.72  3925.6  370.09  4057.9  371.61  4146.1  369.86  4162.5  368.09
  4168.1  368.54  4207.1  366.06  4333.3  356.38  4435.7  351.76  4594.0  349.72
  4654.4  350.19  4667.2  349.39  4682.7  346.37  4711.5  349.93  4980.6  350.63
  4991.9  346.32  4994.7  345.82  4997.9  346.32  5001.4  346.51  5009.3  350.24
  5015.8  351.70  5046.4  356.45  5079.7  357.75  5101.3  360.23  5161.7  364.67
  5201.0  365.49  5210.5  363.10  5221.8  359.44  5250.5  359.81  5260.0  358.61
#Mann=9,-1,0
  3772.7    0.08       0  4207.1    0.05       0  4435.7    0.08       0
  4594.0    0.05       0  4991.9    0.04       0  4997.9    0.05       0
  5046.4    0.16       0  5161.7    0.05       0  5210.5    0.08       0
Bank Sta=4991.9,4997.9
Exp/Cntr=0.3,0.1

Type RM Length L Ch R = 1,2117,0,0,0
BEGIN DESCRIPTION:
UNT 059 IN BOCR 1.0
END DESCRIPTION:
XS GIS Cut Line= 3
      3784072.00     10587440.87      3783707.43     10587956.48
      3783764.66     10588362.29
#Sta/Elev= 30
  4674.2  371.23  4733.7  367.77  4739.8  368.76  4754.6  366.72  4760.8  367.53
  4769.4  365.78  4775.5  366.61  4790.3  364.16  4796.4  364.65  4826.0  362.68
  4855.0  359.01  4891.3  353.39  4977.4  346.81  4983.6  345.65  4988.8  341.22
  4991.5  340.72  4994.8  341.22  4998.4  344.67  5004.5  344.86  5013.1  347.87
  5099.3  347.99  5141.1  346.93  5253.7  347.71  5285.7  347.77  5356.0  345.45
  5390.2  347.03  5430.1  346.42  5498.3  345.85  5674.9  348.41  5715.5  349.25
#Mann=7,-1,0
  4674.2    0.16       0  4855.0    0.12       0  4988.8    0.07       0
  4994.8    0.12       0  5253.7    0.05       0  5430.1    0.16       0
  5674.9     0.1       0
Bank Sta=4988.8,4994.8
Exp/Cntr=0.3,0.1

Chan Stop Cuts=-1