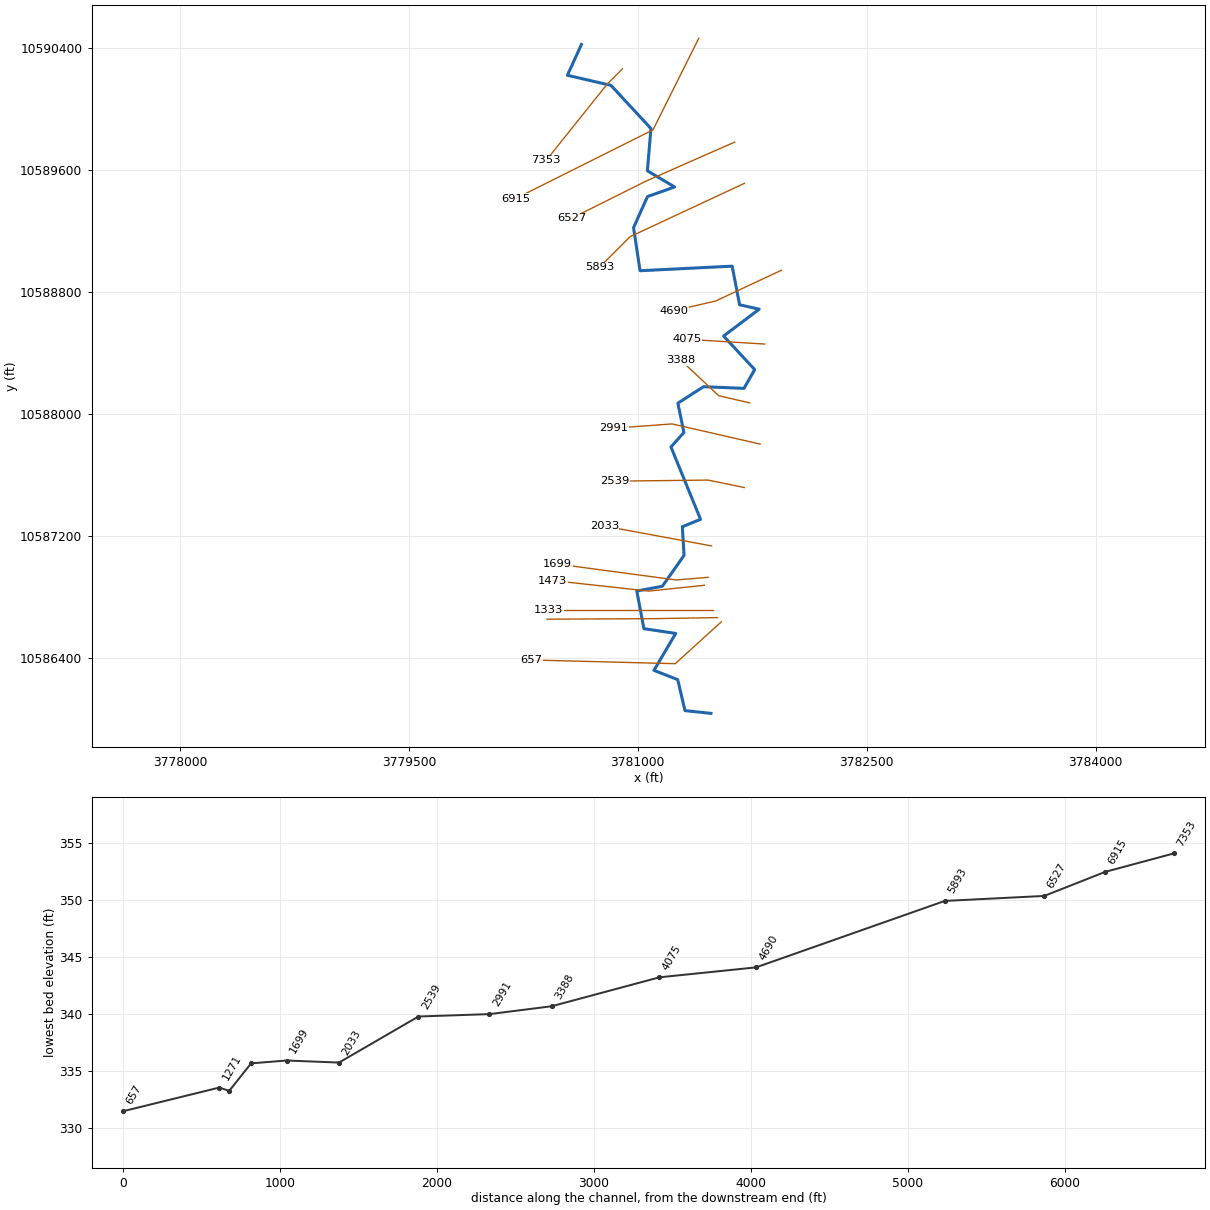
--- UNT 061 IN BOCR.prj (project) ---

Proj Title=UNT 061 IN BOCR Base Level Engineering
Current Plan=p01
Default Exp/Contr=0.3,0.1
English Units
Geom File=g01
Flow File=f01
Plan File=p01
BEGIN DESCRIPTION:
UNT 061 IN BOCR
END DESCRIPTION:

--- UNT 061 IN BOCR.p01 (plan) ---

Plan Title=Multiple Run
Short Identifier=Multiple
Geom File=g01
Flow File=f01
Subcritical Flow
K Sum by GR= 0
Std Step Tol= 0.01
Critical Tol= 0.01
Num of Std Step Trials= 20
Max Error Tol= 0.3
Flow Tol Ratio= 0.001
Split Flow NTrial= 30
Split Flow Tol= 0.02
Split Flow Ratio= 0.02
Log Output Level= 0
Friction Slope Method= 1
Unsteady Friction Slope Method= 2
Unsteady Bridges Friction Slope Method= 1
Parabolic Critical Depth
Global Vel Dist=  1 , 1 , 1
Global Log Level= 0
CheckData=True
Encroach Param= -1, 0, 0, 0
BEGIN DESCRIPTION:
Multiple Run
END DESCRIPTION:

--- UNT 061 IN BOCR.f01 (steady flow) ---

Flow Title=Multiple
Number of Profiles=7
Profile Names=10-year,25-year,50-year,1pct_min,100-year,1pct_plu,500-year
River Rch & RM= UNT 061 IN BOCR,Reach-1,7353
     539     723     874     778    1052    1422    1526
River Rch & RM= UNT 061 IN BOCR,Reach-1,5893
     818    1120    1372    1234    1669    2257    2480
Boundary for River Rch & Prof#=UNT 061 IN BOCR,Reach-1,1
Up Type=0
Dn Type=3
Dn Slope=0.005
Boundary for River Rch & Prof#=UNT 061 IN BOCR,Reach-1,2
Up Type=0
Dn Type=3
Dn Slope=0.005
Boundary for River Rch & Prof#=UNT 061 IN BOCR,Reach-1,3
Up Type=0
Dn Type=3
Dn Slope=0.005
Boundary for River Rch & Prof#=UNT 061 IN BOCR,Reach-1,4
Up Type=0
Dn Type=3
Dn Slope=0.005
Boundary for River Rch & Prof#=UNT 061 IN BOCR,Reach-1,5
Up Type=0
Dn Type=3
Dn Slope=0.005
Boundary for River Rch & Prof#=UNT 061 IN BOCR,Reach-1,6
Up Type=0
Dn Type=3
Dn Slope=0.005
Boundary for River Rch & Prof#=UNT 061 IN BOCR,Reach-1,7
Up Type=0
Dn Type=3
Dn Slope=0.005

--- UNT 061 IN BOCR.g01 (geometry) ---

Geom Title=Existing Conditions

River Reach=UNT 061 IN BOCR,Reach-1
Reach XY= 30
      3780630.75     10590420.00      3780538.75     10590218.00
      3780824.25     10590152.00      3781086.25     10589869.00
      3781063.00     10589592.00      3781241.50     10589486.00
      3781063.50     10589423.00      3780972.25     10589219.00
      3781015.00     10588937.00      3781618.50     10588967.00
      3781667.25     10588714.00      3781795.75     10588685.00
      3781562.50     10588509.00      3781766.25     10588289.00
      3781696.00     10588166.00      3781431.00     10588177.00
      3781263.00     10588069.00      3781302.25     10587877.00
      3781217.50     10587782.00      3781411.25     10587308.00
      3781292.00     10587259.00      3781303.25     10587071.00
      3781160.75     10586869.00      3780993.50     10586838.00
      3781040.25     10586591.00      3781248.75     10586560.00
      3781106.00     10586318.00      3781261.75     10586257.00
      3781309.50     10586054.00      3781479.50     10586036.00

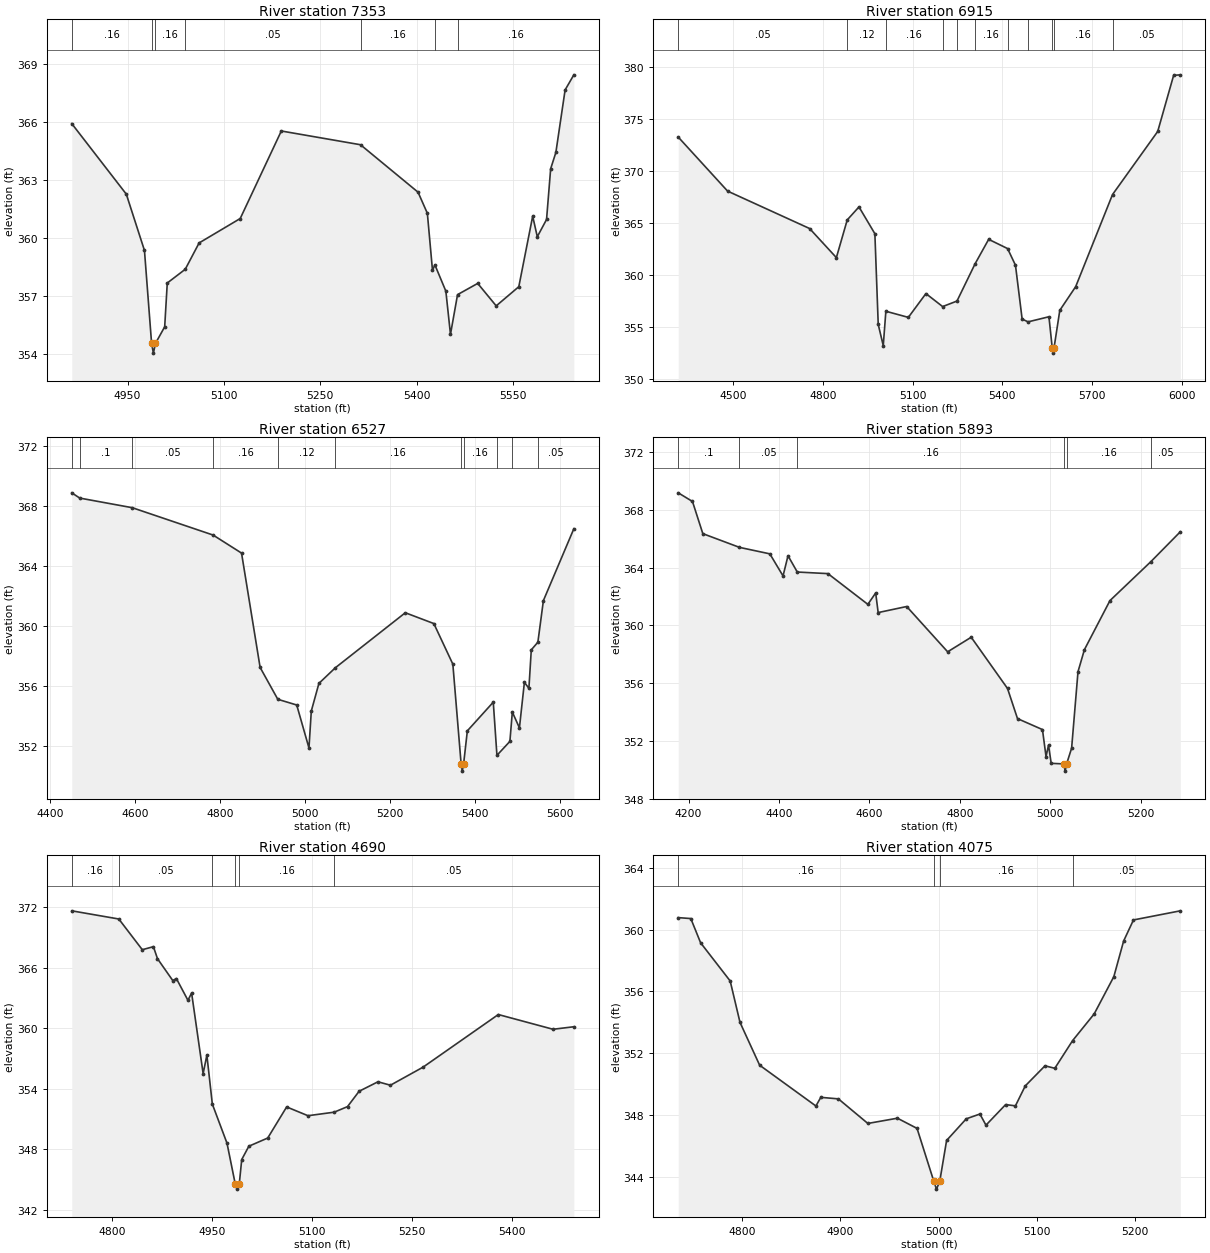
Type RM Length L Ch R = 1,7353,438,438,438
BEGIN DESCRIPTION:
UNT 061 IN BOCR 11.0
END DESCRIPTION:
XS GIS Cut Line= 3
      3780899.63     10590260.21      3780799.61     10590160.19
      3780399.59     10589660.16
#Sta/Elev= 30
  4863.2  365.92  4948.1  362.28  4976.4  359.37  4987.5  354.57  4990.3  354.07
  4993.5  354.57  5007.9  355.43  5011.9  357.69  5039.9  358.40  5061.5  359.76
  5125.5  361.02  5189.5  365.54  5312.8  364.83  5402.4  362.38  5416.9  361.29
  5424.9  358.34  5428.6  358.63  5445.7  357.27  5452.9  355.04  5463.9  357.09
  5495.3  357.67  5524.1  356.51  5559.3  357.50  5580.9  361.14  5588.1  360.08
  5602.5  360.97  5608.9  363.59  5617.0  364.43  5631.4  367.66  5645.0  368.44
#Mann=7,-1,0
  4863.2    0.16       0  4987.5    0.07       0  4993.5    0.16       0
  5039.9    0.05       0  5312.8    0.16       0  5428.6    0.12       0
  5463.9    0.16       0
Bank Sta=4987.5,4993.5
Exp/Cntr=0.3,0.1

Type RM Length L Ch R = 1,6915,388,388,388
BEGIN DESCRIPTION:
UNT 061 IN BOCR 10.0
END DESCRIPTION:
XS GIS Cut Line= 3
      3781399.59     10590460.16      3781099.61     10589860.19
      3780199.62     10589410.20
#Sta/Elev= 30
  4317.2  373.24  4482.1  368.04  4756.0  364.44  4845.4  361.64  4881.7  365.27
  4920.9  366.52  4974.0  363.94  4985.2  355.21  5002.0  353.17  5010.7  356.48
  5085.8  355.89  5144.5  358.18  5200.3  356.93  5248.2  357.46  5308.8  361.05
  5354.1  363.40  5417.3  362.51  5443.6  360.91  5465.9  355.72  5485.8  355.46
  5555.4  355.95  5566.4  352.95  5569.1  352.45  5572.4  352.95  5591.7  356.57
  5644.8  358.85  5767.8  367.71  5918.7  373.78  5971.9  379.18  5994.2  379.23
#Mann=11,-1,0
  4317.2    0.05       0  4881.7    0.12       0  5010.7    0.16       0
  5200.3    0.05       0  5248.2    0.12       0  5308.8    0.16       0
  5417.3    0.12       0  5485.8    0.16       0  5566.4    0.07       0
  5572.4    0.16       0  5767.8    0.05       0
Bank Sta=5566.4,5572.4
Exp/Cntr=0.3,0.1

Type RM Length L Ch R = 1,6527,634,634,634
BEGIN DESCRIPTION:
UNT 061 IN BOCR 9.0
END DESCRIPTION:
XS GIS Cut Line= 3
      3781635.02     10589780.18      3781051.72     10589523.25
      3780565.58     10589280.18
#Sta/Elev= 30
  4451.4  368.86  4470.2  368.51  4593.7  367.87  4783.8  366.05  4850.7  364.85
  4894.4  357.24  4936.0  355.12  4980.5  354.74  5009.3  351.88  5014.8  354.34
  5032.7  356.18  5071.4  357.22  5235.9  360.88  5303.0  360.16  5347.7  357.46
  5367.1  350.84  5369.8  350.34  5373.1  350.84  5381.8  353.02  5442.8  354.93
  5451.4  351.39  5481.9  352.32  5487.6  354.27  5504.3  353.22  5516.0  356.25
  5526.6  355.85  5532.2  358.41  5547.7  358.92  5560.7  361.69  5632.3  366.47
#Mann=11,-1,0
  4451.4    0.05       0  4470.2     0.1       0  4593.7    0.05       0
  4783.8    0.16       0  4936.0    0.12       0  5071.4    0.16       0
  5367.1    0.07       0  5373.1    0.16       0  5451.4    0.12       0
  5487.6    0.16       0  5547.7    0.05       0
Bank Sta=5367.1,5373.1
Exp/Cntr=0.3,0.1

Type RM Length L Ch R = 1,5893,1203,1203,1203
BEGIN DESCRIPTION:
UNT 061 IN BOCR 8.0
END DESCRIPTION:
XS GIS Cut Line= 3
      3781699.63     10589510.20      3780949.61     10589160.19
      3780749.62     10588960.20
#Sta/Elev= 30
  4177.1  369.19  4208.6  368.59  4231.5  366.36  4312.5  365.41  4379.7  364.96
  4408.9  363.43  4419.9  364.83  4440.4  363.70  4508.2  363.59  4596.5  361.46
  4613.8  362.25  4619.3  360.89  4682.4  361.31  4773.0  358.17  4825.1  359.18
  4905.4  355.63  4927.5  353.54  4982.7  352.78  4990.6  350.91  4996.1  351.70
  5002.0  350.44  5030.1  350.40  5032.8  349.90  5036.1  350.40  5047.2  351.49
  5061.3  356.79  5075.5  358.32  5132.0  361.72  5222.5  364.42  5287.6  366.49
#Mann=6,-1,0
  4177.1     0.1       0  4312.5    0.05       0  4440.4    0.16       0
  5030.1    0.07       0  5036.1    0.16       0  5222.5    0.05       0
Bank Sta=5030.1,5036.1
Exp/Cntr=0.3,0.1

Type RM Length L Ch R = 1,4690,615,615,615
BEGIN DESCRIPTION:
UNT 061 IN BOCR 7.0
END DESCRIPTION:
XS GIS Cut Line= 3
      3781940.60     10588939.92      3781510.05     10588738.53
      3781239.19     10588676.02
#Sta/Elev= 30
  4739.2  371.63  4809.8  370.82  4845.0  367.78  4861.7  368.08  4867.8  366.89
  4890.7  364.73  4896.2  364.92  4913.5  362.77  4919.0  363.49  4936.3  355.51
  4941.9  357.34  4950.1  352.49  4972.1  348.62  4984.5  344.57  4987.3  344.07
  4990.5  344.57  4994.2  347.00  5004.9  348.32  5033.2  349.13  5061.6  352.21
  5093.6  351.34  5132.9  351.69  5152.9  352.24  5170.3  353.76  5198.6  354.70
  5217.3  354.36  5266.3  356.15  5379.2  361.36  5461.3  359.90  5492.5  360.15
#Mann=6,-1,0
  4739.2    0.16       0  4809.8    0.05       0  4950.1    0.16       0
  4984.5    0.07       0  4990.5    0.16       0  5132.9    0.05       0
Bank Sta=4984.5,4990.5
Exp/Cntr=0.3,0.1

Type RM Length L Ch R = 1,4075,687,687,687
BEGIN DESCRIPTION:
UNT 061 IN BOCR 6.0
END DESCRIPTION:
XS GIS Cut Line= 2
      3781832.38     10588456.49      3781322.04     10588487.73
#Sta/Elev= 30
  4734.8  360.77  4747.6  360.71  4757.6  359.14  4787.7  356.67  4797.7  353.99
  4817.7  351.22  4875.0  348.58  4880.0  349.14  4897.9  349.04  4927.9  347.45
  4958.0  347.79  4978.0  347.13  4995.1  343.70  4997.8  343.20  5001.1  343.70
  5008.1  346.35  5028.1  347.75  5042.0  348.06  5048.2  347.34  5068.2  348.67
  5078.2  348.59  5088.2  349.88  5108.3  351.18  5118.3  351.02  5136.4  352.81
  5158.4  354.54  5178.4  356.95  5188.4  359.26  5198.4  360.62  5246.1  361.21
#Mann=4,-1,0
  4734.8    0.16       0  4995.1    0.07       0  5001.1    0.16       0
  5136.4    0.05       0
Bank Sta=4995.1,5001.1
Exp/Cntr=0.3,0.1

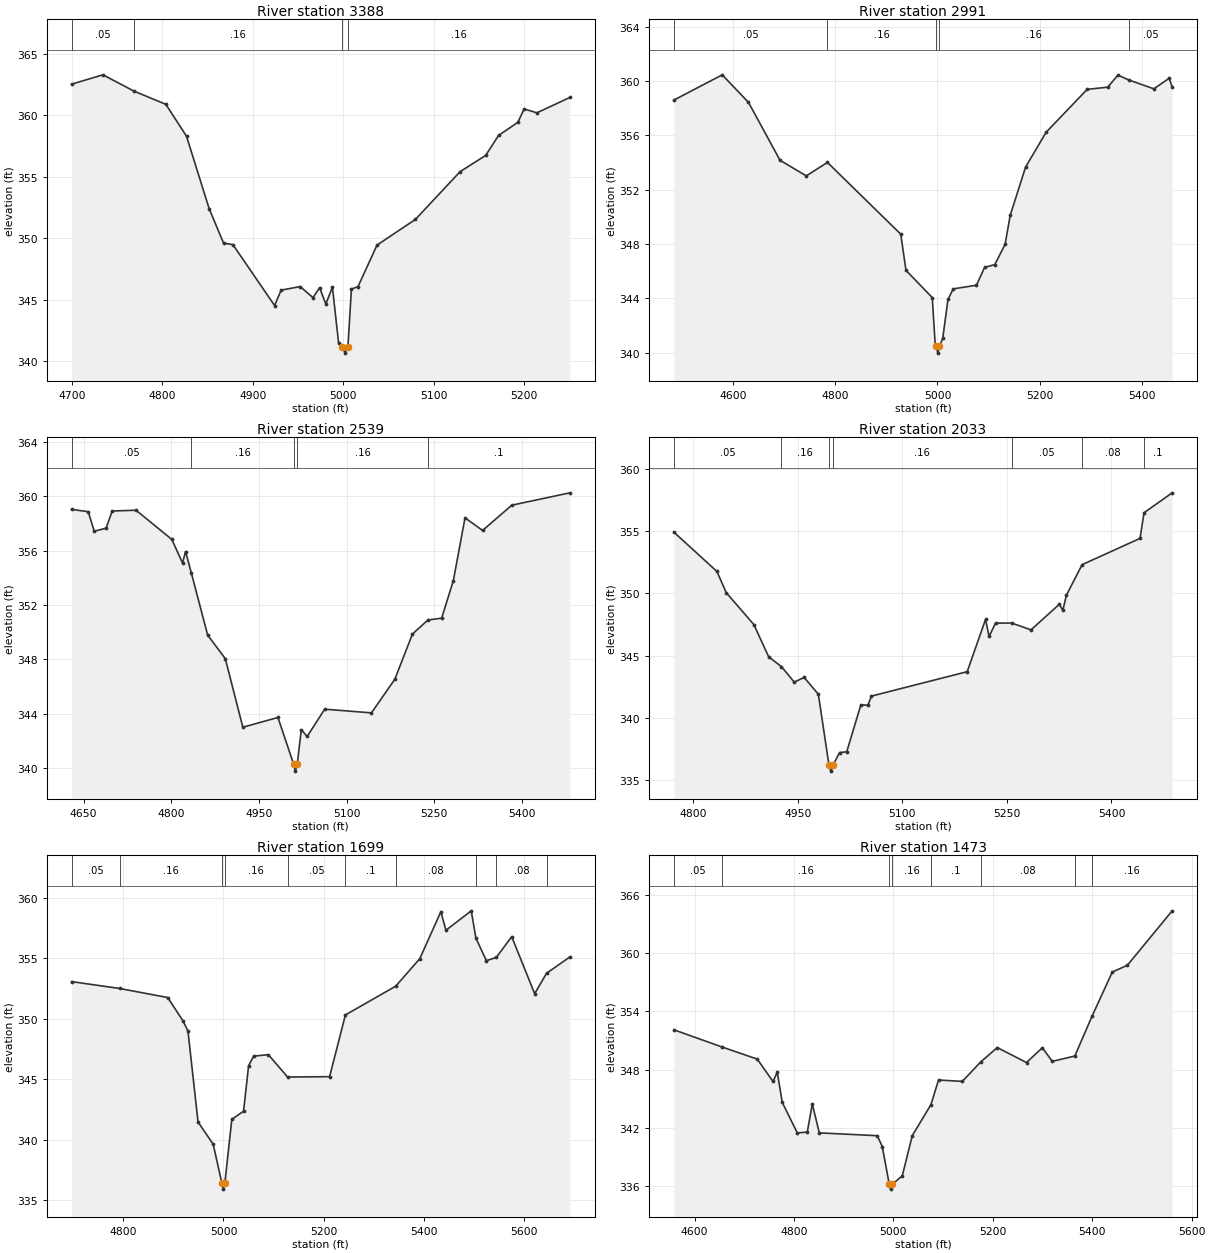
Type RM Length L Ch R = 1,3388,397,397,397
BEGIN DESCRIPTION:
UNT 061 IN BOCR 5.0
END DESCRIPTION:
XS GIS Cut Line= 3
      3781733.43     10588071.07      3781530.35     10588117.94
      3781280.35     10588352.31
#Sta/Elev= 30
  4699.7  362.52  4734.4  363.28  4768.6  361.96  4804.0  360.88  4826.8  358.29
  4851.9  352.39  4867.8  349.60  4878.1  349.48  4924.2  344.53  4931.5  345.78
  4952.5  346.07  4966.7  345.17  4974.0  345.98  4980.9  344.65  4988.2  346.03
  4995.0  341.49  4999.3  341.16  5002.1  340.66  5005.3  341.16  5009.2  345.86
  5016.5  346.07  5037.5  349.44  5080.0  351.53  5129.4  355.41  5157.7  356.73
  5171.9  358.35  5193.3  359.42  5200.2  360.51  5214.3  360.19  5250.8  361.44
#Mann=4,-1,0
  4699.7    0.05       0  4768.6    0.16       0  4999.3    0.07       0
  5005.3    0.16       0
Bank Sta=4999.3,5005.3
Exp/Cntr=0.3,0.1

Type RM Length L Ch R = 1,2991,452,452,452
BEGIN DESCRIPTION:
UNT 061 IN BOCR 4.0
END DESCRIPTION:
XS GIS Cut Line= 3
      3781801.75     10587801.02      3781225.33     10587932.97
      3780843.96     10587905.24
#Sta/Elev= 30
  4484.9  358.60  4579.4  360.46  4630.7  358.43  4692.3  354.17  4743.6  353.02
  4785.0  354.01  4928.2  348.73  4938.5  346.06  4989.8  344.06  4995.7  340.51
  4997.8  340.47  5000.6  339.97  5003.8  340.47  5010.3  341.07  5020.5  343.92
  5030.8  344.70  5076.2  344.97  5092.0  346.28  5112.0  346.49  5132.1  347.98
  5142.1  350.11  5172.2  353.67  5212.3  356.23  5292.5  359.39  5332.6  359.55
  5352.7  360.44  5374.0  360.08  5422.9  359.43  5452.9  360.21  5458.6  359.56
#Mann=5,-1,0
  4484.9    0.05       0  4785.0    0.16       0  4997.8    0.07       0
  5003.8    0.16       0  5374.0    0.05       0
Bank Sta=4997.8,5003.8
Exp/Cntr=0.3,0.1

Type RM Length L Ch R = 1,2539,506,506,506
BEGIN DESCRIPTION:
UNT 061 IN BOCR 3.0
END DESCRIPTION:
XS GIS Cut Line= 3
      3781697.54     10587516.31      3781461.44     10587564.92
      3780850.33     10587557.97
#Sta/Elev= 30
  4629.6  359.03  4658.1  358.86  4668.3  357.42  4688.7  357.65  4699.0  358.91
  4739.8  358.97  4801.0  356.82  4819.4  355.08  4824.5  355.93  4834.6  354.32
  4862.3  349.78  4892.5  348.04  4922.5  342.99  4982.5  343.71  5009.5  340.26
  5012.2  339.76  5015.5  340.26  5022.5  342.81  5032.5  342.31  5062.5  344.32
  5142.5  344.05  5182.5  346.53  5212.5  349.85  5239.1  350.89  5262.5  351.02
  5282.5  353.78  5302.5  358.41  5332.5  357.48  5382.5  359.34  5481.8  360.25
#Mann=5,-1,0
  4629.6    0.05       0  4834.6    0.16       0  5009.5    0.07       0
  5015.5    0.16       0  5239.1     0.1       0
Bank Sta=5009.5,5015.5
Exp/Cntr=0.3,0.1

Type RM Length L Ch R = 1,2033,334,334,334
BEGIN DESCRIPTION:
UNT 061 IN BOCR 2.0
END DESCRIPTION:
XS GIS Cut Line= 2
      3781483.42     10587133.57      3780780.38     10587263.77
#Sta/Elev= 30
  4772.1  354.92  4833.9  351.76  4847.2  350.06  4886.8  347.50  4908.2  344.90
  4926.4  344.12  4944.8  342.87  4959.0  343.25  4979.4  341.90  4994.6  336.22
  4997.4  335.72  5000.6  336.22  5009.9  337.21  5020.1  337.27  5040.4  341.04
  5050.5  341.02  5055.6  341.75  5193.0  343.71  5219.3  347.91  5224.4  346.54
  5233.6  347.61  5256.6  347.62  5284.5  347.07  5325.1  349.12  5330.2  348.64
  5335.3  349.85  5357.9  352.31  5441.0  354.42  5446.7  356.48  5487.1  358.08
#Mann=7,-1,0
  4772.1    0.05       0  4926.4    0.16       0  4994.6    0.07       0
  5000.6    0.16       0  5256.6    0.05       0  5357.9    0.08       0
  5446.7     0.1       0
Bank Sta=4994.6,5000.6
Exp/Cntr=0.3,0.1

Type RM Length L Ch R = 1,1699,226,226,226
BEGIN DESCRIPTION:
Mapping XS f17b9c35
END DESCRIPTION:
XS GIS Cut Line= 3
      3781460.74     10586927.65      3781252.41     10586910.29
      3780474.61     10587014.46
#Sta/Elev= 30
  4697.1  353.08  4793.1  352.51  4888.9  351.76  4919.1  349.84  4929.2  348.99
  4949.3  341.46  4979.6  339.61  4996.8  336.40  4999.5  335.90  5002.8  336.40
  5016.7  341.68  5040.1  342.35  5050.2  346.13  5060.3  346.91  5089.6  347.03
  5127.9  345.18  5211.7  345.21  5243.2  350.32  5343.5  352.70  5391.6  354.98
  5433.6  358.87  5443.7  357.33  5494.2  358.94  5503.5  356.68  5524.4  354.81
  5544.1  355.08  5574.9  356.80  5620.7  352.08  5644.4  353.77  5690.9  355.12
#Mann=10,-1,0
  4697.1    0.05       0  4793.1    0.16       0  4996.8    0.07       0
  5002.8    0.16       0  5127.9    0.05       0  5243.2     0.1       0
  5343.5    0.08       0  5503.5     0.1       0  5544.1    0.08       0
  5644.4    0.16       0
Bank Sta=4996.8,5002.8
Exp/Cntr=0.3,0.1

Type RM Length L Ch R = 1,1473,140,140,140
BEGIN DESCRIPTION:
Mapping XS 1ff52f7f
END DESCRIPTION:
XS GIS Cut Line= 3
      3781436.45     10586875.57      3781071.86     10586837.37
      3780439.95     10586906.81
#Sta/Elev= 30
  4558.5  352.11  4655.0  350.34  4726.3  349.08  4757.8  346.77  4766.5  347.73
  4776.5  344.61  4806.7  341.46  4826.8  341.54  4836.9  344.45  4851.0  341.46
  4967.6  341.17  4977.7  340.05  4991.7  336.15  4994.4  335.65  4997.7  336.15
  5017.9  337.02  5038.0  341.17  5075.6  344.38  5090.8  346.92  5138.6  346.78
  5175.5  348.78  5209.0  350.27  5267.8  348.73  5299.6  350.25  5319.7  348.85
  5365.0  349.40  5399.5  353.50  5440.4  358.08  5470.6  358.77  5560.8  364.40
#Mann=8,-1,0
  4558.5    0.05       0  4655.0    0.16       0  4991.7    0.07       0
  4997.7    0.16       0  5075.6     0.1       0  5175.5    0.08       0
  5365.0    0.05       0  5399.5    0.16       0
Bank Sta=4991.7,4997.7
Exp/Cntr=0.3,0.1

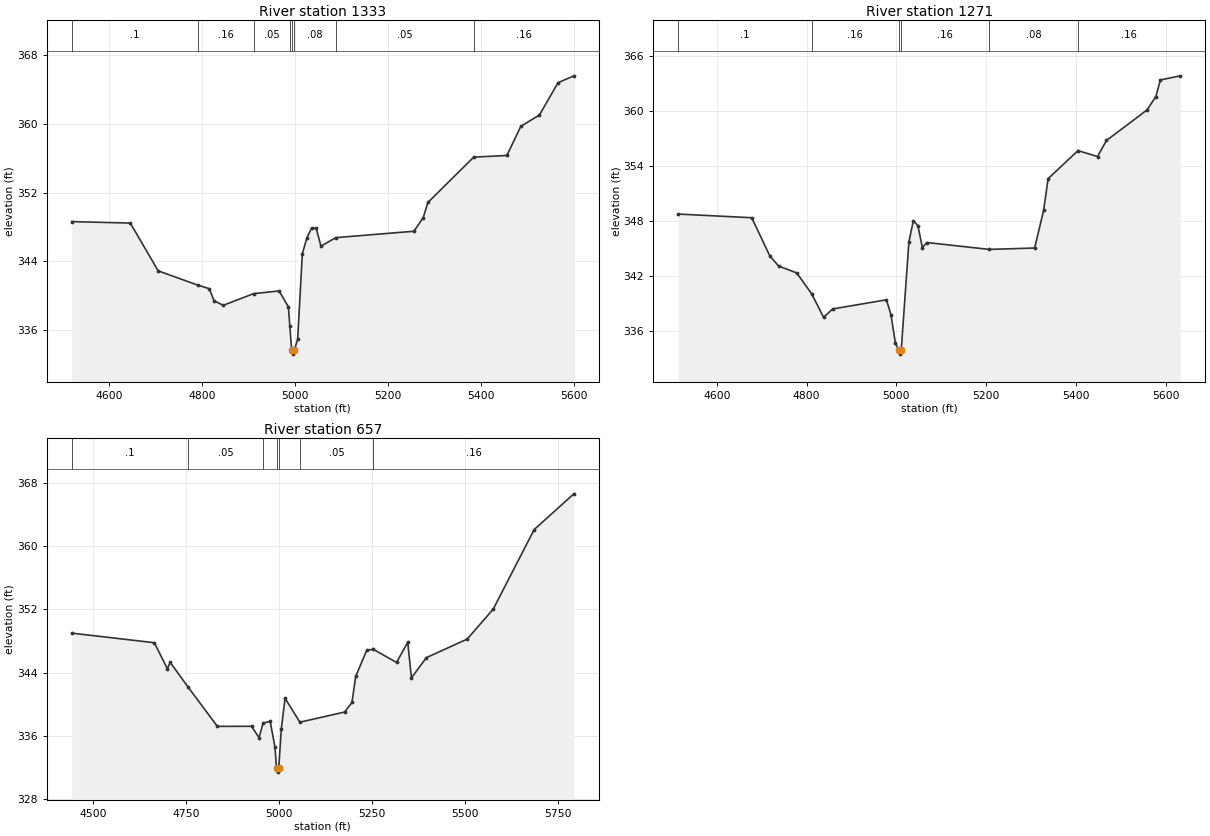
Type RM Length L Ch R = 1,1333,62,62,62
BEGIN DESCRIPTION:
Mapping XS 452deaaa
END DESCRIPTION:
XS GIS Cut Line= 2
      3781495.50     10586712.37      3780415.60     10586712.37
#Sta/Elev= 30
  4519.9  348.62  4645.8  348.45  4705.8  342.90  4791.1  341.24  4815.8  340.83
  4825.8  339.43  4845.8  338.90  4910.8  340.25  4965.8  340.57  4985.8  338.72
  4988.9  336.51  4992.8  333.73  4995.5  333.23  4998.8  333.73  5005.8  334.97
  5015.8  344.89  5025.8  346.76  5035.8  347.87  5045.8  347.84  5055.8  345.77
  5087.8  346.76  5255.8  347.50  5275.8  349.07  5285.8  350.84  5384.5  356.11
  5455.8  356.30  5485.8  359.69  5525.8  361.00  5565.8  364.75  5599.8  365.55
#Mann=8,-1,0
  4519.9     0.1       0  4791.1    0.16       0  4910.8    0.05       0
  4988.9    0.08       0  4992.8    0.07       0  4998.8    0.08       0
  5087.8    0.05       0  5384.5    0.16       0
Bank Sta=4992.8,4998.8
Exp/Cntr=0.3,0.1

Type RM Length L Ch R = 1,1271,614,614,614
BEGIN DESCRIPTION:
Mapping XS 58572d94
END DESCRIPTION:
XS GIS Cut Line= 3
      3781523.24     10586663.76      3781106.58     10586656.82
      3780405.21     10586653.34
#Sta/Elev= 30
  4514.3  348.79  4678.0  348.39  4718.0  344.25  4738.0  343.12  4778.0  342.38
  4811.2  340.12  4838.0  337.54  4858.0  338.45  4978.0  339.45  4988.0  337.83
  4998.0  334.70  5005.0  334.03  5007.7  333.53  5011.0  334.03  5028.0  345.78
  5038.0  348.08  5048.0  347.52  5058.0  345.14  5068.0  345.69  5206.7  344.94
  5308.0  345.09  5328.0  349.19  5338.0  352.65  5404.5  355.70  5448.0  355.06
  5468.0  356.81  5558.0  360.12  5578.0  361.59  5588.0  363.40  5632.4  363.85
#Mann=6,-1,0
  4514.3     0.1       0  4811.2    0.16       0  5005.0    0.07       0
  5011.0    0.16       0  5206.7    0.08       0  5404.5    0.16       0
Bank Sta=5005,5011
Exp/Cntr=0.3,0.1

Type RM Length L Ch R = 1,657,0,0,0
BEGIN DESCRIPTION:
UNT 061 IN BOCR 1.0
END DESCRIPTION:
XS GIS Cut Line= 3
      3781547.53     10586635.96      3781245.47     10586361.68
      3780302.80     10586385.94
#Sta/Elev= 30
  4441.9  349.01  4664.1  347.80  4699.2  344.50  4706.7  345.32  4753.9  342.26
  4833.7  337.23  4925.8  337.24  4945.8  335.80  4956.7  337.64  4975.8  337.87
  4988.6  334.60  4992.8  331.95  4995.6  331.45  4998.8  331.95  5005.8  336.96
  5015.8  340.78  5055.7  337.76  5175.9  339.04  5195.9  340.25  5205.9  343.54
  5235.9  346.88  5253.8  346.95  5315.9  345.31  5345.9  347.87  5355.9  343.35
  5396.0  345.91  5506.0  348.26  5576.0  352.05  5686.1  362.09  5792.9  366.61
#Mann=7,-1,0
  4441.9     0.1       0  4753.9    0.05       0  4956.7    0.16       0
  4992.8    0.07       0  4998.8    0.16       0  5055.7    0.05       0
  5253.8    0.16       0
Bank Sta=4992.8,4998.8
Exp/Cntr=0.3,0.1

Chan Stop Cuts=-1