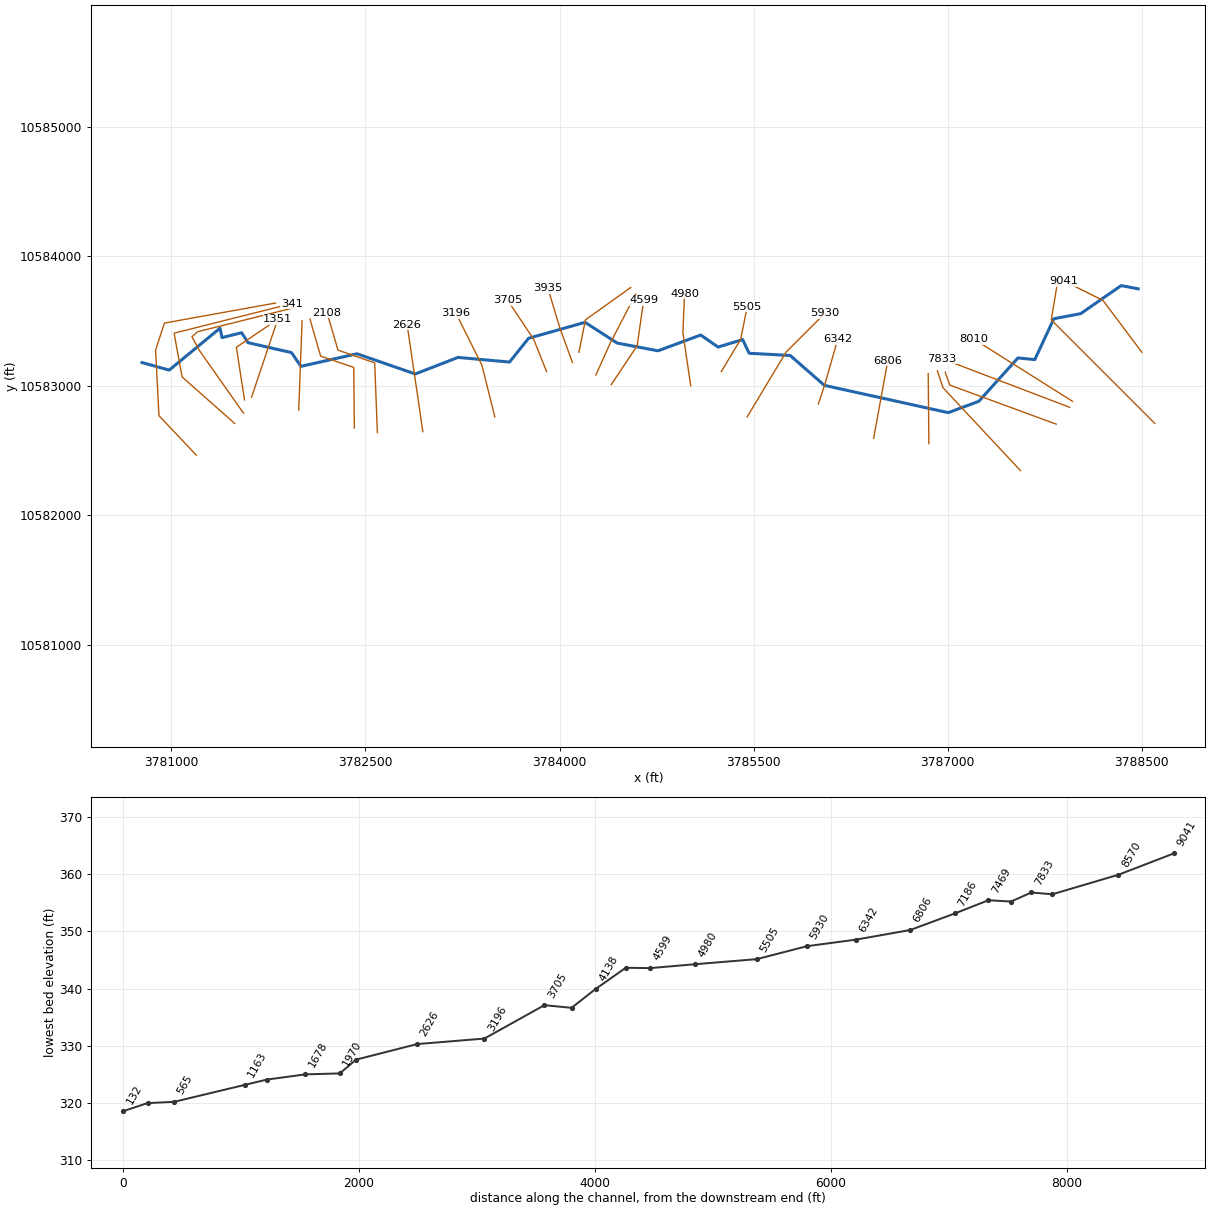
--- UNT 062 IN BOCR.prj (project) ---

Proj Title=UNT 062 IN BOCR Base Level Engineering
Current Plan=p01
Default Exp/Contr=0.3,0.1
English Units
Geom File=g01
Flow File=f01
Plan File=p01
BEGIN DESCRIPTION:
UNT 062 IN BOCR
END DESCRIPTION:

--- UNT 062 IN BOCR.p01 (plan) ---

Plan Title=Multiple Run
Short Identifier=Multiple
Geom File=g01
Flow File=f01
Subcritical Flow
K Sum by GR= 0
Std Step Tol= 0.01
Critical Tol= 0.01
Num of Std Step Trials= 20
Max Error Tol= 0.3
Flow Tol Ratio= 0.001
Split Flow NTrial= 30
Split Flow Tol= 0.02
Split Flow Ratio= 0.02
Log Output Level= 0
Friction Slope Method= 1
Unsteady Friction Slope Method= 2
Unsteady Bridges Friction Slope Method= 1
Parabolic Critical Depth
Global Vel Dist=  1 , 1 , 1
Global Log Level= 0
CheckData=True
Encroach Param= -1, 0, 0, 0
BEGIN DESCRIPTION:
Multiple Run
END DESCRIPTION:

--- UNT 062 IN BOCR.f01 (steady flow) ---

Flow Title=Multiple
Number of Profiles=7
Profile Names=10-year,25-year,50-year,1pct_min,100-year,1pct_plu,500-year
River Rch & RM= UNT 062 IN BOCR,Reach-1,9041
     881    1212    1489    1343    1817    2457    2713
River Rch & RM= UNT 062 IN BOCR,Reach-1,1678
     939    1295    1595    1442    1950    2637    2925
Boundary for River Rch & Prof#=UNT 062 IN BOCR,Reach-1,1
Up Type=0
Dn Type=3
Dn Slope=0.005
Boundary for River Rch & Prof#=UNT 062 IN BOCR,Reach-1,2
Up Type=0
Dn Type=3
Dn Slope=0.005
Boundary for River Rch & Prof#=UNT 062 IN BOCR,Reach-1,3
Up Type=0
Dn Type=3
Dn Slope=0.005
Boundary for River Rch & Prof#=UNT 062 IN BOCR,Reach-1,4
Up Type=0
Dn Type=3
Dn Slope=0.005
Boundary for River Rch & Prof#=UNT 062 IN BOCR,Reach-1,5
Up Type=0
Dn Type=3
Dn Slope=0.005
Boundary for River Rch & Prof#=UNT 062 IN BOCR,Reach-1,6
Up Type=0
Dn Type=3
Dn Slope=0.005
Boundary for River Rch & Prof#=UNT 062 IN BOCR,Reach-1,7
Up Type=0
Dn Type=3
Dn Slope=0.005

--- UNT 062 IN BOCR.g01 (geometry) ---

Geom Title=Existing Conditions

River Reach=UNT 062 IN BOCR,Reach-1
Reach XY= 30
      3788471.75     10583750.00      3788339.75     10583775.00
      3788026.75     10583558.00      3787819.75     10583519.00
      3787672.25     10583203.00      3787542.25     10583216.00
      3787240.25     10582881.00      3787003.75     10582793.00
      3786046.50     10583004.00      3785782.00     10583235.00
      3785464.75     10583252.00      3785414.50     10583358.00
      3785225.00     10583300.00      3785090.50     10583393.00
      3784760.25     10583271.00      3784445.00     10583331.00
      3784196.75     10583491.00      3783760.50     10583368.00
      3783613.00     10583184.00      3783215.00     10583220.00
      3782884.50     10583092.00      3782434.00     10583248.00
      3782001.00     10583151.00      3781928.50     10583257.00
      3781592.00     10583334.00      3781543.00     10583411.00
      3781391.00     10583373.00      3781375.75     10583446.00
      3780983.25     10583122.00      3780773.25     10583180.00

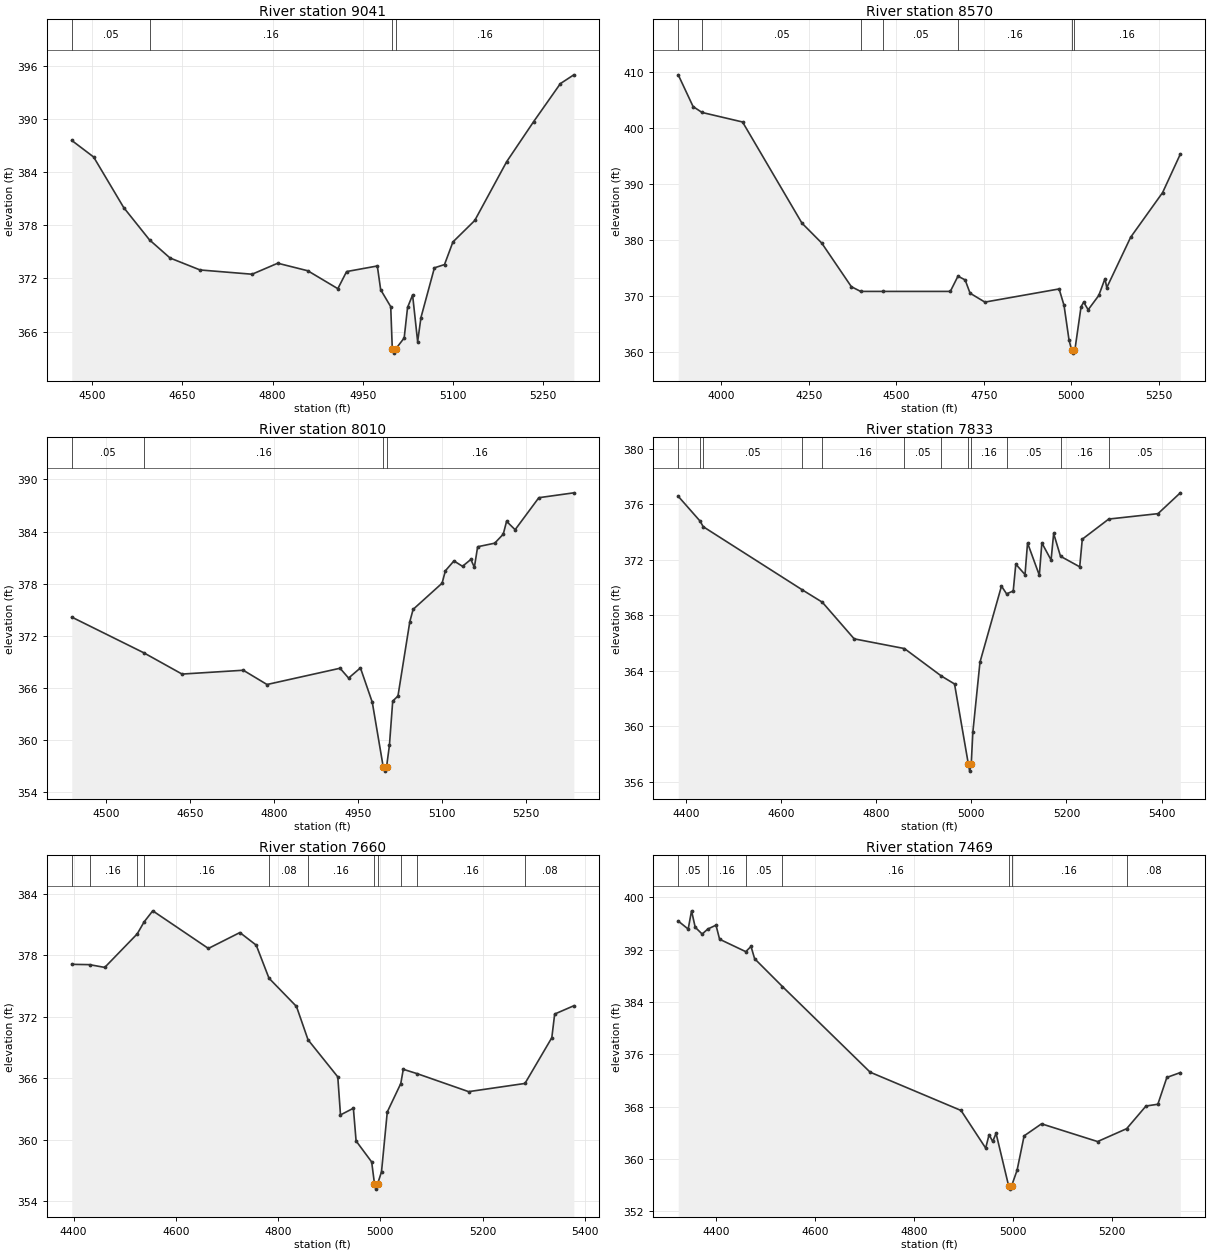
Type RM Length L Ch R = 1,9041,471,471,471
BEGIN DESCRIPTION:
UNT 062 IN BOCR 18.0
END DESCRIPTION:
XS GIS Cut Line= 3
      3788499.60     10583260.20      3788199.61     10583660.19
      3787899.61     10583810.19
#Sta/Elev= 30
  4466.0  387.57  4502.4  385.70  4552.4  380.00  4595.4  376.35  4629.5  374.31
  4679.5  372.96  4766.0  372.48  4808.7  373.72  4858.7  372.87  4908.7  370.85
  4923.3  372.78  4974.4  373.41  4980.0  370.73  4996.7  368.82  4999.3  364.08
  5002.1  363.58  5005.3  364.08  5019.1  365.29  5024.7  368.73  5033.1  370.14
  5041.5  364.87  5047.0  367.59  5069.4  373.20  5086.2  373.57  5100.2  376.12
  5136.5  378.54  5189.6  385.17  5234.3  389.67  5279.0  393.98  5301.4  394.97
#Mann=4,-1,0
  4466.0    0.05       0  4595.4    0.16       0  4999.3    0.07       0
  5005.3    0.16       0
Bank Sta=4999.3,5005.3
Exp/Cntr=0.3,0.1

Type RM Length L Ch R = 1,8570,560,560,560
BEGIN DESCRIPTION:
UNT 062 IN BOCR 17.0
END DESCRIPTION:
XS GIS Cut Line= 3
      3788599.64     10582710.16      3787799.61     10583510.19
      3787849.60     10583810.14
#Sta/Elev= 30
  3876.6  409.54  3919.1  403.87  3944.7  402.82  4060.5  401.12  4230.2  383.07
  4286.8  379.51  4371.6  371.71  4398.1  370.87  4462.0  370.87  4654.5  370.87
  4676.4  373.59  4696.9  372.92  4711.0  370.55  4753.4  368.96  4965.6  371.31
  4979.7  368.36  4993.9  362.20  5001.5  360.35  5004.2  359.85  5007.5  360.35
  5010.5  360.35  5028.3  368.13  5035.9  368.95  5048.6  367.59  5079.0  370.15
  5096.7  373.14  5101.8  371.54  5170.2  380.55  5261.5  388.52  5312.1  395.38
#Mann=7,-1,0
  3876.6    0.08       0  3944.7    0.05       0  4398.1    0.16       0
  4462.0    0.05       0  4676.4    0.16       0  5001.5    0.07       0
  5007.5    0.16       0
Bank Sta=5001.5,5007.5
Exp/Cntr=0.3,0.1

Type RM Length L Ch R = 1,8010,177,177,177
BEGIN DESCRIPTION:
Mapping XS e538df20
END DESCRIPTION:
XS GIS Cut Line= 2
      3787963.31     10582881.21      3787203.74     10583359.84
#Sta/Elev= 30
  4438.5  374.16  4566.9  370.07  4635.7  367.61  4745.2  368.05  4787.6  366.41
  4918.2  368.28  4933.5  367.15  4954.7  368.32  4975.9  364.36  4995.4  356.95
  4998.2  356.45  5001.4  356.95  5006.5  359.40  5012.4  364.50  5021.8  365.09
  5043.0  373.64  5048.9  375.05  5100.7  378.06  5106.6  379.49  5121.9  380.62
  5137.2  380.00  5152.1  380.79  5158.4  379.89  5164.3  382.25  5194.8  382.66
  5210.1  383.70  5216.0  385.17  5231.3  384.21  5273.7  387.89  5336.3  388.45
#Mann=4,-1,0
  4438.5    0.05       0  4566.9    0.16       0  4995.4    0.07       0
  5001.4    0.16       0
Bank Sta=4995.4,5001.4
Exp/Cntr=0.3,0.1

Type RM Length L Ch R = 1,7833,173,173,173
BEGIN DESCRIPTION:
UNT 062 IN BOCR 16.0
END DESCRIPTION:
XS GIS Cut Line= 2
      3787942.45     10582834.35      3786955.98     10583210.07
#Sta/Elev= 30
  4383.9  376.56  4429.9  374.77  4436.4  374.37  4644.7  369.82  4686.8  368.93
  4753.8  366.29  4859.5  365.59  4937.2  363.61  4964.8  363.04  4993.9  357.26
  4996.6  356.76  4999.9  357.26  5003.3  359.56  5018.3  364.61  5063.5  370.09
  5074.3  369.53  5088.2  369.74  5093.6  371.67  5113.0  370.92  5118.3  373.20
  5143.1  370.87  5148.4  373.20  5167.8  371.97  5173.2  373.88  5187.6  372.24
  5228.0  371.48  5233.4  373.47  5289.0  374.92  5392.6  375.31  5439.5  376.81
#Mann=12,-1,0
  4383.9    0.05       0  4429.9    0.08       0  4436.4    0.05       0
  4644.7    0.08       0  4686.8    0.16       0  4859.5    0.05       0
  4937.2    0.16       0  4993.9    0.07       0  4999.9    0.16       0
  5074.3    0.05       0  5187.6    0.16       0  5289.0    0.05       0
Bank Sta=4993.9,4999.9
Exp/Cntr=0.3,0.1

Type RM Length L Ch R = 1,7660,191,191,191
BEGIN DESCRIPTION:
UNT 062 IN BOCR 15.0
END DESCRIPTION:
XS GIS Cut Line= 3
      3787838.28     10582704.14      3787015.37     10583006.22
      3786980.02     10583105.51
#Sta/Elev= 30
  4396.6  377.11  4431.3  377.08  4461.1  376.81  4524.6  380.08  4538.1  381.25
  4555.0  382.33  4663.8  378.66  4725.4  380.21  4757.4  378.98  4782.3  375.76
  4836.1  373.00  4858.7  369.75  4916.9  366.13  4922.2  362.42  4947.4  363.07
  4952.7  359.88  4983.2  357.83  4988.7  355.68  4991.5  355.18  4994.7  355.68
  5002.4  356.87  5013.7  362.71  5040.1  365.48  5045.0  366.87  5072.4  366.44
  5172.8  364.69  5283.0  365.49  5335.5  369.95  5341.1  372.26  5378.6  373.07
#Mann=11,-1,0
  4396.6    0.05       0  4431.3    0.16       0  4524.6    0.08       0
  4538.1    0.16       0  4782.3    0.08       0  4858.7    0.16       0
  4988.7    0.07       0  4994.7    0.16       0  5040.1    0.08       0
  5072.4    0.16       0  5283.0    0.08       0
Bank Sta=4988.7,4994.7
Exp/Cntr=0.3,0.1

Type RM Length L Ch R = 1,7469,283,283,283
BEGIN DESCRIPTION:
Mapping XS a55ecd63
END DESCRIPTION:
XS GIS Cut Line= 3
      3787562.28     10582344.73      3786963.29     10582985.39
      3786919.39     10583115.95
#Sta/Elev= 30
  4324.0  396.38  4344.1  395.15  4350.9  397.94  4358.3  395.43  4372.4  394.39
  4383.6  395.15  4400.3  395.75  4407.6  393.60  4460.5  391.70  4471.1  392.50
  4478.4  390.62  4534.6  386.37  4711.9  373.28  4895.6  367.43  4945.4  361.68
  4952.3  363.73  4959.6  362.69  4966.4  363.94  4991.8  355.91  4994.5  355.41
  4997.8  355.91  5008.9  358.30  5023.1  363.55  5058.3  365.39  5171.6  362.68
  5230.4  364.65  5269.4  368.11  5293.4  368.38  5311.6  372.48  5338.8  373.22
#Mann=7,-1,0
  4324.0    0.05       0  4383.6    0.16       0  4460.5    0.05       0
  4534.6    0.16       0  4991.8    0.07       0  4997.8    0.16       0
  5230.4    0.08       0
Bank Sta=4991.8,4997.8
Exp/Cntr=0.3,0.1

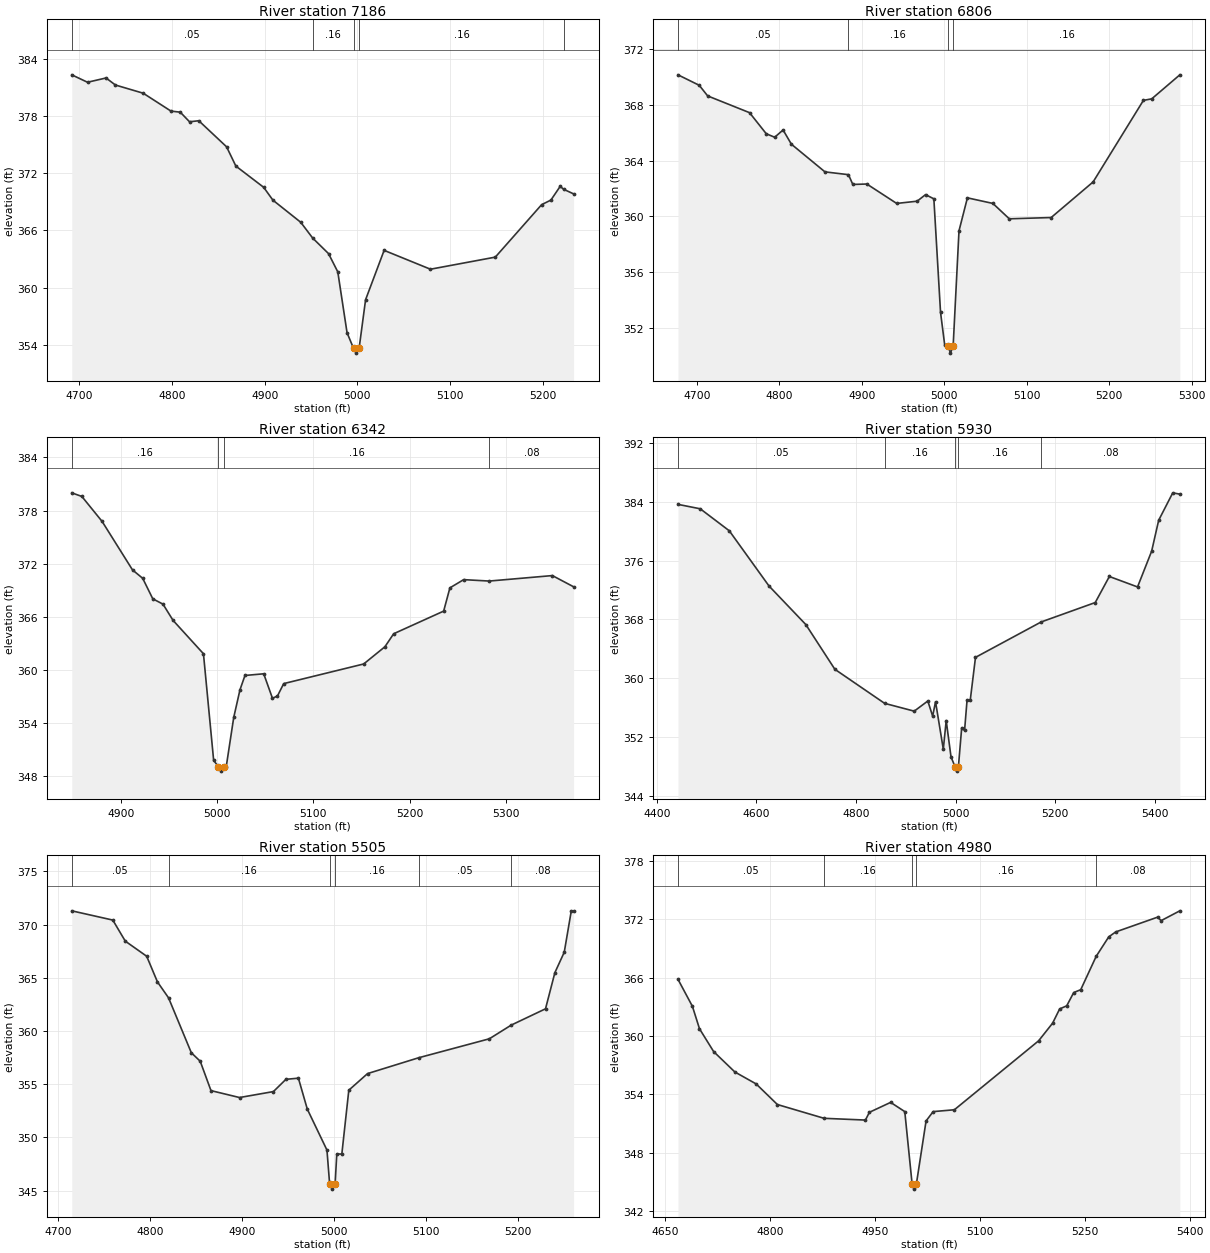
Type RM Length L Ch R = 1,7186,380,380,380
BEGIN DESCRIPTION:
UNT 062 IN BOCR 14.0
END DESCRIPTION:
XS GIS Cut Line= 2
      3786853.91     10582553.14      3786848.71     10583094.71
#Sta/Elev= 30
  4691.8  382.34  4708.8  381.56  4728.8  382.01  4738.9  381.27  4768.9  380.41
  4798.9  378.53  4808.9  378.42  4818.9  377.41  4828.9  377.52  4858.9  374.78
  4868.9  372.76  4898.9  370.53  4908.9  369.18  4938.9  366.86  4951.8  365.20
  4968.9  363.57  4978.9  361.65  4988.9  355.26  4995.9  353.62  4998.6  353.12
  5001.9  353.62  5008.9  358.73  5028.9  363.91  5078.9  361.93  5148.9  363.20
  5198.9  368.71  5208.9  369.19  5218.9  370.63  5222.7  370.32  5233.4  369.84
#Mann=5,-1,0
  4691.8    0.05       0  4951.8    0.16       0  4995.9    0.07       0
  5001.9    0.16       0  5222.7    0.08       0
Bank Sta=4995.9,5001.9
Exp/Cntr=0.3,0.1

Type RM Length L Ch R = 1,6806,464,464,464
BEGIN DESCRIPTION:
UNT 062 IN BOCR 13.0
END DESCRIPTION:
XS GIS Cut Line= 2
      3786426.84     10582594.81      3786536.20     10583193.71
#Sta/Elev= 30
  4676.9  370.14  4702.7  369.39  4712.9  368.63  4763.7  367.43  4784.0  365.92
  4794.2  365.67  4804.4  366.19  4814.5  365.17  4855.2  363.19  4883.7  362.99
  4889.0  362.29  4906.0  362.32  4942.2  360.93  4967.0  361.09  4977.2  361.56
  4987.3  361.26  4995.4  353.13  5000.5  350.77  5004.7  350.71  5007.4  350.21
  5010.7  350.71  5017.8  358.97  5028.0  361.33  5058.9  360.93  5078.8  359.83
  5129.6  359.92  5180.5  362.47  5241.5  368.31  5251.6  368.42  5285.7  370.14
#Mann=4,-1,0
  4676.9    0.05       0  4883.7    0.16       0  5004.7    0.07       0
  5010.7    0.16       0
Bank Sta=5004.7,5010.7
Exp/Cntr=0.3,0.1

Type RM Length L Ch R = 1,6342,412,412,412
BEGIN DESCRIPTION:
UNT 062 IN BOCR 12.0
END DESCRIPTION:
XS GIS Cut Line= 3
      3785999.61     10582860.19      3786049.61     10583010.19
      3786149.60     10583360.17
#Sta/Elev= 30
  4848.6  380.00  4859.1  379.59  4880.2  376.76  4911.8  371.28  4922.4  370.33
  4932.9  368.01  4943.5  367.41  4954.0  365.57  4985.6  361.80  4996.2  349.75
  5001.1  349.02  5003.8  348.52  5007.1  349.02  5009.3  349.02  5017.1  354.59
  5023.6  357.72  5028.8  359.34  5048.3  359.53  5057.4  356.76  5062.6  357.02
  5069.1  358.42  5152.3  360.64  5174.4  362.59  5183.5  364.06  5235.5  366.62
  5242.0  369.25  5256.3  370.18  5282.9  370.02  5348.6  370.64  5370.7  369.37
#Mann=4,-1,0
  4848.6    0.16       0  5001.1    0.07       0  5007.1    0.16       0
  5282.9    0.08       0
Bank Sta=5001.1,5007.1
Exp/Cntr=0.3,0.1

Type RM Length L Ch R = 1,5930,425,425,425
BEGIN DESCRIPTION:
UNT 062 IN BOCR 11.0
END DESCRIPTION:
XS GIS Cut Line= 3
      3785449.61     10582760.20      3785749.61     10583260.19
      3786049.64     10583560.22
#Sta/Elev= 30
  4442.7  383.64  4487.4  383.04  4545.7  380.05  4625.4  372.55  4699.3  367.31
  4757.6  361.23  4857.5  356.60  4916.9  355.54  4944.2  356.92  4953.9  354.86
  4959.7  356.82  4975.3  350.37  4981.1  354.26  4990.8  349.31  4999.5  347.89
  5002.2  347.39  5005.5  347.89  5012.2  353.29  5018.0  352.92  5022.9  356.99
  5029.3  356.99  5039.9  362.85  5171.7  367.66  5280.3  370.30  5308.6  373.84
  5365.2  372.42  5393.5  377.28  5407.6  381.48  5435.9  385.21  5450.1  385.03
#Mann=5,-1,0
  4442.7    0.05       0  4857.5    0.16       0  4999.5    0.07       0
  5005.5    0.16       0  5171.7    0.08       0
Bank Sta=4999.5,5005.5
Exp/Cntr=0.3,0.1

Type RM Length L Ch R = 1,5505,525,525,525
BEGIN DESCRIPTION:
UNT 062 IN BOCR 10.0
END DESCRIPTION:
XS GIS Cut Line= 3
      3785249.62     10583110.20      3785399.61     10583360.19
      3785449.61     10583610.20
#Sta/Elev= 30
  4714.6  371.29  4759.3  370.42  4772.9  368.44  4796.2  367.02  4807.9  364.61
  4820.0  363.11  4844.8  357.95  4854.5  357.15  4866.2  354.39  4897.3  353.74
  4934.2  354.30  4947.8  355.45  4961.4  355.56  4971.1  352.65  4992.5  348.80
  4995.4  345.63  4998.1  345.13  5001.4  345.63  5003.2  348.43  5008.7  348.43
  5016.3  354.43  5036.7  355.99  5092.4  357.48  5169.3  359.26  5193.2  360.55
  5230.5  362.08  5240.7  365.48  5250.9  367.40  5258.5  371.25  5261.1  371.25
#Mann=6,-1,0
  4714.6    0.05       0  4820.0    0.16       0  4995.4    0.07       0
  5001.4    0.16       0  5092.4    0.05       0  5193.2    0.08       0
Bank Sta=4995.4,5001.4
Exp/Cntr=0.3,0.1

Type RM Length L Ch R = 1,4980,381,381,381
BEGIN DESCRIPTION:
UNT 062 IN BOCR 9.0
END DESCRIPTION:
XS GIS Cut Line= 3
      3785013.53     10582999.82      3784952.76     10583412.14
      3784965.78     10583711.58
#Sta/Elev= 30
  4668.5  365.84  4689.1  363.06  4699.2  360.75  4719.4  358.40  4749.7  356.30
  4780.1  355.07  4810.4  352.95  4877.1  351.53  4936.1  351.35  4941.8  352.15
  4972.1  353.17  4992.3  352.22  5002.8  344.74  5005.5  344.24  5008.8  344.74
  5022.7  351.26  5032.8  352.22  5063.1  352.41  5183.4  359.51  5203.4  361.33
  5213.4  362.79  5223.5  363.11  5233.5  364.48  5243.5  364.77  5265.6  368.21
  5283.5  370.21  5293.5  370.72  5353.3  372.24  5358.3  371.88  5385.0  372.89
#Mann=5,-1,0
  4668.5    0.05       0  4877.1    0.16       0  5002.8    0.07       0
  5008.8    0.16       0  5265.6    0.08       0
Bank Sta=5002.8,5008.8
Exp/Cntr=0.3,0.1

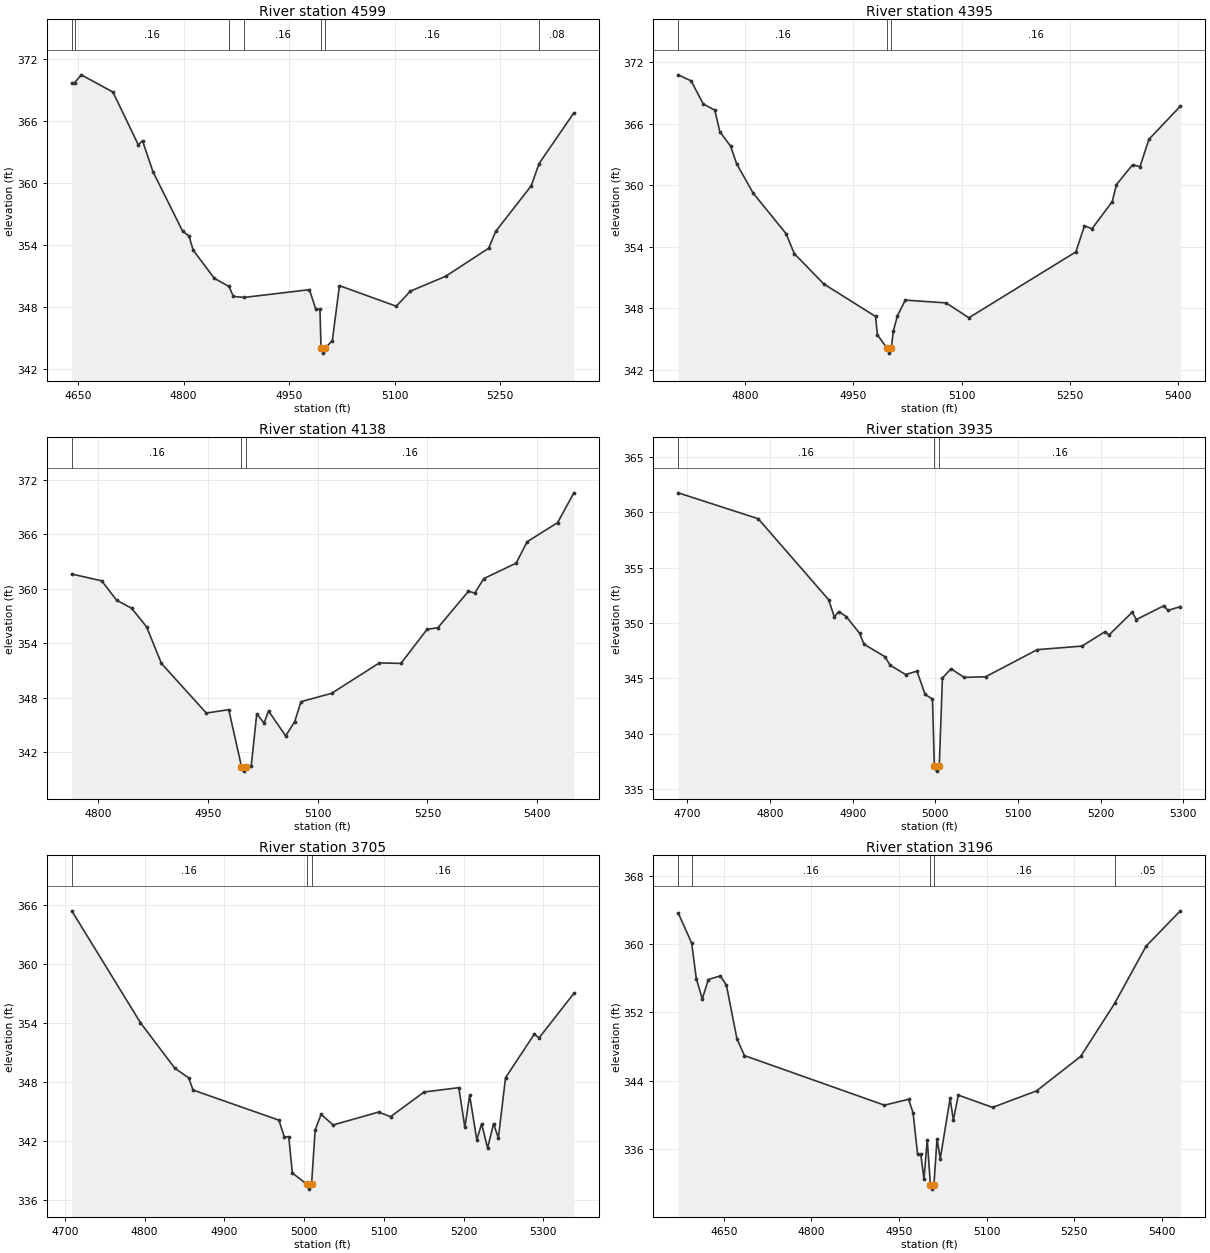
Type RM Length L Ch R = 1,4599,204,204,204
BEGIN DESCRIPTION:
UNT 062 IN BOCR 8.0
END DESCRIPTION:
XS GIS Cut Line= 3
      3784399.63     10583010.22      3784599.61     10583310.19
      3784649.61     10583660.21
#Sta/Elev= 30
  4640.9  369.68  4644.9  369.73  4654.4  370.49  4699.5  368.82  4735.5  363.72
  4741.5  364.11  4756.5  361.10  4798.6  355.36  4807.6  354.89  4813.6  353.52
  4843.7  350.80  4864.5  350.01  4870.7  349.05  4885.9  348.95  4978.9  349.70
  4987.9  347.83  4993.9  347.79  4995.4  344.06  4998.2  343.56  5001.4  344.06
  5011.5  344.77  5021.6  350.09  5102.4  348.10  5122.6  349.56  5173.1  351.01
  5233.8  353.71  5243.9  355.35  5294.4  359.75  5305.5  361.90  5355.0  366.81
#Mann=7,-1,0
  4640.9    0.05       0  4644.9    0.16       0  4864.5    0.05       0
  4885.9    0.16       0  4995.4    0.07       0  5001.4    0.16       0
  5305.5    0.08       0
Bank Sta=4995.4,5001.4
Exp/Cntr=0.3,0.1

Type RM Length L Ch R = 1,4395,257,257,257
BEGIN DESCRIPTION:
Mapping XS f9c41f0d
END DESCRIPTION:
XS GIS Cut Line= 3
      3784280.18     10583083.87      3784393.02     10583333.42
      3784588.34     10583708.87
#Sta/Elev= 30
  4706.7  370.77  4724.6  370.18  4741.4  367.93  4757.5  367.32  4764.5  365.22
  4779.5  363.81  4787.6  362.12  4810.7  359.24  4856.3  355.29  4867.9  353.33
  4908.7  350.38  4980.6  347.21  4983.3  345.40  4996.5  344.13  4999.2  343.63
  5002.5  344.13  5005.4  345.80  5011.0  347.26  5021.9  348.80  5078.4  348.53
  5110.3  347.08  5258.7  353.50  5270.7  356.04  5281.3  355.77  5309.3  358.41
  5315.1  360.06  5337.6  362.01  5347.8  361.81  5360.2  364.48  5403.8  367.71
#Mann=3,-1,0
  4706.7    0.16       0  4996.5    0.07       0  5002.5    0.16       0
Bank Sta=4996.5,5002.5
Exp/Cntr=0.3,0.1

Type RM Length L Ch R = 1,4138,203,203,203
BEGIN DESCRIPTION:
UNT 062 IN BOCR 7.0
END DESCRIPTION:
XS GIS Cut Line= 3
      3784149.60     10583260.14      3784199.61     10583510.19
      3784549.60     10583760.18
#Sta/Elev= 30
  4764.6  361.62  4805.4  360.88  4825.8  358.74  4846.2  357.86  4866.6  355.82
  4887.0  351.77  4948.2  346.31  4978.8  346.68  4996.2  340.41  4999.0  339.91
  5002.2  340.41  5009.4  340.45  5017.0  346.21  5027.0  345.21  5033.1  346.54
  5056.5  343.79  5068.8  345.36  5077.4  347.56  5119.1  348.48  5184.3  351.83
  5213.8  351.78  5249.4  355.53  5264.2  355.71  5305.9  359.73  5314.5  359.53
  5326.8  361.12  5371.1  362.83  5385.8  365.17  5427.6  367.29  5449.7  370.57
#Mann=3,-1,0
  4764.6    0.16       0  4996.2    0.07       0  5002.2    0.16       0
Bank Sta=4996.2,5002.2
Exp/Cntr=0.3,0.1

Type RM Length L Ch R = 1,3935,230,230,230
BEGIN DESCRIPTION:
Mapping XS 21392e1e
END DESCRIPTION:
XS GIS Cut Line= 3
      3784100.07     10583179.30      3784002.40     10583446.27
      3783909.29     10583755.90
#Sta/Elev= 30
  4688.8  361.76  4785.6  359.42  4870.8  352.11  4877.7  350.55  4883.0  351.04
  4892.1  350.59  4908.2  349.08  4913.6  348.09  4938.8  346.97  4945.3  346.19
  4964.0  345.35  4977.7  345.66  4987.6  343.55  4996.5  343.14  4998.7  337.13
  5001.4  336.63  5004.7  337.13  5008.5  345.03  5018.9  345.88  5034.7  345.09
  5060.7  345.15  5123.4  347.60  5177.3  347.92  5205.1  349.21  5210.3  348.94
  5238.1  350.97  5243.3  350.32  5276.4  351.56  5281.6  351.14  5296.4  351.49
#Mann=3,-1,0
  4688.8    0.16       0  4998.7    0.07       0  5004.7    0.16       0
Bank Sta=4998.7,5004.7
Exp/Cntr=0.3,0.1

Type RM Length L Ch R = 1,3705,509,509,509
BEGIN DESCRIPTION:
UNT 062 IN BOCR 6.0
END DESCRIPTION:
XS GIS Cut Line= 3
      3783899.59     10583110.23      3783799.61     10583360.19
      3783599.59     10583660.22
#Sta/Elev= 30
  4708.6  365.38  4794.7  354.02  4837.8  349.39  4855.3  348.40  4860.7  347.17
  4968.4  344.11  4975.1  342.42  4980.8  342.42  4985.3  338.74  5003.4  337.60
  5006.1  337.10  5009.4  337.60  5013.9  343.11  5021.4  344.70  5036.4  343.62
  5093.5  344.93  5108.5  344.46  5150.6  346.97  5194.1  347.41  5201.7  343.37
  5207.7  346.63  5216.7  342.11  5222.7  343.75  5230.2  341.28  5237.7  343.76
  5243.7  342.30  5252.7  348.42  5288.8  352.85  5294.8  352.47  5338.4  356.99
#Mann=3,-1,0
  4708.6    0.16       0  5003.4    0.07       0  5009.4    0.16       0
Bank Sta=5003.4,5009.4
Exp/Cntr=0.3,0.1

Type RM Length L Ch R = 1,3196,570,570,570
BEGIN DESCRIPTION:
UNT 062 IN BOCR 5.0
END DESCRIPTION:
XS GIS Cut Line= 3
      3783499.61     10582760.20      3783399.61     10583160.19
      3783199.61     10583560.18
#Sta/Elev= 30
  4572.0  363.63  4595.0  360.11  4602.9  355.95  4613.2  353.57  4623.5  355.84
  4644.1  356.26  4654.5  355.17  4672.5  348.89  4685.4  346.92  4925.0  341.11
  4966.3  341.80  4974.0  340.22  4981.7  335.39  4987.1  335.39  4992.7  332.46
  4998.3  337.06  5003.7  331.77  5006.4  331.27  5009.7  331.77  5015.0  337.14
  5020.6  334.85  5037.4  341.91  5043.0  339.36  5051.4  342.29  5110.1  340.85
  5185.5  342.79  5261.0  346.83  5319.2  353.05  5372.8  359.74  5431.5  363.89
#Mann=5,-1,0
  4572.0    0.12       0  4595.0    0.16       0  5003.7    0.07       0
  5009.7    0.16       0  5319.2    0.05       0
Bank Sta=5003.7,5009.7
Exp/Cntr=0.3,0.1

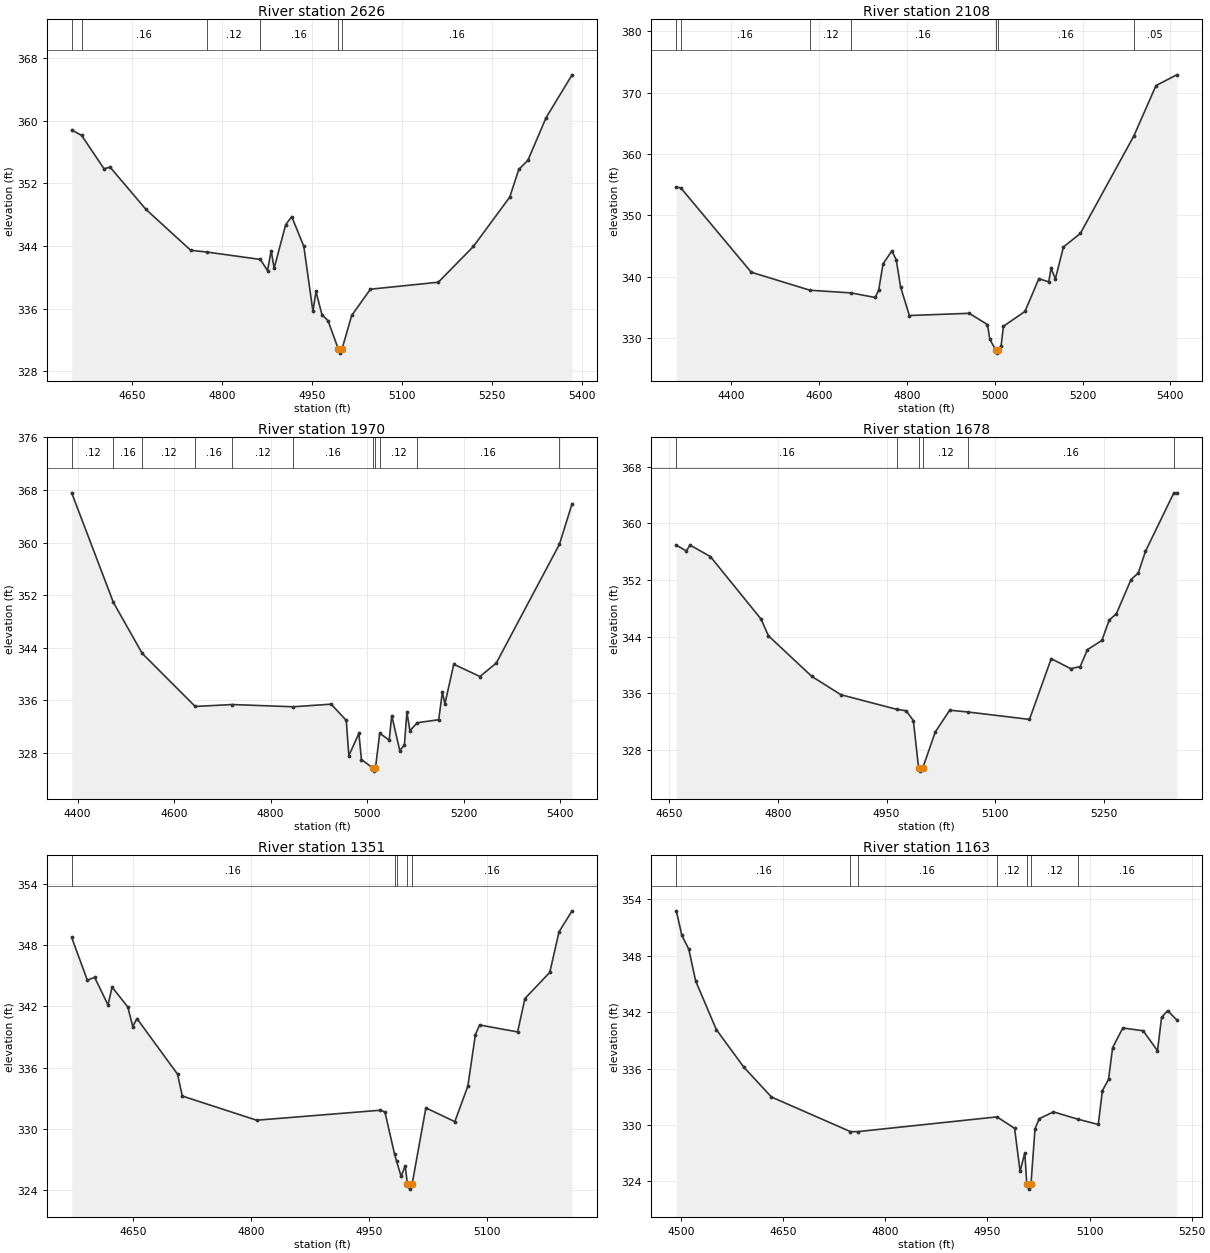
Type RM Length L Ch R = 1,2626,518,518,518
BEGIN DESCRIPTION:
Mapping XS f7938248
END DESCRIPTION:
XS GIS Cut Line= 2
      3782943.21     10582646.81      3782821.68     10583473.22
#Sta/Elev= 30
  4548.8  358.79  4565.4  358.10  4602.8  353.84  4612.9  354.05  4672.6  348.67
  4747.4  343.44  4774.7  343.21  4863.7  342.27  4875.7  340.84  4881.8  343.37
  4886.8  341.15  4906.0  346.70  4916.1  347.73  4936.3  343.94  4951.5  335.63
  4956.6  338.18  4966.6  335.21  4976.7  334.45  4994.0  330.81  4996.7  330.31
  5000.0  330.81  5016.2  335.12  5047.5  338.47  5160.8  339.36  5219.3  343.92
  5280.0  350.22  5295.2  353.77  5310.3  354.91  5340.6  360.35  5384.1  365.83
#Mann=6,-1,0
  4548.8    0.12       0  4565.4    0.16       0  4774.7    0.12       0
  4863.7    0.16       0  4994.0    0.07       0  5000.0    0.16       0
Bank Sta=4994,5000
Exp/Cntr=0.3,0.1

Type RM Length L Ch R = 1,2108,138,138,138
BEGIN DESCRIPTION:
UNT 062 IN BOCR 4.0
END DESCRIPTION:
XS GIS Cut Line= 4
      3782591.65     10582639.56      3782571.25     10583177.55
      3782287.40     10583276.51      3782202.81     10583565.40
#Sta/Elev= 30
  4274.5  354.62  4284.8  354.48  4445.2  340.76  4578.8  337.83  4672.4  337.39
  4727.3  336.65  4735.5  337.82  4745.5  342.13  4765.5  344.22  4775.5  342.80
  4785.5  338.34  4805.5  333.71  4941.7  334.07  4983.4  332.24  4988.7  329.86
  5002.2  328.09  5005.0  327.59  5008.2  328.09  5014.4  328.75  5019.7  331.96
  5068.8  334.37  5100.5  339.71  5123.0  339.18  5128.2  341.38  5138.2  339.70
  5156.4  344.86  5195.0  347.07  5316.9  362.94  5367.3  371.13  5414.5  372.88
#Mann=7,-1,0
  4274.5    0.12       0  4284.8    0.16       0  4578.8    0.12       0
  4672.4    0.16       0  5002.2    0.07       0  5008.2    0.16       0
  5316.9    0.05       0
Bank Sta=5002.2,5008.2
Exp/Cntr=0.3,0.1

Type RM Length L Ch R = 1,1970,292,292,292
BEGIN DESCRIPTION:
UNT 062 IN BOCR 3.0
END DESCRIPTION:
XS GIS Cut Line= 4
      3782413.70     10582674.27      3782409.36     10583143.04
      3782153.28     10583229.85      3782070.98     10583515.75
#Sta/Elev= 30
  4387.9  367.57  4474.3  350.88  4533.9  343.13  4643.8  335.04  4720.4  335.33
  4847.0  334.99  4925.4  335.39  4956.8  332.91  4962.1  327.54  4982.9  330.94
  4988.2  326.96  5011.3  325.69  5014.1  325.19  5017.3  325.69  5026.1  330.96
  5045.7  329.91  5051.0  333.65  5067.6  328.33  5077.2  329.17  5082.4  334.14
  5088.7  331.35  5103.9  332.56  5148.3  333.02  5155.9  337.23  5161.1  335.43
  5179.5  341.47  5233.7  339.60  5267.4  341.63  5398.4  359.74  5424.6  365.91
#Mann=11,-1,0
  4387.9    0.12       0  4474.3    0.16       0  4533.9    0.12       0
  4643.8    0.16       0  4720.4    0.12       0  4847.0    0.16       0
  5011.3    0.07       0  5017.3    0.16       0  5026.1    0.12       0
  5103.9    0.16       0  5398.4    0.05       0
Bank Sta=5011.3,5017.3
Exp/Cntr=0.3,0.1

Type RM Length L Ch R = 1,1678,327,327,327
BEGIN DESCRIPTION:
UNT 062 IN BOCR 2.0
END DESCRIPTION:
XS GIS Cut Line= 2
      3781984.01     10582813.17      3782010.05     10583503.28
#Sta/Elev= 30
  4659.9  356.91  4673.8  356.08  4678.8  356.92  4706.9  355.30  4777.0  346.46
  4787.0  344.12  4847.0  338.38  4887.1  335.80  4964.4  333.73  4977.1  333.54
  4987.1  332.15  4994.2  325.52  4996.9  325.02  5000.2  325.52  5017.2  330.52
  5037.2  333.62  5062.7  333.36  5147.3  332.32  5177.3  340.89  5204.2  339.48
  5217.3  339.77  5227.3  342.16  5247.3  343.47  5257.3  346.33  5267.3  347.24
  5287.4  352.05  5297.4  352.97  5307.4  356.04  5346.3  364.23  5350.5  364.29
#Mann=6,-1,0
  4659.9    0.16       0  4964.4    0.12       0  4994.2    0.07       0
  5000.2    0.12       0  5062.7    0.16       0  5346.3    0.05       0
Bank Sta=4994.2,5000.2
Exp/Cntr=0.3,0.1

Type RM Length L Ch R = 1,1351,188,188,188
BEGIN DESCRIPTION:
Mapping XS 654178a3
END DESCRIPTION:
XS GIS Cut Line= 2
      3781619.54     10582912.48      3781822.41     10583515.89
#Sta/Elev= 30
  4571.8  348.76  4591.7  344.58  4601.0  344.85  4618.0  342.16  4623.2  343.90
  4643.2  341.95  4649.5  340.03  4654.8  340.82  4706.5  335.37  4712.5  333.23
  4807.1  330.86  4964.6  331.84  4970.3  331.67  4982.5  327.55  4985.1  326.87
  4990.9  325.35  4996.1  326.41  4998.9  324.61  5001.7  324.11  5004.9  324.61
  5022.4  332.07  5059.2  330.72  5075.8  334.20  5085.4  339.25  5090.7  340.19
  5139.1  339.51  5148.4  342.78  5180.0  345.34  5191.8  349.32  5208.4  351.37
#Mann=5,-1,0
  4571.8    0.16       0  4982.5    0.12       0  4985.1    0.16       0
  4998.9    0.07       0  5004.9    0.16       0
Bank Sta=4998.9,5004.9
Exp/Cntr=0.3,0.1

Type RM Length L Ch R = 1,1163,598,598,598
BEGIN DESCRIPTION:
Mapping XS e8aba2ed
END DESCRIPTION:
XS GIS Cut Line= 3
      3781564.99     10582892.09      3781502.17     10583298.51
      3781770.08     10583479.58
#Sta/Elev= 30
  4493.4  352.76  4501.6  350.14  4511.7  348.69  4521.8  345.31  4552.2  340.13
  4592.7  336.13  4633.1  332.97  4749.1  329.29  4759.4  329.29  4964.2  330.86
  4990.0  329.64  4998.1  325.06  5005.0  327.04  5008.0  323.68  5010.8  323.18
  5014.0  323.68  5020.0  329.59  5026.0  330.66  5047.0  331.39  5083.1  330.61
  5112.9  330.05  5118.9  333.65  5127.9  334.84  5133.9  338.21  5148.9  340.31
  5178.8  340.01  5199.8  337.89  5205.8  341.44  5214.7  342.15  5228.0  341.17
#Mann=7,-1,0
  4493.4    0.16       0  4749.1    0.12       0  4759.4    0.16       0
  4964.2    0.12       0  5008.0    0.07       0  5014.0    0.12       0
  5083.1    0.16       0
Bank Sta=5008,5014
Exp/Cntr=0.3,0.1

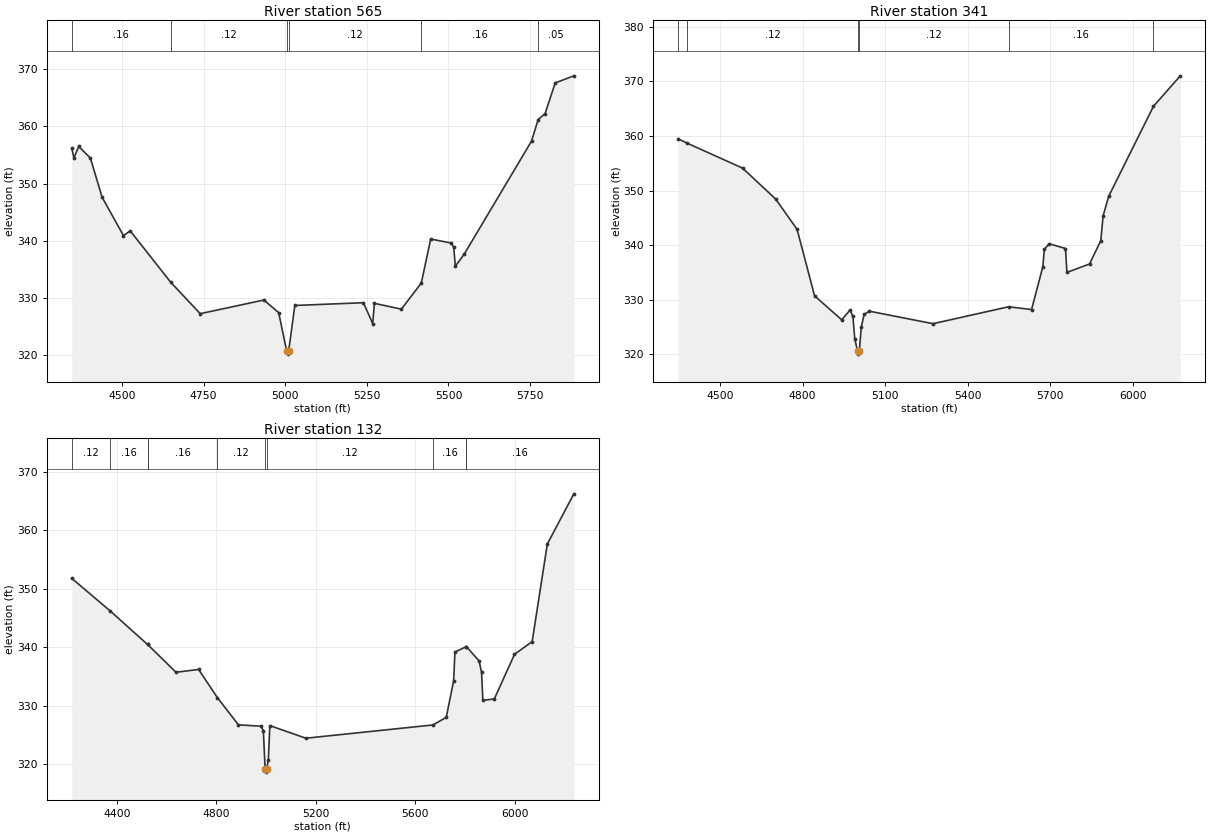
Type RM Length L Ch R = 1,565,224,224,224
BEGIN DESCRIPTION:
Mapping XS 65f524af
END DESCRIPTION:
XS GIS Cut Line= 5
      3781557.59     10582788.63      3781215.82     10583274.50
      3781158.55     10583379.80      3781202.89     10583418.60
      3781945.05     10583603.22
#Sta/Elev= 30
  4346.4  356.16  4353.0  354.46  4367.8  356.47  4403.5  354.43  4439.2  347.62
  4504.6  340.92  4525.5  341.73  4649.9  332.74  4739.8  327.29  4934.7  329.67
  4980.1  327.47  5004.6  320.73  5007.4  320.23  5010.6  320.73  5029.5  328.72
  5239.5  329.20  5268.0  325.57  5273.2  329.09  5355.8  328.08  5416.9  332.64
  5445.6  340.31  5507.4  339.63  5516.0  338.92  5521.1  335.56  5548.6  337.71
  5754.7  357.43  5774.5  361.14  5796.0  362.21  5826.9  367.55  5884.0  368.79
#Mann=6,-1,0
  4346.4    0.16       0  4649.9    0.12       0  5004.6    0.07       0
  5010.6    0.12       0  5416.9    0.16       0  5774.5    0.05       0
Bank Sta=5004.6,5010.6
Exp/Cntr=0.3,0.1

Type RM Length L Ch R = 1,341,209,209,209
BEGIN DESCRIPTION:
UNT 062 IN BOCR 1.0
END DESCRIPTION:
XS GIS Cut Line= 4
      3781489.31     10582709.36      3781083.08     10583068.72
      3781020.58     10583407.26      3781932.08     10583636.44
#Sta/Elev= 30
  4347.3  359.47  4380.5  358.66  4581.5  354.10  4702.0  348.42  4779.7  342.88
  4843.3  330.69  4942.0  326.30  4972.5  328.10  4982.7  326.91  4989.6  322.76
  5000.0  320.51  5002.8  320.01  5006.0  320.51  5013.2  324.96  5023.4  327.28
  5042.6  327.88  5274.2  325.59  5549.1  328.69  5632.7  328.18  5673.8  336.07
  5679.0  339.22  5696.9  340.24  5756.1  339.37  5761.3  334.99  5843.5  336.53
  5884.6  340.82  5892.8  345.33  5913.5  348.97  6076.2  365.44  6173.8  371.02
#Mann=6,-1,0
  4347.3    0.16       0  4380.5    0.12       0  5000.0    0.07       0
  5006.0    0.12       0  5549.1    0.16       0  6076.2    0.05       0
Bank Sta=5000,5006
Exp/Cntr=0.3,0.1

Type RM Length L Ch R = 1,132,0,0,0
BEGIN DESCRIPTION:
Mapping XS 9963cb87
END DESCRIPTION:
XS GIS Cut Line= 5
      3781192.32     10582465.02      3780903.82     10582769.94
      3780878.01     10583276.59      3780946.04     10583485.36
      3781804.54     10583640.17
#Sta/Elev= 30
  4218.7  351.79  4373.6  346.19  4523.3  340.46  4523.6  340.46  4637.9  335.70
  4728.8  336.18  4804.0  331.37  4889.0  326.69  4979.2  326.46  4989.2  325.71
  4996.2  319.09  4998.9  318.59  5002.2  319.09  5009.2  320.71  5015.2  326.56
  5160.1  324.40  5671.0  326.67  5724.6  327.97  5754.4  334.26  5759.5  339.15
  5804.8  340.09  5805.8  340.08  5856.7  337.64  5866.7  335.66  5871.8  330.89
  5917.7  331.12  5999.0  338.76  6070.1  340.96  6131.1  357.67  6237.7  366.27
#Mann=10,-1,0
  4218.7    0.12       0  4373.6    0.16       0  4523.3    0.12       0
  4523.6    0.16       0  4804.0    0.12       0  4996.2    0.07       0
  5002.2    0.12       0  5671.0    0.16       0  5804.8    0.05       0
  5805.8    0.16       0
Bank Sta=4996.2,5002.2
Exp/Cntr=0.3,0.1

Chan Stop Cuts=-1