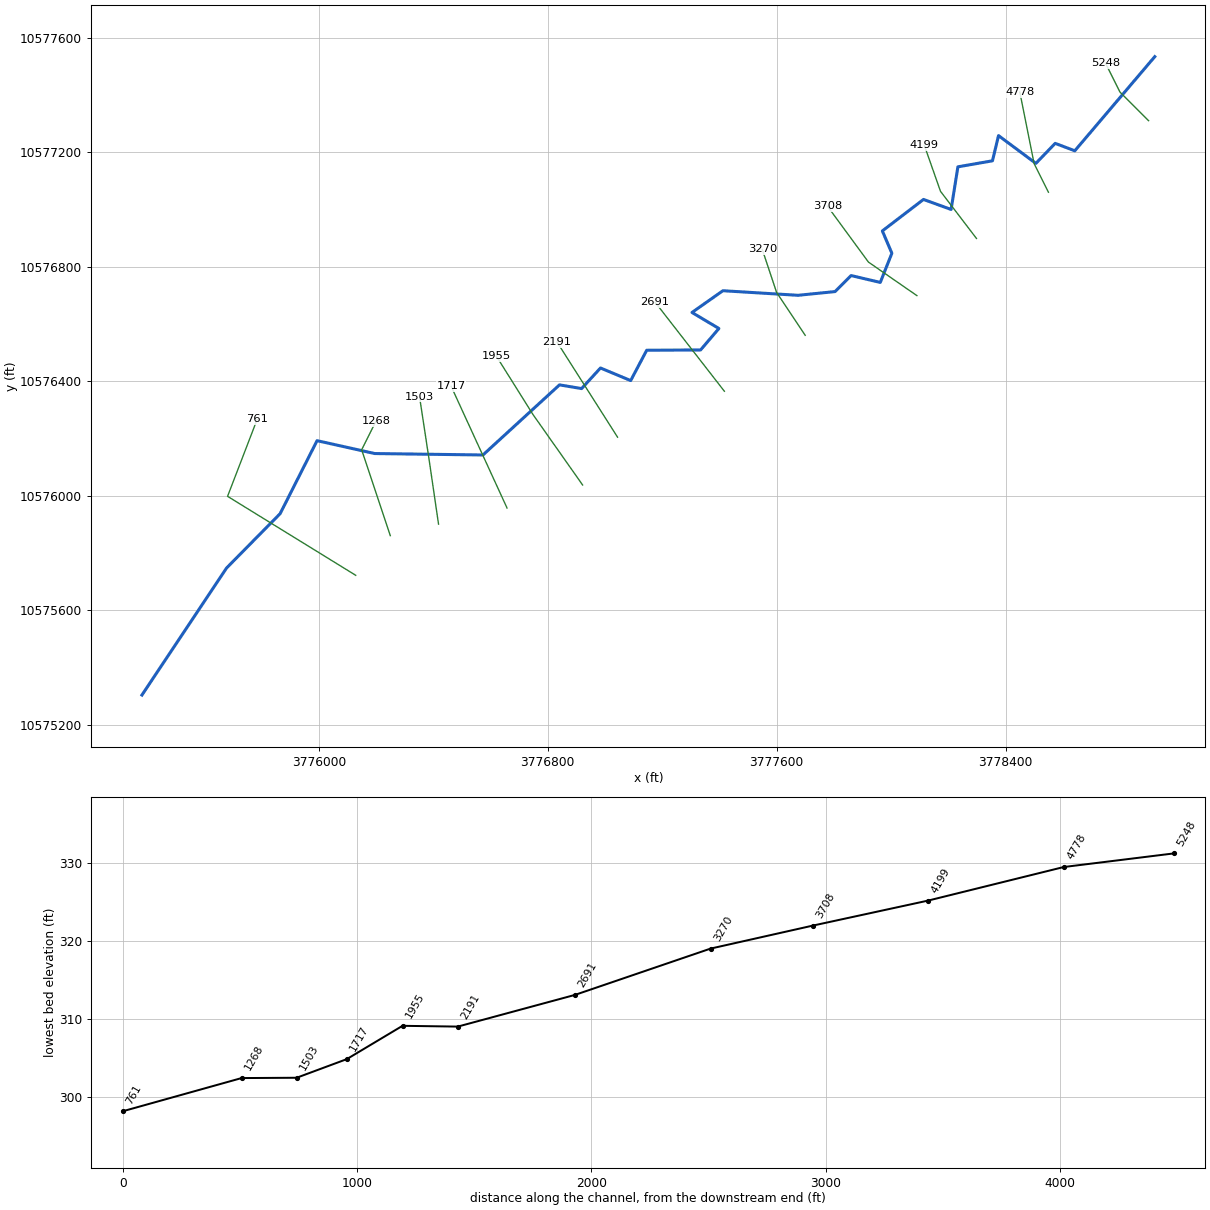
--- UNT 063 IN BOCR.prj (project) ---

Proj Title=UNT 063 IN BOCR Base Level Engineering
Current Plan=p01
Default Exp/Contr=0.3,0.1
English Units
Geom File=g01
Flow File=f01
Plan File=p01
BEGIN DESCRIPTION:
UNT 063 IN BOCR
END DESCRIPTION:

--- UNT 063 IN BOCR.p01 (plan) ---

Plan Title=Multiple Run
Short Identifier=Multiple
Geom File=g01
Flow File=f01
Subcritical Flow
K Sum by GR= 0
Std Step Tol= 0.01
Critical Tol= 0.01
Num of Std Step Trials= 20
Max Error Tol= 0.3
Flow Tol Ratio= 0.001
Split Flow NTrial= 30
Split Flow Tol= 0.02
Split Flow Ratio= 0.02
Log Output Level= 0
Friction Slope Method= 1
Unsteady Friction Slope Method= 2
Unsteady Bridges Friction Slope Method= 1
Parabolic Critical Depth
Global Vel Dist=  1 , 1 , 1
Global Log Level= 0
CheckData=True
Encroach Param= -1, 0, 0, 0
BEGIN DESCRIPTION:
Multiple Run
END DESCRIPTION:

--- UNT 063 IN BOCR.f01 (steady flow) ---

Flow Title=Multiple
Number of Profiles=7
Profile Names=10-year,25-year,50-year,1pct_min,100-year,1pct_plu,500-year
River Rch & RM= UNT 063 IN BOCR,Reach-1,5248
     298     384     452     392     530     717     730
Boundary for River Rch & Prof#=UNT 063 IN BOCR,Reach-1,1
Up Type=0
Dn Type=3
Dn Slope=0.005
Boundary for River Rch & Prof#=UNT 063 IN BOCR,Reach-1,2
Up Type=0
Dn Type=3
Dn Slope=0.005
Boundary for River Rch & Prof#=UNT 063 IN BOCR,Reach-1,3
Up Type=0
Dn Type=3
Dn Slope=0.005
Boundary for River Rch & Prof#=UNT 063 IN BOCR,Reach-1,4
Up Type=0
Dn Type=3
Dn Slope=0.005
Boundary for River Rch & Prof#=UNT 063 IN BOCR,Reach-1,5
Up Type=0
Dn Type=3
Dn Slope=0.005
Boundary for River Rch & Prof#=UNT 063 IN BOCR,Reach-1,6
Up Type=0
Dn Type=3
Dn Slope=0.005
Boundary for River Rch & Prof#=UNT 063 IN BOCR,Reach-1,7
Up Type=0
Dn Type=3
Dn Slope=0.005

--- UNT 063 IN BOCR.g01 (geometry) ---

Geom Title=Existing Conditions

River Reach=UNT 063 IN BOCR,Reach-1
Reach XY= 30
      3778921.25     10577534.00      3778641.75     10577205.00
      3778573.25     10577231.00      3778505.75     10577161.00
      3778375.25     10577258.00      3778354.00     10577170.00
      3778233.25     10577149.00      3778209.50     10577000.00
      3778113.00     10577035.00      3777969.25     10576925.00
      3778002.50     10576847.00      3777962.00     10576745.00
      3777860.00     10576769.00      3777804.00     10576713.00
      3777674.50     10576700.00      3777412.00     10576716.00
      3777304.00     10576640.00      3777398.00     10576584.00
      3777334.00     10576509.00      3777145.75     10576508.00
      3777089.75     10576402.00      3776984.25     10576446.00
      3776918.25     10576374.00      3776841.00     10576387.00
      3776573.50     10576142.00      3776195.50     10576147.00
      3775993.75     10576192.00      3775864.75     10575937.00
      3775677.50     10575747.00      3775381.75     10575303.00

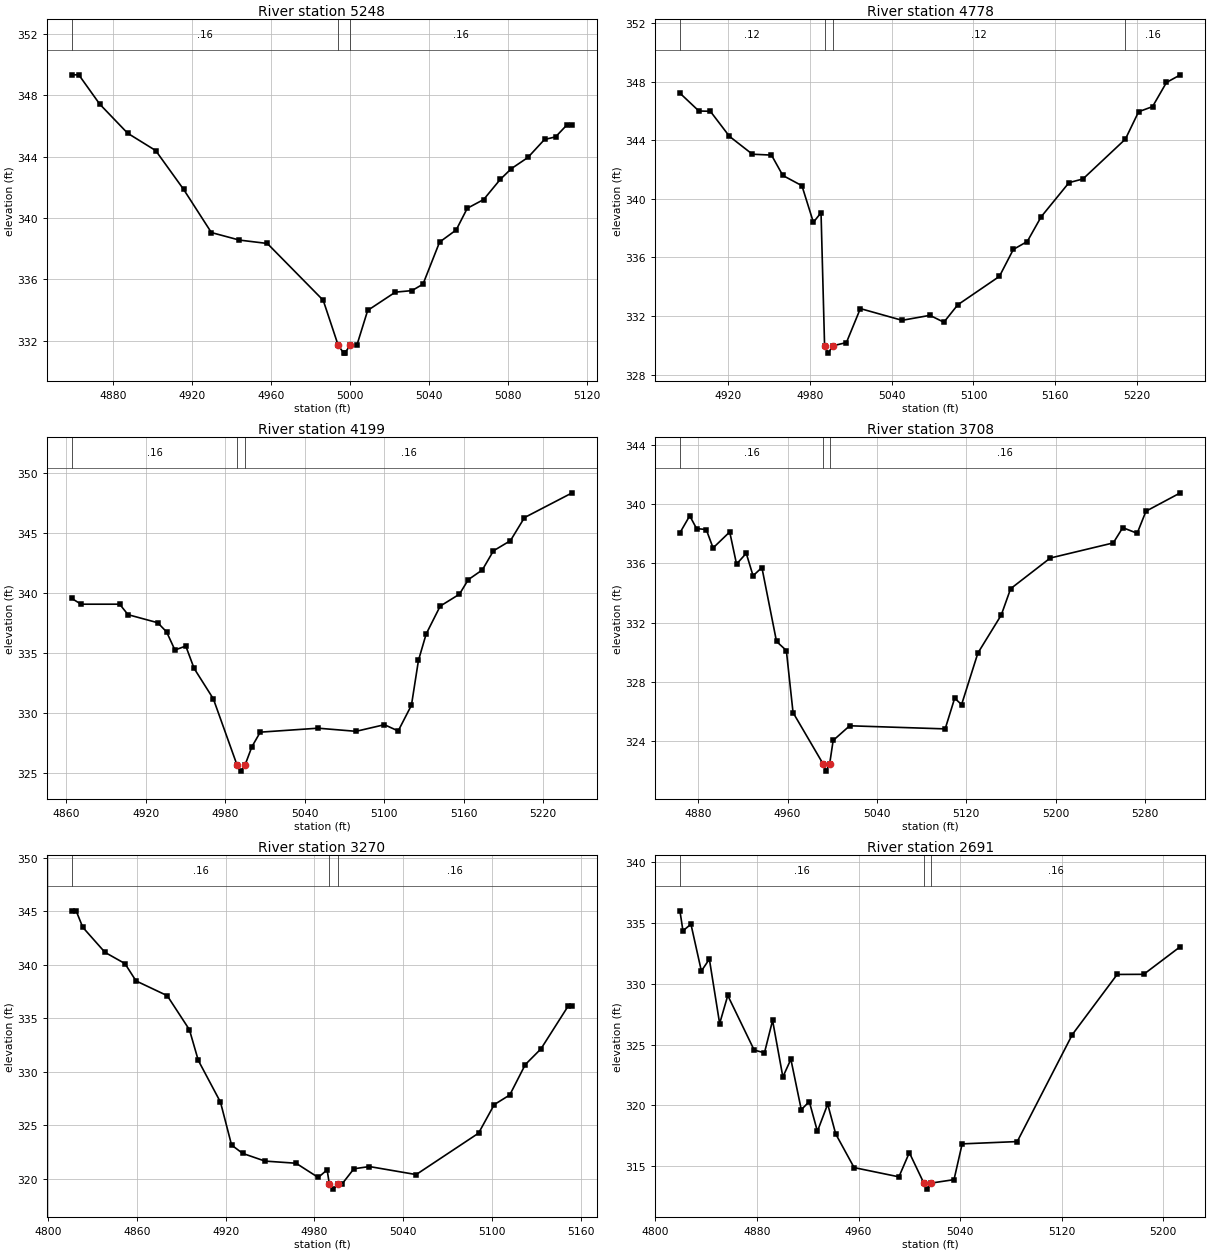
Type RM Length L Ch R = 1,5248,470,470,470
BEGIN DESCRIPTION:
UNT 063 IN BOCR 10.0
END DESCRIPTION:
XS GIS Cut Line= 3
      3778899.63     10577310.16      3778799.61     10577410.19
      3778749.59     10577510.22
#Sta/Elev= 30
  4859.2  349.32  4862.8  349.32  4873.4  347.41  4887.5  345.52  4901.7  344.39
  4915.8  341.87  4929.9  339.05  4944.1  338.56  4958.2  338.34  4986.5  334.64
  4994.1  331.70  4996.9  331.20  4997.4  331.20  5000.1  331.70  5003.5  331.70
  5009.0  333.98  5023.0  335.17  5031.4  335.27  5037.0  335.69  5045.4  338.43
  5053.8  339.22  5059.4  340.63  5067.7  341.20  5076.1  342.51  5081.7  343.21
  5090.1  343.94  5098.5  345.11  5104.1  345.28  5109.7  346.04  5112.5  346.04
#Mann=3,-1,0
  4859.2    0.16       0  4994.1    0.07       0  5000.1    0.16       0
Bank Sta=4994.1,5000.1
Exp/Cntr=0.3,0.1

Type RM Length L Ch R = 1,4778,579,579,579
BEGIN DESCRIPTION:
UNT 063 IN BOCR 9.0
END DESCRIPTION:
XS GIS Cut Line= 3
      3778549.60     10577060.22      3778499.61     10577160.19
      3778449.61     10577410.17
#Sta/Elev= 30
  4884.9  347.21  4898.8  345.99  4907.2  345.97  4921.2  344.26  4938.0  343.04
  4952.0  342.98  4960.3  341.59  4974.3  340.89  4982.7  338.39  4988.3  339.05
  4990.9  329.96  4993.6  329.46  4996.9  329.96  5006.9  330.18  5017.1  332.50
  5047.7  331.70  5068.1  332.04  5078.3  331.57  5088.5  332.76  5119.0  334.70
  5129.2  336.54  5139.4  337.08  5149.6  338.77  5170.0  341.10  5180.2  341.35
  5211.3  344.07  5221.0  345.94  5231.2  346.29  5241.4  347.94  5251.6  348.46
#Mann=4,-1,0
  4884.9    0.12       0  4990.9    0.07       0  4996.9    0.12       0
  5211.3    0.16       0
Bank Sta=4990.9,4996.9
Exp/Cntr=0.3,0.1

Type RM Length L Ch R = 1,4199,491,491,491
BEGIN DESCRIPTION:
UNT 063 IN BOCR 8.0
END DESCRIPTION:
XS GIS Cut Line= 3
      3778298.23     10576898.57      3778172.38     10577063.49
      3778115.94     10577224.11
#Sta/Elev= 30
  4864.2  339.53  4871.3  339.05  4900.4  339.05  4906.7  338.18  4929.1  337.51
  4935.8  336.75  4942.1  335.24  4950.3  335.57  4956.6  333.71  4971.1  331.18
  4989.0  325.67  4991.8  325.17  4995.0  325.67  5000.2  327.20  5006.5  328.41
  5050.1  328.74  5078.8  328.48  5100.2  329.03  5110.6  328.51  5120.6  330.65
  5125.9  334.38  5131.7  336.57  5142.3  338.89  5156.8  339.88  5163.5  341.09
  5174.1  341.90  5182.5  343.49  5195.3  344.33  5205.9  346.25  5241.9  348.31
#Mann=3,-1,0
  4864.2    0.16       0  4989.0    0.07       0  4995.0    0.16       0
Bank Sta=4989,4995
Exp/Cntr=0.3,0.1

Type RM Length L Ch R = 1,3708,438,438,438
BEGIN DESCRIPTION:
UNT 063 IN BOCR 7.0
END DESCRIPTION:
XS GIS Cut Line= 3
      3778089.93     10576698.89      3777920.64     10576816.09
      3777777.42     10577011.40
#Sta/Elev= 30
  4863.6  338.06  4872.4  339.21  4878.5  338.35  4887.2  338.28  4893.3  337.04
  4908.2  338.12  4914.3  335.95  4923.0  336.68  4929.1  335.16  4937.0  335.72
  4950.1  330.73  4958.9  330.12  4964.9  325.93  4991.7  322.48  4994.4  321.98
  4997.7  322.48  5000.8  324.05  5015.6  325.04  5101.1  324.83  5109.6  326.90
  5115.8  326.47  5130.4  329.95  5151.3  332.51  5159.7  334.29  5195.2  336.36
  5251.6  337.38  5260.1  338.41  5273.0  338.03  5280.9  339.52  5311.7  340.76
#Mann=3,-1,0
  4863.6    0.16       0  4991.7    0.07       0  4997.7    0.16       0
Bank Sta=4991.7,4997.7
Exp/Cntr=0.3,0.1

Type RM Length L Ch R = 1,3270,579,579,579
BEGIN DESCRIPTION:
UNT 063 IN BOCR 6.0
END DESCRIPTION:
XS GIS Cut Line= 3
      3777699.59     10576560.22      3777599.61     10576710.19
      3777549.60     10576860.23
#Sta/Elev= 30
  4815.9  345.04  4818.9  345.04  4823.4  343.50  4838.4  341.16  4851.9  340.11
  4859.4  338.49  4880.5  337.11  4895.5  333.93  4901.5  331.06  4916.5  327.16
  4924.0  323.15  4931.5  322.37  4946.6  321.65  4967.6  321.45  4982.6  320.12
  4988.6  320.83  4990.1  319.53  4992.9  319.03  4996.1  319.53  4998.8  319.53
  5006.7  320.93  5017.2  321.14  5048.8  320.39  5091.0  324.26  5101.6  326.93
  5112.1  327.83  5122.6  330.67  5133.2  332.14  5151.6  336.14  5154.3  336.14
#Mann=3,-1,0
  4815.9    0.16       0  4990.1    0.07       0  4996.1    0.16       0
Bank Sta=4990.1,4996.1
Exp/Cntr=0.3,0.1

Type RM Length L Ch R = 1,2691,500,500,500
BEGIN DESCRIPTION:
UNT 063 IN BOCR 5.0
END DESCRIPTION:
XS GIS Cut Line= 2
      3777417.17     10576364.71      3777175.15     10576675.87
#Sta/Elev= 30
  4819.3  335.99  4821.7  334.35  4828.0  334.89  4836.2  331.04  4842.5  332.02
  4850.6  326.72  4857.0  329.03  4877.8  324.54  4885.9  324.32  4892.3  326.98
  4900.4  322.33  4906.7  323.79  4914.9  319.64  4921.2  320.31  4927.6  317.86
  4935.7  320.10  4942.0  317.65  4956.5  314.88  4991.8  314.12  5000.0  316.11
  5011.4  313.61  5014.2  313.11  5017.4  313.61  5035.2  313.89  5041.6  316.83
  5085.0  317.02  5128.4  325.82  5163.7  330.76  5184.6  330.77  5213.5  333.05
#Mann=3,-1,0
  4819.3    0.16       0  5011.4    0.07       0  5017.4    0.16       0
Bank Sta=5011.4,5017.4
Exp/Cntr=0.3,0.1

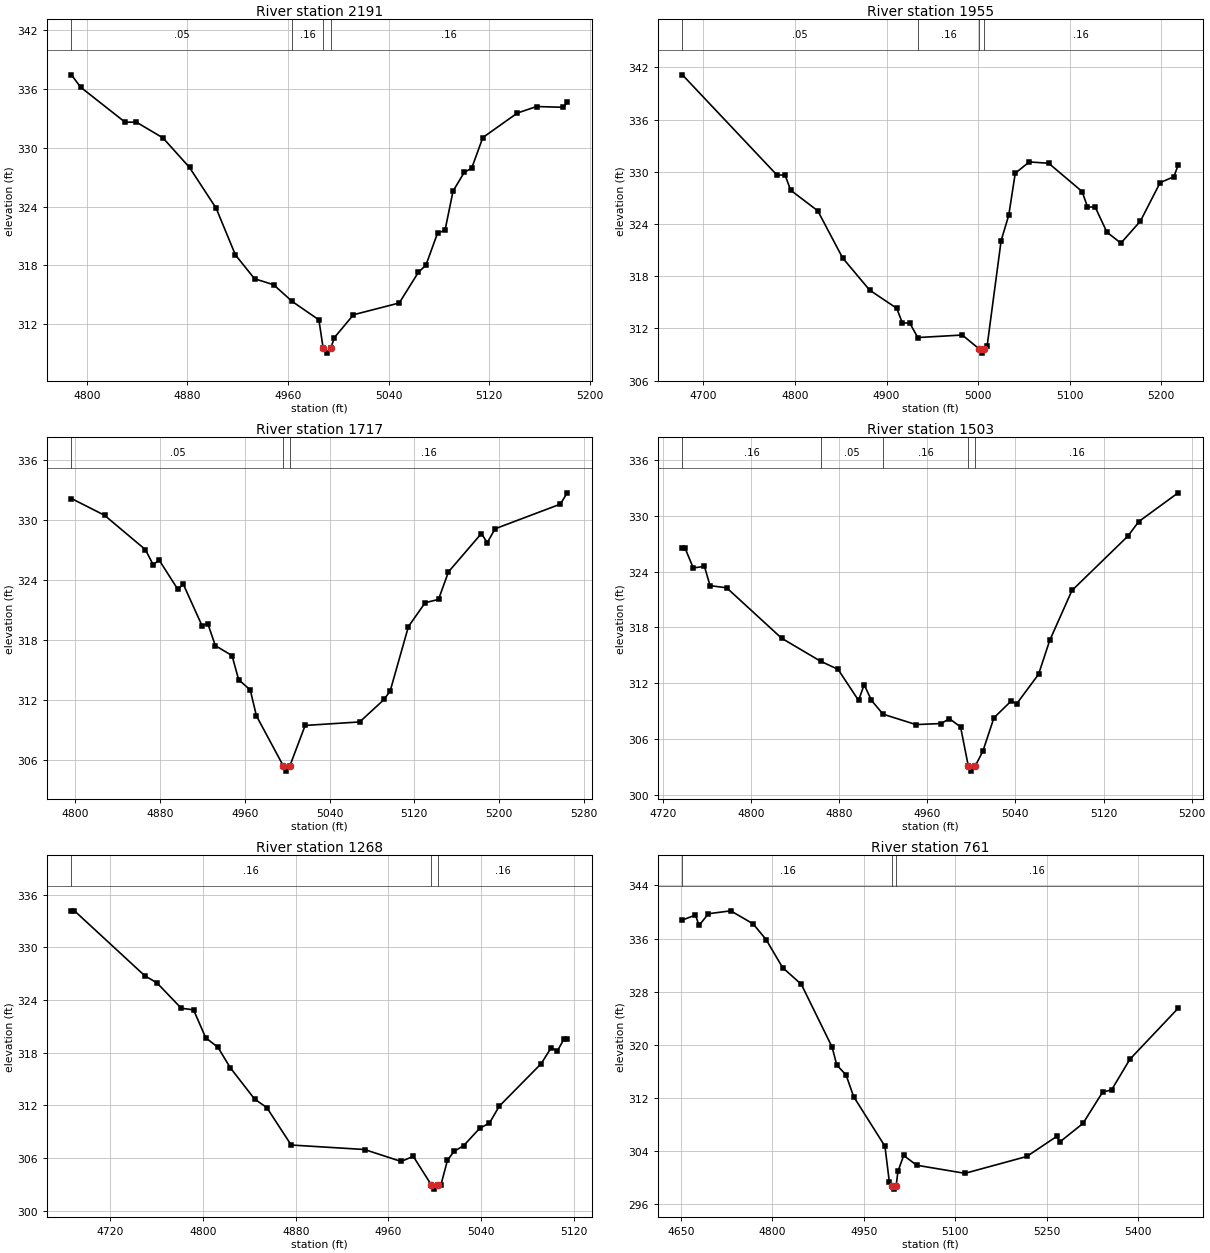
Type RM Length L Ch R = 1,2191,236,236,236
BEGIN DESCRIPTION:
UNT 063 IN BOCR 4.0
END DESCRIPTION:
XS GIS Cut Line= 2
      3777043.90     10576204.13      3776832.21     10576536.78
#Sta/Elev= 30
  4787.8  337.42  4795.0  336.17  4830.5  332.59  4839.4  332.60  4860.6  330.99
  4881.7  327.98  4902.9  323.82  4918.2  319.07  4933.4  316.64  4948.6  316.03
  4963.3  314.33  4984.6  312.45  4988.0  309.56  4990.7  309.06  4994.0  309.56
  4996.9  310.64  5012.1  312.97  5048.5  314.17  5063.8  317.31  5069.7  318.02
  5079.0  321.30  5084.9  321.57  5091.3  325.57  5100.2  327.48  5106.1  327.90
  5115.0  331.03  5142.5  333.53  5157.8  334.19  5178.9  334.11  5182.1  334.62
#Mann=4,-1,0
  4787.8    0.05       0  4963.3    0.16       0  4988.0    0.07       0
  4994.0    0.16       0
Bank Sta=4988,4994
Exp/Cntr=0.3,0.1

Type RM Length L Ch R = 1,1955,238,238,238
BEGIN DESCRIPTION:
Mapping XS a19fd724
END DESCRIPTION:
XS GIS Cut Line= 3
      3776921.72     10576037.15      3776748.11     10576283.68
      3776620.67     10576486.90
#Sta/Elev= 30
  4677.0  341.14  4780.4  329.61  4789.1  329.64  4795.2  327.88  4824.8  325.52
  4852.0  320.10  4881.5  316.40  4911.1  314.31  4917.2  312.63  4925.3  312.61
  4934.1  310.95  4982.7  311.24  5000.9  309.66  5003.7  309.16  5006.9  309.66
  5009.8  309.99  5025.1  322.10  5033.4  325.00  5040.5  329.83  5055.8  331.13
  5077.0  330.98  5113.5  327.73  5119.4  325.98  5127.9  325.92  5140.6  323.06
  5155.9  321.80  5177.2  324.33  5198.7  328.75  5213.7  329.43  5218.4  330.76
#Mann=4,-1,0
  4677.0    0.05       0  4934.1    0.16       0  5000.9    0.07       0
  5006.9    0.16       0
Bank Sta=5000.9,5006.9
Exp/Cntr=0.3,0.1

Type RM Length L Ch R = 1,1717,214,214,214
BEGIN DESCRIPTION:
UNT 063 IN BOCR 3.0
END DESCRIPTION:
XS GIS Cut Line= 2
      3776657.61     10575956.75      3776462.31     10576382.06
#Sta/Elev= 30
  4796.3  332.11  4827.5  330.44  4866.1  327.01  4873.5  325.49  4879.0  325.98
  4896.5  323.08  4902.0  323.53  4919.5  319.43  4925.0  319.63  4932.1  317.43
  4947.9  316.43  4954.1  314.03  4965.1  313.00  4970.9  310.42  4996.4  305.40
  4999.2  304.90  5002.4  305.40  5016.9  309.46  5068.4  309.81  5091.4  312.05
  5097.2  312.91  5114.4  319.33  5130.2  321.71  5142.8  322.04  5152.2  324.79
  5183.3  328.62  5188.8  327.70  5196.2  329.09  5257.8  331.55  5264.3  332.68
#Mann=3,-1,0
  4796.3    0.05       0  4996.4    0.07       0  5002.4    0.16       0
Bank Sta=4996.4,5002.4
Exp/Cntr=0.3,0.1

Type RM Length L Ch R = 1,1503,235,235,235
BEGIN DESCRIPTION:
Mapping XS 7743a848
END DESCRIPTION:
XS GIS Cut Line= 3
      3776418.25     10575900.40      3776385.70     10576123.09
      3776351.88     10576345.47
#Sta/Elev= 30
  4737.7  326.52  4740.1  326.52  4747.6  324.38  4757.7  324.56  4762.8  322.48
  4777.9  322.25  4827.7  316.83  4863.1  314.35  4879.0  313.47  4897.6  310.13
  4902.7  311.82  4909.3  310.14  4919.8  308.65  4949.7  307.53  4972.5  307.64
  4980.1  308.16  4990.2  307.28  4997.3  303.02  5000.0  302.52  5003.3  303.02
  5010.4  304.65  5020.5  308.26  5036.1  310.06  5041.2  309.78  5061.0  312.94
  5071.1  316.58  5091.3  321.96  5141.9  327.79  5152.0  329.38  5187.7  332.47
#Mann=5,-1,0
  4737.7    0.16       0  4863.1    0.05       0  4919.8    0.16       0
  4997.3    0.07       0  5003.3    0.16       0
Bank Sta=4997.3,5003.3
Exp/Cntr=0.3,0.1

Type RM Length L Ch R = 1,1268,507,507,507
BEGIN DESCRIPTION:
UNT 063 IN BOCR 2.0
END DESCRIPTION:
XS GIS Cut Line= 3
      3776249.60     10575860.21      3776149.61     10576160.19
      3776199.61     10576260.18
#Sta/Elev= 30
  4686.4  334.16  4689.0  334.16  4749.6  326.78  4760.2  325.96  4781.2  323.07
  4791.8  322.89  4802.3  319.71  4812.9  318.62  4823.4  316.32  4844.5  312.73
  4855.0  311.77  4876.1  307.50  4939.4  306.99  4971.0  305.63  4981.5  306.21
  4997.0  302.98  4999.7  302.48  5003.0  302.98  5005.4  302.98  5011.0  305.76
  5016.6  306.77  5025.0  307.43  5038.9  309.41  5047.3  310.00  5055.7  311.92
  5092.0  316.77  5100.4  318.55  5106.0  318.23  5111.6  319.56  5114.4  319.56
#Mann=3,-1,0
  4686.4    0.16       0  4997.0    0.07       0  5003.0    0.16       0
Bank Sta=4997,5003
Exp/Cntr=0.3,0.1

Type RM Length L Ch R = 1,761,0,0,0
BEGIN DESCRIPTION:
UNT 063 IN BOCR 1.0
END DESCRIPTION:
XS GIS Cut Line= 3
      3776128.90     10575721.47      3775681.00     10575997.50
      3775784.27     10576266.00
#Sta/Elev= 30
  4652.3  338.78  4673.8  339.54  4679.6  337.96  4695.0  339.73  4731.7  340.17
  4768.4  338.21  4789.7  335.84  4816.8  331.62  4847.6  329.09  4898.1  319.63
  4905.6  316.96  4921.0  315.43  4933.4  312.18  4984.8  304.70  4992.1  299.26
  4997.2  298.74  5000.0  298.24  5003.2  298.74  5006.1  300.91  5015.6  303.31
  5036.9  301.84  5116.1  300.62  5217.6  303.16  5266.9  306.19  5272.2  305.37
  5309.9  308.14  5342.0  312.84  5356.9  313.20  5386.9  317.81  5466.1  325.49
#Mann=3,-1,0
  4652.3    0.16       0  4997.2    0.07       0  5003.2    0.16       0
Bank Sta=4997.2,5003.2
Exp/Cntr=0.3,0.1

Chan Stop Cuts=-1