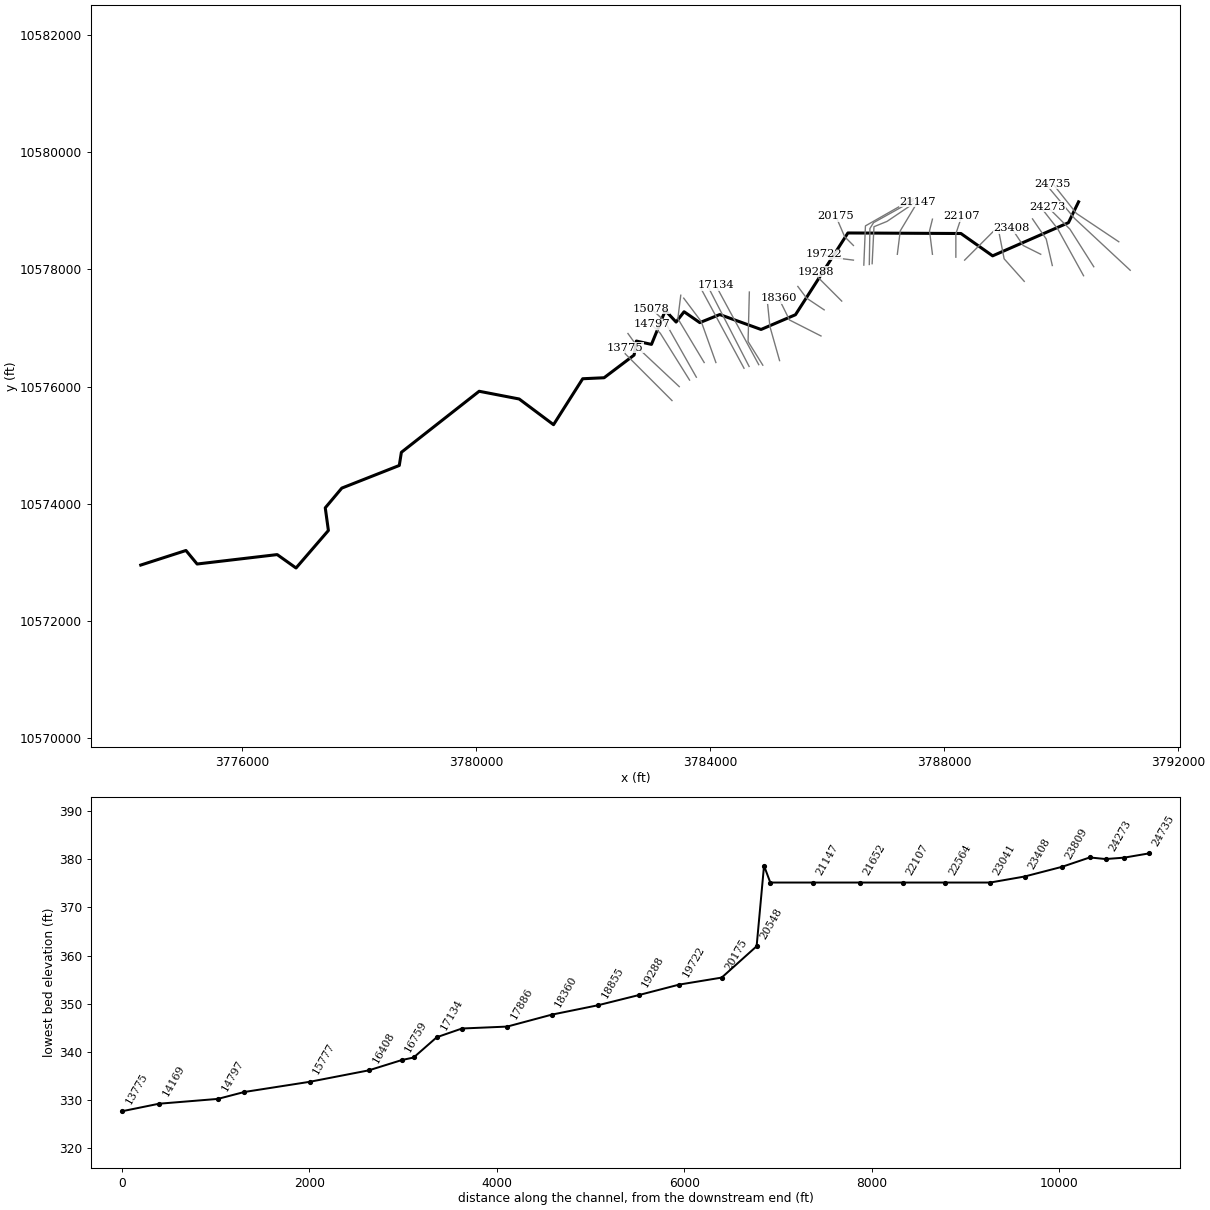
--- UNT 064 IN BOCR.prj (project) ---

Proj Title=UNT 064 IN BOCR Base Level Engineering
Current Plan=p01
Default Exp/Contr=0.3,0.1
English Units
Geom File=g01
Flow File=f01
Plan File=p01
BEGIN DESCRIPTION:
UNT 064 IN BOCR
END DESCRIPTION:

--- UNT 064 IN BOCR.p01 (plan) ---

Plan Title=Multiple Run
Short Identifier=Multiple
Geom File=g01
Flow File=f01
Subcritical Flow
K Sum by GR= 0
Std Step Tol= 0.01
Critical Tol= 0.01
Num of Std Step Trials= 20
Max Error Tol= 0.3
Flow Tol Ratio= 0.001
Split Flow NTrial= 30
Split Flow Tol= 0.02
Split Flow Ratio= 0.02
Log Output Level= 0
Friction Slope Method= 1
Unsteady Friction Slope Method= 2
Unsteady Bridges Friction Slope Method= 1
Parabolic Critical Depth
Global Vel Dist=  1 , 1 , 1
Global Log Level= 0
CheckData=True
Encroach Param= -1, 0, 0, 0
BEGIN DESCRIPTION:
Multiple Run
END DESCRIPTION:

--- UNT 064 IN BOCR.f01 (steady flow) ---

Flow Title=Multiple
Number of Profiles=7
Profile Names=10-year,25-year,50-year,1pct_min,100-year,1pct_plu,500-year
River Rch & RM= UNT 064 IN BOCR,Reach-1,24735
     618     835    1014     906    1225    1657    1793
River Rch & RM= UNT 064 IN BOCR,Reach-1,20175
     807    1105    1355    1220    1650    2231    2455
River Rch & RM= UNT 064 IN BOCR,Reach-1,17886
    1259    1759    2183    1986    2686    3632    4082
River Rch & RM= UNT 064 IN BOCR,Reach-1,6577
    1374    1924    2393    2181    2949    3988    4498
River Rch & RM= UNT 064 IN BOCR,Reach-1,2722
    1818    2578    3234    2970    4016    5431    6220
Boundary for River Rch & Prof#=UNT 064 IN BOCR,Reach-1,1
Up Type=0
Dn Type=3
Dn Slope=0.005
Boundary for River Rch & Prof#=UNT 064 IN BOCR,Reach-1,2
Up Type=0
Dn Type=3
Dn Slope=0.005
Boundary for River Rch & Prof#=UNT 064 IN BOCR,Reach-1,3
Up Type=0
Dn Type=3
Dn Slope=0.005
Boundary for River Rch & Prof#=UNT 064 IN BOCR,Reach-1,4
Up Type=0
Dn Type=3
Dn Slope=0.005
Boundary for River Rch & Prof#=UNT 064 IN BOCR,Reach-1,5
Up Type=0
Dn Type=3
Dn Slope=0.005
Boundary for River Rch & Prof#=UNT 064 IN BOCR,Reach-1,6
Up Type=0
Dn Type=3
Dn Slope=0.005
Boundary for River Rch & Prof#=UNT 064 IN BOCR,Reach-1,7
Up Type=0
Dn Type=3
Dn Slope=0.005

--- UNT 064 IN BOCR.g01 (geometry) ---

Geom Title=Existing Conditions

River Reach=UNT 064 IN BOCR,Reach-1
Reach XY= 30
      3790296.14     10579155.77      3790123.50     10578800.00
      3788827.75     10578233.00      3788286.00     10578615.00
      3786355.00     10578624.00      3785459.50     10577227.00
      3784871.25     10576975.00      3784165.75     10577230.00
      3783824.50     10577092.00      3783556.00     10577278.00
      3783420.00     10577102.00      3783235.50     10577299.00
      3782999.00     10576720.00      3782741.00     10576777.00
      3782702.75     10576538.00      3782189.50     10576150.00
      3781824.00     10576133.00      3781325.50     10575348.00
      3780738.75     10575787.00      3780054.75     10575919.00
      3778726.00     10574876.00      3778690.25     10574651.00
      3777708.00     10574264.00      3777425.50     10573927.00
      3777479.00     10573540.00      3776926.25     10572899.00
      3776604.00     10573128.00      3775236.00     10572967.00
      3775045.25     10573198.00      3774273.25     10572949.00

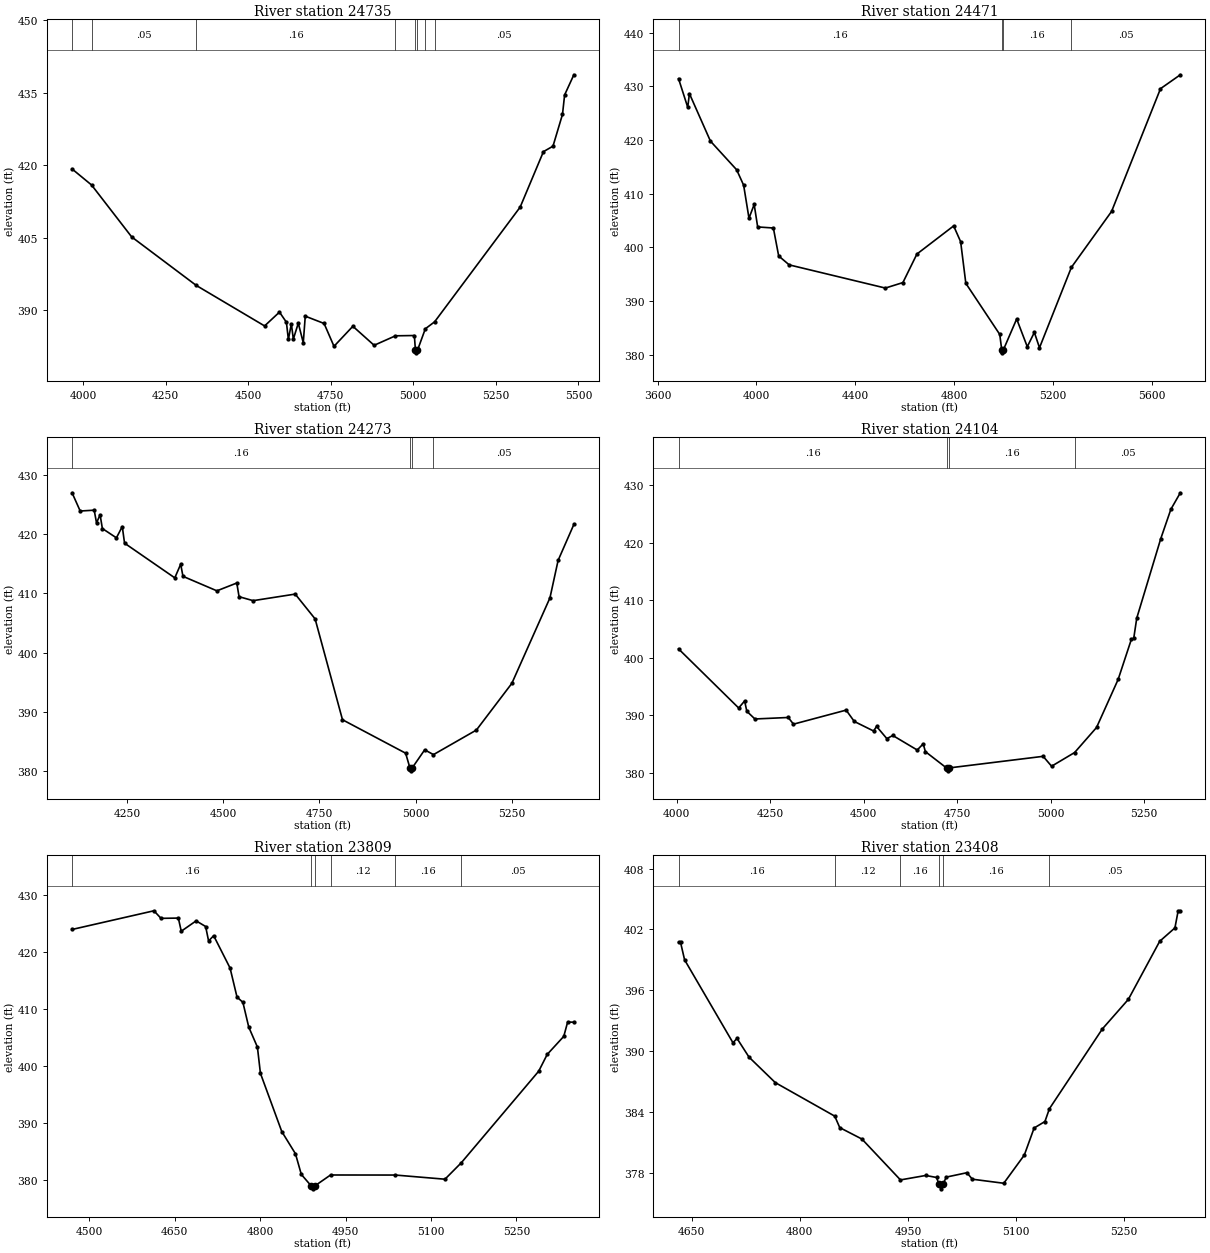
Type RM Length L Ch R = 1,24735,264,264,264
BEGIN DESCRIPTION:
UNT 064 IN BOCR 47.0
END DESCRIPTION:
XS GIS Cut Line= 3
      3790983.27     10578473.89      3790259.34     10578958.25
      3789856.02     10579465.66
#Sta/Elev= 30
  3967.0  419.22  4026.1  415.90  4147.5  405.17  4343.1  395.14  4549.9  386.77
  4594.9  389.63  4615.9  387.54  4621.9  383.97  4630.9  387.22  4636.9  384.05
  4651.9  387.34  4667.0  383.30  4673.0  388.79  4730.0  387.28  4760.0  382.56
  4817.1  386.70  4881.5  382.77  4946.1  384.73  5003.3  384.79  5006.6  381.71
  5009.4  381.21  5012.6  381.71  5036.5  386.18  5064.6  387.62  5323.6  411.33
  5394.1  422.80  5423.0  423.93  5451.8  430.51  5458.2  434.52  5486.2  438.69
#Mann=8,-1,0
  3967.0    0.16       0  4026.1    0.05       0  4343.1    0.16       0
  4946.1    0.05       0  5006.6    0.03       0  5012.6    0.05       0
  5036.5    0.16       0  5064.6    0.05       0
Bank Sta=5006.6,5012.6
Exp/Cntr=0.3,0.1

Type RM Length L Ch R = 1,24471,198,198,198
BEGIN DESCRIPTION:
Mapping XS 56e71ed3
END DESCRIPTION:
XS GIS Cut Line= 3
      3791178.61     10577986.90      3790228.09     10578872.31
      3789759.36     10579432.19
#Sta/Elev= 30
  3684.9  431.42  3722.1  426.08  3728.9  428.63  3813.9  419.78  3919.9  414.44
  3948.2  411.56  3969.8  405.41  3990.8  407.98  4004.9  403.79  4068.4  403.59
  4089.9  398.38  4132.4  396.72  4521.3  392.40  4592.2  393.42  4648.9  398.74
  4797.4  403.98  4825.7  401.04  4846.7  393.28  4983.9  383.76  4992.0  380.83
  4994.8  380.33  4998.0  380.83  5052.3  386.64  5095.2  381.47  5123.8  384.14
  5144.6  381.28  5273.6  396.26  5436.1  406.68  5633.9  429.55  5714.1  432.14
#Mann=4,-1,0
  3684.9    0.16       0  4992.0    0.07       0  4998.0    0.16       0
  5273.6    0.05       0
Bank Sta=4992,4998
Exp/Cntr=0.3,0.1

Type RM Length L Ch R = 1,24273,169,169,169
BEGIN DESCRIPTION:
UNT 064 IN BOCR 46.0
END DESCRIPTION:
XS GIS Cut Line= 3
      3790555.76     10578047.12      3790149.54     10578687.71
      3789764.40     10579072.85
#Sta/Elev= 30
  4107.8  427.00  4128.9  423.92  4165.3  424.06  4171.3  421.91  4180.6  423.28
  4186.5  420.96  4223.0  419.39  4238.2  421.30  4244.1  418.49  4374.6  412.63
  4389.9  414.94  4395.8  412.89  4483.9  410.44  4535.6  411.76  4541.5  409.45
  4578.0  408.78  4687.3  409.89  4739.0  405.70  4810.1  388.67  4974.1  383.02
  4985.2  380.54  4988.0  380.04  4991.2  380.54  5023.6  383.59  5046.4  382.78
  5157.9  386.93  5249.9  394.81  5348.9  409.25  5370.1  415.58  5411.0  421.65
#Mann=4,-1,0
  4107.8    0.16       0  4985.2    0.07       0  4991.2    0.16       0
  5046.4    0.05       0
Bank Sta=4985.2,4991.2
Exp/Cntr=0.3,0.1

Type RM Length L Ch R = 1,24104,295,295,295
BEGIN DESCRIPTION:
Mapping XS 276a3b09
END DESCRIPTION:
XS GIS Cut Line= 3
      3790381.72     10577893.18      3789939.03     10578695.23
      3789675.98     10579031.20
#Sta/Elev= 30
  4004.5  401.56  4165.4  391.29  4181.4  392.51  4187.2  390.72  4208.9  389.38
  4298.1  389.64  4312.1  388.48  4453.0  390.92  4474.8  388.95  4526.5  387.29
  4534.4  388.09  4561.9  385.97  4577.9  386.51  4643.2  383.99  4659.3  385.06
  4665.0  383.71  4721.6  380.87  4724.3  380.37  4727.6  380.87  4980.2  382.89
  5002.8  381.17  5064.4  383.55  5123.1  387.90  5180.9  396.25  5216.2  403.20
  5222.6  403.38  5230.7  406.90  5294.9  420.70  5322.0  425.81  5347.3  428.68
#Mann=4,-1,0
  4004.5    0.16       0  4721.6    0.07       0  4727.6    0.16       0
  5064.4    0.05       0
Bank Sta=4721.6,4727.6
Exp/Cntr=0.3,0.1

Type RM Length L Ch R = 1,23809,401,401,401
BEGIN DESCRIPTION:
UNT 064 IN BOCR 45.0
END DESCRIPTION:
XS GIS Cut Line= 3
      3789847.46     10578067.91      3789743.29     10578521.04
      3789508.91     10578864.80
#Sta/Elev= 30
  4469.8  423.95  4613.5  427.23  4626.0  425.90  4656.4  425.95  4661.5  423.64
  4687.6  425.46  4704.3  424.47  4709.5  421.93  4718.4  422.86  4747.2  417.18
  4759.4  412.08  4769.7  411.17  4780.0  406.82  4795.2  403.31  4800.5  398.71
  4838.0  388.48  4862.0  384.59  4872.3  380.96  4889.8  378.93  4892.6  378.43
  4895.8  378.93  4923.6  380.86  5037.5  380.85  5124.5  380.12  5153.2  383.01
  5289.1  399.08  5304.0  402.02  5333.1  405.19  5339.9  407.71  5350.8  407.67
#Mann=6,-1,0
  4469.8    0.16       0  4889.8    0.07       0  4895.8    0.16       0
  4923.6    0.12       0  5037.5    0.16       0  5153.2    0.05       0
Bank Sta=4889.8,4895.8
Exp/Cntr=0.3,0.1

Type RM Length L Ch R = 1,23408,367,367,367
BEGIN DESCRIPTION:
UNT 064 IN BOCR 44.0
END DESCRIPTION:
XS GIS Cut Line= 3
      3789649.61     10578260.19      3789349.61     10578410.19
      3789149.59     10578710.21
#Sta/Elev= 30
  4631.8  400.72  4634.6  400.72  4640.2  399.00  4707.3  390.82  4712.9  391.25
  4729.6  389.40  4766.0  386.89  4848.5  383.58  4855.4  382.45  4886.2  381.32
  4939.6  377.29  4974.7  377.73  4989.7  377.53  4992.8  376.91  4995.5  376.41
  4998.8  376.91  5003.3  377.57  5031.8  378.00  5039.3  377.36  5082.9  376.96
  5111.4  379.74  5125.0  382.41  5140.0  383.05  5146.2  384.31  5219.6  392.18
  5255.7  395.10  5299.2  400.83  5320.3  402.15  5324.8  403.84  5327.8  403.84
#Mann=6,-1,0
  4631.8    0.16       0  4848.5    0.12       0  4939.6    0.16       0
  4992.8    0.07       0  4998.8    0.16       0  5146.2    0.05       0
Bank Sta=4992.8,4998.8
Exp/Cntr=0.3,0.1

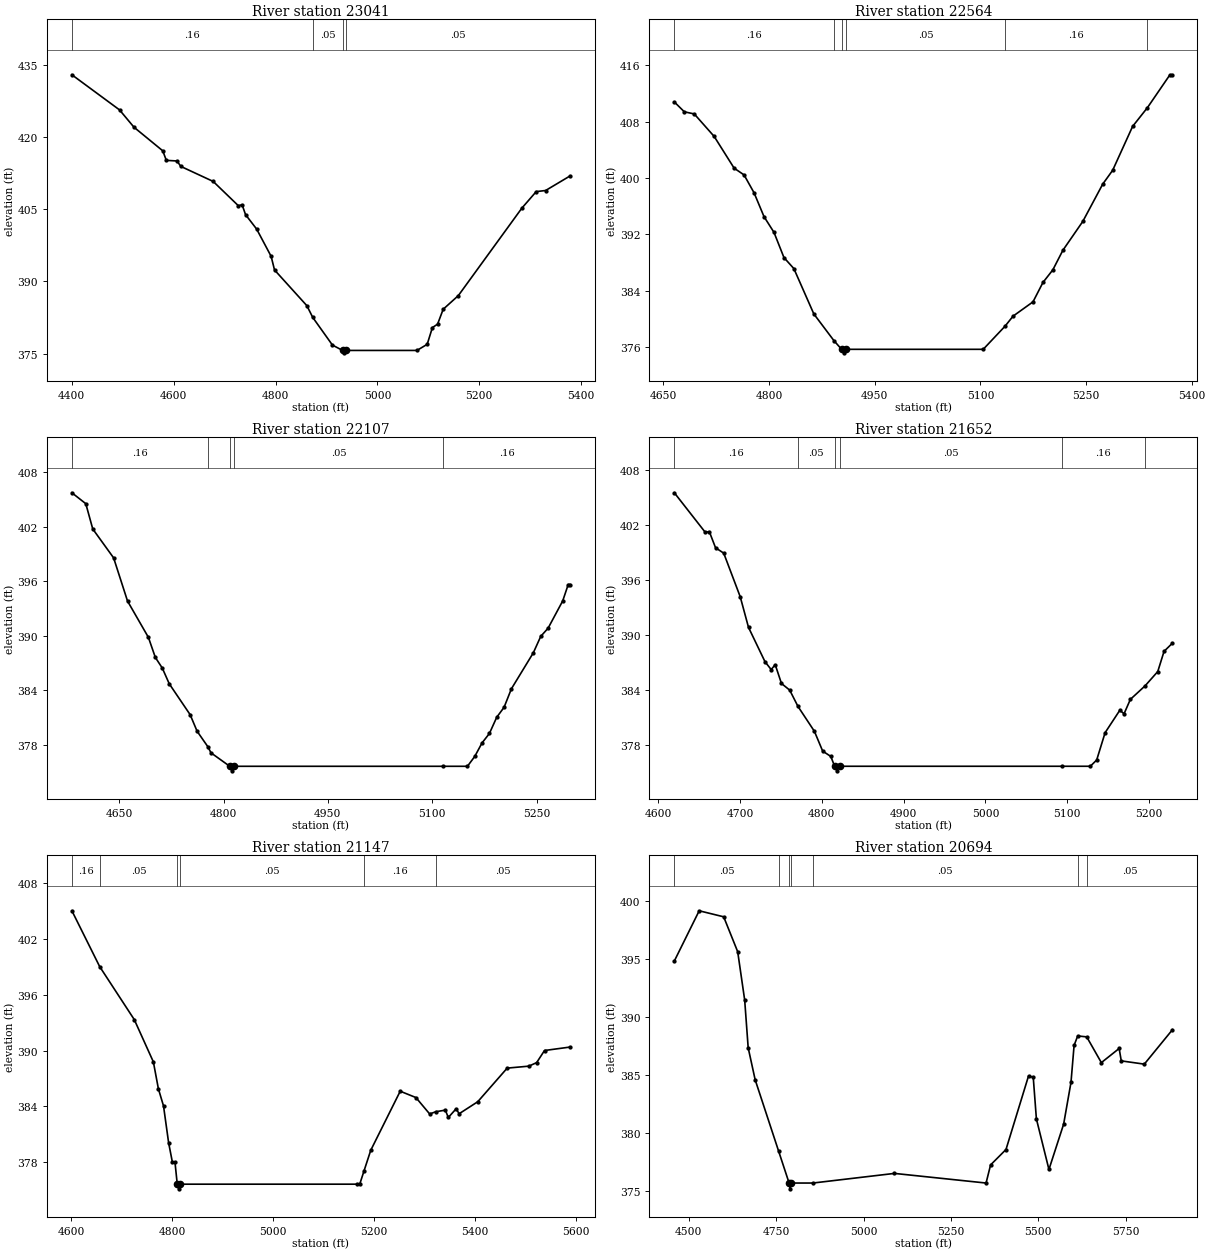
Type RM Length L Ch R = 1,23041,477,477,477
BEGIN DESCRIPTION:
UNT 064 IN BOCR 43.0
END DESCRIPTION:
XS GIS Cut Line= 3
      3789368.29     10577797.09      3789024.54     10578182.50
      3788936.04     10578635.40
#Sta/Elev= 30
  4400.2  432.90  4493.7  425.61  4522.1  422.01  4578.6  417.11  4585.6  415.13
  4606.5  415.00  4614.1  413.87  4677.6  410.75  4726.9  405.72  4734.4  405.90
  4741.1  403.86  4762.9  400.86  4791.3  395.21  4798.0  392.37  4861.5  384.95
  4873.0  382.52  4911.7  376.77  4931.7  375.66  4934.4  375.16  4937.7  375.66
  5077.6  375.66  5097.7  376.93  5107.9  380.40  5118.1  381.12  5129.1  384.21
  5158.8  387.04  5283.7  405.23  5311.7  408.64  5330.2  408.87  5378.1  411.89
#Mann=4,-1,0
  4400.2    0.16       0  4873.0    0.05       0  4931.7   0.033       0
  4937.7    0.05       0
Bank Sta=4931.7,4937.7
Exp/Cntr=0.3,0.1

Type RM Length L Ch R = 1,22564,457,457,457
BEGIN DESCRIPTION:
UNT 064 IN BOCR 42.0
END DESCRIPTION:
XS GIS Cut Line= 3
      3788349.58     10578160.16      3788599.61     10578410.19
      3788849.64     10578660.22
#Sta/Elev= 30
  4665.5  410.78  4679.7  409.38  4693.8  409.08  4722.1  405.88  4750.4  401.38
  4764.5  400.42  4778.7  397.88  4792.8  394.50  4807.0  392.26  4821.1  388.69
  4835.2  387.12  4863.5  380.69  4892.0  376.90  4903.0  375.66  4905.7  375.16
  4909.0  375.66  5104.0  375.66  5134.8  378.92  5146.4  380.37  5174.7  382.40
  5188.8  385.15  5202.9  386.95  5217.1  389.72  5245.4  393.82  5273.7  399.12
  5287.8  401.08  5316.1  407.31  5337.2  409.98  5369.1  414.64  5372.7  414.64
#Mann=6,-1,0
  4665.5    0.16       0  4892.0    0.05       0  4903.0   0.033       0
  4909.0    0.05       0  5134.8    0.16       0  5337.2    0.05       0
Bank Sta=4903,4909
Exp/Cntr=0.3,0.1

Type RM Length L Ch R = 1,22107,455,455,455
BEGIN DESCRIPTION:
UNT 064 IN BOCR 41.0
END DESCRIPTION:
XS GIS Cut Line= 3
      3788199.61     10578210.18      3788199.61     10578610.19
      3788299.60     10578910.16
#Sta/Elev= 30
  4582.0  405.74  4602.0  404.54  4612.0  401.76  4642.0  398.58  4662.0  393.83
  4692.0  389.84  4702.0  387.63  4712.0  386.46  4722.0  384.73  4752.0  381.34
  4762.0  379.52  4777.5  377.81  4782.0  377.14  4809.0  375.66  4811.8  375.16
  4815.0  375.66  5115.8  375.66  5150.7  375.66  5161.2  376.74  5171.7  378.23
  5182.3  379.27  5192.8  381.05  5203.4  382.15  5213.9  384.18  5245.5  388.15
  5256.1  389.95  5266.6  390.84  5287.7  393.85  5295.6  395.65  5298.2  395.65
#Mann=5,-1,0
  4582.0    0.16       0  4777.5    0.05       0  4809.0   0.033       0
  4815.0    0.05       0  5115.8    0.16       0
Bank Sta=4809,4815
Exp/Cntr=0.3,0.1

Type RM Length L Ch R = 1,21652,505,505,505
BEGIN DESCRIPTION:
UNT 064 IN BOCR 40.0
END DESCRIPTION:
XS GIS Cut Line= 3
      3787799.61     10578260.22      3787749.61     10578660.19
      3787799.60     10578860.15
#Sta/Elev= 30
  4619.6  405.55  4657.4  401.23  4662.4  401.30  4670.0  399.54  4680.0  398.95
  4700.2  394.18  4710.3  390.84  4730.4  387.10  4738.0  386.23  4743.0  386.76
  4750.6  384.71  4760.7  383.98  4770.8  382.20  4790.9  379.48  4801.0  377.32
  4811.0  376.73  4815.6  375.66  4818.4  375.16  4821.6  375.66  5093.2  375.66
  5128.3  375.66  5136.1  376.34  5146.4  379.33  5164.4  381.78  5169.6  381.40
  5177.3  382.97  5195.3  384.45  5210.8  386.01  5218.5  388.22  5228.8  389.12
#Mann=6,-1,0
  4619.6    0.16       0  4770.8    0.05       0  4815.6   0.033       0
  4821.6    0.05       0  5093.2    0.16       0  5195.3    0.05       0
Bank Sta=4815.6,4821.6
Exp/Cntr=0.3,0.1

Type RM Length L Ch R = 1,21147,453,453,453
BEGIN DESCRIPTION:
UNT 064 IN BOCR 39.0
END DESCRIPTION:
XS GIS Cut Line= 3
      3787199.61     10578260.18      3787249.61     10578660.19
      3787549.60     10579160.17
#Sta/Elev= 30
  4601.5  405.01  4656.6  399.01  4725.0  393.33  4762.8  388.79  4772.8  385.89
  4782.9  384.06  4793.0  380.11  4800.5  378.01  4805.6  378.02  4810.1  375.66
  4812.9  375.16  4816.1  375.66  5165.9  375.66  5171.8  375.73  5179.7  377.06
  5193.2  379.30  5251.5  385.64  5282.6  384.96  5309.8  383.20  5322.2  383.44
  5340.9  383.61  5346.7  382.82  5362.3  383.76  5368.1  383.22  5405.0  384.51
  5463.3  388.12  5506.1  388.33  5521.6  388.71  5537.2  390.01  5587.7  390.38
#Mann=6,-1,0
  4601.5    0.16       0  4656.6    0.05       0  4810.1   0.033       0
  4816.1    0.05       0  5179.7    0.16       0  5322.2    0.05       0
Bank Sta=4810.1,4816.1
Exp/Cntr=0.3,0.1

Type RM Length L Ch R = 1,20694,67,67,67
BEGIN DESCRIPTION:
Mapping XS 1b39d3f5
END DESCRIPTION:
XS GIS Cut Line= 4
      3786769.33     10578099.16      3786800.58     10578731.11
      3787022.80     10578821.39      3787481.17     10579130.43
#Sta/Elev= 30
  4458.4  394.80  4529.5  399.13  4599.6  398.61  4639.7  395.60  4659.7  391.43
  4669.7  387.32  4689.7  384.56  4756.7  378.42  4786.8  375.66  4789.6  375.16
  4792.8  375.66  4854.7  375.66  5088.2  376.49  5350.4  375.66  5363.3  377.22
  5407.4  378.55  5471.9  384.89  5485.4  384.78  5494.4  381.19  5530.3  376.83
  5572.4  380.74  5593.4  384.34  5602.3  387.53  5612.6  388.34  5638.4  388.26
  5680.3  386.04  5731.2  387.26  5737.3  386.19  5803.2  385.91  5883.8  388.88
#Mann=7,-1,0
  4458.4    0.05       0  4756.7    0.16       0  4786.8   0.033       0
  4792.8    0.16       0  4854.7    0.05       0  5612.6    0.16       0
  5638.4    0.05       0
Bank Sta=4786.8,4792.8
Exp/Cntr=0.3,0.1

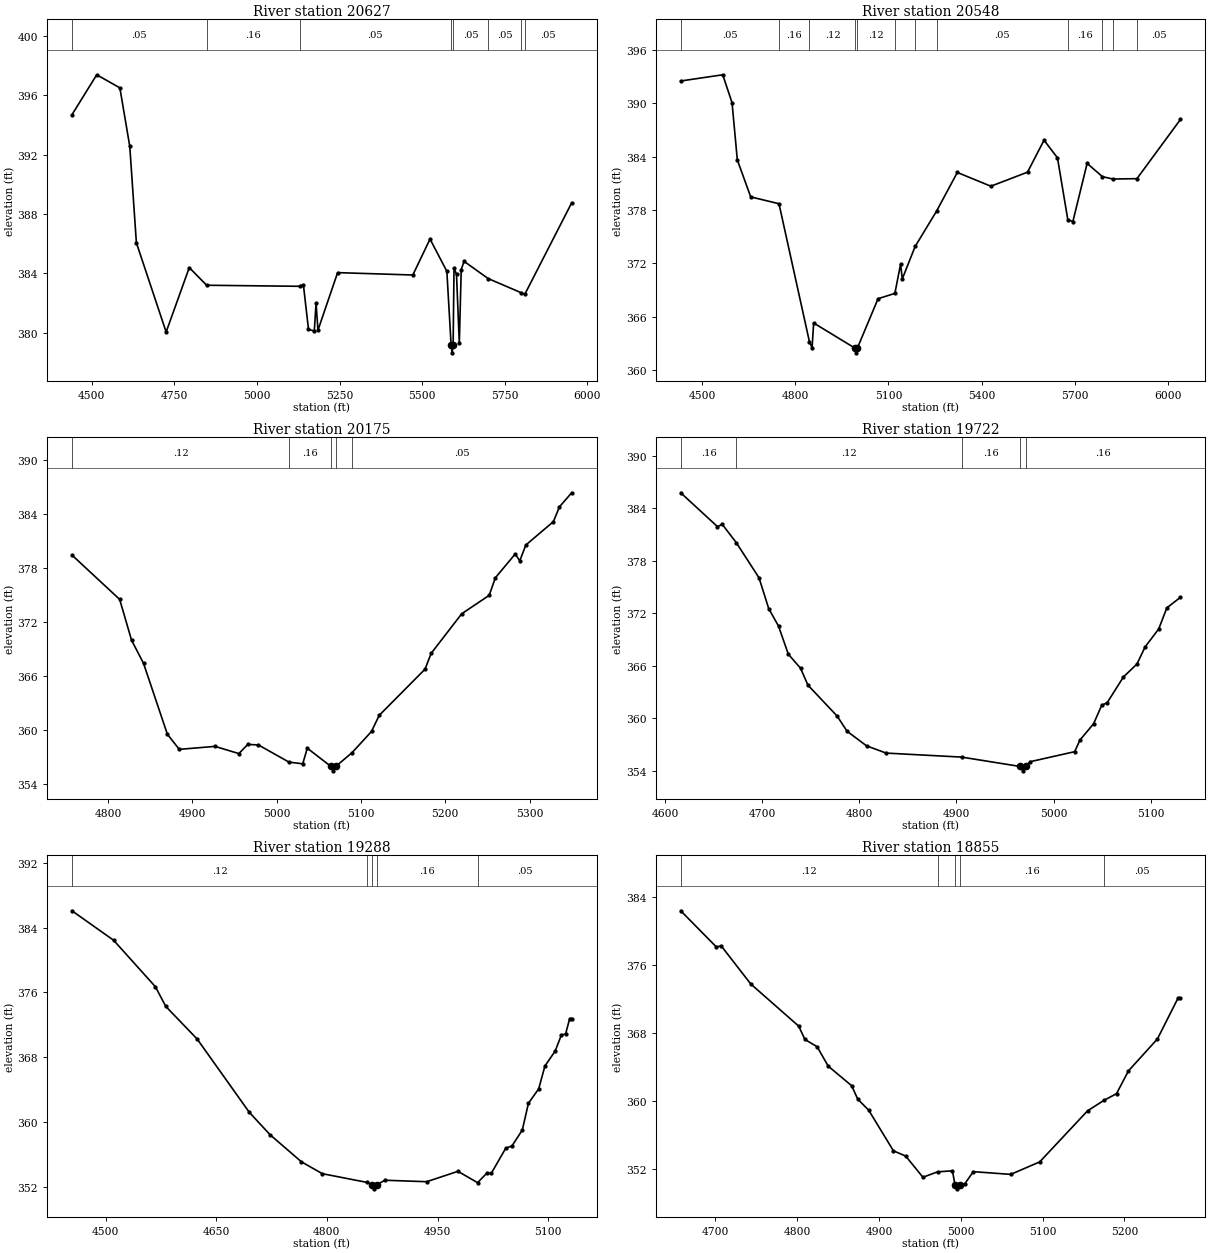
Type RM Length L Ch R = 1,20627,79,79,79
BEGIN DESCRIPTION:
Mapping XS 6fa2c970
END DESCRIPTION:
XS GIS Cut Line= 4
      3786720.72     10578085.29      3786731.14     10578699.86
      3786793.64     10578800.55      3787474.21     10579179.03
#Sta/Elev= 30
  4440.4  394.68  4515.3  397.37  4585.3  396.49  4615.3  392.55  4635.3  386.06
  4725.3  380.05  4795.3  384.39  4847.8  383.20  5128.9  383.13  5140.6  383.23
  5156.0  380.23  5173.6  380.12  5178.9  382.01  5184.6  380.17  5244.1  384.05
  5471.7  383.89  5523.7  386.31  5574.6  384.14  5587.6  379.15  5590.4  378.65
  5593.6  379.15  5596.3  384.38  5603.8  383.93  5612.3  379.30  5618.1  384.25
  5626.7  384.81  5699.6  383.65  5799.2  382.70  5810.4  382.59  5952.3  388.75
#Mann=8,-1,0
  4440.4    0.05       0  4847.8    0.16       0  5128.9    0.05       0
  5587.6    0.07       0  5593.6    0.05       0  5699.6    0.05       0
  5799.2    0.16       0  5810.4    0.05       0
Bank Sta=5587.6,5593.6
Exp/Cntr=0.3,0.1

Type RM Length L Ch R = 1,20548,373,373,373
BEGIN DESCRIPTION:
UNT 064 IN BOCR 38.0
END DESCRIPTION:
XS GIS Cut Line= 3
      3786626.97     10578074.89      3786654.75     10578745.00
      3787470.73     10579210.28
#Sta/Elev= 30
  4430.7  392.52  4566.1  393.22  4596.1  390.08  4613.1  383.64  4656.2  379.48
  4747.3  378.71  4845.6  363.15  4854.0  362.49  4859.0  365.29  4993.5  362.43
  4996.2  361.93  4999.5  362.43  5066.5  368.02  5120.7  368.62  5139.0  371.89
  5144.7  370.26  5186.0  373.90  5254.9  377.87  5321.9  382.23  5429.9  380.68
  5548.0  382.26  5601.3  385.86  5644.6  383.87  5677.8  376.93  5694.1  376.69
  5740.1  383.25  5789.2  381.76  5822.9  381.49  5900.6  381.53  6040.7  388.19
#Mann=12,-1,0
  4430.7    0.05       0  4747.3    0.16       0  4845.6    0.12       0
  4993.5    0.07       0  4999.5    0.12       0  5120.7    0.16       0
  5186.0    0.12       0  5254.9    0.05       0  5677.8    0.16       0
  5789.2    0.05       0  5822.9    0.16       0  5900.6    0.05       0
Bank Sta=4993.5,4999.5
Exp/Cntr=0.3,0.1

Type RM Length L Ch R = 1,20175,453,453,453
BEGIN DESCRIPTION:
UNT 064 IN BOCR 37.0
END DESCRIPTION:
XS GIS Cut Line= 3
      3786449.63     10578410.17      3786299.61     10578560.19
      3786149.63     10578910.14
#Sta/Elev= 30
  4757.1  379.42  4813.7  374.49  4827.8  369.95  4842.0  367.38  4870.3  359.49
  4884.4  357.81  4926.8  358.14  4955.1  357.34  4965.7  358.36  4978.3  358.30
  5014.6  356.39  5030.9  356.20  5036.3  357.94  5064.2  355.92  5066.9  355.42
  5070.2  355.92  5089.4  357.44  5112.5  359.80  5121.6  361.59  5176.0  366.73
  5183.2  368.48  5219.5  372.89  5252.1  374.94  5259.4  376.89  5283.0  379.54
  5288.4  378.78  5295.6  380.54  5328.3  383.14  5335.5  384.79  5350.0  386.35
#Mann=5,-1,0
  4757.1    0.12       0  5014.6    0.16       0  5064.2    0.07       0
  5070.2    0.16       0  5089.4    0.05       0
Bank Sta=5064.2,5070.2
Exp/Cntr=0.3,0.1

Type RM Length L Ch R = 1,19722,434,434,434
BEGIN DESCRIPTION:
UNT 064 IN BOCR 36.0
END DESCRIPTION:
XS GIS Cut Line= 3
      3786449.65     10578160.18      3786049.61     10578210.19
      3785949.57     10578260.21
#Sta/Elev= 30
  4615.8  385.76  4653.6  381.90  4658.7  382.14  4673.2  380.04  4696.5  376.04
  4706.5  372.52  4716.6  370.52  4726.7  367.31  4739.3  365.70  4746.9  363.77
  4777.1  360.22  4787.2  358.50  4807.3  356.83  4827.5  356.00  4905.4  355.54
  4965.6  354.47  4968.3  353.97  4971.6  354.47  4976.1  355.02  5021.8  356.16
  5027.3  357.50  5041.3  359.35  5049.7  361.47  5055.3  361.76  5072.1  364.71
  5086.0  366.18  5094.4  368.14  5108.4  370.19  5116.8  372.60  5130.8  373.81
#Mann=5,-1,0
  4615.8    0.16       0  4673.2    0.12       0  4905.4    0.16       0
  4965.6    0.07       0  4971.6    0.16       0
Bank Sta=4965.6,4971.6
Exp/Cntr=0.3,0.1

Type RM Length L Ch R = 1,19288,433,433,433
BEGIN DESCRIPTION:
UNT 064 IN BOCR 35.0
END DESCRIPTION:
XS GIS Cut Line= 3
      3786249.58     10577460.22      3785849.61     10577860.19
      3785799.63     10577960.14
#Sta/Elev= 30
  4454.5  386.08  4511.0  382.44  4567.6  376.71  4581.7  374.28  4624.2  370.26
  4694.9  361.22  4723.2  358.44  4765.6  355.11  4793.9  353.65  4854.6  352.57
  4861.6  352.28  4864.3  351.78  4867.6  352.28  4878.7  352.84  4935.3  352.66
  4977.7  353.94  5004.3  352.54  5016.6  353.69  5022.9  353.69  5042.5  356.79
  5050.9  357.07  5064.9  359.02  5073.3  362.34  5087.2  364.12  5095.6  366.93
  5109.6  368.79  5118.0  370.78  5123.6  370.87  5129.2  372.79  5131.9  372.79
#Mann=5,-1,0
  4454.5    0.12       0  4854.6    0.16       0  4861.6    0.07       0
  4867.6    0.16       0  5004.3    0.05       0
Bank Sta=4861.6,4867.6
Exp/Cntr=0.3,0.1

Type RM Length L Ch R = 1,18855,495,495,495
BEGIN DESCRIPTION:
UNT 064 IN BOCR 34.0
END DESCRIPTION:
XS GIS Cut Line= 3
      3785949.58     10577310.21      3785649.61     10577510.19
      3785499.62     10577710.17
#Sta/Elev= 30
  4657.9  382.38  4701.4  378.13  4707.4  378.25  4743.5  373.77  4802.1  368.81
  4809.6  367.25  4824.6  366.39  4838.1  364.11  4866.7  361.81  4874.2  360.23
  4887.7  358.91  4917.8  354.15  4932.8  353.53  4953.8  351.04  4971.7  351.68
  4989.9  351.80  4992.9  350.18  4995.6  349.68  4998.9  350.18  5004.9  350.27
  5015.4  351.70  5061.1  351.38  5096.5  352.85  5154.9  358.85  5175.0  360.09
  5190.3  360.87  5204.9  363.55  5240.3  367.31  5265.3  372.08  5268.4  372.08
#Mann=5,-1,0
  4657.9    0.12       0  4971.7    0.16       0  4992.9    0.07       0
  4998.9    0.16       0  5175.0    0.05       0
Bank Sta=4992.9,4998.9
Exp/Cntr=0.3,0.1

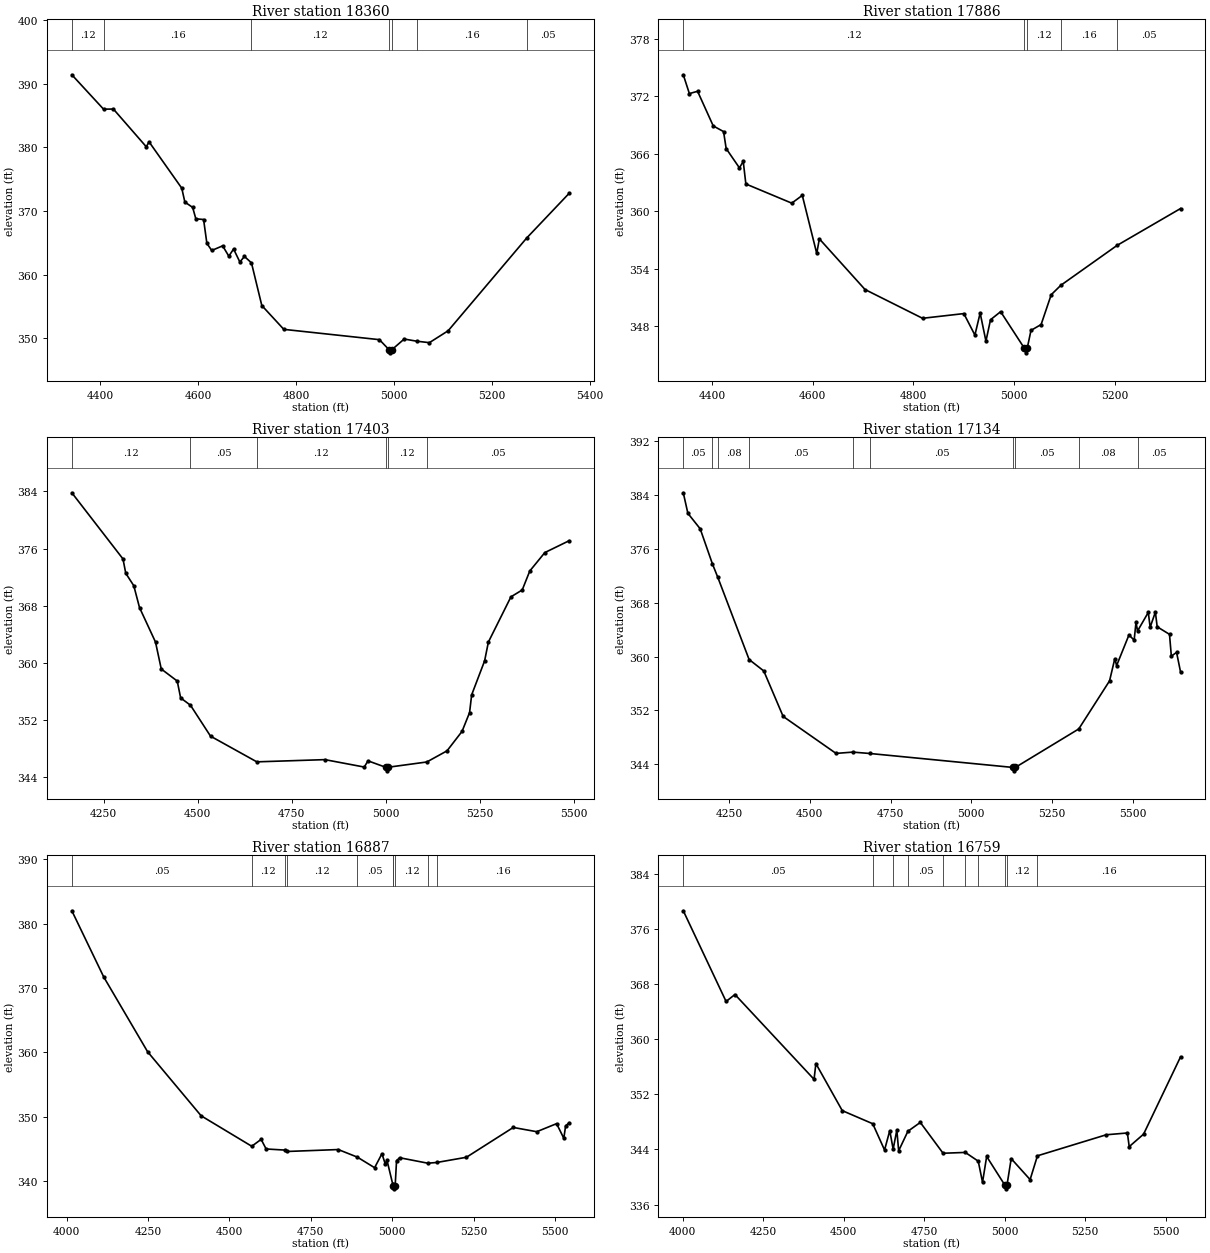
Type RM Length L Ch R = 1,18360,474,474,474
BEGIN DESCRIPTION:
UNT 064 IN BOCR 33.0
END DESCRIPTION:
XS GIS Cut Line= 3
      3785895.21     10576863.92      3785357.00     10577137.36
      3785174.97     10577505.76
#Sta/Elev= 30
  4342.3  391.43  4406.9  386.03  4427.1  386.04  4494.2  380.11  4499.8  380.89
  4566.6  373.60  4572.9  371.42  4588.8  370.58  4595.3  368.79  4611.1  368.68
  4617.8  364.94  4627.7  363.81  4650.0  364.54  4662.6  362.91  4672.3  364.04
  4685.1  362.00  4694.5  362.87  4708.8  361.86  4729.9  355.16  4774.8  351.41
  4969.9  349.79  4989.4  348.22  4992.1  347.72  4995.4  348.22  5020.4  349.89
  5046.0  349.55  5071.8  349.32  5110.1  351.19  5270.1  365.75  5356.9  372.79
#Mann=7,-1,0
  4342.3    0.12       0  4406.9    0.16       0  4708.8    0.12       0
  4989.4    0.07       0  4995.4    0.12       0  5046.0    0.16       0
  5270.1    0.05       0
Bank Sta=4989.4,4995.4
Exp/Cntr=0.3,0.1

Type RM Length L Ch R = 1,17886,483,483,483
BEGIN DESCRIPTION:
UNT 064 IN BOCR 32.0
END DESCRIPTION:
XS GIS Cut Line= 3
      3785187.74     10576442.90      3785022.80     10577024.51
      3784983.81     10577405.78
#Sta/Elev= 30
  4342.9  374.23  4355.0  372.27  4371.3  372.51  4402.4  368.90  4422.9  368.31
  4428.1  366.54  4454.4  364.53  4462.0  365.20  4467.2  362.85  4558.4  360.85
  4579.3  361.66  4608.0  355.61  4613.2  357.13  4703.9  351.85  4818.2  348.85
  4900.2  349.34  4922.2  347.10  4932.6  349.40  4944.1  346.47  4953.2  348.70
  4973.3  349.54  5020.2  345.75  5023.0  345.25  5026.2  345.75  5033.6  347.59
  5053.7  348.20  5073.8  351.31  5092.9  352.29  5204.7  356.45  5330.7  360.29
#Mann=5,-1,0
  4342.9    0.12       0  5020.2    0.07       0  5026.2    0.12       0
  5092.9    0.16       0  5204.7    0.05       0
Bank Sta=5020.2,5026.2
Exp/Cntr=0.3,0.1

Type RM Length L Ch R = 1,17403,269,269,269
BEGIN DESCRIPTION:
UNT 064 IN BOCR 31.0
END DESCRIPTION:
XS GIS Cut Line= 3
      3784901.30     10576364.75      3784649.54     10576768.44
      3784671.24     10577614.80
#Sta/Elev= 30
  4165.6  383.81  4301.6  374.54  4309.0  372.53  4330.3  370.79  4345.6  367.72
  4388.1  362.89  4403.4  359.12  4445.9  357.43  4454.9  355.07  4481.1  354.04
  4534.4  349.71  4657.5  346.11  4838.6  346.42  4943.2  345.38  4953.2  346.25
  5000.2  345.35  5003.0  344.85  5006.2  345.35  5109.5  346.09  5163.3  347.65
  5203.3  350.38  5223.3  353.01  5228.8  355.49  5263.3  360.26  5273.3  362.89
  5333.3  369.23  5363.3  370.19  5383.4  372.85  5423.4  375.43  5488.0  377.09
#Mann=6,-1,0
  4165.6    0.12       0  4481.1    0.05       0  4657.5    0.12       0
  5000.2    0.07       0  5006.2    0.12       0  5109.5    0.05       0
Bank Sta=5000.2,5006.2
Exp/Cntr=0.3,0.1

Type RM Length L Ch R = 1,17134,247,247,247
BEGIN DESCRIPTION:
Mapping XS 898e1ba5
END DESCRIPTION:
XS GIS Cut Line= 2
      3784831.82     10576373.49      3784098.97     10577726.45
#Sta/Elev= 30
  4108.7  384.33  4122.9  381.28  4161.0  378.98  4199.1  373.74  4215.3  371.80
  4312.4  359.57  4357.8  357.87  4417.7  351.12  4581.3  345.63  4633.1  345.82
  4685.1  345.62  5129.9  343.54  5132.7  343.04  5135.9  343.54  5332.4  349.26
  5427.7  356.40  5443.9  359.69  5449.6  358.68  5487.7  363.21  5503.8  362.45
  5509.5  365.07  5514.5  363.82  5547.6  366.57  5553.3  364.36  5569.5  366.61
  5575.1  364.43  5613.2  363.31  5618.9  360.07  5635.1  360.63  5647.4  357.72
#Mann=10,-1,0
  4108.7    0.05       0  4199.1    0.12       0  4215.3    0.08       0
  4312.4    0.05       0  4633.1    0.12       0  4685.1    0.05       0
  5129.9    0.04       0  5135.9    0.05       0  5332.4    0.08       0
  5514.5    0.05       0
Bank Sta=5129.9,5135.9
Exp/Cntr=0.3,0.1

Type RM Length L Ch R = 1,16887,128,128,128
BEGIN DESCRIPTION:
UNT 064 IN BOCR 30.0
END DESCRIPTION:
XS GIS Cut Line= 2
      3784666.88     10576343.13      3783968.14     10577701.55
#Sta/Elev= 30
  4015.7  382.00  4113.7  371.72  4248.5  360.11  4412.9  350.17  4568.4  345.44
  4597.2  346.51  4612.5  345.02  4669.2  344.85  4676.5  344.63  4834.2  344.93
  4892.9  343.75  4945.8  342.11  4968.3  344.28  4978.2  342.74  4983.9  343.25
  5001.1  339.63  5003.0  339.33  5005.8  338.83  5009.0  339.33  5013.2  343.21
  5022.6  343.66  5109.2  342.81  5136.3  342.92  5227.8  343.73  5371.8  348.36
  5443.9  347.70  5504.8  348.95  5527.0  346.68  5532.6  348.61  5543.3  349.08
#Mann=10,-1,0
  4015.7    0.05       0  4568.4    0.12       0  4669.2    0.16       0
  4676.5    0.12       0  4892.9    0.05       0  5001.1    0.12       0
  5003.0    0.03       0  5009.0    0.12       0  5109.2    0.08       0
  5136.3    0.16       0
Bank Sta=5003,5009
Exp/Cntr=0.3,0.1

Type RM Length L Ch R = 1,16759,351,351,351
BEGIN DESCRIPTION:
Mapping XS 27d6bb27
END DESCRIPTION:
XS GIS Cut Line= 2
      3784580.10     10576312.69      3783846.59     10577671.21
#Sta/Elev= 30
  4002.1  378.61  4135.0  365.46  4162.5  366.47  4408.1  354.17  4413.8  356.45
  4495.7  349.63  4590.3  347.73  4627.0  343.92  4643.2  346.73  4653.7  344.04
  4665.1  346.81  4670.8  343.81  4699.5  346.64  4738.0  347.92  4808.7  343.45
  4877.7  343.57  4917.9  342.30  4931.2  339.24  4944.0  342.98  5001.0  338.79
  5003.7  338.29  5007.0  338.79  5020.2  342.67  5078.9  339.63  5101.7  343.08
  5315.3  346.13  5380.9  346.39  5386.6  344.41  5431.2  346.22  5546.0  357.43
#Mann=10,-1,0
  4002.1    0.05       0  4590.3    0.16       0  4653.7    0.12       0
  4699.5    0.05       0  4808.7    0.16       0  4877.7    0.05       0
  4917.9    0.12       0  5001.0    0.07       0  5007.0    0.12       0
  5101.7    0.16       0
Bank Sta=5001,5007
Exp/Cntr=0.3,0.1

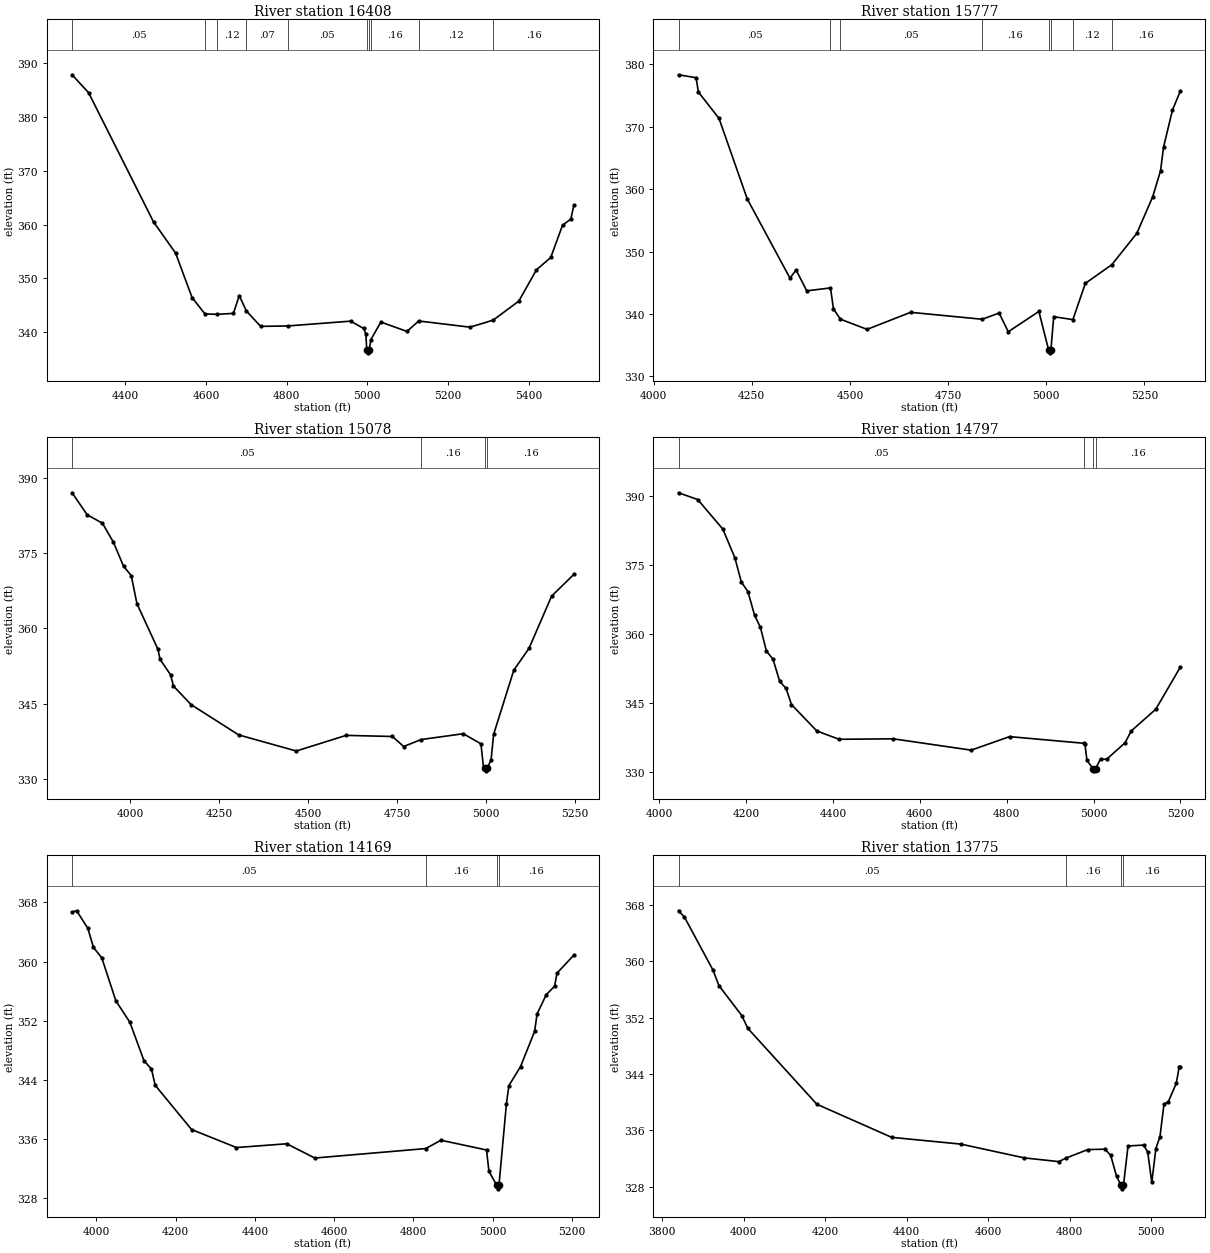
Type RM Length L Ch R = 1,16408,631,631,631
BEGIN DESCRIPTION:
UNT 064 IN BOCR 29.0
END DESCRIPTION:
XS GIS Cut Line= 3
      3784099.62     10576410.16      3783849.61     10577110.19
      3783549.63     10577510.16
#Sta/Elev= 30
  4268.4  387.84  4309.3  384.51  4470.2  360.50  4524.9  354.70  4565.8  346.42
  4597.6  343.40  4626.6  343.32  4668.2  343.49  4682.6  346.79  4700.4  343.93
  4735.6  341.08  4803.1  341.16  4958.6  342.05  4990.5  340.70  4996.3  339.69
  4998.6  336.66  5001.4  336.16  5004.6  336.66  5008.6  338.60  5033.6  341.88
  5098.2  340.14  5127.3  342.08  5254.4  340.93  5311.8  342.24  5375.3  345.77
  5419.0  351.59  5454.4  353.88  5483.6  359.87  5504.4  361.03  5511.7  363.63
#Mann=10,-1,0
  4268.4    0.05       0  4597.6    0.07       0  4626.6    0.12       0
  4700.4    0.07       0  4803.1    0.05       0  4998.6    0.03       0
  5004.6    0.05       0  5008.6    0.16       0  5127.3    0.12       0
  5311.8    0.16       0
Bank Sta=4998.6,5004.6
Exp/Cntr=0.3,0.1

Type RM Length L Ch R = 1,15777,699,699,699
BEGIN DESCRIPTION:
UNT 064 IN BOCR 28.0
END DESCRIPTION:
XS GIS Cut Line= 3
      3783899.60     10576410.20      3783449.61     10577160.19
      3783499.60     10577560.15
#Sta/Elev= 30
  4063.6  378.32  4108.3  377.85  4114.1  375.56  4166.6  371.34  4238.5  358.44
  4347.4  345.74  4362.9  347.06  4390.1  343.71  4450.5  344.18  4458.1  340.82
  4475.8  339.17  4543.7  337.54  4654.5  340.27  4836.6  339.16  4879.9  340.15
  4903.2  337.16  4981.1  340.41  5005.8  334.28  5008.5  333.78  5011.8  334.28
  5018.9  339.57  5067.7  339.10  5099.5  344.91  5167.0  347.91  5230.5  352.92
  5270.8  358.75  5291.0  362.96  5298.5  366.71  5321.2  372.65  5341.3  375.71
#Mann=8,-1,0
  4063.6    0.05       0  4450.5    0.12       0  4475.8    0.05       0
  4836.6    0.16       0  5005.8    0.07       0  5011.8    0.16       0
  5067.7    0.12       0  5167.0    0.16       0
Bank Sta=5005.8,5011.8
Exp/Cntr=0.3,0.1

Type RM Length L Ch R = 1,15078,281,281,281
BEGIN DESCRIPTION:
UNT 064 IN BOCR 27.0
END DESCRIPTION:
XS GIS Cut Line= 3
      3783765.84     10576159.48      3783222.28     10577119.59
      3782997.68     10577326.53
#Sta/Elev= 30
  3837.4  387.02  3879.5  382.66  3922.7  380.95  3953.1  377.23  3981.9  372.40
  4003.6  370.53  4019.5  364.94  4078.6  355.85  4084.4  353.85  4114.0  350.77
  4121.9  348.55  4171.5  344.85  4305.2  338.81  4466.8  335.61  4606.8  338.72
  4736.6  338.50  4768.4  336.50  4817.2  337.89  4935.8  339.05  4985.2  337.04
  4992.6  332.24  4996.4  332.16  4999.1  331.66  5002.4  332.16  5013.6  333.79
  5020.9  338.94  5077.6  351.72  5120.2  356.05  5183.7  366.45  5246.1  370.77
#Mann=4,-1,0
  3837.4    0.05       0  4817.2    0.16       0  4996.4    0.07       0
  5002.4    0.16       0
Bank Sta=4996.4,5002.4
Exp/Cntr=0.3,0.1

Type RM Length L Ch R = 1,14797,628,628,628
BEGIN DESCRIPTION:
UNT 064 IN BOCR 26.0
END DESCRIPTION:
XS GIS Cut Line= 3
      3783649.61     10576110.18      3783149.61     10576910.19
      3782999.63     10577060.16
#Sta/Elev= 30
  4044.4  390.69  4088.6  389.22  4146.4  382.79  4174.1  376.57  4188.9  371.31
  4204.2  369.18  4219.5  364.06  4233.1  361.40  4246.6  356.31  4262.0  354.48
  4277.3  349.70  4292.0  348.15  4304.4  344.65  4362.8  338.90  4414.1  337.09
  4539.1  337.19  4718.3  334.73  4806.8  337.67  4978.1  336.22  4980.1  336.13
  4984.9  332.48  4998.9  330.73  5001.7  330.23  5004.9  330.73  5016.1  332.81
  5030.2  332.74  5072.7  336.34  5086.8  338.90  5143.4  343.63  5199.9  352.78
#Mann=4,-1,0
  4044.4    0.05       0  4978.1    0.16       0  4998.9    0.07       0
  5004.9    0.16       0
Bank Sta=4998.9,5004.9
Exp/Cntr=0.3,0.1

Type RM Length L Ch R = 1,14169,394,394,394
BEGIN DESCRIPTION:
UNT 064 IN BOCR 25.0
END DESCRIPTION:
XS GIS Cut Line= 3
      3783473.77     10575998.11      3782787.97     10576640.92
      3782597.01     10576905.93
#Sta/Elev= 30
  3938.7  366.72  3950.2  366.87  3978.5  364.50  3992.6  361.92  4013.7  360.50
  4049.3  354.67  4084.5  351.79  4120.1  346.60  4139.1  345.44  4148.5  343.25
  4240.3  337.26  4353.6  334.82  4480.6  335.33  4551.4  333.40  4831.1  334.68
  4869.9  335.81  4984.8  334.49  4990.9  331.62  5010.3  329.73  5013.1  329.23
  5016.3  329.73  5035.1  340.76  5041.3  343.20  5070.7  345.78  5106.3  350.55
  5112.4  352.89  5135.7  355.52  5156.6  356.65  5162.8  358.43  5205.3  360.87
#Mann=4,-1,0
  3938.7    0.05       0  4831.1    0.16       0  5010.3    0.07       0
  5016.3    0.16       0
Bank Sta=5010.3,5016.3
Exp/Cntr=0.3,0.1

Type RM Length L Ch R = 1,13775,854,854,854
BEGIN DESCRIPTION:
UNT 064 IN BOCR 24.0
END DESCRIPTION:
XS GIS Cut Line= 3
      3783349.60     10575760.20      3782549.61     10576560.19
      3782549.61     10576660.24
#Sta/Elev= 30
  3840.1  367.21  3854.2  366.36  3924.9  358.75  3939.1  356.58  3995.6  352.29
  4009.8  350.51  4179.5  339.70  4363.3  334.99  4533.0  334.03  4688.6  332.07
  4773.5  331.54  4790.3  332.03  4844.2  333.25  4886.6  333.31  4900.7  332.42
  4914.9  329.46  4926.0  328.17  4928.8  327.67  4932.0  328.17  4943.2  333.77
  4981.5  333.89  4991.5  332.89  5001.5  328.58  5011.5  333.40  5021.5  335.08
  5031.5  339.76  5041.5  339.99  5061.5  342.67  5069.0  345.06  5071.5  345.06
#Mann=4,-1,0
  3840.1    0.05       0  4790.3    0.16       0  4926.0    0.07       0
  4932.0    0.16       0
Bank Sta=4926,4932
Exp/Cntr=0.3,0.1