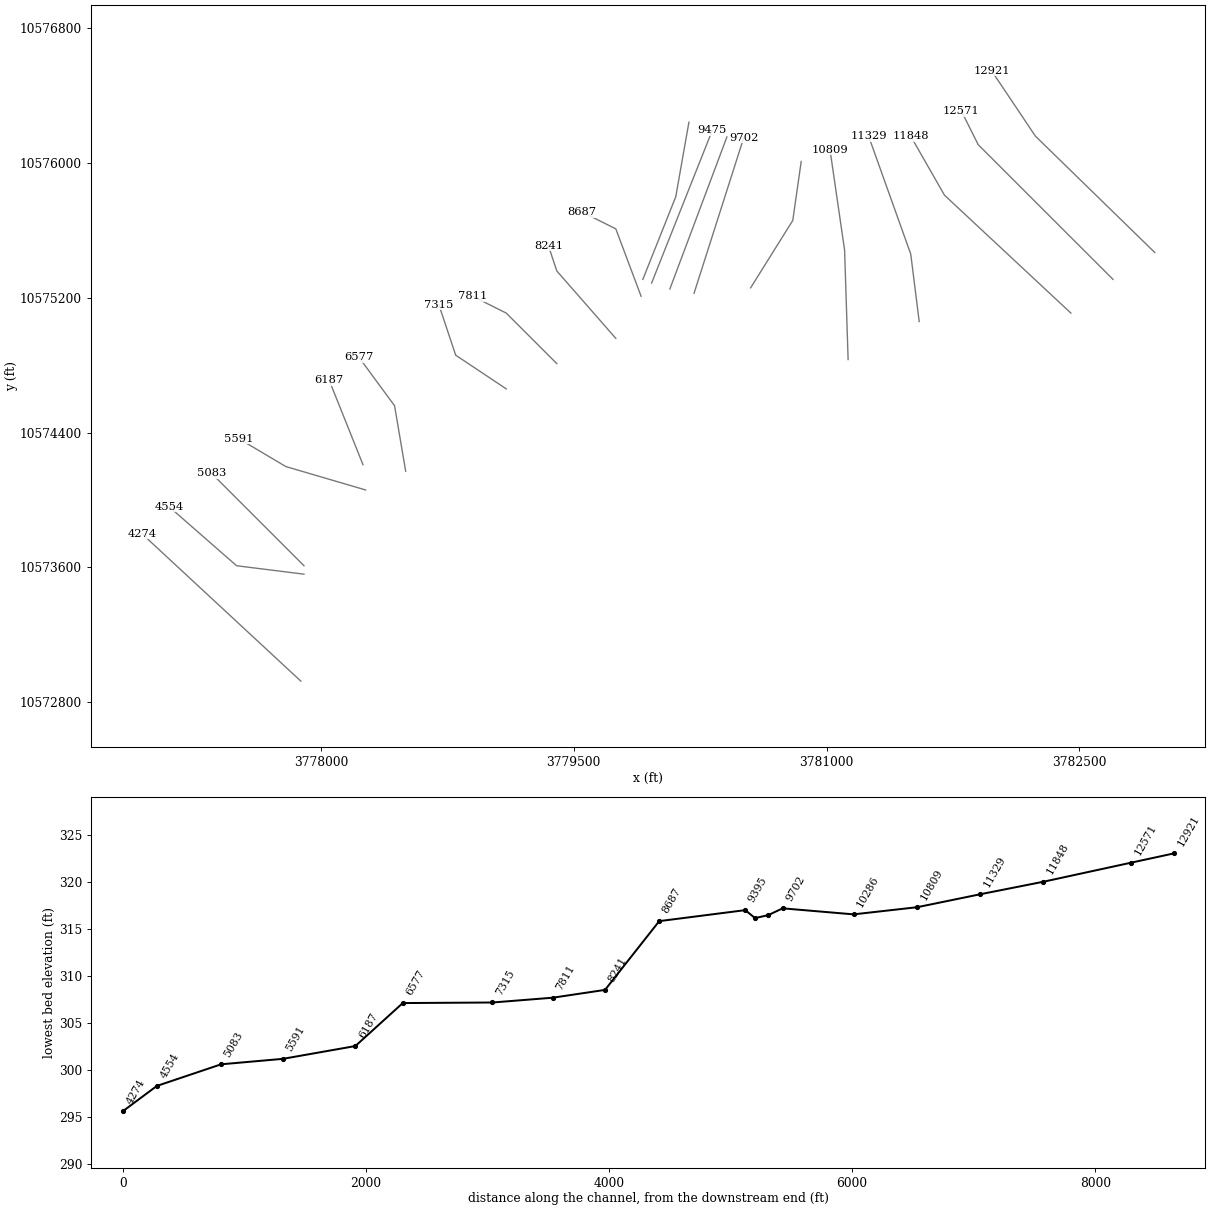
HEC-RAS study UNT 064 IN BOCR.prj: UNT 064 IN BOCR Base Level Engineering

--- UNT 064 IN BOCR.g01 (geometry) --- (continued)

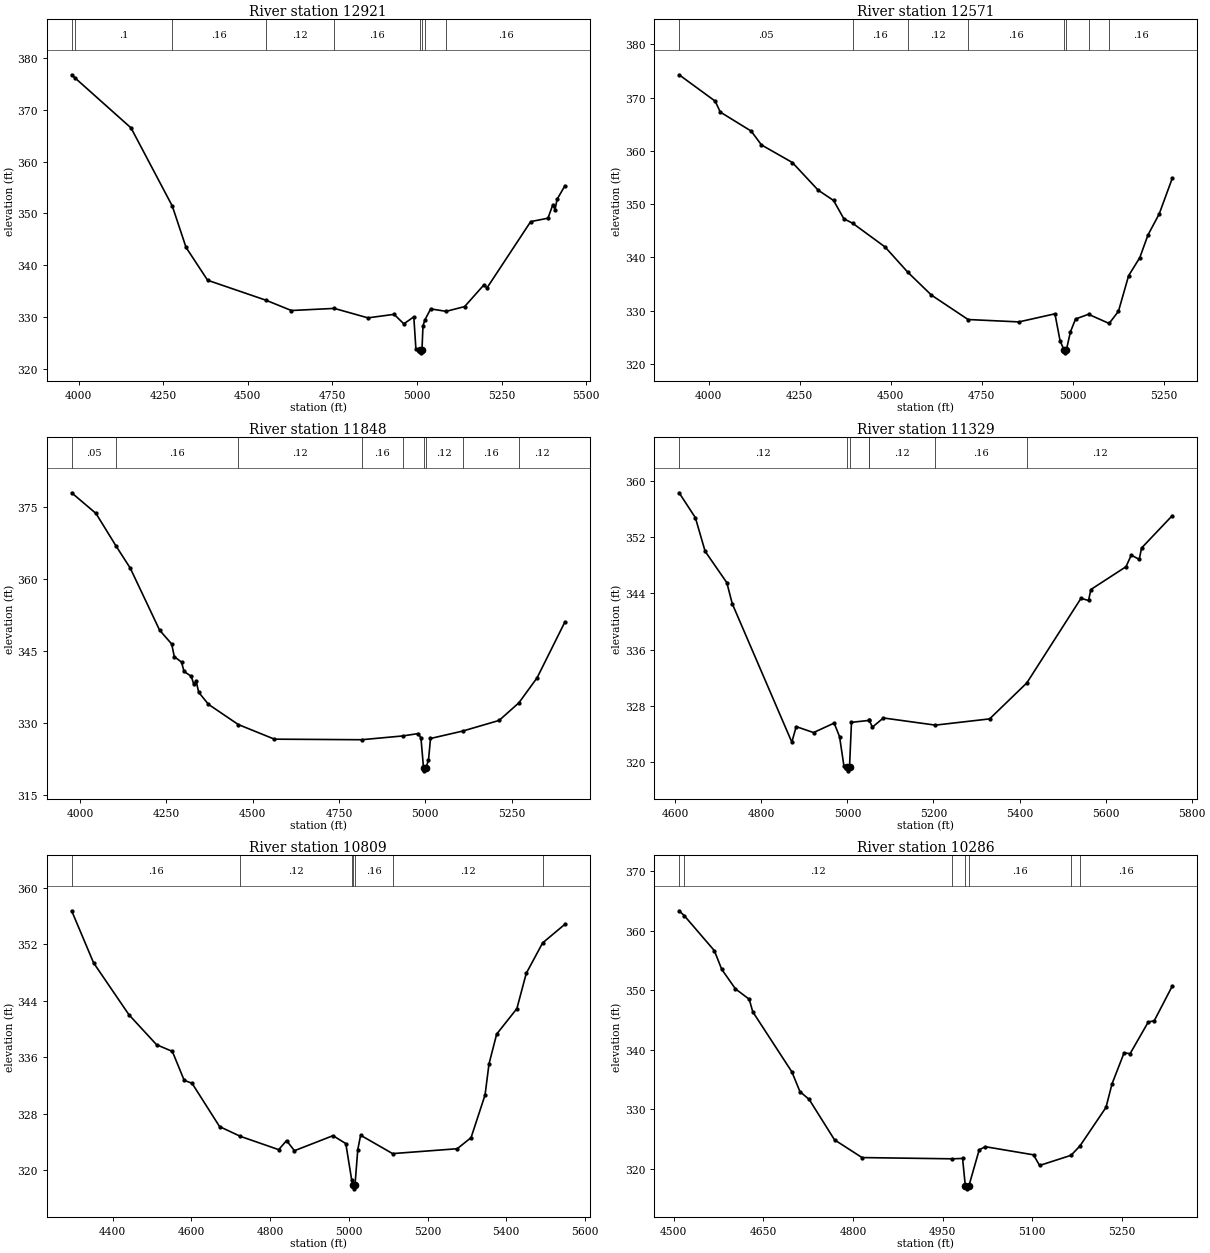
Type RM Length L Ch R = 1,12921,350,350,350
BEGIN DESCRIPTION:
UNT 064 IN BOCR 23.0
END DESCRIPTION:
XS GIS Cut Line= 3
      3782947.38     10575469.86      3782239.03     10576160.85
      3781978.61     10576549.75
#Sta/Elev= 30
  3979.5  376.80  3990.0  376.16  4155.0  366.53  4277.0  351.42  4317.6  343.43
  4381.3  337.09  4553.3  333.24  4628.8  331.24  4755.5  331.65  4855.1  329.82
  4932.3  330.50  4961.1  328.66  4990.6  330.01  4996.7  323.86  5008.7  323.56
  5011.4  323.06  5014.7  323.56  5017.7  328.27  5023.4  329.44  5040.5  331.55
  5086.3  331.08  5140.8  332.00  5197.8  336.20  5206.8  335.60  5335.9  348.42
  5386.9  349.08  5401.5  351.69  5407.9  350.71  5414.0  352.74  5437.1  355.34
#Mann=9,-1,0
  3979.5    0.05       0  3990.0     0.1       0  4277.0    0.16       0
  4553.3    0.12       0  4755.5    0.16       0  5008.7    0.07       0
  5014.7    0.16       0  5023.4    0.12       0  5086.3    0.16       0
Bank Sta=5008.7,5014.7
Exp/Cntr=0.3,0.1

Type RM Length L Ch R = 1,12571,723,723,723
BEGIN DESCRIPTION:
UNT 064 IN BOCR 22.0
END DESCRIPTION:
XS GIS Cut Line= 3
      3782699.62     10575310.17      3781899.61     10576110.19
      3781799.61     10576310.19
#Sta/Elev= 30
  3919.1  374.31  4018.1  369.36  4032.3  367.30  4117.1  363.73  4145.4  361.13
  4230.2  357.83  4301.0  352.64  4343.4  350.70  4371.7  347.26  4396.1  346.41
  4484.8  341.97  4547.5  337.21  4612.1  332.93  4712.8  328.34  4852.5  327.89
  4951.5  329.41  4965.6  324.34  4976.8  322.58  4979.5  322.08  4982.8  322.58
  4993.9  325.99  5008.1  328.44  5043.7  329.32  5100.4  327.60  5126.0  329.89
  5153.9  336.57  5184.7  339.98  5207.0  344.21  5237.8  348.16  5274.1  354.92
#Mann=8,-1,0
  3919.1    0.05       0  4396.1    0.16       0  4547.5    0.12       0
  4712.8    0.16       0  4976.8    0.07       0  4982.8    0.16       0
  5043.7    0.12       0  5100.4    0.16       0
Bank Sta=4976.8,4982.8
Exp/Cntr=0.3,0.1

Type RM Length L Ch R = 1,11848,519,519,519
BEGIN DESCRIPTION:
UNT 064 IN BOCR 21.0
END DESCRIPTION:
XS GIS Cut Line= 3
      3782449.60     10575110.20      3781699.61     10575810.19
      3781499.61     10576160.18
#Sta/Elev= 30
  3975.5  377.97  4046.1  373.66  4104.5  366.84  4145.2  362.29  4230.3  349.36
  4265.4  346.46  4272.8  343.83  4293.8  342.70  4301.1  340.75  4322.1  339.74
  4329.4  338.05  4336.3  338.72  4343.6  336.41  4371.9  333.90  4458.1  329.70
  4562.9  326.65  4815.3  326.53  4934.9  327.32  4980.1  327.82  4987.5  326.87
  4995.0  320.55  4997.7  320.05  5001.0  320.55  5009.3  322.25  5015.1  326.79
  5108.6  328.34  5213.8  330.55  5271.2  334.22  5323.9  339.43  5404.5  351.06
#Mann=9,-1,0
  3975.5    0.05       0  4104.5    0.16       0  4458.1    0.12       0
  4815.3    0.16       0  4934.9    0.12       0  4995.0    0.07       0
  5001.0    0.12       0  5108.6    0.16       0  5271.2    0.12       0
Bank Sta=4995,5001
Exp/Cntr=0.3,0.1

Type RM Length L Ch R = 1,11329,520,520,520
BEGIN DESCRIPTION:
UNT 064 IN BOCR 20.0
END DESCRIPTION:
XS GIS Cut Line= 3
      3781549.61     10575060.19      3781499.61     10575460.19
      3781249.62     10576160.17
#Sta/Elev= 30
  4608.8  358.32  4646.6  354.77  4669.3  349.98  4719.7  345.52  4732.3  342.52
  4870.8  322.80  4880.9  325.02  4921.2  324.17  4969.1  325.52  4981.7  323.59
  4991.8  319.42  4998.8  319.22  5001.6  318.72  5004.8  319.22  5009.4  325.63
  5050.0  325.90  5050.5  325.93  5058.1  324.95  5083.6  326.25  5204.4  325.23
  5330.5  326.12  5416.9  331.24  5542.8  343.29  5560.4  342.98  5565.7  344.54
  5647.4  347.79  5659.7  349.45  5678.2  348.82  5683.5  350.45  5755.2  355.08
#Mann=7,-1,0
  4608.8    0.12       0  4998.8    0.07       0  5004.8    0.12       0
  5050.0    0.16       0  5050.5    0.12       0  5204.4    0.16       0
  5416.9    0.12       0
Bank Sta=4998.8,5004.8
Exp/Cntr=0.3,0.1

Type RM Length L Ch R = 1,10809,523,523,523
BEGIN DESCRIPTION:
UNT 064 IN BOCR 19.0
END DESCRIPTION:
XS GIS Cut Line= 3
      3781127.92     10574834.47      3781107.09     10575483.77
      3781020.29     10576080.96
#Sta/Elev= 30
  4295.9  356.72  4351.7  349.34  4441.7  341.98  4511.7  337.75  4551.8  336.80
  4581.8  332.71  4601.8  332.29  4671.8  326.15  4724.8  324.77  4821.9  322.89
  4841.9  324.17  4861.9  322.74  4959.9  324.87  4992.4  323.75  5007.2  318.64
  5009.7  317.84  5012.4  317.34  5015.7  317.84  5022.8  322.89  5030.0  324.93
  5111.3  322.33  5275.4  323.02  5310.6  324.59  5346.1  330.63  5356.2  335.04
  5375.6  339.25  5427.0  342.87  5450.8  347.86  5492.4  352.17  5549.0  354.81
#Mann=7,-1,0
  4295.9    0.16       0  4724.8    0.12       0  5007.2    0.16       0
  5009.7    0.07       0  5015.7    0.16       0  5111.3    0.12       0
  5492.4    0.16       0
Bank Sta=5009.7,5015.7
Exp/Cntr=0.3,0.1

Type RM Length L Ch R = 1,10286,584,584,584
BEGIN DESCRIPTION:
UNT 064 IN BOCR 18.0
END DESCRIPTION:
XS GIS Cut Line= 3
      3780549.62     10575260.21      3780799.61     10575660.19
      3780849.60     10576010.16
#Sta/Elev= 30
  4509.2  363.35  4518.1  362.50  4568.1  356.65  4580.5  353.50  4603.5  350.21
  4626.5  348.47  4632.4  346.36  4697.9  336.24  4711.4  332.92  4726.7  331.63
  4769.2  324.82  4815.2  321.84  4965.6  321.63  4983.4  321.69  4988.0  317.08
  4990.7  316.58  4994.0  317.08  5011.2  323.14  5021.3  323.67  5102.1  322.30
  5112.2  320.51  5164.9  322.22  5179.8  323.80  5223.3  330.27  5233.4  334.23
  5253.6  339.45  5263.7  339.32  5294.0  344.63  5304.1  344.86  5334.4  350.72
#Mann=7,-1,0
  4509.2    0.16       0  4518.1    0.12       0  4965.6    0.16       0
  4988.0    0.07       0  4994.0    0.16       0  5164.9    0.12       0
  5179.8    0.16       0
Bank Sta=4988,4994
Exp/Cntr=0.3,0.1

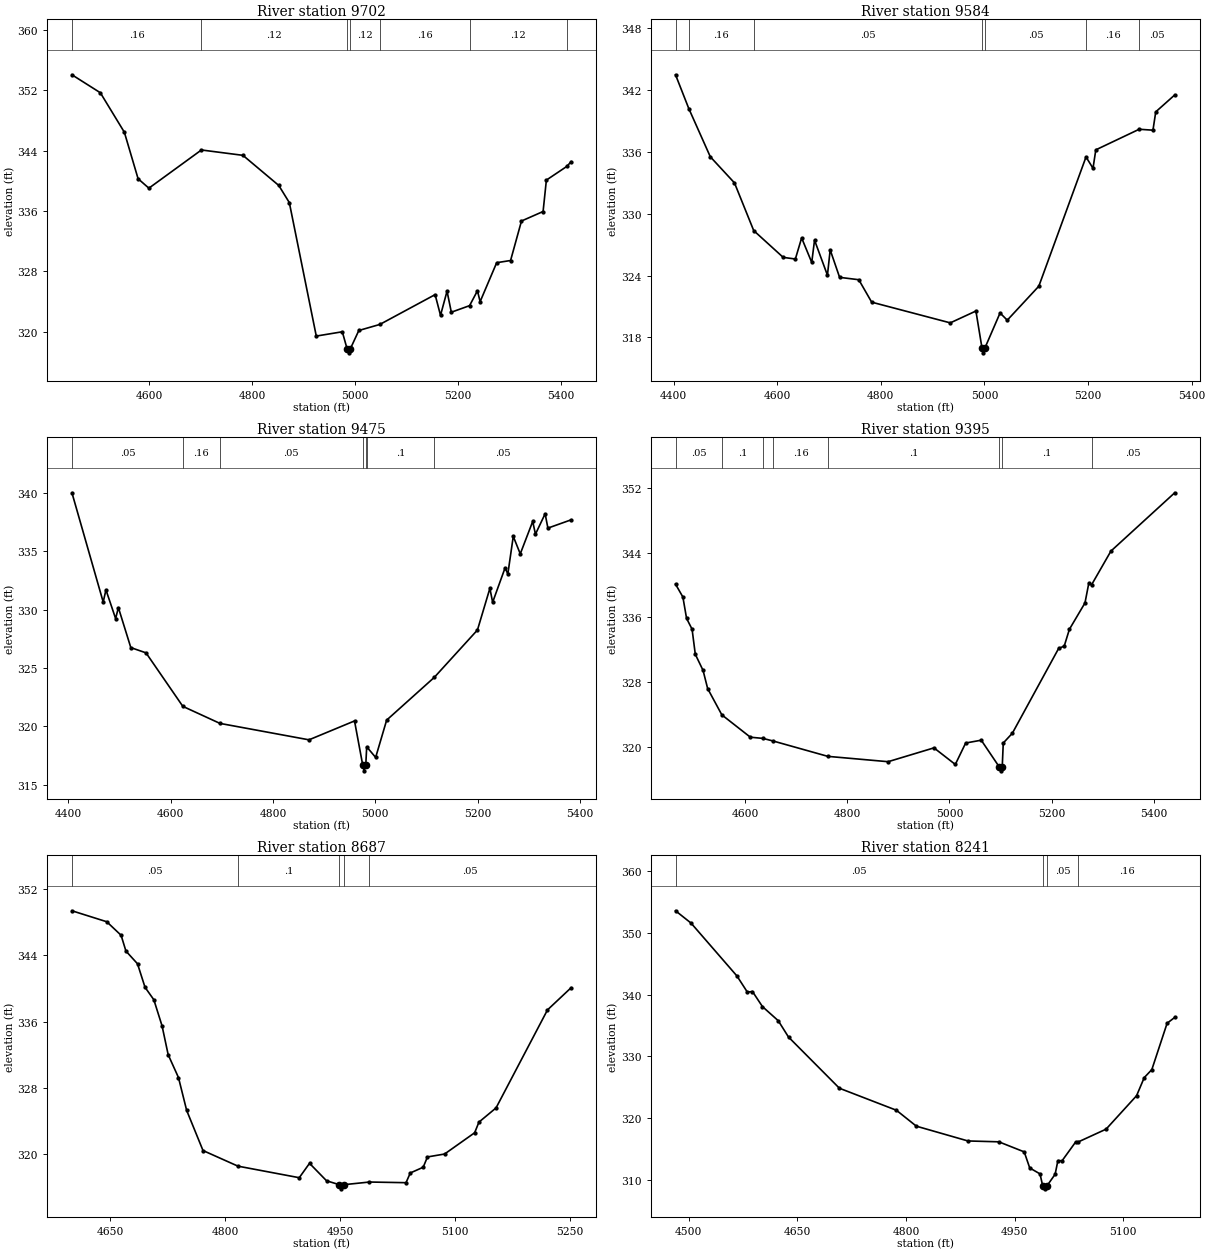
Type RM Length L Ch R = 1,9702,118,118,118
BEGIN DESCRIPTION:
Mapping XS befceec0
END DESCRIPTION:
XS GIS Cut Line= 2
      3780213.78     10575227.64      3780508.90     10576152.07
#Sta/Elev= 30
  4449.7  354.05  4504.9  351.67  4551.6  346.44  4578.3  340.28  4599.3  339.03
  4701.4  344.09  4782.1  343.38  4851.8  339.39  4872.3  337.12  4924.7  319.44
  4975.3  320.01  4984.7  317.72  4987.5  317.22  4990.7  317.72  5007.4  320.18
  5048.2  320.98  5155.7  324.93  5166.2  322.19  5178.9  325.39  5187.2  322.60
  5222.7  323.47  5238.0  325.44  5243.2  324.00  5275.4  329.16  5302.4  329.45
  5323.6  334.68  5365.6  335.94  5372.0  340.10  5412.1  341.93  5420.1  342.55
#Mann=7,-1,0
  4449.7    0.16       0  4701.4    0.12       0  4984.7    0.07       0
  4990.7    0.12       0  5048.2    0.16       0  5222.7    0.12       0
  5412.1    0.16       0
Bank Sta=4984.7,4990.7
Exp/Cntr=0.3,0.1

Type RM Length L Ch R = 1,9584,109,109,109
BEGIN DESCRIPTION:
UNT 064 IN BOCR 17.0
END DESCRIPTION:
XS GIS Cut Line= 2
      3780070.54     10575253.66      3780408.85     10576155.81
#Sta/Elev= 30
  4403.7  343.50  4429.3  340.22  4470.8  335.54  4517.5  333.00  4554.6  328.37
  4611.5  325.77  4635.0  325.61  4647.1  327.66  4666.6  325.28  4672.0  327.44
  4696.9  324.04  4702.2  326.50  4720.4  323.83  4757.4  323.60  4782.3  321.42
  4934.0  319.41  4983.5  320.56  4995.1  317.00  4997.8  316.50  5001.1  317.00
  5030.1  320.37  5044.0  319.67  5104.9  322.97  5196.0  335.52  5209.5  334.42
  5214.9  336.21  5298.6  338.21  5325.2  338.12  5330.6  339.90  5367.2  341.54
#Mann=7,-1,0
  4403.7    0.05       0  4429.3    0.16       0  4554.6    0.05       0
  4995.1    0.04       0  5001.1    0.05       0  5196.0    0.16       0
  5298.6    0.05       0
Bank Sta=4995.1,5001.1
Exp/Cntr=0.3,0.1

Type RM Length L Ch R = 1,9475,80,80,80
BEGIN DESCRIPTION:
UNT 064 IN BOCR 16.0
END DESCRIPTION:
XS GIS Cut Line= 2
      3779962.04     10575288.41      3780322.20     10576195.31
#Sta/Elev= 30
  4407.0  340.03  4468.1  330.66  4473.5  331.70  4492.4  329.24  4497.8  330.18
  4522.1  326.75  4551.8  326.30  4623.8  321.71  4696.3  320.25  4870.4  318.84
  4959.4  320.46  4975.4  316.68  4978.1  316.18  4981.4  316.68  4983.2  318.24
  5000.7  317.33  5022.2  320.53  5115.4  324.20  5199.7  328.26  5224.0  331.83
  5229.4  330.64  5253.7  333.59  5259.1  333.06  5269.7  336.29  5283.4  334.79
  5307.7  337.57  5313.1  336.48  5332.0  338.23  5337.4  337.00  5382.8  337.71
#Mann=7,-1,0
  4407.0    0.05       0  4623.8    0.16       0  4696.3    0.05       0
  4975.4    0.07       0  4981.4    0.05       0  4983.2     0.1       0
  5115.4    0.05       0
Bank Sta=4975.4,4981.4
Exp/Cntr=0.3,0.1

Type RM Length L Ch R = 1,9395,708,708,708
BEGIN DESCRIPTION:
Mapping XS 1129bb16
END DESCRIPTION:
XS GIS Cut Line= 3
      3779909.96     10575310.12      3780105.27     10575800.55
      3780183.39     10576243.22
#Sta/Elev= 30
  4463.6  340.11  4478.0  338.52  4485.2  335.88  4496.0  334.54  4502.3  331.44
  4517.5  329.45  4526.5  327.20  4554.3  323.95  4610.1  321.19  4634.8  321.04
  4654.6  320.72  4761.8  318.82  4879.8  318.16  4969.6  319.87  5011.4  317.82
  5031.7  320.47  5062.2  320.82  5097.3  317.53  5100.0  317.03  5103.3  317.53
  5105.3  320.47  5123.1  321.68  5213.7  332.16  5224.7  332.46  5234.8  334.53
  5265.3  337.79  5272.9  340.27  5278.1  340.02  5316.1  344.20  5441.0  351.41
#Mann=8,-1,0
  4463.6    0.05       0  4554.3     0.1       0  4634.8    0.05       0
  4654.6    0.16       0  4761.8     0.1       0  5097.3    0.07       0
  5103.3     0.1       0  5278.1    0.05       0
Bank Sta=5097.3,5103.3
Exp/Cntr=0.3,0.1

Type RM Length L Ch R = 1,8687,446,446,446
BEGIN DESCRIPTION:
UNT 064 IN BOCR 15.0
END DESCRIPTION:
XS GIS Cut Line= 3
      3779899.63     10575210.14      3779749.61     10575610.19
      3779549.57     10575710.21
#Sta/Elev= 30
  4600.5  349.33  4645.9  348.01  4664.6  346.38  4670.9  344.48  4686.0  342.95
  4695.8  340.12  4707.3  338.62  4718.0  335.48  4726.0  332.00  4739.4  329.26
  4750.1  325.30  4771.4  320.47  4817.0  318.59  4896.9  317.20  4910.3  318.93
  4932.5  316.83  4949.1  316.36  4951.8  315.86  4955.1  316.36  4988.5  316.68
  5036.1  316.60  5041.7  317.77  5058.5  318.46  5064.1  319.70  5086.4  320.05
  5125.6  322.61  5131.2  323.89  5153.5  325.60  5220.6  337.40  5251.4  340.07
#Mann=5,-1,0
  4600.5    0.05       0  4817.0     0.1       0  4949.1    0.03       0
  4955.1     0.1       0  4988.5    0.05       0
Bank Sta=4949.1,4955.1
Exp/Cntr=0.3,0.1

Type RM Length L Ch R = 1,8241,430,430,430
BEGIN DESCRIPTION:
UNT 064 IN BOCR 14.0
END DESCRIPTION:
XS GIS Cut Line= 3
      3779749.61     10574960.19      3779399.61     10575360.19
      3779349.62     10575510.17
#Sta/Elev= 30
  4481.6  353.55  4503.0  351.56  4566.5  342.99  4580.8  340.39  4587.9  340.48
  4601.7  338.04  4623.5  335.76  4637.7  333.11  4708.0  324.83  4786.7  321.27
  4814.3  318.69  4885.5  316.30  4928.2  316.16  4963.3  314.53  4970.9  311.93
  4985.1  310.97  4988.8  309.05  4991.5  308.55  4994.8  309.05  5006.0  310.91
  5009.8  313.11  5015.7  313.11  5034.2  316.11  5037.9  316.14  5076.4  318.21
  5118.5  323.62  5129.1  326.55  5139.6  327.85  5160.7  335.35  5171.2  336.29
#Mann=4,-1,0
  4481.6    0.05       0  4988.8    0.03       0  4994.8    0.05       0
  5037.9    0.16       0
Bank Sta=4988.8,4994.8
Exp/Cntr=0.3,0.1

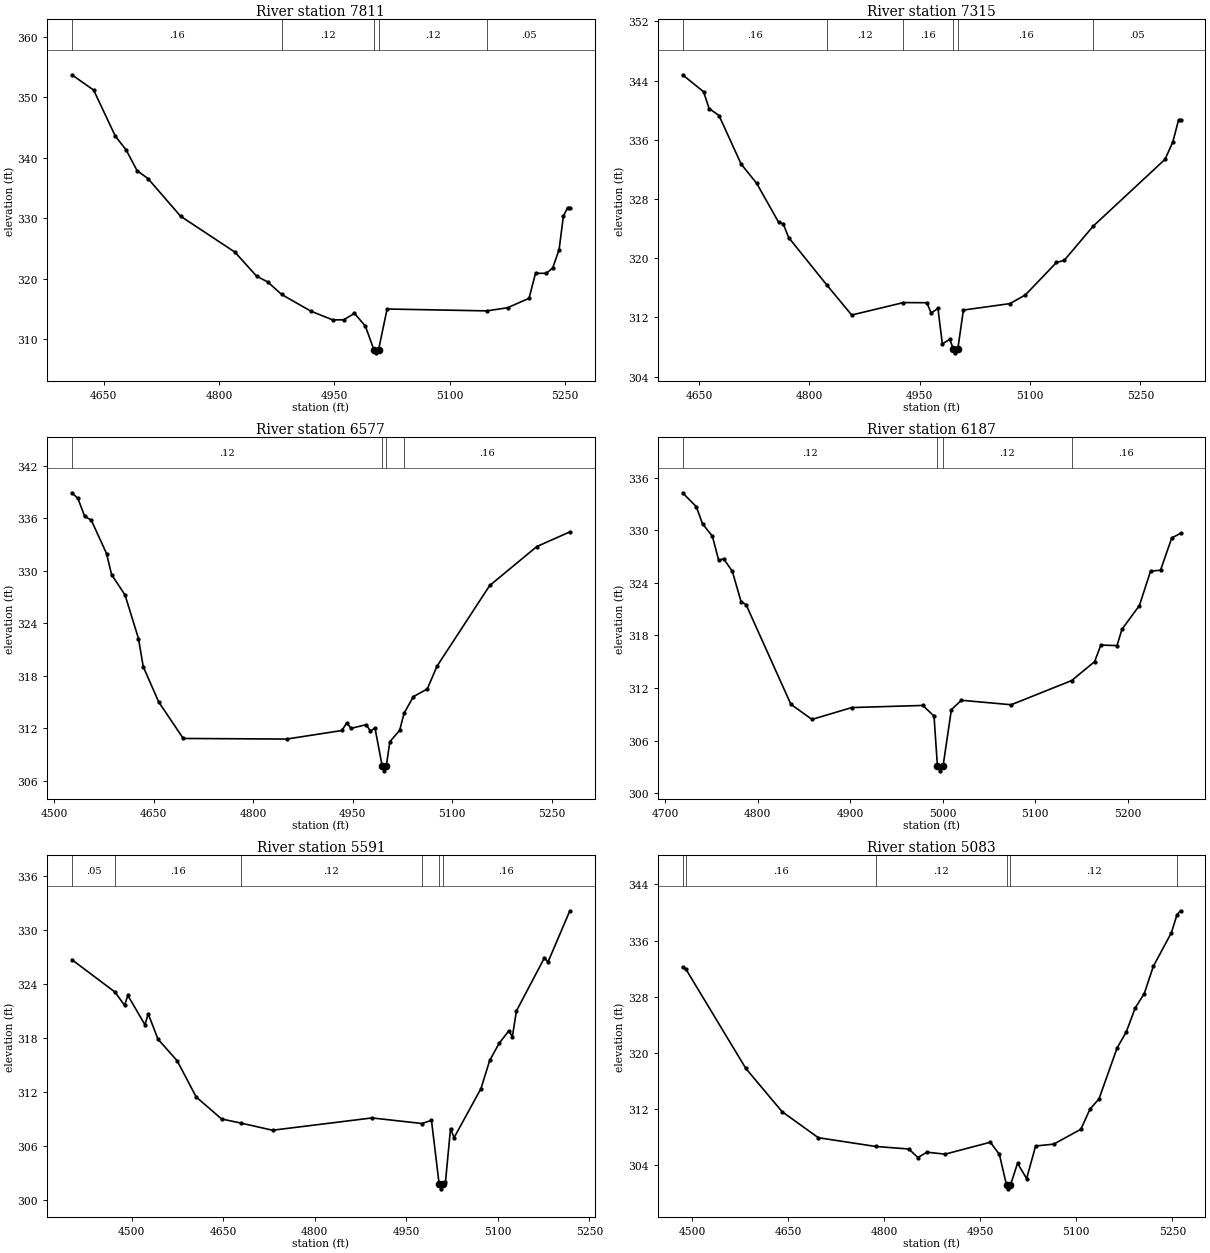
Type RM Length L Ch R = 1,7811,496,496,496
BEGIN DESCRIPTION:
UNT 064 IN BOCR 13.0
END DESCRIPTION:
XS GIS Cut Line= 3
      3779399.61     10574810.19      3779099.61     10575110.19
      3778899.59     10575210.20
#Sta/Elev= 30
  4608.4  353.71  4636.7  351.18  4665.0  343.55  4679.1  341.26  4693.3  337.84
  4707.4  336.55  4749.8  330.32  4820.5  324.38  4848.8  320.39  4863.0  319.46
  4881.4  317.37  4919.5  314.60  4947.8  313.17  4962.0  313.18  4976.1  314.25
  4990.2  312.15  5001.4  308.22  5004.1  307.72  5007.4  308.22  5018.5  314.97
  5148.4  314.66  5175.2  315.18  5203.2  316.74  5211.6  320.88  5225.5  320.87
  5233.9  321.74  5242.3  324.79  5247.9  330.34  5253.5  331.75  5256.3  331.75
#Mann=5,-1,0
  4608.4    0.16       0  4881.4    0.12       0  5001.4    0.07       0
  5007.4    0.12       0  5148.4    0.05       0
Bank Sta=5001.4,5007.4
Exp/Cntr=0.3,0.1

Type RM Length L Ch R = 1,7315,738,738,738
BEGIN DESCRIPTION:
UNT 064 IN BOCR 12.0
END DESCRIPTION:
XS GIS Cut Line= 3
      3779099.63     10574660.17      3778799.61     10574860.19
      3778699.61     10575160.18
#Sta/Elev= 30
  4627.7  344.78  4656.3  342.49  4663.8  340.22  4677.3  339.27  4707.3  332.72
  4728.4  330.12  4758.4  324.83  4764.4  324.67  4771.9  322.79  4823.5  316.41
  4857.6  312.32  4927.9  314.00  4959.7  313.98  4965.7  312.57  4974.8  313.23
  4980.8  308.42  4990.9  309.04  4995.8  307.71  4998.6  307.21  5001.8  307.71
  5009.4  312.99  5072.6  313.86  5093.7  315.04  5135.9  319.42  5146.4  319.70
  5185.8  324.33  5283.4  333.35  5294.0  335.69  5301.9  338.70  5304.5  338.70
#Mann=6,-1,0
  4627.7    0.16       0  4823.5    0.12       0  4927.9    0.16       0
  4995.8    0.07       0  5001.8    0.16       0  5185.8    0.05       0
Bank Sta=4995.8,5001.8
Exp/Cntr=0.3,0.1

Type RM Length L Ch R = 1,6577,390,390,390
BEGIN DESCRIPTION:
UNT 064 IN BOCR 11.0
END DESCRIPTION:
XS GIS Cut Line= 3
      3778502.92     10574171.25      3778436.95     10574560.16
      3778226.28     10574846.81
#Sta/Elev= 30
  4526.8  338.92  4535.9  338.27  4546.0  336.24  4556.1  335.78  4579.0  331.98
  4586.6  329.57  4606.9  327.24  4627.1  322.27  4634.3  319.05  4657.6  315.02
  4694.6  310.85  4850.3  310.78  4933.7  311.76  4941.0  312.66  4947.2  312.00
  4970.3  312.43  4976.5  311.68  4983.4  312.06  4994.4  307.65  4997.1  307.15
  5000.4  307.65  5005.8  310.48  5020.5  311.76  5027.3  313.74  5041.3  315.63
  5062.2  316.50  5076.8  319.10  5156.3  328.33  5227.3  332.78  5277.0  334.45
#Mann=4,-1,0
  4526.8    0.12       0  4994.4    0.07       0  5000.4    0.12       0
  5027.3    0.16       0
Bank Sta=4994.4,5000.4
Exp/Cntr=0.3,0.1

Type RM Length L Ch R = 1,6187,596,596,596
BEGIN DESCRIPTION:
UNT 064 IN BOCR 10.0
END DESCRIPTION:
XS GIS Cut Line= 3
      3778249.62     10574210.16      3778149.61     10574460.19
      3778049.59     10574710.23
#Sta/Elev= 30
  4718.7  334.26  4733.5  332.69  4740.3  330.73  4751.0  329.30  4757.8  326.57
  4763.2  326.74  4772.6  325.30  4782.0  321.85  4787.4  321.52  4835.9  310.16
  4858.7  308.44  4901.8  309.79  4978.6  310.03  4990.7  308.82  4994.4  303.08
  4997.2  302.58  5000.4  303.08  5009.5  309.56  5020.3  310.62  5074.2  310.11
  5139.6  312.87  5164.4  315.02  5171.1  316.91  5188.6  316.85  5194.0  318.72
  5212.8  321.41  5224.9  325.33  5235.7  325.44  5247.8  329.11  5257.3  329.64
#Mann=4,-1,0
  4718.7    0.12       0  4994.4    0.07       0  5000.4    0.12       0
  5139.6    0.16       0
Bank Sta=4994.4,5000.4
Exp/Cntr=0.3,0.1

Type RM Length L Ch R = 1,5591,508,508,508
BEGIN DESCRIPTION:
UNT 064 IN BOCR 9.0
END DESCRIPTION:
XS GIS Cut Line= 3
      3778264.98     10574060.10      3777791.90     10574198.99
      3777514.38     10574363.77
#Sta/Elev= 30
  4402.1  326.72  4472.8  323.11  4488.5  321.63  4493.7  322.75  4521.9  319.47
  4527.1  320.70  4543.2  317.87  4574.5  315.48  4605.7  311.45  4647.4  308.99
  4678.9  308.54  4730.8  307.74  4893.7  309.11  4975.6  308.49  4991.2  308.84
  5003.8  301.72  5006.5  301.22  5009.8  301.72  5014.1  301.96  5022.4  307.93
  5028.2  306.91  5072.3  312.38  5086.6  315.51  5102.2  317.43  5117.9  318.80
  5123.7  318.17  5130.4  321.02  5176.3  326.93  5182.1  326.46  5217.9  332.16
#Mann=6,-1,0
  4402.1    0.05       0  4472.8    0.16       0  4678.9    0.12       0
  4975.6    0.16       0  5003.8    0.07       0  5009.8    0.16       0
Bank Sta=5003.8,5009.8
Exp/Cntr=0.3,0.1

Type RM Length L Ch R = 1,5083,529,529,529
BEGIN DESCRIPTION:
UNT 064 IN BOCR 8.0
END DESCRIPTION:
XS GIS Cut Line= 3
      3777899.58     10573610.22      3777499.61     10574010.19
      3777349.59     10574160.21
#Sta/Elev= 30
  4485.0  332.18  4489.9  331.98  4583.9  317.78  4640.5  311.63  4697.1  307.92
  4786.4  306.68  4838.5  306.31  4852.6  305.10  4866.8  305.86  4895.1  305.58
  4965.8  307.28  4979.9  305.54  4991.1  301.14  4993.8  300.64  4997.1  301.14
  5008.2  304.28  5022.4  302.10  5036.5  306.74  5064.8  307.01  5107.2  309.13
  5121.4  312.00  5135.5  313.45  5163.8  320.72  5177.9  322.95  5192.1  326.41
  5206.2  328.45  5220.3  332.32  5248.6  337.13  5257.4  339.71  5262.8  340.24
#Mann=6,-1,0
  4485.0    0.12       0  4489.9    0.16       0  4786.4    0.12       0
  4991.1    0.07       0  4997.1    0.12       0  5257.4    0.05       0
Bank Sta=4991.1,4997.1
Exp/Cntr=0.3,0.1

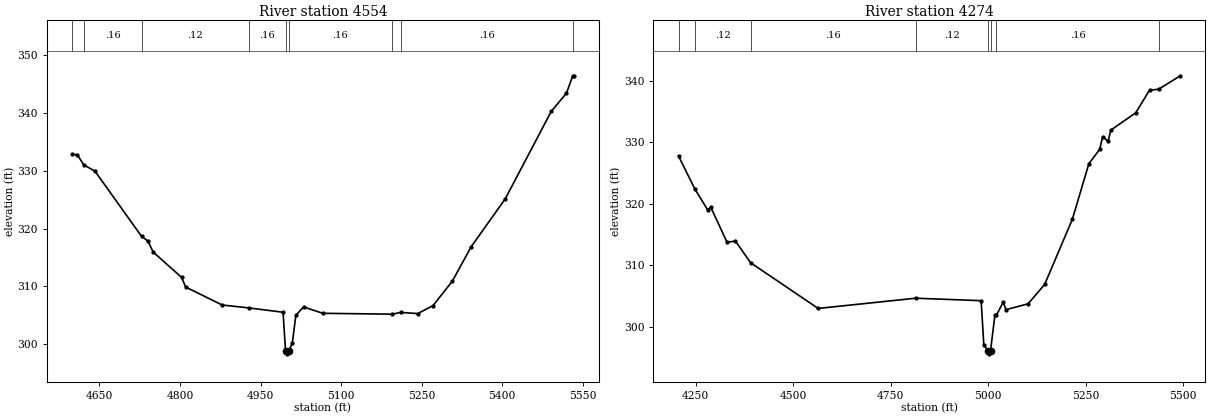
Type RM Length L Ch R = 1,4554,280,280,280
BEGIN DESCRIPTION:
UNT 064 IN BOCR 7.0
END DESCRIPTION:
XS GIS Cut Line= 3
      3777899.58     10573560.19      3777499.61     10573610.19
      3777099.60     10573960.19
#Sta/Elev= 30
  4599.0  332.86  4609.0  332.75  4620.5  331.04  4641.8  329.91  4728.4  318.66
  4740.1  317.86  4750.1  315.94  4803.0  311.56  4810.6  309.89  4878.6  306.78
  4928.7  306.28  4992.0  305.53  4996.6  298.84  4999.3  298.34  5002.6  298.84
  5009.2  300.16  5015.8  305.00  5030.1  306.45  5066.1  305.35  5194.1  305.20
  5211.9  305.50  5242.7  305.30  5271.2  306.67  5307.2  310.90  5342.3  316.85
  5405.9  325.16  5491.4  340.25  5519.8  343.40  5531.5  346.42  5533.6  346.42
#Mann=9,-1,0
  4599.0    0.12       0  4620.5    0.16       0  4728.4    0.12       0
  4928.7    0.16       0  4996.6    0.07       0  5002.6    0.16       0
  5194.1    0.12       0  5211.9    0.16       0  5531.5    0.05       0
Bank Sta=4996.6,5002.6
Exp/Cntr=0.3,0.1

Type RM Length L Ch R = 1,4274,591,591,591
BEGIN DESCRIPTION:
UNT 064 IN BOCR 6.0
END DESCRIPTION:
XS GIS Cut Line= 2
      3777880.80     10572925.27      3776938.10     10573800.26
#Sta/Elev= 30
  4206.1  327.76  4247.9  322.41  4281.1  318.99  4288.5  319.48  4330.5  313.76
  4352.0  313.96  4390.8  310.44  4564.0  303.02  4813.8  304.68  4981.8  304.28
  4988.6  297.06  4999.8  296.15  5002.6  295.65  5005.8  296.15  5017.0  301.91
  5021.0  301.95  5038.5  304.05  5045.3  302.82  5102.0  303.77  5144.5  306.91
  5215.4  317.47  5257.9  326.52  5285.7  328.86  5293.1  330.89  5307.2  330.15
  5314.1  331.97  5378.1  334.78  5413.3  338.45  5436.4  338.60  5492.3  340.79
#Mann=8,-1,0
  4206.1    0.16       0  4247.9    0.12       0  4390.8    0.16       0
  4813.8    0.12       0  4999.8    0.07       0  5005.8    0.12       0
  5021.0    0.16       0  5436.4    0.05       0
Bank Sta=4999.8,5005.8
Exp/Cntr=0.3,0.1