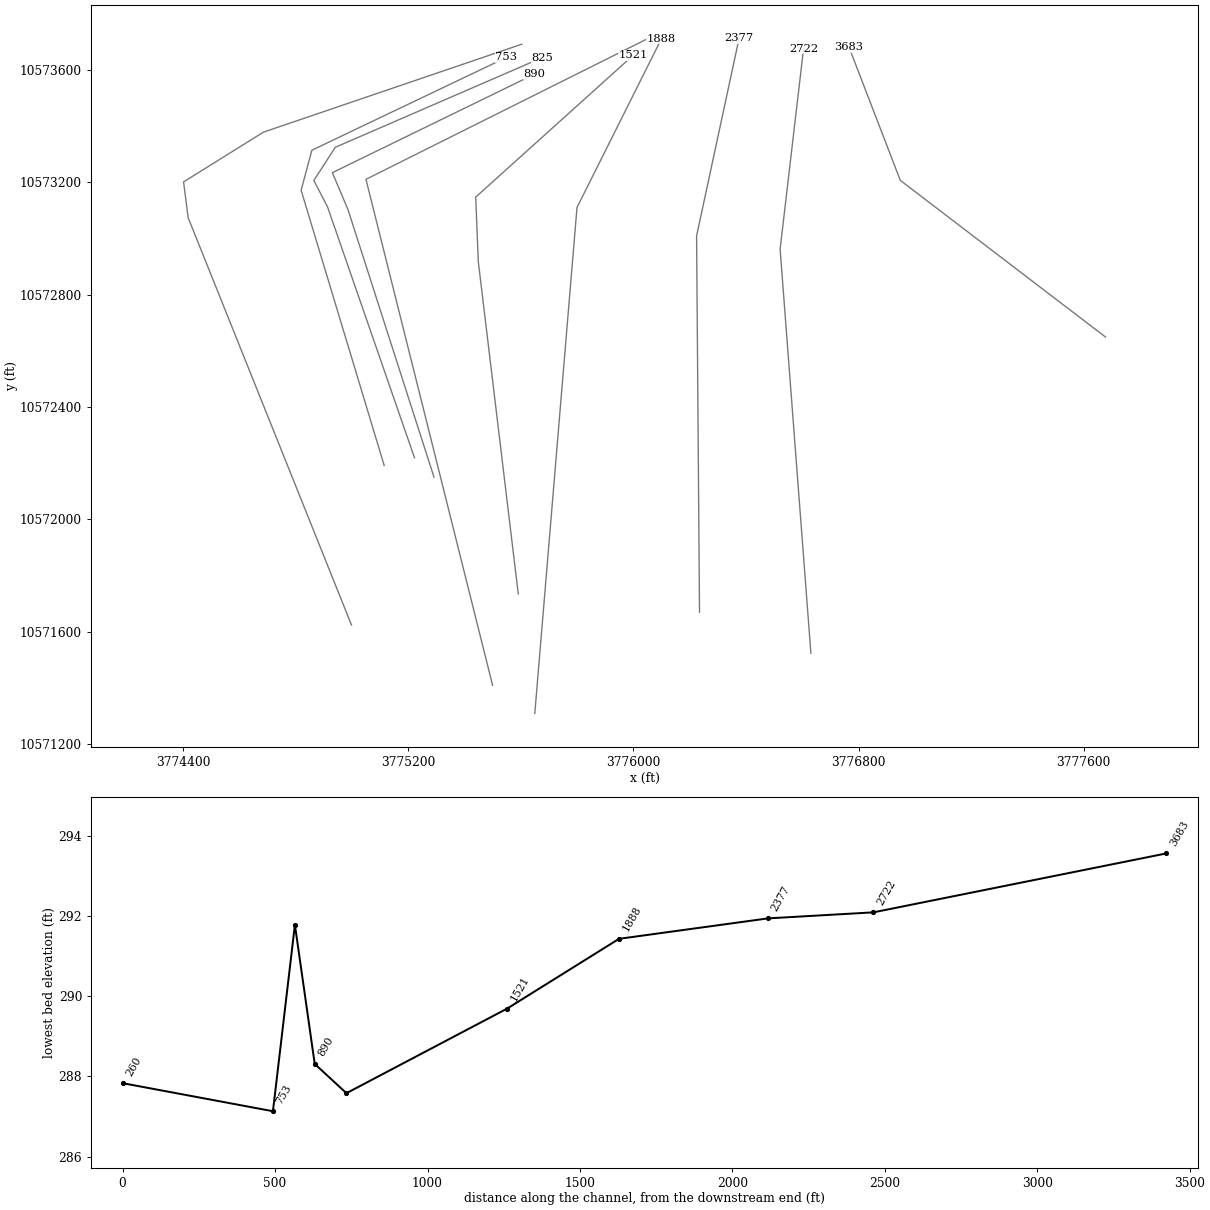
HEC-RAS study UNT 064 IN BOCR.prj: UNT 064 IN BOCR Base Level Engineering

--- UNT 064 IN BOCR.g01 (geometry) --- (continued)

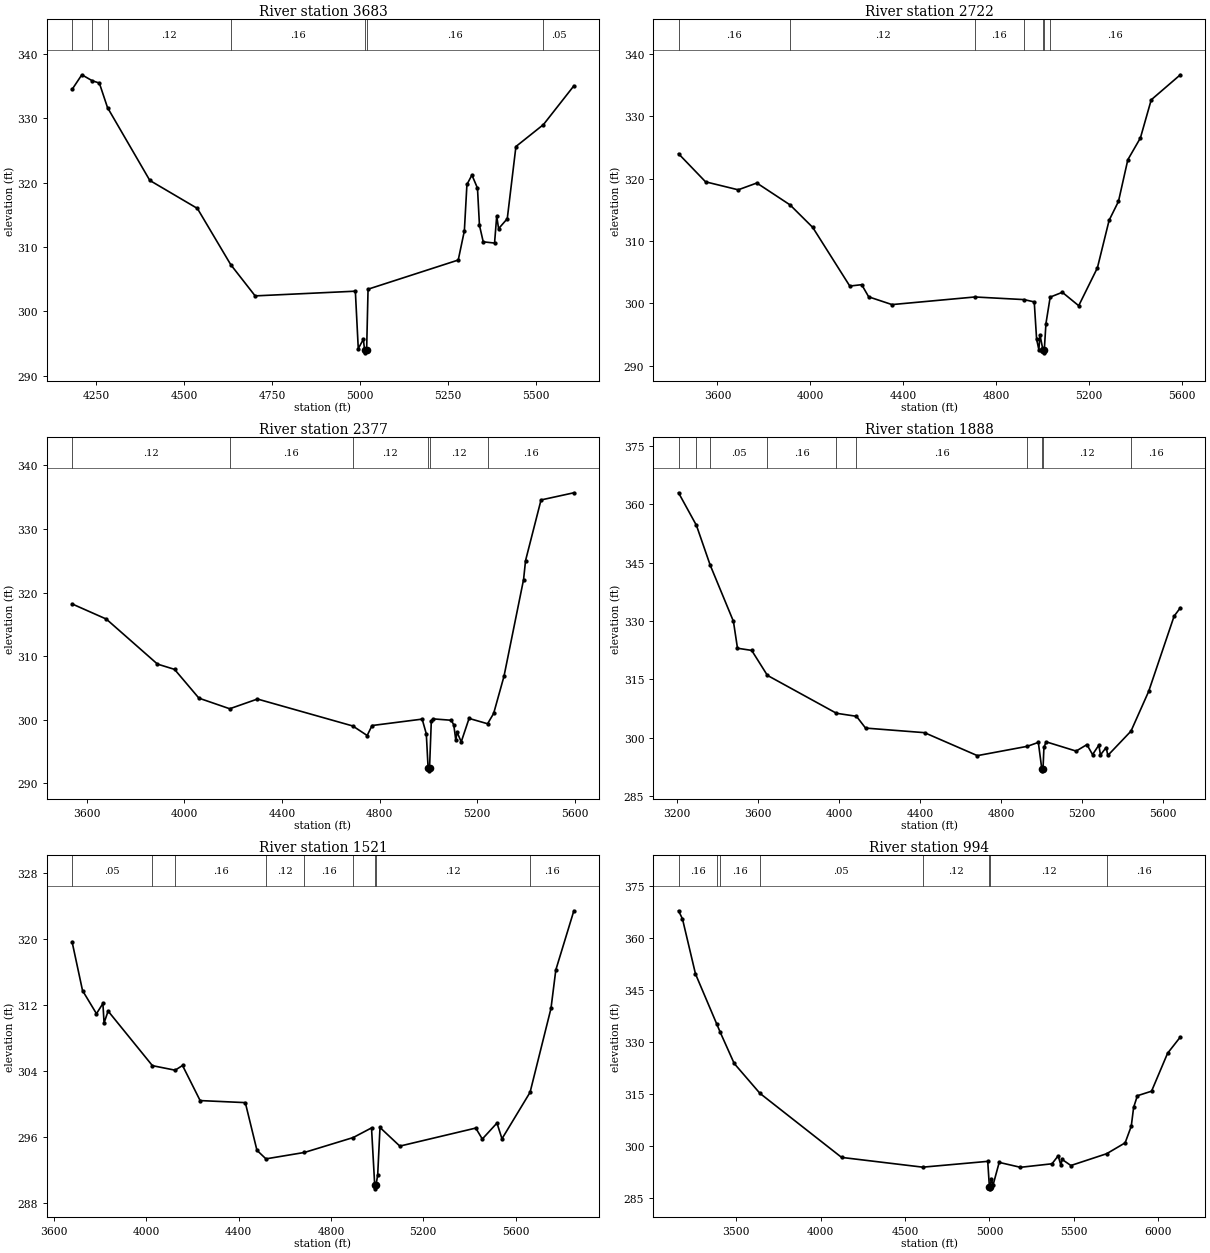
Type RM Length L Ch R = 1,3683,961,961,961
BEGIN DESCRIPTION:
UNT 064 IN BOCR 5.0
END DESCRIPTION:
XS GIS Cut Line= 3
      3777677.68     10572649.22      3776948.51     10573206.51
      3776766.20     10573680.52
#Sta/Elev= 30
  4181.4  334.49  4209.1  336.77  4238.5  335.85  4258.9  335.48  4282.1  331.67
  4402.3  320.35  4537.4  316.00  4632.1  307.27  4701.5  302.41  4986.2  303.14
  4994.5  294.22  5009.0  295.66  5012.3  294.06  5015.0  293.56  5018.3  294.06
  5022.3  303.45  5278.5  307.98  5295.9  312.51  5303.2  319.72  5317.4  321.19
  5333.2  319.15  5338.8  313.38  5349.5  310.81  5381.7  310.62  5387.8  314.80
  5393.2  312.86  5417.8  314.40  5442.4  325.62  5520.6  329.03  5607.0  335.05
#Mann=7,-1,0
  4181.4    0.12       0  4238.5    0.16       0  4282.1    0.12       0
  4632.1    0.16       0  5012.3    0.07       0  5018.3    0.16       0
  5520.6    0.05       0
Bank Sta=5012.3,5018.3
Exp/Cntr=0.3,0.1

Type RM Length L Ch R = 1,2722,345,345,345
BEGIN DESCRIPTION:
UNT 064 IN BOCR 4.0
END DESCRIPTION:
XS GIS Cut Line= 3
      3776630.80     10571524.25      3776521.43     10572961.72
      3776604.68     10573674.55
#Sta/Elev= 30
  3432.7  323.99  3549.0  319.49  3689.4  318.21  3769.6  319.30  3912.7  315.79
  4010.3  312.18  4169.6  302.79  4220.9  303.01  4251.0  301.06  4351.3  299.82
  4707.9  301.04  4919.3  300.62  4963.4  300.25  4973.5  294.29  4983.2  292.61
  4988.3  294.91  5000.7  292.59  5003.4  292.09  5006.7  292.59  5013.7  296.77
  5032.0  301.02  5084.2  301.79  5154.7  299.64  5235.2  305.71  5285.6  313.33
  5325.8  316.35  5366.1  323.03  5420.2  326.52  5466.8  332.63  5592.0  336.64
#Mann=7,-1,0
  3432.7    0.16       0  3912.7    0.12       0  4707.9    0.16       0
  4919.3    0.12       0  5000.7    0.07       0  5006.7    0.12       0
  5032.0    0.16       0
Bank Sta=5000.7,5006.7
Exp/Cntr=0.3,0.1

Type RM Length L Ch R = 1,2377,489,489,489
BEGIN DESCRIPTION:
UNT 064 IN BOCR 3.0
END DESCRIPTION:
XS GIS Cut Line= 3
      3776234.97     10571670.03      3776224.55     10573008.60
      3776375.60     10573711.75
#Sta/Elev= 30
  3539.1  318.21  3679.3  315.83  3889.3  308.74  3959.3  307.91  4059.3  303.38
  4185.6  301.71  4299.3  303.24  4690.2  299.00  4749.3  297.50  4769.3  299.07
  4974.8  300.08  4991.8  297.76  4999.1  292.44  5001.8  291.94  5005.1  292.44
  5012.3  299.78  5019.1  300.12  5094.1  299.90  5104.4  299.18  5112.8  296.76
  5117.9  298.03  5135.0  296.50  5167.2  300.19  5243.1  299.35  5268.0  300.98
  5310.3  306.81  5390.7  322.05  5398.8  325.03  5462.3  334.57  5596.9  335.70
#Mann=6,-1,0
  3539.1    0.12       0  4185.6    0.16       0  4690.2    0.12       0
  4999.1    0.07       0  5005.1    0.12       0  5243.1    0.16       0
Bank Sta=4999.1,5005.1
Exp/Cntr=0.3,0.1

Type RM Length L Ch R = 1,1888,367,367,367
BEGIN DESCRIPTION:
UNT 064 IN BOCR 2.0
END DESCRIPTION:
XS GIS Cut Line= 3
      3775649.61     10571310.20      3775799.61     10573110.19
      3776099.59     10573710.15
#Sta/Elev= 30
  3208.3  362.96  3296.6  354.58  3364.5  344.36  3479.2  329.90  3499.3  322.97
  3569.5  322.41  3646.9  315.99  3987.8  306.24  4086.6  305.46  4131.5  302.43
  4422.5  301.25  4683.4  295.34  4930.2  297.74  4984.4  298.75  5001.5  291.93
  5004.2  291.43  5007.5  291.93  5012.0  297.44  5022.9  298.89  5171.0  296.51
  5224.2  298.18  5252.1  295.61  5282.9  298.03  5291.2  295.54  5319.2  297.42
  5327.6  295.40  5441.8  301.65  5528.8  311.84  5654.6  331.22  5685.3  333.37
#Mann=10,-1,0
  3208.3    0.12       0  3296.6    0.16       0  3364.5    0.05       0
  3646.9    0.16       0  3987.8    0.12       0  4086.6    0.16       0
  4930.2    0.12       0  5001.5    0.07       0  5007.5    0.12       0
  5441.8    0.16       0
Bank Sta=5001.5,5007.5
Exp/Cntr=0.3,0.1

Type RM Length L Ch R = 1,1521,527,527,527
BEGIN DESCRIPTION:
Mapping XS c80ca3cf
END DESCRIPTION:
XS GIS Cut Line= 4
      3775590.85     10571735.22      3775448.78     10572917.69
      3775439.61     10573146.86      3775998.76     10573651.01
#Sta/Elev= 30
  3679.1  319.70  3724.4  313.77  3784.8  310.96  3812.6  312.20  3817.7  309.84
  3835.2  311.28  4027.1  304.65  4125.4  304.10  4157.5  304.67  4233.7  300.41
  4429.4  300.16  4479.8  294.37  4518.8  293.33  4685.5  294.11  4896.7  295.92
  4976.0  297.09  4989.7  290.19  4992.4  289.69  4995.7  290.19  5002.7  291.38
  5012.7  297.14  5098.6  294.88  5427.4  297.07  5455.8  295.74  5519.3  297.68
  5541.0  295.77  5662.6  301.41  5753.2  311.60  5774.2  316.28  5852.3  323.46
#Mann=9,-1,0
  3679.1    0.05       0  4027.1    0.08       0  4125.4    0.16       0
  4518.8    0.12       0  4685.5    0.16       0  4896.7    0.12       0
  4989.7    0.07       0  4995.7    0.12       0  5662.6    0.16       0
Bank Sta=4989.7,4995.7
Exp/Cntr=0.3,0.1

Type RM Length L Ch R = 1,994,104,104,104
BEGIN DESCRIPTION:
UNT 064 IN BOCR 1.0
END DESCRIPTION:
XS GIS Cut Line= 3
      3775499.60     10571410.22      3775049.61     10573210.19
      3776049.61     10573710.19
#Sta/Elev= 30
  3157.8  367.91  3181.0  365.58  3258.3  349.66  3384.7  335.14  3405.5  332.75
  3487.6  323.80  3640.1  315.17  4124.1  296.66  4605.0  293.84  4990.0  295.52
  4999.9  288.08  5002.6  287.58  5005.9  288.08  5010.6  290.53  5021.5  288.67
  5057.9  295.22  5183.7  293.80  5370.9  294.82  5407.3  297.12  5424.0  294.33
  5429.6  296.11  5482.7  294.32  5694.4  297.72  5804.2  300.87  5840.5  305.68
  5854.5  311.12  5876.8  314.48  5960.7  315.79  6055.7  326.75  6131.2  331.44
#Mann=8,-1,0
  3157.8    0.16       0  3384.7    0.05       0  3405.5    0.16       0
  3640.1    0.05       0  4605.0    0.12       0  4999.9    0.07       0
  5005.9    0.12       0  5694.4    0.16       0
Bank Sta=4999.9,5005.9
Exp/Cntr=0.3,0.1

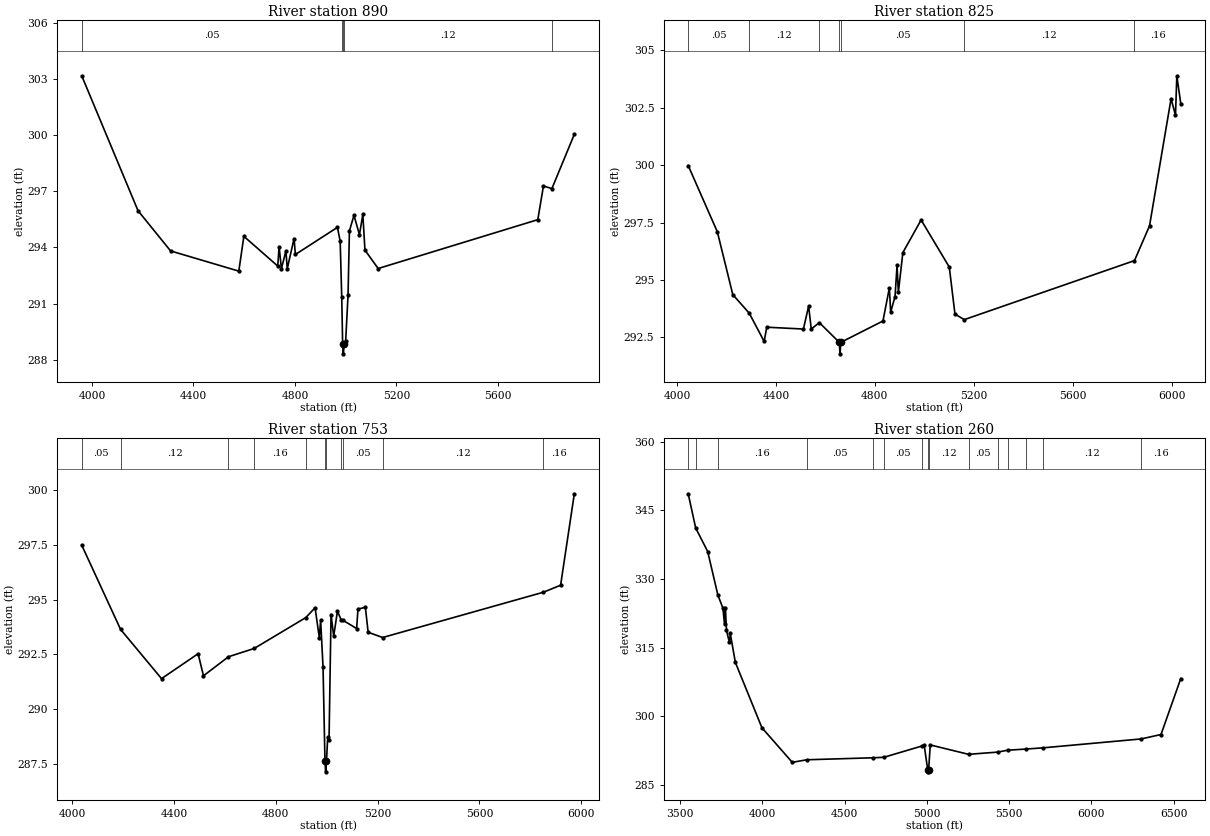
Type RM Length L Ch R = 1,890,65,65,65
BEGIN DESCRIPTION:
Mapping XS 64e273be
END DESCRIPTION:
XS GIS Cut Line= 4
      3775291.37     10572150.58      3774985.83     10573101.93
      3774930.27     10573233.88      3775649.01     10573584.56
#Sta/Elev= 30
  3959.6  303.17  4181.5  295.96  4309.9  293.81  4578.9  292.73  4598.8  294.59
  4732.5  293.00  4737.8  294.04  4746.9  292.86  4764.6  293.81  4769.9  292.86
  4796.7  294.47  4802.0  293.62  4967.8  295.07  4978.6  294.32  4984.7  291.33
  4988.3  288.81  4991.1  288.31  4994.3  288.81  5000.3  289.02  5009.6  291.46
  5015.0  294.88  5032.9  295.71  5054.6  294.68  5067.9  295.76  5076.3  293.85
  5128.4  292.87  5757.7  295.48  5780.0  297.28  5813.3  297.14  5901.7  300.04
#Mann=5,-1,0
  3959.6    0.05       0  4984.7    0.12       0  4988.3    0.07       0
  4994.3    0.12       0  5813.3    0.16       0
Bank Sta=4988.3,4994.3
Exp/Cntr=0.3,0.1

Type RM Length L Ch R = 1,825,72,72,72
BEGIN DESCRIPTION:
Mapping XS b2702fcf
END DESCRIPTION:
XS GIS Cut Line= 5
      3775221.95     10572219.96      3774912.91     10573112.35
      3774864.30     10573206.10      3774940.69     10573324.15
      3775675.66     10573643.10
#Sta/Elev= 30
  4045.5  299.98  4163.5  297.09  4225.8  294.36  4292.3  293.55  4352.6  292.32
  4363.2  292.94  4511.4  292.86  4532.5  293.86  4543.1  292.86  4575.8  293.14
  4656.5  292.28  4659.3  291.78  4662.5  292.28  4833.0  293.21  4858.9  294.65
  4864.2  293.60  4881.8  294.27  4890.0  295.63  4895.3  294.46  4913.5  296.19
  4987.3  297.61  5101.2  295.56  5124.2  293.51  5161.8  293.27  5850.0  295.84
  5910.8  297.35  5998.0  302.89  6015.9  302.17  6021.3  303.89  6037.3  302.67
#Mann=7,-1,0
  4045.5    0.05       0  4292.3    0.12       0  4575.8    0.05       0
  4656.5    0.04       0  4662.5    0.05       0  5161.8    0.12       0
  5850.0    0.16       0
Bank Sta=4656.5,4662.5
Exp/Cntr=0.3,0.1

Type RM Length L Ch R = 1,753,493,493,493
BEGIN DESCRIPTION:
Mapping XS cb6e1e1e
END DESCRIPTION:
XS GIS Cut Line= 4
      3775114.30     10572192.21      3774819.16     10573171.38
      3774857.35     10573313.74      3775548.28     10573643.58
#Sta/Elev= 30
  4037.3  297.49  4190.0  293.64  4350.9  291.39  4494.7  292.53  4515.6  291.52
  4613.9  292.39  4715.1  292.77  4917.7  294.18  4954.3  294.63  4970.9  293.26
  4976.1  294.06  4985.6  291.91  4993.1  287.63  4995.8  287.13  4999.1  287.63
  5003.9  288.70  5009.1  288.58  5017.0  294.32  5027.4  293.33  5042.1  294.47
  5057.3  294.07  5062.2  294.07  5117.6  293.68  5122.8  294.57  5151.9  294.65
  5162.8  293.51  5219.8  293.27  5851.4  295.34  5919.1  295.66  5973.0  299.84
#Mann=11,-1,0
  4037.3    0.05       0  4190.0    0.12       0  4613.9    0.05       0
  4715.1    0.16       0  4917.7    0.05       0  4993.1    0.04       0
  4999.1    0.05       0  5057.3    0.16       0  5062.2    0.05       0
  5219.8    0.12       0  5851.4    0.16       0
Bank Sta=4993.1,4999.1
Exp/Cntr=0.3,0.1

Type RM Length L Ch R = 1,260,0,0,0
BEGIN DESCRIPTION:
Mapping XS acb53691
END DESCRIPTION:
XS GIS Cut Line= 5
      3774998.31     10571624.25      3774417.82     10573073.41
      3774401.36     10573201.04      3774685.43     10573378.07
      3775603.47     10573690.94
#Sta/Elev= 30
  3549.6  348.61  3595.2  341.12  3668.1  335.99  3730.1  326.45  3760.7  323.61
  3770.4  320.08  3775.8  323.67  3782.2  318.77  3800.0  316.13  3805.4  318.08
  3836.1  311.77  3997.7  297.47  4182.1  289.91  4271.5  290.47  4670.4  290.90
  4739.1  291.01  4970.7  293.48  4984.1  293.68  5005.3  288.33  5008.1  287.83
  5011.3  288.33  5021.1  293.71  5253.7  291.66  5430.3  292.14  5492.0  292.56
  5602.9  292.81  5707.8  293.08  6302.8  295.02  6423.7  295.99  6544.0  308.23
#Mann=15,-1,0
  3549.6    0.16       0  3595.2    0.12       0  3730.1    0.16       0
  4271.5    0.05       0  4670.4    0.16       0  4739.1    0.05       0
  4970.7    0.12       0  5005.3    0.07       0  5011.3    0.12       0
  5253.7    0.05       0  5430.3    0.12       0  5492.0    0.16       0
  5602.9    0.05       0  5707.8    0.12       0  6302.8    0.16       0
Bank Sta=5005.3,5011.3
Exp/Cntr=0.3,0.1

Chan Stop Cuts=-1