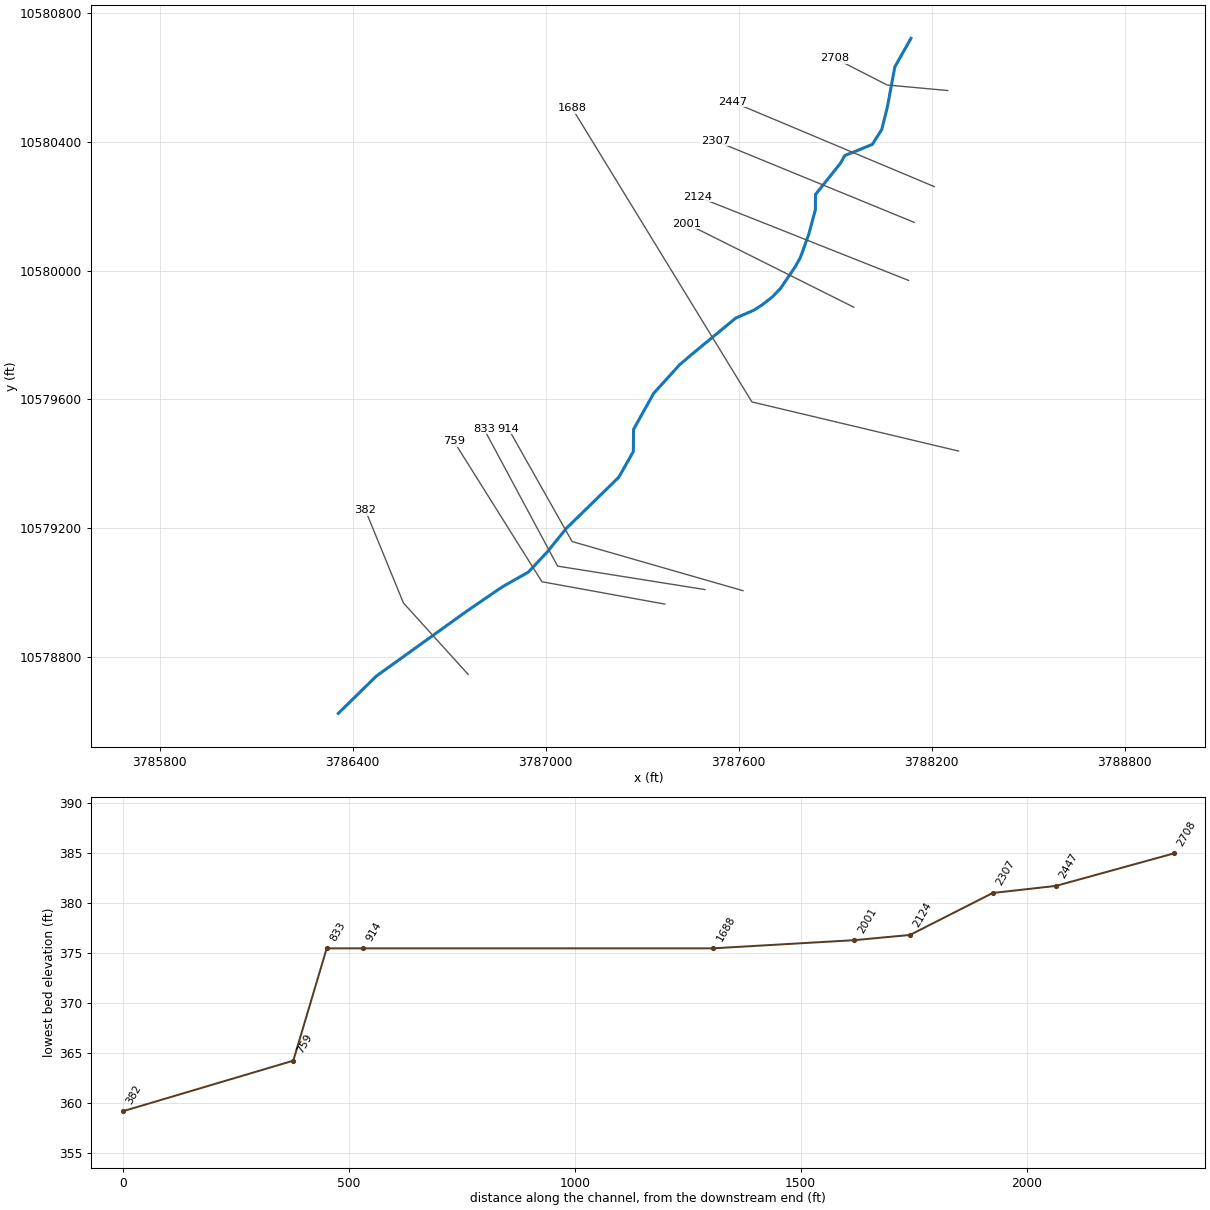
--- UNT 065 IN BOCR.prj (project) ---

Proj Title=UNT 065 IN BOCR Base Level Engineering
Current Plan=p01
Default Exp/Contr=0.3,0.1
English Units
Geom File=g01
Flow File=f01
Plan File=p01
BEGIN DESCRIPTION:
UNT 065 IN BOCR
END DESCRIPTION:

--- UNT 065 IN BOCR.p01 (plan) ---

Plan Title=Multiple Run
Short Identifier=Multiple
Geom File=g01
Flow File=f01
Subcritical Flow
K Sum by GR= 0
Std Step Tol= 0.01
Critical Tol= 0.01
Num of Std Step Trials= 20
Max Error Tol= 0.3
Flow Tol Ratio= 0.001
Split Flow NTrial= 30
Split Flow Tol= 0.02
Split Flow Ratio= 0.02
Log Output Level= 0
Friction Slope Method= 1
Unsteady Friction Slope Method= 2
Unsteady Bridges Friction Slope Method= 1
Parabolic Critical Depth
Global Vel Dist=  1 , 1 , 1
Global Log Level= 0
CheckData=True
Encroach Param= -1, 0, 0, 0
BEGIN DESCRIPTION:
Multiple Run
END DESCRIPTION:

--- UNT 065 IN BOCR.f01 (steady flow) ---

Flow Title=Multiple
Number of Profiles=7
Profile Names=10-year,25-year,50-year,1pct_min,100-year,1pct_plu,500-year
River Rch & RM= UNT 065 IN BOCR,Reach-1,2708
     309     404     480     421     569     770     802
Boundary for River Rch & Prof#=UNT 065 IN BOCR,Reach-1,1
Up Type=0
Dn Type=3
Dn Slope=0.005
Boundary for River Rch & Prof#=UNT 065 IN BOCR,Reach-1,2
Up Type=0
Dn Type=3
Dn Slope=0.005
Boundary for River Rch & Prof#=UNT 065 IN BOCR,Reach-1,3
Up Type=0
Dn Type=3
Dn Slope=0.005
Boundary for River Rch & Prof#=UNT 065 IN BOCR,Reach-1,4
Up Type=0
Dn Type=3
Dn Slope=0.005
Boundary for River Rch & Prof#=UNT 065 IN BOCR,Reach-1,5
Up Type=0
Dn Type=3
Dn Slope=0.005
Boundary for River Rch & Prof#=UNT 065 IN BOCR,Reach-1,6
Up Type=0
Dn Type=3
Dn Slope=0.005
Boundary for River Rch & Prof#=UNT 065 IN BOCR,Reach-1,7
Up Type=0
Dn Type=3
Dn Slope=0.005

--- UNT 065 IN BOCR.g01 (geometry) ---

Geom Title=Existing Conditions

River Reach=UNT 065 IN BOCR,Reach-1
Reach XY= 30
      3788135.27     10580722.49      3788085.09     10580633.52
      3788061.99     10580509.04      3788044.58     10580439.42
      3788015.27     10580392.70      3787929.73     10580358.08
      3787916.29     10580334.27      3787838.46     10580236.95
      3787838.25     10580190.00      3787817.50     10580113.00
      3787791.50     10580041.00      3787775.25     10580012.00
      3787729.75     10579945.00      3787704.75     10579919.00
      3787674.25     10579895.00      3787648.25     10579878.00
      3787590.75     10579853.00      3787452.75     10579739.00
      3787416.25     10579708.00      3787335.50     10579619.00
      3787273.00     10579507.00      3787272.25     10579438.00
      3787227.00     10579358.00      3787063.75     10579199.00
      3787004.75     10579126.00      3786945.75     10579063.00
      3786866.00     10579018.00      3786754.75     10578942.00
      3786473.50     10578740.00      3786355.00     10578624.00

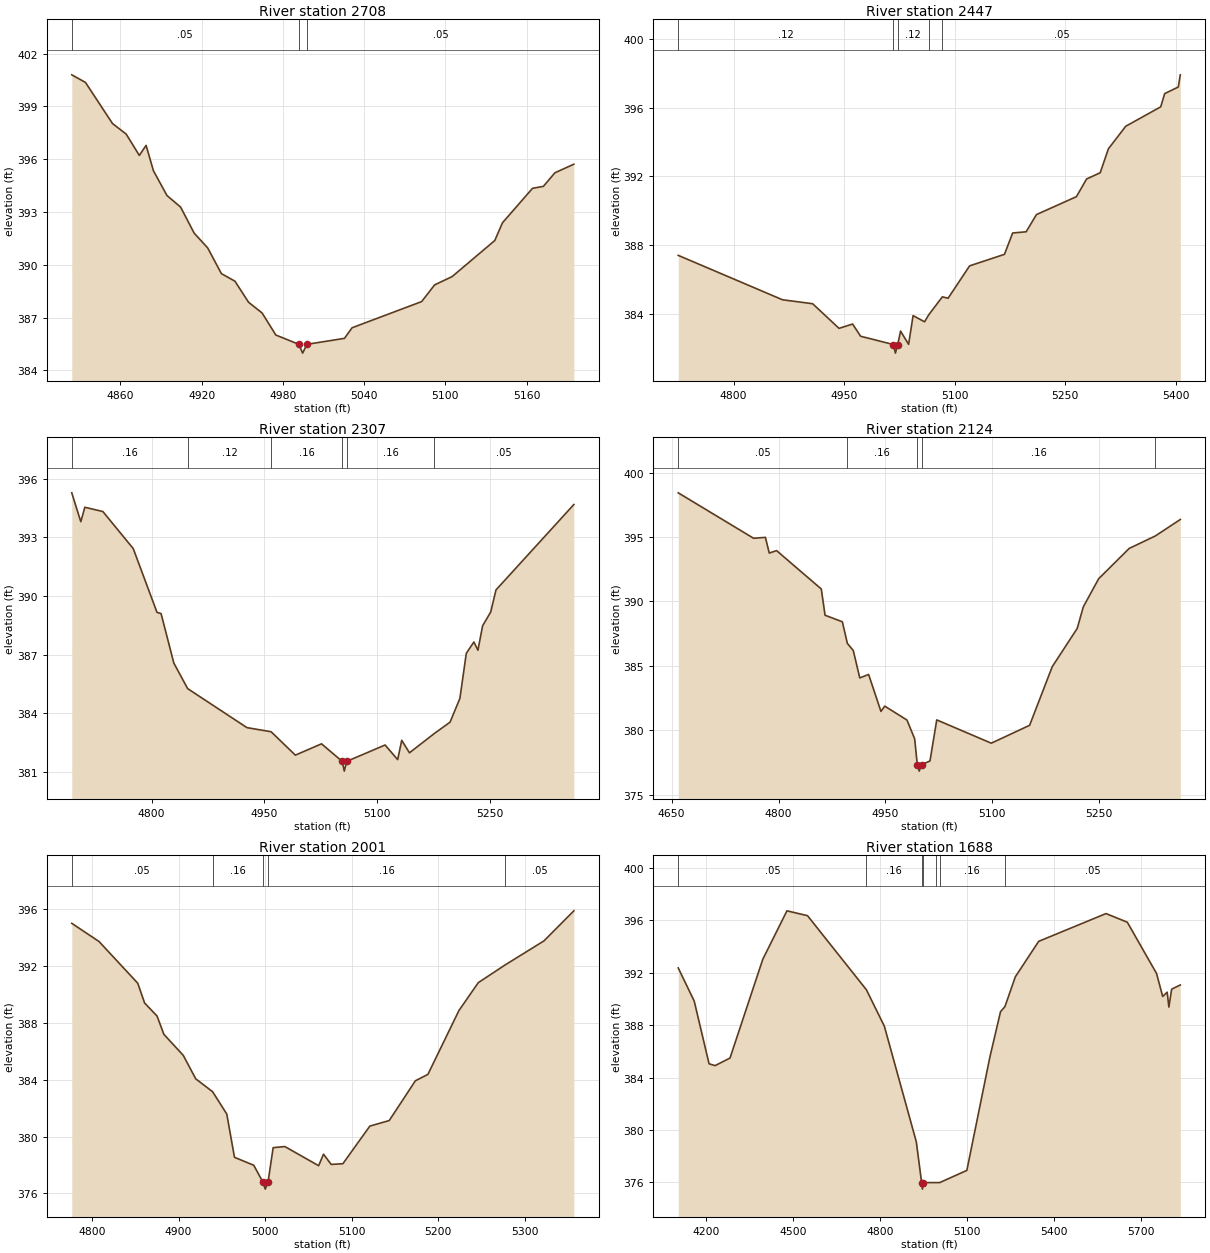
Type RM Length L Ch R = 1,2708,261,261,261
BEGIN DESCRIPTION:
UNT 065 IN BOCR 6.0
END DESCRIPTION:
XS GIS Cut Line= 3
      3788249.63     10580560.19      3788060.99     10580577.53
      3787899.57     10580660.21
#Sta/Elev= 30
  4824.1  400.80  4834.2  400.37  4854.2  398.03  4864.3  397.43  4874.0  396.22
  4879.0  396.79  4884.4  395.35  4894.4  393.94  4904.5  393.28  4914.5  391.80
  4924.5  390.96  4934.6  389.50  4944.6  389.07  4954.7  387.87  4964.7  387.26
  4974.8  386.01  4991.8  385.48  4994.6  384.98  4997.8  385.48  5025.5  385.82
  5031.1  386.42  5082.5  387.91  5092.1  388.86  5105.0  389.33  5136.5  391.38
  5142.2  392.39  5164.4  394.35  5172.4  394.46  5180.9  395.23  5194.9  395.72
#Mann=3,-1,0
  4824.1    0.05       0  4991.8    0.03       0  4997.8    0.05       0
Bank Sta=4991.8,4997.8
Exp/Cntr=0.3,0.1

Type RM Length L Ch R = 1,2447,140,140,140
BEGIN DESCRIPTION:
Mapping XS 81d176bc
END DESCRIPTION:
XS GIS Cut Line= 2
      3788207.80     10580261.54      3787579.63     10580525.30
#Sta/Elev= 30
  4725.0  387.41  4866.5  384.83  4907.4  384.60  4943.2  383.17  4961.6  383.42
  4972.5  382.71  5016.9  382.23  5019.7  381.73  5022.9  382.23  5026.7  383.01
  5037.6  382.24  5043.7  383.91  5059.3  383.55  5064.8  383.95  5083.4  385.00
  5091.2  384.92  5120.4  386.80  5167.7  387.47  5178.8  388.71  5197.1  388.78
  5211.1  389.78  5265.3  390.82  5279.2  391.85  5297.6  392.21  5308.7  393.60
  5332.2  394.91  5379.7  396.04  5385.1  396.81  5403.5  397.19  5406.3  397.90
#Mann=5,-1,0
  4725.0    0.12       0  5016.9    0.07       0  5022.9    0.12       0
  5064.8    0.16       0  5083.4    0.05       0
Bank Sta=5016.9,5022.9
Exp/Cntr=0.3,0.1

Type RM Length L Ch R = 1,2307,183,183,183
BEGIN DESCRIPTION:
UNT 065 IN BOCR 5.0
END DESCRIPTION:
XS GIS Cut Line= 2
      3788145.29     10580150.43      3787527.24     10580403.90
#Sta/Elev= 30
  4693.7  395.29  4705.7  393.81  4711.1  394.55  4735.1  394.33  4775.5  392.43
  4807.1  389.16  4812.5  389.10  4829.5  386.56  4847.9  385.25  4926.8  383.25
  4958.9  383.04  4991.2  381.84  5026.0  382.42  5053.5  381.52  5056.3  381.02
  5059.5  381.52  5110.6  382.36  5127.3  381.61  5132.7  382.60  5143.0  381.96
  5176.1  382.95  5197.0  383.53  5210.1  384.75  5218.6  387.06  5228.7  387.64
  5234.1  387.22  5240.3  388.47  5251.1  389.18  5258.1  390.31  5361.7  394.69
#Mann=6,-1,0
  4693.7    0.16       0  4847.9    0.12       0  4958.9    0.16       0
  5053.5    0.07       0  5059.5    0.16       0  5176.1    0.05       0
Bank Sta=5053.5,5059.5
Exp/Cntr=0.3,0.1

Type RM Length L Ch R = 1,2124,123,123,123
BEGIN DESCRIPTION:
Mapping XS 1b35c692
END DESCRIPTION:
XS GIS Cut Line= 2
      3788127.88     10579969.90      3787473.15     10580229.71
#Sta/Elev= 30
  4659.3  398.44  4765.0  394.91  4781.6  394.98  4787.0  393.76  4797.3  393.95
  4860.0  390.97  4865.3  388.93  4889.6  388.42  4896.6  386.74  4904.9  386.19
  4914.0  384.06  4926.4  384.33  4943.7  381.46  4949.0  381.87  4980.2  380.79
  4991.0  379.33  4994.7  377.32  4997.4  376.82  5000.7  377.32  5012.5  377.61
  5022.0  380.80  5098.5  378.99  5152.3  380.38  5184.0  384.93  5219.1  387.91
  5227.6  389.58  5249.2  391.77  5292.0  394.12  5328.7  395.09  5363.7  396.37
#Mann=5,-1,0
  4659.3    0.05       0  4896.6    0.16       0  4994.7    0.07       0
  5000.7    0.16       0  5328.7    0.05       0
Bank Sta=4994.7,5000.7
Exp/Cntr=0.3,0.1

Type RM Length L Ch R = 1,2001,313,313,313
BEGIN DESCRIPTION:
UNT 065 IN BOCR 4.0
END DESCRIPTION:
XS GIS Cut Line= 2
      3787957.82     10579886.53      3787438.70     10580146.09
#Sta/Elev= 30
  4776.5  395.02  4808.0  393.74  4852.8  390.80  4860.7  389.41  4875.1  388.49
  4883.0  387.20  4905.4  385.72  4919.8  384.07  4939.3  383.16  4955.7  381.59
  4964.6  378.54  4986.9  377.98  4997.4  376.80  5000.2  376.30  5003.4  376.80
  5009.3  379.22  5022.8  379.30  5061.9  377.95  5067.5  378.76  5076.4  378.04
  5089.9  378.09  5121.1  380.74  5143.5  381.13  5173.7  383.93  5188.2  384.38
  5224.0  388.87  5246.4  390.84  5277.5  392.09  5322.3  393.78  5356.9  395.90
#Mann=5,-1,0
  4776.5    0.05       0  4939.3    0.16       0  4997.4    0.07       0
  5003.4    0.16       0  5277.5    0.05       0
Bank Sta=4997.4,5003.4
Exp/Cntr=0.3,0.1

Type RM Length L Ch R = 1,1688,774,774,774
BEGIN DESCRIPTION:
UNT 065 IN BOCR 3.0
END DESCRIPTION:
XS GIS Cut Line= 3
      3788283.24     10579439.44      3787640.86     10579592.22
      3787081.89     10580505.32
#Sta/Elev= 30
  4104.4  392.37  4159.5  389.84  4210.7  385.05  4231.5  384.91  4282.9  385.49
  4395.9  393.03  4479.2  396.73  4550.1  396.36  4753.2  390.70  4815.0  387.92
  4925.2  379.09  4943.5  375.98  4946.3  375.48  4949.5  375.98  4992.1  375.98
  5005.9  375.98  5099.4  376.91  5178.7  385.55  5215.5  389.03  5230.6  389.41
  5266.5  391.69  5347.0  394.40  5579.2  396.52  5652.6  395.86  5753.3  391.95
  5774.6  390.19  5790.0  390.52  5795.9  389.38  5805.5  390.75  5835.3  391.07
#Mann=7,-1,0
  4104.4    0.05       0  4753.2    0.16       0  4943.5   0.033       0
  4949.5    0.16       0  4992.1    0.05       0  5005.9    0.16       0
  5230.6    0.05       0
Bank Sta=4943.5,4949.5
Exp/Cntr=0.3,0.1

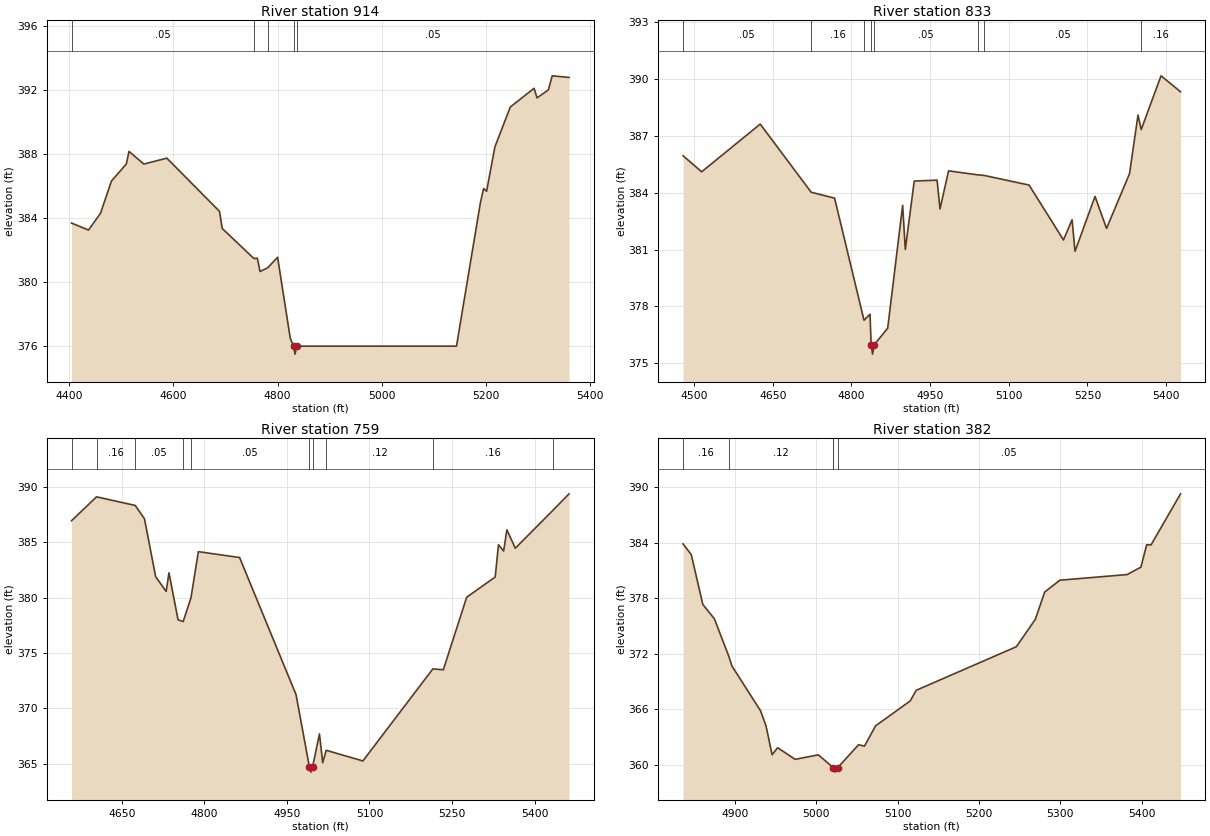
Type RM Length L Ch R = 1,914,81,81,81
BEGIN DESCRIPTION:
UNT 065 IN BOCR 2.0
END DESCRIPTION:
XS GIS Cut Line= 3
      3787613.08     10579005.41      3787081.83     10579158.19
      3786884.24     10579508.30
#Sta/Elev= 30
  4404.5  383.68  4437.0  383.24  4460.1  384.29  4481.1  386.31  4509.6  387.37
  4514.8  388.16  4543.3  387.37  4587.4  387.74  4688.5  384.41  4693.7  383.34
  4754.6  381.46  4761.1  381.48  4766.3  380.65  4780.9  380.88  4800.0  381.54
  4824.3  376.47  4830.7  375.98  4833.4  375.48  4836.7  375.98  5143.3  375.98
  5189.2  384.95  5195.4  385.84  5201.1  385.67  5217.0  388.44  5246.6  390.94
  5292.2  392.11  5297.9  391.51  5319.6  392.01  5327.0  392.89  5359.3  392.79
#Mann=5,-1,0
  4404.5    0.05       0  4754.6    0.16       0  4780.9    0.05       0
  4830.7   0.033       0  4836.7    0.05       0
Bank Sta=4830.7,4836.7
Exp/Cntr=0.3,0.1

Type RM Length L Ch R = 1,833,74,74,74
BEGIN DESCRIPTION:
Mapping XS 4a42ac3c
END DESCRIPTION:
XS GIS Cut Line= 3
      3787495.03     10579008.89      3787036.69     10579081.80
      3786807.52     10579508.90
#Sta/Elev= 30
  4478.8  385.96  4514.3  385.11  4626.0  387.63  4723.2  384.03  4767.8  383.72
  4823.9  377.27  4835.4  377.59  4837.5  375.98  4840.2  375.48  4843.5  375.98
  4869.1  376.85  4897.6  383.34  4902.7  381.01  4919.7  384.62  4963.3  384.67
  4968.9  383.15  4985.2  385.16  5040.8  384.95  5052.9  384.92  5138.7  384.41
  5204.4  381.51  5220.7  382.58  5226.4  380.91  5264.5  383.81  5286.5  382.12
  5330.3  385.01  5346.5  388.11  5352.6  387.34  5390.4  390.18  5427.6  389.34
#Mann=8,-1,0
  4478.8    0.05       0  4723.2    0.16       0  4823.9    0.05       0
  4837.5    0.03       0  4843.5    0.05       0  5040.8    0.12       0
  5052.9    0.05       0  5352.6    0.16       0
Bank Sta=4837.5,4843.5
Exp/Cntr=0.3,0.1

Type RM Length L Ch R = 1,759,377,377,377
BEGIN DESCRIPTION:
Mapping XS 4e90cbc9
END DESCRIPTION:
XS GIS Cut Line= 3
      3787369.99     10578963.75      3786988.08     10579033.19
      3786714.17     10579470.06
#Sta/Elev= 30
  4558.8  386.93  4604.2  389.09  4674.6  388.31  4691.3  387.11  4711.6  381.88
  4730.7  380.55  4735.8  382.23  4752.3  377.99  4761.6  377.83  4775.8  379.98
  4789.2  384.14  4864.1  383.61  4966.7  371.23  4990.8  364.74  4993.6  364.24
  4996.8  364.74  5009.2  367.69  5015.1  365.09  5021.4  366.21  5088.1  365.25
  5215.2  373.56  5234.2  373.48  5276.7  380.03  5328.5  381.85  5334.4  384.76
  5343.8  384.20  5349.7  386.11  5365.0  384.45  5433.7  387.89  5462.6  389.36
#Mann=10,-1,0
  4558.8    0.05       0  4604.2    0.16       0  4674.6    0.05       0
  4761.6    0.16       0  4775.8    0.05       0  4990.8    0.03       0
  4996.8    0.05       0  5021.4    0.12       0  5215.2    0.16       0
  5433.7    0.05       0
Bank Sta=4990.8,4996.8
Exp/Cntr=0.3,0.1

Type RM Length L Ch R = 1,382,0,0,0
BEGIN DESCRIPTION:
UNT 065 IN BOCR 1.0
END DESCRIPTION:
XS GIS Cut Line= 3
      3786758.92     10578744.99      3786557.53     10578967.22
      3786439.53     10579255.28
#Sta/Elev= 30
  4836.5  383.86  4846.6  382.70  4860.8  377.31  4875.0  375.76  4892.7  371.71
  4896.6  370.65  4931.8  365.80  4938.5  364.16  4945.9  361.06  4952.7  361.82
  4974.3  360.56  5002.7  361.05  5020.6  359.70  5020.7  359.68  5023.4  359.18
  5026.7  359.68  5052.1  362.14  5059.4  361.99  5073.0  364.18  5115.6  366.88
  5123.0  368.03  5246.0  372.74  5269.3  375.70  5280.8  378.65  5299.4  379.93
  5382.1  380.54  5399.0  381.34  5406.1  383.76  5411.5  383.75  5447.7  389.27
#Mann=5,-1,0
  4836.5    0.16       0  4892.7    0.12       0  5020.6    0.05       0
  5020.7    0.07       0  5026.7    0.05       0
Bank Sta=5020.7,5026.7
Exp/Cntr=0.3,0.1

Chan Stop Cuts=-1