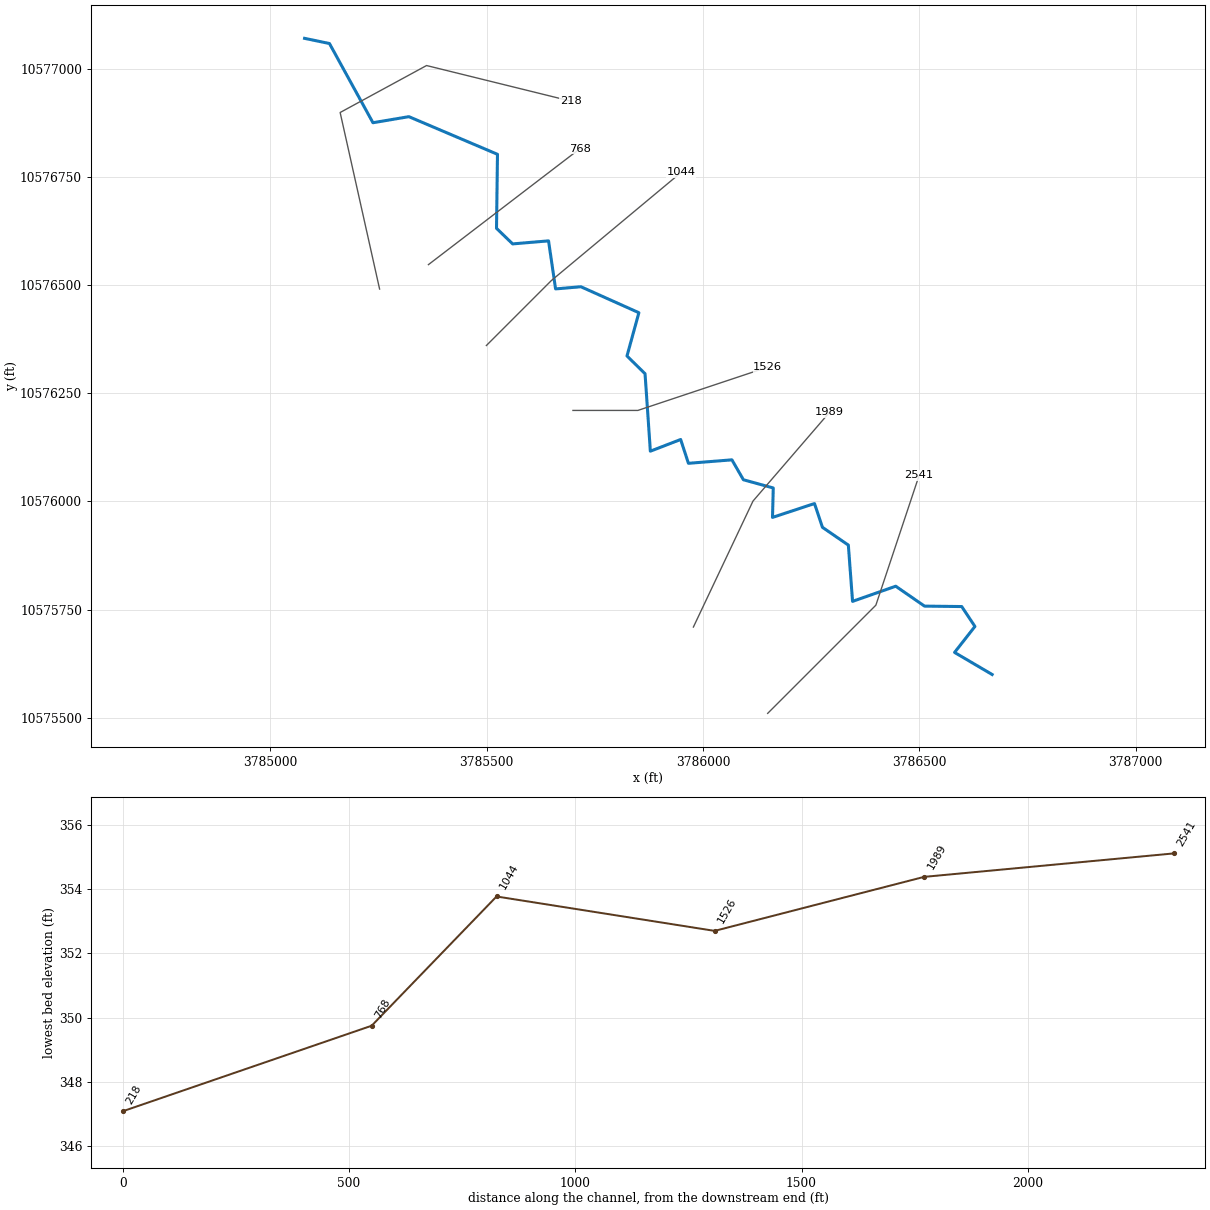
--- UNT 066 IN BOCR.prj (project) ---

Proj Title=UNT 066 IN BOCR Base Level Engineering
Current Plan=p01
Default Exp/Contr=0.3,0.1
English Units
Geom File=g01
Flow File=f01
Plan File=p01
BEGIN DESCRIPTION:
UNT 066 IN BOCR
END DESCRIPTION:

--- UNT 066 IN BOCR.p01 (plan) ---

Plan Title=Multiple Run
Short Identifier=Multiple
Geom File=g01
Flow File=f01
Subcritical Flow
K Sum by GR= 0
Std Step Tol= 0.01
Critical Tol= 0.01
Num of Std Step Trials= 20
Max Error Tol= 0.3
Flow Tol Ratio= 0.001
Split Flow NTrial= 30
Split Flow Tol= 0.02
Split Flow Ratio= 0.02
Log Output Level= 0
Friction Slope Method= 1
Unsteady Friction Slope Method= 2
Unsteady Bridges Friction Slope Method= 1
Parabolic Critical Depth
Global Vel Dist=  1 , 1 , 1
Global Log Level= 0
CheckData=True
Encroach Param= -1, 0, 0, 0
BEGIN DESCRIPTION:
Multiple Run
END DESCRIPTION:

--- UNT 066 IN BOCR.f01 (steady flow) ---

Flow Title=Multiple
Number of Profiles=7
Profile Names=10-year,25-year,50-year,1pct_min,100-year,1pct_plu,500-year
River Rch & RM= UNT 066 IN BOCR,Reach-1,2541
     477     638     771     686     927    1254    1344
Boundary for River Rch & Prof#=UNT 066 IN BOCR,Reach-1,1
Up Type=0
Dn Type=3
Dn Slope=0.005
Boundary for River Rch & Prof#=UNT 066 IN BOCR,Reach-1,2
Up Type=0
Dn Type=3
Dn Slope=0.005
Boundary for River Rch & Prof#=UNT 066 IN BOCR,Reach-1,3
Up Type=0
Dn Type=3
Dn Slope=0.005
Boundary for River Rch & Prof#=UNT 066 IN BOCR,Reach-1,4
Up Type=0
Dn Type=3
Dn Slope=0.005
Boundary for River Rch & Prof#=UNT 066 IN BOCR,Reach-1,5
Up Type=0
Dn Type=3
Dn Slope=0.005
Boundary for River Rch & Prof#=UNT 066 IN BOCR,Reach-1,6
Up Type=0
Dn Type=3
Dn Slope=0.005
Boundary for River Rch & Prof#=UNT 066 IN BOCR,Reach-1,7
Up Type=0
Dn Type=3
Dn Slope=0.005

--- UNT 066 IN BOCR.g01 (geometry) ---

Geom Title=Existing Conditions

River Reach=UNT 066 IN BOCR,Reach-1
Reach XY= 30
      3786668.25     10575600.00      3786581.50     10575651.00
      3786628.50     10575711.00      3786598.00     10575757.00
      3786512.00     10575758.00      3786445.50     10575804.00
      3786345.75     10575769.00      3786336.00     10575899.00
      3786276.25     10575940.00      3786257.75     10575995.00
      3786160.75     10575963.00      3786162.50     10576031.00
      3786093.50     10576050.00      3786067.00     10576096.00
      3785966.50     10576088.00      3785948.50     10576143.00
      3785878.50     10576116.00      3785866.25     10576295.00
      3785824.50     10576336.00      3785852.00     10576436.00
      3785718.00     10576496.00      3785659.50     10576491.00
      3785643.25     10576602.00      3785560.25     10576595.00
      3785523.00     10576631.00      3785525.25     10576802.00
      3785320.50     10576889.00      3785237.50     10576875.00
      3785137.00     10577058.00      3785079.50     10577070.00

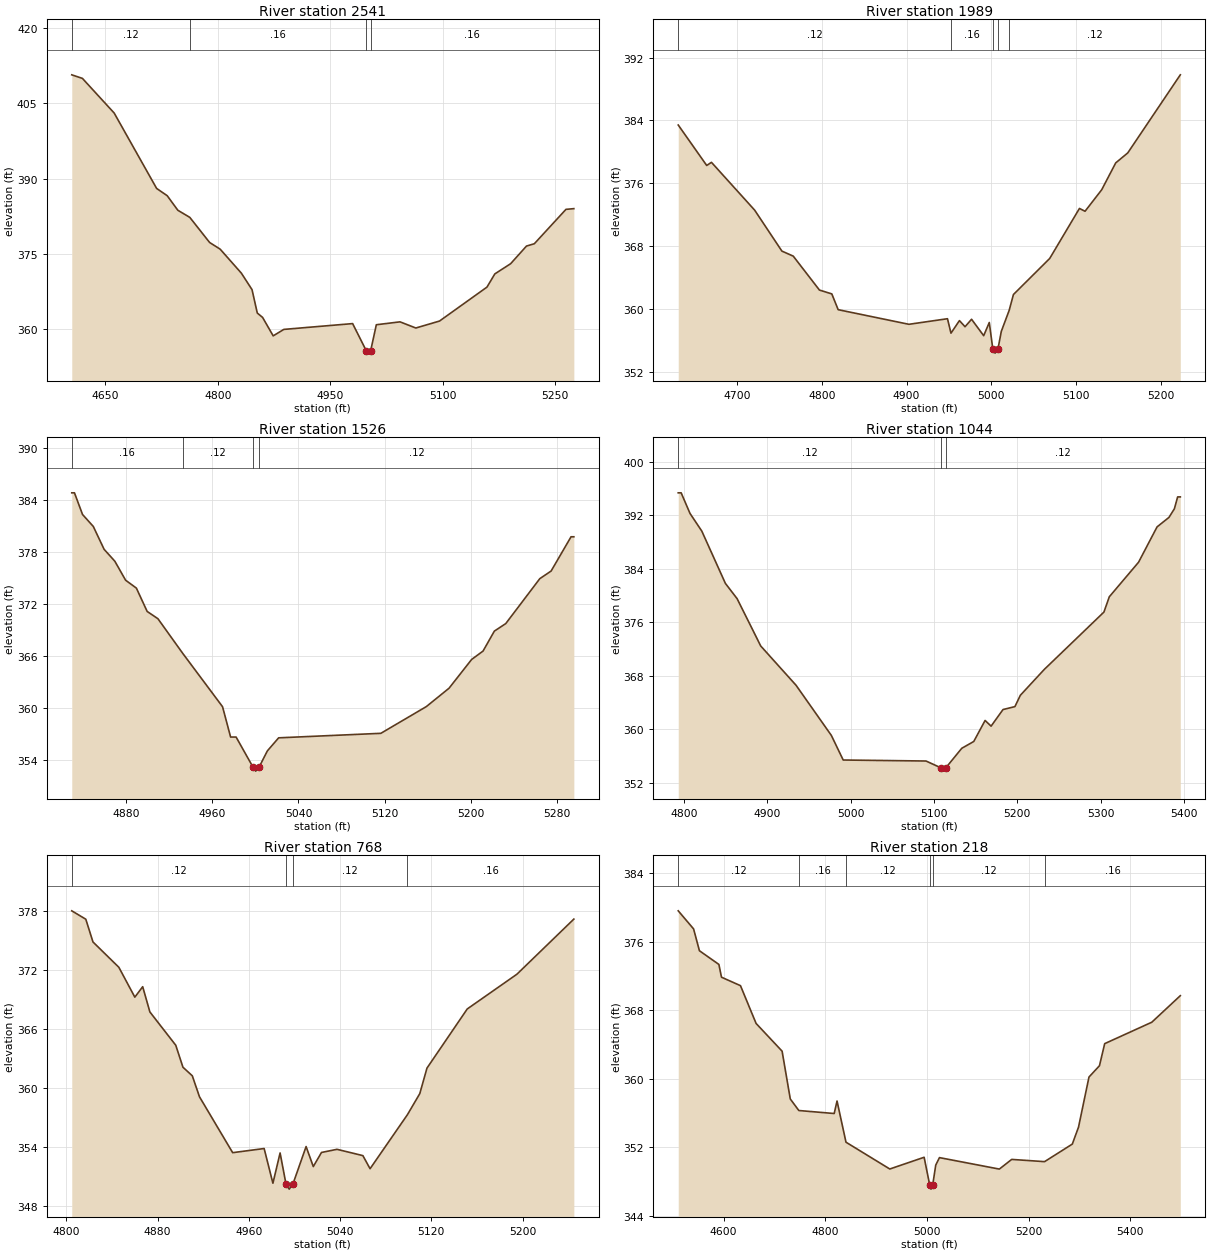
Type RM Length L Ch R = 1,2541,552,552,552
BEGIN DESCRIPTION:
UNT 066 IN BOCR 5.0
END DESCRIPTION:
XS GIS Cut Line= 3
      3786149.58     10575510.16      3786399.61     10575760.19
      3786499.60     10576060.16
#Sta/Elev= 30
  4605.3  410.72  4619.5  410.01  4661.9  403.08  4718.5  388.02  4732.6  386.57
  4746.8  383.66  4762.8  382.23  4789.2  377.22  4803.3  375.88  4831.6  371.08
  4845.8  367.79  4852.8  363.12  4859.9  362.24  4874.0  358.56  4888.2  359.85
  4980.0  361.01  4998.1  355.61  5000.8  355.11  5004.1  355.61  5011.6  360.78
  5043.2  361.36  5064.3  360.13  5095.9  361.52  5159.2  368.30  5169.7  370.94
  5190.8  372.98  5211.9  376.50  5222.4  376.97  5264.6  383.84  5275.1  383.98
#Mann=4,-1,0
  4605.3    0.12       0  4762.8    0.16       0  4998.1    0.07       0
  5004.1    0.16       0
Bank Sta=4998.1,5004.1
Exp/Cntr=0.3,0.1

Type RM Length L Ch R = 1,1989,463,463,463
BEGIN DESCRIPTION:
UNT 066 IN BOCR 4.0
END DESCRIPTION:
XS GIS Cut Line= 3
      3785977.94     10575709.61      3786115.68     10576000.73
      3786292.18     10576205.51
#Sta/Elev= 30
  4630.6  383.42  4664.2  378.27  4669.8  378.67  4720.8  372.58  4752.9  367.37
  4766.3  366.73  4797.2  362.41  4811.8  361.92  4819.3  359.91  4902.8  358.05
  4948.3  358.76  4952.4  356.92  4962.4  358.52  4969.0  357.74  4976.7  358.69
  4991.0  356.60  4997.6  358.28  5001.8  354.88  5004.5  354.38  5007.8  354.88
  5011.8  357.15  5021.1  359.83  5026.1  361.84  5068.9  366.43  5104.0  372.80
  5110.6  372.44  5130.2  375.17  5146.8  378.60  5161.0  379.87  5223.0  389.81
#Mann=5,-1,0
  4630.6    0.12       0  4952.4    0.16       0  5001.8    0.07       0
  5007.8    0.16       0  5021.1    0.12       0
Bank Sta=5001.8,5007.8
Exp/Cntr=0.3,0.1

Type RM Length L Ch R = 1,1526,482,482,482
BEGIN DESCRIPTION:
UNT 066 IN BOCR 3.0
END DESCRIPTION:
XS GIS Cut Line= 3
      3785699.64     10576210.19      3785849.61     10576210.19
      3786149.61     10576310.19
#Sta/Elev= 30
  4829.5  384.80  4832.0  384.80  4839.5  382.30  4849.5  380.92  4859.5  378.29
  4869.5  376.91  4879.5  374.72  4889.5  373.81  4899.5  371.12  4909.5  370.28
  4932.5  366.29  4969.5  360.13  4977.0  356.63  4982.1  356.63  4997.6  353.20
  5000.3  352.70  5003.6  353.20  5011.1  355.03  5021.6  356.54  5116.5  357.06
  5158.7  360.14  5179.8  362.26  5200.8  365.58  5211.4  366.55  5221.9  368.85
  5232.5  369.72  5264.1  374.90  5274.6  375.78  5293.1  379.73  5295.7  379.73
#Mann=4,-1,0
  4829.5    0.16       0  4932.5    0.12       0  4997.6    0.07       0
  5003.6    0.12       0
Bank Sta=4997.6,5003.6
Exp/Cntr=0.3,0.1

Type RM Length L Ch R = 1,1044,276,276,276
BEGIN DESCRIPTION:
UNT 066 IN BOCR 2.0
END DESCRIPTION:
XS GIS Cut Line= 3
      3785499.61     10576360.19      3785649.61     10576510.19
      3785949.58     10576760.16
#Sta/Elev= 30
  4793.1  395.35  4796.6  395.35  4807.2  392.28  4821.4  389.63  4849.7  381.82
  4863.8  379.53  4892.1  372.47  4934.5  366.60  4976.9  359.10  4991.1  355.43
  5090.5  355.28  5108.3  354.27  5111.1  353.77  5114.3  354.27  5133.4  357.18
  5147.8  358.20  5161.4  361.34  5168.6  360.49  5182.9  362.97  5197.2  363.41
  5203.7  365.10  5232.4  368.96  5304.0  377.53  5310.5  379.82  5345.6  384.98
  5367.8  390.26  5382.1  391.68  5388.6  392.97  5392.5  394.74  5395.7  394.74
#Mann=3,-1,0
  4793.1    0.12       0  5108.3    0.07       0  5114.3    0.12       0
Bank Sta=5108.3,5114.3
Exp/Cntr=0.3,0.1

Type RM Length L Ch R = 1,768,550,550,550
BEGIN DESCRIPTION:
Mapping XS 28958dd3
END DESCRIPTION:
XS GIS Cut Line= 2
      3785365.68     10576547.07      3785715.31     10576814.69
#Sta/Elev= 30
  4804.7  377.99  4817.0  377.14  4823.3  374.83  4846.0  372.26  4860.0  369.23
  4866.9  370.29  4873.2  367.73  4895.9  364.35  4902.2  362.12  4910.4  361.25
  4916.7  359.12  4945.8  353.45  4973.4  353.87  4981.1  350.35  4987.4  353.42
  4992.6  350.25  4995.4  349.75  4998.6  350.25  5010.2  354.07  5016.5  352.04
  5023.7  353.47  5037.3  353.79  5060.0  353.15  5066.3  351.82  5099.1  357.31
  5109.9  359.44  5116.2  362.03  5151.5  368.03  5195.1  371.56  5245.0  377.15
#Mann=4,-1,0
  4804.7    0.12       0  4992.6    0.07       0  4998.6    0.12       0
  5099.1    0.16       0
Bank Sta=4992.6,4998.6
Exp/Cntr=0.3,0.1

Type RM Length L Ch R = 1,218,0,0,0
BEGIN DESCRIPTION:
UNT 066 IN BOCR 1.0
END DESCRIPTION:
XS GIS Cut Line= 4
      3785252.84     10576490.67      3785161.69     10576898.64
      3785361.35     10577007.15      3785694.10     10576925.04
#Sta/Elev= 30
  4510.7  379.59  4540.9  377.48  4552.4  374.93  4590.7  373.33  4595.8  371.84
  4633.2  370.85  4663.9  366.44  4715.1  363.20  4731.2  357.62  4748.0  356.27
  4817.6  355.92  4823.2  357.38  4840.8  352.57  4927.0  349.44  4994.6  350.81
  5005.5  347.59  5008.2  347.09  5011.5  347.59  5017.4  349.89  5024.7  350.77
  5142.6  349.43  5166.9  350.56  5231.6  350.30  5286.2  352.35  5298.4  354.33
  5319.0  360.18  5339.6  361.50  5349.9  364.08  5442.6  366.58  5498.7  369.68
#Mann=6,-1,0
  4510.7    0.12       0  4748.0    0.16       0  4840.8    0.12       0
  5005.5    0.07       0  5011.5    0.12       0  5231.6    0.16       0
Bank Sta=5005.5,5011.5
Exp/Cntr=0.3,0.1

Chan Stop Cuts=-1