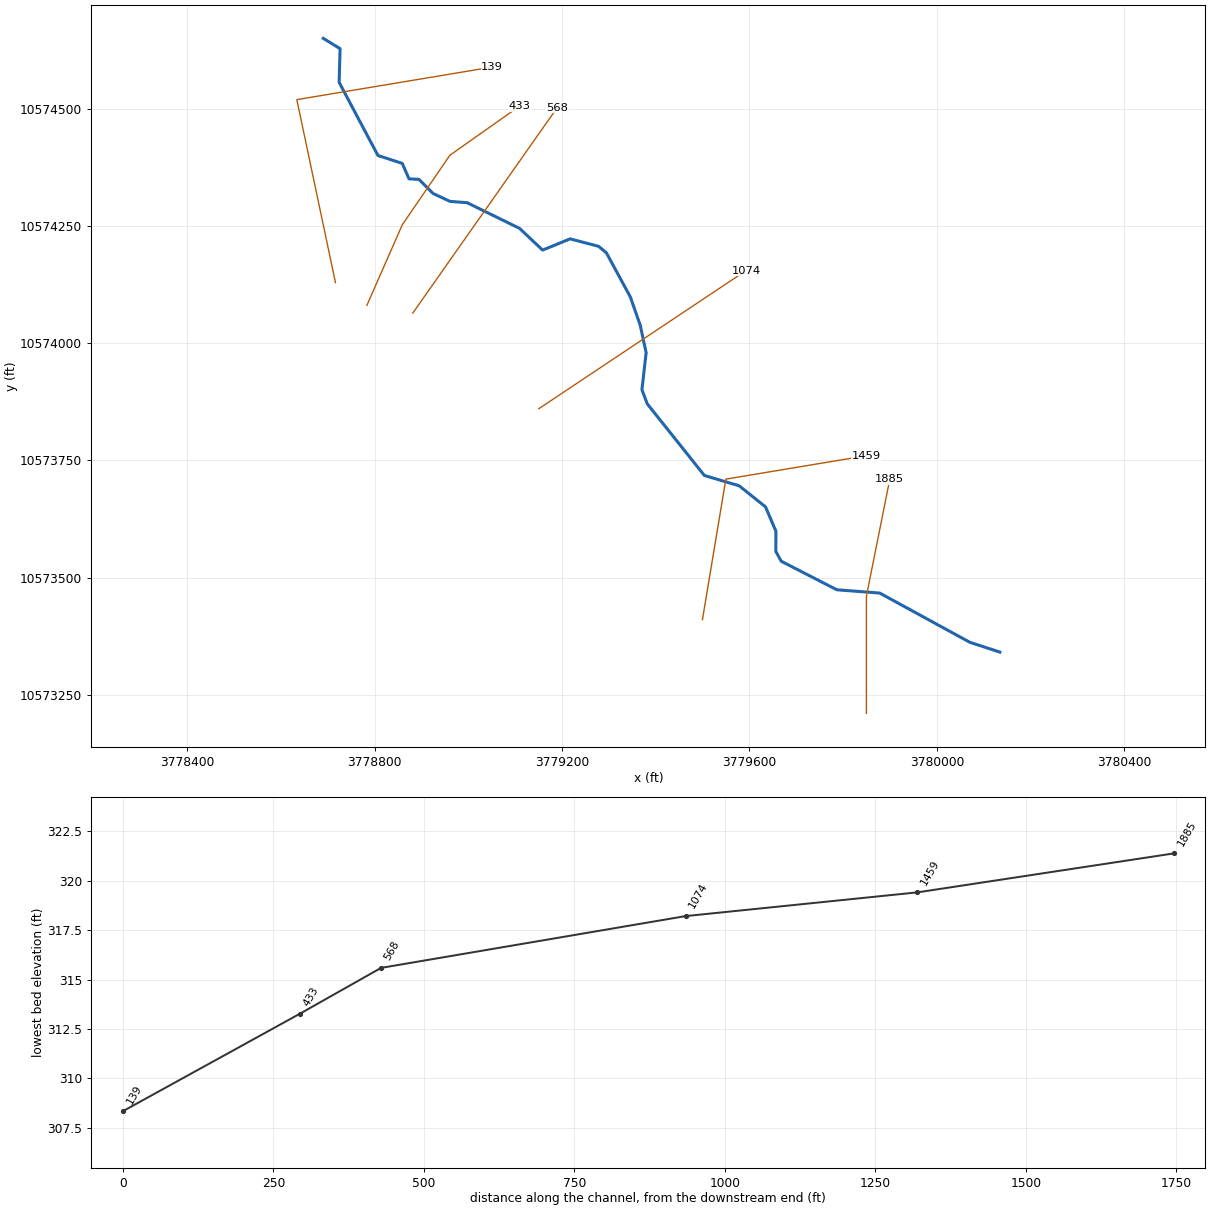
--- UNT 067 IN BOCR.prj (project) ---

Proj Title=UNT 067 IN BOCR Base Level Engineering
Current Plan=p01
Default Exp/Contr=0.3,0.1
English Units
Geom File=g01
Flow File=f01
Plan File=p01
BEGIN DESCRIPTION:
UNT 067 IN BOCR
END DESCRIPTION:

--- UNT 067 IN BOCR.p01 (plan) ---

Plan Title=Multiple Run
Short Identifier=Multiple
Geom File=g01
Flow File=f01
Subcritical Flow
K Sum by GR= 0
Std Step Tol= 0.01
Critical Tol= 0.01
Num of Std Step Trials= 20
Max Error Tol= 0.3
Flow Tol Ratio= 0.001
Split Flow NTrial= 30
Split Flow Tol= 0.02
Split Flow Ratio= 0.02
Log Output Level= 0
Friction Slope Method= 1
Unsteady Friction Slope Method= 2
Unsteady Bridges Friction Slope Method= 1
Parabolic Critical Depth
Global Vel Dist=  1 , 1 , 1
Global Log Level= 0
CheckData=True
Encroach Param= -1, 0, 0, 0
BEGIN DESCRIPTION:
Multiple Run
END DESCRIPTION:

--- UNT 067 IN BOCR.f01 (steady flow) ---

Flow Title=Multiple
Number of Profiles=7
Profile Names=10-year,25-year,50-year,1pct_min,100-year,1pct_plu,500-year
River Rch & RM= UNT 067 IN BOCR,Reach-1,1885
     238     304     356     307     416     562     567
Boundary for River Rch & Prof#=UNT 067 IN BOCR,Reach-1,1
Up Type=0
Dn Type=3
Dn Slope=0.005
Boundary for River Rch & Prof#=UNT 067 IN BOCR,Reach-1,2
Up Type=0
Dn Type=3
Dn Slope=0.005
Boundary for River Rch & Prof#=UNT 067 IN BOCR,Reach-1,3
Up Type=0
Dn Type=3
Dn Slope=0.005
Boundary for River Rch & Prof#=UNT 067 IN BOCR,Reach-1,4
Up Type=0
Dn Type=3
Dn Slope=0.005
Boundary for River Rch & Prof#=UNT 067 IN BOCR,Reach-1,5
Up Type=0
Dn Type=3
Dn Slope=0.005
Boundary for River Rch & Prof#=UNT 067 IN BOCR,Reach-1,6
Up Type=0
Dn Type=3
Dn Slope=0.005
Boundary for River Rch & Prof#=UNT 067 IN BOCR,Reach-1,7
Up Type=0
Dn Type=3
Dn Slope=0.005

--- UNT 067 IN BOCR.g01 (geometry) ---

Geom Title=Existing Conditions

River Reach=UNT 067 IN BOCR,Reach-1
Reach XY= 30
      3780134.50     10573341.00      3780070.25     10573362.00
      3779878.00     10573467.00      3779786.50     10573474.00
      3779667.75     10573535.00      3779656.25     10573556.00
      3779656.50     10573599.00      3779634.25     10573651.00
      3779578.00     10573696.00      3779503.75     10573718.00
      3779381.75     10573871.00      3779370.50     10573901.00
      3779379.50     10573980.00      3779366.75     10574039.00
      3779345.75     10574099.00      3779294.75     10574193.00
      3779278.25     10574207.00      3779217.25     10574223.00
      3779158.50     10574199.00      3779109.29     10574245.42
      3778997.35     10574300.19      3778960.75     10574303.00
      3778924.50     10574320.00      3778894.57     10574350.02
      3778873.39     10574351.06      3778859.00     10574384.00
      3778807.00     10574401.00      3778724.25     10574557.00
      3778726.25     10574629.00      3778690.25     10574651.00

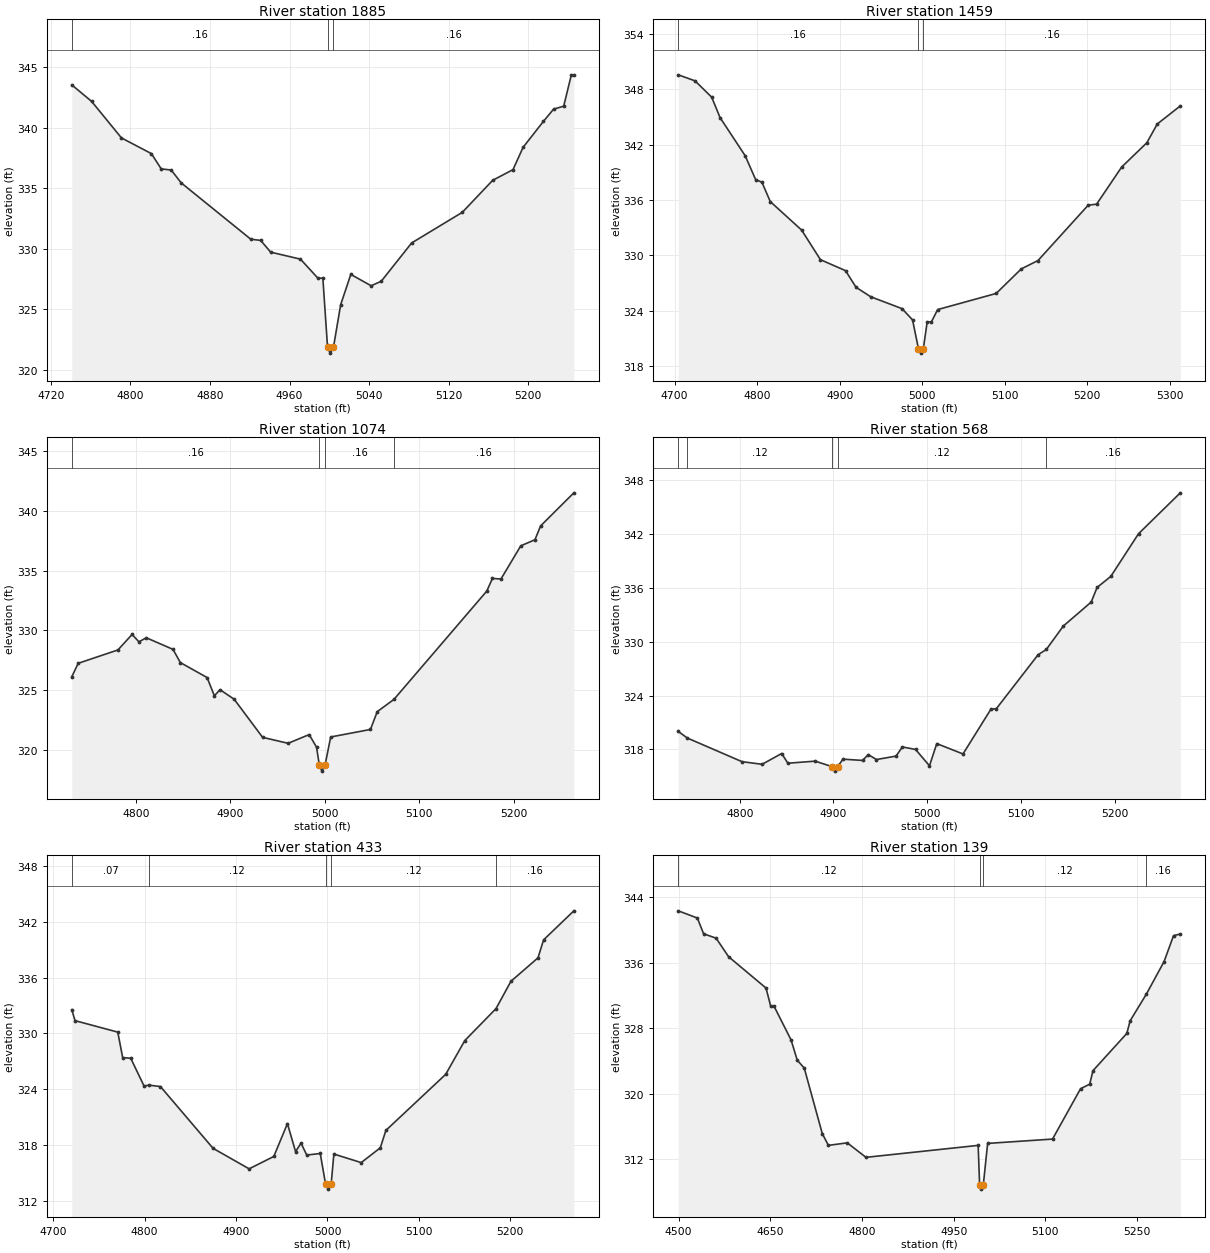
Type RM Length L Ch R = 1,1885,426,426,426
BEGIN DESCRIPTION:
UNT 067 IN BOCR 4.0
END DESCRIPTION:
XS GIS Cut Line= 3
      3779849.61     10573210.21      3779849.61     10573460.19
      3779899.60     10573710.16
#Sta/Elev= 30
  4741.0  343.56  4761.0  342.19  4791.0  339.17  4821.0  337.88  4831.0  336.61
  4841.0  336.52  4851.0  335.46  4921.0  330.80  4931.0  330.70  4941.0  329.73
  4971.0  329.15  4988.5  327.58  4993.5  327.58  4998.2  321.88  5000.9  321.38
  5004.2  321.88  5011.4  325.38  5021.6  327.89  5042.0  326.95  5052.2  327.32
  5082.8  330.49  5133.7  333.02  5164.3  335.67  5184.7  336.55  5194.9  338.40
  5215.3  340.54  5225.5  341.55  5235.7  341.80  5243.4  344.39  5245.9  344.39
#Mann=3,-1,0
  4741.0    0.16       0  4998.2    0.07       0  5004.2    0.16       0
Bank Sta=4998.2,5004.2
Exp/Cntr=0.3,0.1

Type RM Length L Ch R = 1,1459,385,385,385
BEGIN DESCRIPTION:
UNT 067 IN BOCR 3.0
END DESCRIPTION:
XS GIS Cut Line= 3
      3779499.61     10573410.20      3779549.61     10573710.19
      3779849.64     10573760.19
#Sta/Elev= 30
  4704.4  349.58  4724.7  348.93  4744.9  347.16  4755.1  344.94  4785.5  340.81
  4798.2  338.22  4805.8  337.94  4815.9  335.84  4853.9  332.75  4876.7  329.54
  4907.1  328.35  4919.8  326.55  4937.6  325.52  4975.6  324.23  4988.3  323.01
  4995.4  319.91  4998.1  319.41  5001.4  319.91  5006.0  322.79  5011.1  322.79
  5018.7  324.13  5089.6  325.88  5120.0  328.54  5140.3  329.45  5201.1  335.45
  5211.3  335.56  5241.7  339.59  5272.1  342.21  5284.8  344.25  5312.7  346.21
#Mann=3,-1,0
  4704.4    0.16       0  4995.4    0.07       0  5001.4    0.16       0
Bank Sta=4995.4,5001.4
Exp/Cntr=0.3,0.1

Type RM Length L Ch R = 1,1074,506,506,506
BEGIN DESCRIPTION:
UNT 067 IN BOCR 2.0
END DESCRIPTION:
XS GIS Cut Line= 2
      3779150.41     10573860.45      3779592.81     10574155.38
#Sta/Elev= 30
  4732.2  326.11  4739.0  327.24  4781.1  328.36  4796.1  329.66  4803.3  329.04
  4811.1  329.38  4839.4  328.41  4847.2  327.30  4875.5  326.05  4883.2  324.52
  4889.2  325.03  4904.2  324.23  4934.3  321.04  4961.3  320.54  4983.6  321.27
  4991.4  320.22  4994.4  318.71  4997.1  318.21  5000.4  318.71  5006.4  321.07
  5048.5  321.70  5055.7  323.19  5073.4  324.22  5171.7  333.29  5177.7  334.35
  5186.7  334.30  5207.7  337.08  5222.7  337.59  5228.7  338.75  5263.9  341.52
#Mann=4,-1,0
  4732.2    0.16       0  4994.4    0.07       0  5000.4    0.16       0
  5073.4    0.16       0
Bank Sta=4994.4,5000.4
Exp/Cntr=0.3,0.1

Type RM Length L Ch R = 1,568,135,135,135
BEGIN DESCRIPTION:
Mapping XS a0e86f0f
END DESCRIPTION:
XS GIS Cut Line= 2
      3778881.34     10574064.48      3779189.47     10574502.81
#Sta/Elev= 30
  4734.4  320.01  4744.1  319.27  4802.5  316.64  4823.9  316.35  4844.8  317.55
  4851.4  316.47  4880.6  316.70  4898.5  316.09  4901.2  315.59  4904.5  316.09
  4910.2  316.92  4931.1  316.78  4937.2  317.43  4945.9  316.88  4966.8  317.26
  4973.6  318.28  4987.7  318.00  5002.5  316.18  5010.3  318.65  5038.3  317.50
  5067.9  322.45  5074.0  322.55  5118.4  328.53  5127.2  329.12  5145.4  331.73
  5175.1  334.39  5181.4  336.02  5196.0  337.24  5225.6  341.99  5270.2  346.54
#Mann=5,-1,0
  4734.4    0.07       0  4744.1    0.12       0  4898.5    0.07       0
  4904.5    0.12       0  5127.2    0.16       0
Bank Sta=4898.5,4904.5
Exp/Cntr=0.3,0.1

Type RM Length L Ch R = 1,433,294,294,294
BEGIN DESCRIPTION:
Mapping XS 1b3aefd6
END DESCRIPTION:
XS GIS Cut Line= 4
      3778783.49     10574081.18      3778859.01     10574253.06
      3778960.57     10574401.49      3779109.04     10574506.07
#Sta/Elev= 30
  4720.3  332.55  4723.9  331.37  4770.6  330.14  4776.0  327.40  4784.8  327.33
  4799.4  324.34  4804.8  324.44  4817.3  324.29  4874.9  317.65  4914.3  315.45
  4941.3  316.78  4956.2  320.31  4965.1  317.30  4971.1  318.21  4977.3  316.93
  4992.1  317.10  4998.0  313.77  5000.7  313.27  5004.0  313.77  5007.0  317.04
  5036.9  316.12  5057.8  317.71  5063.9  319.58  5129.3  325.60  5150.2  329.23
  5184.4  332.67  5200.7  335.60  5230.3  338.12  5236.4  340.05  5269.5  343.17
#Mann=5,-1,0
  4720.3    0.07       0  4804.8    0.12       0  4998.0    0.07       0
  5004.0    0.12       0  5184.4    0.16       0
Bank Sta=4998,5004
Exp/Cntr=0.3,0.1

Type RM Length L Ch R = 1,139,0,0,0
BEGIN DESCRIPTION:
UNT 067 IN BOCR 1.0
END DESCRIPTION:
XS GIS Cut Line= 3
      3778716.37     10574129.59      3778633.91     10574520.17
      3779050.57     10574589.61
#Sta/Elev= 30
  4499.3  342.31  4530.6  341.43  4540.8  339.51  4561.3  338.97  4581.7  336.71
  4643.0  332.88  4650.6  330.66  4655.7  330.72  4683.9  326.56  4694.1  324.07
  4705.5  323.12  4735.0  315.12  4745.0  313.68  4775.9  313.99  4806.5  312.22
  4990.1  313.68  4992.5  308.84  4995.3  308.34  4998.5  308.84  5005.6  313.92
  5111.8  314.45  5157.7  320.60  5172.6  321.15  5178.0  322.80  5233.4  327.35
  5238.8  328.89  5265.1  332.11  5294.3  336.11  5309.8  339.28  5320.9  339.48
#Mann=4,-1,0
  4499.3    0.12       0  4992.5    0.07       0  4998.5    0.12       0
  5265.1    0.16       0
Bank Sta=4992.5,4998.5
Exp/Cntr=0.3,0.1

Chan Stop Cuts=-1