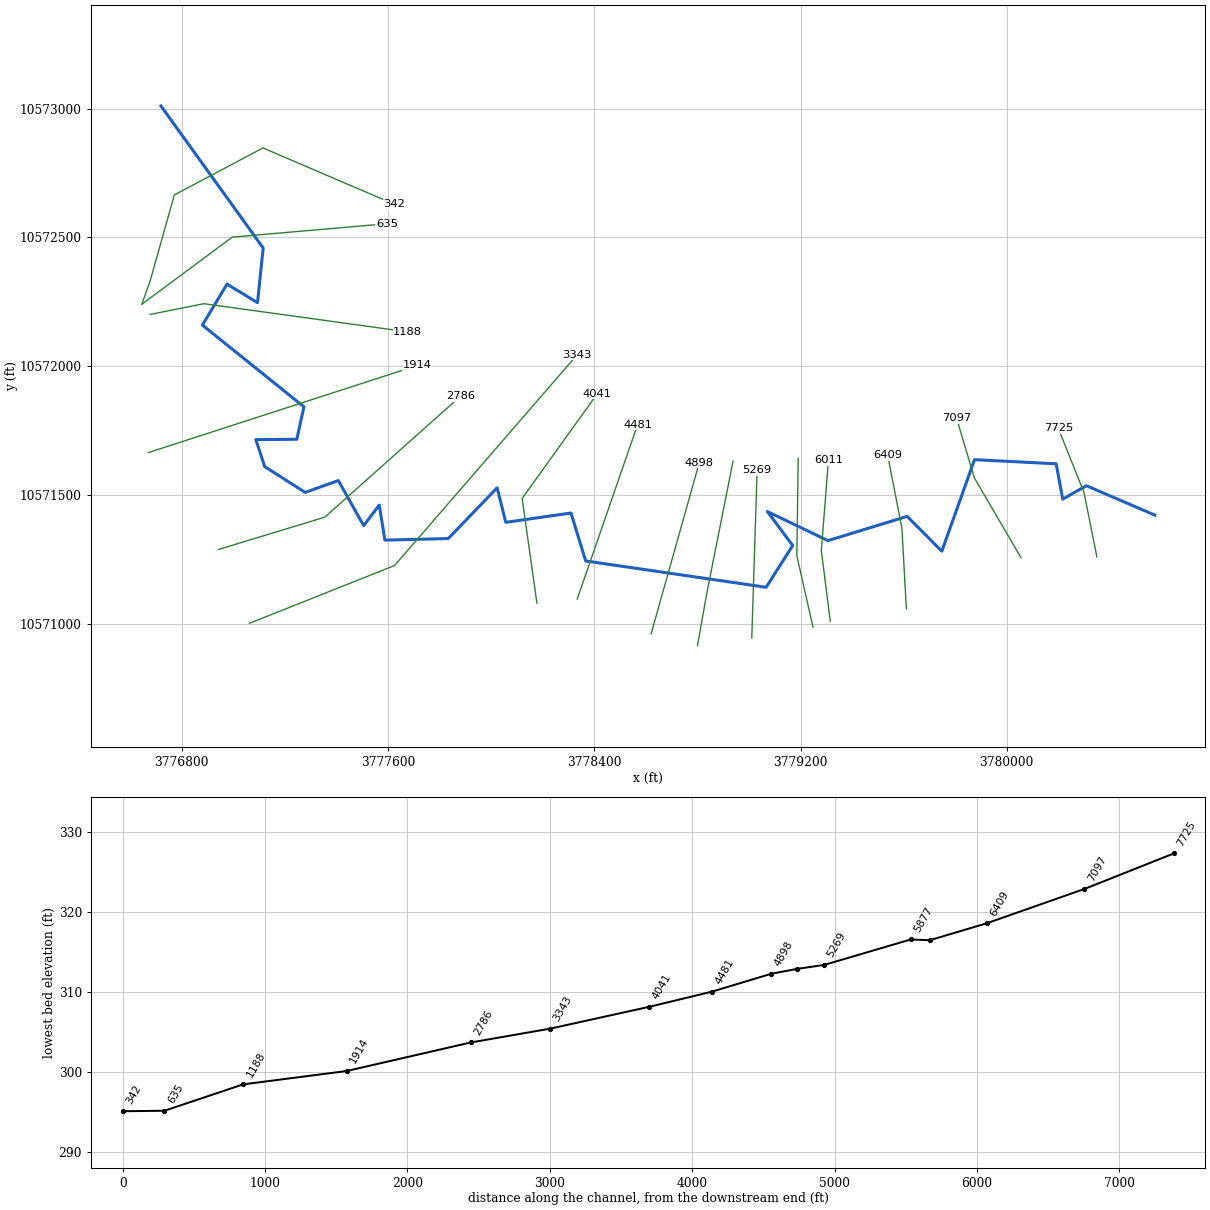
--- UNT 068 IN BOCR.prj (project) ---

Proj Title=UNT 068 IN BOCR Base Level Engineering
Current Plan=p01
Default Exp/Contr=0.3,0.1
English Units
Geom File=g01
Flow File=f01
Plan File=p01
Y Axis Title=Elevation
X Axis Title(PF)=Main Channel Distance
X Axis Title(XS)=Station
BEGIN DESCRIPTION:
UNT 068 IN BOCR
END DESCRIPTION:
DSS Export Rating Curves= 0
DSS Export Rating Curve Sorted= 0
DSS Export Volume Flow Curves= 0
DXF OffsetX= 0
DXF OffsetY= 0
DXF ScaleX= 1
DXF ScaleY= 10

--- UNT 068 IN BOCR.p01 (plan) ---

Plan Title=Multiple Run
Short Identifier=Multiple
Geom File=g01
Flow File=f01
Subcritical Flow
K Sum by GR= 0
Std Step Tol= 0.01
Critical Tol= 0.01
Num of Std Step Trials= 20
Max Error Tol= 0.3
Flow Tol Ratio= 0.001
Split Flow NTrial= 30
Split Flow Tol= 0.02
Split Flow Ratio= 0.02
Log Output Level= 0
Friction Slope Method= 1
Unsteady Friction Slope Method= 2
Unsteady Bridges Friction Slope Method= 1
Parabolic Critical Depth
Global Vel Dist=  1 , 1 , 1
Global Log Level= 0
CheckData=True
Encroach Param= -1, 0, 0, 0
BEGIN DESCRIPTION:
Multiple Run
END DESCRIPTION:

--- UNT 068 IN BOCR.f01 (steady flow) ---

Flow Title=Multiple
Program Version=4.10
Number of Profiles= 7
Profile Names=10-year,25-year,50-year,1pct_min,100-year,1pct_plu,500-year
River Rch & RM=UNT 068 IN BOCR,Reach-1         ,7725
     550     738     892     793    1072    1450    1554
River Rch & RM=UNT 068 IN BOCR,Reach-1         ,3343
     783    1071    1311    1179    1595    2157    2368
River Rch & RM=UNT 068 IN BOCR,Reach-1         ,1914
     783    1071    1311    1179    1595    2157    2368
Boundary for River Rch & Prof#=UNT 068 IN BOCR,Reach-1         , 1
Up Type= 0
Dn Type= 3
Dn Slope=0.005
Boundary for River Rch & Prof#=UNT 068 IN BOCR,Reach-1         , 2
Up Type= 0
Dn Type= 3
Dn Slope=0.005
Boundary for River Rch & Prof#=UNT 068 IN BOCR,Reach-1         , 3
Up Type= 0
Dn Type= 3
Dn Slope=0.005
Boundary for River Rch & Prof#=UNT 068 IN BOCR,Reach-1         , 4
Up Type= 0
Dn Type= 3
Dn Slope=0.005
Boundary for River Rch & Prof#=UNT 068 IN BOCR,Reach-1         , 5
Up Type= 0
Dn Type= 3
Dn Slope=0.005
Boundary for River Rch & Prof#=UNT 068 IN BOCR,Reach-1         , 6
Up Type= 0
Dn Type= 3
Dn Slope=0.005
Boundary for River Rch & Prof#=UNT 068 IN BOCR,Reach-1         , 7
Up Type= 0
Dn Type= 3
Dn Slope=0.005
DSS Import GetInterval= 0
DSS Import GetPeak= 0
DSS Import FillOption= 0

--- UNT 068 IN BOCR.g01 (geometry) ---

Geom Title=Existing Conditions

River Reach=UNT 068 IN BOCR,Reach-1
Reach XY= 30
      3780574.00     10571423.00      3780309.00     10571537.00
      3780217.00     10571485.00      3780191.50     10571622.00
      3779874.75     10571638.00      3779748.25     10571283.00
      3779613.50     10571418.00      3779306.50     10571324.00
      3779071.43     10571436.78      3779169.75     10571305.00
      3779066.75     10571143.00      3778367.00     10571245.00
      3778309.75     10571431.00      3778056.75     10571395.00
      3778023.50     10571529.00      3777833.75     10571332.00
      3777588.00     10571326.00      3777566.25     10571462.00
      3777505.75     10571382.00      3777407.50     10571557.00
      3777279.00     10571511.00      3777122.00     10571611.00
      3777087.50     10571716.00      3777246.50     10571717.00
      3777274.00     10571843.00      3776880.25     10572160.00
      3776975.75     10572319.00      3777094.00     10572247.00
      3777116.00     10572459.00      3776719.50     10573010.00

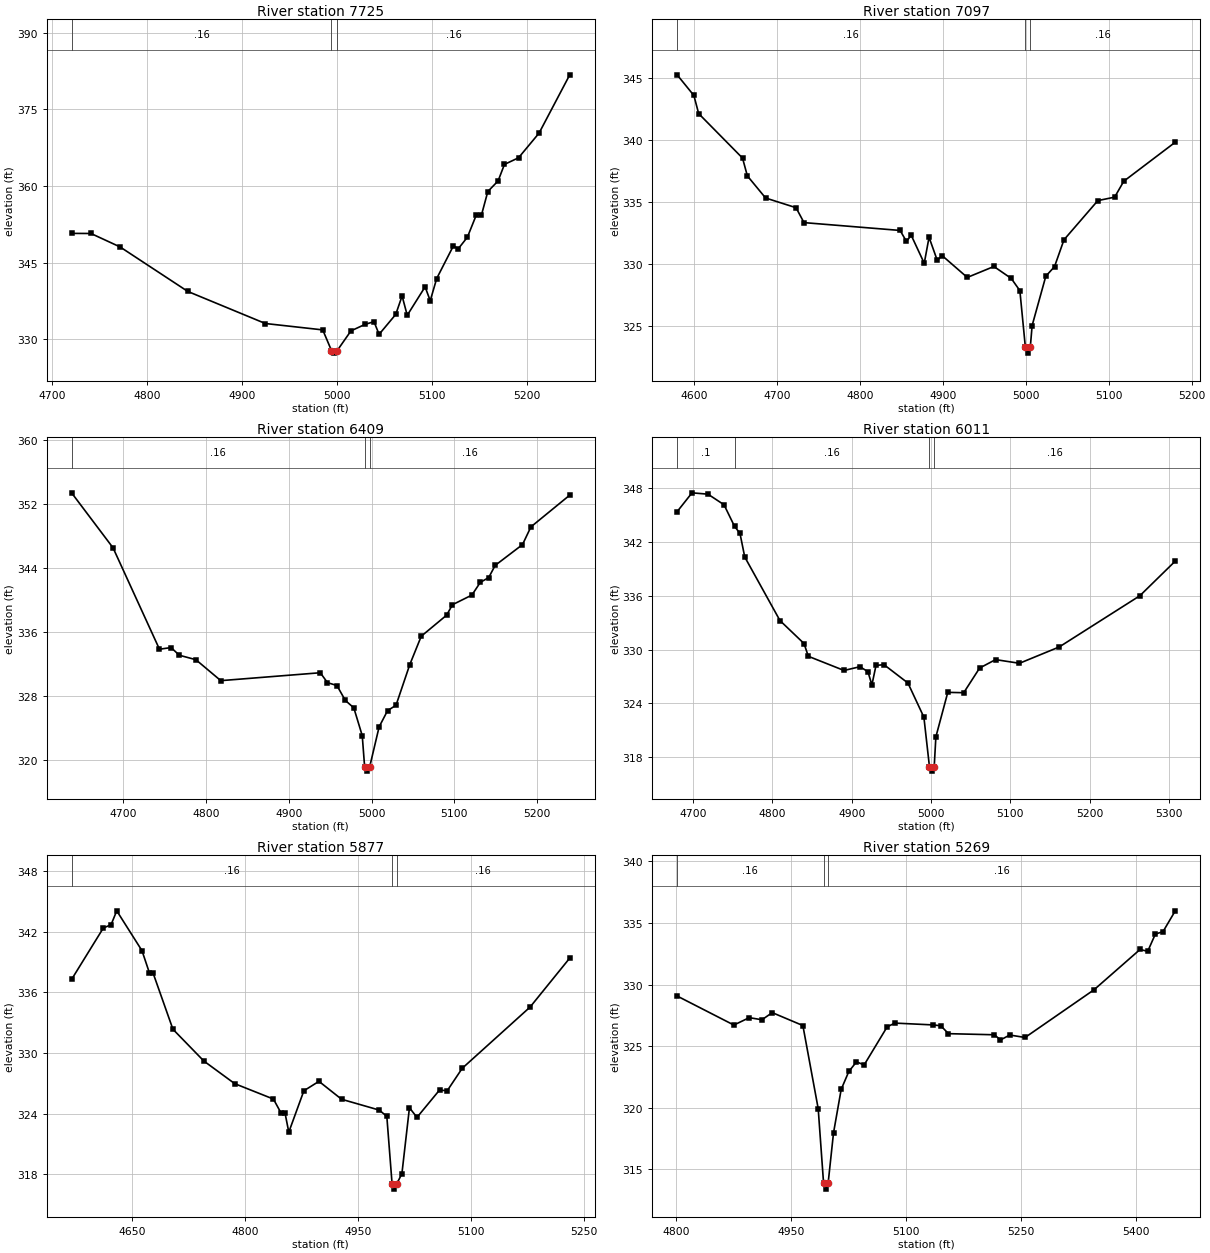
Type RM Length L Ch R = 1,7725,628,628,628
BEGIN DESCRIPTION:
UNT 068 IN BOCR 10.0
END DESCRIPTION:
XS GIS Cut Line= 3
      3780349.60     10571260.22      3780299.61     10571510.19
      3780199.60     10571760.21
#Sta/Elev= 30
  4720.8  350.73  4741.2  350.71  4771.8  348.08  4843.1  339.36  4924.7  333.08
  4985.1  331.83  4994.3  327.78  4997.0  327.28  5000.3  327.78  5014.8  331.64
  5029.6  332.91  5039.0  333.44  5044.4  330.96  5061.9  334.86  5068.6  338.48
  5074.0  334.69  5092.8  340.26  5098.2  337.54  5105.0  341.89  5122.5  348.26
  5127.8  347.74  5137.3  349.98  5146.7  354.34  5152.1  354.31  5158.8  358.93
  5169.6  361.00  5176.3  364.24  5191.1  365.53  5212.7  370.36  5245.0  381.78
#Mann=3,-1,0
  4720.8    0.16       0  4994.3    0.07       0  5000.3    0.16       0
Bank Sta=4994.3,5000.3
Exp/Cntr=0.3,0.1

Type RM Length L Ch R = 1,7097,688,688,688
BEGIN DESCRIPTION:
UNT 068 IN BOCR 9.0
END DESCRIPTION:
XS GIS Cut Line= 3
      3780055.02     10571258.05      3779874.45     10571567.10
      3779805.01     10571799.72
#Sta/Elev= 30
  4579.5  345.24  4599.7  343.58  4605.5  342.12  4658.4  338.54  4664.2  337.11
  4686.2  335.33  4722.9  334.55  4732.5  333.35  4848.4  332.72  4856.0  331.84
  4861.8  332.33  4877.5  330.08  4883.3  332.17  4893.2  330.31  4899.0  330.70
  4929.4  328.94  4961.5  329.82  4982.4  328.86  4992.8  327.88  4999.4  323.35
  5002.2  322.85  5005.4  323.35  5007.6  325.07  5024.1  329.04  5034.6  329.81
  5046.0  331.97  5086.8  335.12  5107.1  335.40  5118.1  336.68  5180.2  339.82
#Mann=3,-1,0
  4579.5    0.16       0  4999.4    0.07       0  5005.4    0.16       0
Bank Sta=4999.4,5005.4
Exp/Cntr=0.3,0.1

Type RM Length L Ch R = 1,6409,398,398,398
BEGIN DESCRIPTION:
UNT 068 IN BOCR 8.0
END DESCRIPTION:
XS GIS Cut Line= 3
      3779610.56     10571060.17      3779593.20     10571372.66
      3779537.87     10571656.24
#Sta/Elev= 30
  4637.6  353.38  4687.7  346.50  4743.8  333.81  4757.8  334.02  4767.8  333.06
  4787.8  332.50  4817.9  329.88  4938.1  330.87  4946.8  329.63  4958.2  329.27
  4968.4  327.40  4978.6  326.48  4988.8  323.00  4991.7  319.06  4994.4  318.56
  4997.7  319.06  5009.2  324.10  5019.4  326.13  5029.6  326.80  5046.2  331.88
  5060.1  335.44  5090.7  338.07  5097.8  339.38  5121.3  340.59  5131.4  342.17
  5141.6  342.78  5149.4  344.30  5182.4  346.90  5192.6  349.12  5239.5  353.09
#Mann=3,-1,0
  4637.6    0.16       0  4991.7    0.07       0  4997.7    0.16       0
Bank Sta=4991.7,4997.7
Exp/Cntr=0.3,0.1

Type RM Length L Ch R = 1,6011,134,134,134
BEGIN DESCRIPTION:
UNT 068 IN BOCR 7.0
END DESCRIPTION:
XS GIS Cut Line= 3
      3779315.42     10571011.59      3779280.70     10571285.85
      3779308.43     10571635.90
#Sta/Elev= 30
  4680.1  345.38  4698.9  347.48  4719.0  347.33  4739.2  346.15  4752.4  343.75
  4759.3  342.96  4765.3  340.33  4809.7  333.24  4840.0  330.68  4845.4  329.26
  4890.4  327.68  4910.5  328.10  4920.5  327.54  4925.5  326.07  4930.7  328.25
  4940.8  328.32  4970.9  326.28  4991.0  322.47  4998.0  316.96  5000.8  316.46
  5004.0  316.96  5006.1  320.28  5021.1  325.24  5041.2  325.20  5061.2  327.95
  5081.3  328.89  5111.4  328.48  5161.5  330.30  5263.1  336.01  5307.7  339.87
#Mann=4,-1,0
  4680.1     0.1       0  4752.4    0.16       0  4998.0    0.07       0
  5004.0    0.16       0
Bank Sta=4998,5004
Exp/Cntr=0.3,0.1

Type RM Length L Ch R = 1,5877,608,608,608
BEGIN DESCRIPTION:
Mapping XS 0f45ca53
END DESCRIPTION:
XS GIS Cut Line= 3
      3779248.37     10570989.11      3779185.87     10571265.19
      3779191.07     10571642.79
#Sta/Elev= 30
  4570.0  337.27  4612.1  342.35  4622.4  342.68  4629.9  344.05  4663.4  340.11
  4673.1  337.95  4678.2  337.88  4704.4  332.35  4745.4  329.21  4786.4  326.97
  4837.7  325.45  4847.9  324.06  4853.1  324.06  4858.1  322.18  4878.1  326.27
  4898.1  327.20  4928.1  325.43  4978.1  324.36  4988.1  323.74  4995.1  317.05
  4997.8  316.55  5001.1  317.05  5008.1  318.07  5018.1  324.59  5028.1  323.64
  5058.1  326.35  5068.1  326.26  5088.1  328.49  5178.1  334.54  5230.7  339.38
#Mann=3,-1,0
  4570.0    0.16       0  4995.1    0.07       0  5001.1    0.16       0
Bank Sta=4995.1,5001.1
Exp/Cntr=0.3,0.1

Type RM Length L Ch R = 1,5269,188,188,188
BEGIN DESCRIPTION:
UNT 068 IN BOCR 6.0
END DESCRIPTION:
XS GIS Cut Line= 2
      3779011.01     10570946.08      3779031.81     10571596.15
#Sta/Elev= 30
  4801.4  329.07  4875.5  326.71  4895.6  327.31  4912.2  327.14  4925.6  327.72
  4965.6  326.67  4985.6  319.92  4992.6  313.88  4995.4  313.38  4998.6  313.88
  5005.6  317.95  5015.6  321.48  5025.6  322.94  5035.6  323.72  5045.6  323.47
  5075.6  326.56  5085.6  326.87  5135.7  326.72  5145.7  326.65  5155.7  326.01
  5215.7  325.92  5223.6  325.50  5235.7  325.90  5255.7  325.70  5345.8  329.58
  5405.8  332.85  5415.8  332.70  5425.8  334.10  5435.8  334.30  5451.8  335.99
#Mann=3,-1,0
  4801.4    0.16       0  4992.6    0.07       0  4998.6    0.16       0
Bank Sta=4992.6,4998.6
Exp/Cntr=0.3,0.1

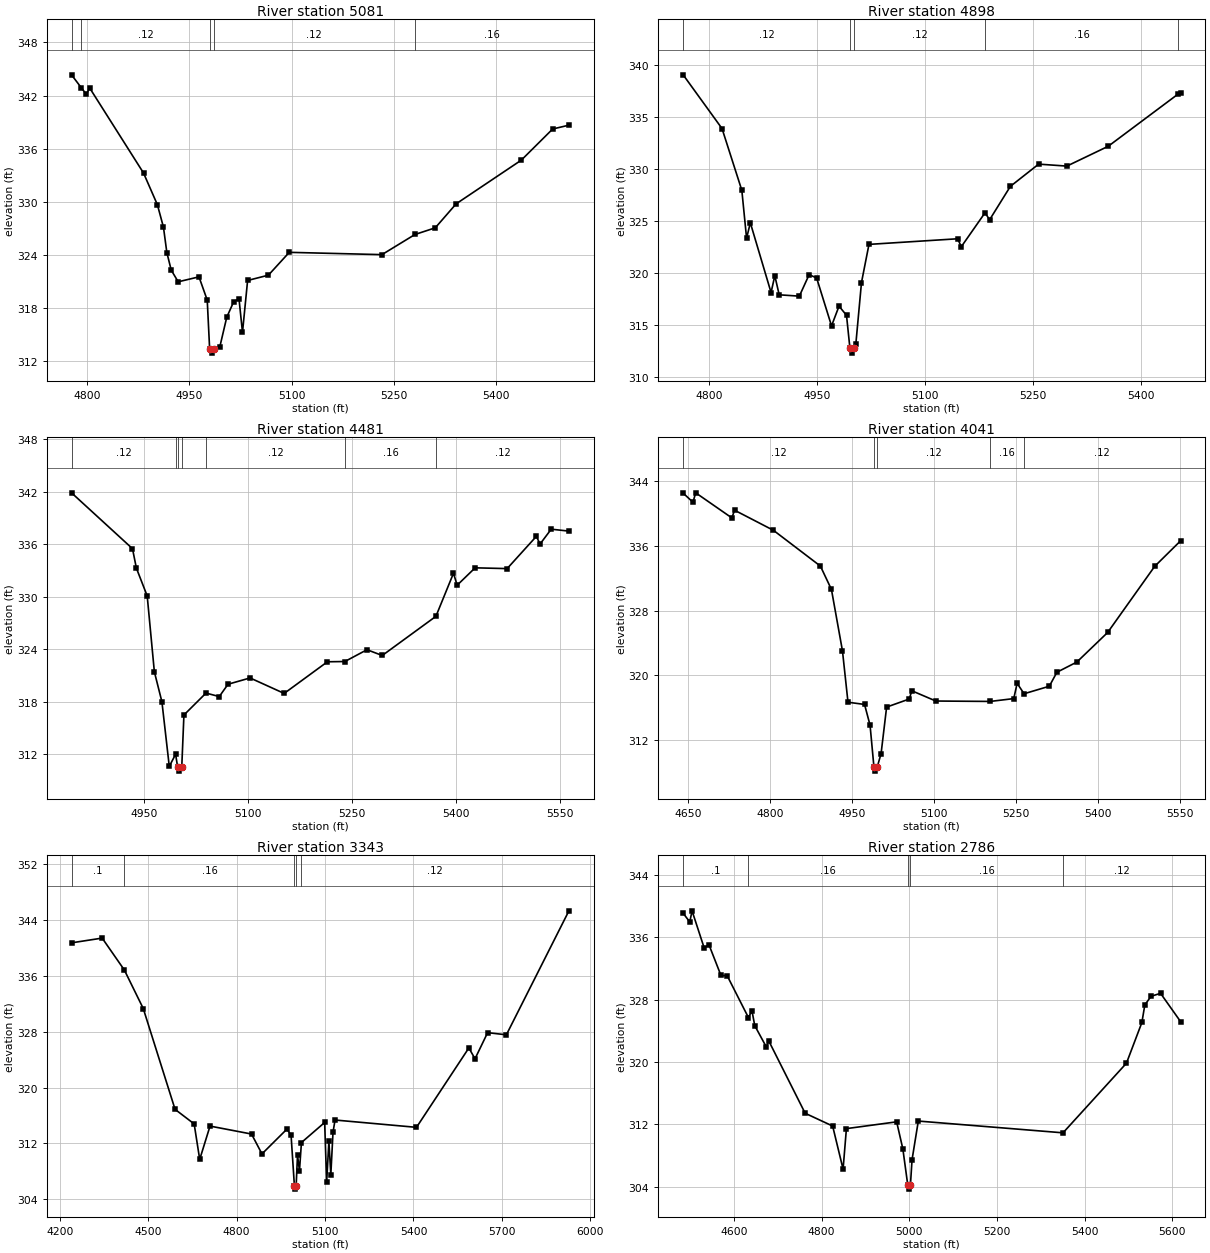
Type RM Length L Ch R = 1,5081,183,183,183
BEGIN DESCRIPTION:
Mapping XS bbe27126
END DESCRIPTION:
XS GIS Cut Line= 3
      3778800.44     10570916.19      3778836.91     10571121.96
      3778938.47     10571632.38
#Sta/Elev= 30
  4777.1  344.34  4791.5  342.87  4798.7  342.15  4803.8  342.84  4882.7  333.24
  4903.0  329.66  4911.9  327.12  4916.9  324.24  4923.3  322.27  4933.5  320.95
  4964.0  321.51  4976.1  318.88  4979.6  313.39  4982.4  312.89  4985.6  313.39
  4994.5  313.58  5004.7  316.94  5014.9  318.70  5022.7  319.01  5027.8  315.24
  5035.3  321.10  5065.8  321.70  5096.4  324.28  5232.3  324.02  5280.8  326.30
  5310.5  327.05  5341.1  329.76  5436.7  334.70  5482.7  338.22  5506.5  338.65
#Mann=5,-1,0
  4777.1    0.16       0  4791.5    0.12       0  4979.6    0.07       0
  4985.6    0.12       0  5280.8    0.16       0
Bank Sta=4979.6,4985.6
Exp/Cntr=0.3,0.1

Type RM Length L Ch R = 1,4898,417,417,417
BEGIN DESCRIPTION:
UNT 068 IN BOCR 5.0
END DESCRIPTION:
XS GIS Cut Line= 2
      3778620.39     10570961.74      3778807.45     10571626.84
#Sta/Elev= 30
  4764.0  339.05  4818.0  333.88  4845.5  327.94  4852.1  323.33  4857.3  324.82
  4886.1  318.11  4891.3  319.73  4897.4  317.89  4925.4  317.76  4939.0  319.83
  4949.4  319.51  4970.1  314.90  4980.5  316.80  4990.9  315.92  4995.6  312.78
  4998.4  312.28  5001.6  312.78  5003.8  313.11  5011.7  319.07  5022.1  322.74
  5145.2  323.28  5150.4  322.52  5183.3  325.78  5189.7  325.11  5218.5  328.32
  5257.8  330.46  5297.0  330.27  5354.5  332.18  5451.5  337.20  5454.9  337.28
#Mann=5,-1,0
  4764.0    0.12       0  4995.6    0.07       0  5001.6    0.12       0
  5183.3    0.16       0  5451.5    0.05       0
Bank Sta=4995.6,5001.6
Exp/Cntr=0.3,0.1

Type RM Length L Ch R = 1,4481,440,440,440
BEGIN DESCRIPTION:
UNT 068 IN BOCR 4.0
END DESCRIPTION:
XS GIS Cut Line= 2
      3778333.94     10571097.18      3778568.32     10571774.26
#Sta/Elev= 30
  4845.9  341.89  4933.7  335.50  4939.3  333.28  4954.9  330.09  4965.2  321.42
  4976.1  317.98  4986.7  310.59  4995.8  311.98  4998.7  310.55  5001.4  310.05
  5004.7  310.55  5007.8  316.47  5039.6  318.98  5058.7  318.58  5071.3  319.99
  5103.1  320.71  5152.2  318.94  5214.5  322.56  5239.6  322.59  5271.5  323.94
  5293.5  323.28  5370.8  327.76  5396.1  332.69  5401.4  331.32  5427.3  333.31
  5473.4  333.22  5515.5  336.91  5520.8  336.03  5536.9  337.73  5562.4  337.51
#Mann=7,-1,0
  4845.9    0.12       0  4995.8    0.16       0  4998.7    0.07       0
  5004.7    0.16       0  5039.6    0.12       0  5239.6    0.16       0
  5370.8    0.12       0
Bank Sta=4998.7,5004.7
Exp/Cntr=0.3,0.1

Type RM Length L Ch R = 1,4041,698,698,698
BEGIN DESCRIPTION:
UNT 068 IN BOCR 3.0
END DESCRIPTION:
XS GIS Cut Line= 3
      3778177.69     10571081.47      3778120.39     10571487.76
      3778412.04     10571893.99
#Sta/Elev= 30
  4641.2  342.54  4659.1  341.42  4664.2  342.58  4730.3  339.48  4735.3  340.43
  4806.5  337.94  4892.4  333.52  4912.6  330.63  4932.8  323.03  4942.9  316.68
  4973.2  316.41  4983.3  313.84  4990.4  308.66  4993.1  308.16  4996.4  308.66
  5003.5  310.34  5013.6  316.08  5055.1  317.08  5059.7  318.10  5103.7  316.83
  5203.1  316.78  5246.3  317.13  5252.5  319.02  5265.2  317.73  5311.4  318.66
  5325.3  320.39  5361.8  321.65  5418.2  325.31  5504.2  333.48  5551.6  336.64
#Mann=5,-1,0
  4641.2    0.12       0  4990.4    0.07       0  4996.4    0.12       0
  5203.1    0.16       0  5265.2    0.12       0
Bank Sta=4990.4,4996.4
Exp/Cntr=0.3,0.1

Type RM Length L Ch R = 1,3343,557,557,557
BEGIN DESCRIPTION:
UNT 068 IN BOCR 2.0
END DESCRIPTION:
XS GIS Cut Line= 3
      3777063.12     10571003.40      3777625.60     10571227.35
      3778333.96     10572045.09
#Sta/Elev= 30
  4240.0  340.75  4343.9  341.43  4419.2  336.85  4483.3  331.33  4591.2  316.87
  4656.0  314.78  4674.8  309.69  4709.8  314.47  4850.6  313.33  4886.0  310.48
  4970.5  314.03  4984.7  313.18  4996.0  305.93  4998.7  305.43  5002.0  305.93
  5006.6  310.30  5013.2  308.06  5019.9  312.11  5098.7  314.99  5105.4  306.39
  5113.0  312.31  5119.6  307.51  5127.0  313.59  5133.9  315.34  5410.2  314.29
  5587.9  325.68  5608.7  324.12  5651.5  327.87  5715.1  327.56  5927.3  345.34
#Mann=5,-1,0
  4240.0     0.1       0  4419.2    0.16       0  4996.0    0.07       0
  5002.0    0.16       0  5019.9    0.12       0
Bank Sta=4996,5002
Exp/Cntr=0.3,0.1

Type RM Length L Ch R = 1,2786,872,872,872
BEGIN DESCRIPTION:
Mapping XS f40279e8
END DESCRIPTION:
XS GIS Cut Line= 3
      3776943.32     10571289.85      3777354.76     10571414.85
      3777880.80     10571883.60
#Sta/Elev= 30
  4484.2  339.09  4499.3  337.97  4504.5  339.40  4532.2  334.63  4543.0  335.06
  4570.3  331.13  4584.8  331.06  4633.0  325.72  4641.2  326.57  4647.5  324.68
  4674.1  321.92  4679.3  322.74  4762.5  313.44  4825.2  311.80  4849.0  306.27
  4856.6  311.47  4971.2  312.34  4985.4  308.85  4996.6  304.21  4999.4  303.71
  5002.6  304.21  5006.3  307.47  5020.6  312.44  5350.7  310.93  5495.4  319.86
  5530.6  325.08  5537.3  327.33  5551.5  328.44  5573.2  328.82  5618.8  325.20
#Mann=5,-1,0
  4484.2     0.1       0  4633.0    0.16       0  4996.6    0.07       0
  5002.6    0.16       0  5350.7    0.12       0
Bank Sta=4996.6,5002.6
Exp/Cntr=0.3,0.1

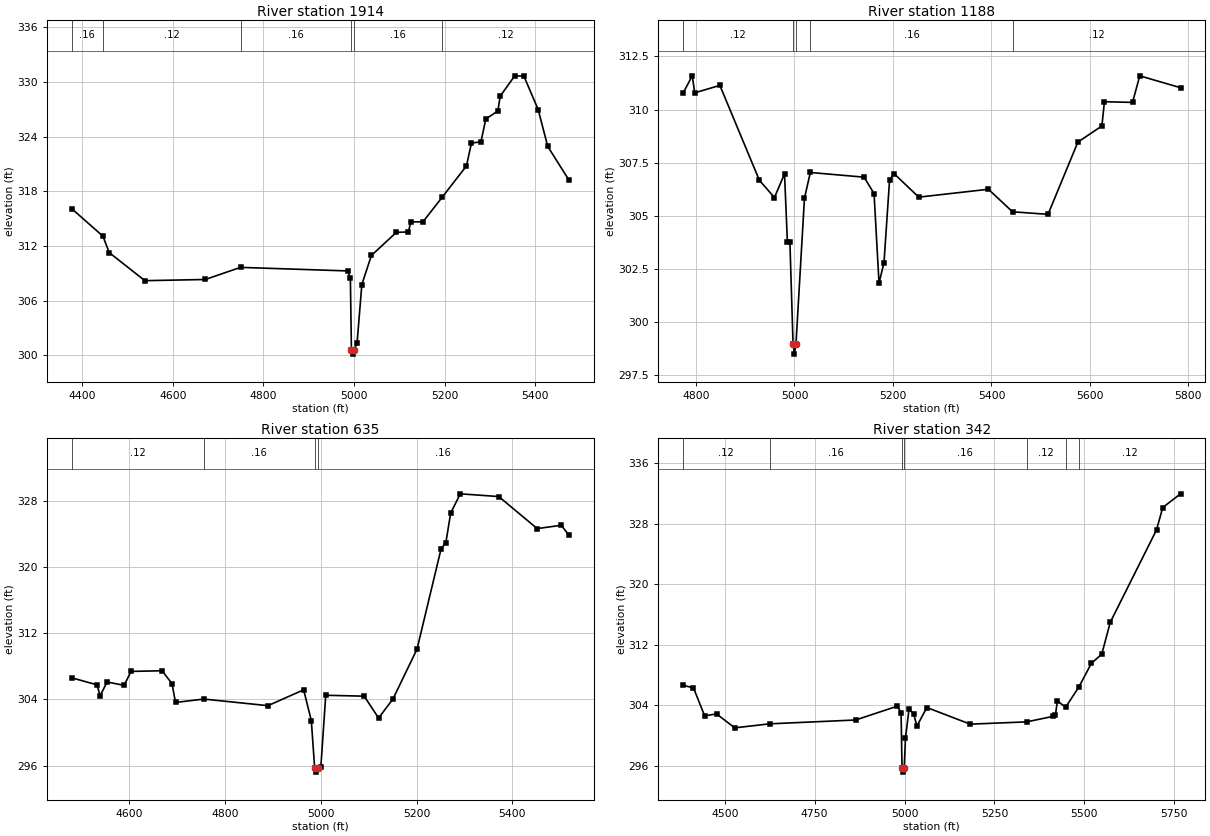
Type RM Length L Ch R = 1,1914,726,726,726
BEGIN DESCRIPTION:
Mapping XS 3d1ad016
END DESCRIPTION:
XS GIS Cut Line= 2
      3776670.41     10571665.45      3777714.16     10572003.40
#Sta/Elev= 30
  4376.9  316.13  4446.0  313.10  4460.1  311.29  4538.7  308.21  4671.9  308.34
  4749.6  309.67  4985.7  309.28  4991.9  308.50  4994.2  300.65  4996.9  300.15
  5000.2  300.65  5006.7  301.39  5017.2  307.79  5038.3  310.98  5093.2  313.51
  5119.9  313.56  5125.2  314.67  5151.9  314.66  5194.1  317.35  5247.9  320.80
  5259.0  323.32  5279.9  323.44  5290.5  325.94  5317.2  326.84  5322.4  328.46
  5354.4  330.69  5374.6  330.66  5406.1  326.99  5427.2  322.94  5474.0  319.25
#Mann=6,-1,0
  4376.9    0.16       0  4446.0    0.12       0  4749.6    0.16       0
  4994.2    0.07       0  5000.2    0.16       0  5194.1    0.12       0
Bank Sta=4994.2,5000.2
Exp/Cntr=0.3,0.1

Type RM Length L Ch R = 1,1188,553,553,553
BEGIN DESCRIPTION:
Mapping XS b3b65f63
END DESCRIPTION:
XS GIS Cut Line= 3
      3776677.70     10572201.31      3776886.01     10572242.97
      3777676.17     10572133.81
#Sta/Elev= 30
  4773.9  310.78  4792.4  311.59  4797.5  310.79  4848.5  311.14  4928.8  306.67
  4959.4  305.86  4979.8  306.98  4985.6  303.78  4990.7  303.78  4997.1  298.99
  4999.8  298.49  5003.1  298.99  5020.3  305.83  5032.2  307.04  5141.4  306.82
  5161.6  306.05  5171.7  301.83  5181.8  302.80  5193.1  306.68  5202.0  306.99
  5252.4  305.88  5393.8  306.25  5442.8  305.19  5514.9  305.07  5575.5  308.47
  5624.3  309.23  5629.4  310.37  5686.5  310.34  5701.2  311.59  5784.0  311.03
#Mann=5,-1,0
  4773.9    0.12       0  4997.1    0.07       0  5003.1    0.12       0
  5032.2    0.16       0  5442.8    0.12       0
Bank Sta=4997.1,5003.1
Exp/Cntr=0.3,0.1

Type RM Length L Ch R = 1,635,293,293,293
BEGIN DESCRIPTION:
Mapping XS 3c9ab31f
END DESCRIPTION:
XS GIS Cut Line= 3
      3776645.30     10572240.73      3776995.98     10572501.13
      3777595.64     10572553.12
#Sta/Elev= 30
  4479.5  306.63  4532.9  305.77  4539.1  304.43  4553.7  306.12  4589.2  305.71
  4603.8  307.40  4668.5  307.48  4689.3  305.92  4696.6  303.64  4755.8  304.05
  4889.6  303.25  4964.2  305.17  4980.2  301.44  4987.2  295.70  4989.9  295.20
  4993.2  295.70  5000.2  295.88  5010.3  304.51  5090.6  304.40  5120.7  301.75
  5150.8  304.07  5201.0  310.11  5251.2  322.25  5261.2  323.01  5271.2  326.58
  5291.3  328.91  5371.6  328.58  5451.9  324.70  5502.1  325.10  5518.2  323.90
#Mann=4,-1,0
  4479.5    0.12       0  4755.8    0.16       0  4987.2    0.07       0
  4993.2    0.16       0
Bank Sta=4987.2,4993.2
Exp/Cntr=0.3,0.1

Type RM Length L Ch R = 1,342,0,0,0
BEGIN DESCRIPTION:
UNT 068 IN BOCR 1.0
END DESCRIPTION:
XS GIS Cut Line= 5
      3776646.42     10572243.90      3776677.68     10572331.51
      3776771.43     10572664.85      3777115.18     10572847.14
      3777625.14     10572628.58
#Sta/Elev= 30
  4384.4  306.63  4413.2  306.29  4444.2  302.59  4477.4  302.84  4528.0  301.00
  4624.8  301.53  4864.2  302.04  4980.1  303.87  4990.5  302.98  4993.1  295.64
  4995.9  295.14  4999.1  295.64  5002.7  299.65  5012.5  303.44  5025.4  302.89
  5034.4  301.22  5062.1  303.69  5182.7  301.49  5339.4  301.79  5413.4  302.52
  5419.8  302.76  5425.3  304.59  5447.7  303.70  5484.9  306.41  5519.6  309.53
  5548.6  310.76  5572.2  314.97  5700.9  327.21  5718.1  330.16  5767.6  331.97
#Mann=7,-1,0
  4384.4    0.12       0  4624.8    0.16       0  4993.1    0.07       0
  4999.1    0.16       0  5339.4    0.12       0  5447.7    0.16       0
  5484.9    0.12       0
Bank Sta=4993.1,4999.1
Exp/Cntr=0.3,0.1

Chan Stop Cuts=-1