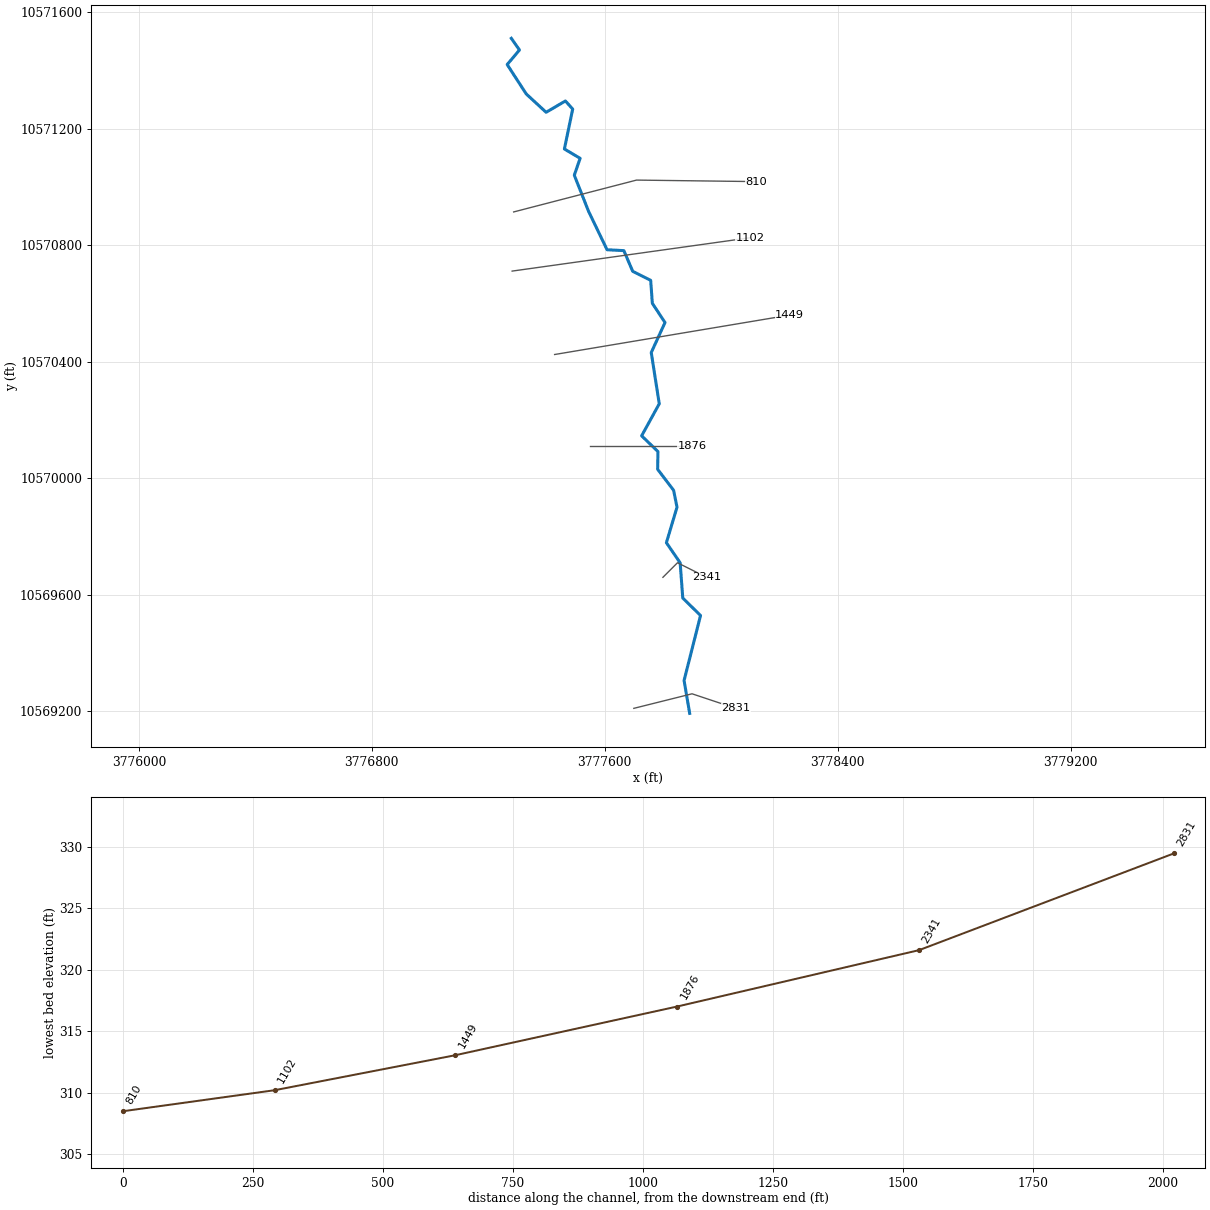
--- UNT 069 IN BOCR.prj (project) ---

Proj Title=UNT 069 IN BOCR Base Level Engineering
Current Plan=p01
Default Exp/Contr=0.3,0.1
English Units
Geom File=g01
Flow File=f01
Plan File=p01
Y Axis Title=Elevation
X Axis Title(PF)=Main Channel Distance
X Axis Title(XS)=Station
BEGIN DESCRIPTION:
UNT 069 IN BOCR
END DESCRIPTION:
DSS Export Rating Curves= 0
DSS Export Rating Curve Sorted= 0
DSS Export Volume Flow Curves= 0
DXF OffsetX= 0
DXF OffsetY= 0
DXF ScaleX= 1
DXF ScaleY= 10

--- UNT 069 IN BOCR.p01 (plan) ---

Plan Title=Multiple Run
Short Identifier=Multiple
Geom File=g01
Flow File=f01
Subcritical Flow
K Sum by GR= 0
Std Step Tol= 0.01
Critical Tol= 0.01
Num of Std Step Trials= 20
Max Error Tol= 0.3
Flow Tol Ratio= 0.001
Split Flow NTrial= 30
Split Flow Tol= 0.02
Split Flow Ratio= 0.02
Log Output Level= 0
Friction Slope Method= 1
Unsteady Friction Slope Method= 2
Unsteady Bridges Friction Slope Method= 1
Parabolic Critical Depth
Global Vel Dist=  1 , 1 , 1
Global Log Level= 0
CheckData=True
Encroach Param= -1, 0, 0, 0
BEGIN DESCRIPTION:
Multiple Run
END DESCRIPTION:

--- UNT 069 IN BOCR.f01 (steady flow) ---

Flow Title=Multiple
Program Version=4.10
Number of Profiles= 7
Profile Names=10-year,25-year,50-year,1pct_min,100-year,1pct_plu,500-year
River Rch & RM=UNT 069 IN BOCR,Reach-1         ,2831
     392     518     621     548     741    1002    1058
Boundary for River Rch & Prof#=UNT 069 IN BOCR,Reach-1         , 1
Up Type= 0
Dn Type= 3
Dn Slope=0.006
Boundary for River Rch & Prof#=UNT 069 IN BOCR,Reach-1         , 2
Up Type= 0
Dn Type= 3
Dn Slope=0.006
Boundary for River Rch & Prof#=UNT 069 IN BOCR,Reach-1         , 3
Up Type= 0
Dn Type= 3
Dn Slope=0.006
Boundary for River Rch & Prof#=UNT 069 IN BOCR,Reach-1         , 4
Up Type= 0
Dn Type= 3
Dn Slope=0.006
Boundary for River Rch & Prof#=UNT 069 IN BOCR,Reach-1         , 5
Up Type= 0
Dn Type= 3
Dn Slope=0.006
Boundary for River Rch & Prof#=UNT 069 IN BOCR,Reach-1         , 6
Up Type= 0
Dn Type= 3
Dn Slope=0.006
Boundary for River Rch & Prof#=UNT 069 IN BOCR,Reach-1         , 7
Up Type= 0
Dn Type= 3
Dn Slope=0.006
DSS Import GetInterval= 0
DSS Import GetPeak= 0
DSS Import FillOption= 0

--- UNT 069 IN BOCR.g01 (geometry) ---

Geom Title=Existing Conditions
Program Version=4.10

River Reach=UNT 069 IN BOCR ,Reach-1
Reach XY= 30
      3777891.44     10569192.94      3777872.25       10569306.
      3777928.75       10569529.      3777867.75       10569589.
      3777858.75       10569710.       3777811.5       10569779.
        3777848.       10569901.      3777836.25       10569959.
       3777781.5       10570031.       3777782.5       10570092.
       3777726.5       10570146.        3777787.       10570256.
       3777759.5       10570432.      3777806.75       10570535.
      3777763.25       10570601.       3777757.5       10570680.
      3777695.75       10570711.       3777665.5       10570782.
      3777607.75       10570785.      3777544.25       10570917.
      3777495.25       10571041.      3777515.25       10571099.
      3777461.25       10571131.      3777489.75       10571268.
      3777464.75       10571296.       3777398.5       10571257.
      3777330.25       10571320.      3777264.75       10571421.
        3777307.       10571471.        3777279.       10571511.

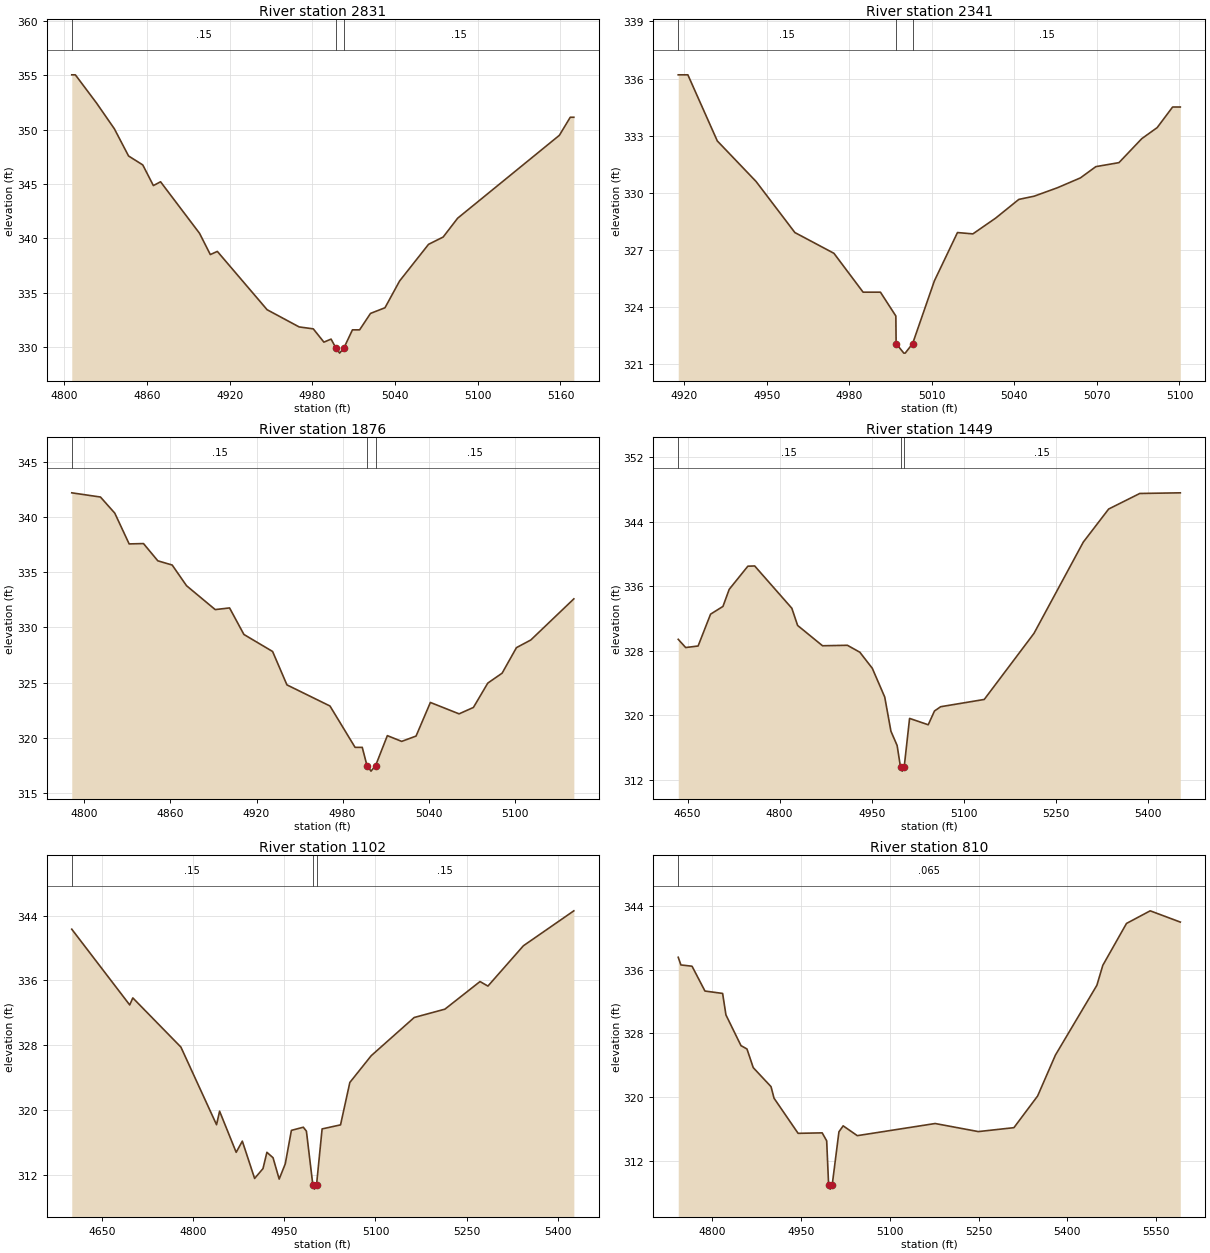
Type RM Length L Ch R = 1 ,2831    ,490,490,490
BEGIN DESCRIPTION:
UNT 069 IN BOCR 6.0
END DESCRIPTION:
XS GIS Cut Line= 3
      3777699.63     10569210.19      3777899.61     10569260.19
      3778049.57      10569210.2
#Sta/Elev= 30
  4805.5  355.03  4808.1  355.03  4823.5  352.43  4836.4  350.07  4846.7  347.57
    4857  346.75  4864.7  344.85  4869.9   345.2  4898.2  340.46    4906  338.51
  4911.1   338.8  4947.2  333.44  4970.4  331.86  4980.7  331.68  4988.4  330.46
  4993.6  330.74    4997  329.95  4999.8  329.45    5003  329.95  5009.1  331.59
  5014.3  331.59  5022.2   333.1  5032.7  333.62  5043.3  336.08  5064.3  339.45
  5074.9  340.12  5085.4  341.85  5159.2  349.47  5167.1  351.13  5169.7  351.13
#Mann= 3 ,-1 , 0
  4805.5     .15       0    4997     .05       0    5003     .15       0
Bank Sta=4997,5003
XS Rating Curve= 0 ,0
Exp/Cntr=0.3,0.1

Type RM Length L Ch R = 1 ,2341    ,465,465,465
BEGIN DESCRIPTION:
UNT 069 IN BOCR 5.0
END DESCRIPTION:
XS GIS Cut Line= 3
       3777799.6     10569660.18      3777849.61     10569710.19
      3777949.59      10569660.2
#Sta/Elev= 28
  4917.8   336.2  4921.3   336.2    4932  332.73  4946.1   330.6  4960.2  327.92
  4974.4  326.83    4985  324.79  4988.5  324.79  4991.3  324.79  4996.9  323.54
    4997  322.09  4999.8  321.59  5000.3  321.59    5003  322.09  5010.9  325.38
  5019.3  327.92  5024.9  327.85  5033.2  328.68  5041.6  329.66  5047.2  329.83
  5055.6  330.27    5064  330.79  5069.6  331.38    5078  331.59  5086.3  332.85
  5091.9  333.43  5097.5  334.51  5100.3  334.51
#Mann= 3 ,-1 , 0
  4917.8     .15       0    4997     .05       0    5003     .15       0
Bank Sta=4997,5003
XS Rating Curve= 0 ,0
Exp/Cntr=0.3,0.1

Type RM Length L Ch R = 1 ,1876    ,427,427,427
BEGIN DESCRIPTION:
UNT 069 IN BOCR 4.0
END DESCRIPTION:
XS GIS Cut Line= 3
      3777549.63     10570110.19      3777749.61     10570110.19
      3777899.63     10570110.19
#Sta/Elev= 30
  4791.2  342.18  4811.2   341.8  4821.2  340.34  4831.2  337.56  4841.2  337.59
  4851.2  336.03  4861.2  335.65  4871.2  333.78  4891.2  331.62  4901.2  331.77
  4911.2  329.37  4931.2  327.83  4941.2  324.81  4971.2   322.9  4988.7  319.16
  4993.7  319.16    4997  317.51  4999.8  317.01    5003  317.51  5011.2  320.22
  5021.2   319.7  5031.2  320.18  5041.2  323.22  5061.2  322.19  5071.2  322.77
  5081.2  324.97  5091.2  325.87  5101.2  328.18  5111.2  328.87  5141.2  332.59
#Mann= 3 ,-1 , 0
  4791.2     .15       0    4997     .05       0    5003     .15       0
Bank Sta=4997,5003
XS Rating Curve= 0 ,0
Exp/Cntr=0.3,0.1

Type RM Length L Ch R = 1 ,1449    ,347,347,347
BEGIN DESCRIPTION:
UNT 069 IN BOCR 3.0
END DESCRIPTION:
XS GIS Cut Line= 2
      3777427.68     10570425.26       3778234.8     10570560.65
#Sta/Elev= 30
  4634.7   329.4  4646.8  328.38  4667.1  328.57  4687.4  332.52  4707.6  333.48
  4717.8   335.6  4748.2  338.47  4759.3   338.5  4819.9  333.25  4829.3  331.12
  4869.9   328.6  4910.4  328.66  4930.7   327.8    4951  325.81  4971.3  322.24
  4981.4     318  4991.5  316.23    4997  313.55  4999.8  313.05    5003  313.55
  5011.8  319.59  5042.2   318.8  5052.4  320.51  5062.5  321.04  5133.5  321.94
  5214.6  330.14  5294.9  341.45  5336.3  345.56    5387  347.49  5453.1  347.57
#Mann= 3 ,-1 , 0
  4634.7     .15       0    4997     .05       0    5003     .15       0
Bank Sta=4997,5003
XS Rating Curve= 0 ,0
Exp/Cntr=0.3,0.1

Type RM Length L Ch R = 1 ,1102    ,292,292,292
BEGIN DESCRIPTION:
UNT 069 IN BOCR 2.0
END DESCRIPTION:
XS GIS Cut Line= 2
      3777281.86     10570711.72      3778099.57     10570826.31
#Sta/Elev= 30
  4600.5  342.33  4695.8  332.97  4700.9  333.84    4780  327.76  4838.6  318.17
  4843.6  319.84  4870.9  314.76    4881  316.14  4901.2  311.53    4915  312.75
  4921.4  314.76  4931.5  314.09  4941.6  311.45  4951.6  313.33  4961.7  317.47
  4981.3  317.86  4986.4  317.37    4997  310.71  4999.8  310.21    5003  310.71
  5012.2  317.65  5042.5  318.15  5057.8  323.39    5093   326.7  5163.7  331.42
  5214.2  332.45  5271.9  335.86  5284.9   335.3  5343.2  340.28  5426.2   344.6
#Mann= 3 ,-1 , 0
  4600.5     .15       0    4997     .05       0    5003     .15       0
Bank Sta=4997,5003
XS Rating Curve= 0 ,0
Exp/Cntr=0.3,0.1

Type RM Length L Ch R = 1 ,810     ,0,0,0
BEGIN DESCRIPTION:
UNT 069 IN BOCR 1.0
END DESCRIPTION:
XS GIS Cut Line= 3
      3777287.09     10570914.86      3777708.93     10571024.22
      3778120.41     10571019.01
#Sta/Elev= 30
  4743.2  337.55  4747.7  336.59  4766.5  336.43  4788.3  333.32  4818.1  333.02
  4823.7  330.33  4849.1  326.48  4859.2  326.06  4869.8  323.72  4899.8  321.34
  4904.9  319.89  4945.5  315.49  4986.1  315.55  4993.7  314.56    4997     309
  4999.8   308.5    5003     309  5014.4  315.68  5021.5  316.43  5045.4   315.2
  5176.8  316.72  5249.7  315.71  5309.7   316.2  5349.7  320.17  5379.7  325.29
  5449.7  334.04  5459.7  336.54  5499.7  341.79  5539.7  343.37  5590.5  341.96
#Mann= 1 ,-1 , 0
  4743.2    .065       0
Bank Sta=4997,5003
XS Rating Curve= 0 ,0
Exp/Cntr=0.3,0.1

Chan Stop Cuts=-1
Use User Specified Reach Order=0
Composite Channel Slope=5