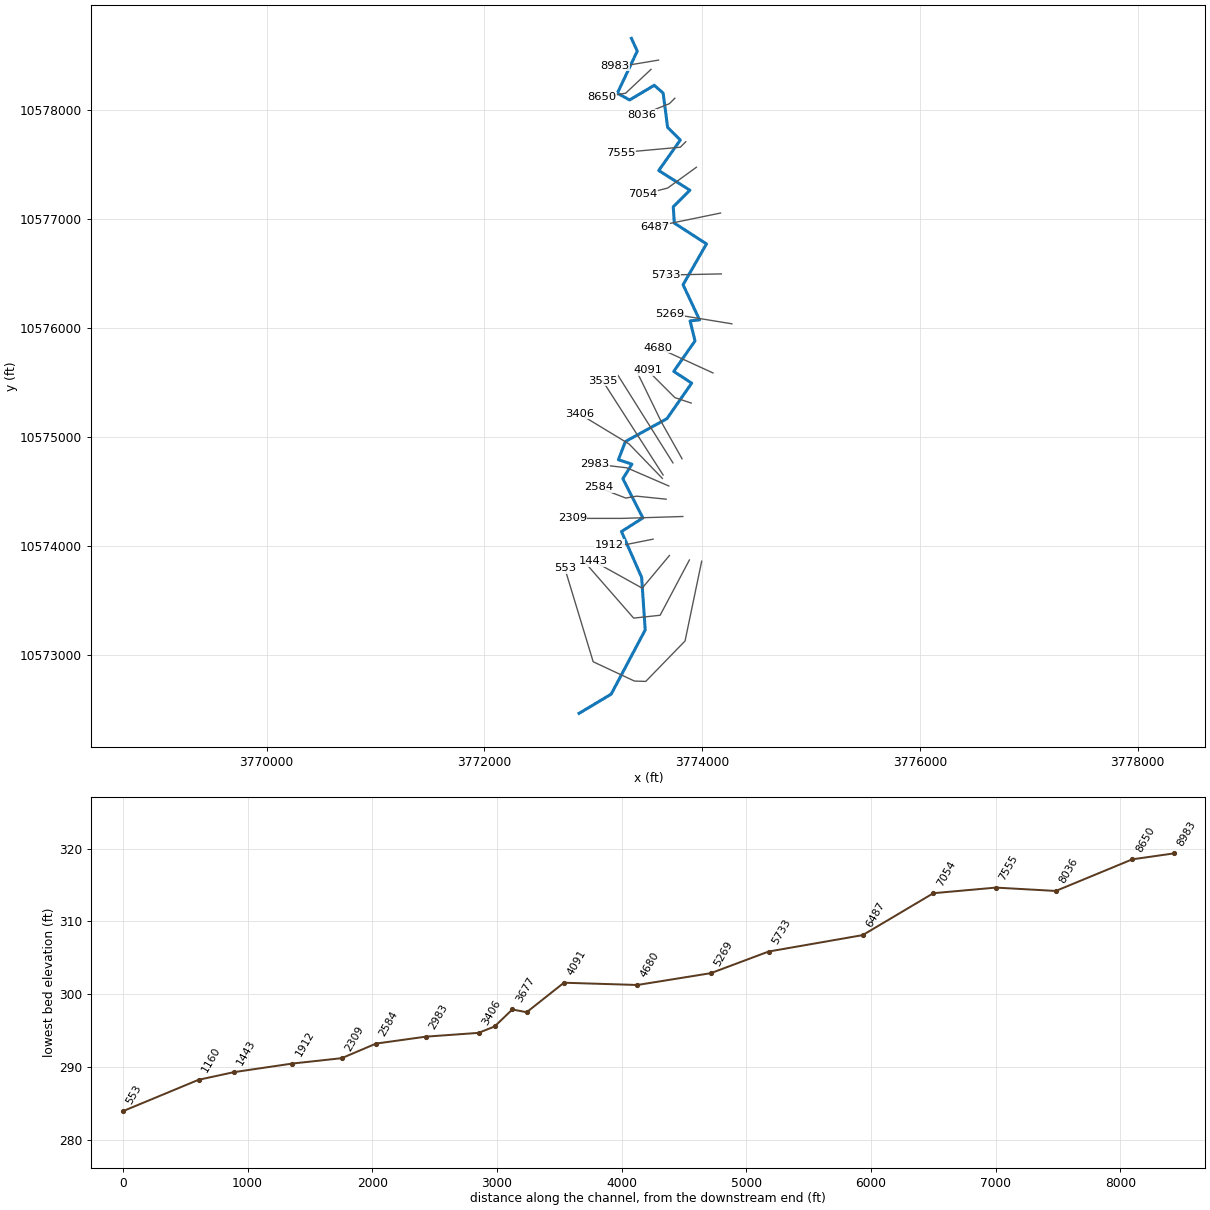
--- UNT 070 IN BOCR.prj (project) ---

Proj Title=UNT 070 IN BOCR Base Level Engineering
Current Plan=p01
Default Exp/Contr=0.3,0.1
English Units
Geom File=g01
Flow File=f01
Plan File=p01
BEGIN DESCRIPTION:
UNT 070 IN BOCR
END DESCRIPTION:

--- UNT 070 IN BOCR.p01 (plan) ---

Plan Title=Multiple Run
Short Identifier=Multiple
Geom File=g01
Flow File=f01
Subcritical Flow
K Sum by GR= 0
Std Step Tol= 0.01
Critical Tol= 0.01
Num of Std Step Trials= 20
Max Error Tol= 0.3
Flow Tol Ratio= 0.001
Split Flow NTrial= 30
Split Flow Tol= 0.02
Split Flow Ratio= 0.02
Log Output Level= 0
Friction Slope Method= 1
Unsteady Friction Slope Method= 2
Unsteady Bridges Friction Slope Method= 1
Parabolic Critical Depth
Global Vel Dist=  1 , 1 , 1
Global Log Level= 0
CheckData=True
Encroach Param= -1, 0, 0, 0
BEGIN DESCRIPTION:
Multiple Run
END DESCRIPTION:

--- UNT 070 IN BOCR.f01 (steady flow) ---

Flow Title=Multiple
Number of Profiles=7
Profile Names=10-year,25-year,50-year,1pct_min,100-year,1pct_plu,500-year
River Rch & RM= UNT 070 IN BOCR,Reach-1,8983
     483     639     765     673     910    1231    1292
Boundary for River Rch & Prof#=UNT 070 IN BOCR,Reach-1,1
Up Type=0
Dn Type=3
Dn Slope=0.005
Boundary for River Rch & Prof#=UNT 070 IN BOCR,Reach-1,2
Up Type=0
Dn Type=3
Dn Slope=0.005
Boundary for River Rch & Prof#=UNT 070 IN BOCR,Reach-1,3
Up Type=0
Dn Type=3
Dn Slope=0.005
Boundary for River Rch & Prof#=UNT 070 IN BOCR,Reach-1,4
Up Type=0
Dn Type=3
Dn Slope=0.005
Boundary for River Rch & Prof#=UNT 070 IN BOCR,Reach-1,5
Up Type=0
Dn Type=3
Dn Slope=0.005
Boundary for River Rch & Prof#=UNT 070 IN BOCR,Reach-1,6
Up Type=0
Dn Type=3
Dn Slope=0.005
Boundary for River Rch & Prof#=UNT 070 IN BOCR,Reach-1,7
Up Type=0
Dn Type=3
Dn Slope=0.005

--- UNT 070 IN BOCR.g01 (geometry) ---

Geom Title=Existing Conditions

River Reach=UNT 070 IN BOCR,Reach-1
Reach XY= 30
      3773350.51     10578660.10      3773404.25     10578543.00
      3773221.50     10578156.00      3773334.50     10578094.00
      3773560.25     10578229.00      3773642.00     10578157.00
      3773683.00     10577842.00      3773799.50     10577726.00
      3773601.25     10577446.00      3773887.75     10577265.00
      3773734.75     10577113.00      3773744.50     10576963.00
      3774040.00     10576772.00      3773825.00     10576397.00
      3773976.25     10576074.00      3773889.50     10576065.00
      3773934.50     10575881.00      3773739.25     10575601.00
      3773904.00     10575493.00      3773676.75     10575167.00
      3773295.75     10574957.00      3773230.75     10574790.00
      3773355.25     10574749.00      3773272.00     10574615.00
      3773455.50     10574255.00      3773259.00     10574130.00
      3773444.50     10573709.00      3773477.00     10573226.00
      3773164.75     10572637.00      3772869.50     10572460.00

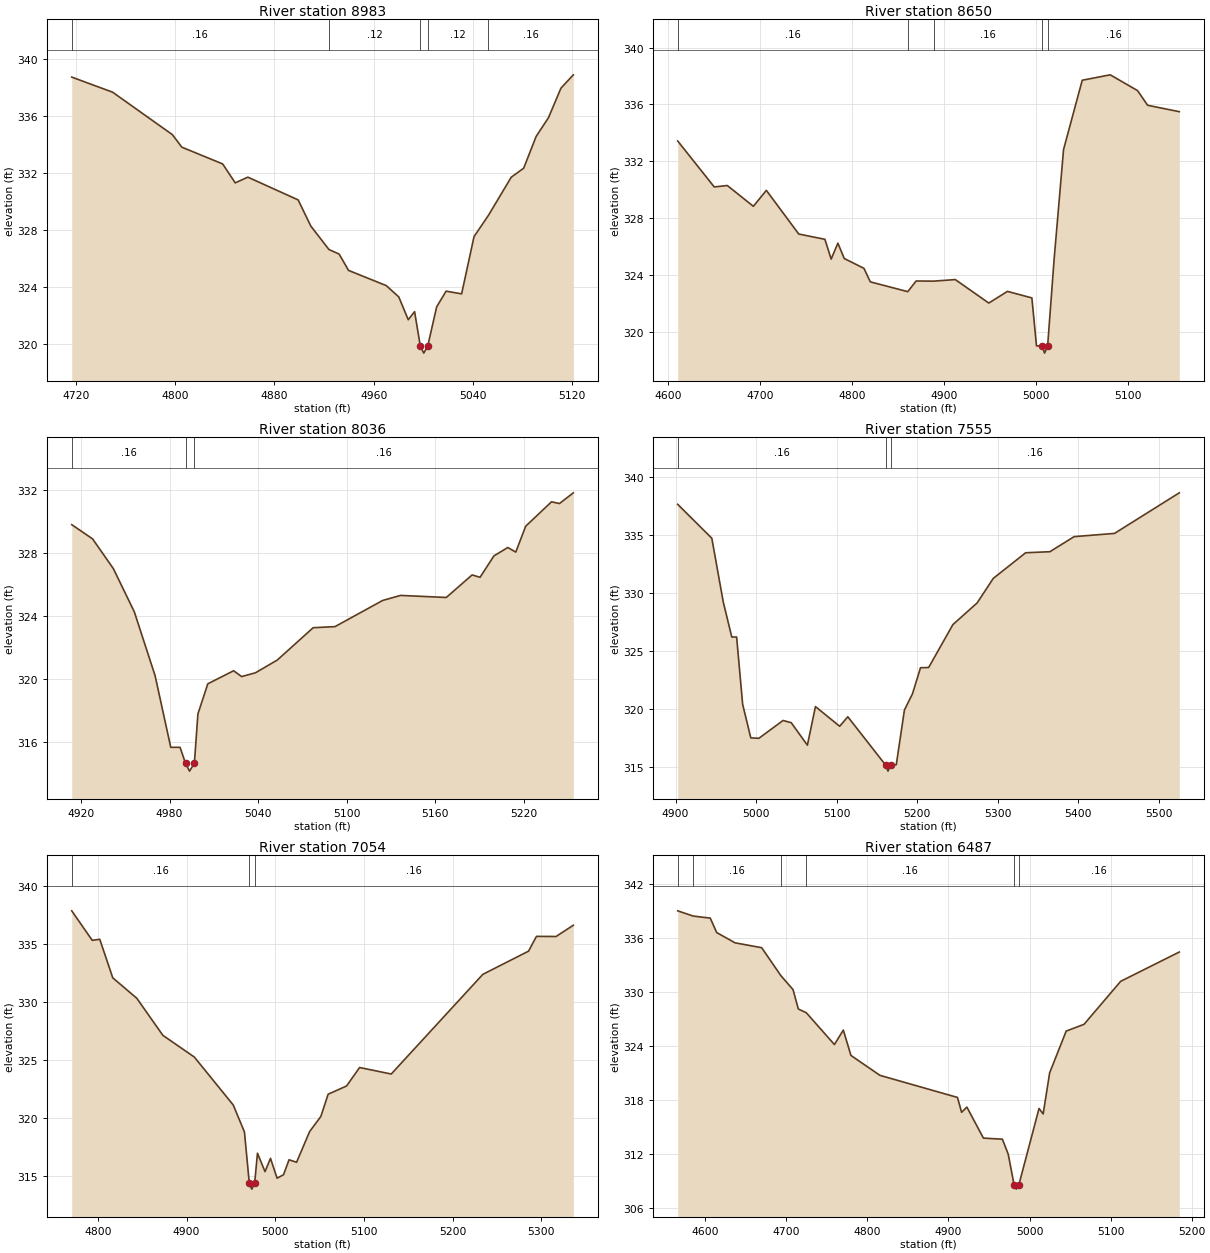
Type RM Length L Ch R = 1,8983,333,333,333
BEGIN DESCRIPTION:
UNT 070 IN BOCR 15.0
END DESCRIPTION:
XS GIS Cut Line= 3
      3773599.56     10578460.18      3773299.61     10578410.19
      3773199.60     10578410.19
#Sta/Elev= 30
  4716.8  338.75  4749.7  337.69  4797.9  334.70  4805.5  333.82  4838.4  332.64
  4848.5  331.31  4858.7  331.71  4899.2  330.11  4909.4  328.27  4924.0  326.62
  4932.2  326.30  4939.8  325.15  4970.2  324.08  4980.3  323.28  4987.9  321.68
  4993.0  322.25  4997.6  319.83  5000.4  319.33  5003.6  319.83  5010.8  322.59
  5018.4  323.69  5030.9  323.50  5040.9  327.53  5052.4  329.01  5070.9  331.71
  5080.9  332.34  5090.9  334.57  5100.9  335.90  5110.9  337.97  5120.9  338.91
#Mann=5,-1,0
  4716.8    0.16       0  4924.0    0.12       0  4997.6    0.07       0
  5003.6    0.12       0  5052.4    0.16       0
Bank Sta=4997.6,5003.6
Exp/Cntr=0.3,0.1

Type RM Length L Ch R = 1,8650,614,614,614
BEGIN DESCRIPTION:
UNT 070 IN BOCR 14.0
END DESCRIPTION:
XS GIS Cut Line= 3
      3773530.55     10578375.18      3773297.93     10578156.45
      3773075.70     10578118.25
#Sta/Elev= 30
  4610.7  333.43  4650.4  330.20  4664.6  330.30  4692.9  328.84  4707.0  329.96
  4742.2  326.89  4770.6  326.52  4777.4  325.13  4784.7  326.25  4791.6  325.17
  4813.0  324.48  4819.9  323.53  4860.6  322.84  4869.7  323.59  4888.8  323.58
  4912.2  323.69  4948.6  322.04  4968.9  322.86  4995.4  322.40  5000.4  319.03
  5006.5  319.02  5009.2  318.52  5012.5  319.02  5019.6  325.16  5029.8  332.83
  5050.1  337.70  5080.5  338.08  5110.2  336.97  5121.1  335.94  5155.5  335.49
#Mann=5,-1,0
  4610.7    0.16       0  4860.6    0.12       0  4888.8    0.16       0
  5006.5    0.07       0  5012.5    0.16       0
Bank Sta=5006.5,5012.5
Exp/Cntr=0.3,0.1

Type RM Length L Ch R = 1,8036,481,481,481
BEGIN DESCRIPTION:
UNT 070 IN BOCR 13.0
END DESCRIPTION:
XS GIS Cut Line= 3
      3773749.58     10578110.16      3773699.61     10578060.19
      3773449.64     10577960.20
#Sta/Elev= 30
  4913.7  329.82  4927.8  328.92  4941.9  327.03  4956.1  324.29  4970.2  320.23
  4980.8  315.69  4987.1  315.69  4990.8  314.68  4993.5  314.18  4996.8  314.68
  4999.2  317.81  5005.9  319.72  5023.4  320.55  5028.8  320.18  5038.2  320.42
  5053.0  321.23  5077.3  323.28  5092.1  323.35  5124.4  325.01  5136.5  325.33
  5167.5  325.20  5185.0  326.63  5190.4  326.48  5199.8  327.84  5209.2  328.37
  5214.6  328.08  5221.3  329.72  5238.8  331.27  5244.2  331.16  5253.6  331.84
#Mann=3,-1,0
  4913.7    0.16       0  4990.8    0.07       0  4996.8    0.16       0
Bank Sta=4990.8,4996.8
Exp/Cntr=0.3,0.1

Type RM Length L Ch R = 1,7555,501,501,501
BEGIN DESCRIPTION:
UNT 070 IN BOCR 12.0
END DESCRIPTION:
XS GIS Cut Line= 3
      3773849.60     10577710.18      3773799.61     10577660.19
      3773249.57     10577610.19
#Sta/Elev= 30
  4902.6  337.66  4945.0  334.73  4959.2  329.23  4969.8  326.21  4975.8  326.21
  4983.3  320.40  4993.4  317.51  5003.4  317.47  5033.5  319.01  5043.6  318.82
  5063.7  316.88  5073.7  320.21  5103.8  318.51  5113.9  319.33  5161.1  315.14
  5163.8  314.64  5167.1  315.14  5174.1  315.19  5184.2  319.91  5194.2  321.31
  5204.2  323.56  5214.3  323.58  5244.4  327.28  5274.5  329.15  5294.6  331.27
  5334.8  333.48  5364.9  333.57  5395.0  334.87  5445.2  335.15  5525.6  338.65
#Mann=3,-1,0
  4902.6    0.16       0  5161.1    0.07       0  5167.1    0.16       0
Bank Sta=5161.1,5167.1
Exp/Cntr=0.3,0.1

Type RM Length L Ch R = 1,7054,567,567,567
BEGIN DESCRIPTION:
UNT 070 IN BOCR 11.0
END DESCRIPTION:
XS GIS Cut Line= 3
      3773947.24     10577475.90      3773683.34     10577284.92
      3773450.67     10577225.88
#Sta/Elev= 30
  4770.5  337.83  4793.6  335.29  4802.1  335.38  4816.8  332.06  4843.9  330.30
  4873.3  327.11  4908.8  325.24  4952.7  321.11  4965.3  318.79  4970.8  314.37
  4973.6  313.87  4976.8  314.37  4980.0  316.96  4988.5  315.38  4994.7  316.52
  5002.1  314.81  5009.4  315.11  5015.6  316.40  5024.1  316.18  5038.8  318.82
  5051.5  320.13  5059.7  322.04  5080.5  322.75  5095.2  324.34  5130.9  323.78
  5234.2  332.36  5285.8  334.36  5294.7  335.63  5316.8  335.62  5336.3  336.59
#Mann=3,-1,0
  4770.5    0.16       0  4970.8    0.07       0  4976.8    0.16       0
Bank Sta=4970.8,4976.8
Exp/Cntr=0.3,0.1

Type RM Length L Ch R = 1,6487,754,754,754
BEGIN DESCRIPTION:
Mapping XS 96da906c
END DESCRIPTION:
XS GIS Cut Line= 2
      3774168.97     10577055.47      3773562.96     10576930.80
#Sta/Elev= 30
  4566.0  338.99  4585.1  338.41  4606.2  338.18  4614.1  336.58  4636.8  335.44
  4669.6  334.90  4693.2  331.81  4708.3  330.25  4714.8  328.10  4724.6  327.69
  4759.3  324.16  4770.3  325.76  4779.7  322.95  4815.5  320.74  4911.1  318.29
  4916.2  316.64  4922.7  317.22  4943.1  313.78  4966.5  313.66  4973.7  312.00
  4980.9  308.62  4983.7  308.12  4986.9  308.62  5011.7  317.07  5016.8  316.46
  5024.8  321.02  5045.2  325.65  5067.2  326.40  5112.4  331.17  5184.7  334.42
#Mann=6,-1,0
  4566.0    0.05       0  4585.1    0.16       0  4693.2    0.12       0
  4724.6    0.16       0  4980.9    0.07       0  4986.9    0.16       0
Bank Sta=4980.9,4986.9
Exp/Cntr=0.3,0.1

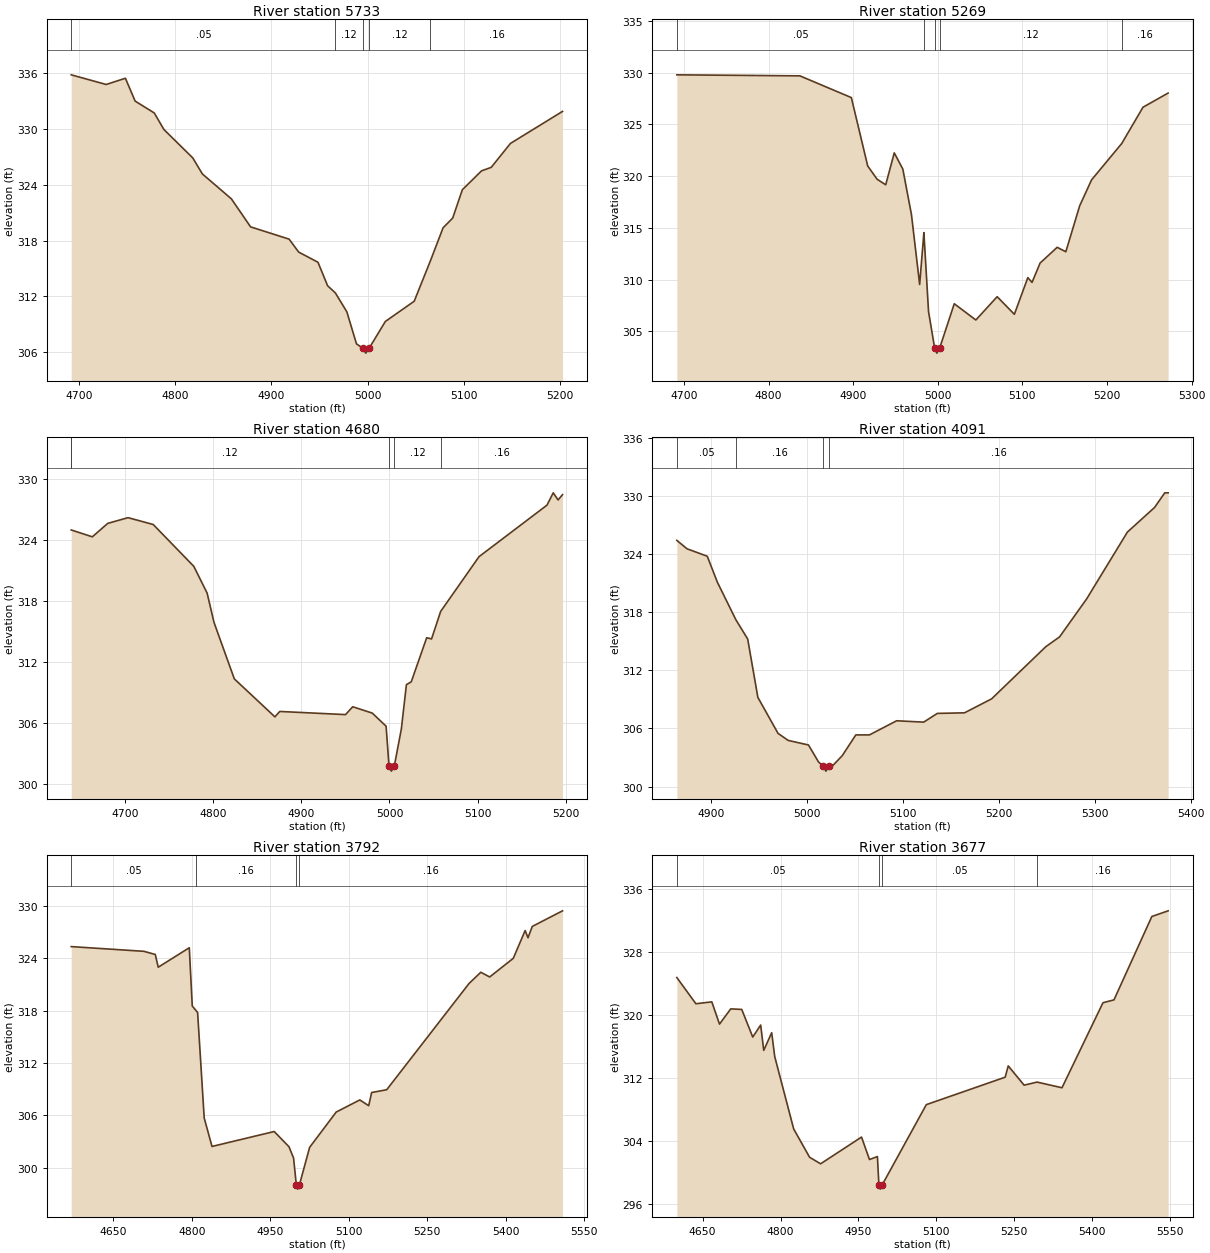
Type RM Length L Ch R = 1,5733,464,464,464
BEGIN DESCRIPTION:
Mapping XS 87787a08
END DESCRIPTION:
XS GIS Cut Line= 2
      3774175.93     10576496.44      3773665.53     10576486.03
#Sta/Elev= 30
  4692.1  335.85  4728.4  334.81  4748.4  335.48  4758.5  333.02  4778.4  331.74
  4788.4  329.96  4818.4  326.90  4828.4  325.17  4858.5  322.49  4878.5  319.47
  4918.5  318.15  4928.5  316.75  4948.5  315.66  4958.5  313.13  4966.6  312.35
  4978.5  310.32  4988.5  306.87  4995.5  306.37  4998.2  305.87  5001.5  306.37
  5018.5  309.28  5048.5  311.46  5065.4  315.83  5078.5  319.37  5088.5  320.42
  5098.5  323.47  5118.5  325.51  5128.5  325.88  5148.5  328.46  5202.6  331.91
#Mann=5,-1,0
  4692.1    0.05       0  4966.6    0.12       0  4995.5    0.07       0
  5001.5    0.12       0  5065.4    0.16       0
Bank Sta=4995.5,5001.5
Exp/Cntr=0.3,0.1

Type RM Length L Ch R = 1,5269,589,589,589
BEGIN DESCRIPTION:
Mapping XS a84a48f6
END DESCRIPTION:
XS GIS Cut Line= 2
      3774273.14     10576038.11      3773700.26     10576131.86
#Sta/Elev= 30
  4691.7  329.78  4837.1  329.68  4897.9  327.58  4917.2  320.98  4928.3  319.70
  4938.5  319.16  4948.6  322.24  4958.7  320.68  4968.9  316.29  4978.6  309.53
  4983.6  314.54  4983.9  314.12  4989.1  306.91  4996.3  303.40  4999.0  302.90
  5002.3  303.40  5019.5  307.67  5045.0  306.10  5070.2  308.35  5090.5  306.65
  5106.4  310.19  5111.4  309.73  5120.9  311.60  5141.1  313.12  5151.3  312.69
  5167.7  317.13  5181.7  319.63  5217.4  323.15  5242.5  326.65  5272.2  328.02
#Mann=5,-1,0
  4691.7    0.05       0  4983.9    0.12       0  4996.3    0.07       0
  5002.3    0.12       0  5217.4    0.16       0
Bank Sta=4996.3,5002.3
Exp/Cntr=0.3,0.1

Type RM Length L Ch R = 1,4680,589,589,589
BEGIN DESCRIPTION:
Mapping XS 1fee2caf
END DESCRIPTION:
XS GIS Cut Line= 2
      3774099.58     10575586.71      3773593.61     10575818.90
#Sta/Elev= 30
  4639.4  324.96  4639.5  324.96  4663.3  324.29  4680.8  325.61  4703.8  326.17
  4732.3  325.50  4778.3  321.39  4793.4  318.76  4801.2  315.88  4824.2  310.34
  4870.2  306.61  4875.7  307.14  4950.2  306.83  4958.4  307.60  4980.5  306.98
  4996.2  305.69  4999.5  301.78  5002.2  301.28  5005.5  301.78  5013.5  305.43
  5019.2  309.77  5024.7  310.05  5042.2  314.38  5047.7  314.26  5058.0  316.96
  5101.5  322.34  5178.5  327.40  5185.6  328.61  5191.1  327.91  5196.1  328.43
#Mann=5,-1,0
  4639.4    0.05       0  4639.5    0.12       0  4999.5    0.07       0
  5005.5    0.12       0  5058.0    0.16       0
Bank Sta=4999.5,5005.5
Exp/Cntr=0.3,0.1

Type RM Length L Ch R = 1,4091,299,299,299
BEGIN DESCRIPTION:
UNT 070 IN BOCR 6.0
END DESCRIPTION:
XS GIS Cut Line= 3
      3773899.64     10575310.18      3773749.61     10575360.19
      3773499.61     10575610.19
#Sta/Elev= 30
  4864.2  325.42  4874.8  324.55  4895.9  323.78  4906.4  321.10  4925.7  317.22
  4938.0  315.23  4948.6  309.20  4969.6  305.49  4980.2  304.76  5001.3  304.29
  5011.8  302.53  5016.7  302.09  5019.5  301.59  5022.7  302.09  5025.9  302.09
  5036.5  303.19  5050.6  305.33  5064.8  305.33  5093.1  306.79  5121.3  306.65
  5135.5  307.55  5163.8  307.61  5192.0  309.05  5248.6  314.45  5262.8  315.45
  5291.0  319.37  5333.5  326.28  5361.8  328.82  5372.4  330.33  5375.9  330.33
#Mann=4,-1,0
  4864.2    0.05       0  4925.7    0.16       0  5016.7    0.07       0
  5022.7    0.16       0
Bank Sta=5016.7,5022.7
Exp/Cntr=0.3,0.1

Type RM Length L Ch R = 1,3792,115,115,115
BEGIN DESCRIPTION:
Mapping XS 7362fe16
END DESCRIPTION:
XS GIS Cut Line= 3
      3773815.27     10574798.83      3773627.79     10575132.14
      3773384.72     10575632.17
#Sta/Elev= 30
  4569.9  325.33  4708.7  324.79  4730.4  324.43  4736.1  322.97  4795.4  325.20
  4801.1  318.52  4808.4  317.99  4811.3  317.78  4823.9  305.69  4838.8  302.43
  4957.6  304.14  4985.8  302.40  4994.6  301.10  4999.8  298.04  5002.5  297.54
  5005.8  298.04  5025.3  302.33  5076.0  306.37  5121.1  307.76  5138.1  307.10
  5143.7  308.61  5172.5  308.93  5329.7  321.10  5352.2  322.39  5369.2  321.85
  5414.3  323.99  5436.9  327.17  5442.4  326.34  5450.5  327.64  5508.3  329.43
#Mann=4,-1,0
  4569.9    0.05       0  4808.4    0.16       0  4999.8    0.07       0
  5005.8    0.16       0
Bank Sta=4999.8,5005.8
Exp/Cntr=0.3,0.1

Type RM Length L Ch R = 1,3677,142,142,142
BEGIN DESCRIPTION:
UNT 070 IN BOCR 5.0
END DESCRIPTION:
XS GIS Cut Line= 2
      3773731.96     10574760.60      3773228.49     10575562.68
#Sta/Elev= 30
  4600.2  324.74  4636.9  321.42  4667.6  321.66  4682.4  318.84  4704.1  320.77
  4725.3  320.70  4746.5  317.20  4761.8  318.72  4767.7  315.51  4783.0  317.75
  4788.9  314.72  4825.4  305.55  4856.1  301.96  4877.3  301.13  4956.2  304.52
  4971.5  301.67  4986.8  302.05  4989.7  298.42  4992.5  297.92  4995.7  298.42
  5081.1  308.63  5233.1  312.11  5239.0  313.54  5269.6  311.10  5294.6  311.49
  5342.6  310.77  5421.6  321.55  5442.8  321.91  5515.8  332.48  5547.2  333.20
#Mann=4,-1,0
  4600.2    0.05       0  4989.7    0.04       0  4995.7    0.05       0
  5294.6    0.16       0
Bank Sta=4989.7,4995.7
Exp/Cntr=0.3,0.1

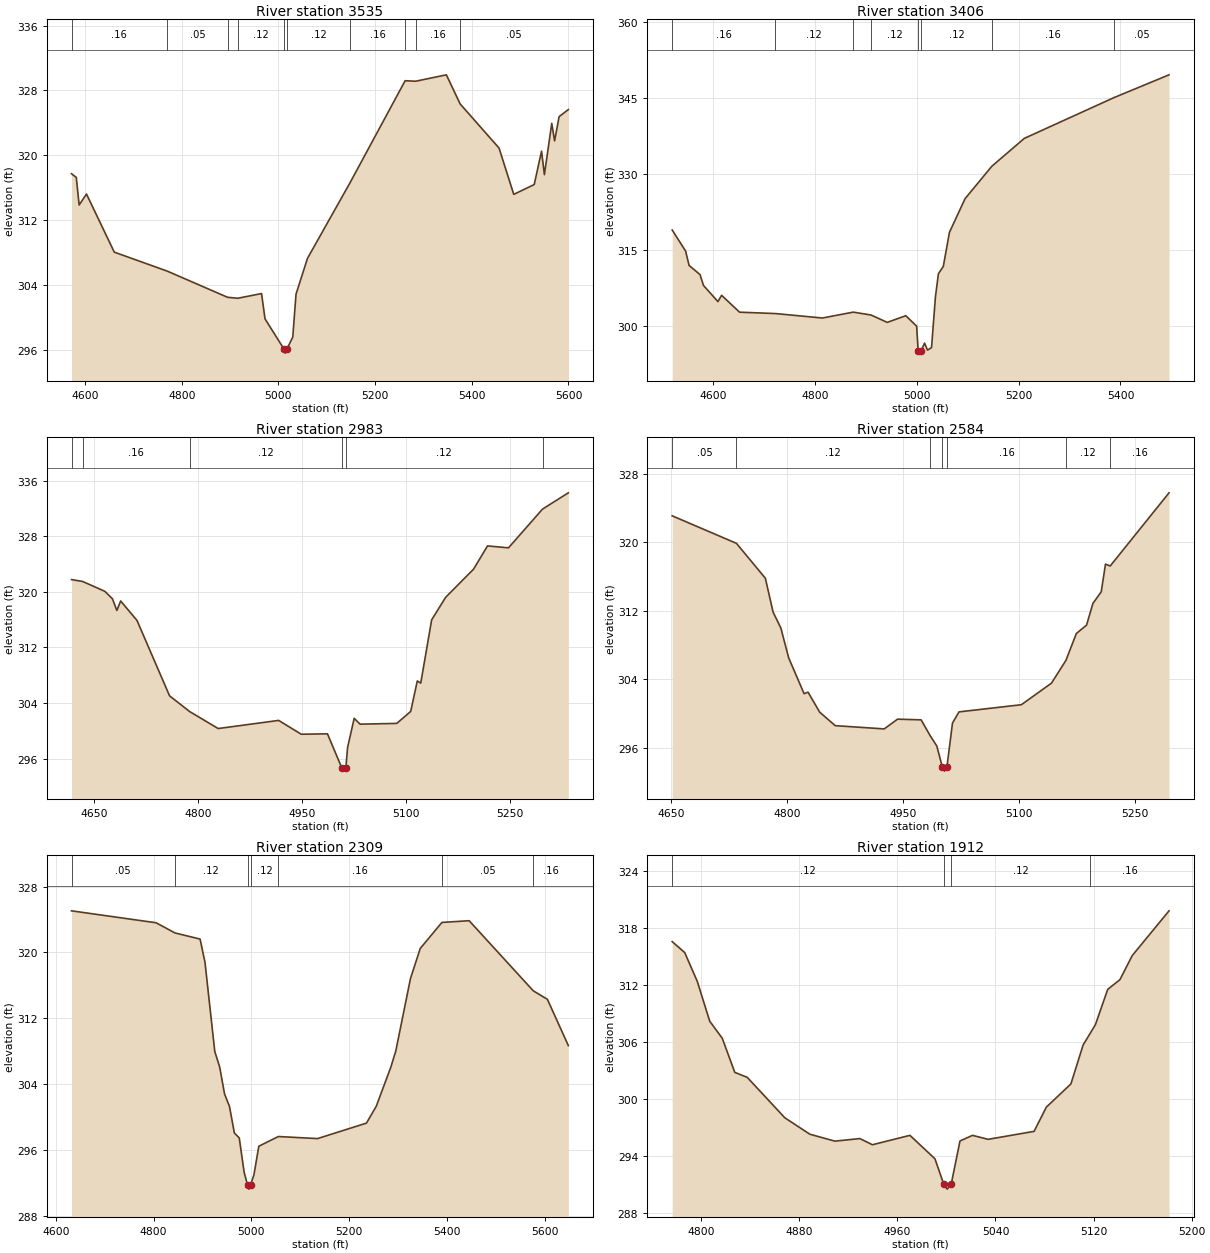
Type RM Length L Ch R = 1,3535,129,129,129
BEGIN DESCRIPTION:
Mapping XS 1f7021e5
END DESCRIPTION:
XS GIS Cut Line= 2
      3773641.66     10574649.52      3773086.10     10575514.11
#Sta/Elev= 30
  4572.0  317.73  4581.9  317.27  4587.8  313.87  4603.0  315.22  4660.5  308.05
  4770.0  305.71  4894.8  302.48  4915.9  302.36  4965.1  302.94  4972.3  299.82
  5011.5  296.09  5014.3  295.59  5017.5  296.09  5029.7  297.57  5036.4  302.86
  5060.1  307.28  5148.3  316.63  5262.1  329.20  5283.9  329.14  5347.4  329.93
  5375.9  326.34  5456.4  320.89  5486.8  315.18  5529.1  316.39  5544.3  320.51
  5550.2  317.62  5565.4  323.94  5571.3  321.78  5580.6  324.77  5599.7  325.64
#Mann=10,-1,0
  4572.0    0.16       0  4770.0    0.05       0  4894.8    0.16       0
  4915.9    0.12       0  5011.5    0.07       0  5017.5    0.12       0
  5148.3    0.16       0  5262.1    0.05       0  5283.9    0.16       0
  5375.9    0.05       0
Bank Sta=5011.5,5017.5
Exp/Cntr=0.3,0.1

Type RM Length L Ch R = 1,3406,423,423,423
BEGIN DESCRIPTION:
Mapping XS 90d4e03b
END DESCRIPTION:
XS GIS Cut Line= 3
      3773634.75     10574618.23      3773329.18     10574934.22
      3772870.85     10575212.00
#Sta/Elev= 30
  4519.8  319.01  4546.1  314.86  4553.0  312.01  4574.4  310.21  4581.3  308.06
  4609.6  304.88  4616.8  306.12  4652.1  302.79  4722.2  302.52  4814.7  301.64
  4875.4  302.80  4910.3  302.23  4942.0  300.78  4978.5  302.09  4999.8  300.02
  5002.7  295.21  5005.4  294.71  5008.7  295.21  5015.3  296.69  5021.1  295.31
  5029.0  295.80  5036.6  305.78  5042.5  310.37  5052.1  311.81  5064.1  318.53
  5094.8  325.19  5147.5  331.60  5211.2  337.09  5386.7  345.11  5495.3  349.63
#Mann=8,-1,0
  4519.8    0.16       0  4722.2    0.12       0  4875.4    0.16       0
  4910.3    0.12       0  5002.7    0.07       0  5008.7    0.12       0
  5147.5    0.16       0  5386.7    0.05       0
Bank Sta=5002.7,5008.7
Exp/Cntr=0.3,0.1

Type RM Length L Ch R = 1,2983,399,399,399
BEGIN DESCRIPTION:
UNT 070 IN BOCR 4.0
END DESCRIPTION:
XS GIS Cut Line= 3
      3773693.74     10574548.82      3773308.34     10574715.47
      3773013.86     10574750.12
#Sta/Elev= 30
  4617.6  321.76  4633.7  321.49  4665.7  320.07  4676.6  319.00  4683.0  317.32
  4688.5  318.68  4712.0  315.89  4759.0  305.03  4788.2  302.75  4829.1  300.32
  4916.3  301.49  4948.9  299.50  4986.7  299.56  5007.2  294.69  5010.0  294.19
  5013.2  294.69  5015.7  297.59  5025.2  301.79  5033.7  300.95  5086.6  301.06
  5106.7  302.78  5116.2  307.17  5121.2  306.86  5136.9  315.96  5157.0  319.20
  5197.3  323.26  5217.5  326.61  5247.7  326.33  5296.8  331.91  5334.0  334.25
#Mann=6,-1,0
  4617.6    0.05       0  4633.7    0.16       0  4788.2    0.12       0
  5007.2    0.07       0  5013.2    0.12       0  5296.8    0.16       0
Bank Sta=5007.2,5013.2
Exp/Cntr=0.3,0.1

Type RM Length L Ch R = 1,2584,275,275,275
BEGIN DESCRIPTION:
UNT 070 IN BOCR 3.0
END DESCRIPTION:
XS GIS Cut Line= 4
      3773669.45     10574427.28      3773398.62     10574455.06
      3773297.93     10574437.70      3773047.90     10574534.93
#Sta/Elev= 30
  4651.5  323.11  4734.6  319.89  4772.0  315.81  4782.0  311.85  4792.1  309.97
  4802.1  306.51  4822.1  302.30  4827.2  302.48  4842.3  300.14  4862.4  298.56
  4925.8  298.18  4943.0  299.32  4973.5  299.24  4985.2  297.39  4993.8  296.18
  5000.9  293.74  5003.7  293.24  5006.9  293.74  5014.1  298.87  5022.5  300.17
  5103.2  301.01  5142.2  303.54  5160.8  306.19  5174.3  309.34  5187.5  310.32
  5195.8  312.87  5206.5  314.22  5212.0  317.46  5218.1  317.24  5294.2  325.80
#Mann=7,-1,0
  4651.5    0.05       0  4734.6    0.12       0  4985.2    0.16       0
  5000.9    0.07       0  5006.9    0.16       0  5160.8    0.12       0
  5218.1    0.16       0
Bank Sta=5000.9,5006.9
Exp/Cntr=0.3,0.1

Type RM Length L Ch R = 1,2309,397,397,397
BEGIN DESCRIPTION:
Mapping XS 433f5e2c
END DESCRIPTION:
XS GIS Cut Line= 3
      3773822.43     10574268.25      3773262.52     10574250.89
      3772806.80     10574250.89
#Sta/Elev= 30
  4632.3  325.05  4805.2  323.60  4844.0  322.36  4895.2  321.62  4905.2  318.82
  4925.3  307.95  4935.3  306.07  4945.3  302.79  4955.3  301.29  4965.3  298.06
  4975.3  297.46  4985.3  293.28  4992.3  291.74  4995.0  291.24  4998.3  291.74
  5005.3  292.97  5015.3  296.45  5055.3  297.63  5135.4  297.38  5235.4  299.26
  5255.4  301.30  5285.4  306.08  5295.4  308.03  5325.4  316.82  5345.4  320.48
  5389.7  323.64  5445.4  323.85  5576.4  315.34  5605.4  314.30  5648.2  308.68
#Mann=7,-1,0
  4632.3    0.05       0  4844.0    0.12       0  4992.3    0.07       0
  4998.3    0.12       0  5055.3    0.16       0  5389.7    0.05       0
  5576.4    0.16       0
Bank Sta=4992.3,4998.3
Exp/Cntr=0.3,0.1

Type RM Length L Ch R = 1,1912,469,469,469
BEGIN DESCRIPTION:
UNT 070 IN BOCR 2.0
END DESCRIPTION:
XS GIS Cut Line= 3
      3773549.66     10574060.20      3773299.61     10574010.19
      3773149.61     10574010.19
#Sta/Elev= 30
  4776.5  316.55  4786.7  315.40  4796.9  312.38  4807.1  308.17  4817.3  306.38
  4827.5  302.79  4837.7  302.26  4868.3  298.01  4888.7  296.28  4909.1  295.55
  4929.5  295.82  4939.7  295.17  4970.3  296.16  4990.7  293.69  4997.9  291.00
  5000.7  290.50  5003.9  291.00  5011.1  295.57  5021.3  296.16  5034.0  295.74
  5071.5  296.58  5081.5  299.13  5101.5  301.57  5111.5  305.68  5117.1  306.87
  5121.5  307.81  5131.5  311.52  5141.5  312.55  5151.5  315.08  5181.5  319.79
#Mann=4,-1,0
  4776.5    0.12       0  4997.9    0.07       0  5003.9    0.12       0
  5117.1    0.16       0
Bank Sta=4997.9,5003.9
Exp/Cntr=0.3,0.1

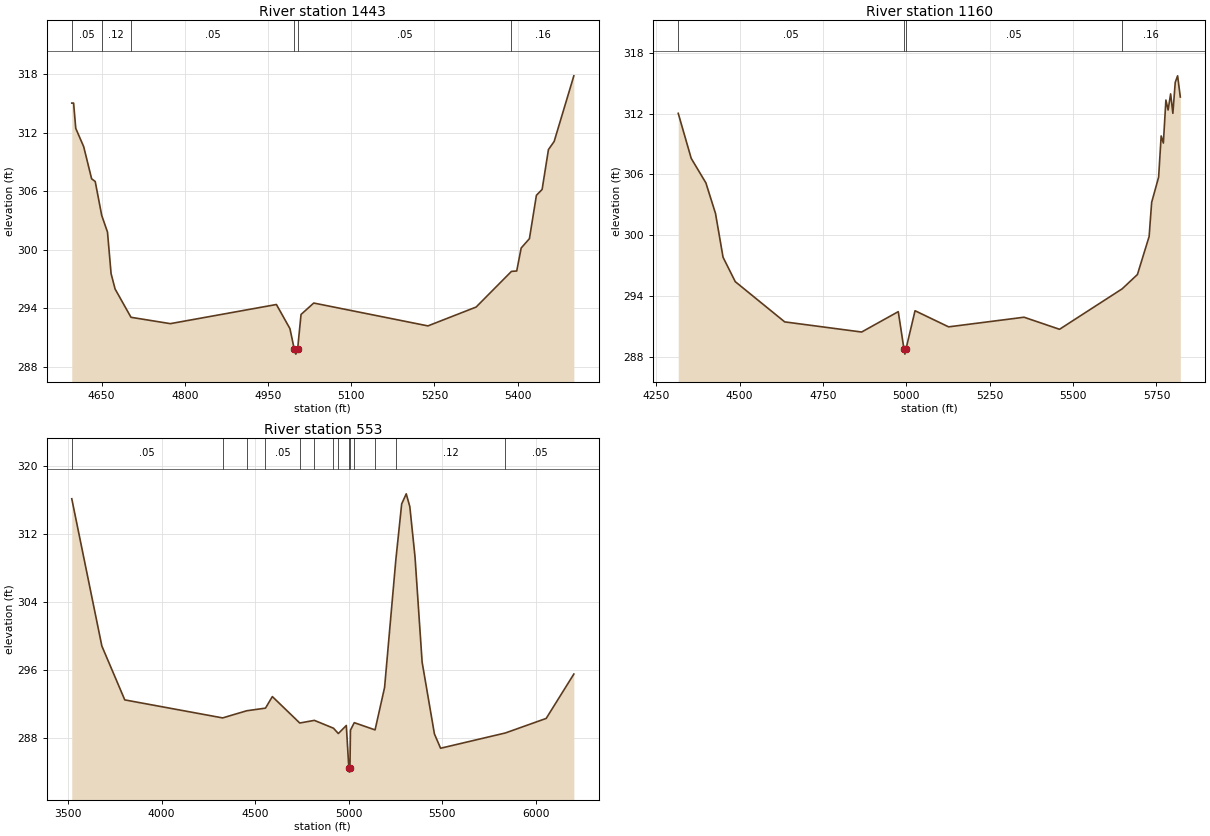
Type RM Length L Ch R = 1,1443,283,283,283
BEGIN DESCRIPTION:
UNT 070 IN BOCR 1.0
END DESCRIPTION:
XS GIS Cut Line= 3
      3773699.61     10573910.19      3773449.61     10573610.19
      3772999.60     10573860.19
#Sta/Elev= 30
  4596.1  315.02  4599.4  315.02  4603.3  312.43  4617.6  310.56  4631.9  307.27
  4638.4  306.99  4650.1  303.52  4660.5  301.82  4667.0  297.56  4674.2  295.99
  4702.9  293.09  4773.8  292.44  4965.1  294.40  4989.5  291.93  4997.3  289.82
  5000.1  289.32  5003.3  289.82  5009.5  293.38  5032.4  294.55  5238.3  292.21
  5325.2  294.14  5388.9  297.79  5398.4  297.83  5406.4  300.18  5421.3  301.14
  5433.9  305.58  5444.2  306.18  5455.6  310.26  5465.9  311.09  5501.4  317.81
#Mann=6,-1,0
  4596.1    0.05       0  4650.1    0.12       0  4702.9    0.05       0
  4997.3    0.03       0  5003.3    0.05       0  5388.9    0.16       0
Bank Sta=4997.3,5003.3
Exp/Cntr=0.3,0.1

Type RM Length L Ch R = 1,1160,607,607,607
BEGIN DESCRIPTION:
Mapping XS 47ea309a
END DESCRIPTION:
XS GIS Cut Line= 4
      3773883.16     10573868.91      3773614.08     10573361.14
      3773371.02     10573335.09      3772919.60     10573851.62
#Sta/Elev= 30
  4316.3  312.02  4355.2  307.58  4399.2  305.16  4428.0  302.15  4450.7  297.82
  4487.2  295.42  4635.5  291.45  4866.1  290.45  4975.9  292.46  4993.0  288.77
  4995.8  288.27  4999.0  288.77  5026.2  292.55  5126.8  290.96  5353.0  291.91
  5459.3  290.72  5647.1  294.71  5692.8  296.12  5727.9  299.87  5735.5  303.24
  5756.4  305.73  5764.0  309.79  5770.6  309.09  5778.2  313.33  5784.8  312.35
  5792.4  313.94  5799.1  312.02  5806.2  315.08  5813.3  315.72  5821.4  313.63
#Mann=4,-1,0
  4316.3    0.05       0  4993.0    0.03       0  4999.0    0.05       0
  5647.1    0.16       0
Bank Sta=4993,4999
Exp/Cntr=0.3,0.1

Type RM Length L Ch R = 1,553,0,0,0
BEGIN DESCRIPTION:
Mapping XS 61e89ed7
END DESCRIPTION:
XS GIS Cut Line= 6
      3773995.91     10573857.69      3773843.13     10573125.04
      3773482.02     10572753.51      3773377.85     10572756.98
      3772999.38     10572934.07      3772738.97     10573791.70
#Sta/Elev= 30
  3519.6  316.13  3680.5  298.80  3803.1  292.46  4326.4  290.34  4454.8  291.18
  4555.5  291.49  4592.2  292.85  4738.9  289.74  4816.9  290.05  4919.1  289.13
  4945.1  288.50  4987.8  289.45  5001.2  284.46  5004.0  283.96  5007.2  284.46
  5009.9  288.90  5030.3  289.78  5141.5  288.93  5192.4  293.92  5252.6  308.94
  5283.8  315.52  5308.2  316.71  5327.4  315.20  5355.1  309.30  5393.2  296.90
  5459.0  288.45  5491.9  286.77  5838.7  288.57  6056.6  290.28  6204.5  295.50
#Mann=14,-1,0
  3519.6    0.05       0  4326.4    0.12       0  4454.8    0.16       0
  4555.5    0.05       0  4738.9    0.16       0  4816.9    0.05       0
  4919.1    0.12       0  4945.1    0.16       0  5001.2    0.07       0
  5007.2    0.16       0  5030.3    0.12       0  5141.5    0.16       0
  5252.6    0.12       0  5838.7    0.05       0
Bank Sta=5001.2,5007.2
Exp/Cntr=0.3,0.1

Chan Stop Cuts=-1