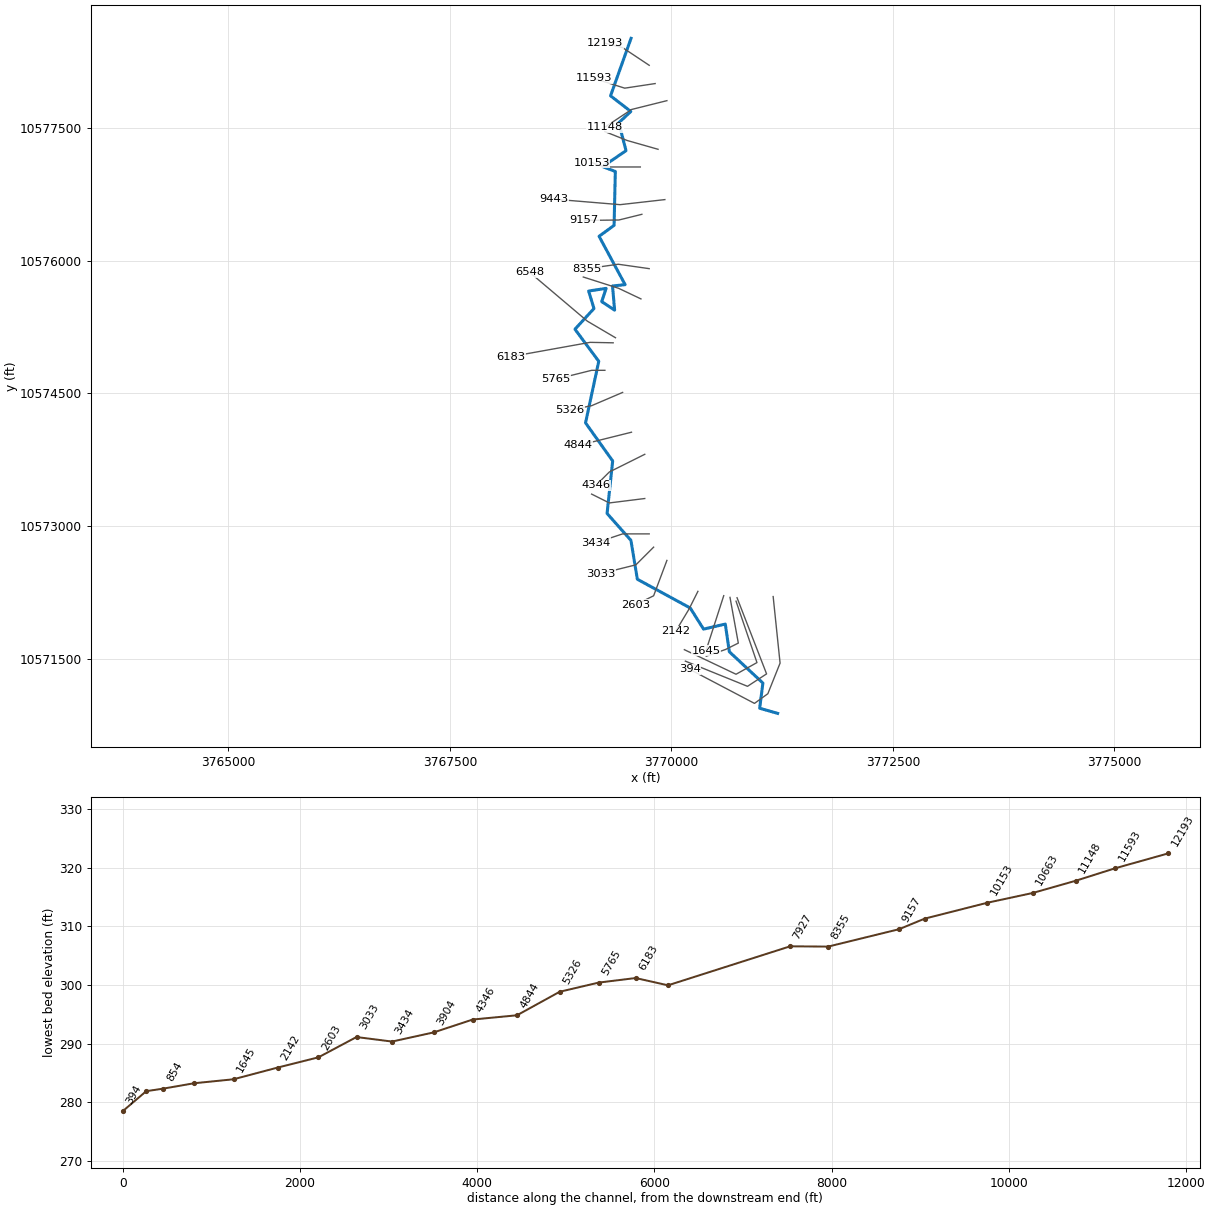
--- UNT 071 IN BOCR.prj (project) ---

Proj Title=UNT 071 IN BOCR Base Level Engineering
Current Plan=p01
Default Exp/Contr=0.3,0.1
English Units
Geom File=g01
Flow File=f01
Plan File=p01
BEGIN DESCRIPTION:
UNT 071 IN BOCR
END DESCRIPTION:

--- UNT 071 IN BOCR.p01 (plan) ---

Plan Title=Multiple Run
Short Identifier=Multiple
Geom File=g01
Flow File=f01
Subcritical Flow
K Sum by GR= 0
Std Step Tol= 0.01
Critical Tol= 0.01
Num of Std Step Trials= 20
Max Error Tol= 0.3
Flow Tol Ratio= 0.001
Split Flow NTrial= 30
Split Flow Tol= 0.02
Split Flow Ratio= 0.02
Log Output Level= 0
Friction Slope Method= 1
Unsteady Friction Slope Method= 2
Unsteady Bridges Friction Slope Method= 1
Parabolic Critical Depth
Global Vel Dist=  1 , 1 , 1
Global Log Level= 0
CheckData=True
Encroach Param= -1, 0, 0, 0
BEGIN DESCRIPTION:
Multiple Run
END DESCRIPTION:

--- UNT 071 IN BOCR.f01 (steady flow) ---

Flow Title=Multiple
Number of Profiles=7
Profile Names=10-year,25-year,50-year,1pct_min,100-year,1pct_plu,500-year
River Rch & RM= UNT 071 IN BOCR,Reach-1,12193
     559     755     917     819    1107    1498    1621
River Rch & RM= UNT 071 IN BOCR,Reach-1,11148
     742    1012    1237    1111    1502    2031    2222
Boundary for River Rch & Prof#=UNT 071 IN BOCR,Reach-1,1
Up Type=0
Dn Type=3
Dn Slope=0.005
Boundary for River Rch & Prof#=UNT 071 IN BOCR,Reach-1,2
Up Type=0
Dn Type=3
Dn Slope=0.005
Boundary for River Rch & Prof#=UNT 071 IN BOCR,Reach-1,3
Up Type=0
Dn Type=3
Dn Slope=0.005
Boundary for River Rch & Prof#=UNT 071 IN BOCR,Reach-1,4
Up Type=0
Dn Type=3
Dn Slope=0.005
Boundary for River Rch & Prof#=UNT 071 IN BOCR,Reach-1,5
Up Type=0
Dn Type=3
Dn Slope=0.005
Boundary for River Rch & Prof#=UNT 071 IN BOCR,Reach-1,6
Up Type=0
Dn Type=3
Dn Slope=0.005
Boundary for River Rch & Prof#=UNT 071 IN BOCR,Reach-1,7
Up Type=0
Dn Type=3
Dn Slope=0.005

--- UNT 071 IN BOCR.g01 (geometry) ---

Geom Title=Existing Conditions

River Reach=UNT 071 IN BOCR,Reach-1
Reach XY= 30
      3769544.75     10578515.20      3769313.25     10577865.00
      3769542.25     10577688.00      3769406.00     10577560.00
      3769488.00     10577245.00      3769225.50     10577064.00
      3769367.25     10577009.00      3769353.25     10576400.00
      3769183.75     10576276.00      3769477.75     10575729.00
      3769335.50     10575714.00      3769359.25     10575441.00
      3769213.50     10575537.00      3769263.25     10575687.00
      3769066.00     10575657.00      3769126.00     10575459.00
      3768911.50     10575225.00      3769180.25     10574862.00
      3769031.00     10574166.00      3769337.25     10573735.00
      3769274.25     10573141.00      3769543.25     10572837.00
      3769616.00     10572397.00      3770212.75     10572072.00
      3770363.50     10571833.00      3770608.75     10571890.00
      3770654.25     10571577.00      3771033.25     10571223.00
      3770996.75     10570938.00      3771199.50     10570880.00

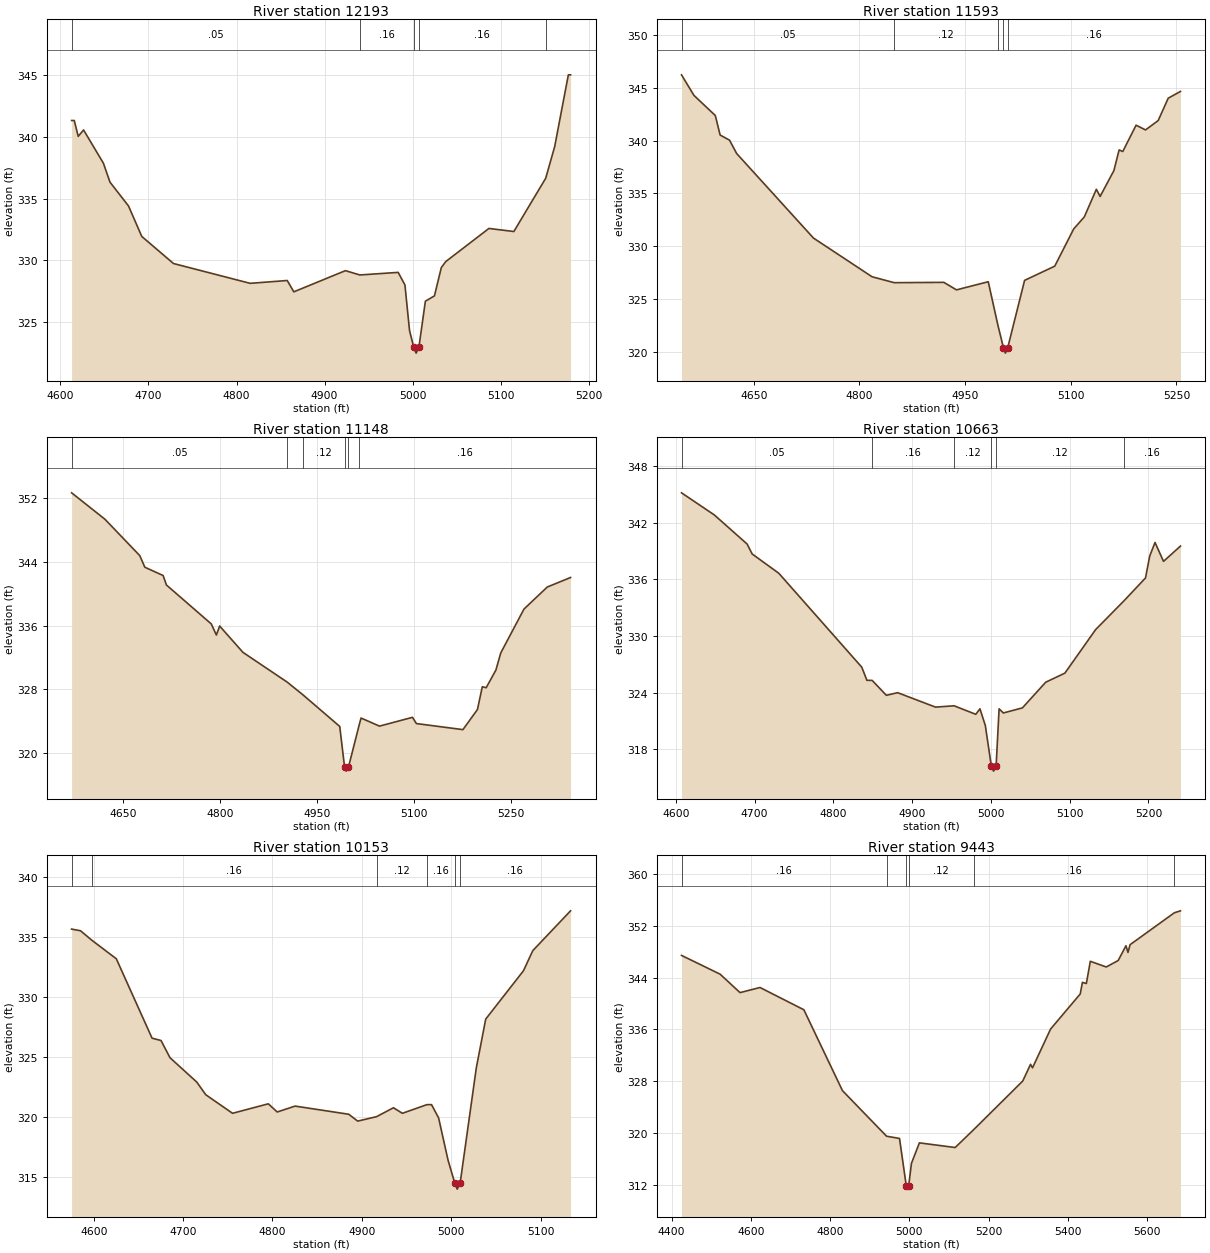
Type RM Length L Ch R = 1,12193,600,600,600
BEGIN DESCRIPTION:
UNT 071 IN BOCR 21.0
END DESCRIPTION:
XS GIS Cut Line= 3
      3769749.64     10578210.17      3769449.61     10578410.19
      3769249.65     10578460.18
#Sta/Elev= 30
  4612.7  341.34  4615.7  341.34  4620.2  340.05  4626.3  340.57  4648.8  337.87
  4656.3  336.33  4677.3  334.40  4692.4  331.92  4728.4  329.72  4815.5  328.11
  4857.6  328.34  4865.1  327.42  4923.7  329.14  4940.1  328.79  4983.6  329.00
  4991.3  327.98  4996.5  324.28  5001.2  322.94  5004.0  322.44  5007.2  322.94
  5014.5  326.66  5024.8  327.09  5032.6  329.39  5037.7  329.88  5086.7  332.57
  5115.0  332.32  5151.2  336.65  5161.4  339.23  5176.9  345.05  5179.4  345.05
#Mann=5,-1,0
  4612.7    0.05       0  4940.1    0.16       0  5001.2    0.07       0
  5007.2    0.16       0  5151.2     0.1       0
Bank Sta=5001.2,5007.2
Exp/Cntr=0.3,0.1

Type RM Length L Ch R = 1,11593,445,445,445
BEGIN DESCRIPTION:
UNT 071 IN BOCR 20.0
END DESCRIPTION:
XS GIS Cut Line= 3
      3769817.03     10578003.67      3769473.27     10577951.58
      3769129.54     10578060.95
#Sta/Elev= 30
  4547.4  346.21  4565.0  344.27  4595.4  342.36  4602.2  340.52  4615.6  340.03
  4625.7  338.77  4734.7  330.78  4817.9  327.12  4849.4  326.56  4919.9  326.59
  4937.8  325.88  4982.9  326.65  4996.5  322.57  5004.5  320.40  5007.3  319.90
  5010.5  320.40  5034.5  326.78  5077.3  328.12  5104.2  331.64  5119.3  332.78
  5136.4  335.39  5141.7  334.71  5161.3  337.16  5168.7  339.11  5173.9  338.96
  5192.8  341.45  5206.2  341.00  5224.2  341.89  5238.4  344.00  5255.8  344.64
#Mann=5,-1,0
  4547.4    0.05       0  4849.4    0.12       0  4996.5    0.16       0
  5004.5    0.07       0  5010.5    0.16       0
Bank Sta=5004.5,5010.5
Exp/Cntr=0.3,0.1

Type RM Length L Ch R = 1,11148,485,485,485
BEGIN DESCRIPTION:
UNT 071 IN BOCR 19.0
END DESCRIPTION:
XS GIS Cut Line= 3
      3769949.58     10577810.18      3769549.61     10577710.19
      3769249.64     10577510.21
#Sta/Elev= 30
  4569.9  352.64  4621.4  349.34  4675.5  344.77  4683.3  343.32  4711.6  342.28
  4716.8  341.09  4786.3  336.21  4794.1  334.82  4799.2  335.95  4835.3  332.65
  4903.7  328.93  4928.5  327.31  4985.2  323.37  4992.7  318.27  4995.4  317.77
  4998.7  318.27  5015.2  323.52  5018.2  324.42  5046.8  323.41  5097.9  324.51
  5103.9  323.73  5176.0  322.97  5198.5  325.49  5206.0  328.34  5212.0  328.22
  5227.1  330.44  5234.6  332.58  5270.6  338.08  5306.7  340.84  5342.7  342.03
#Mann=6,-1,0
  4569.9    0.05       0  4903.7    0.16       0  4928.5    0.12       0
  4992.7    0.07       0  4998.7    0.12       0  5015.2    0.16       0
Bank Sta=4992.7,4998.7
Exp/Cntr=0.3,0.1

Type RM Length L Ch R = 1,10663,510,510,510
BEGIN DESCRIPTION:
UNT 071 IN BOCR 18.0
END DESCRIPTION:
XS GIS Cut Line= 3
      3769849.64     10577260.18      3769499.61     10577360.19
      3769249.61     10577460.19
#Sta/Elev= 30
  4607.3  345.17  4648.9  342.83  4690.5  339.75  4697.0  338.69  4730.8  336.65
  4836.1  326.70  4842.6  325.31  4849.3  325.30  4867.3  323.72  4881.6  324.00
  4929.7  322.47  4953.3  322.61  4980.8  321.71  4986.1  322.29  4992.9  320.53
  5000.6  316.19  5003.4  315.69  5006.6  316.19  5010.4  322.29  5015.8  321.85
  5040.0  322.39  5069.6  325.11  5093.9  326.07  5132.9  330.68  5169.0  333.74
  5196.2  336.15  5201.6  338.48  5208.3  339.91  5219.1  337.91  5240.6  339.53
#Mann=6,-1,0
  4607.3    0.05       0  4849.3    0.16       0  4953.3    0.12       0
  5000.6    0.07       0  5006.6    0.12       0  5169.0    0.16       0
Bank Sta=5000.6,5006.6
Exp/Cntr=0.3,0.1

Type RM Length L Ch R = 1,10153,710,710,710
BEGIN DESCRIPTION:
UNT 071 IN BOCR 17.0
END DESCRIPTION:
XS GIS Cut Line= 3
      3769649.59     10577060.19      3769249.61     10577060.19
      3769099.60     10577110.19
#Sta/Elev= 30
  4575.3  335.67  4585.3  335.53  4597.8  334.75  4625.3  333.20  4665.3  326.59
  4675.3  326.40  4685.3  324.97  4715.3  322.94  4725.3  321.89  4755.3  320.34
  4795.3  321.13  4805.3  320.45  4825.3  320.94  4885.3  320.26  4895.3  319.69
  4916.4  320.06  4935.3  320.80  4945.3  320.34  4972.7  321.06  4977.9  321.06
  4985.8  319.96  4996.4  316.43  5003.9  314.53  5006.6  314.03  5009.9  314.53
  5028.0  324.13  5038.5  328.18  5080.7  332.20  5091.2  333.88  5133.4  337.19
#Mann=6,-1,0
  4575.3    0.05       0  4597.8    0.16       0  4916.4    0.12       0
  4972.7    0.16       0  5003.9    0.07       0  5009.9    0.16       0
Bank Sta=5003.9,5009.9
Exp/Cntr=0.3,0.1

Type RM Length L Ch R = 1,9443,286,286,286
BEGIN DESCRIPTION:
UNT 071 IN BOCR 16.0
END DESCRIPTION:
XS GIS Cut Line= 3
      3769926.41     10576691.17      3769421.19     10576633.88
      3768672.94     10576696.23
#Sta/Elev= 30
  4425.0  347.43  4522.4  344.53  4572.7  341.68  4623.1  342.47  4733.8  339.03
  4831.2  326.53  4942.5  319.49  4975.2  319.14  4992.3  311.81  4995.0  311.31
  4998.3  311.81  5005.3  315.29  5025.4  318.46  5115.7  317.74  5163.0  320.54
  5286.3  328.02  5305.9  330.60  5310.9  330.06  5356.5  336.05  5431.3  341.47
  5436.8  343.26  5446.8  343.09  5456.8  346.52  5497.0  345.64  5527.1  346.64
  5546.7  348.92  5551.8  347.90  5557.2  349.09  5668.9  354.02  5684.3  354.32
#Mann=6,-1,0
  4425.0    0.16       0  4942.5    0.12       0  4992.3    0.07       0
  4998.3    0.12       0  5163.0    0.16       0  5668.9    0.05       0
Bank Sta=4992.3,4998.3
Exp/Cntr=0.3,0.1

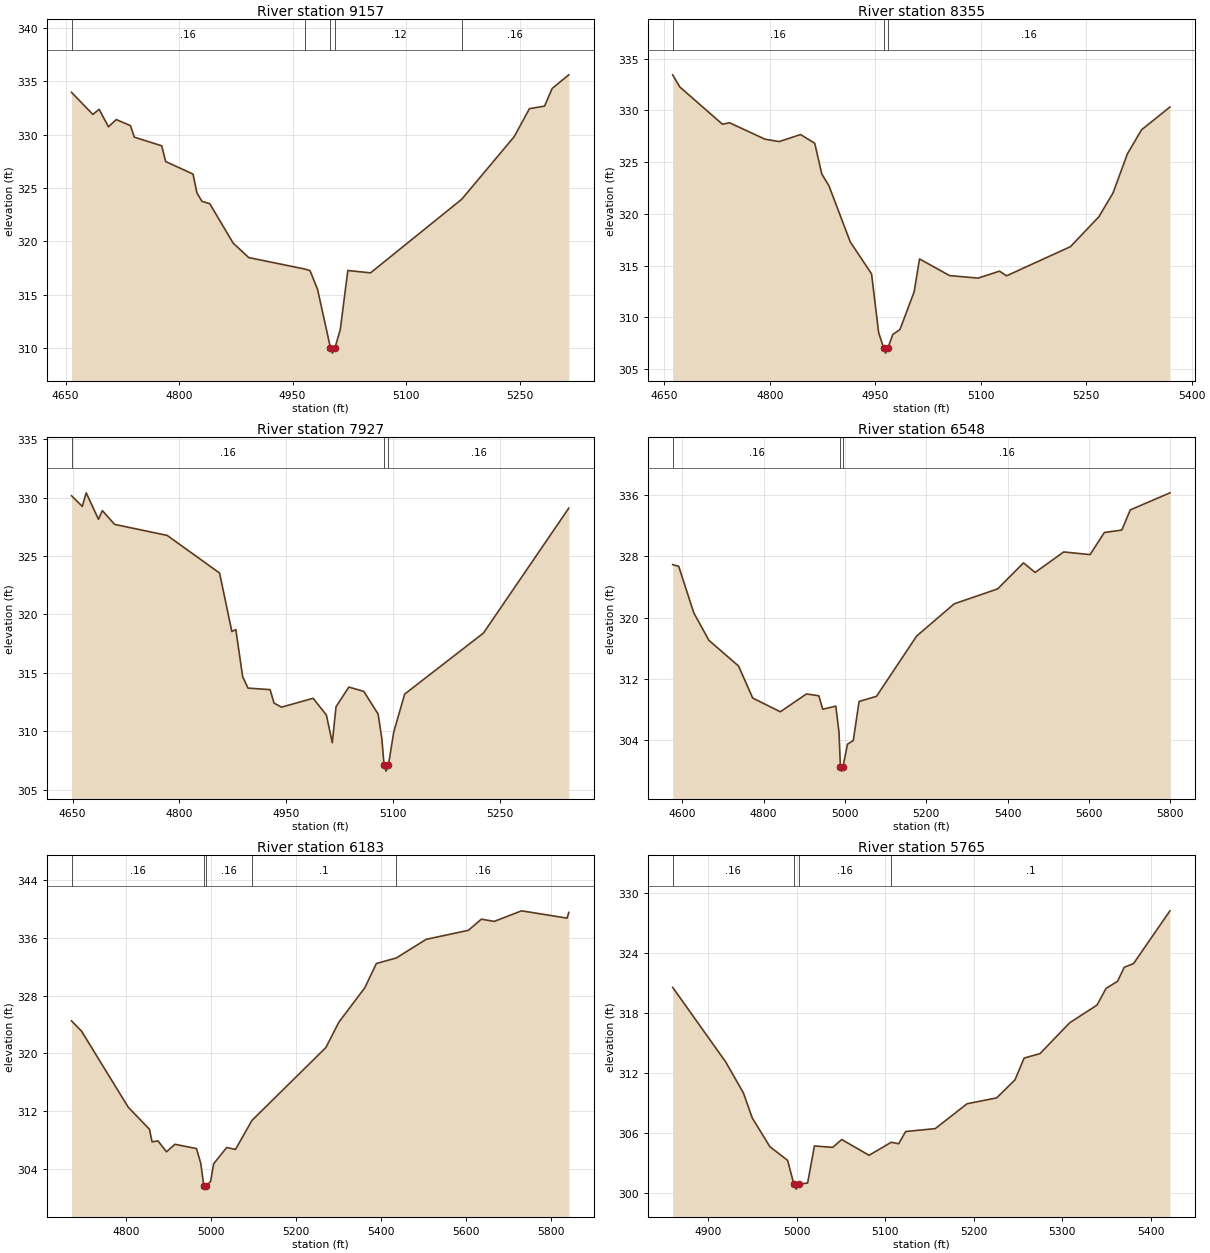
Type RM Length L Ch R = 1,9157,802,802,802
BEGIN DESCRIPTION:
UNT 071 IN BOCR 15.0
END DESCRIPTION:
XS GIS Cut Line= 3
      3769666.94     10576524.77      3769408.26     10576460.53
      3769017.63     10576455.33
#Sta/Elev= 30
  4657.9  333.95  4686.1  331.88  4694.4  332.36  4706.7  330.72  4717.0  331.40
  4735.8  330.83  4740.9  329.75  4777.1  328.94  4782.3  327.47  4818.5  326.29
  4823.7  324.52  4830.3  323.74  4840.6  323.52  4871.5  319.83  4892.1  318.47
  4966.0  317.40  4973.1  317.25  4983.1  315.49  5000.1  310.02  5002.8  309.52
  5006.1  310.02  5013.1  311.73  5023.1  317.26  5053.1  317.04  5173.7  323.94
  5243.1  329.81  5263.1  332.42  5283.1  332.66  5293.1  334.31  5315.1  335.59
#Mann=5,-1,0
  4657.9    0.16       0  4966.0    0.12       0  5000.1    0.07       0
  5006.1    0.12       0  5173.7    0.16       0
Bank Sta=5000.1,5006.1
Exp/Cntr=0.3,0.1

Type RM Length L Ch R = 1,8355,428,428,428
BEGIN DESCRIPTION:
UNT 071 IN BOCR 14.0
END DESCRIPTION:
XS GIS Cut Line= 3
      3769749.60     10575910.19      3769399.61     10575960.19
      3769049.60     10575910.19
#Sta/Elev= 30
  4662.0  333.44  4672.1  332.27  4732.7  328.67  4742.8  328.81  4793.3  327.22
  4813.5  326.99  4843.8  327.67  4864.0  326.83  4874.1  323.85  4884.2  322.72
  4914.5  317.30  4944.8  314.21  4954.9  308.53  4962.0  307.05  4964.8  306.55
  4968.0  307.05  4975.1  308.36  4985.2  308.83  5005.4  312.48  5013.0  315.65
  5055.9  314.04  5096.4  313.80  5126.7  314.47  5136.8  314.02  5227.7  316.84
  5268.1  319.73  5288.3  322.04  5308.5  325.79  5328.7  328.13  5369.1  330.33
#Mann=3,-1,0
  4662.0    0.16       0  4962.0    0.07       0  4968.0    0.16       0
Bank Sta=4962,4968
Exp/Cntr=0.3,0.1

Type RM Length L Ch R = 1,7927,1379,1379,1379
BEGIN DESCRIPTION:
UNT 071 IN BOCR 13.0
END DESCRIPTION:
XS GIS Cut Line= 3
      3769656.49     10575567.88      3769404.80     10575687.65
      3769005.61     10575815.52
#Sta/Elev= 30
  4648.5  330.15  4663.6  329.24  4669.1  330.40  4686.3  328.14  4691.8  328.88
  4709.0  327.70  4782.7  326.76  4856.3  323.54  4873.5  318.54  4879.1  318.71
  4888.7  314.67  4896.2  313.70  4927.2  313.57  4932.7  312.42  4943.2  312.07
  4987.6  312.83  5006.2  311.40  5014.5  309.03  5019.7  312.10  5037.7  313.79
  5058.7  313.42  5078.8  311.48  5084.0  309.40  5087.2  307.10  5089.9  306.60
  5093.2  307.10  5100.7  309.93  5116.1  313.19  5226.7  318.41  5346.4  329.09
#Mann=3,-1,0
  4648.5    0.16       0  5087.2    0.07       0  5093.2    0.16       0
Bank Sta=5087.2,5093.2
Exp/Cntr=0.3,0.1

Type RM Length L Ch R = 1,6548,365,365,365
BEGIN DESCRIPTION:
UNT 071 IN BOCR 12.0
END DESCRIPTION:
XS GIS Cut Line= 3
      3769369.07     10575128.69      3769051.40     10575316.17
      3768400.34     10575868.26
#Sta/Elev= 30
  4576.3  326.91  4591.1  326.70  4628.2  320.62  4665.3  317.03  4738.2  313.68
  4773.1  309.49  4840.9  307.70  4905.2  310.03  4935.6  309.79  4945.2  308.03
  4977.4  308.44  4985.2  305.02  4988.7  300.45  4991.5  299.95  4994.7  300.45
  5006.0  303.46  5020.3  303.95  5034.6  309.05  5077.4  309.72  5176.3  317.60
  5268.5  321.80  5375.1  323.74  5438.8  327.14  5467.4  325.89  5537.6  328.57
  5602.5  328.22  5637.6  331.11  5680.5  331.43  5701.3  334.06  5798.8  336.29
#Mann=3,-1,0
  4576.3    0.16       0  4988.7    0.07       0  4994.7    0.16       0
Bank Sta=4988.7,4994.7
Exp/Cntr=0.3,0.1

Type RM Length L Ch R = 1,6183,418,418,418
BEGIN DESCRIPTION:
UNT 071 IN BOCR 11.0
END DESCRIPTION:
XS GIS Cut Line= 3
      3769343.10     10575071.37      3769082.65     10575076.58
      3768186.99     10574915.16
#Sta/Elev= 30
  4670.9  324.49  4694.4  323.08  4804.4  312.54  4854.4  309.48  4860.5  307.74
  4874.4  307.87  4894.4  306.36  4914.4  307.40  4965.0  306.81  4975.1  304.78
  4982.3  301.69  4985.0  301.19  4988.3  301.69  4998.1  302.23  5005.6  304.71
  5036.1  306.95  5056.8  306.69  5095.7  310.71  5269.8  320.81  5300.3  324.32
  5361.3  329.08  5388.5  332.44  5435.5  333.21  5505.8  335.79  5605.1  337.04
  5635.6  338.58  5666.1  338.28  5730.4  339.74  5837.5  338.73  5841.5  339.52
#Mann=5,-1,0
  4670.9    0.16       0  4982.3    0.07       0  4988.3    0.16       0
  5095.7     0.1       0  5435.5    0.16       0
Bank Sta=4982.3,4988.3
Exp/Cntr=0.3,0.1

Type RM Length L Ch R = 1,5765,439,439,439
BEGIN DESCRIPTION:
UNT 071 IN BOCR 10.0
END DESCRIPTION:
XS GIS Cut Line= 3
      3769249.59     10574760.19      3769099.61     10574760.19
      3768699.60     10574660.19
#Sta/Elev= 30
  4859.6  320.55  4919.6  313.10  4939.6  310.01  4949.6  307.51  4969.6  304.64
  4989.6  303.28  4996.6  300.91  4999.3  300.41  5002.6  300.91  5012.2  301.02
  5019.9  304.72  5040.5  304.58  5050.8  305.36  5081.7  303.79  5106.8  305.09
  5115.2  304.94  5123.0  306.16  5156.5  306.45  5192.5  308.93  5226.0  309.52
  5246.7  311.32  5257.0  313.49  5275.0  313.94  5308.5  317.01  5339.4  318.78
  5349.7  320.45  5362.6  321.15  5370.3  322.56  5380.7  322.92  5421.9  328.19
#Mann=4,-1,0
  4859.6    0.16       0  4996.6    0.07       0  5002.6    0.16       0
  5106.8     0.1       0
Bank Sta=4996.6,5002.6
Exp/Cntr=0.3,0.1

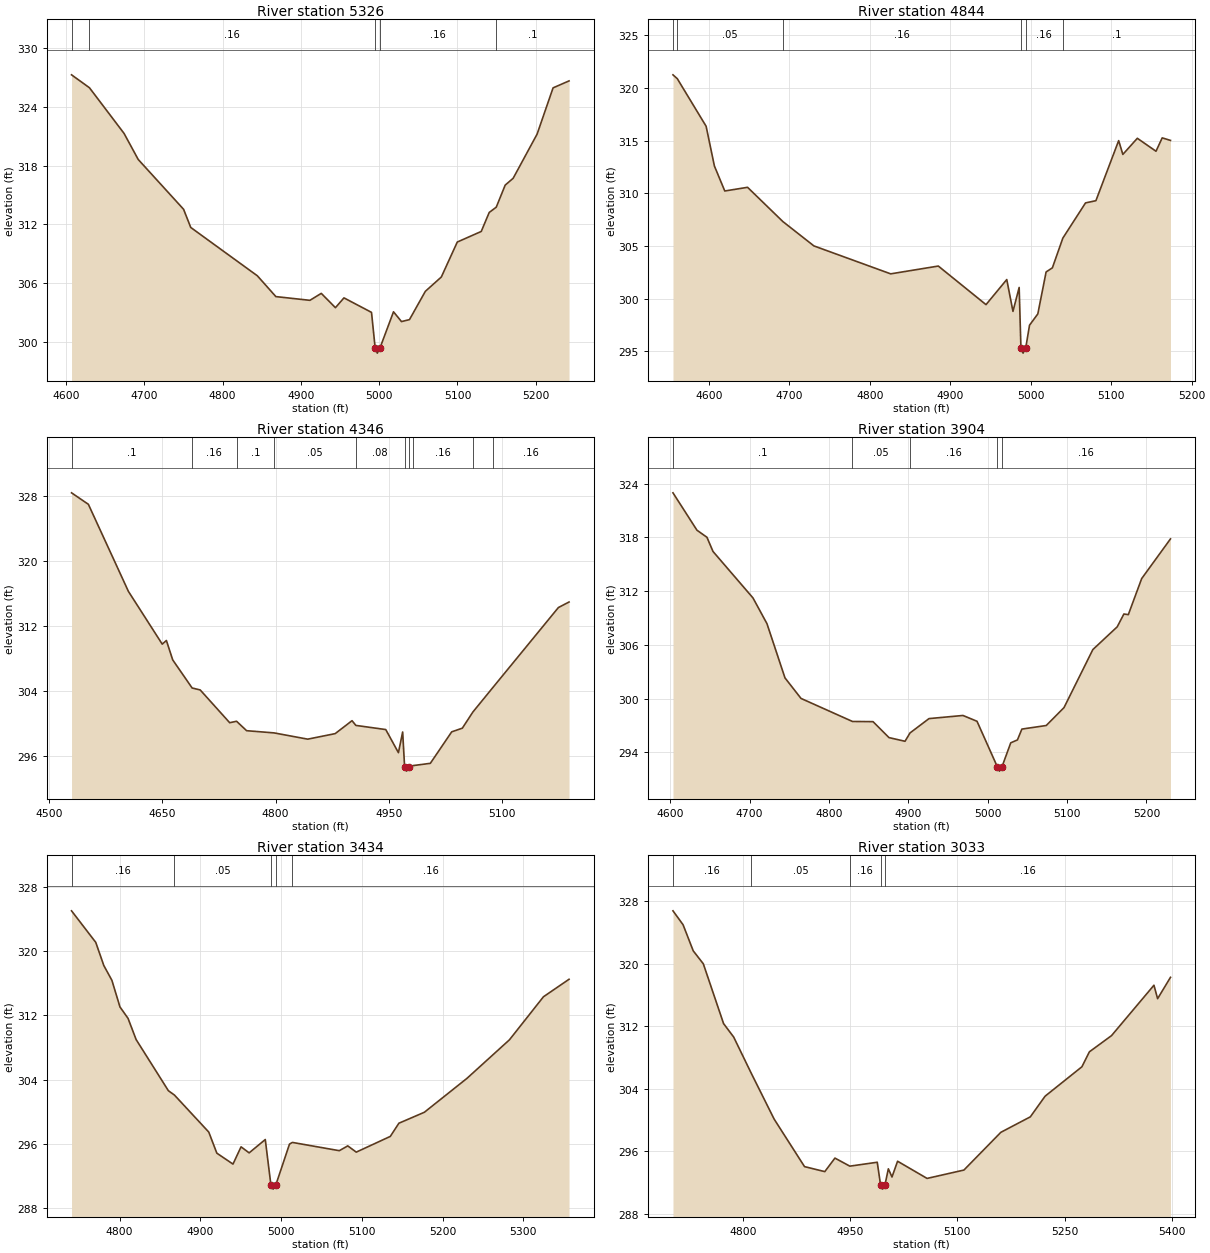
Type RM Length L Ch R = 1,5326,482,482,482
BEGIN DESCRIPTION:
UNT 071 IN BOCR 9.0
END DESCRIPTION:
XS GIS Cut Line= 3
      3769449.58     10574510.18      3769099.61     10574360.19
      3768849.62     10574310.19
#Sta/Elev= 30
  4606.9  327.26  4629.8  325.94  4674.0  321.28  4692.1  318.62  4750.1  313.53
  4759.2  311.68  4844.4  306.74  4868.0  304.62  4911.5  304.24  4926.0  304.95
  4944.1  303.49  4955.0  304.49  4990.2  303.01  4994.9  299.35  4997.6  298.85
  5000.9  299.35  5018.3  303.07  5028.5  302.07  5038.7  302.27  5059.0  305.16
  5079.4  306.62  5099.8  310.19  5130.4  311.27  5140.6  313.21  5149.6  313.75
  5161.0  316.00  5171.2  316.70  5201.8  321.21  5222.2  325.93  5242.6  326.64
#Mann=5,-1,0
  4606.9     0.1       0  4629.8    0.16       0  4994.9    0.07       0
  5000.9    0.16       0  5149.6     0.1       0
Bank Sta=4994.9,5000.9
Exp/Cntr=0.3,0.1

Type RM Length L Ch R = 1,4844,498,498,498
BEGIN DESCRIPTION:
UNT 071 IN BOCR 8.0
END DESCRIPTION:
XS GIS Cut Line= 3
      3769549.59     10574060.18      3769149.61     10573960.19
      3768949.65     10573910.20
#Sta/Elev= 30
  4555.2  321.24  4560.6  320.87  4596.4  316.36  4606.7  312.59  4619.6  310.22
  4647.9  310.57  4691.8  307.32  4730.4  305.01  4825.8  302.36  4885.0  303.10
  4944.3  299.44  4970.1  301.82  4977.8  298.80  4985.5  301.07  4987.7  295.34
  4990.4  294.84  4993.7  295.34  4998.4  297.49  5008.7  298.56  5019.0  302.54
  5026.8  302.93  5039.8  305.75  5068.0  309.09  5080.9  309.30  5109.2  315.00
  5114.4  313.69  5132.4  315.22  5155.6  313.99  5163.3  315.26  5173.6  315.02
#Mann=6,-1,0
  4555.2    0.16       0  4560.6    0.05       0  4691.8    0.16       0
  4987.7    0.07       0  4993.7    0.16       0  5039.8     0.1       0
Bank Sta=4987.7,4993.7
Exp/Cntr=0.3,0.1

Type RM Length L Ch R = 1,4346,442,442,442
BEGIN DESCRIPTION:
UNT 071 IN BOCR 7.0
END DESCRIPTION:
XS GIS Cut Line= 3
      3769699.58     10573810.17      3769299.61     10573610.19
      3769149.62     10573460.20
#Sta/Elev= 30
  4529.5  328.33  4551.8  326.92  4604.9  316.21  4649.7  309.73  4655.2  310.18
  4663.6  307.79  4689.3  304.34  4700.0  304.10  4739.1  300.07  4748.2  300.25
  4761.5  299.09  4797.8  298.82  4842.5  298.05  4878.9  298.73  4901.2  300.32
  4906.3  299.74  4945.9  299.23  4962.7  296.39  4968.3  298.93  4970.9  294.62
  4973.6  294.12  4976.9  294.62  4982.2  294.80  5005.0  295.08  5033.3  298.95
  5047.4  299.40  5061.4  301.39  5088.4  304.46  5174.7  314.23  5188.8  314.91
#Mann=10,-1,0
  4529.5     0.1       0  4689.3    0.16       0  4748.2     0.1       0
  4797.8    0.05       0  4906.3    0.08       0  4970.9    0.07       0
  4976.9    0.08       0  4982.2    0.16       0  5061.4    0.05       0
  5088.4    0.16       0
Bank Sta=4970.9,4976.9
Exp/Cntr=0.3,0.1

Type RM Length L Ch R = 1,3904,470,470,470
BEGIN DESCRIPTION:
UNT 071 IN BOCR 6.0
END DESCRIPTION:
XS GIS Cut Line= 3
      3769699.62     10573310.19      3769299.61     10573260.19
      3769099.64     10573360.18
#Sta/Elev= 30
  4603.6  322.97  4633.8  318.80  4646.4  318.01  4654.0  316.43  4704.4  311.24
  4722.0  308.37  4744.7  302.32  4764.9  300.03  4829.7  297.46  4855.6  297.44
  4875.7  295.66  4895.9  295.25  4902.2  296.18  4926.1  297.78  4968.9  298.13
  4986.6  297.48  5012.1  292.42  5014.9  291.92  5018.1  292.42  5029.1  295.08
  5037.5  295.40  5043.1  296.61  5073.8  297.01  5096.2  299.01  5132.5  305.48
  5163.2  308.02  5171.6  309.45  5177.2  309.38  5194.0  313.40  5230.3  317.83
#Mann=5,-1,0
  4603.6     0.1       0  4829.7    0.05       0  4902.2    0.16       0
  5012.1    0.07       0  5018.1    0.16       0
Bank Sta=5012.1,5018.1
Exp/Cntr=0.3,0.1

Type RM Length L Ch R = 1,3434,401,401,401
BEGIN DESCRIPTION:
UNT 071 IN BOCR 5.0
END DESCRIPTION:
XS GIS Cut Line= 3
      3769749.65     10572910.19      3769449.61     10572910.19
      3769149.58     10572810.18
#Sta/Elev= 30
  4740.4  325.04  4770.4  321.11  4780.4  318.22  4790.4  316.38  4800.4  313.06
  4810.4  311.64  4820.4  309.00  4860.4  302.62  4867.9  302.08  4910.4  297.47
  4920.4  294.84  4940.4  293.48  4950.4  295.63  4960.4  294.88  4980.4  296.54
  4987.4  290.86  4990.2  290.36  4993.4  290.86  5010.4  295.97  5014.0  296.18
  5072.1  295.15  5082.6  295.75  5093.1  294.97  5135.3  296.93  5145.9  298.57
  5177.5  299.94  5230.2  304.16  5282.9  308.97  5325.0  314.33  5356.7  316.51
#Mann=5,-1,0
  4740.4    0.16       0  4867.9    0.05       0  4987.4    0.04       0
  4993.4    0.05       0  5014.0    0.16       0
Bank Sta=4987.4,4993.4
Exp/Cntr=0.3,0.1

Type RM Length L Ch R = 1,3033,430,430,430
BEGIN DESCRIPTION:
UNT 071 IN BOCR 4.0
END DESCRIPTION:
XS GIS Cut Line= 3
      3769799.60     10572760.18      3769599.61     10572560.19
      3769199.65     10572460.20
#Sta/Elev= 30
  4702.6  326.74  4716.7  324.96  4730.9  321.62  4745.0  319.96  4773.3  312.31
  4787.4  310.59  4812.1  305.93  4844.0  300.08  4886.4  294.01  4914.7  293.37
  4928.9  295.10  4949.7  294.07  4988.0  294.57  4992.7  291.63  4995.5  291.13
  4998.7  291.63  5003.5  293.73  5008.6  292.68  5016.4  294.70  5057.6  292.50
  5109.1  293.57  5160.7  298.40  5201.9  300.38  5222.5  303.02  5274.0  306.79
  5284.4  308.70  5315.3  310.77  5374.6  317.22  5379.7  315.50  5397.7  318.23
#Mann=5,-1,0
  4702.6    0.16       0  4812.1    0.05       0  4949.7    0.16       0
  4992.7    0.07       0  4998.7    0.16       0
Bank Sta=4992.7,4998.7
Exp/Cntr=0.3,0.1

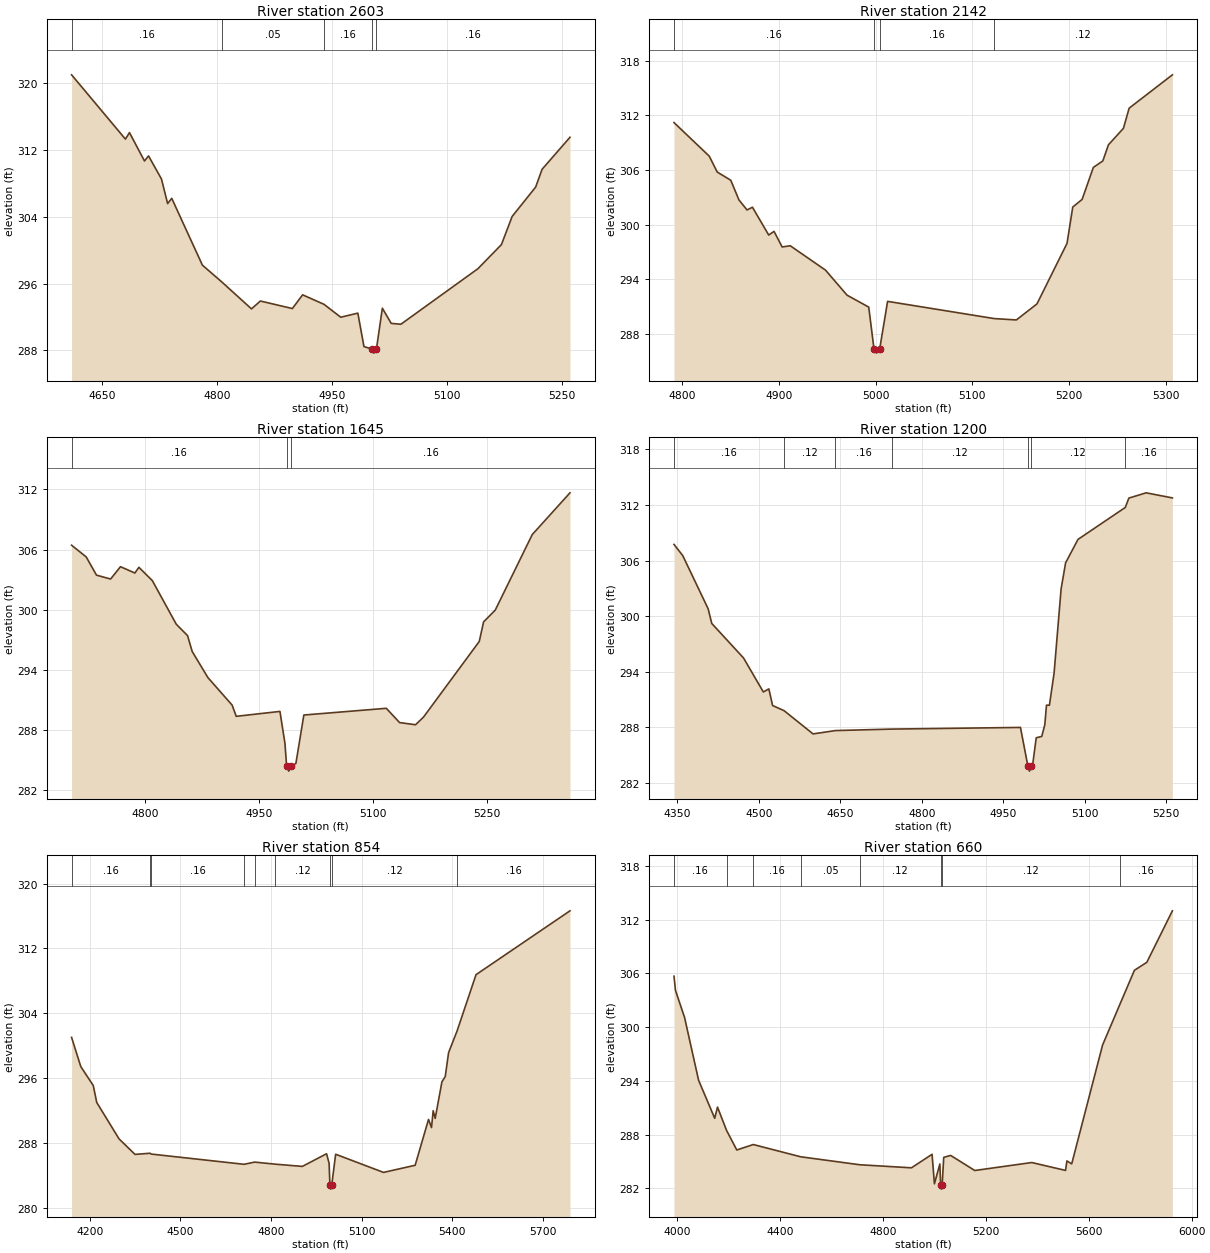
Type RM Length L Ch R = 1,2603,461,461,461
BEGIN DESCRIPTION:
UNT 071 IN BOCR 3.0
END DESCRIPTION:
XS GIS Cut Line= 3
      3769949.59     10572610.15      3769799.61     10572210.19
      3769599.58     10572110.17
#Sta/Elev= 30
  4610.1  321.00  4680.4  313.30  4685.7  314.08  4705.3  310.68  4710.6  311.29
  4727.5  308.52  4735.5  305.58  4740.9  306.21  4780.9  298.21  4806.3  296.19
  4845.0  292.97  4856.6  293.91  4898.4  293.01  4911.8  294.65  4939.6  293.52
  4961.6  291.97  4983.9  292.46  4991.9  288.45  5002.2  288.17  5005.0  287.67
  5008.2  288.17  5015.9  293.05  5027.5  291.23  5040.1  291.13  5140.7  297.78
  5171.4  300.67  5185.4  304.04  5216.1  307.56  5224.5  309.69  5260.9  313.52
#Mann=5,-1,0
  4610.1    0.16       0  4806.3    0.05       0  4939.6    0.16       0
  5002.2    0.07       0  5008.2    0.16       0
Bank Sta=5002.2,5008.2
Exp/Cntr=0.3,0.1

Type RM Length L Ch R = 1,2142,497,497,497
BEGIN DESCRIPTION:
UNT 071 IN BOCR 2.0
END DESCRIPTION:
XS GIS Cut Line= 3
      3770299.62     10572260.21      3770199.61     10572060.19
      3770049.60     10571810.17
#Sta/Elev= 30
  4791.5  311.22  4827.9  307.54  4836.2  305.79  4850.2  304.89  4858.6  302.74
  4867.0  301.63  4872.6  301.93  4889.4  298.88  4894.9  299.28  4903.3  297.57
  4911.7  297.70  4948.1  295.03  4970.4  292.28  4992.8  290.97  4998.2  286.42
  5000.9  285.92  5004.2  286.42  5012.3  291.60  5122.6  289.71  5145.4  289.56
  5166.7  291.32  5197.8  297.97  5203.7  301.95  5213.4  302.79  5225.0  306.30
  5234.8  307.01  5240.6  308.78  5256.1  310.59  5262.0  312.80  5306.7  316.46
#Mann=4,-1,0
  4791.5    0.16       0  4998.2    0.07       0  5004.2    0.16       0
  5122.6    0.12       0
Bank Sta=4998.2,5004.2
Exp/Cntr=0.3,0.1

Type RM Length L Ch R = 1,1645,445,445,445
BEGIN DESCRIPTION:
Mapping XS 50546cf9
END DESCRIPTION:
XS GIS Cut Line= 2
      3770591.21     10572211.45      3770389.83     10571586.49
#Sta/Elev= 30
  4702.7  306.44  4722.0  305.27  4735.5  303.46  4754.1  303.07  4767.1  304.30
  4786.1  303.67  4791.4  304.24  4809.1  302.91  4840.6  298.57  4855.5  297.43
  4861.6  295.85  4882.3  293.25  4914.2  290.51  4919.6  289.39  4977.2  289.88
  4983.8  286.70  4986.0  284.43  4988.8  283.93  4992.0  284.43  4998.2  284.69
  5008.7  289.52  5117.3  290.19  5134.8  288.77  5155.8  288.55  5166.3  289.31
  5239.8  296.85  5245.5  298.80  5260.9  299.98  5309.6  307.50  5359.3  311.66
#Mann=3,-1,0
  4702.7    0.16       0  4986.0    0.07       0  4992.0    0.16       0
Bank Sta=4986,4992
Exp/Cntr=0.3,0.1

Type RM Length L Ch R = 1,1200,346,346,346
BEGIN DESCRIPTION:
Mapping XS 41ec4b2c
END DESCRIPTION:
XS GIS Cut Line= 4
      3770661.89     10572191.97      3770755.76     10571674.87
      3770610.84     10571602.41      3770394.01     10571526.84
#Sta/Elev= 30
  4344.0  307.74  4360.1  306.53  4406.8  300.79  4413.5  299.20  4472.0  295.47
  4508.4  291.80  4518.6  292.13  4525.4  290.34  4546.6  289.78  4599.9  287.27
  4641.2  287.63  4744.6  287.79  4981.6  287.97  4995.4  283.75  4998.2  283.25
  5001.4  283.75  5004.0  283.91  5010.6  286.85  5020.8  287.00  5026.4  288.26
  5029.5  290.37  5034.9  290.37  5043.5  293.85  5056.4  302.93  5064.7  305.75
  5087.5  308.28  5174.5  311.73  5181.1  312.74  5212.9  313.31  5261.2  312.76
#Mann=7,-1,0
  4344.0    0.16       0  4546.6    0.12       0  4641.2    0.16       0
  4744.6    0.12       0  4995.4    0.07       0  5001.4    0.12       0
  5174.5    0.16       0
Bank Sta=4995.4,5001.4
Exp/Cntr=0.3,0.1

Type RM Length L Ch R = 1,854,194,194,194
BEGIN DESCRIPTION:
UNT 071 IN BOCR 1.0
END DESCRIPTION:
XS GIS Cut Line= 4
      3770730.10     10572149.02      3770966.22     10571454.55
      3770730.11     10571322.60      3770146.77     10571600.38
#Sta/Elev= 30
  4139.6  301.04  4170.1  297.44  4211.4  295.11  4222.9  293.02  4296.8  288.53
  4349.6  286.62  4399.4  286.76  4403.7  286.66  4710.5  285.40  4745.7  285.67
  4812.7  285.42  4903.6  285.14  4983.8  286.70  4992.2  285.52  4994.9  282.84
  4997.6  282.34  5000.9  282.84  5013.9  286.64  5172.4  284.40  5277.1  285.28
  5321.4  290.93  5331.3  289.93  5336.8  292.00  5343.5  291.06  5365.7  295.56
  5376.7  296.21  5387.8  299.16  5416.1  301.85  5478.6  308.77  5789.7  316.64
#Mann=9,-1,0
  4139.6    0.16       0  4399.4    0.12       0  4403.7    0.16       0
  4710.5    0.12       0  4745.7    0.05       0  4812.7    0.12       0
  4994.9    0.07       0  5000.9    0.12       0  5416.1    0.16       0
Bank Sta=4994.9,5000.9
Exp/Cntr=0.3,0.1

Type RM Length L Ch R = 1,660,266,266,266
BEGIN DESCRIPTION:
Mapping XS dc683933
END DESCRIPTION:
XS GIS Cut Line= 4
      3770741.47     10572187.84      3771074.80     10571326.73
      3770859.52     10571186.10      3770158.13     10571470.83
#Sta/Elev= 30
  3987.6  305.68  3993.4  304.09  4028.7  301.07  4083.2  294.06  4145.9  289.81
  4156.7  291.06  4192.1  288.45  4231.7  286.27  4295.8  286.88  4480.3  285.51
  4710.3  284.62  4910.7  284.28  4990.9  285.79  5000.0  282.49  5021.1  284.71
  5024.1  282.40  5026.8  281.90  5030.1  282.40  5036.2  285.45  5063.3  285.66
  5156.8  283.98  5378.4  284.87  5509.7  283.99  5515.0  285.05  5533.7  284.72
  5653.7  297.99  5719.6  302.44  5777.5  306.34  5825.7  307.23  5925.1  312.98
#Mann=8,-1,0
  3987.6    0.16       0  4192.1    0.12       0  4295.8    0.16       0
  4480.3    0.05       0  4710.3    0.12       0  5024.1    0.07       0
  5030.1    0.12       0  5719.6    0.16       0
Bank Sta=5024.1,5030.1
Exp/Cntr=0.3,0.1

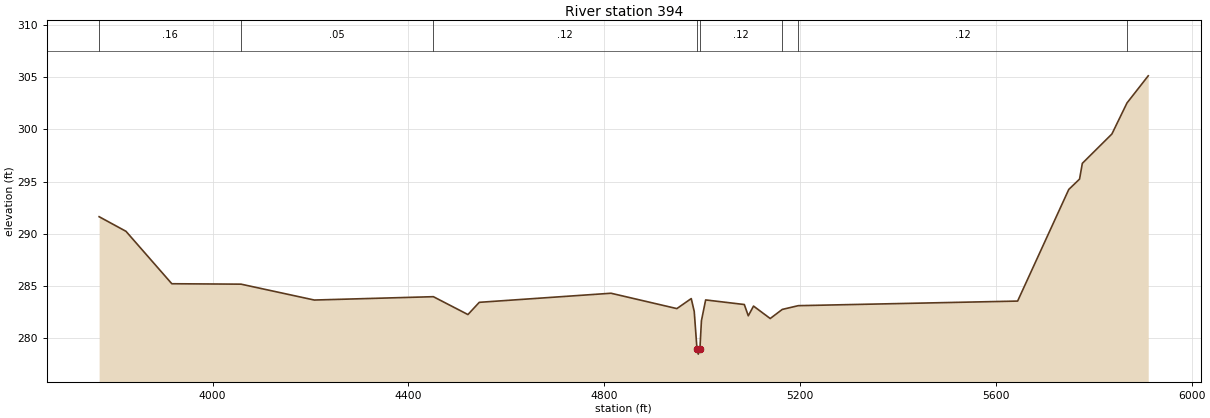
Type RM Length L Ch R = 1,394,0,0,0
BEGIN DESCRIPTION:
Mapping XS f2889a09
END DESCRIPTION:
XS GIS Cut Line= 5
      3771149.10     10572201.29      3771227.23     10571448.67
      3771089.21     10571102.31      3770938.17     10570992.94
      3770206.36     10571378.37
#Sta/Elev= 30
  3768.2  291.64  3823.1  290.24  3916.7  285.22  4058.1  285.18  4207.8  283.66
  4451.0  283.98  4521.6  282.27  4544.8  283.44  4813.9  284.31  4948.4  282.84
  4977.8  283.80  4983.9  282.56  4989.5  278.98  4992.2  278.48  4995.5  278.98
  4998.6  281.68  5007.2  283.67  5086.2  283.23  5094.3  282.15  5105.0  283.08
  5139.1  281.89  5163.7  282.76  5196.4  283.12  5644.5  283.56  5749.0  294.25
  5771.0  295.24  5776.7  296.75  5837.1  299.56  5867.9  302.53  5911.3  305.13
#Mann=8,-1,0
  3768.2    0.16       0  4058.1    0.05       0  4451.0    0.12       0
  4989.5    0.07       0  4995.5    0.12       0  5163.7    0.16       0
  5196.4    0.12       0  5867.9    0.16       0
Bank Sta=4989.5,4995.5
Exp/Cntr=0.3,0.1

Chan Stop Cuts=-1