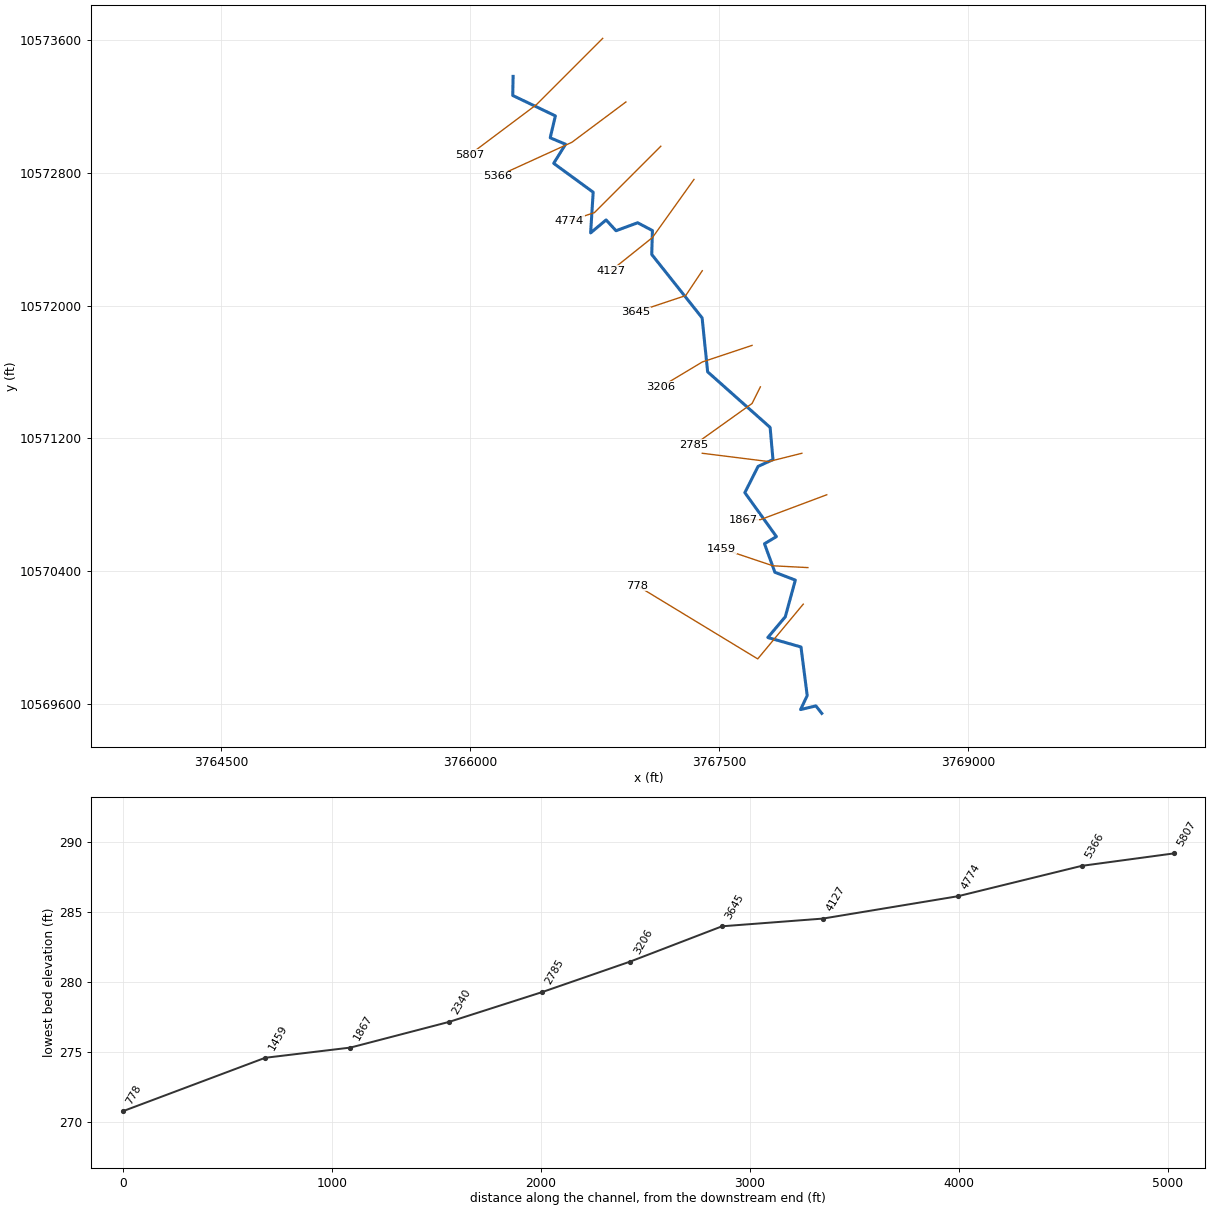
--- UNT 072 IN BOCR.prj (project) ---

Proj Title=UNT 072 IN BOCR Base Level Engineering
Current Plan=p01
Default Exp/Contr=0.3,0.1
English Units
Geom File=g01
Flow File=f01
Plan File=p01
Y Axis Title=Elevation
X Axis Title(PF)=Main Channel Distance
X Axis Title(XS)=Station
BEGIN DESCRIPTION:
UNT 072 IN BOCR
END DESCRIPTION:
DSS Export Rating Curves= 0
DSS Export Rating Curve Sorted= 0
DSS Export Volume Flow Curves= 0
DXF OffsetX= 0
DXF OffsetY= 0
DXF ScaleX= 1
DXF ScaleY= 10

--- UNT 072 IN BOCR.p01 (plan) ---

Plan Title=Multiple Run
Short Identifier=Multiple
Geom File=g01
Flow File=f01
Subcritical Flow
K Sum by GR= 0
Std Step Tol= 0.01
Critical Tol= 0.01
Num of Std Step Trials= 20
Max Error Tol= 0.3
Flow Tol Ratio= 0.001
Split Flow NTrial= 30
Split Flow Tol= 0.02
Split Flow Ratio= 0.02
Log Output Level= 0
Friction Slope Method= 1
Unsteady Friction Slope Method= 2
Unsteady Bridges Friction Slope Method= 1
Parabolic Critical Depth
Global Vel Dist=  1 , 1 , 1
Global Log Level= 0
CheckData=True
Encroach Param= -1, 0, 0, 0
BEGIN DESCRIPTION:
Multiple Run
END DESCRIPTION:

--- UNT 072 IN BOCR.f01 (steady flow) ---

Flow Title=Multiple
Program Version=4.10
Number of Profiles= 7
Profile Names=10-year,25-year,50-year,1pct_min,100-year,1pct_plu,500-year
River Rch & RM=UNT 072 IN BOCR,Reach-1         ,5807
     658     895    1090     977    1321    1786    1945
Boundary for River Rch & Prof#=UNT 072 IN BOCR,Reach-1         , 1
Up Type= 0
Dn Type= 3
Dn Slope=0.005
Boundary for River Rch & Prof#=UNT 072 IN BOCR,Reach-1         , 2
Up Type= 0
Dn Type= 3
Dn Slope=0.005
Boundary for River Rch & Prof#=UNT 072 IN BOCR,Reach-1         , 3
Up Type= 0
Dn Type= 3
Dn Slope=0.005
Boundary for River Rch & Prof#=UNT 072 IN BOCR,Reach-1         , 4
Up Type= 0
Dn Type= 3
Dn Slope=0.005
Boundary for River Rch & Prof#=UNT 072 IN BOCR,Reach-1         , 5
Up Type= 0
Dn Type= 3
Dn Slope=0.005
Boundary for River Rch & Prof#=UNT 072 IN BOCR,Reach-1         , 6
Up Type= 0
Dn Type= 3
Dn Slope=0.005
Boundary for River Rch & Prof#=UNT 072 IN BOCR,Reach-1         , 7
Up Type= 0
Dn Type= 3
Dn Slope=0.005
DSS Import GetInterval= 0
DSS Import GetPeak= 0
DSS Import FillOption= 0

--- UNT 072 IN BOCR.g01 (geometry) ---

Geom Title=Existing Conditions

River Reach=UNT 072 IN BOCR,Reach-1
Reach XY= 30
      3766259.75     10573381.00      3766257.50     10573266.00
      3766514.50     10573143.00      3766483.25     10573011.00
      3766575.75     10572972.00      3766504.25     10572857.00
      3766742.25     10572683.00      3766726.75     10572438.00
      3766820.00     10572516.00      3766880.00     10572451.00
      3767010.00     10572499.00      3767099.25     10572452.00
      3767095.00     10572308.00      3767398.50     10571926.00
      3767431.75     10571601.00      3767808.25     10571266.00
      3767825.50     10571072.00      3767735.75     10571031.00
      3767656.00     10570873.00      3767846.25     10570608.00
      3767774.25     10570565.00      3767837.25     10570393.00
      3767960.25     10570346.00      3767899.75     10570125.00
      3767794.50     10570000.00      3767994.25     10569943.00
      3768031.75     10569650.00      3767991.75     10569566.00
      3768084.00     10569588.00      3768119.50     10569543.00

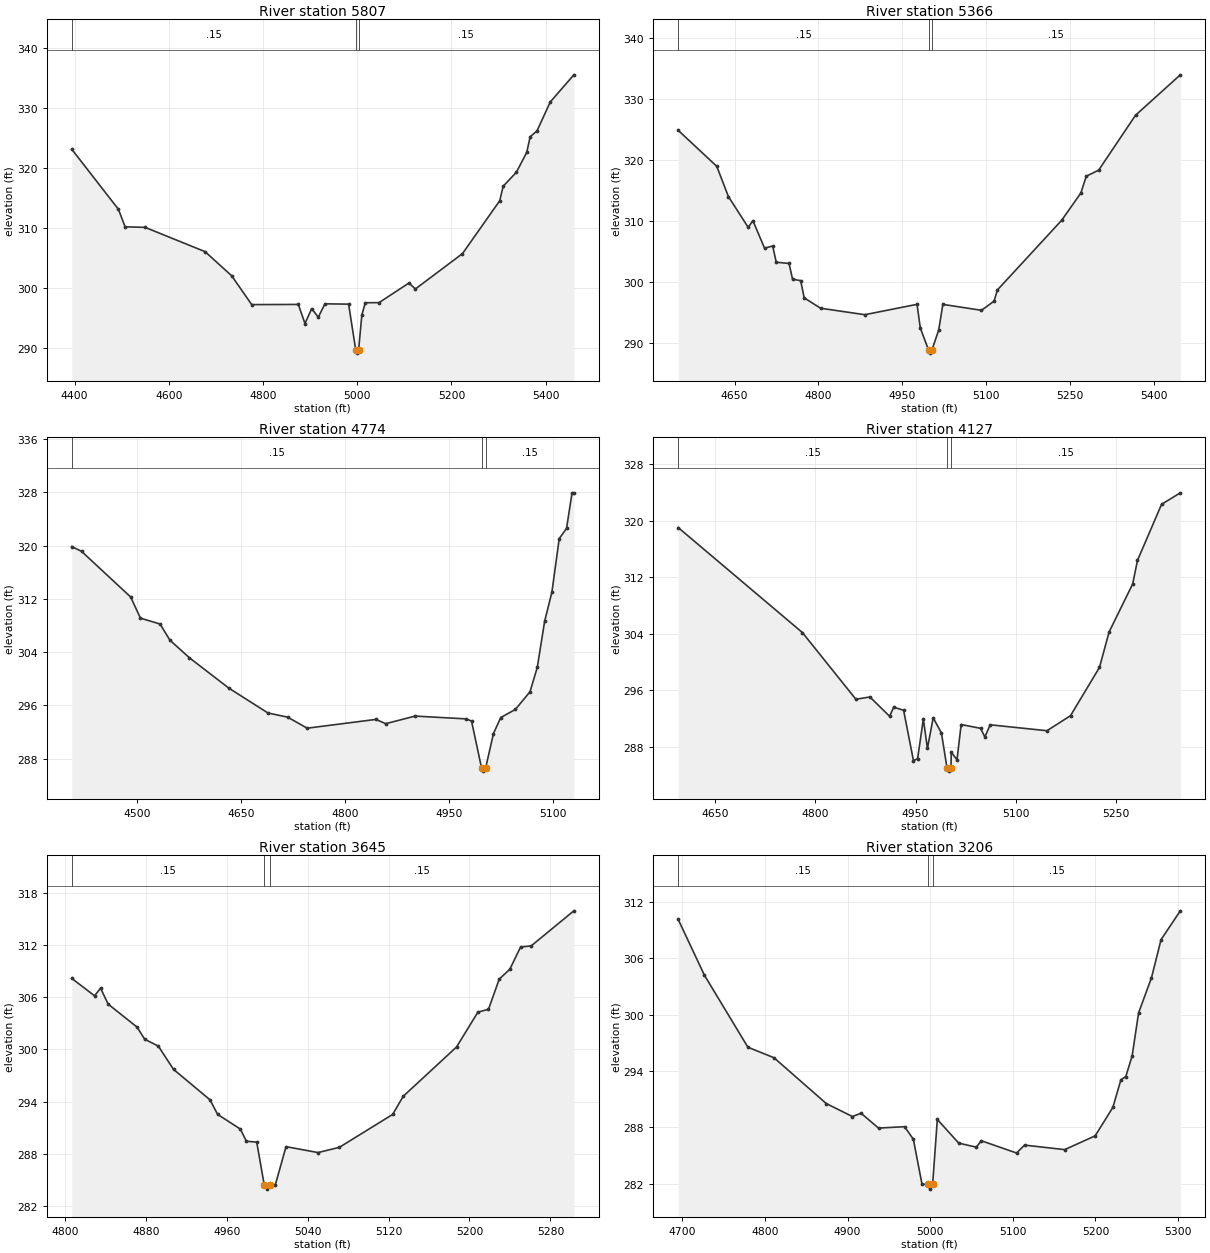
Type RM Length L Ch R = 1,5807,441,441,441
BEGIN DESCRIPTION:
UNT 072 IN BOCR 11.0
END DESCRIPTION:
XS GIS Cut Line= 3
      3766799.63     10573610.21      3766399.61     10573210.19
      3765999.63     10572910.20
#Sta/Elev= 30
  4394.2  323.08  4493.2  313.10  4507.4  310.18  4549.8  310.09  4677.1  306.05
  4733.6  302.04  4776.1  297.24  4875.1  297.27  4889.2  294.09  4903.4  296.57
  4917.5  295.15  4931.6  297.37  4981.8  297.32  4997.0  289.67  4999.8  289.17
  5003.0  289.67  5009.9  295.50  5017.2  297.55  5046.4  297.57  5109.9  300.83
  5123.5  299.84  5223.5  305.72  5302.6  314.52  5309.9  316.93  5338.0  319.26
  5359.9  322.56  5367.2  325.16  5381.8  326.15  5409.9  330.95  5459.9  335.46
#Mann=3,-1,0
  4394.2    0.15       0  4997.0    0.05       0  5003.0    0.15       0
Bank Sta=4997,5003
Exp/Cntr=0.3,0.1

Type RM Length L Ch R = 1,5366,592,592,592
BEGIN DESCRIPTION:
UNT 072 IN BOCR 10.0
END DESCRIPTION:
XS GIS Cut Line= 3
      3766939.30     10573226.74      3766613.76     10572983.67
      3766166.68     10572779.66
#Sta/Elev= 30
  4549.4  324.80  4618.3  318.90  4639.1  313.95  4674.5  308.89  4682.9  310.00
  4703.7  305.49  4718.3  305.84  4724.6  303.18  4747.5  302.98  4753.8  300.40
  4768.3  300.16  4774.6  297.35  4803.8  295.64  4883.0  294.58  4976.4  296.28
  4982.2  292.41  4997.0  288.78  4999.8  288.28  5003.0  288.78  5015.2  292.10
  5022.5  296.27  5091.6  295.30  5114.1  296.80  5120.1  298.64  5235.0  310.06
  5269.3  314.53  5279.0  317.29  5301.0  318.26  5367.0  327.27  5447.1  333.90
#Mann=3,-1,0
  4549.4    0.15       0  4997.0    0.05       0  5003.0    0.15       0
Bank Sta=4997,5003
Exp/Cntr=0.3,0.1

Type RM Length L Ch R = 1,4774,647,647,647
BEGIN DESCRIPTION:
UNT 072 IN BOCR 9.0
END DESCRIPTION:
XS GIS Cut Line= 3
      3767149.63     10572960.21      3766749.61     10572560.19
      3766599.64     10572510.20
#Sta/Elev= 30
  4406.3  319.85  4420.5  319.12  4491.2  312.27  4505.3  309.09  4533.6  308.21
  4547.8  305.78  4576.0  303.13  4632.6  298.59  4689.2  294.84  4717.5  294.22
  4745.7  292.56  4844.7  293.88  4858.9  293.24  4901.3  294.38  4974.6  293.96
  4982.6  293.64  4997.0  286.61  4999.8  286.11  5003.0  286.61  5014.2  291.75
  5024.7  294.16  5045.8  295.38  5066.9  298.03  5077.4  301.70  5088.0  308.63
  5098.5  313.02  5109.0  321.04  5119.6  322.58  5127.5  327.92  5130.1  327.92
#Mann=3,-1,0
  4406.3    0.15       0  4997.0    0.05       0  5003.0    0.15       0
Bank Sta=4997,5003
Exp/Cntr=0.3,0.1

Type RM Length L Ch R = 1,4127,482,482,482
BEGIN DESCRIPTION:
UNT 072 IN BOCR 8.0
END DESCRIPTION:
XS GIS Cut Line= 3
      3767349.64     10572760.23      3767099.61     10572410.19
      3766849.62     10572210.20
#Sta/Elev= 30
  4595.4  319.05  4781.0  304.16  4860.9  294.70  4881.8  295.03  4911.3  292.29
  4917.4  293.58  4932.2  293.14  4946.9  286.00  4953.1  286.27  4961.7  291.89
  4967.8  287.74  4976.4  292.07  4988.7  289.93  4997.0  285.01  4999.8  284.51
  5003.0  285.01  5003.4  287.18  5012.0  286.13  5018.2  291.12  5047.2  290.58
  5053.6  289.36  5061.6  291.08  5146.4  290.24  5181.6  292.37  5224.9  299.22
  5239.3  304.25  5274.5  311.05  5281.7  314.40  5317.7  322.35  5345.7  323.98
#Mann=3,-1,0
  4595.4    0.15       0  4997.0    0.05       0  5003.0    0.15       0
Bank Sta=4997,5003
Exp/Cntr=0.3,0.1

Type RM Length L Ch R = 1,3645,439,439,439
BEGIN DESCRIPTION:
UNT 072 IN BOCR 7.0
END DESCRIPTION:
XS GIS Cut Line= 3
      3767399.59     10572210.15      3767299.61     10572060.19
      3766999.58     10571960.18
#Sta/Elev= 30
  4806.7  308.17  4829.2  306.17  4835.2  307.04  4842.7  305.21  4871.3  302.57
  4878.8  301.18  4892.3  300.39  4907.3  297.72  4943.4  294.22  4950.9  292.55
  4973.4  290.86  4979.4  289.46  4989.6  289.36  4997.0  284.46  4999.8  283.96
  5003.0  284.46  5008.0  284.46  5018.6  288.84  5050.2  288.16  5071.3  288.76
  5124.0  292.54  5134.5  294.63  5187.2  300.29  5208.3  304.29  5218.8  304.62
  5229.4  308.08  5239.9  309.22  5250.5  311.77  5261.0  311.90  5303.2  315.93
#Mann=3,-1,0
  4806.7    0.15       0  4997.0    0.05       0  5003.0    0.15       0
Bank Sta=4997,5003
Exp/Cntr=0.3,0.1

Type RM Length L Ch R = 1,3206,421,421,421
BEGIN DESCRIPTION:
UNT 072 IN BOCR 6.0
END DESCRIPTION:
XS GIS Cut Line= 3
      3767699.58     10571760.18      3767399.61     10571660.19
      3767149.65     10571510.21
#Sta/Elev= 30
  4695.1  310.11  4726.7  304.20  4779.4  296.53  4811.0  295.41  4874.3  290.54
  4905.9  289.16  4916.4  289.51  4937.5  287.93  4969.1  288.08  4979.7  286.74
  4990.2  281.94  4997.0  281.94  4999.8  281.44  5003.0  281.94  5008.7  288.85
  5034.6  286.33  5056.0  285.90  5061.8  286.59  5104.6  285.28  5114.3  286.12
  5162.9  285.64  5199.8  287.11  5221.2  290.14  5230.9  293.07  5236.8  293.41
  5244.5  295.60  5252.3  300.18  5267.9  303.91  5279.5  307.97  5302.8  311.03
#Mann=3,-1,0
  4695.1    0.15       0  4997.0    0.05       0  5003.0    0.15       0
Bank Sta=4997,5003
Exp/Cntr=0.3,0.1

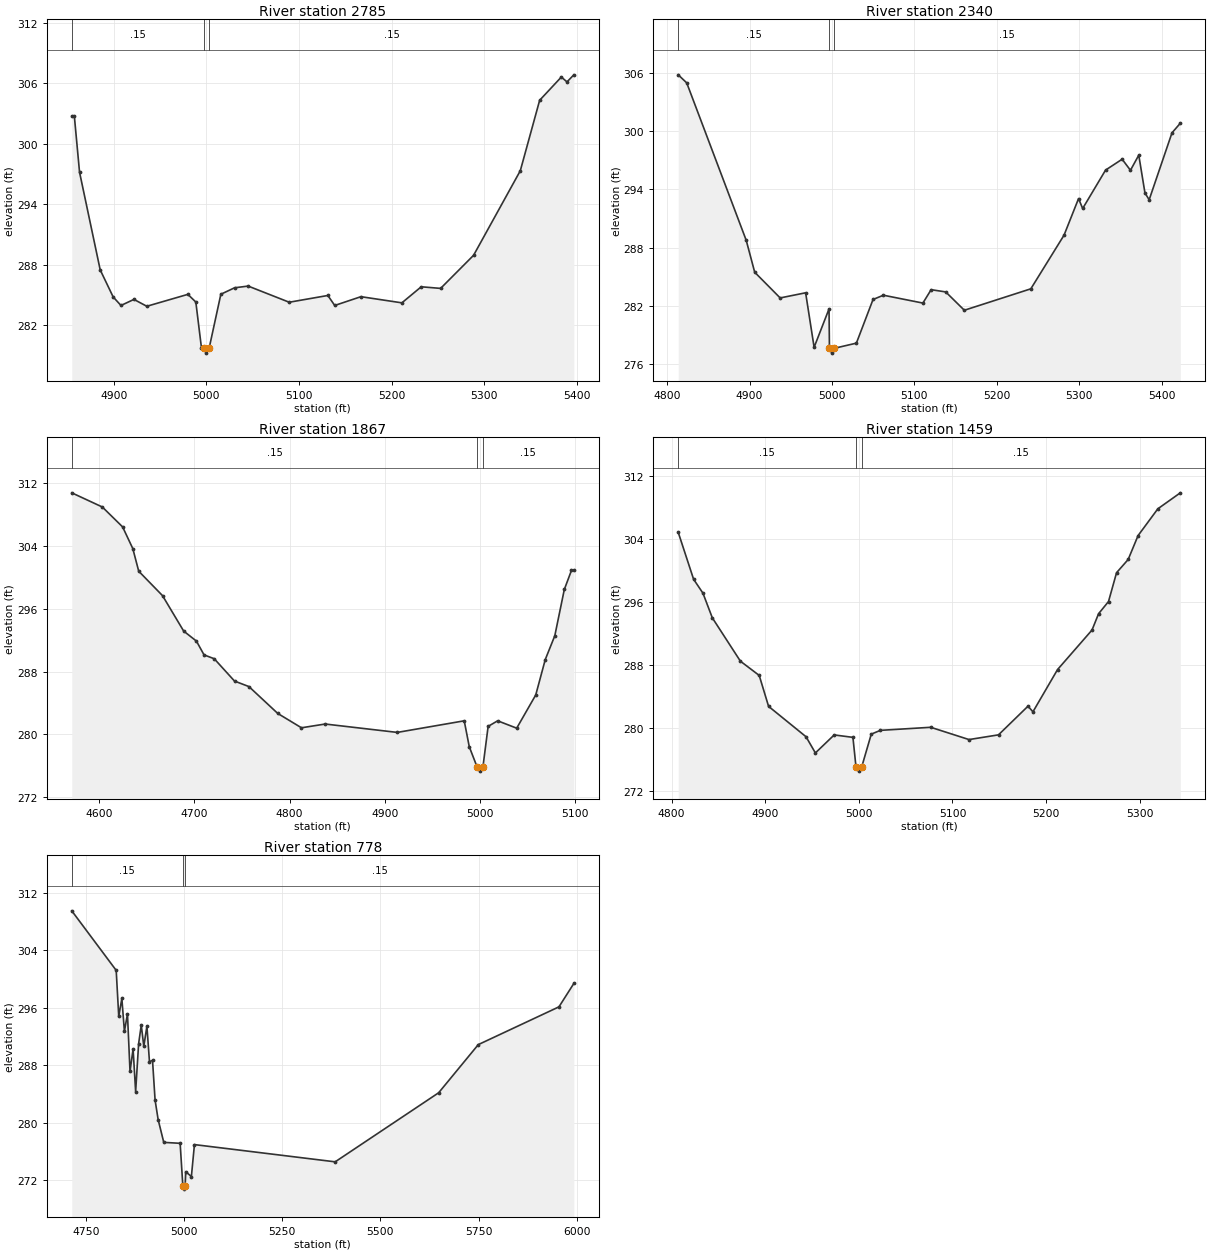
Type RM Length L Ch R = 1,2785,445,445,445
BEGIN DESCRIPTION:
UNT 072 IN BOCR 5.0
END DESCRIPTION:
XS GIS Cut Line= 3
      3767749.60     10571510.16      3767699.61     10571410.19
      3767349.60     10571160.18
#Sta/Elev= 30
  4854.7  302.71  4857.5  302.71  4863.1  297.17  4885.4  287.50  4899.4  284.82
  4907.8  283.98  4921.8  284.58  4935.7  283.90  4980.0  285.08  4988.6  284.32
  4994.7  279.76  4997.0  279.76  4999.8  279.26  5003.0  279.76  5015.6  285.09
  5030.4  285.73  5045.1  285.90  5089.4  284.30  5131.1  284.97  5138.5  283.98
  5166.8  284.85  5211.0  284.24  5231.9  285.83  5252.8  285.67  5288.4  288.95
  5338.8  297.32  5359.7  304.30  5383.1  306.60  5389.2  306.12  5396.6  306.82
#Mann=3,-1,0
  4854.7    0.15       0  4997.0    0.05       0  5003.0    0.15       0
Bank Sta=4997,5003
Exp/Cntr=0.3,0.1

Type RM Length L Ch R = 1,2340,473,473,473
BEGIN DESCRIPTION:
UNT 072 IN BOCR 4.0
END DESCRIPTION:
XS GIS Cut Line= 3
      3767999.61     10571110.19      3767799.61     10571060.19
      3767399.58     10571110.19
#Sta/Elev= 30
  4813.5  305.82  4823.8  304.99  4896.0  288.76  4906.3  285.47  4937.2  282.82
  4968.1  283.35  4978.4  277.73  4996.5  281.69  4997.0  277.63  4999.8  277.13
  5003.0  277.63  5029.7  278.16  5049.9  282.66  5062.5  283.10  5110.4  282.29
  5120.4  283.67  5138.1  283.44  5160.7  281.55  5241.4  283.76  5281.7  289.29
  5299.3  293.06  5304.3  292.04  5332.1  296.00  5352.2  297.12  5362.3  295.98
  5372.4  297.54  5379.9  293.64  5385.0  292.94  5412.7  299.84  5422.8  300.83
#Mann=3,-1,0
  4813.5    0.15       0  4997.0    0.05       0  5003.0    0.15       0
Bank Sta=4997,5003
Exp/Cntr=0.3,0.1

Type RM Length L Ch R = 1,1867,408,408,408
BEGIN DESCRIPTION:
UNT 072 IN BOCR 3.0
END DESCRIPTION:
XS GIS Cut Line= 3
      3768149.64     10570860.20      3767749.61     10570710.19
      3767649.64     10570710.19
#Sta/Elev= 30
  4571.3  310.80  4603.4  308.99  4624.7  306.45  4635.4  303.68  4641.6  300.80
  4666.6  297.68  4688.8  293.16  4702.2  291.88  4710.2  290.12  4720.9  289.63
  4742.2  286.78  4757.3  286.08  4787.6  282.65  4812.5  280.82  4837.4  281.30
  4913.1  280.23  4983.4  281.71  4988.7  278.40  4997.0  275.79  4999.8  275.29
  5003.0  275.79  5008.5  281.00  5018.5  281.71  5038.5  280.77  5058.5  285.01
  5068.5  289.53  5078.5  292.56  5088.5  298.47  5096.0  300.90  5098.5  300.90
#Mann=3,-1,0
  4571.3    0.15       0  4997.0    0.05       0  5003.0    0.15       0
Bank Sta=4997,5003
Exp/Cntr=0.3,0.1

Type RM Length L Ch R = 1,1459,681,681,681
BEGIN DESCRIPTION:
UNT 072 IN BOCR 2.0
END DESCRIPTION:
XS GIS Cut Line= 3
      3768035.95     10570421.34      3767825.44     10570432.19
      3767516.85     10570535.77
#Sta/Elev= 30
  4807.1  304.90  4823.5  298.94  4833.5  297.17  4843.5  294.04  4873.5  288.53
  4893.6  286.72  4903.6  282.79  4943.6  278.93  4953.6  276.87  4973.7  279.16
  4993.7  278.85  4997.0  275.06  4999.8  274.56  5003.0  275.06  5013.3  279.26
  5023.0  279.74  5076.8  280.13  5117.7  278.57  5149.2  279.17  5180.7  282.81
  5186.0  282.10  5212.3  287.47  5249.1  292.49  5256.1  294.56  5266.7  296.11
  5275.3  299.77  5287.7  301.45  5298.3  304.49  5319.4  307.89  5343.4  309.92
#Mann=3,-1,0
  4807.1    0.15       0  4997.0    0.05       0  5003.0    0.15       0
Bank Sta=4997,5003
Exp/Cntr=0.3,0.1

Type RM Length L Ch R = 1,778,0,0,0
BEGIN DESCRIPTION:
UNT 072 IN BOCR 1.0
END DESCRIPTION:
XS GIS Cut Line= 3
      3768007.88     10570201.06      3767733.58     10569871.21
      3767007.86     10570312.20
#Sta/Elev= 30
  4714.3  309.49  4827.4  301.20  4833.9  294.79  4841.8  297.29  4848.3  292.72
  4856.1  295.12  4862.6  287.12  4870.4  290.27  4876.9  284.32  4884.5  290.99
  4891.2  293.57  4897.7  290.63  4905.6  293.43  4912.1  288.49  4919.9  288.67
  4926.4  283.14  4934.2  280.42  4948.5  277.25  4990.2  277.12  4997.0  271.24
  4999.8  270.74  5003.0  271.24  5004.5  273.17  5018.8  272.49  5026.6  276.94
  5384.9  274.54  5648.4  284.16  5749.2  290.86  5954.6  296.12  5992.5  299.38
#Mann=3,-1,0
  4714.3    0.15       0  4997.0    0.05       0  5003.0    0.15       0
Bank Sta=4997,5003
Exp/Cntr=0.3,0.1

Chan Stop Cuts=-1