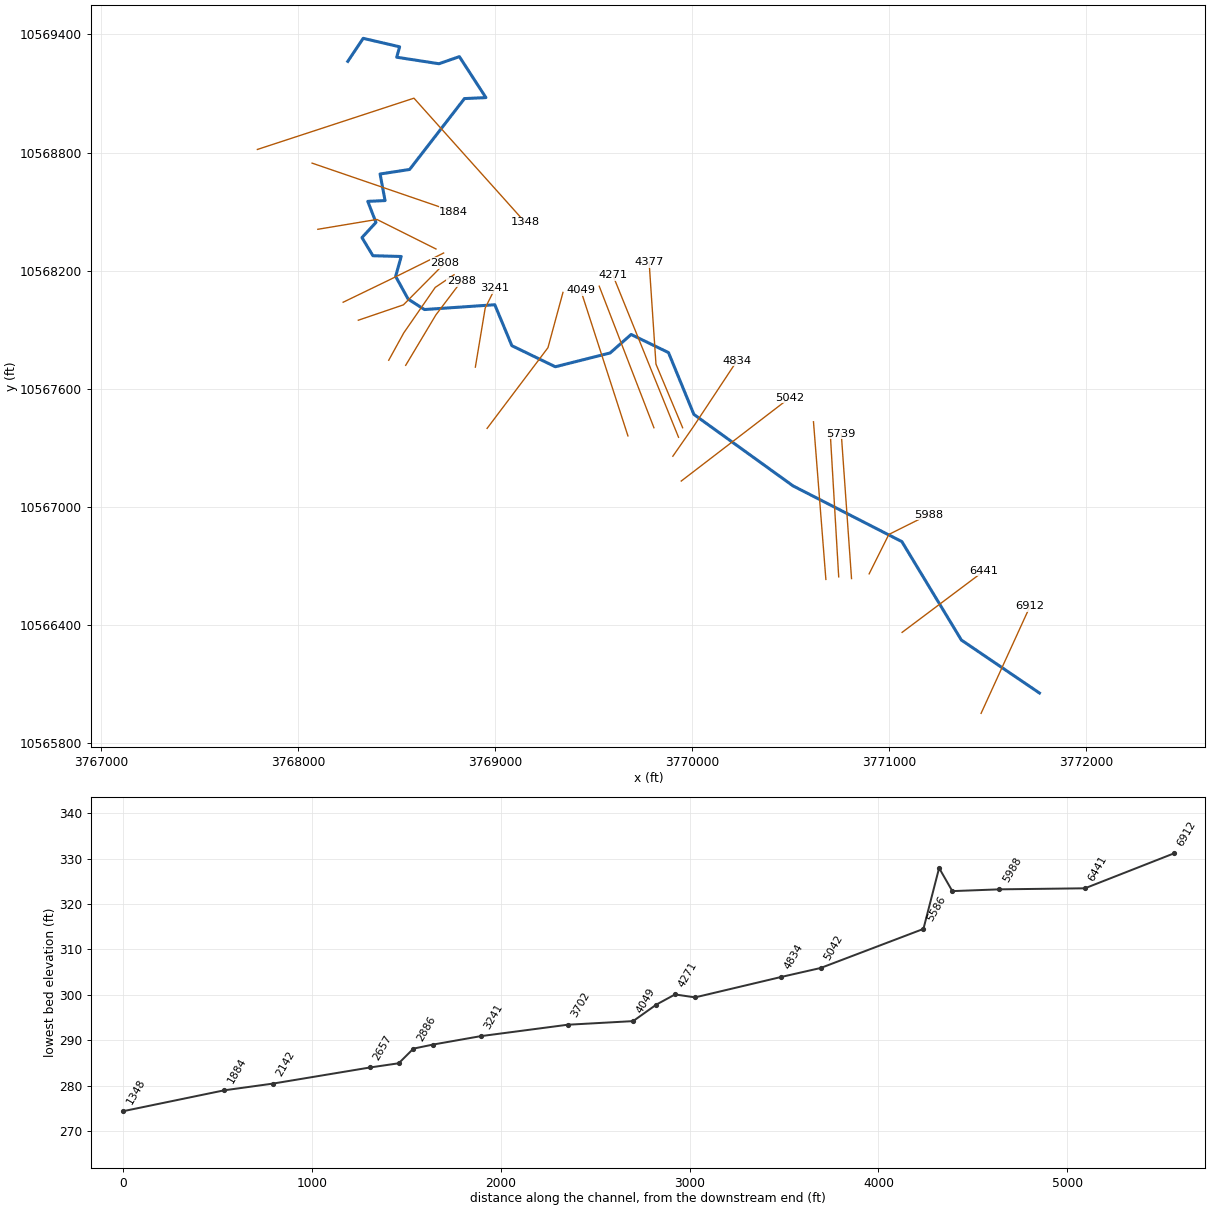
--- UNT 073 IN BOCR.prj (project) ---

Proj Title=UNT 073 IN BOCR Base Level Engineering
Current Plan=p01
Default Exp/Contr=0.3,0.1
English Units
Geom File=g01
Flow File=f01
Plan File=p01
BEGIN DESCRIPTION:
UNT 073 IN BOCR
END DESCRIPTION:

--- UNT 073 IN BOCR.p01 (plan) ---

Plan Title=Multiple Run
Short Identifier=Multiple
Geom File=g01
Flow File=f01
Subcritical Flow
K Sum by GR= 0
Std Step Tol= 0.01
Critical Tol= 0.01
Num of Std Step Trials= 20
Max Error Tol= 0.3
Flow Tol Ratio= 0.001
Split Flow NTrial= 30
Split Flow Tol= 0.02
Split Flow Ratio= 0.02
Log Output Level= 0
Friction Slope Method= 1
Unsteady Friction Slope Method= 2
Unsteady Bridges Friction Slope Method= 1
Parabolic Critical Depth
Global Vel Dist=  1 , 1 , 1
Global Log Level= 0
CheckData=True
Encroach Param= -1, 0, 0, 0
BEGIN DESCRIPTION:
Multiple Run
END DESCRIPTION:

--- UNT 073 IN BOCR.f01 (steady flow) ---

Flow Title=Multiple
Number of Profiles=7
Profile Names=10-year,25-year,50-year,1pct_min,100-year,1pct_plu,500-year
River Rch & RM= UNT 073 IN BOCR,Reach-1,6912
     324     424     504     442     598     809     842
Boundary for River Rch & Prof#=UNT 073 IN BOCR,Reach-1,1
Up Type=0
Dn Type=3
Dn Slope=0.005
Boundary for River Rch & Prof#=UNT 073 IN BOCR,Reach-1,2
Up Type=0
Dn Type=3
Dn Slope=0.005
Boundary for River Rch & Prof#=UNT 073 IN BOCR,Reach-1,3
Up Type=0
Dn Type=3
Dn Slope=0.005
Boundary for River Rch & Prof#=UNT 073 IN BOCR,Reach-1,4
Up Type=0
Dn Type=3
Dn Slope=0.005
Boundary for River Rch & Prof#=UNT 073 IN BOCR,Reach-1,5
Up Type=0
Dn Type=3
Dn Slope=0.005
Boundary for River Rch & Prof#=UNT 073 IN BOCR,Reach-1,6
Up Type=0
Dn Type=3
Dn Slope=0.005
Boundary for River Rch & Prof#=UNT 073 IN BOCR,Reach-1,7
Up Type=0
Dn Type=3
Dn Slope=0.005

--- UNT 073 IN BOCR.g01 (geometry) ---

Geom Title=Existing Conditions

River Reach=UNT 073 IN BOCR,Reach-1
Reach XY= 30
      3771764.50     10566055.00      3771368.00     10566324.00
      3771065.75     10566824.00      3770513.00     10567107.00
      3770009.50     10567470.00      3769880.50     10567784.00
      3769690.75     10567876.00      3769584.00     10567782.00
      3769305.75     10567712.00      3769085.00     10567819.00
      3768998.25     10568027.00      3768641.09     10568002.55
      3768558.00     10568056.00      3768494.75     10568171.00
      3768523.00     10568272.00      3768379.25     10568276.00
      3768323.75     10568368.00      3768394.75     10568445.00
      3768353.25     10568552.00      3768441.00     10568556.00
      3768415.75     10568691.00      3768565.75     10568714.00
      3768844.25     10569074.00      3768953.25     10569079.00
      3768818.50     10569287.00      3768714.75     10569251.00
      3768500.25     10569284.00      3768515.00     10569337.00
      3768330.00     10569380.00      3768251.75     10569263.00

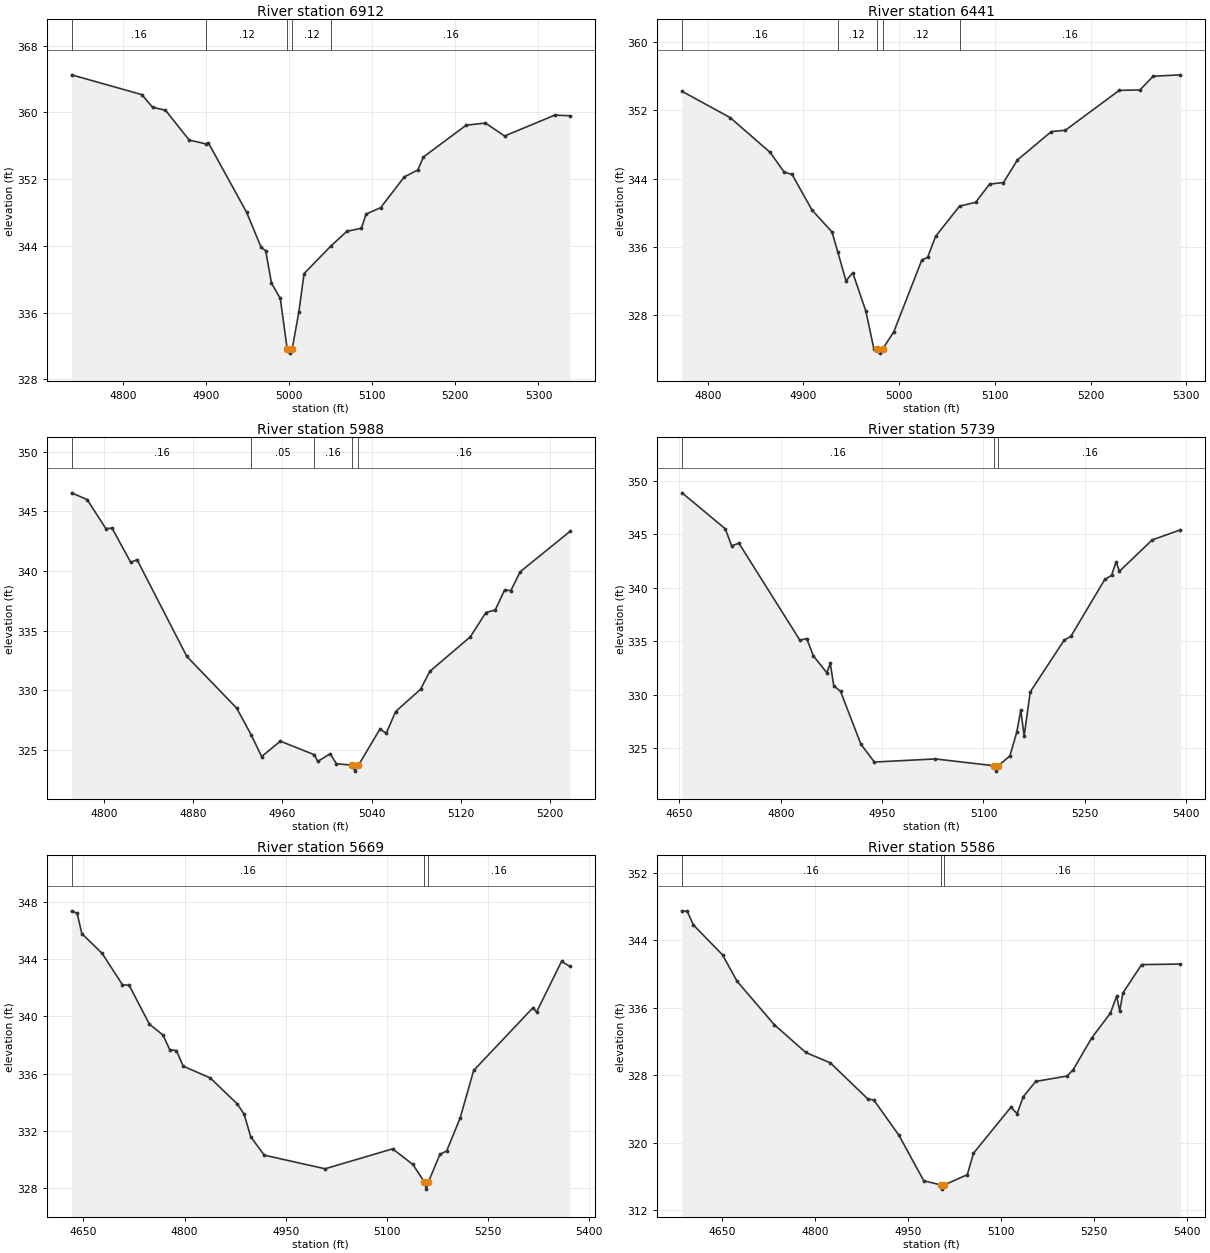
Type RM Length L Ch R = 1,6912,471,471,471
BEGIN DESCRIPTION:
UNT 073 IN BOCR 12.0
END DESCRIPTION:
XS GIS Cut Line= 2
      3771468.07     10565951.60      3771717.32     10566496.83
#Sta/Elev= 30
  4738.5  364.51  4822.9  362.14  4835.9  360.62  4851.4  360.27  4879.9  356.70
  4900.0  356.23  4903.0  356.36  4949.0  348.04  4966.5  343.83  4972.0  343.42
  4978.9  339.55  4989.5  337.71  4997.8  331.66  5000.6  331.16  5003.8  331.66
  5011.8  336.06  5018.1  340.69  5050.3  343.99  5069.6  345.76  5087.1  346.12
  5092.6  347.82  5110.2  348.59  5138.7  352.28  5154.8  353.10  5161.7  354.67
  5213.2  358.48  5236.3  358.73  5259.3  357.18  5319.7  359.68  5338.0  359.61
#Mann=5,-1,0
  4738.5    0.16       0  4900.0    0.12       0  4997.8    0.07       0
  5003.8    0.12       0  5050.3    0.16       0
Bank Sta=4997.8,5003.8
Exp/Cntr=0.3,0.1

Type RM Length L Ch R = 1,6441,453,453,453
BEGIN DESCRIPTION:
UNT 073 IN BOCR 11.0
END DESCRIPTION:
XS GIS Cut Line= 2
      3771066.99     10566363.02      3771483.47     10566675.38
#Sta/Elev= 30
  4773.2  354.25  4823.5  351.16  4865.2  347.07  4879.8  344.76  4888.1  344.48
  4908.9  340.30  4929.8  337.72  4935.8  335.39  4944.4  331.97  4951.5  332.92
  4965.2  328.40  4973.5  324.01  4976.8  323.97  4979.5  323.47  4982.8  323.97
  4994.4  325.99  5023.5  334.38  5029.8  334.76  5038.1  337.21  5063.0  340.75
  5079.8  341.20  5094.4  343.34  5108.9  343.53  5123.5  346.18  5158.9  349.52
  5173.5  349.67  5229.8  354.36  5251.5  354.42  5265.2  356.02  5293.8  356.19
#Mann=5,-1,0
  4773.2    0.16       0  4935.8    0.12       0  4976.8    0.07       0
  4982.8    0.12       0  5063.0    0.16       0
Bank Sta=4976.8,4982.8
Exp/Cntr=0.3,0.1

Type RM Length L Ch R = 1,5988,249,249,249
BEGIN DESCRIPTION:
UNT 073 IN BOCR 10.0
END DESCRIPTION:
XS GIS Cut Line= 3
      3770899.61     10566660.19      3770999.61     10566860.19
      3771199.60     10566960.18
#Sta/Elev= 30
  4770.8  346.56  4784.8  345.99  4801.5  343.57  4807.1  343.60  4823.9  340.73
  4829.5  340.96  4874.2  332.85  4918.9  328.52  4932.0  326.27  4941.3  324.46
  4958.1  325.75  4988.7  324.61  4991.6  324.05  5002.8  324.70  5008.4  323.86
  5022.2  323.74  5024.9  323.24  5028.2  323.74  5047.5  326.77  5053.1  326.41
  5061.5  328.23  5083.9  330.10  5092.2  331.60  5128.6  334.50  5142.5  336.53
  5150.9  336.74  5159.3  338.42  5164.9  338.37  5173.3  339.95  5218.0  343.33
#Mann=5,-1,0
  4770.8    0.16       0  4932.0    0.05       0  4988.7    0.16       0
  5022.2    0.07       0  5028.2    0.16       0
Bank Sta=5022.2,5028.2
Exp/Cntr=0.3,0.1

Type RM Length L Ch R = 1,5739,70,70,70
BEGIN DESCRIPTION:
UNT 073 IN BOCR 9.0
END DESCRIPTION:
XS GIS Cut Line= 2
      3770810.08     10566636.26      3770758.00     10567371.92
#Sta/Elev= 30
  4654.0  348.87  4718.1  345.50  4727.3  343.91  4738.1  344.16  4828.4  335.09
  4838.4  335.25  4848.4  333.62  4868.2  332.05  4873.3  332.93  4878.5  330.83
  4888.5  330.31  4918.6  325.37  4938.6  323.70  5028.9  323.99  5116.1  323.35
  5118.8  322.85  5122.1  323.35  5139.1  324.28  5149.2  326.48  5155.2  328.54
  5160.2  326.15  5169.2  330.26  5219.3  335.09  5229.4  335.46  5279.5  340.77
  5289.5  341.16  5296.2  342.41  5301.2  341.54  5349.7  344.47  5391.5  345.41
#Mann=3,-1,0
  4654.0    0.16       0  5116.1    0.07       0  5122.1    0.16       0
Bank Sta=5116.1,5122.1
Exp/Cntr=0.3,0.1

Type RM Length L Ch R = 1,5669,83,83,83
BEGIN DESCRIPTION:
Mapping XS c80528c2
END DESCRIPTION:
XS GIS Cut Line= 2
      3770744.97     10566644.98      3770701.57     10567382.81
#Sta/Elev= 30
  4632.5  347.36  4640.7  347.19  4647.7  345.77  4677.8  344.39  4707.8  342.21
  4717.9  342.16  4747.9  339.45  4767.9  338.70  4778.0  337.68  4788.0  337.60
  4798.0  336.52  4838.1  335.70  4878.1  333.89  4888.1  333.19  4898.2  331.59
  4918.2  330.31  5008.4  329.36  5108.5  330.75  5138.6  329.66  5155.6  328.44
  5158.4  327.94  5161.6  328.44  5178.6  330.36  5188.7  330.61  5208.7  332.91
  5228.7  336.22  5316.9  340.61  5321.9  340.29  5359.0  343.83  5371.6  343.48
#Mann=3,-1,0
  4632.5    0.16       0  5155.6    0.07       0  5161.6    0.16       0
Bank Sta=5155.6,5161.6
Exp/Cntr=0.3,0.1

Type RM Length L Ch R = 1,5586,544,544,544
BEGIN DESCRIPTION:
Mapping XS 355e3890
END DESCRIPTION:
XS GIS Cut Line= 2
      3770679.87     10566631.90      3770616.93     10567432.73
#Sta/Elev= 30
  4585.7  347.47  4594.0  347.41  4604.1  345.79  4651.0  342.25  4674.3  339.14
  4734.5  333.98  4785.1  330.70  4824.7  329.47  4884.9  325.21  4894.9  325.06
  4935.1  320.91  4975.2  315.52  5002.3  315.02  5005.0  314.52  5008.3  315.02
  5045.4  316.23  5055.4  318.77  5115.6  324.21  5125.7  323.47  5135.7  325.47
  5155.7  327.27  5205.9  327.91  5215.9  328.64  5246.0  332.43  5276.1  335.36
  5286.1  337.38  5291.1  335.61  5296.2  337.75  5326.3  341.10  5389.0  341.17
#Mann=3,-1,0
  4585.7    0.16       0  5002.3    0.07       0  5008.3    0.16       0
Bank Sta=5002.3,5008.3
Exp/Cntr=0.3,0.1

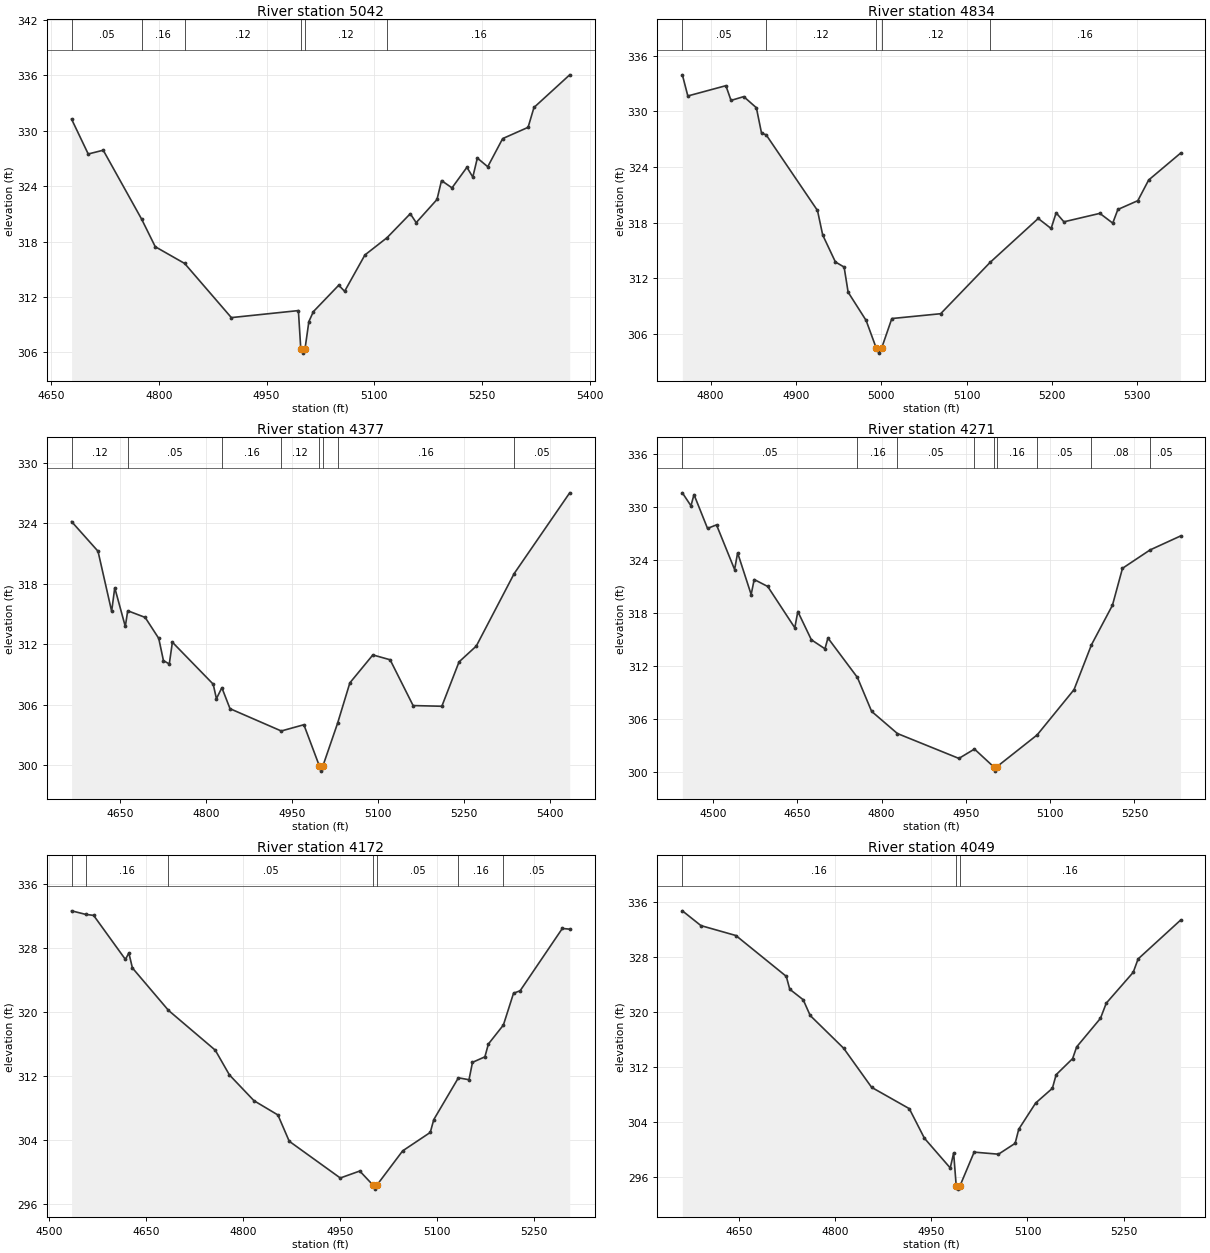
Type RM Length L Ch R = 1,5042,208,208,208
BEGIN DESCRIPTION:
UNT 073 IN BOCR 8.0
END DESCRIPTION:
XS GIS Cut Line= 2
      3769945.40     10567131.64      3770495.99     10567554.11
#Sta/Elev= 30
  4678.4  331.27  4701.6  327.49  4722.5  327.90  4776.0  320.43  4795.0  317.44
  4835.9  315.63  4901.0  309.76  4994.4  310.52  4997.7  306.41  5000.5  305.91
  5003.7  306.41  5009.0  309.33  5015.3  310.41  5050.6  313.27  5058.8  312.61
  5087.1  316.55  5117.9  318.42  5150.3  321.02  5158.5  320.05  5187.5  322.56
  5193.8  324.61  5208.4  323.82  5229.2  326.05  5237.4  324.99  5243.7  327.05
  5258.2  326.11  5279.0  329.16  5314.4  330.38  5322.6  332.53  5372.4  336.07
#Mann=6,-1,0
  4678.4    0.05       0  4776.0    0.16       0  4835.9    0.12       0
  4997.7    0.07       0  5003.7    0.12       0  5117.9    0.16       0
Bank Sta=4997.7,5003.7
Exp/Cntr=0.3,0.1

Type RM Length L Ch R = 1,4834,457,457,457
BEGIN DESCRIPTION:
Mapping XS 2236d6e1
END DESCRIPTION:
XS GIS Cut Line= 3
      3769902.62     10567257.53      3770009.40     10567411.18
      3770228.13     10567741.88
#Sta/Elev= 30
  4767.0  333.95  4773.4  331.67  4818.0  332.78  4824.0  331.19  4838.9  331.60
  4853.7  330.40  4859.8  327.64  4865.1  327.49  4925.3  319.32  4931.4  316.68
  4946.3  313.77  4956.5  313.22  4961.2  310.51  4982.3  307.46  4994.3  304.44
  4997.1  303.94  5000.3  304.44  5012.4  307.67  5069.6  308.19  5127.5  313.72
  5183.9  318.46  5199.0  317.38  5204.9  319.07  5214.0  318.10  5256.1  319.01
  5271.2  317.96  5277.2  319.43  5300.6  320.38  5313.3  322.61  5350.6  325.50
#Mann=5,-1,0
  4767.0    0.05       0  4865.1    0.12       0  4994.3    0.07       0
  5000.3    0.12       0  5127.5    0.16       0
Bank Sta=4994.3,5000.3
Exp/Cntr=0.3,0.1

Type RM Length L Ch R = 1,4377,106,106,106
BEGIN DESCRIPTION:
Mapping XS 764f7b02
END DESCRIPTION:
XS GIS Cut Line= 3
      3769952.34     10567402.44      3769816.92     10567725.38
      3769782.19     10568242.72
#Sta/Elev= 30
  4565.1  324.17  4611.2  321.23  4635.0  315.27  4640.4  317.61  4658.8  313.77
  4663.0  315.33  4693.4  314.67  4717.1  312.59  4725.3  310.39  4735.5  310.05
  4740.9  312.21  4812.1  308.05  4817.7  306.61  4827.2  307.70  4841.4  305.62
  4930.8  303.41  4970.2  304.03  4997.3  299.93  5000.0  299.43  5003.3  299.93
  5028.9  304.16  5050.4  308.18  5090.5  310.95  5120.6  310.47  5160.7  305.93
  5210.8  305.86  5240.8  310.26  5270.9  311.83  5337.0  319.02  5433.8  327.02
#Mann=8,-1,0
  4565.1    0.12       0  4663.0    0.05       0  4827.2    0.16       0
  4930.8    0.12       0  4997.3    0.07       0  5003.3    0.12       0
  5028.9    0.16       0  5337.0    0.05       0
Bank Sta=4997.3,5003.3
Exp/Cntr=0.3,0.1

Type RM Length L Ch R = 1,4271,99,99,99
BEGIN DESCRIPTION:
UNT 073 IN BOCR 7.0
END DESCRIPTION:
XS GIS Cut Line= 2
      3769931.51     10567353.83      3769598.50     10568175.95
#Sta/Elev= 30
  4445.1  331.61  4460.4  330.14  4465.8  331.41  4489.9  327.58  4505.9  327.98
  4538.1  322.92  4543.5  324.81  4567.6  320.09  4573.0  321.79  4597.1  321.00
  4645.3  316.32  4650.7  318.16  4674.8  314.96  4699.0  313.94  4704.3  315.16
  4756.8  310.69  4782.1  306.85  4828.0  304.34  4937.5  301.52  4965.2  302.58
  4999.2  300.58  5002.0  300.08  5005.2  300.58  5076.8  304.18  5142.5  309.31
  5173.6  314.40  5210.9  318.87  5228.8  323.06  5277.9  325.14  5332.1  326.72
#Mann=9,-1,0
  4445.1    0.05       0  4756.8    0.16       0  4828.0    0.05       0
  4965.2    0.16       0  4999.2    0.07       0  5005.2    0.16       0
  5076.8    0.05       0  5173.6    0.08       0  5277.9    0.05       0
Bank Sta=4999.2,5005.2
Exp/Cntr=0.3,0.1

Type RM Length L Ch R = 1,4172,123,123,123
BEGIN DESCRIPTION:
UNT 073 IN BOCR 6.0
END DESCRIPTION:
XS GIS Cut Line= 2
      3769806.51     10567402.43      3769528.72     10568121.22
#Sta/Elev= 30
  4534.6  332.59  4556.2  332.15  4568.7  332.02  4617.9  326.52  4623.2  327.33
  4628.7  325.46  4684.5  320.16  4756.9  315.19  4778.8  312.10  4816.8  308.88
  4853.8  307.10  4871.3  303.82  4950.3  299.23  4980.4  300.10  5000.9  298.34
  5003.7  297.84  5006.9  298.34  5046.8  302.62  5089.5  304.92  5094.9  306.52
  5133.0  311.74  5149.4  311.50  5154.8  313.67  5174.0  314.36  5179.4  315.96
  5202.6  318.33  5218.3  322.30  5228.5  322.61  5293.8  330.39  5305.2  330.30
#Mann=7,-1,0
  4534.6    0.05       0  4556.2    0.16       0  4684.5    0.05       0
  5000.9    0.04       0  5006.9    0.05       0  5133.0    0.16       0
  5202.6    0.05       0
Bank Sta=5000.9,5006.9
Exp/Cntr=0.3,0.1

Type RM Length L Ch R = 1,4049,347,347,347
BEGIN DESCRIPTION:
Mapping XS c7a0ff32
END DESCRIPTION:
XS GIS Cut Line= 2
      3769674.56     10567360.77      3769434.96     10568100.43
#Sta/Elev= 30
  4561.4  334.67  4590.4  332.52  4644.9  331.08  4723.6  325.14  4729.0  323.27
  4750.0  321.74  4760.9  319.45  4813.1  314.69  4856.8  309.00  4915.6  305.90
  4939.2  301.60  4979.5  297.28  4984.8  299.45  4988.8  294.70  4991.5  294.20
  4994.8  294.70  5016.8  299.58  5054.8  299.28  5080.8  300.86  5086.4  302.91
  5112.8  306.72  5138.9  308.86  5144.8  310.84  5170.5  313.18  5176.8  314.88
  5214.0  319.04  5223.0  321.24  5265.1  325.73  5272.7  327.67  5338.9  333.31
#Mann=3,-1,0
  4561.4    0.16       0  4988.8    0.07       0  4994.8    0.16       0
Bank Sta=4988.8,4994.8
Exp/Cntr=0.3,0.1

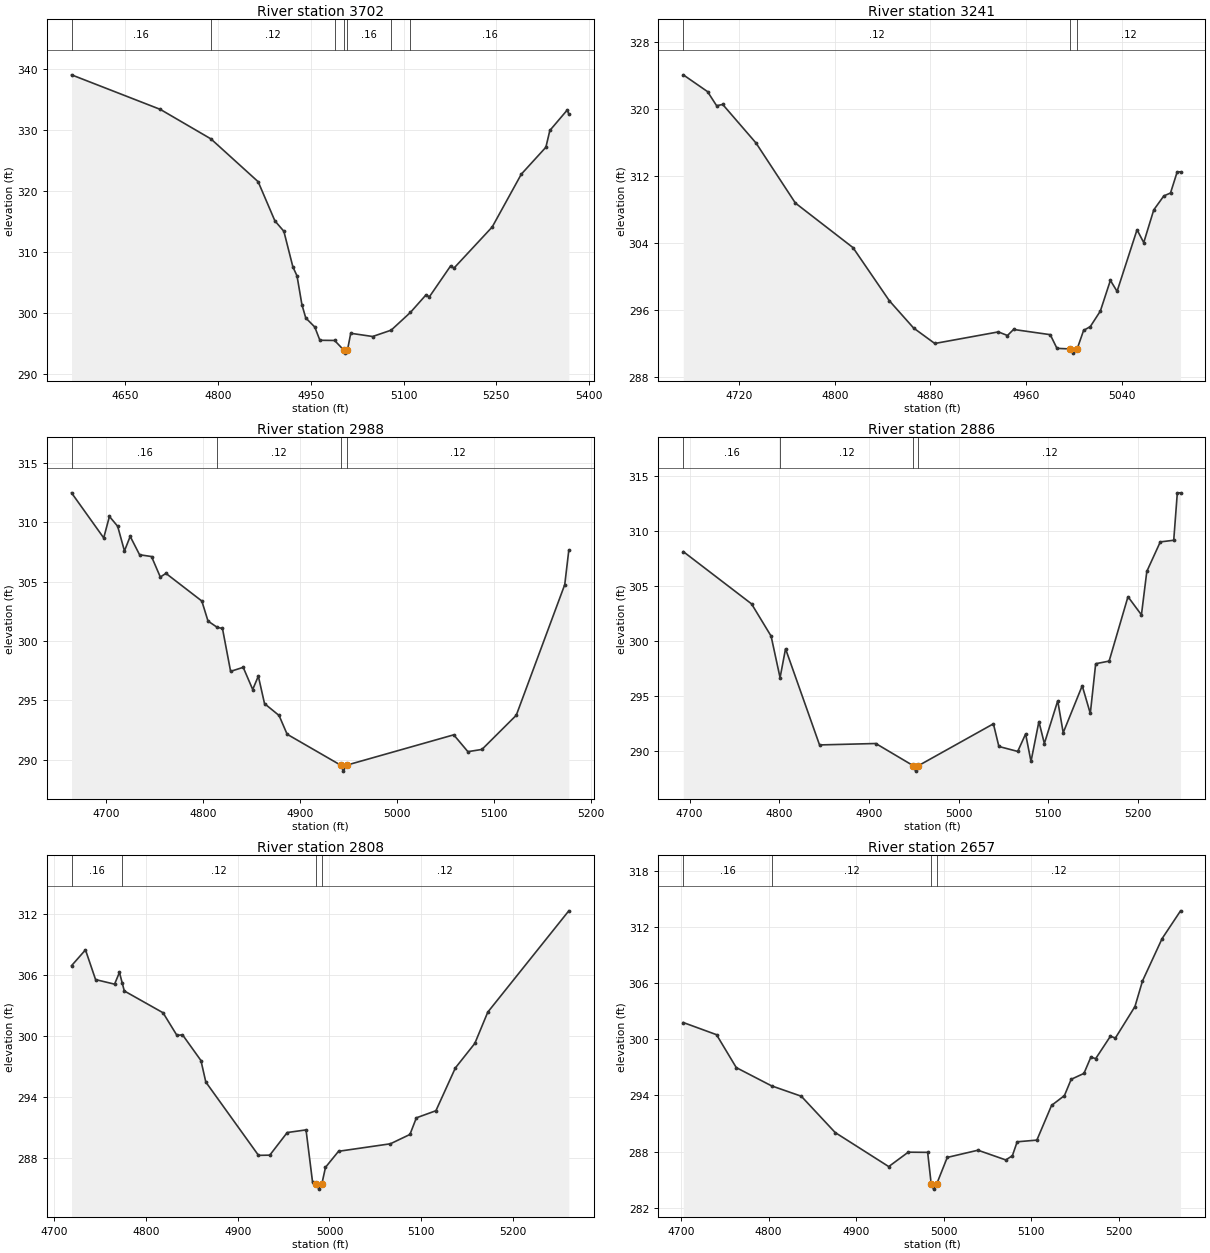
Type RM Length L Ch R = 1,3702,461,461,461
BEGIN DESCRIPTION:
UNT 073 IN BOCR 5.0
END DESCRIPTION:
XS GIS Cut Line= 3
      3768959.25     10567398.95      3769268.30     10567808.71
      3769344.64     10568089.78
#Sta/Elev= 30
  4562.8  339.10  4706.5  333.42  4788.3  328.58  4864.7  321.55  4891.8  315.12
  4906.3  313.41  4920.9  307.56  4927.6  306.08  4935.5  301.37  4941.7  299.18
  4956.3  297.69  4964.6  295.51  4988.4  295.48  5003.2  293.90  5006.0  293.40
  5009.2  293.90  5014.5  296.66  5049.9  296.13  5079.9  297.17  5111.0  300.08
  5136.4  302.98  5141.6  302.63  5176.2  307.74  5181.4  307.35  5243.4  314.12
  5290.4  322.78  5330.2  327.21  5336.6  329.96  5364.9  333.34  5367.3  332.63
#Mann=7,-1,0
  4562.8    0.16       0  4788.3    0.12       0  4988.4    0.16       0
  5003.2    0.07       0  5009.2    0.16       0  5079.9    0.12       0
  5111.0    0.16       0
Bank Sta=5003.2,5009.2
Exp/Cntr=0.3,0.1

Type RM Length L Ch R = 1,3241,253,253,253
BEGIN DESCRIPTION:
UNT 073 IN BOCR 4.0
END DESCRIPTION:
XS GIS Cut Line= 3
      3768899.60     10567710.14      3768949.61     10568010.19
      3768999.62     10568110.20
#Sta/Elev= 30
  4673.2  324.04  4693.5  322.04  4701.1  320.36  4706.2  320.51  4734.1  315.91
  4767.0  308.76  4815.2  303.45  4845.6  297.12  4865.9  293.87  4883.6  292.03
  4936.8  293.41  4944.4  292.98  4949.5  293.70  4980.2  293.08  4985.8  291.45
  4996.7  291.38  4999.5  290.88  5002.7  291.38  5008.1  293.59  5013.7  294.04
  5022.1  295.89  5030.5  299.55  5036.1  298.24  5052.8  305.58  5058.4  304.05
  5066.8  307.95  5075.2  309.61  5080.8  309.96  5086.4  312.48  5089.2  312.48
#Mann=3,-1,0
  4673.2    0.12       0  4996.7    0.07       0  5002.7    0.12       0
Bank Sta=4996.7,5002.7
Exp/Cntr=0.3,0.1

Type RM Length L Ch R = 1,2988,102,102,102
BEGIN DESCRIPTION:
Mapping XS 412542b9
END DESCRIPTION:
XS GIS Cut Line= 3
      3768545.89     10567719.39      3768699.53     10567975.89
      3768828.76     10568146.48
#Sta/Elev= 30
  4664.6  312.48  4697.8  308.68  4703.7  310.49  4712.2  309.66  4719.2  307.58
  4725.1  308.81  4734.8  307.26  4747.1  307.11  4756.2  305.38  4762.0  305.69
  4799.0  303.36  4805.4  301.67  4814.9  301.14  4820.3  301.05  4828.7  297.43
  4841.7  297.77  4851.5  295.90  4857.3  297.03  4863.7  294.71  4878.7  293.71
  4887.0  292.13  4942.3  289.52  4945.0  289.02  4948.3  289.52  5058.9  292.08
  5073.5  290.66  5088.0  290.85  5123.4  293.73  5173.4  304.74  5177.6  307.65
#Mann=4,-1,0
  4664.6    0.16       0  4814.9    0.12       0  4942.3    0.07       0
  4948.3    0.12       0
Bank Sta=4942.3,4948.3
Exp/Cntr=0.3,0.1

Type RM Length L Ch R = 1,2886,78,78,78
BEGIN DESCRIPTION:
Mapping XS 4a6708a8
END DESCRIPTION:
XS GIS Cut Line= 4
      3768459.70     10567745.21      3768536.07     10567884.07
      3768695.79     10568114.98      3768791.26     10568179.20
#Sta/Elev= 30
  4693.0  308.09  4769.1  303.34  4790.9  300.41  4800.9  296.63  4807.0  299.26
  4844.9  290.52  4907.6  290.65  4949.2  288.64  4952.0  288.14  4955.2  288.64
  5038.7  292.44  5044.8  290.38  5065.8  289.93  5074.6  291.52  5080.6  289.02
  5089.4  292.64  5095.5  290.65  5110.4  294.53  5116.5  291.63  5137.7  295.90
  5146.7  293.38  5152.7  297.90  5167.7  298.14  5188.7  303.99  5203.7  302.34
  5209.7  306.29  5224.7  308.97  5239.7  309.12  5243.7  313.43  5247.3  313.43
#Mann=4,-1,0
  4693.0    0.16       0  4800.9    0.12       0  4949.2    0.07       0
  4955.2    0.12       0
Bank Sta=4949.2,4955.2
Exp/Cntr=0.3,0.1

Type RM Length L Ch R = 1,2808,151,151,151
BEGIN DESCRIPTION:
Mapping XS 4ce7e635
END DESCRIPTION:
XS GIS Cut Line= 3
      3768305.20     10567948.32      3768534.34     10568026.43
      3768745.40     10568239.23
#Sta/Elev= 30
  4719.0  306.94  4734.2  308.50  4745.2  305.57  4765.9  305.12  4771.2  306.28
  4774.1  305.28  4776.5  304.45  4818.7  302.30  4833.9  300.06  4839.9  300.13
  4860.0  297.59  4865.3  295.47  4922.7  288.24  4935.0  288.26  4954.0  290.49
  4974.5  290.75  4981.6  285.60  4985.7  285.41  4988.4  284.91  4991.7  285.41
  4995.7  287.06  5009.9  288.64  5066.4  289.38  5087.7  290.30  5094.7  291.94
  5116.0  292.64  5137.2  296.86  5158.4  299.28  5172.5  302.36  5260.8  312.35
#Mann=4,-1,0
  4719.0    0.16       0  4774.1    0.12       0  4985.7    0.07       0
  4991.7    0.12       0
Bank Sta=4985.7,4991.7
Exp/Cntr=0.3,0.1

Type RM Length L Ch R = 1,2657,515,515,515
BEGIN DESCRIPTION:
Mapping XS dbfdeda9
END DESCRIPTION:
XS GIS Cut Line= 3
      3768228.19     10568039.70      3768465.15     10568154.27
      3768738.55     10568289.67
#Sta/Elev= 30
  4702.4  301.80  4740.4  300.50  4763.0  296.98  4803.3  295.03  4837.3  293.92
  4876.0  290.04  4937.2  286.40  4959.5  287.94  4981.7  287.92  4985.8  284.49
  4988.5  283.99  4991.8  284.49  5004.1  287.38  5039.2  288.15  5071.0  287.11
  5078.5  287.56  5084.0  289.05  5106.5  289.23  5123.3  292.94  5138.0  293.99
  5145.7  295.73  5160.3  296.36  5168.2  298.10  5173.7  297.94  5190.6  300.34
  5196.2  300.14  5218.6  303.51  5227.2  306.24  5249.6  310.77  5270.7  313.74
#Mann=4,-1,0
  4702.4    0.16       0  4803.3    0.12       0  4985.8    0.07       0
  4991.8    0.12       0
Bank Sta=4985.8,4991.8
Exp/Cntr=0.3,0.1

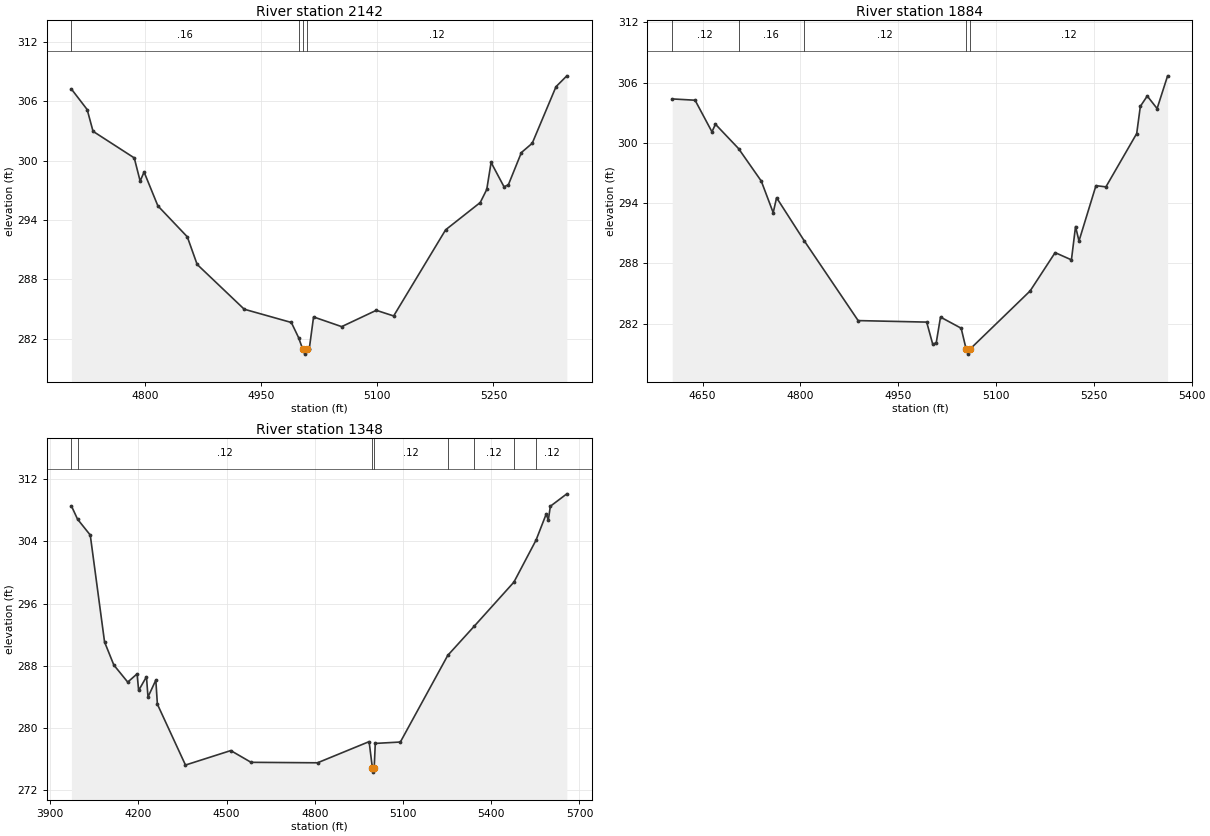
Type RM Length L Ch R = 1,2142,258,258,258
BEGIN DESCRIPTION:
UNT 073 IN BOCR 2.0
END DESCRIPTION:
XS GIS Cut Line= 3
      3768099.57     10568410.18      3768399.61     10568460.19
      3768699.62     10568310.19
#Sta/Elev= 30
  4705.1  307.23  4725.4  305.16  4733.0  302.96  4786.2  300.27  4793.8  297.93
  4798.9  298.84  4816.7  295.42  4854.7  292.29  4867.4  289.50  4928.2  284.97
  4989.0  283.63  4998.3  282.11  5003.7  280.93  5006.5  280.43  5009.7  280.93
  5012.1  280.93  5017.7  284.19  5054.0  283.21  5098.7  284.86  5121.1  284.29
  5188.2  293.00  5232.9  295.76  5241.3  297.08  5246.9  299.81  5263.6  297.35
  5269.2  297.55  5286.0  300.81  5300.0  301.75  5330.7  307.47  5344.7  308.57
#Mann=4,-1,0
  4705.1    0.16       0  4998.3    0.12       0  5003.7    0.07       0
  5009.7    0.12       0
Bank Sta=5003.7,5009.7
Exp/Cntr=0.3,0.1

Type RM Length L Ch R = 1,1884,536,536,536
BEGIN DESCRIPTION:
Mapping XS 8cd2b37a
END DESCRIPTION:
XS GIS Cut Line= 2
      3768070.40     10568746.21      3768789.10     10568499.70
#Sta/Elev= 30
  4603.3  304.37  4638.4  304.24  4664.3  301.09  4669.6  301.85  4705.0  299.43
  4739.9  296.19  4758.2  293.04  4763.4  294.53  4805.8  290.24  4888.5  282.29
  4993.6  282.14  5003.0  279.91  5008.3  280.10  5014.8  282.64  5046.5  281.53
  5054.1  279.45  5056.8  278.95  5060.1  279.45  5152.2  285.24  5190.6  289.06
  5215.6  288.34  5221.9  291.66  5227.2  290.22  5253.2  295.73  5268.5  295.61
  5315.7  300.92  5321.3  303.63  5331.9  304.66  5347.0  303.41  5363.1  306.67
#Mann=5,-1,0
  4603.3    0.12       0  4705.0    0.16       0  4805.8    0.12       0
  5054.1    0.07       0  5060.1    0.12       0
Bank Sta=5054.1,5060.1
Exp/Cntr=0.3,0.1

Type RM Length L Ch R = 1,1348,0,0,0
BEGIN DESCRIPTION:
UNT 073 IN BOCR 1.0
END DESCRIPTION:
XS GIS Cut Line= 3
      3767792.62     10568815.66      3768587.75     10569076.07
      3769153.24     10568444.67
#Sta/Elev= 30
  3972.8  308.55  3993.6  306.85  4036.8  304.81  4085.4  291.07  4116.9  288.11
  4164.2  285.91  4196.0  286.97  4201.3  284.84  4227.9  286.60  4233.1  283.99
  4259.7  286.17  4265.0  283.07  4360.5  275.25  4514.5  277.11  4583.5  275.60
  4809.5  275.54  4984.9  278.26  4996.1  274.84  4998.9  274.34  5002.1  274.84
  5005.8  278.03  5091.1  278.21  5252.3  289.35  5343.1  293.13  5477.1  298.76
  5552.4  304.16  5586.7  307.49  5594.2  306.75  5601.0  308.51  5657.1  310.11
#Mann=8,-1,0
  3972.8    0.16       0  3993.6    0.12       0  4996.1    0.07       0
  5002.1    0.12       0  5252.3    0.16       0  5343.1    0.12       0
  5477.1    0.16       0  5552.4    0.12       0
Bank Sta=4996.1,5002.1
Exp/Cntr=0.3,0.1

Chan Stop Cuts=-1