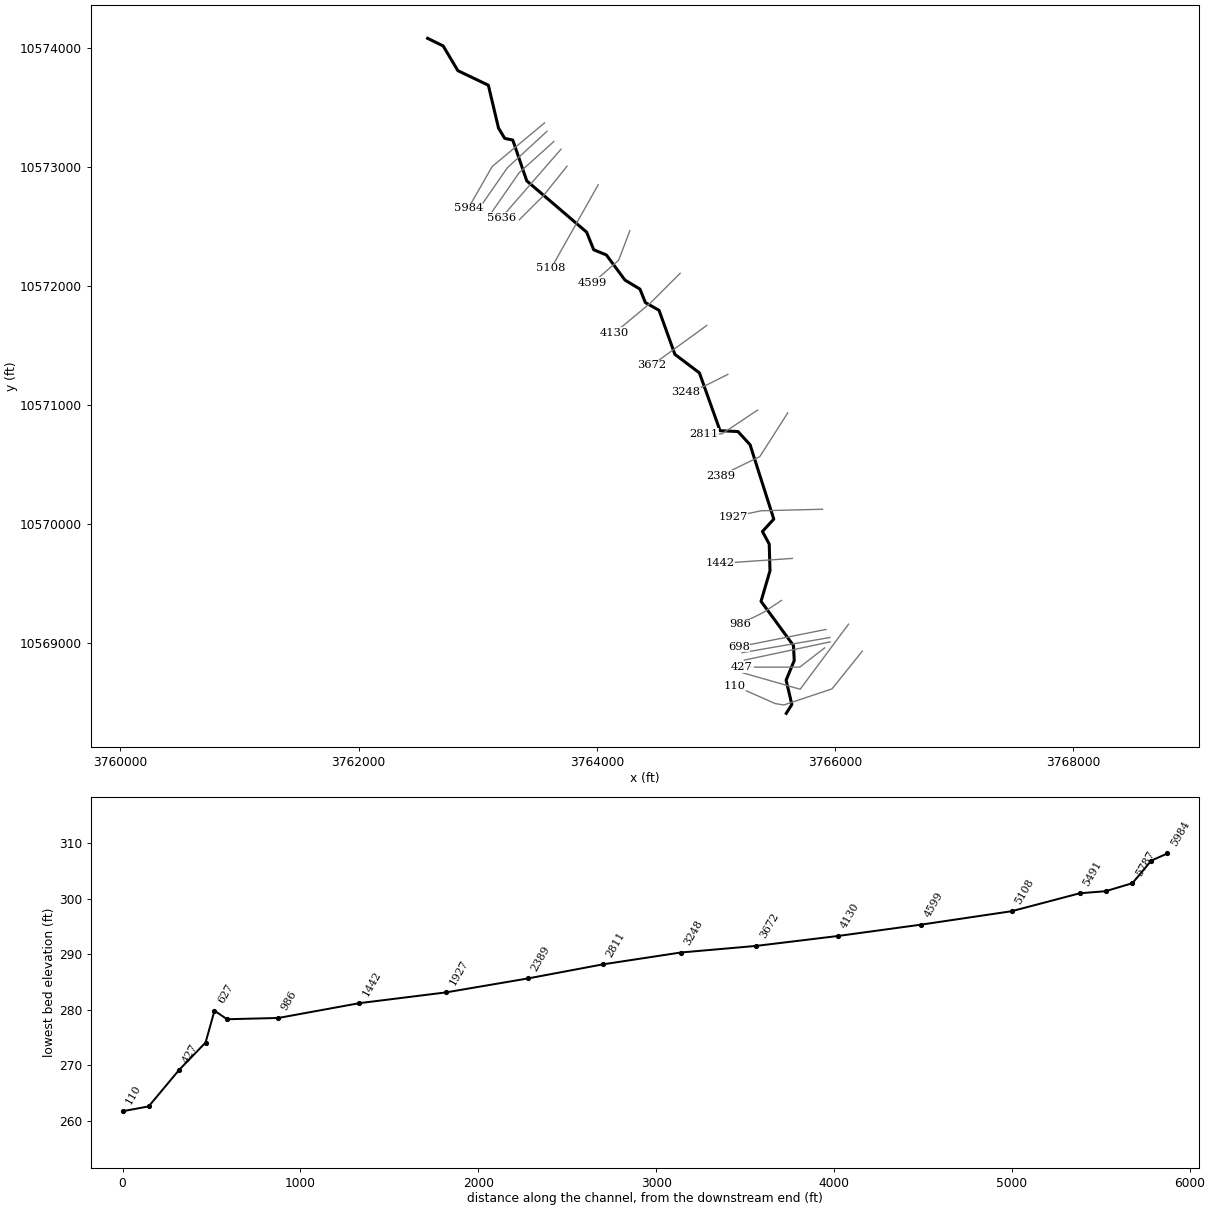
--- UNT 074 IN BOCR.prj (project) ---

Proj Title=UNT 074 IN BOCR Base Level Engineering
Current Plan=p01
Default Exp/Contr=0.3,0.1
English Units
Geom File=g01
Flow File=f01
Plan File=p01
BEGIN DESCRIPTION:
UNT 074 IN BOCR
END DESCRIPTION:

--- UNT 074 IN BOCR.p01 (plan) ---

Plan Title=Multiple Run
Short Identifier=Multiple
Geom File=g01
Flow File=f01
Subcritical Flow
K Sum by GR= 0
Std Step Tol= 0.01
Critical Tol= 0.01
Num of Std Step Trials= 20
Max Error Tol= 0.3
Flow Tol Ratio= 0.001
Split Flow NTrial= 30
Split Flow Tol= 0.02
Split Flow Ratio= 0.02
Log Output Level= 0
Friction Slope Method= 1
Unsteady Friction Slope Method= 2
Unsteady Bridges Friction Slope Method= 1
Parabolic Critical Depth
Global Vel Dist=  1 , 1 , 1
Global Log Level= 0
CheckData=True
Encroach Param= -1, 0, 0, 0
BEGIN DESCRIPTION:
Multiple Run
END DESCRIPTION:

--- UNT 074 IN BOCR.f01 (steady flow) ---

Flow Title=Multiple
Number of Profiles=7
Profile Names=10-year,25-year,50-year,1pct_min,100-year,1pct_plu,500-year
River Rch & RM= UNT 074 IN BOCR,Reach-1,5984
     383     504     600     527     713     964    1006
Boundary for River Rch & Prof#=UNT 074 IN BOCR,Reach-1,1
Up Type=0
Dn Type=3
Dn Slope=0.005
Boundary for River Rch & Prof#=UNT 074 IN BOCR,Reach-1,2
Up Type=0
Dn Type=3
Dn Slope=0.005
Boundary for River Rch & Prof#=UNT 074 IN BOCR,Reach-1,3
Up Type=0
Dn Type=3
Dn Slope=0.005
Boundary for River Rch & Prof#=UNT 074 IN BOCR,Reach-1,4
Up Type=0
Dn Type=3
Dn Slope=0.005
Boundary for River Rch & Prof#=UNT 074 IN BOCR,Reach-1,5
Up Type=0
Dn Type=3
Dn Slope=0.005
Boundary for River Rch & Prof#=UNT 074 IN BOCR,Reach-1,6
Up Type=0
Dn Type=3
Dn Slope=0.005
Boundary for River Rch & Prof#=UNT 074 IN BOCR,Reach-1,7
Up Type=0
Dn Type=3
Dn Slope=0.005

--- UNT 074 IN BOCR.g01 (geometry) ---

Geom Title=Existing Conditions

River Reach=UNT 074 IN BOCR,Reach-1
Reach XY= 30
      3762579.50     10574085.00      3762710.00     10574021.00
      3762833.50     10573813.00      3763089.25     10573691.00
      3763174.75     10573330.00      3763226.75     10573244.00
      3763294.25     10573230.00      3763411.75     10572887.00
      3763914.25     10572456.00      3763973.75     10572308.00
      3764080.25     10572264.00      3764236.25     10572053.00
      3764362.25     10571977.00      3764407.25     10571864.00
      3764522.25     10571799.00      3764655.00     10571429.00
      3764861.25     10571273.00      3765034.50     10570787.00
      3765184.75     10570780.00      3765286.50     10570669.00
      3765485.50     10570044.00      3765390.25     10569940.00
      3765447.25     10569834.00      3765453.75     10569610.00
      3765378.50     10569353.00      3765650.75     10568981.00
      3765657.25     10568855.00      3765589.00     10568690.00
      3765637.00     10568486.00      3765590.25     10568411.00

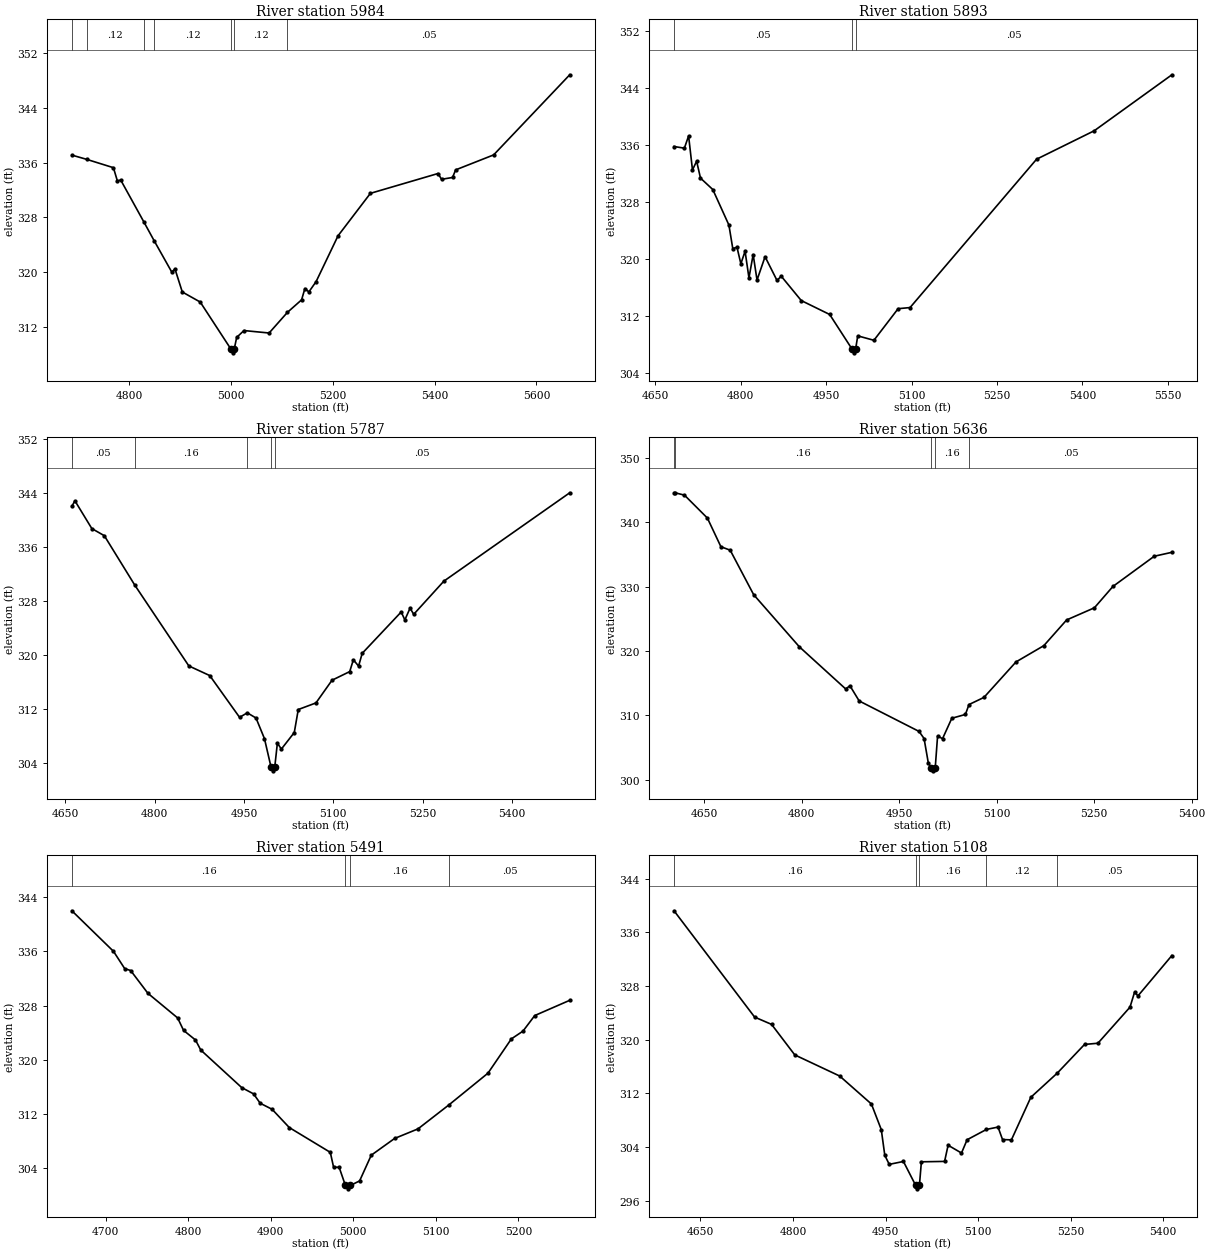
Type RM Length L Ch R = 1,5984,91,91,91
BEGIN DESCRIPTION:
UNT 074 IN BOCR 16.0
END DESCRIPTION:
XS GIS Cut Line= 3
      3763561.06     10573374.25      3763120.95     10573007.06
      3762920.43     10572655.50
#Sta/Elev= 30
  4687.5  337.10  4716.6  336.48  4769.1  335.26  4776.9  333.32  4783.4  333.46
  4828.8  327.34  4849.6  324.51  4883.6  320.01  4890.1  320.43  4904.4  317.08
  4939.6  315.61  5000.3  308.68  5003.1  308.18  5006.3  308.68  5011.2  310.44
  5025.5  311.44  5074.9  311.08  5111.0  314.11  5138.7  315.93  5145.2  317.59
  5153.0  317.09  5167.3  318.61  5210.3  325.30  5273.9  331.51  5406.7  334.41
  5413.6  333.56  5435.2  333.83  5441.3  334.94  5515.9  337.13  5665.4  348.85
#Mann=7,-1,0
  4687.5    0.05       0  4716.6    0.12       0  4828.8    0.05       0
  4849.6    0.12       0  5000.3    0.07       0  5006.3    0.12       0
  5111.0    0.05       0
Bank Sta=5000.3,5006.3
Exp/Cntr=0.3,0.1

Type RM Length L Ch R = 1,5893,106,106,106
BEGIN DESCRIPTION:
UNT 074 IN BOCR 13.0
END DESCRIPTION:
XS GIS Cut Line= 3
      3763581.87     10573303.92      3763248.56     10572996.65
      3763008.96     10572650.27
#Sta/Elev= 30
  4682.6  335.81  4700.8  335.58  4708.2  337.30  4715.0  332.53  4722.3  333.75
  4729.1  331.38  4750.7  329.78  4779.0  324.80  4785.8  321.50  4793.2  321.68
  4800.0  319.37  4807.4  321.13  4814.2  317.39  4821.6  320.66  4828.4  317.09
  4842.5  320.36  4863.5  317.03  4870.9  317.63  4906.1  314.21  4956.0  312.26
  4995.5  307.38  4998.2  306.88  5001.5  307.38  5005.3  309.26  5033.7  308.64
  5076.2  313.07  5097.2  313.23  5319.4  334.03  5420.7  338.02  5557.1  345.87
#Mann=3,-1,0
  4682.6    0.05       0  4995.5    0.04       0  5001.5    0.05       0
Bank Sta=4995.5,5001.5
Exp/Cntr=0.3,0.1

Type RM Length L Ch R = 1,5787,151,151,151
BEGIN DESCRIPTION:
Mapping XS 599b2403
END DESCRIPTION:
XS GIS Cut Line= 3
      3763639.15     10573217.98      3763347.51     10572954.98
      3763094.88     10572590.36
#Sta/Elev= 30
  4660.8  342.09  4665.9  342.90  4694.3  338.78  4715.3  337.72  4766.5  330.38
  4857.3  318.39  4892.4  316.96  4942.5  310.76  4955.5  311.43  4970.1  310.66
  4984.3  307.60  4995.5  303.32  4998.3  302.82  5001.5  303.32  5006.0  306.93
  5012.7  306.05  5034.4  308.51  5041.1  311.92  5070.8  312.90  5097.8  316.27
  5127.5  317.55  5133.6  319.30  5142.4  318.37  5148.5  320.26  5214.0  326.40
  5220.1  325.22  5228.9  326.97  5235.0  326.05  5285.6  330.97  5497.1  344.09
#Mann=5,-1,0
  4660.8    0.05       0  4766.5    0.16       0  4955.5    0.05       0
  4995.5    0.04       0  5001.5    0.05       0
Bank Sta=4995.5,5001.5
Exp/Cntr=0.3,0.1

Type RM Length L Ch R = 1,5636,145,145,145
BEGIN DESCRIPTION:
Mapping XS 435b4213
END DESCRIPTION:
XS GIS Cut Line= 2
      3763699.08     10573152.90      3763196.64     10572574.97
#Sta/Elev= 30
  4603.7  344.62  4605.3  344.62  4619.8  344.25  4655.0  340.69  4675.8  336.23
  4690.1  335.69  4726.2  328.77  4796.4  320.67  4867.7  314.11  4874.3  314.60
  4888.5  312.24  4980.6  307.50  4988.3  306.40  4994.9  302.56  4999.5  301.87
  5002.2  301.37  5005.5  301.87  5009.1  306.80  5016.7  306.37  5031.0  309.55
  5051.9  310.14  5057.4  311.68  5080.4  312.79  5129.7  318.31  5172.5  320.84
  5207.6  324.84  5250.3  326.73  5278.8  330.05  5342.4  334.75  5369.5  335.36
#Mann=5,-1,0
  4603.7    0.05       0  4605.3    0.16       0  4999.5    0.07       0
  5005.5    0.16       0  5057.4    0.05       0
Bank Sta=4999.5,5005.5
Exp/Cntr=0.3,0.1

Type RM Length L Ch R = 1,5491,383,383,383
BEGIN DESCRIPTION:
UNT 074 IN BOCR 12.0
END DESCRIPTION:
XS GIS Cut Line= 3
      3763749.62     10573010.20      3763549.61     10572760.19
      3763349.62     10572560.19
#Sta/Elev= 30
  4659.2  342.00  4709.6  336.02  4723.2  333.47  4730.4  333.19  4751.3  329.83
  4787.3  326.20  4794.5  324.36  4808.9  322.95  4815.3  321.47  4864.9  315.93
  4879.3  315.00  4887.3  313.62  4901.7  312.73  4922.5  310.04  4972.2  306.38
  4976.2  304.18  4982.9  304.18  4990.5  301.50  4993.3  301.00  4996.5  301.50
  5007.7  302.17  5021.8  305.96  5050.1  308.43  5078.4  309.84  5116.2  313.41
  5163.2  318.06  5191.5  323.11  5205.6  324.26  5219.8  326.55  5262.2  328.80
#Mann=4,-1,0
  4659.2    0.16       0  4990.5    0.07       0  4996.5    0.16       0
  5116.2    0.05       0
Bank Sta=4990.5,4996.5
Exp/Cntr=0.3,0.1

Type RM Length L Ch R = 1,5108,509,509,509
BEGIN DESCRIPTION:
UNT 074 IN BOCR 11.0
END DESCRIPTION:
XS GIS Cut Line= 2
      3764011.46     10572854.13      3763615.62     10572151.00
#Sta/Elev= 30
  4607.2  339.23  4737.8  323.38  4765.3  322.29  4802.9  317.74  4875.7  314.59
  4927.1  310.42  4943.1  306.60  4948.8  302.77  4956.0  301.42  4979.0  301.85
  4998.9  298.27  5001.7  297.77  5004.9  298.27  5008.1  301.80  5045.7  301.86
  5051.4  304.27  5073.1  303.11  5082.2  305.09  5113.6  306.63  5132.3  306.98
  5139.6  305.12  5154.0  305.07  5185.5  311.42  5228.6  315.05  5272.5  319.30
  5294.2  319.48  5346.2  324.86  5353.5  327.06  5359.2  326.55  5414.1  332.56
#Mann=5,-1,0
  4607.2    0.16       0  4998.9    0.07       0  5004.9    0.16       0
  5113.6    0.12       0  5228.6    0.05       0
Bank Sta=4998.9,5004.9
Exp/Cntr=0.3,0.1

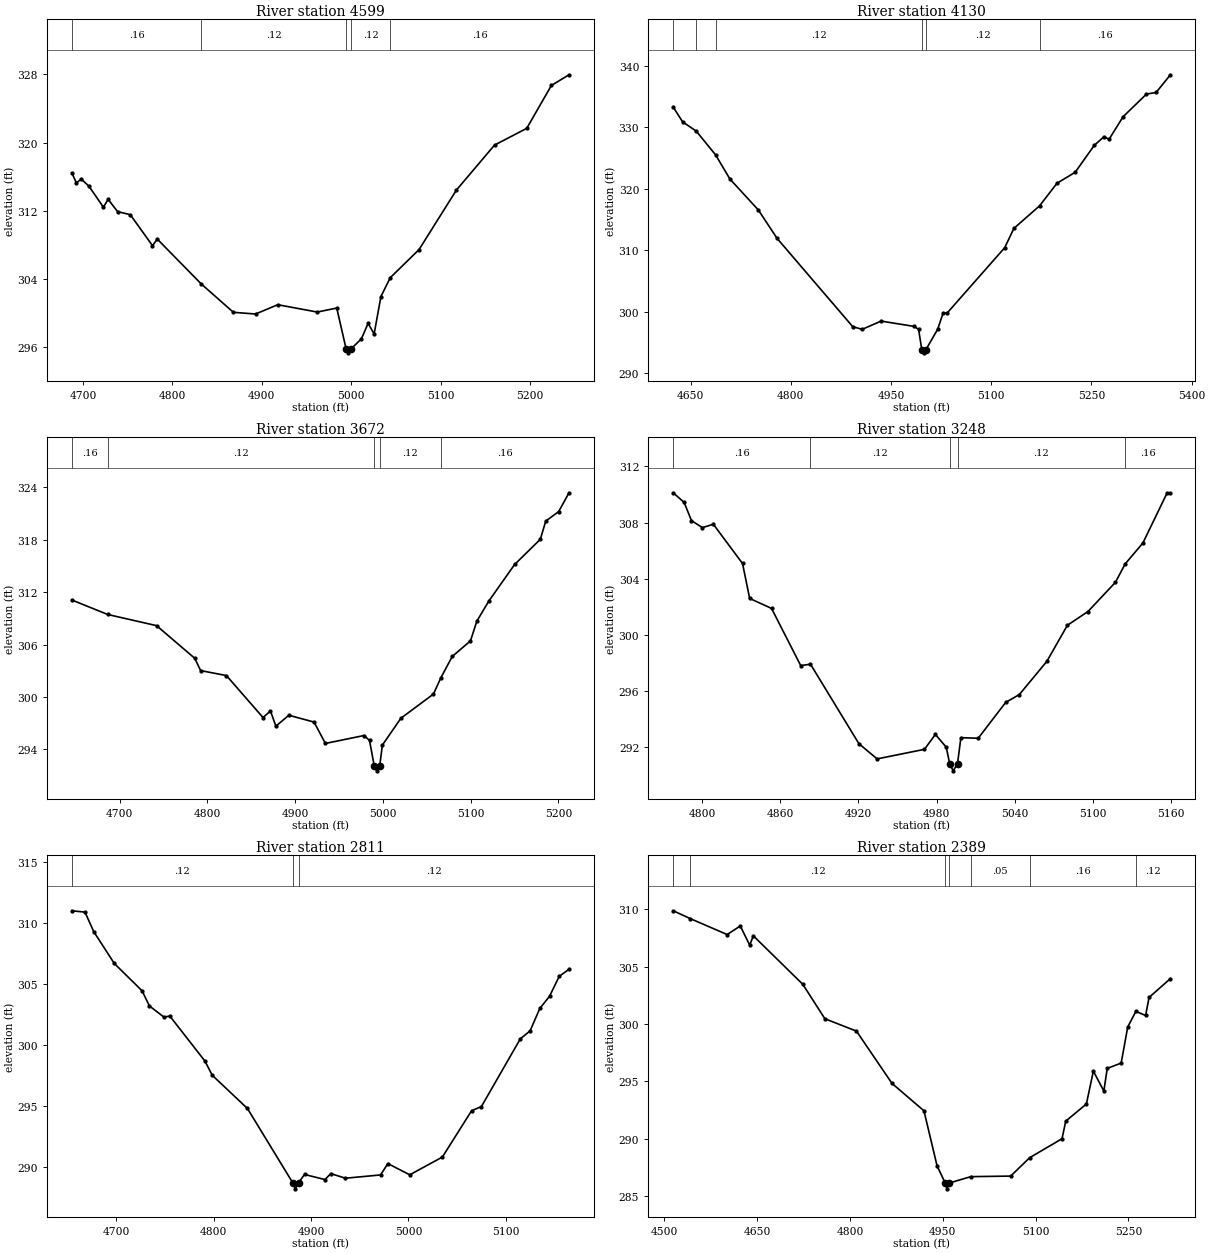
Type RM Length L Ch R = 1,4599,469,469,469
BEGIN DESCRIPTION:
UNT 074 IN BOCR 10.0
END DESCRIPTION:
XS GIS Cut Line= 3
      3764277.19     10572467.98      3764183.45     10572220.61
      3763964.68     10572027.88
#Sta/Elev= 30
  4687.5  316.44  4692.6  315.27  4698.0  315.71  4706.5  314.90  4722.8  312.42
  4728.1  313.34  4738.6  311.91  4752.9  311.54  4777.7  307.91  4783.1  308.68
  4832.3  303.42  4868.2  300.10  4893.0  299.90  4917.8  300.99  4962.0  300.13
  4983.8  300.60  4994.2  295.85  4996.9  295.35  5000.2  295.85  5011.4  297.00
  5018.9  298.81  5025.6  297.56  5033.2  301.94  5043.6  304.15  5075.9  307.46
  5117.6  314.42  5160.3  319.70  5196.3  321.66  5223.9  326.69  5243.6  327.94
#Mann=5,-1,0
  4687.5    0.16       0  4832.3    0.12       0  4994.2    0.07       0
  5000.2    0.12       0  5043.6    0.16       0
Bank Sta=4994.2,5000.2
Exp/Cntr=0.3,0.1

Type RM Length L Ch R = 1,4130,458,458,458
BEGIN DESCRIPTION:
UNT 074 IN BOCR 9.0
END DESCRIPTION:
XS GIS Cut Line= 3
      3764699.59     10572110.17      3764449.61     10571860.19
      3764149.64     10571610.21
#Sta/Elev= 30
  4624.1  333.30  4638.2  330.90  4658.5  329.40  4687.5  325.53  4708.9  321.60
  4751.4  316.57  4779.6  311.92  4892.8  297.55  4906.9  297.13  4935.2  298.47
  4984.8  297.60  4991.3  297.11  4996.1  293.80  4998.9  293.30  5002.1  293.80
  5019.9  297.15  5027.7  299.71  5034.3  299.82  5120.2  310.43  5133.8  313.55
  5172.3  317.23  5198.3  320.90  5225.6  322.70  5254.2  327.08  5268.6  328.48
  5276.4  328.08  5297.2  331.73  5332.3  335.43  5346.7  335.69  5368.1  338.57
#Mann=6,-1,0
  4624.1    0.12       0  4658.5    0.16       0  4687.5    0.12       0
  4996.1    0.07       0  5002.1    0.12       0  5172.3    0.16       0
Bank Sta=4996.1,5002.1
Exp/Cntr=0.3,0.1

Type RM Length L Ch R = 1,3672,424,424,424
BEGIN DESCRIPTION:
UNT 074 IN BOCR 8.0
END DESCRIPTION:
XS GIS Cut Line= 2
      3764922.94     10571671.86      3764464.63     10571338.55
#Sta/Elev= 30
  4645.4  311.10  4686.3  309.44  4742.0  308.16  4785.5  304.42  4792.2  303.01
  4821.6  302.44  4863.3  297.63  4871.8  298.38  4878.0  296.64  4892.7  297.89
  4921.5  297.11  4934.4  294.66  4978.5  295.57  4984.7  295.00  4990.2  292.02
  4992.9  291.52  4996.2  292.02  4999.4  294.48  5020.5  297.55  5057.6  300.32
  5065.9  302.16  5079.0  304.63  5099.8  306.42  5107.0  308.67  5120.7  310.98
  5150.1  315.17  5179.4  318.06  5185.6  320.15  5200.3  321.23  5212.1  323.39
#Mann=5,-1,0
  4645.4    0.16       0  4686.3    0.12       0  4990.2    0.07       0
  4996.2    0.12       0  5065.9    0.16       0
Bank Sta=4990.2,4996.2
Exp/Cntr=0.3,0.1

Type RM Length L Ch R = 1,3248,437,437,437
BEGIN DESCRIPTION:
UNT 074 IN BOCR 7.0
END DESCRIPTION:
XS GIS Cut Line= 3
      3765099.65     10571260.21      3764899.61     10571160.19
      3764749.58     10571110.18
#Sta/Elev= 30
  4777.8  310.12  4786.2  309.43  4791.8  308.14  4800.2  307.64  4808.6  307.88
  4831.0  305.09  4836.5  302.60  4853.3  301.89  4875.7  297.82  4883.2  297.92
  4920.4  292.26  4934.4  291.18  4970.7  291.86  4979.1  292.92  4987.5  292.01
  4990.1  290.83  4992.8  290.33  4996.1  290.83  4998.7  292.69  5012.0  292.65
  5033.1  295.20  5043.6  295.76  5064.7  298.12  5080.5  300.69  5096.3  301.67
  5117.4  303.75  5124.8  305.05  5138.5  306.55  5156.9  310.08  5159.6  310.08
#Mann=5,-1,0
  4777.8    0.16       0  4883.2    0.12       0  4990.1    0.07       0
  4996.1    0.12       0  5124.8    0.16       0
Bank Sta=4990.1,4996.1
Exp/Cntr=0.3,0.1

Type RM Length L Ch R = 1,2811,422,422,422
BEGIN DESCRIPTION:
UNT 074 IN BOCR 6.0
END DESCRIPTION:
XS GIS Cut Line= 3
      3765349.60     10570960.18      3765049.61     10570760.19
      3764899.65     10570760.19
#Sta/Elev= 30
  4654.4  311.00  4667.9  310.89  4676.9  309.29  4698.0  306.68  4726.5  304.44
  4734.0  303.20  4749.0  302.28  4755.0  302.37  4791.1  298.67  4798.6  297.51
  4834.7  294.79  4881.2  288.70  4884.0  288.20  4887.2  288.70  4893.3  289.38
  4914.3  288.96  4920.3  289.45  4935.3  289.07  4971.4  289.34  4978.9  290.27
  5001.4  289.35  5034.9  290.81  5064.9  294.61  5074.9  294.94  5114.9  300.50
  5124.9  301.15  5134.9  302.99  5144.9  303.99  5154.9  305.63  5164.9  306.20
#Mann=3,-1,0
  4654.4    0.12       0  4881.2    0.07       0  4887.2    0.12       0
Bank Sta=4881.2,4887.2
Exp/Cntr=0.3,0.1

Type RM Length L Ch R = 1,2389,462,462,462
BEGIN DESCRIPTION:
UNT 074 IN BOCR 5.0
END DESCRIPTION:
XS GIS Cut Line= 3
      3765602.74     10570936.78      3765368.35     10570569.56
      3765037.60     10570408.10
#Sta/Elev= 30
  4514.2  309.85  4541.7  309.17  4601.4  307.78  4622.6  308.53  4637.8  306.86
  4643.7  307.67  4723.7  303.45  4759.3  300.46  4810.4  299.38  4867.9  294.83
  4919.5  292.45  4940.7  287.66  4953.9  286.16  4956.7  285.66  4959.9  286.16
  4995.3  286.72  5059.7  286.77  5090.4  288.37  5142.7  290.02  5148.7  291.55
  5182.1  293.04  5193.3  295.90  5210.3  294.17  5215.8  296.14  5238.3  296.60
  5248.9  299.74  5262.1  301.10  5277.8  300.74  5283.4  302.31  5317.9  303.95
#Mann=7,-1,0
  4514.2    0.16       0  4541.7    0.12       0  4953.9    0.03       0
  4959.9    0.12       0  4995.3    0.05       0  5090.4    0.16       0
  5262.1    0.12       0
Bank Sta=4953.9,4959.9
Exp/Cntr=0.3,0.1

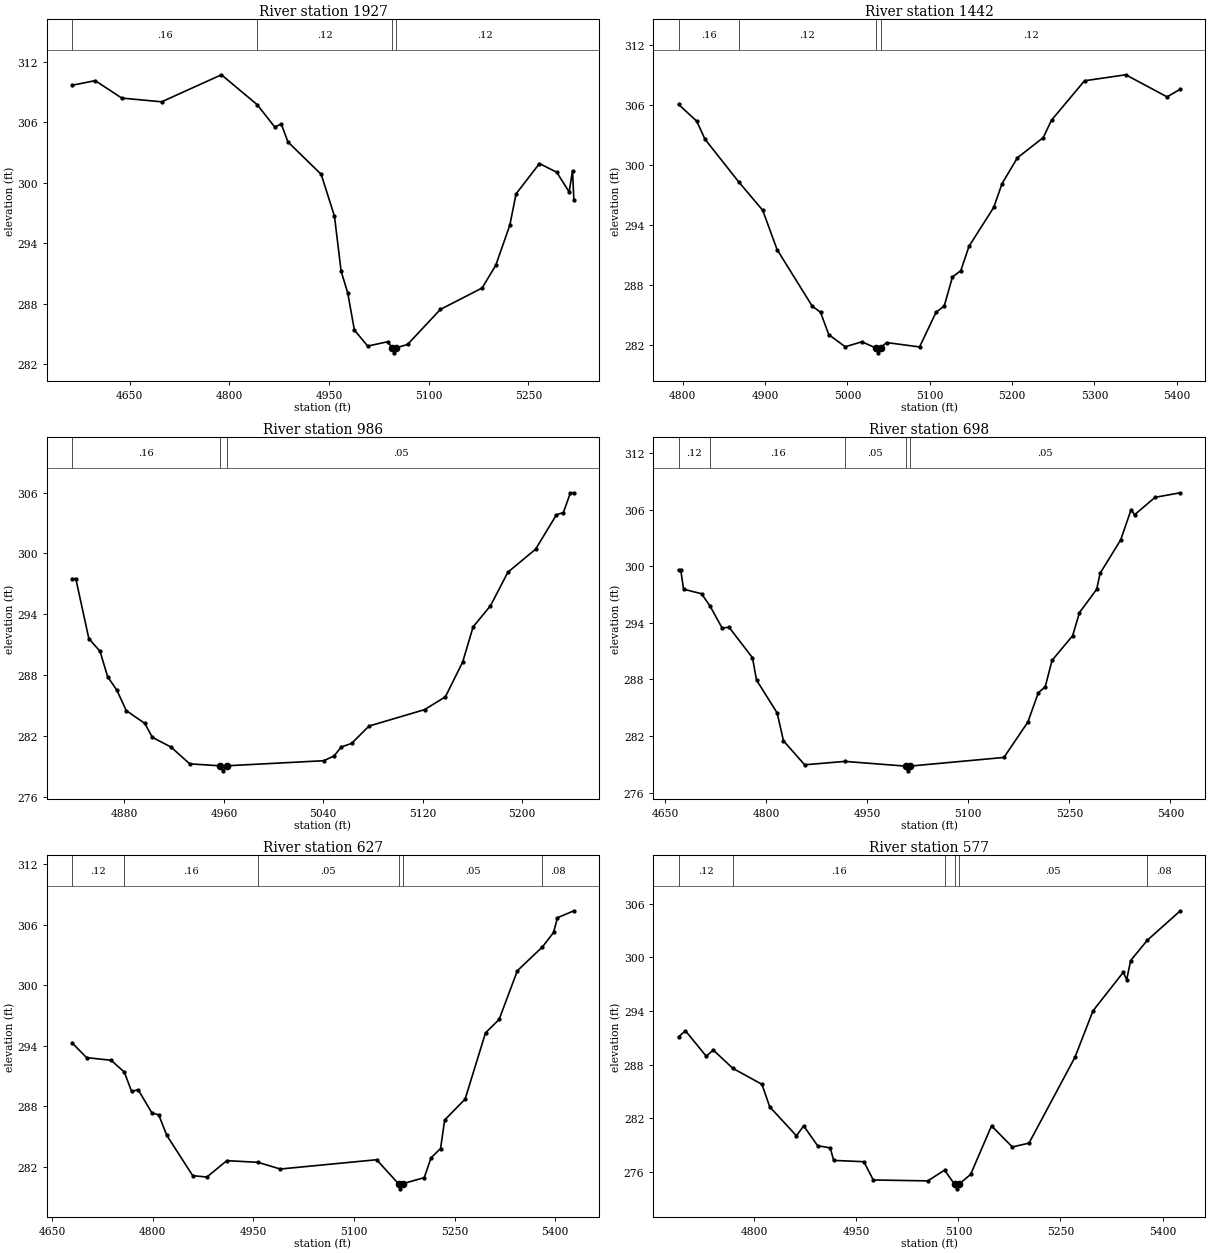
Type RM Length L Ch R = 1,1927,485,485,485
BEGIN DESCRIPTION:
UNT 074 IN BOCR 4.0
END DESCRIPTION:
XS GIS Cut Line= 3
      3765894.37     10570126.85      3765378.76     10570113.83
      3765144.50     10570064.38
#Sta/Elev= 30
  4563.1  309.67  4597.9  310.13  4637.9  308.40  4697.9  308.03  4787.9  310.71
  4841.8  307.74  4868.0  305.54  4878.0  305.82  4888.0  304.05  4938.0  300.84
  4958.0  296.69  4968.0  291.24  4978.0  289.07  4988.0  285.40  5008.0  283.81
  5038.0  284.24  5045.0  283.64  5047.8  283.14  5051.0  283.64  5068.0  283.97
  5117.3  287.44  5180.2  289.57  5200.7  291.81  5221.9  295.79  5231.3  298.90
  5266.5  301.91  5292.6  301.04  5311.2  299.09  5316.3  301.20  5318.3  298.33
#Mann=4,-1,0
  4563.1    0.16       0  4841.8    0.12       0  5045.0    0.07       0
  5051.0    0.12       0
Bank Sta=5045,5051
Exp/Cntr=0.3,0.1

Type RM Length L Ch R = 1,1442,456,456,456
BEGIN DESCRIPTION:
UNT 074 IN BOCR 3.0
END DESCRIPTION:
XS GIS Cut Line= 2
      3765641.68     10569713.52      3765033.50     10569671.93
#Sta/Elev= 30
  4794.8  306.06  4816.9  304.38  4826.9  302.58  4867.8  298.32  4897.1  295.46
  4914.5  291.54  4957.2  285.88  4967.3  285.27  4977.3  283.03  4997.3  281.82
  5017.4  282.31  5034.4  281.71  5037.2  281.21  5040.4  281.71  5047.5  282.24
  5087.6  281.80  5107.6  285.26  5117.6  285.90  5127.6  288.80  5137.7  289.43
  5147.7  291.87  5177.8  295.77  5187.8  298.13  5206.5  300.72  5237.9  302.74
  5247.9  304.48  5288.0  308.42  5338.1  309.02  5388.3  306.81  5404.4  307.58
#Mann=4,-1,0
  4794.8    0.16       0  4867.8    0.12       0  5034.4    0.07       0
  5040.4    0.12       0
Bank Sta=5034.4,5040.4
Exp/Cntr=0.3,0.1

Type RM Length L Ch R = 1,986,288,288,288
BEGIN DESCRIPTION:
UNT 074 IN BOCR 2.0
END DESCRIPTION:
XS GIS Cut Line= 3
      3765549.62     10569360.19      3765399.61     10569260.19
      3765199.60     10569160.19
#Sta/Elev= 30
  4837.8  297.51  4840.8  297.51  4851.3  291.60  4860.3  290.34  4866.4  287.84
  4873.9  286.49  4881.4  284.49  4896.4  283.22  4902.4  281.85  4917.4  280.89
  4932.5  279.23  4956.5  279.04  4959.2  278.54  4962.5  279.04  5040.4  279.54
  5048.8  280.02  5054.4  280.89  5062.8  281.25  5076.8  282.96  5121.5  284.58
  5138.3  285.85  5152.2  289.28  5160.6  292.75  5174.6  294.84  5188.6  298.15
  5210.9  300.42  5227.7  303.82  5233.3  304.04  5238.9  305.99  5241.7  305.99
#Mann=3,-1,0
  4837.8    0.16       0  4956.5   0.033       0  4962.5    0.05       0
Bank Sta=4956.5,4962.5
Exp/Cntr=0.3,0.1

Type RM Length L Ch R = 1,698,71,71,71
BEGIN DESCRIPTION:
Mapping XS a2113f2b
END DESCRIPTION:
XS GIS Cut Line= 2
      3765923.08     10569116.45      3765192.94     10568970.94
#Sta/Elev= 30
  4670.1  299.62  4673.3  299.62  4677.6  297.56  4704.2  297.08  4716.8  295.78
  4734.8  293.44  4745.0  293.53  4779.8  290.30  4785.8  287.93  4816.4  284.45
  4825.8  281.49  4857.2  278.95  4916.9  279.31  5007.1  278.81  5009.9  278.31
  5013.1  278.81  5152.9  279.73  5188.4  283.48  5203.9  286.59  5214.1  287.21
  5224.3  290.02  5254.8  292.63  5265.0  295.09  5290.5  297.55  5295.6  299.25
  5326.2  302.80  5341.6  306.00  5346.7  305.45  5377.2  307.30  5414.6  307.78
#Mann=5,-1,0
  4670.1    0.12       0  4716.8    0.16       0  4916.9    0.05       0
  5007.1   0.033       0  5013.1    0.05       0
Bank Sta=5007.1,5013.1
Exp/Cntr=0.3,0.1

Type RM Length L Ch R = 1,627,50,50,50
BEGIN DESCRIPTION:
Mapping XS 6f92d9d0
END DESCRIPTION:
XS GIS Cut Line= 2
      3765956.91     10569048.73      3765219.88     10568921.12
#Sta/Elev= 30
  4679.7  294.29  4701.4  292.83  4737.9  292.57  4757.7  291.39  4768.3  289.51
  4778.4  289.64  4798.7  287.36  4808.9  287.17  4820.9  285.14  4859.6  281.15
  4880.7  281.02  4910.4  282.64  4957.1  282.47  4990.0  281.81  5133.7  282.73
  5166.3  280.35  5169.0  279.85  5172.3  280.35  5204.7  280.96  5214.8  282.92
  5229.0  283.84  5235.1  286.66  5265.6  288.73  5296.0  295.28  5316.3  296.61
  5343.5  301.43  5380.9  303.79  5397.5  305.22  5403.2  306.67  5427.7  307.36
#Mann=6,-1,0
  4679.7    0.12       0  4757.7    0.16       0  4957.1    0.05       0
  5166.3   0.033       0  5172.3    0.05       0  5380.9    0.08       0
Bank Sta=5166.3,5172.3
Exp/Cntr=0.3,0.1

Type RM Length L Ch R = 1,577,150,150,150
BEGIN DESCRIPTION:
Mapping XS d268721d
END DESCRIPTION:
XS GIS Cut Line= 2
      3765959.49     10569012.27      3765238.17     10568858.63
#Sta/Elev= 30
  4688.7  291.10  4698.8  291.79  4729.5  288.94  4739.7  289.64  4768.3  287.60
  4811.3  285.80  4822.7  283.29  4862.0  280.05  4872.6  281.16  4893.1  278.94
  4911.6  278.70  4916.7  277.30  4961.1  277.15  4974.9  275.11  5055.1  275.01
  5079.7  276.21  5094.5  274.62  5097.3  274.12  5100.5  274.62  5118.0  275.73
  5148.7  281.16  5179.3  278.80  5203.8  279.23  5271.4  288.84  5297.8  294.01
  5342.3  298.32  5347.4  297.51  5353.2  299.64  5377.7  301.91  5426.2  305.20
#Mann=6,-1,0
  4688.7    0.12       0  4768.3    0.16       0  5079.7    0.05       0
  5094.5    0.07       0  5100.5    0.05       0  5377.7    0.08       0
Bank Sta=5094.5,5100.5
Exp/Cntr=0.3,0.1

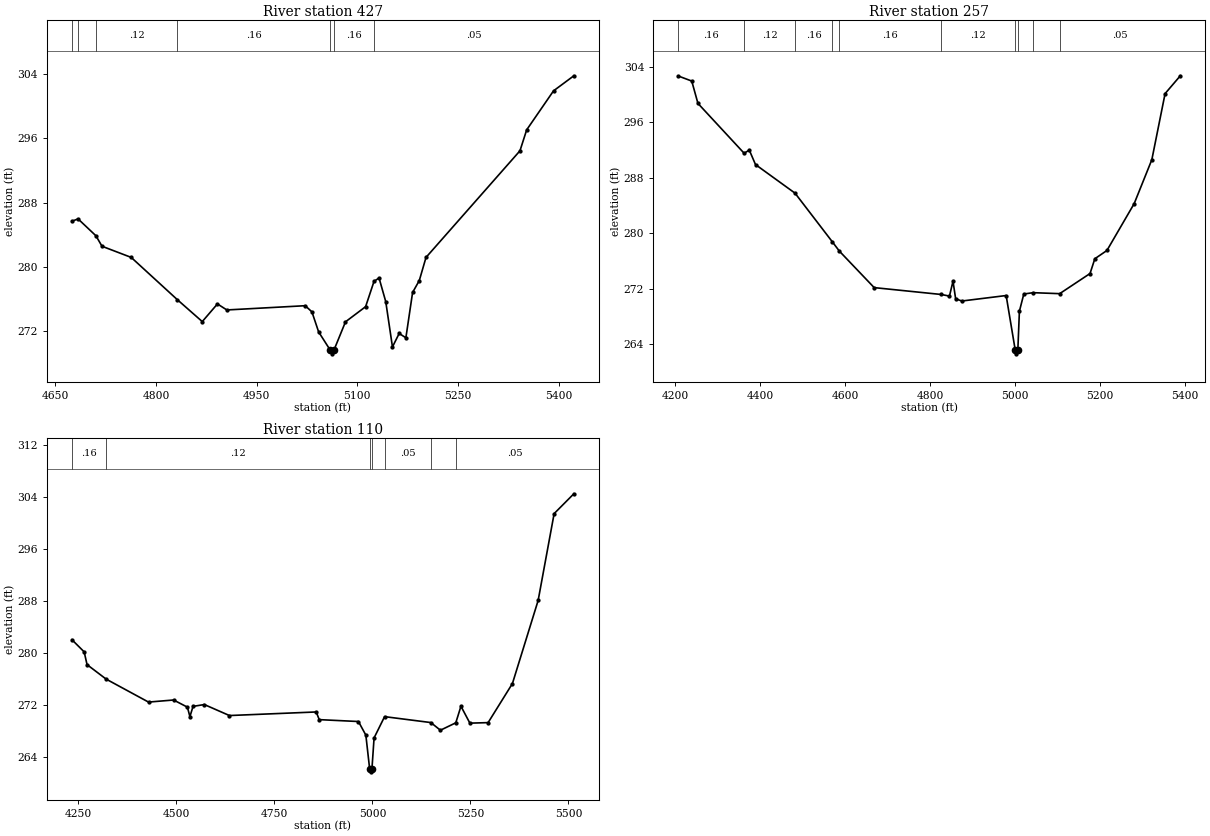
Type RM Length L Ch R = 1,427,170,170,170
BEGIN DESCRIPTION:
Mapping XS 1ecab600
END DESCRIPTION:
XS GIS Cut Line= 3
      3765912.01     10568961.11      3765703.68     10568799.66
      3765219.35     10568799.66
#Sta/Elev= 30
  4674.9  285.67  4684.0  285.96  4710.6  283.86  4719.7  282.55  4763.2  281.16
  4832.1  275.88  4869.1  273.16  4891.7  275.36  4905.7  274.61  5022.5  275.14
  5032.5  274.37  5042.5  271.87  5059.5  269.64  5062.3  269.14  5065.5  269.64
  5082.5  273.13  5112.5  275.02  5125.0  278.17  5132.5  278.60  5142.5  275.65
  5152.5  270.00  5162.5  271.68  5172.5  271.14  5182.5  276.79  5192.5  278.28
  5202.5  281.16  5342.5  294.45  5352.5  297.06  5392.5  301.92  5422.8  303.80
#Mann=7,-1,0
  4674.9    0.12       0  4684.0    0.16       0  4710.6    0.12       0
  4832.1    0.16       0  5059.5    0.07       0  5065.5    0.16       0
  5125.0    0.05       0
Bank Sta=5059.5,5065.5
Exp/Cntr=0.3,0.1

Type RM Length L Ch R = 1,257,147,147,147
BEGIN DESCRIPTION:
UNT 074 IN BOCR 1.0
END DESCRIPTION:
XS GIS Cut Line= 3
      3766113.14     10569160.71      3765706.89     10568613.83
      3765225.13     10568751.85
#Sta/Elev= 30
  4207.6  302.63  4239.0  301.91  4253.6  298.69  4362.4  291.51  4374.6  291.96
  4389.2  289.88  4482.3  285.76  4570.3  278.74  4586.9  277.40  4668.8  272.15
  4827.0  271.16  4846.1  270.93  4854.5  273.07  4860.7  270.54  4875.3  270.22
  4979.7  271.01  5001.2  263.11  5003.9  262.61  5007.2  263.11  5010.9  268.75
  5021.3  271.23  5043.3  271.42  5105.8  271.28  5177.3  274.18  5188.6  276.31
  5217.1  277.50  5281.3  284.25  5322.9  290.58  5354.1  300.10  5390.0  302.67
#Mann=10,-1,0
  4207.6    0.16       0  4362.4    0.12       0  4482.3    0.16       0
  4570.3    0.12       0  4586.9    0.16       0  4827.0    0.12       0
  5001.2    0.07       0  5007.2    0.12       0  5043.3    0.12       0
  5105.8    0.05       0
Bank Sta=5001.2,5007.2
Exp/Cntr=0.3,0.1

Type RM Length L Ch R = 1,110,0,0,0
BEGIN DESCRIPTION:
Mapping XS c0e86b91
END DESCRIPTION:
XS GIS Cut Line= 5
      3766229.26     10568934.53      3765974.06     10568616.83
      3765569.54     10568481.41      3765496.63     10568493.57
      3765156.35     10568644.60
#Sta/Elev= 30
  4233.5  282.06  4264.7  280.19  4272.0  278.23  4320.8  276.00  4428.8  272.47
  4492.8  272.79  4528.0  271.69  4534.4  270.23  4542.4  271.81  4571.2  272.09
  4635.2  270.40  4856.6  270.95  4864.3  269.77  4964.3  269.48  4983.2  267.39
  4992.8  262.24  4995.6  261.74  4998.8  262.24  5004.2  266.96  5031.0  270.23
  5149.0  269.32  5173.4  268.14  5212.6  269.28  5225.8  271.83  5248.6  269.23
  5295.1  269.31  5357.1  275.32  5422.7  288.10  5463.5  301.46  5513.8  304.51
#Mann=7,-1,0
  4233.5    0.16       0  4320.8    0.12       0  4992.8    0.07       0
  4998.8    0.12       0  5031.0    0.05       0  5149.0    0.07       0
  5212.6    0.05       0
Bank Sta=4992.8,4998.8
Exp/Cntr=0.3,0.1

Chan Stop Cuts=-1