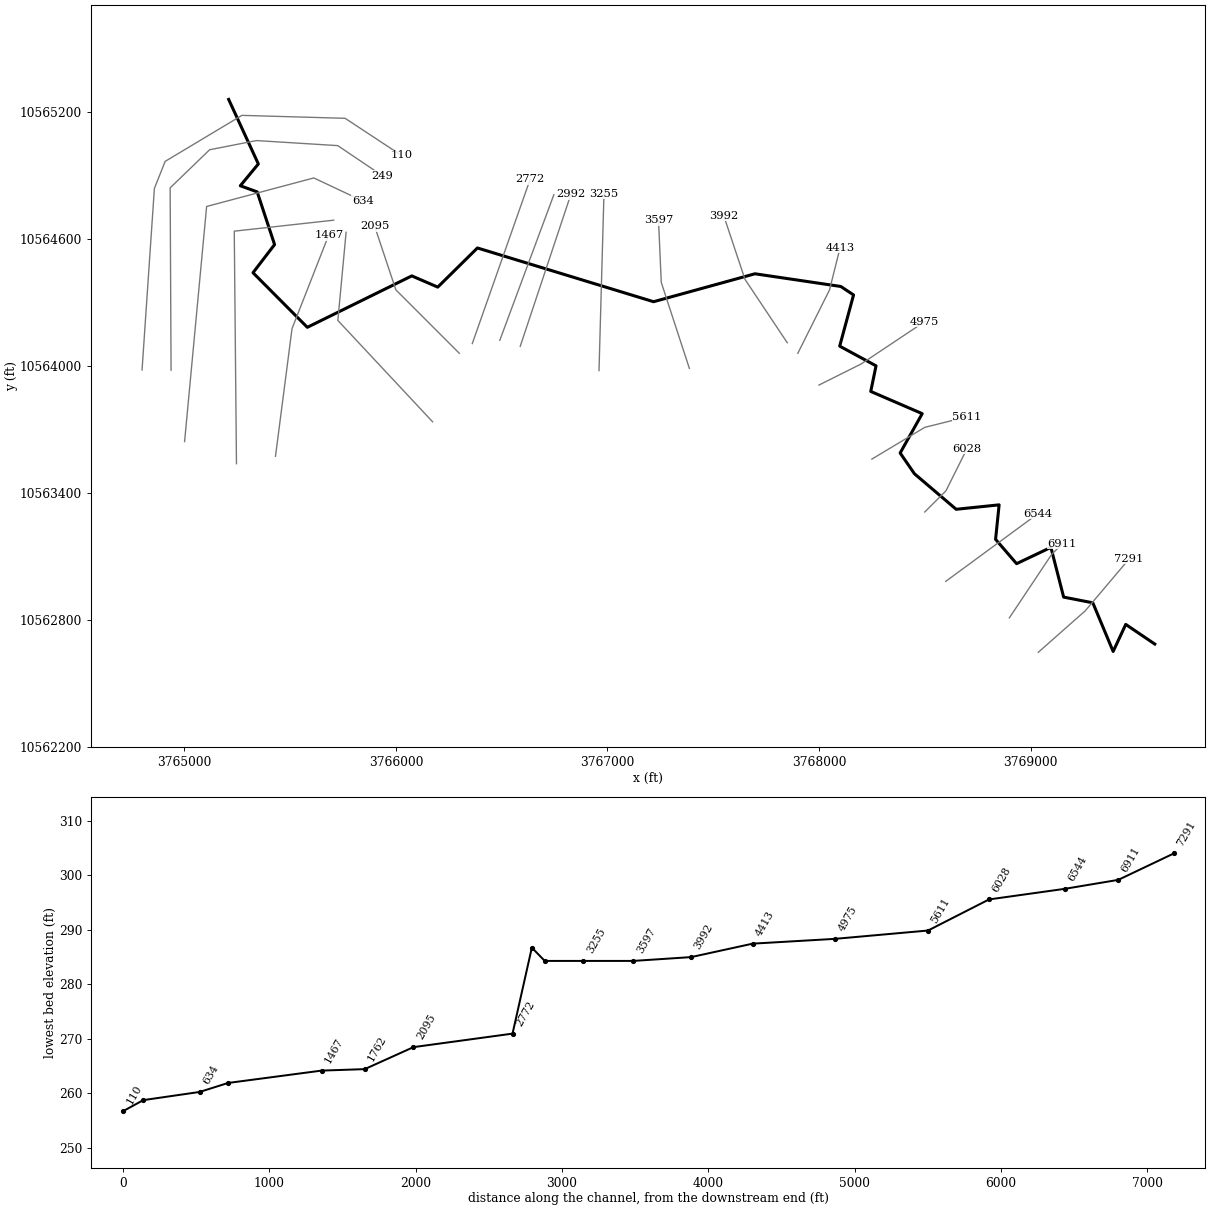
--- UNT 075 IN BOCR.prj (project) ---

Proj Title=UNT 075 IN BOCR Base Level Engineering
Current Plan=p01
Default Exp/Contr=0.3,0.1
English Units
Geom File=g01
Flow File=f01
Plan File=p01
Y Axis Title=Elevation
X Axis Title(PF)=Main Channel Distance
X Axis Title(XS)=Station
BEGIN DESCRIPTION:
UNT 075 IN BOCR
END DESCRIPTION:
DSS Export Rating Curves= 0
DSS Export Rating Curve Sorted= 0
DSS Export Volume Flow Curves= 0
DXF OffsetX= 0
DXF OffsetY= 0
DXF ScaleX= 1
DXF ScaleY= 10

--- UNT 075 IN BOCR.p01 (plan) ---

Plan Title=Multiple Run
Short Identifier=Multiple
Geom File=g01
Flow File=f01
Subcritical Flow
K Sum by GR= 0
Std Step Tol= 0.01
Critical Tol= 0.01
Num of Std Step Trials= 20
Max Error Tol= 0.3
Flow Tol Ratio= 0.001
Split Flow NTrial= 30
Split Flow Tol= 0.02
Split Flow Ratio= 0.02
Log Output Level= 0
Friction Slope Method= 1
Unsteady Friction Slope Method= 2
Unsteady Bridges Friction Slope Method= 1
Parabolic Critical Depth
Global Vel Dist=  1 , 1 , 1
Global Log Level= 0
CheckData=True
Encroach Param= -1, 0, 0, 0
BEGIN DESCRIPTION:
Multiple Run
END DESCRIPTION:

--- UNT 075 IN BOCR.f01 (steady flow) ---

Flow Title=Multiple
Program Version=4.10
Number of Profiles= 7
Profile Names=10-year,25-year,50-year,1pct_min,100-year,1pct_plu,500-year
River Rch & RM=UNT 075 IN BOCR,Reach-1         ,7291
     678     923    1128    1012    1368    1851    2023
Boundary for River Rch & Prof#=UNT 075 IN BOCR,Reach-1         , 1
Up Type= 0
Dn Type= 3
Dn Slope=0.007
Boundary for River Rch & Prof#=UNT 075 IN BOCR,Reach-1         , 2
Up Type= 0
Dn Type= 3
Dn Slope=0.007
Boundary for River Rch & Prof#=UNT 075 IN BOCR,Reach-1         , 3
Up Type= 0
Dn Type= 3
Dn Slope=0.007
Boundary for River Rch & Prof#=UNT 075 IN BOCR,Reach-1         , 4
Up Type= 0
Dn Type= 3
Dn Slope=0.007
Boundary for River Rch & Prof#=UNT 075 IN BOCR,Reach-1         , 5
Up Type= 0
Dn Type= 3
Dn Slope=0.007
Boundary for River Rch & Prof#=UNT 075 IN BOCR,Reach-1         , 6
Up Type= 0
Dn Type= 3
Dn Slope=0.007
Boundary for River Rch & Prof#=UNT 075 IN BOCR,Reach-1         , 7
Up Type= 0
Dn Type= 3
Dn Slope=0.007
DSS Import GetInterval= 0
DSS Import GetPeak= 0
DSS Import FillOption= 0

--- UNT 075 IN BOCR.g01 (geometry) ---

Geom Title=Existing Conditions
Program Version=4.10

River Reach=UNT 075 IN BOCR ,Reach-1
Reach XY= 30
      3769586.73     10562686.09       3769449.5       10562779.
        3769390.       10562651.        3769294.       10562881.
        3769156.       10562908.      3769095.75       10563143.
       3768933.5       10563066.      3768834.25       10563181.
        3768851.       10563344.        3768648.       10563323.
      3768450.75       10563491.      3768383.25       10563589.
       3768487.5       10563775.      3768244.25       10563880.
      3768269.25       10564001.       3768097.5       10564094.
        3768163.       10564336.      3768102.75       10564376.
        3767697.       10564436.      3767217.75       10564304.
      3766385.25       10564558.      3766197.75       10564373.
        3766075.       10564426.      3765581.25       10564183.
       3765324.5       10564441.       3765426.5       10564574.
      3765344.25       10564823.       3765264.5       10564852.
      3765349.75       10564955.       3765209.5       10565260.

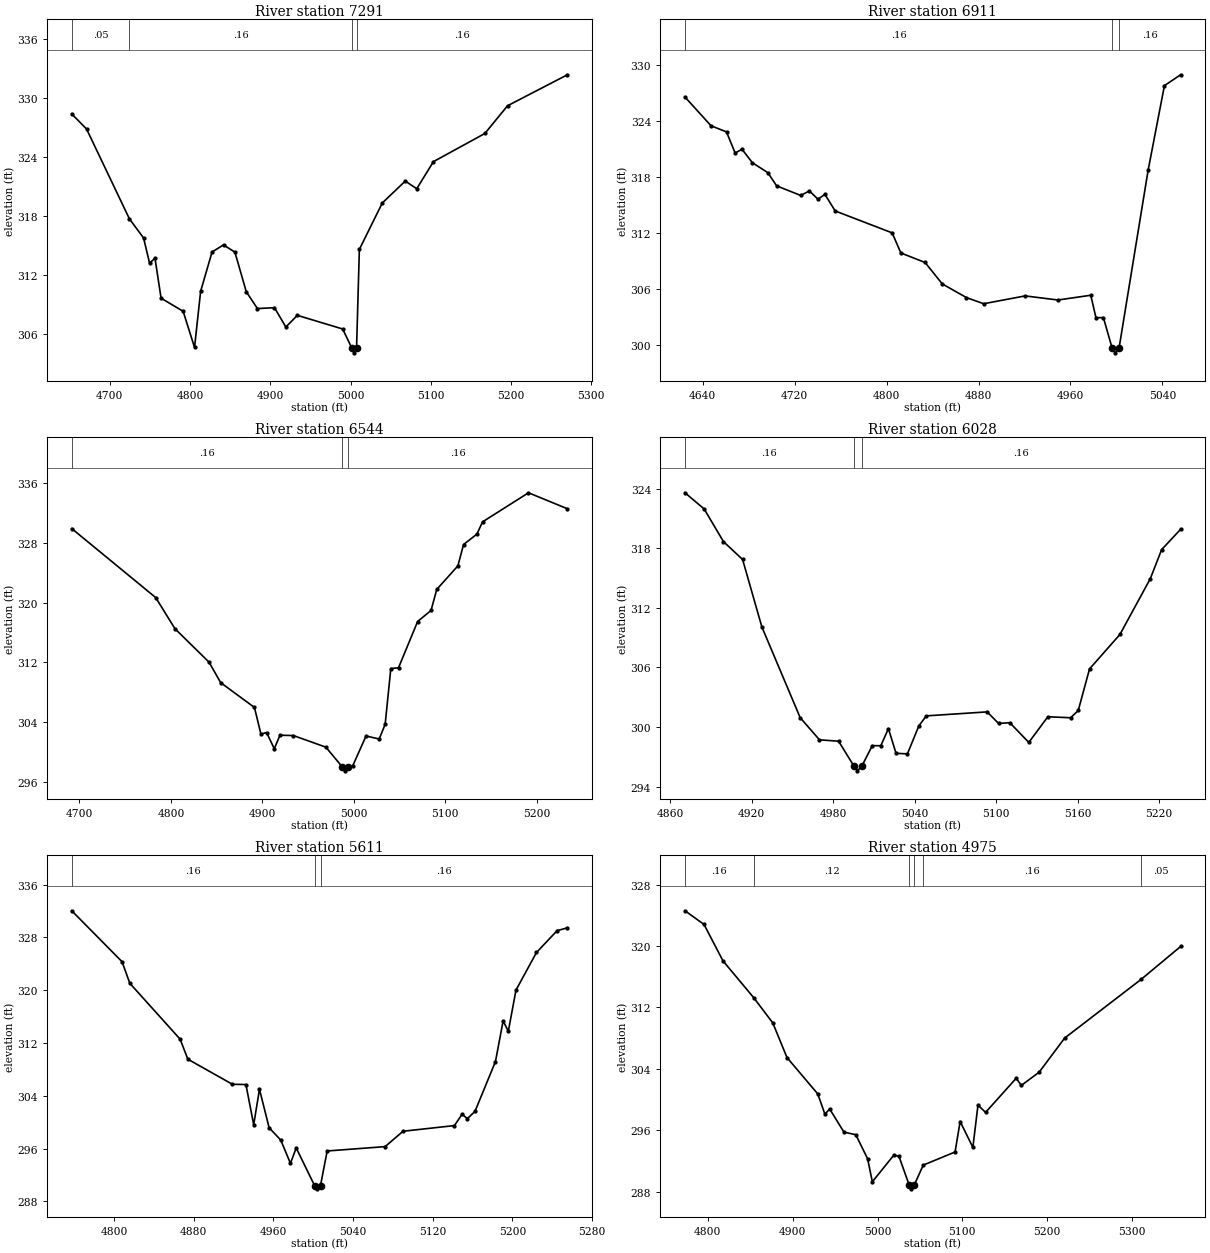
Type RM Length L Ch R = 1 ,7291    ,380,380,380
BEGIN DESCRIPTION:
UNT 075 IN BOCR 14.0
END DESCRIPTION:
XS GIS Cut Line= 3
      3769036.13     10562647.21      3769258.34     10562843.38
      3769465.65      10563088.7
#Sta/Elev= 30
  4652.6  328.39    4671  326.86  4724.4  317.71  4742.1  315.75  4749.6  313.18
  4756.3   313.7  4763.9  309.62  4791.4  308.28  4805.6   304.6  4813.2  310.32
  4827.4  314.32  4841.7  315.05  4855.9  314.31  4870.1  310.27    4884  308.56
  4905.2  308.65  4919.4  306.68  4933.7  307.87  4990.2  306.48  5001.5  304.55
  5004.2  304.05  5007.5  304.55    5011  314.59  5039.6  319.32  5068.2  321.55
  5082.5  320.77  5103.3  323.53  5167.4   326.4  5195.6  329.22  5270.2  332.38
#Mann= 4 ,-1 , 0
  4652.6     .05       0  4724.4     .16       0  5001.5     .07       0
  5007.5     .16       0
Bank Sta=5001.5,5007.5
XS Rating Curve= 0 ,0
Exp/Cntr=0.3,0.1

Type RM Length L Ch R = 1 ,6911    ,367,367,367
BEGIN DESCRIPTION:
UNT 075 IN BOCR 13.0
END DESCRIPTION:
XS GIS Cut Line= 3
      3768899.59     10562810.16      3769099.61     10563110.19
      3769149.61     10563160.19
#Sta/Elev= 30
  4624.6  326.59  4647.2  323.52  4660.7  322.86  4668.2   320.6  4674.2     321
  4683.2  319.56  4696.7  318.49  4704.3  317.08  4725.3  316.05  4732.8  316.54
  4740.3  315.65  4746.3  316.17  4755.3  314.39  4804.9  312.04  4812.4  309.89
  4833.5  308.87  4848.5  306.57  4869.5  305.11  4884.5  304.45  4920.6  305.29
  4949.1  304.85  4977.7  305.36  4982.2  302.96  4988.7  302.96  4996.3  299.69
  4999.1  299.19  5002.3  299.69  5027.6  318.75  5041.8  327.82  5055.9  328.98
#Mann= 3 ,-1 , 0
  4624.6     .16       0  4996.3     .07       0  5002.3     .16       0
Bank Sta=4996.3,5002.3
XS Rating Curve= 0 ,0
Exp/Cntr=0.3,0.1

Type RM Length L Ch R = 1 ,6544    ,516,516,516
BEGIN DESCRIPTION:
UNT 075 IN BOCR 12.0
END DESCRIPTION:
XS GIS Cut Line= 2
      3768598.65     10562982.29       3769035.4     10563302.92
#Sta/Elev= 30
  4691.6  329.87  4783.4  320.66  4804.4  316.51  4841.7  312.04  4854.4  309.31
  4891.3     306  4898.4  302.45  4904.6  302.65    4913  300.49  4919.2  302.29
  4933.9  302.25  4969.4   300.7  4987.5  298.04  4990.3  297.54  4993.5  298.04
  4998.7  298.19  5013.3  302.19  5027.7  301.79  5034.2  303.75  5040.4  311.19
  5048.8  311.29  5069.7  317.47  5084.4  318.95  5090.6  321.75  5113.7  324.89
  5119.9  327.74  5134.5  329.13  5140.7  330.77  5190.9  334.65  5233.4  332.52
#Mann= 3 ,-1 , 0
  4691.6     .16       0  4987.5     .07       0  4993.5     .16       0
Bank Sta=4987.5,4993.5
XS Rating Curve= 0 ,0
Exp/Cntr=0.3,0.1

Type RM Length L Ch R = 1 ,6028    ,417,417,417
BEGIN DESCRIPTION:
UNT 075 IN BOCR 11.0
END DESCRIPTION:
XS GIS Cut Line= 3
      3768499.62      10563310.2      3768599.61     10563410.19
       3768699.6     10563610.17
#Sta/Elev= 30
  4870.9  323.57    4885  321.94  4899.2  318.66  4913.3  316.86  4927.5  310.07
  4955.7  300.95  4969.9  298.72    4984  298.58  4995.2   296.1  4997.9   295.6
  5001.2   296.1  5008.8  298.13  5015.1  298.13  5020.7  299.85  5026.3  297.36
  5034.7  297.31  5043.1  300.12  5048.6  301.13  5093.4  301.53  5101.8  300.37
  5110.1  300.44  5124.1  298.46  5138.1  301.04  5154.9  300.94  5160.5  301.67
  5168.8  305.85  5191.2  309.32  5213.6  314.94  5221.9  317.85  5235.9   319.9
#Mann= 3 ,-1 , 0
  4870.9     .16       0  4995.2     .07       0  5001.2     .16       0
Bank Sta=4995.2,5001.2
XS Rating Curve= 0 ,0
Exp/Cntr=0.3,0.1

Type RM Length L Ch R = 1 ,5611    ,636,636,636
BEGIN DESCRIPTION:
UNT 075 IN BOCR 10.0
END DESCRIPTION:
XS GIS Cut Line= 3
      3768249.63      10563560.2      3768499.61     10563710.19
      3768699.64      10563760.2
#Sta/Elev= 30
  4757.5  332.04    4808  324.32  4815.8  321.05  4866.3  312.58  4874.1  309.54
  4918.8  305.74  4932.4   305.7  4940.2  299.61    4946  304.98  4955.7  299.15
  4967.4  297.28  4977.1  293.75  4982.9  296.09  5001.3  290.39  5004.1  289.89
  5007.3  290.39    5014  295.63  5072.2  296.29  5090.2  298.62  5141.8  299.48
  5149.5  301.21  5154.7  300.53  5162.4  301.62    5183  309.19  5190.7  315.35
  5195.9  313.77  5203.6  320.02  5224.2  325.72  5244.9  329.03  5255.2  329.45
#Mann= 3 ,-1 , 0
  4757.5     .16       0  5001.3     .07       0  5007.3     .16       0
Bank Sta=5001.3,5007.3
XS Rating Curve= 0 ,0
Exp/Cntr=0.3,0.1

Type RM Length L Ch R = 1 ,4975    ,562,562,562
BEGIN DESCRIPTION:
UNT 075 IN BOCR 9.0
END DESCRIPTION:
XS GIS Cut Line= 3
      3767999.59     10563910.18      3768199.61     10564010.19
      3768499.63      10564210.2
#Sta/Elev= 30
  4773.1  324.58  4795.5   322.8  4817.8  318.06  4854.2  313.24  4876.5  309.98
  4893.3  305.46  4929.6  300.72    4938  298.08  4943.6  298.77  4960.4  295.75
  4974.4  295.41  4988.3  292.28  4993.9  289.28  5019.3  292.76  5025.3  292.59
  5037.3  288.86    5040  288.36  5043.3  288.86  5053.9  291.45  5091.4  293.16
  5097.4  297.13  5112.4  293.76  5118.4  299.26  5127.4  298.32  5163.5  302.77
  5169.5  301.83  5190.5  303.55  5220.6     308  5310.9  315.66  5357.3  319.93
#Mann= 6 ,-1 , 0
  4773.1     .16       0  4854.2     .12       0  5037.3     .07       0
  5043.3     .12       0  5053.9     .16       0  5310.9     .05       0
Bank Sta=5037.3,5043.3
XS Rating Curve= 0 ,0
Exp/Cntr=0.3,0.1

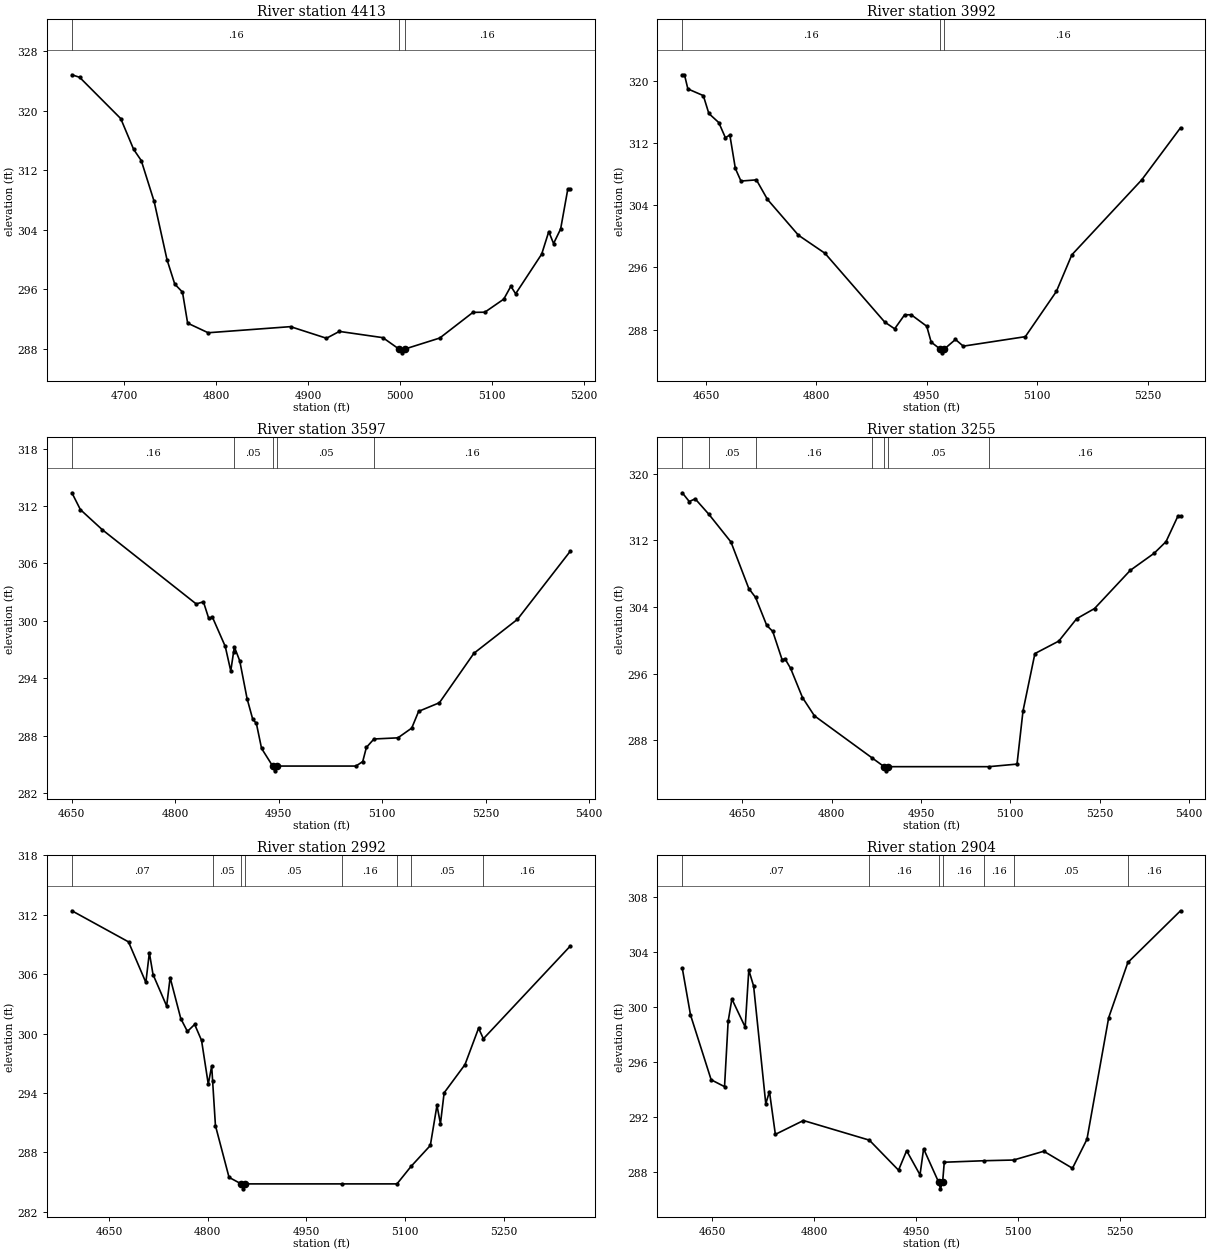
Type RM Length L Ch R = 1 ,4413    ,421,421,421
BEGIN DESCRIPTION:
UNT 075 IN BOCR 8.0
END DESCRIPTION:
XS GIS Cut Line= 3
      3767899.62     10564060.21      3768049.61     10564360.19
       3768099.6     10564560.15
#Sta/Elev= 30
  4643.3  324.85  4651.7  324.51  4696.4  318.96  4710.4  314.83  4718.7  313.32
  4732.7  307.82  4746.7  299.99  4755.1  296.72  4763.5  295.64  4769.1  291.47
  4791.4  290.18  4880.9     291    4920  289.44    4934  290.36  4981.3  289.52
  4998.9  287.98  5001.6  287.48  5004.9  287.98  5043.1  289.47  5079.2  292.92
  5092.1  292.94  5112.7   294.7  5120.4  296.43  5125.6  295.42  5153.9  300.75
  5161.6  303.77  5166.8  302.17  5174.5  304.13  5182.3   309.5  5184.8   309.5
#Mann= 3 ,-1 , 0
  4643.3     .16       0  4998.9     .07       0  5004.9     .16       0
Bank Sta=4998.9,5004.9
XS Rating Curve= 0 ,0
Exp/Cntr=0.3,0.1

Type RM Length L Ch R = 1 ,3992    ,395,395,395
BEGIN DESCRIPTION:
UNT 075 IN BOCR 7.0
END DESCRIPTION:
XS GIS Cut Line= 3
      3767849.63     10564110.16      3767649.61     10564410.19
      3767549.62     10564710.17
#Sta/Elev= 30
  4617.9  320.78  4620.9  320.78  4625.5  318.96  4646.5   318.1    4654   315.8
  4667.5  314.63  4676.5  312.68  4682.5  313.04    4690  308.73  4697.6  307.11
  4718.6  307.26  4733.6  304.75  4775.7  300.14  4811.7  297.82  4892.9  288.97
  4906.4   288.1  4919.9   289.9  4928.9  289.91    4950  288.43    4956  286.39
    4968  285.51  4970.7  285.01    4974  285.51    4989  286.73  4999.6  285.87
  5083.9  287.09  5126.1  292.91  5147.1  297.62    5242  307.26  5294.7  313.96
#Mann= 3 ,-1 , 0
  4617.9     .16       0    4968     .07       0    4974     .16       0
Bank Sta=4968,4974
XS Rating Curve= 0 ,0
Exp/Cntr=0.3,0.1

Type RM Length L Ch R = 1 ,3597    ,342,342,342
BEGIN DESCRIPTION:
UNT 075 IN BOCR 6.0
END DESCRIPTION:
XS GIS Cut Line= 3
      3767386.97     10563988.98      3767254.17      10564395.2
      3767241.15     10564689.44
#Sta/Elev= 30
  4650.5  313.38  4662.8  311.62  4694.7  309.51  4830.6  301.76  4841.1  301.98
  4848.8  300.24  4854.1  300.38  4872.7  297.32  4880.7  294.75  4884.7  296.69
  4885.9  297.27  4893.7  295.81  4904.3  291.87  4912.5  289.71  4917.8  289.27
  4925.3  286.66  4941.4  284.81  4944.2  284.31  4947.4  284.81  5062.1  284.81
  5071.9  285.28  5077.2  286.76  5088.2  287.64  5122.9  287.76  5142.9  288.78
  5152.9  290.53    5183  291.43    5233   296.6  5296.1  300.15  5372.4  307.25
#Mann= 5 ,-1 , 0
  4650.5     .16       0  4884.7     .05       0  4941.4    .033       0
  4947.4     .05       0  5088.2     .16       0
Bank Sta=4941.4,4947.4
XS Rating Curve= 0 ,0
Exp/Cntr=0.3,0.1

Type RM Length L Ch R = 1 ,3255    ,263,263,263
BEGIN DESCRIPTION:
UNT 075 IN BOCR 5.0
END DESCRIPTION:
XS GIS Cut Line= 2
       3766959.9     10563978.48      3766983.34     10564814.46
#Sta/Elev= 30
  4549.3  317.72    4561  316.67    4571  316.99    4594  315.13    4631  311.81
    4661  306.21  4672.3  305.15  4691.1  301.78  4701.1  301.07  4716.8  297.68
  4721.8  297.76  4731.1  296.63  4751.1  293.11  4771.1  290.92  4867.4  285.89
  4888.1  284.81  4890.9  284.31  4894.1  284.81  5063.9  284.81  5111.2  285.12
  5121.2  291.49  5141.2   298.4  5181.3   299.9  5211.3  302.59  5241.3  303.81
  5301.3   308.4  5341.3  310.45  5361.3  311.85    5381  314.88  5385.6  314.88
#Mann= 7 ,-1 , 0
  4549.3     .16       0    4594     .05       0  4672.3     .16       0
  4867.4     .05       0  4888.1    .033       0  4894.1     .05       0
  5063.9     .16       0
Bank Sta=4888.1,4894.1
XS Rating Curve= 0 ,0
Exp/Cntr=0.3,0.1

Type RM Length L Ch R = 1 ,2992    ,88,88,88
BEGIN DESCRIPTION:
Mapping XS 80e656c4
END DESCRIPTION:
XS GIS Cut Line= 2
      3766587.49     10564093.09       3766827.1     10564811.91
#Sta/Elev= 30
  4593.4   312.4  4679.5  309.26  4705.9  305.16  4711.2  308.16  4716.8  305.96
  4737.5  302.78  4742.8  305.65    4759  301.51  4769.1  300.21  4780.1  300.92
  4790.6   299.3  4800.8  294.89    4806  296.71  4807.4  295.23  4811.7   290.7
  4832.4  285.47  4850.9  284.81  4853.6  284.31  4856.9  284.81  5004.4  284.81
  5087.8  284.81  5109.1  286.57  5138.5  288.69  5148.6  292.74  5153.9  290.89
  5159.5  294.01  5191.2  296.86  5211.9  300.54  5219.2  299.47  5351.1  308.82
#Mann= 8 ,-1 , 0
  4593.4     .07       0  4807.4     .05       0  4850.9    .033       0
  4856.9     .05       0  5004.4     .16       0  5087.8      .1       0
  5109.1     .05       0  5219.2     .16       0
Bank Sta=4850.9,4856.9
XS Rating Curve= 0 ,0
Exp/Cntr=0.3,0.1

Type RM Length L Ch R = 1 ,2904    ,132,132,132
BEGIN DESCRIPTION:
Mapping XS 1048af4a
END DESCRIPTION:
XS GIS Cut Line= 2
      3766491.15     10564121.77      3766746.35     10564809.24
#Sta/Elev= 30
  4606.1  302.84  4618.2  299.43  4648.6   294.7  4668.3   294.2  4673.6  298.95
  4679.1  300.59  4698.7  298.54    4704   302.7  4711.1  301.53    4729  292.95
  4734.4  293.84  4743.1  290.72  4784.4  291.73  4881.4   290.3  4924.4  288.11
  4936.3  289.53    4956  287.77  4961.3  289.67  4983.3  287.25  4986.1  286.75
  4989.3  287.25  4991.7  288.69  5050.7   288.8  5093.7  288.85  5138.2  289.49
  5180.4  288.25  5201.7  290.36  5233.7  299.23  5261.9  303.25  5339.4  307.02
#Mann= 7 ,-1 , 0
  4606.1     .07       0  4881.4     .16       0  4983.3     .03       0
  4989.3     .16       0  5050.7     .16       0  5093.7     .05       0
  5261.9     .16       0
Bank Sta=4983.3,4989.3
XS Rating Curve= 0 ,0
Exp/Cntr=0.3,0.1

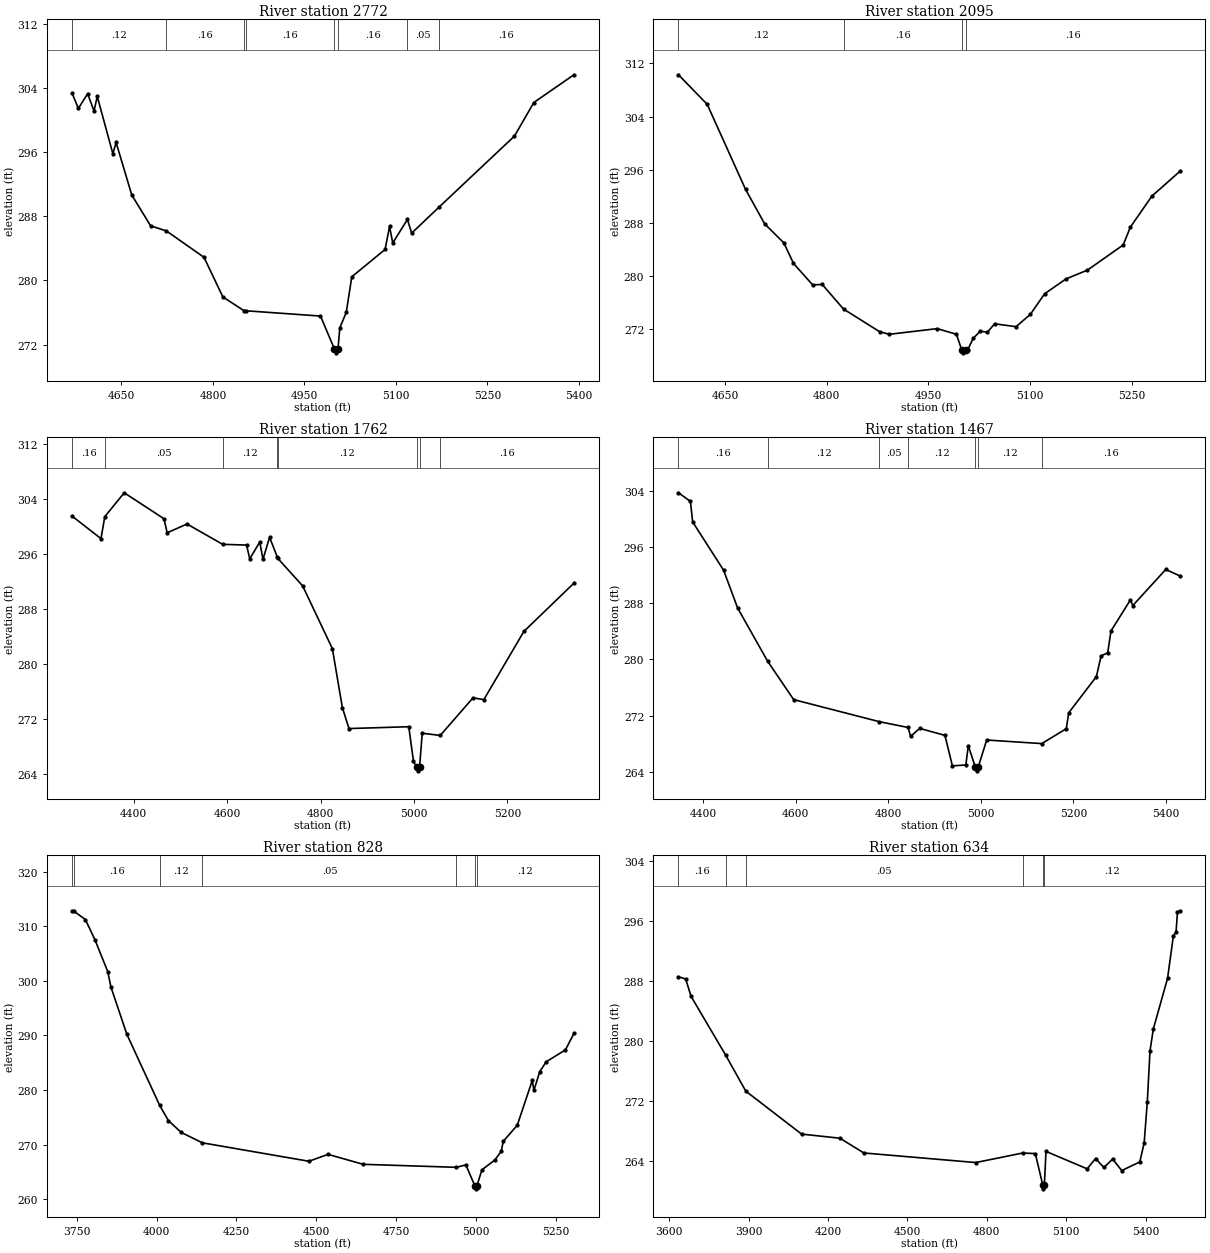
Type RM Length L Ch R = 1 ,2772    ,677,677,677
BEGIN DESCRIPTION:
UNT 075 IN BOCR 4.0
END DESCRIPTION:
XS GIS Cut Line= 2
      3766360.94     10564106.15      3766634.38     10564882.19
#Sta/Elev= 30
    4569  303.37  4579.3  301.46  4594.5   303.3    4605  301.13  4610.3  302.96
  4635.9   295.8  4641.2  297.21  4666.9  290.65  4697.8  286.81  4723.7  286.17
  4785.3  282.88  4816.3  277.93  4850.5  276.24  4853.9  276.21  4976.3  275.55
    4999  271.46  5001.7  270.96    5005  271.46    5008  274.08  5018.6  276.02
  5027.6  280.45  5082.2  283.86  5089.5  286.73  5094.8  284.67  5118.8   287.6
  5125.8   285.9  5170.2  289.11  5294.3  298.01  5326.1   302.2  5391.8  305.66
#Mann= 8 ,-1 , 0
    4569     .12       0  4723.7     .16       0  4850.5     .07       0
  4853.9     .16       0    4999     .07       0    5005     .16       0
  5118.8     .05       0  5170.2     .16       0
Bank Sta=4999,5005
XS Rating Curve= 0 ,0
Exp/Cntr=0.3,0.1

Type RM Length L Ch R = 1 ,2095    ,333,333,333
BEGIN DESCRIPTION:
UNT 075 IN BOCR 3.0
END DESCRIPTION:
XS GIS Cut Line= 3
      3766299.58     10564060.22      3765999.61     10564360.19
      3765899.62     10564660.14
#Sta/Elev= 30
  4581.4  310.29  4623.8  305.84  4680.4  293.05  4708.6  287.87  4736.9  285.01
  4751.1  281.93  4779.3   278.7  4793.5  278.76  4824.9  275.06  4878.3  271.65
  4892.5  271.27  4963.2  272.12  4991.5  271.27  4999.1  268.98  5001.8  268.48
  5005.1  268.98  5008.3  268.98  5016.2  270.66  5026.7  271.74  5037.2  271.58
  5047.8  272.85  5079.4  272.41  5100.5  274.26  5121.6  277.36  5153.2   279.6
  5184.8  280.92  5237.5   284.7  5248.1  287.38  5279.7  292.03  5321.8  295.83
#Mann= 4 ,-1 , 0
  4581.4     .12       0  4824.9     .16       0  4999.1     .07       0
  5005.1     .16       0
Bank Sta=4999.1,5005.1
XS Rating Curve= 0 ,0
Exp/Cntr=0.3,0.1

Type RM Length L Ch R = 1 ,1762    ,295,295,295
BEGIN DESCRIPTION:
UNT 075 IN BOCR 2.0
END DESCRIPTION:
XS GIS Cut Line= 3
      3766173.47     10563736.31      3765725.52     10564215.51
      3765764.59     10564632.22
#Sta/Elev= 30
    4268  301.56  4329.9  298.28  4338.1  301.49  4379.7  304.96  4464.7  301.18
  4471.6  299.13  4514.1  300.41  4590.4  297.45  4641.6  297.34  4648.4  295.34
  4669.9  297.78  4676.7  295.26  4690.9  298.47  4707.7  295.54  4708.6  295.39
  4761.7  291.39  4825.3  282.25  4846.7  273.66  4860.9   270.6  4988.9  270.87
    4999  265.83    5006  264.94  5008.8  264.44    5012  264.94  5017.7  269.92
  5056.3   269.6  5126.5  275.08  5149.6  274.81  5235.3  284.75  5342.5  291.79
#Mann= 8 ,-1 , 0
    4268     .16       0  4338.1     .05       0  4590.4     .12       0
  4707.7     .16       0  4708.6     .12       0    5006     .07       0
    5012     .12       0  5056.3     .16       0
Bank Sta=5006,5012
XS Rating Curve= 0 ,0
Exp/Cntr=0.3,0.1

Type RM Length L Ch R = 1 ,1467    ,639,639,639
BEGIN DESCRIPTION:
Mapping XS b48706a7
END DESCRIPTION:
XS GIS Cut Line= 3
      3765430.82     10563573.48      3765508.95     10564176.79
      3765682.57     10564619.52
#Sta/Elev= 30
  4347.1  303.68  4372.8  302.46  4377.8  299.53  4444.6  292.67  4474.9   287.3
  4539.5  279.76  4595.9  274.29  4781.2  271.15  4843.1  270.33  4848.4  269.06
  4868.1   270.2  4922.6  269.21  4938.7  264.88  4967.7     265  4973.1  267.75
  4988.3  264.67  4991.1  264.17  4994.3  264.67  5012.8  268.55  5131.8  268.04
  5184.7  270.16  5190.1  272.43  5249.7  277.56  5259.9   280.5  5274.1  280.94
  5281.3  284.05    5323  288.44  5328.4  287.66  5399.5  292.78    5431  291.84
#Mann= 7 ,-1 , 0
  4347.1     .16       0  4539.5     .12       0  4781.2     .05       0
  4843.1     .12       0  4988.3     .07       0  4994.3     .12       0
  5131.8     .16       0
Bank Sta=4988.3,4994.3
XS Rating Curve= 0 ,0
Exp/Cntr=0.3,0.1

Type RM Length L Ch R = 1 ,828     ,194,194,194
BEGIN DESCRIPTION:
UNT 075 IN BOCR 1.0
END DESCRIPTION:
XS GIS Cut Line= 3
      3765246.36     10563538.47      3765235.94     10564637.39
      3765705.92     10564689.32
#Sta/Elev= 30
  3735.2  312.81  3740.4  312.76  3776.9   311.2  3806.9  307.49  3846.9  301.68
  3856.9  298.85  3906.9  290.18  4009.5  277.19  4036.9   274.4  4076.9  272.23
  4143.7  270.32  4476.9  266.95  4536.9  268.21    4647  266.39  4939.1  265.84
  4968.6  266.29    4997   262.4  4999.8   261.9    5003   262.4  5018.9  265.39
  5059.2  267.17  5079.3  268.76  5085.8   270.6  5129.6  273.55  5176.6  281.75
  5181.6  279.91    5200  283.35  5220.2  285.16  5280.5  287.35    5307  290.35
#Mann= 7 ,-1 , 0
  3735.2     .05       0  3740.4     .16       0  4009.5     .12       0
  4143.7     .05       0  4939.1     .12       0    4997     .07       0
    5003     .12       0
Bank Sta=4997,5003
XS Rating Curve= 0 ,0
Exp/Cntr=0.3,0.1

Type RM Length L Ch R = 1 ,634     ,385,385,385
BEGIN DESCRIPTION:
Mapping XS 861732f4
END DESCRIPTION:
XS GIS Cut Line= 4
      3765001.14     10563642.96       3765105.3     10564754.05
      3765611.88     10564888.89      3765843.19     10564780.07
#Sta/Elev= 30
  3635.2  288.57  3662.5  288.27  3682.6  285.96  3813.3  278.11  3889.4   273.3
  4100.2  267.56  4245.1  267.01  4335.5  265.04  4758.2  263.76  4934.9  265.03
  4983.3  264.96  5011.3  260.75  5014.1  260.25  5017.3  260.75  5023.6  265.25
    5179  262.92  5210.9   264.3    5242   263.1  5275.4  264.23  5309.6  262.69
  5377.9  263.84  5394.4  266.37  5406.3  271.89  5416.5  278.69  5429.1  281.61
  5482.8  288.36  5504.9  294.07  5514.7  294.48  5520.3  297.24    5531  297.38
#Mann= 6 ,-1 , 0
  3635.2     .16       0  3813.3     .12       0  3889.4     .05       0
  4934.9     .12       0  5011.3     .07       0  5017.3     .12       0
Bank Sta=5011.3,5017.3
XS Rating Curve= 0 ,0
Exp/Cntr=0.3,0.1

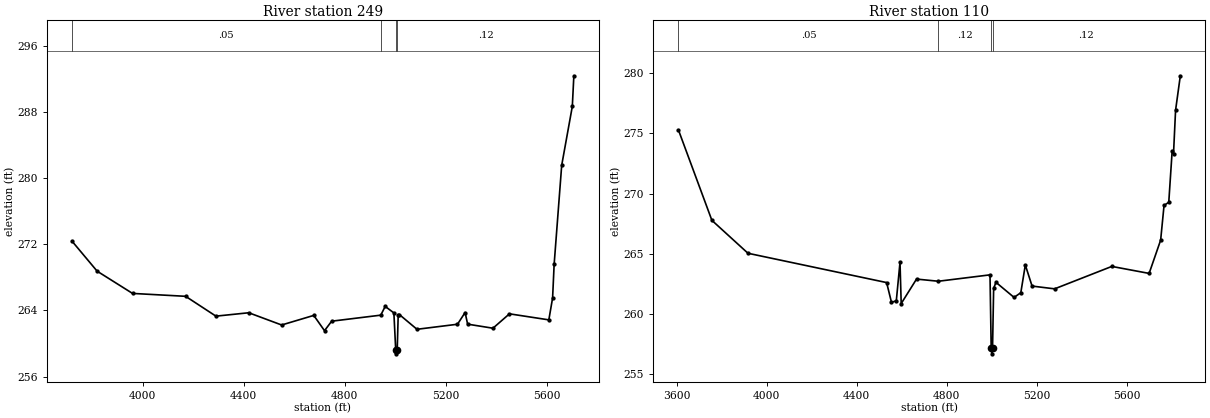
Type RM Length L Ch R = 1 ,249     ,139,139,139
BEGIN DESCRIPTION:
Mapping XS e7fdb239
END DESCRIPTION:
XS GIS Cut Line= 6
      3764937.25     10563980.51      3764932.91     10564842.02
      3765119.54     10565022.15       3765340.9     10565065.55
      3765725.01     10565041.68      3765936.17     10564899.47
#Sta/Elev= 30
  3720.4  272.39  3820.1  268.75  3960.1  266.06  4170.1  265.71  4290.1  263.31
  4420.1  263.72  4550.1  262.24  4677.2   263.4  4719.7  261.55    4748   262.7
  4942.4  263.43  4959.8  264.49  4994.2   263.7  5001.4  259.25  5004.2  258.75
  5007.4  259.25  5011.3  263.44  5016.4  263.49  5085.6  261.72  5245.9  262.33
    5276  263.75    5286  262.34  5386.2  261.85  5451.5  263.59  5607.3  262.86
  5622.2  265.51  5628.3  269.57  5658.2  281.56  5700.2  288.68  5706.3  292.39
#Mann= 4 ,-1 , 0
  3720.4     .05       0  4942.4     .12       0  5001.4     .07       0
  5007.4     .12       0
Bank Sta=5001.4,5007.4
XS Rating Curve= 0 ,0
Exp/Cntr=0.3,0.1

Type RM Length L Ch R = 1 ,110     ,0,0,0
BEGIN DESCRIPTION:
Mapping XS 8a67b3a3
END DESCRIPTION:
XS GIS Cut Line= 6
      3764800.12      10563981.8      3764858.42     10564839.33
      3764909.26      10564967.2      3765272.22     10565184.64
      3765759.91     10565170.79      3766025.61      10564995.8
#Sta/Elev= 30
  3607.5  275.28  3756.2  267.78  3916.6  265.05  4532.5  262.62    4554  260.98
  4575.5  261.11  4591.9   264.3  4597.2  260.88  4665.3  262.91  4762.3  262.73
  4991.7  263.26    4997  257.21  4999.8  256.71    5003  257.21  5007.9  262.14
  5018.2  262.64  5098.6  261.39  5128.6  261.78  5148.6  264.08  5178.6  262.33
  5278.7   262.1  5532.9  263.96  5698.6  263.38  5749.8  266.14  5764.9  269.02
  5785.9  269.28    5801  273.55    5807  273.32  5816.1  276.91  5837.2  279.77
#Mann= 4 ,-1 , 0
  3607.5     .05       0  4762.3     .12       0    4997     .07       0
    5003     .12       0
Bank Sta=4997,5003
XS Rating Curve= 0 ,0
Exp/Cntr=0.3,0.1

Chan Stop Cuts=-1
Use User Specified Reach Order=0
Composite Channel Slope=5