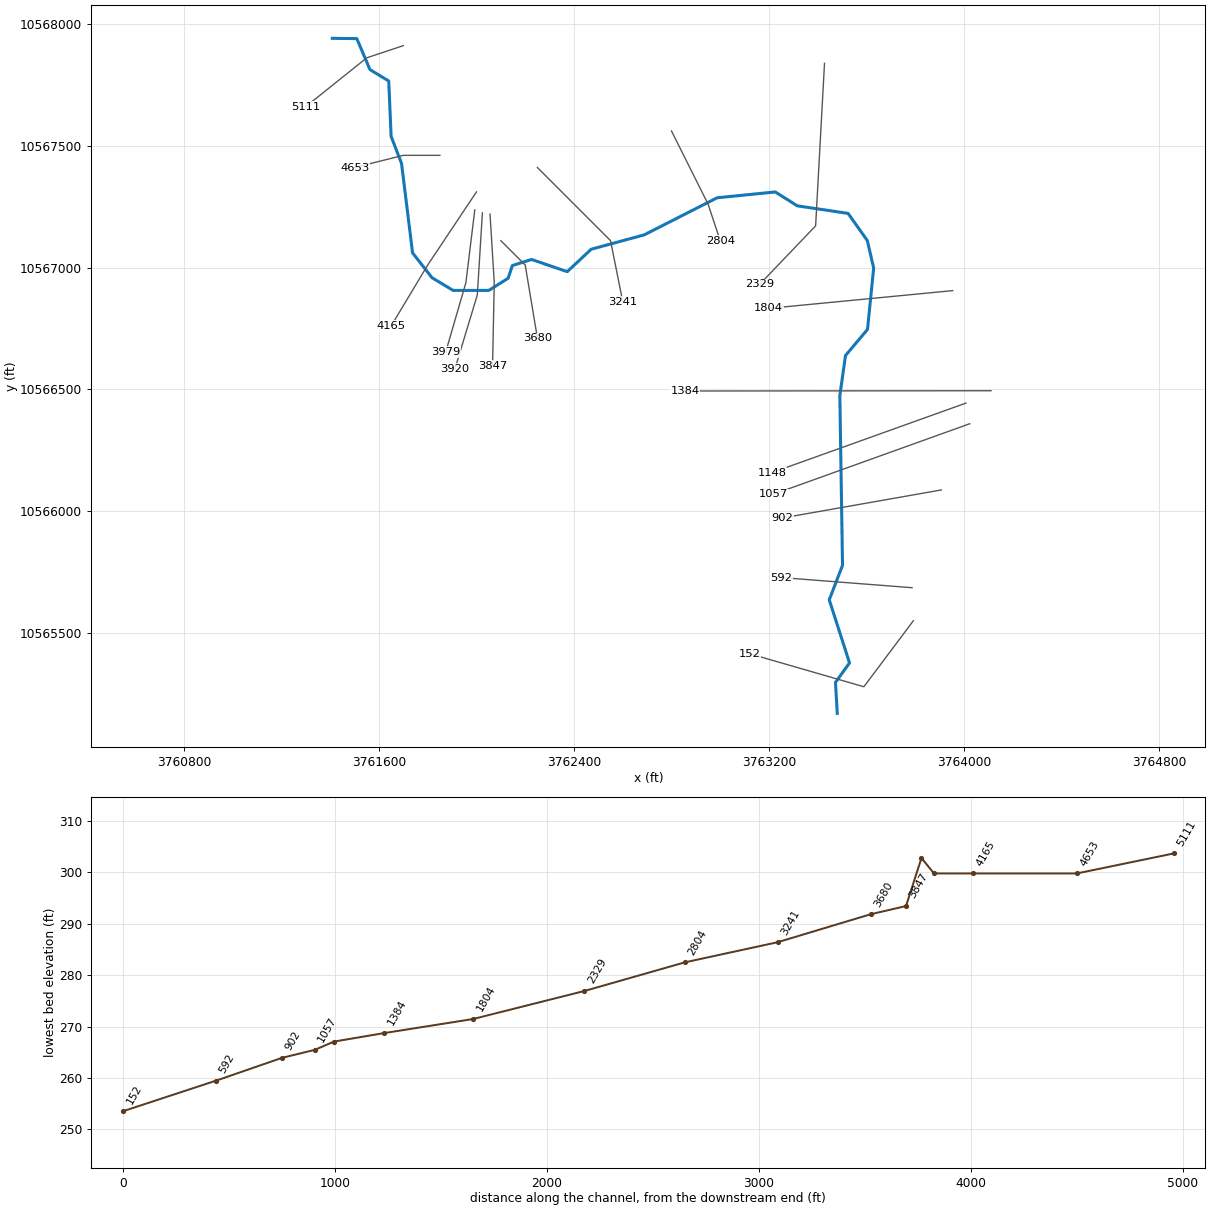
--- UNT 077 IN BOCR.prj (project) ---

Proj Title=UNT 077 IN BOCR Base Level Engineering
Current Plan=p01
Default Exp/Contr=0.3,0.1
English Units
Geom File=g01
Flow File=f01
Plan File=p01
BEGIN DESCRIPTION:
UNT 077 IN BOCR
END DESCRIPTION:

--- UNT 077 IN BOCR.p01 (plan) ---

Plan Title=Multiple Run
Short Identifier=Multiple
Geom File=g01
Flow File=f01
Subcritical Flow
K Sum by GR= 0
Std Step Tol= 0.01
Critical Tol= 0.01
Num of Std Step Trials= 20
Max Error Tol= 0.3
Flow Tol Ratio= 0.001
Split Flow NTrial= 30
Split Flow Tol= 0.02
Split Flow Ratio= 0.02
Log Output Level= 0
Friction Slope Method= 1
Unsteady Friction Slope Method= 2
Unsteady Bridges Friction Slope Method= 1
Parabolic Critical Depth
Global Vel Dist=  1 , 1 , 1
Global Log Level= 0
CheckData=True
Encroach Param= -1, 0, 0, 0
BEGIN DESCRIPTION:
Multiple Run
END DESCRIPTION:

--- UNT 077 IN BOCR.f01 (steady flow) ---

Flow Title=Multiple
Number of Profiles=7
Profile Names=10-year,25-year,50-year,1pct_min,100-year,1pct_plu,500-year
River Rch & RM= UNT 077 IN BOCR,Reach-1,5111
     312     403     476     414     559     756     774
River Rch & RM= UNT 077 IN BOCR,Reach-1,1804
     502     669     806     713     964    1304    1386
Boundary for River Rch & Prof#=UNT 077 IN BOCR,Reach-1,1
Up Type=0
Dn Type=3
Dn Slope=0.005
Boundary for River Rch & Prof#=UNT 077 IN BOCR,Reach-1,2
Up Type=0
Dn Type=3
Dn Slope=0.005
Boundary for River Rch & Prof#=UNT 077 IN BOCR,Reach-1,3
Up Type=0
Dn Type=3
Dn Slope=0.005
Boundary for River Rch & Prof#=UNT 077 IN BOCR,Reach-1,4
Up Type=0
Dn Type=3
Dn Slope=0.005
Boundary for River Rch & Prof#=UNT 077 IN BOCR,Reach-1,5
Up Type=0
Dn Type=3
Dn Slope=0.005
Boundary for River Rch & Prof#=UNT 077 IN BOCR,Reach-1,6
Up Type=0
Dn Type=3
Dn Slope=0.005
Boundary for River Rch & Prof#=UNT 077 IN BOCR,Reach-1,7
Up Type=0
Dn Type=3
Dn Slope=0.005

--- UNT 077 IN BOCR.g01 (geometry) ---

Geom Title=Existing Conditions

River Reach=UNT 077 IN BOCR,Reach-1
Reach XY= 30
      3761408.06     10567940.14      3761508.75     10567939.00
      3761562.75     10567812.00      3761639.75     10567765.00
      3761649.50     10567538.00      3761692.25     10567427.00
      3761737.50     10567060.00      3761817.25     10566958.00
      3761904.00     10566906.00      3762050.00     10566906.00
      3762129.75     10566956.00      3762146.75     10567008.00
      3762225.75     10567033.00      3762372.00     10566983.00
      3762470.25     10567075.00      3762688.00     10567134.00
      3762986.75     10567286.00      3763225.50     10567310.00
      3763315.75     10567253.00      3763524.00     10567222.00
      3763602.75     10567111.00      3763629.00     10566998.00
      3763603.75     10566746.00      3763513.50     10566639.00
      3763490.25     10566475.00      3763501.25     10565778.00
      3763446.75     10565637.00      3763530.00     10565378.00
      3763472.25     10565298.00      3763479.75     10565171.00

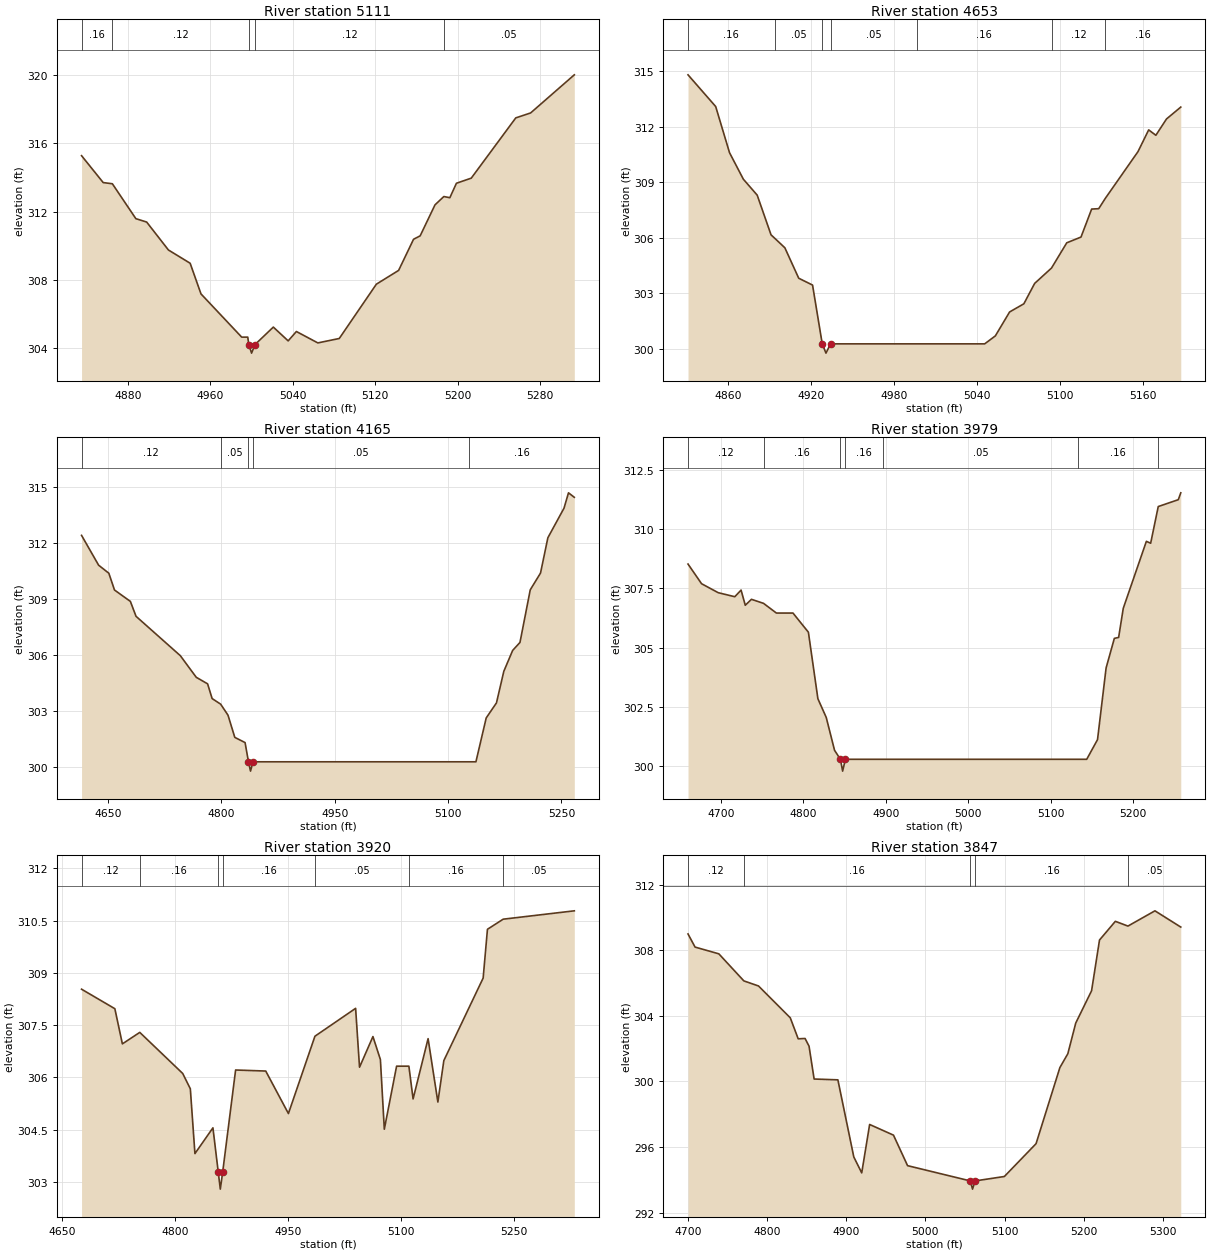
Type RM Length L Ch R = 1,5111,458,458,458
BEGIN DESCRIPTION:
UNT 077 IN BOCR 8.0
END DESCRIPTION:
XS GIS Cut Line= 3
      3761699.57     10567910.17      3761549.61     10567860.19
      3761299.63     10567660.21
#Sta/Elev= 30
  4834.9  315.28  4855.9  313.70  4864.8  313.63  4887.6  311.58  4898.1  311.38
  4919.2  309.74  4940.3  308.96  4950.8  307.16  4990.3  304.62  4996.2  304.62
  4997.2  304.18  4999.9  303.68  5003.2  304.18  5021.0  305.21  5035.4  304.40
  5043.4  304.95  5064.2  304.28  5085.0  304.54  5121.0  307.73  5142.6  308.54
  5157.1  310.37  5163.5  310.57  5177.9  312.39  5186.5  312.88  5192.3  312.81
  5198.7  313.66  5213.1  313.96  5256.3  317.50  5270.7  317.79  5313.1  320.03
#Mann=5,-1,0
  4834.9    0.16       0  4864.8    0.12       0  4997.2    0.07       0
  5003.2    0.12       0  5186.5    0.05       0
Bank Sta=4997.2,5003.2
Exp/Cntr=0.3,0.1

Type RM Length L Ch R = 1,4653,488,488,488
BEGIN DESCRIPTION:
UNT 077 IN BOCR 7.0
END DESCRIPTION:
XS GIS Cut Line= 3
      3761849.57     10567460.19      3761699.61     10567460.19
      3761499.63     10567410.19
#Sta/Elev= 30
  4831.1  314.79  4851.1  313.08  4861.1  310.59  4871.1  309.16  4881.1  308.30
  4891.1  306.16  4893.7  305.98  4901.1  305.46  4911.1  303.82  4921.1  303.45
  4928.1  300.28  4930.8  299.78  4934.1  300.28  4996.4  300.28  5045.5  300.28
  5053.2  300.71  5063.5  302.00  5073.8  302.44  5081.6  303.54  5093.8  304.37
  5104.8  305.73  5115.1  306.04  5122.8  307.55  5127.9  307.57  5132.6  308.12
  5156.3  310.65  5164.0  311.82  5169.2  311.53  5176.9  312.41  5187.2  313.05
#Mann=7,-1,0
  4831.1    0.16       0  4893.7    0.05       0  4928.1    0.07       0
  4934.1    0.05       0  4996.4    0.16       0  5093.8    0.12       0
  5132.6    0.16       0
Bank Sta=4928.1,4934.1
Exp/Cntr=0.3,0.1

Type RM Length L Ch R = 1,4165,186,186,186
BEGIN DESCRIPTION:
UNT 077 IN BOCR 6.0
END DESCRIPTION:
XS GIS Cut Line= 3
      3761999.62     10567310.21      3761799.61     10567010.19
      3761649.62     10566760.21
#Sta/Elev= 30
  4615.0  312.42  4637.6  310.82  4651.1  310.39  4658.6  309.49  4679.6  308.88
  4687.1  308.08  4745.7  305.97  4766.8  304.81  4781.8  304.46  4787.8  303.67
  4799.1  303.37  4808.8  302.78  4817.8  301.59  4831.4  301.31  4835.9  300.28
  4838.6  299.78  4841.9  300.28  5127.7  300.28  5136.9  300.28  5150.5  302.63
  5164.1  303.44  5173.8  305.13  5185.5  306.25  5195.2  306.68  5208.8  309.50
  5222.4  310.40  5232.1  312.29  5253.5  313.88  5259.4  314.70  5267.1  314.46
#Mann=5,-1,0
  4615.0    0.12       0  4799.1    0.05       0  4835.9   0.033       0
  4841.9    0.05       0  5127.7    0.16       0
Bank Sta=4835.9,4841.9
Exp/Cntr=0.3,0.1

Type RM Length L Ch R = 1,3979,59,59,59
BEGIN DESCRIPTION:
Mapping XS 45c8d849
END DESCRIPTION:
XS GIS Cut Line= 3
      3761992.72     10567236.47      3761956.26     10566937.83
      3761873.48     10566653.29
#Sta/Elev= 30
  4660.4  308.53  4676.8  307.70  4697.0  307.32  4717.1  307.15  4724.7  307.43
  4729.8  306.79  4737.3  307.04  4751.9  306.87  4767.5  306.46  4787.6  306.46
  4806.3  305.65  4817.8  302.84  4827.9  302.05  4838.0  300.66  4845.1  300.28
  4847.8  299.78  4851.1  300.28  4896.8  300.28  5133.5  300.28  5143.6  300.28
  5156.7  301.11  5167.1  304.14  5177.1  305.39  5182.3  305.43  5187.9  306.66
  5215.9  309.49  5221.1  309.41  5230.3  310.96  5254.6  311.25  5257.6  311.54
#Mann=7,-1,0
  4660.4    0.12       0  4751.9    0.16       0  4845.1   0.033       0
  4851.1    0.16       0  4896.8    0.05       0  5133.5    0.16       0
  5230.3    0.05       0
Bank Sta=4845.1,4851.1
Exp/Cntr=0.3,0.1

Type RM Length L Ch R = 1,3920,73,73,73
BEGIN DESCRIPTION:
Mapping XS 449946d1
END DESCRIPTION:
XS GIS Cut Line= 3
      3762023.97     10567224.26      3762003.13     10566887.48
      3761911.34     10566584.40
#Sta/Elev= 30
  4675.7  308.53  4719.9  307.97  4729.9  306.96  4753.0  307.29  4810.0  306.11
  4820.1  305.67  4826.2  303.81  4850.1  304.55  4857.1  303.29  4859.9  302.79
  4863.1  303.29  4880.2  306.21  4920.2  306.18  4950.3  304.96  4985.5  307.18
  5039.5  307.98  5044.7  306.29  5062.5  307.17  5072.4  306.51  5077.6  304.51
  5093.9  306.32  5110.2  306.32  5115.8  305.38  5135.7  307.11  5148.7  305.29
  5156.6  306.48  5208.8  308.85  5214.5  310.25  5235.4  310.54  5329.8  310.78
#Mann=7,-1,0
  4675.7    0.12       0  4753.0    0.16       0  4857.1   0.033       0
  4863.1    0.16       0  4985.5    0.05       0  5110.2    0.16       0
  5235.4    0.05       0
Bank Sta=4857.1,4863.1
Exp/Cntr=0.3,0.1

Type RM Length L Ch R = 1,3847,167,167,167
BEGIN DESCRIPTION:
Mapping XS 9111ec03
END DESCRIPTION:
XS GIS Cut Line= 3
      3762055.22     10567219.06      3762072.58     10566939.56
      3762065.63     10566597.57
#Sta/Elev= 30
  4700.3  308.99  4709.2  308.19  4739.2  307.78  4770.8  306.13  4789.3  305.82
  4829.4  303.88  4839.4  302.60  4848.1  302.62  4853.1  302.15  4859.5  300.15
  4889.5  300.10  4909.6  295.40  4919.6  294.43  4929.6  297.38  4959.7  296.73
  4977.5  294.87  5056.7  293.94  5059.5  293.44  5062.7  293.94  5099.7  294.21
  5139.7  296.21  5169.8  300.85  5179.8  301.69  5189.8  303.56  5209.8  305.53
  5219.8  308.62  5239.8  309.76  5255.7  309.47  5289.8  310.40  5322.4  309.41
#Mann=5,-1,0
  4700.3    0.12       0  4770.8    0.16       0  5056.7    0.07       0
  5062.7    0.16       0  5255.7    0.05       0
Bank Sta=5056.7,5062.7
Exp/Cntr=0.3,0.1

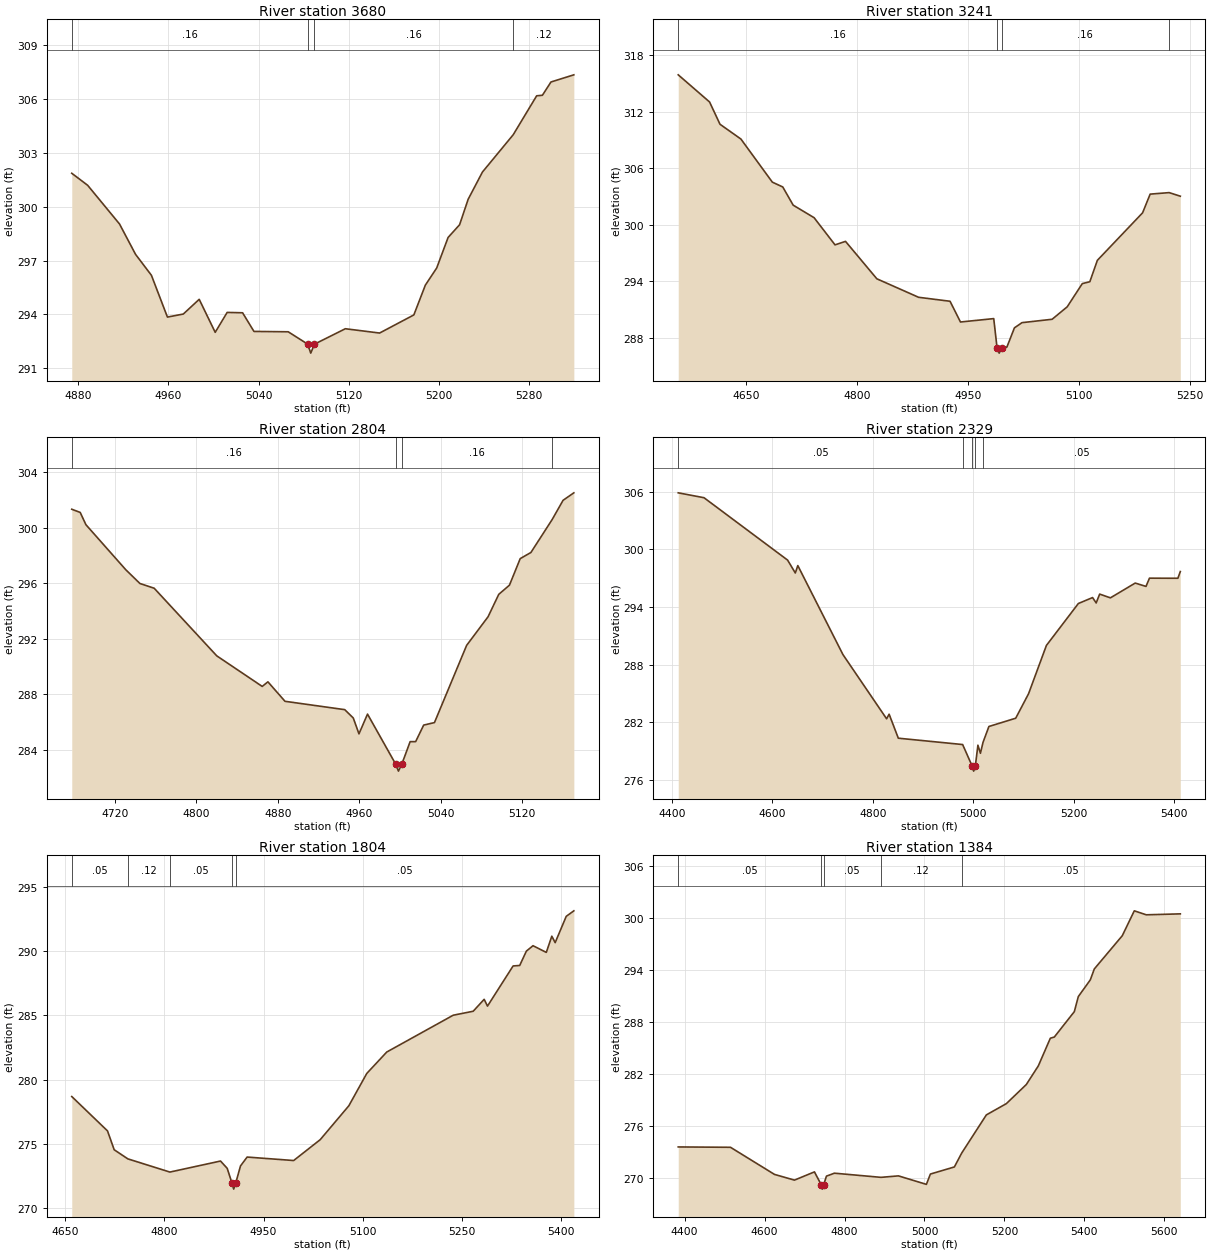
Type RM Length L Ch R = 1,3680,439,439,439
BEGIN DESCRIPTION:
UNT 077 IN BOCR 5.0
END DESCRIPTION:
XS GIS Cut Line= 3
      3762099.61     10567110.19      3762199.61     10567010.19
      3762249.62     10566710.15
#Sta/Elev= 30
  4874.2  301.87  4888.3  301.20  4916.6  299.04  4930.8  297.35  4944.9  296.18
  4959.1  293.85  4973.2  294.02  4987.3  294.84  5001.5  293.00  5012.1  294.11
  5025.8  294.09  5035.9  293.05  5066.3  293.03  5083.6  292.34  5086.3  291.84
  5089.6  292.34  5117.0  293.20  5147.4  292.96  5177.8  293.97  5188.0  295.63
  5198.1  296.59  5208.2  298.29  5218.4  299.00  5226.0  300.42  5238.7  301.94
  5266.0  304.02  5286.8  306.19  5291.9  306.22  5299.5  306.96  5319.8  307.36
#Mann=4,-1,0
  4874.2    0.16       0  5083.6    0.07       0  5089.6    0.16       0
  5266.0    0.12       0
Bank Sta=5083.6,5089.6
Exp/Cntr=0.3,0.1

Type RM Length L Ch R = 1,3241,437,437,437
BEGIN DESCRIPTION:
UNT 077 IN BOCR 4.0
END DESCRIPTION:
XS GIS Cut Line= 3
      3762249.63     10567410.17      3762549.61     10567110.19
      3762599.61     10566860.18
#Sta/Elev= 30
  4558.2  315.91  4600.6  313.03  4614.7  310.67  4643.0  309.10  4685.5  304.53
  4699.6  304.02  4713.7  302.09  4742.0  300.76  4770.3  297.88  4784.5  298.25
  4826.9  294.28  4883.4  292.32  4925.9  291.90  4940.0  289.70  4985.0  290.06
  4989.6  286.90  4992.4  286.40  4995.6  286.90  5002.8  287.04  5013.0  289.08
  5023.2  289.63  5064.0  289.99  5084.4  291.31  5104.8  293.77  5115.0  293.97
  5125.2  296.24  5186.4  301.28  5196.6  303.26  5222.3  303.42  5237.4  303.04
#Mann=4,-1,0
  4558.2    0.16       0  4989.6    0.07       0  4995.6    0.16       0
  5222.3    0.05       0
Bank Sta=4989.6,4995.6
Exp/Cntr=0.3,0.1

Type RM Length L Ch R = 1,2804,475,475,475
BEGIN DESCRIPTION:
UNT 077 IN BOCR 3.0
END DESCRIPTION:
XS GIS Cut Line= 3
      3762799.63     10567560.15      3762949.61     10567260.19
      3762999.61     10567110.17
#Sta/Elev= 30
  4677.5  301.32  4685.8  301.09  4691.4  300.21  4730.6  296.97  4744.5  295.98
  4758.5  295.64  4820.0  290.78  4864.7  288.58  4870.3  288.91  4887.1  287.51
  4945.8  286.91  4954.2  286.31  4959.8  285.17  4968.2  286.59  4995.9  282.99
  4998.6  282.49  5001.9  282.99  5010.1  284.61  5015.5  284.61  5023.4  285.80
  5034.0  285.98  5065.6  291.53  5086.7  293.59  5097.2  295.20  5107.7  295.86
  5118.3  297.77  5128.8  298.21  5149.7  300.58  5160.4  301.96  5171.0  302.50
#Mann=4,-1,0
  4677.5    0.16       0  4995.9    0.07       0  5001.9    0.16       0
  5149.7    0.05       0
Bank Sta=4995.9,5001.9
Exp/Cntr=0.3,0.1

Type RM Length L Ch R = 1,2329,525,525,525
BEGIN DESCRIPTION:
UNT 077 IN BOCR 2.0
END DESCRIPTION:
XS GIS Cut Line= 3
      3763427.35     10567837.53      3763390.89     10567170.85
      3763161.73     10566931.28
#Sta/Elev= 30
  4412.6  305.90  4463.9  305.39  4630.3  298.89  4645.6  297.55  4650.6  298.32
  4740.4  289.05  4827.3  282.36  4832.3  282.84  4850.6  280.34  4978.6  279.68
  4997.8  277.41  5000.6  276.91  5003.8  277.41  5009.0  279.61  5014.0  278.77
  5019.2  279.91  5030.9  281.56  5084.2  282.42  5109.8  284.97  5145.3  290.00
  5208.9  294.37  5237.2  294.99  5244.4  294.43  5251.3  295.35  5272.7  294.96
  5322.1  296.50  5343.5  296.15  5350.4  297.01  5407.0  297.00  5411.8  297.70
#Mann=5,-1,0
  4412.6    0.05       0  4978.6    0.16       0  4997.8    0.07       0
  5003.8    0.16       0  5019.2    0.05       0
Bank Sta=4997.8,5003.8
Exp/Cntr=0.3,0.1

Type RM Length L Ch R = 1,1804,420,420,420
BEGIN DESCRIPTION:
Mapping XS e359367f
END DESCRIPTION:
XS GIS Cut Line= 2
      3763953.39     10566905.23      3763198.20     10566832.31
#Sta/Elev= 30
  4660.1  278.68  4714.1  276.00  4724.2  274.53  4744.8  273.82  4808.4  272.79
  4884.9  273.65  4895.0  273.08  4902.0  271.96  4904.8  271.46  4908.0  271.96
  4915.1  273.27  4925.1  273.96  4995.4  273.69  5035.6  275.32  5078.8  277.96
  5105.9  280.48  5136.1  282.15  5236.5  285.02  5266.7  285.33  5283.3  286.26
  5288.3  285.73  5327.0  288.86  5337.0  288.90  5347.1  290.02  5357.1  290.44
  5377.2  289.92  5385.5  291.18  5390.6  290.68  5407.3  292.73  5418.8  293.16
#Mann=5,-1,0
  4660.1    0.05       0  4744.8    0.12       0  4808.4    0.05       0
  4902.0    0.03       0  4908.0    0.05       0
Bank Sta=4902,4908
Exp/Cntr=0.3,0.1

Type RM Length L Ch R = 1,1384,236,236,236
BEGIN DESCRIPTION:
Mapping XS 505bf738
END DESCRIPTION:
XS GIS Cut Line= 2
      3764110.35     10566494.57      3762854.55     10566493.38
#Sta/Elev= 30
  4384.1  273.59  4514.8  273.55  4624.8  270.42  4674.8  269.76  4724.8  270.71
  4741.8  269.22  4744.6  268.72  4747.8  269.22  4754.8  270.22  4774.8  270.56
  4891.2  270.08  4934.8  270.25  5004.8  269.27  5014.8  270.46  5074.8  271.28
  5093.2  272.89  5154.8  277.29  5204.8  278.59  5254.8  280.80  5284.8  282.95
  5314.8  286.14  5324.8  286.28  5374.8  289.21  5384.8  290.95  5414.8  292.88
  5424.8  294.14  5494.8  297.98  5524.8  300.85  5554.8  300.39  5639.9  300.50
#Mann=5,-1,0
  4384.1    0.05       0  4741.8    0.07       0  4747.8    0.05       0
  4891.2    0.12       0  5093.2    0.05       0
Bank Sta=4741.8,4747.8
Exp/Cntr=0.3,0.1

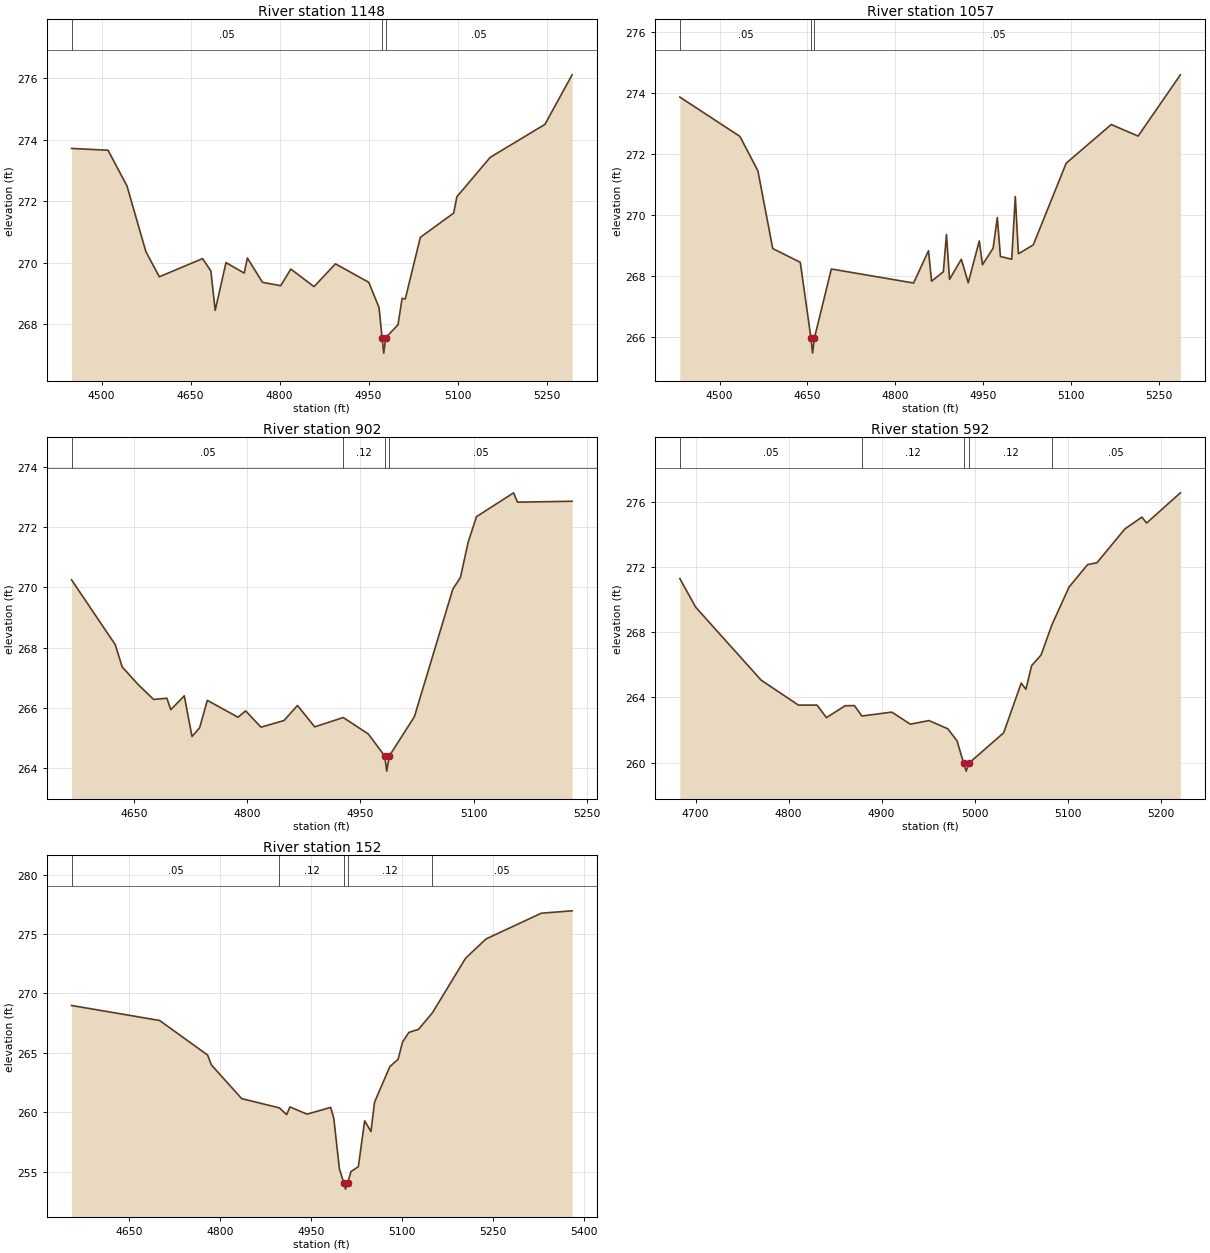
Type RM Length L Ch R = 1,1148,91,91,91
BEGIN DESCRIPTION:
Mapping XS 53fb6a72
END DESCRIPTION:
XS GIS Cut Line= 2
      3764007.50     10566443.78      3763213.27     10566159.10
#Sta/Elev= 30
  4449.3  273.72  4510.8  273.66  4542.7  272.50  4574.5  270.37  4597.2  269.55
  4670.1  270.14  4684.1  269.74  4691.4  268.46  4709.6  270.01  4740.3  269.67
  4745.7  270.16  4771.1  269.37  4801.8  269.26  4818.9  269.80  4858.0  269.23
  4894.1  269.97  4950.3  269.37  4967.6  268.55  4972.7  267.57  4975.5  267.07
  4978.7  267.57  4999.5  267.99  5006.5  268.85  5011.8  268.83  5037.2  270.83
  5093.4  271.62  5098.8  272.15  5155.0  273.43  5247.2  274.50  5293.0  276.11
#Mann=3,-1,0
  4449.3    0.05       0  4972.7    0.03       0  4978.7    0.05       0
Bank Sta=4972.7,4978.7
Exp/Cntr=0.3,0.1

Type RM Length L Ch R = 1,1057,155,155,155
BEGIN DESCRIPTION:
Mapping XS bf840918
END DESCRIPTION:
XS GIS Cut Line= 2
      3764023.16     10566359.16      3763218.51     10566070.10
#Sta/Elev= 30
  4432.0  273.86  4534.6  272.57  4565.3  271.44  4590.7  268.89  4637.7  268.44
  4655.9  265.96  4658.7  265.46  4661.9  265.96  4690.8  268.22  4831.3  267.76
  4856.7  268.82  4862.0  267.82  4882.1  268.13  4887.4  269.35  4892.7  267.88
  4912.8  268.54  4924.6  267.77  4943.5  269.14  4948.9  268.36  4967.1  268.90
  4974.3  269.91  4979.6  268.63  4998.9  268.54  5005.0  270.60  5010.3  268.72
  5035.7  269.01  5091.9  271.69  5168.9  272.96  5214.8  272.58  5287.0  274.59
#Mann=3,-1,0
  4432.0    0.05       0  4655.9    0.03       0  4661.9    0.05       0
Bank Sta=4655.9,4661.9
Exp/Cntr=0.3,0.1

Type RM Length L Ch R = 1,902,310,310,310
BEGIN DESCRIPTION:
Mapping XS 30840315
END DESCRIPTION:
XS GIS Cut Line= 2
      3763906.54     10566087.52      3763254.10     10565972.52
#Sta/Elev= 30
  4567.7  270.25  4625.5  268.10  4634.7  267.36  4656.0  266.77  4676.3  266.28
  4693.9  266.32  4699.0  265.94  4716.9  266.40  4727.1  265.05  4737.2  265.34
  4747.4  266.25  4788.0  265.69  4798.1  265.90  4818.4  265.36  4848.9  265.58
  4866.7  266.08  4889.5  265.37  4927.3  265.68  4960.6  265.13  4982.2  264.40
  4984.9  263.90  4988.2  264.40  5021.5  265.71  5072.3  269.94  5082.4  270.33
  5092.6  271.50  5103.7  272.35  5152.8  273.14  5157.9  272.83  5230.2  272.86
#Mann=4,-1,0
  4567.7    0.05       0  4927.3    0.12       0  4982.2    0.03       0
  4988.2    0.05       0
Bank Sta=4982.2,4988.2
Exp/Cntr=0.3,0.1

Type RM Length L Ch R = 1,592,440,440,440
BEGIN DESCRIPTION:
Mapping XS 3b53e79b
END DESCRIPTION:
XS GIS Cut Line= 2
      3763786.70     10565686.48      3763250.22     10565728.15
#Sta/Elev= 30
  4683.1  271.29  4700.2  269.53  4770.5  265.06  4810.6  263.53  4830.6  263.53
  4840.7  262.76  4860.7  263.49  4870.8  263.50  4878.8  262.86  4910.9  263.10
  4930.9  262.36  4951.0  262.58  4971.1  262.08  4981.1  261.34  4988.1  259.98
  4990.9  259.48  4994.1  259.98  5031.2  261.83  5050.1  264.88  5055.1  264.50
  5061.3  265.95  5071.4  266.60  5083.2  268.47  5101.5  270.77  5121.5  272.15
  5131.5  272.26  5161.6  274.34  5179.8  275.06  5184.9  274.70  5221.2  276.55
#Mann=5,-1,0
  4683.1    0.05       0  4878.8    0.12       0  4988.1    0.07       0
  4994.1    0.12       0  5083.2    0.05       0
Bank Sta=4988.1,4994.1
Exp/Cntr=0.3,0.1

Type RM Length L Ch R = 1,152,0,0,0
BEGIN DESCRIPTION:
UNT 077 IN BOCR 1.0
END DESCRIPTION:
XS GIS Cut Line= 3
      3763791.95     10565551.09      3763588.80     10565280.23
      3763120.82     10565415.42
#Sta/Elev= 30
  4554.5  268.98  4699.7  267.72  4778.9  264.81  4785.1  263.98  4835.1  261.14
  4897.3  260.36  4909.4  259.79  4914.6  260.44  4943.0  259.83  4981.9  260.40
  4987.1  259.48  4996.3  255.23  5003.7  254.02  5006.5  253.52  5009.7  254.02
  5015.5  255.00  5027.6  255.41  5038.0  259.27  5048.4  258.37  5054.3  260.84
  5079.6  263.84  5093.2  264.45  5100.4  265.89  5110.8  266.71  5126.8  266.97
  5149.7  268.36  5204.5  272.96  5238.1  274.58  5329.4  276.75  5380.2  276.95
#Mann=5,-1,0
  4554.5    0.05       0  4897.3    0.12       0  5003.7    0.07       0
  5009.7    0.12       0  5149.7    0.05       0
Bank Sta=5003.7,5009.7
Exp/Cntr=0.3,0.1

Chan Stop Cuts=-1