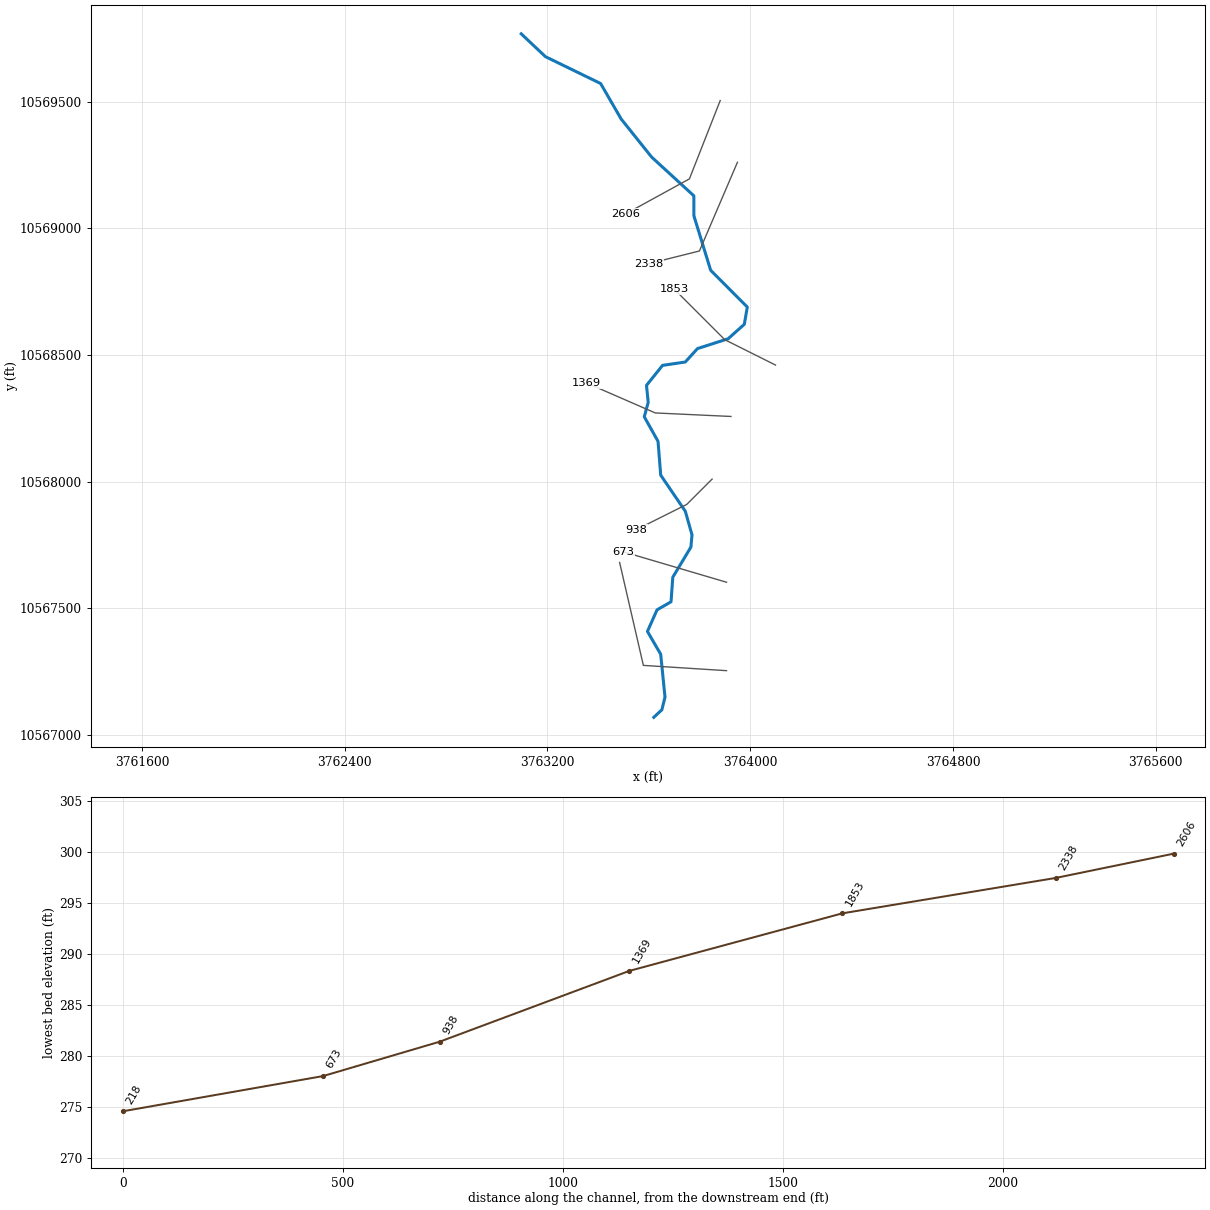
--- UNT 078 IN BOCR.prj (project) ---

Proj Title=UNT 078 IN BOCR Base Level Engineering
Current Plan=p01
Default Exp/Contr=0.3,0.1
English Units
Geom File=g01
Flow File=f01
Plan File=p01
Y Axis Title=Elevation
X Axis Title(PF)=Main Channel Distance
X Axis Title(XS)=Station
BEGIN DESCRIPTION:
UNT 078 IN BOCR
END DESCRIPTION:
DSS Export Rating Curves= 0
DSS Export Rating Curve Sorted= 0
DSS Export Volume Flow Curves= 0
DXF OffsetX= 0
DXF OffsetY= 0
DXF ScaleX= 1
DXF ScaleY= 10

--- UNT 078 IN BOCR.p01 (plan) ---

Plan Title=Multiple Run
Short Identifier=Multiple
Geom File=g01
Flow File=f01
Subcritical Flow
K Sum by GR= 0
Std Step Tol= 0.01
Critical Tol= 0.01
Num of Std Step Trials= 20
Max Error Tol= 0.3
Flow Tol Ratio= 0.001
Split Flow NTrial= 30
Split Flow Tol= 0.02
Split Flow Ratio= 0.02
Log Output Level= 0
Friction Slope Method= 1
Unsteady Friction Slope Method= 2
Unsteady Bridges Friction Slope Method= 1
Parabolic Critical Depth
Global Vel Dist=  1 , 1 , 1
Global Log Level= 0
CheckData=True
Encroach Param= -1, 0, 0, 0
BEGIN DESCRIPTION:
Multiple Run
END DESCRIPTION:

--- UNT 078 IN BOCR.f01 (steady flow) ---

Flow Title=Multiple
Program Version=4.10
Number of Profiles= 7
Profile Names=10-year,25-year,50-year,1pct_min,100-year,1pct_plu,500-year
River Rch & RM=UNT 078 IN BOCR,Reach-1         ,2606
     271     351     414     361     488     660     679
Boundary for River Rch & Prof#=UNT 078 IN BOCR,Reach-1         , 1
Up Type= 0
Dn Type= 3
Dn Slope=0.005
Boundary for River Rch & Prof#=UNT 078 IN BOCR,Reach-1         , 2
Up Type= 0
Dn Type= 3
Dn Slope=0.005
Boundary for River Rch & Prof#=UNT 078 IN BOCR,Reach-1         , 3
Up Type= 0
Dn Type= 3
Dn Slope=0.005
Boundary for River Rch & Prof#=UNT 078 IN BOCR,Reach-1         , 4
Up Type= 0
Dn Type= 3
Dn Slope=0.005
Boundary for River Rch & Prof#=UNT 078 IN BOCR,Reach-1         , 5
Up Type= 0
Dn Type= 3
Dn Slope=0.005
Boundary for River Rch & Prof#=UNT 078 IN BOCR,Reach-1         , 6
Up Type= 0
Dn Type= 3
Dn Slope=0.005
Boundary for River Rch & Prof#=UNT 078 IN BOCR,Reach-1         , 7
Up Type= 0
Dn Type= 3
Dn Slope=0.005
DSS Import GetInterval= 0
DSS Import GetPeak= 0
DSS Import FillOption= 0

--- UNT 078 IN BOCR.g01 (geometry) ---

Geom Title=Existing Conditions
Program Version=4.10

River Reach=UNT 078 IN BOCR ,Reach-1
Reach XY= 30
       3763096.5       10569767.        3763192.       10569677.
      3763409.75       10569571.      3763490.75       10569431.
      3763610.75       10569281.       3763777.5       10569128.
      3763777.75       10569049.        3763844.       10568834.
       3763988.5       10568689.      3763976.75       10568621.
        3763913.       10568564.      3763791.75       10568525.
      3763743.75       10568472.      3763654.25       10568459.
      3763590.75       10568380.       3763597.5       10568313.
        3763582.       10568256.      3763636.25       10568159.
      3763646.86     10568025.58        3763744.       10567883.
      3763770.25       10567790.        3763766.       10567742.
       3763694.5       10567623.       3763687.5       10567526.
      3763632.25       10567494.       3763594.5       10567409.
      3763646.75       10567319.      3763663.75       10567150.
       3763651.5       10567100.       3763619.5       10567070.

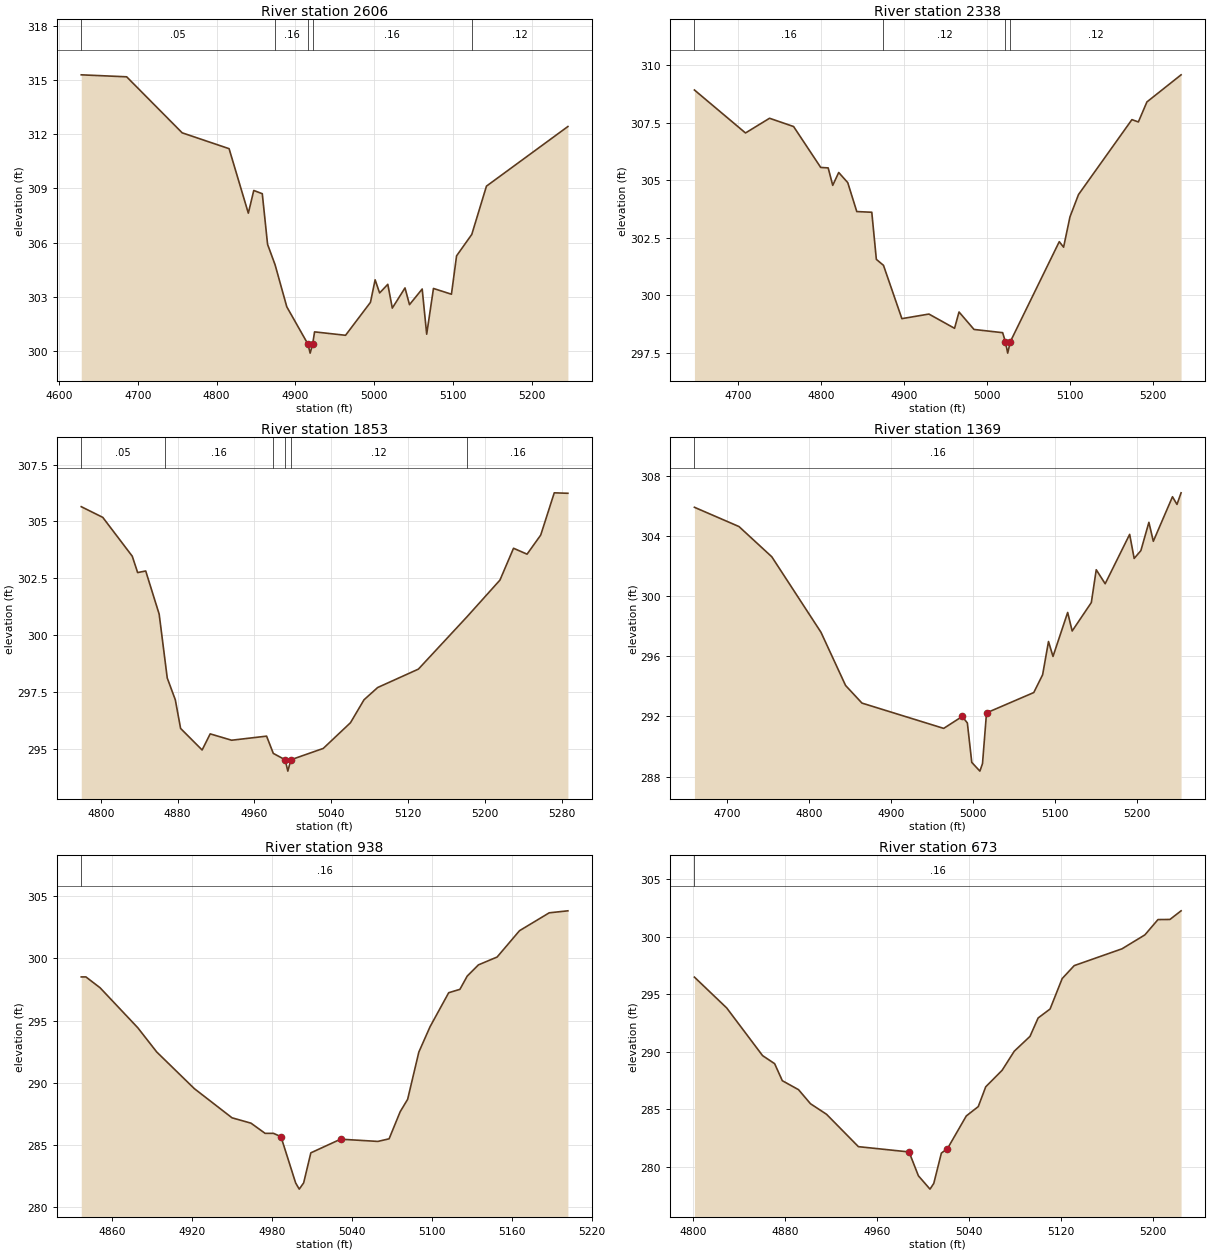
Type RM Length L Ch R = 1 ,2606    ,268,268,268
BEGIN DESCRIPTION:
Mapping XS 33c2ffd8
END DESCRIPTION:
XS GIS Cut Line= 3
      3763881.62     10569503.82      3763760.08     10569194.77
      3763510.12     10569057.64
#Sta/Elev= 30
  4628.4  315.31    4686   315.2  4756.4  312.09  4815.9  311.21  4840.3  307.63
  4847.2  308.89    4858  308.71  4864.7   305.9  4874.2  304.77  4889.1  302.43
  4915.9  300.36  4918.7  299.86  4921.9  300.36  4924.3  301.04  4963.6  300.85
  4995.2  302.68  5001.1  303.93  5006.8   303.2  5017.2  303.68  5022.9  302.36
    5039  303.48  5044.7  302.55  5060.8  303.42  5066.5  300.91  5075.1  303.45
  5097.9  303.13  5104.4  305.26  5123.7  306.45  5142.3  309.13  5245.6  312.44
#Mann= 5 ,-1 , 0
  4628.4     .05       0  4874.2     .16       0  4915.9     .07       0
  4921.9     .16       0  5123.7     .12       0
Bank Sta=4915.9,4921.9
XS Rating Curve= 0 ,0
Exp/Cntr=0.3,0.1

Type RM Length L Ch R = 1 ,2338    ,485,485,485
BEGIN DESCRIPTION:
UNT 078 IN BOCR 5.0
END DESCRIPTION:
XS GIS Cut Line= 3
      3763949.59     10569260.15      3763799.61     10568910.19
      3763599.61     10568860.19
#Sta/Elev= 30
  4647.5  308.93  4709.1  307.06  4738.1   307.7  4767.1  307.34  4799.8  305.56
  4808.8  305.54  4814.3  304.78  4821.5  305.34  4832.4   304.9  4843.3  303.64
  4861.4  303.61  4866.9  301.56  4875.5   301.3  4897.7  298.98  4930.3  299.18
  4961.2  298.56  4966.6  299.27  4984.7  298.51  5019.2  298.37  5022.5  297.98
  5025.3  297.48  5028.5  297.98  5087.5  302.33  5092.7  302.09  5100.4  303.41
  5110.7  304.38  5175.1  307.64  5182.9  307.54  5193.2  308.41  5234.4  309.59
#Mann= 4 ,-1 , 0
  4647.5     .16       0  4875.5     .12       0  5022.5     .07       0
  5028.5     .12       0
Bank Sta=5022.5,5028.5
XS Rating Curve= 0 ,0
Exp/Cntr=0.3,0.1

Type RM Length L Ch R = 1 ,1853    ,484,484,484
BEGIN DESCRIPTION:
UNT 078 IN BOCR 4.0
END DESCRIPTION:
XS GIS Cut Line= 3
      3764099.63     10568460.18      3763899.61     10568560.19
      3763699.59     10568760.21
#Sta/Elev= 30
  4779.7  305.65  4802.1  305.18  4832.8  303.47  4838.4  302.75  4846.8  302.82
  4860.8  300.92  4866.9  298.88  4869.2  298.11  4877.6  297.15  4883.1  295.89
  4905.5  294.94  4913.9  295.65  4936.2  295.37  4972.6  295.55  4979.6  294.79
  4991.9  294.51  4994.7  294.01  4997.9  294.51  5031.6  295.01  5059.9  296.14
    5074  297.15  5088.2  297.69  5130.6   298.5  5181.1   300.8  5215.5  302.42
  5229.6  303.82  5243.7  303.56  5257.9   304.4    5272  306.26  5286.2  306.24
#Mann= 6 ,-1 , 0
  4779.7     .05       0  4866.9     .16       0  4979.6     .12       0
  4991.9     .07       0  4997.9     .12       0  5181.1     .16       0
Bank Sta=4991.9,4997.9
XS Rating Curve= 0 ,0
Exp/Cntr=0.3,0.1

Type RM Length L Ch R = 1 ,1369    ,431,431,431
BEGIN DESCRIPTION:
UNT 078 IN BOCR 3.0
END DESCRIPTION:
XS GIS Cut Line= 3
      3763923.97     10568257.27      3763625.36     10568271.16
       3763354.6     10568389.18
#Sta/Elev= 30
  4659.7   305.9  4714.1  304.62  4754.2  302.61  4814.2   297.6  4844.3  294.06
  4864.3  292.89  4964.1  291.21  4986.7     292    4993  291.57  4998.4  288.95
  5008.3  288.37  5011.5  288.87  5016.4  292.24  5074.1  293.59  5084.9  294.77
  5092.1  296.98  5097.6  295.99  5115.5  298.91    5121  297.68  5144.4  299.57
  5150.4  301.75  5161.3  300.82  5191.2   304.1  5196.7   302.5  5204.9  303.02
  5214.7   304.9  5220.1  303.64  5243.5   306.6    5249  306.09    5254  306.86
#Mann= 1 ,-1 , 0
  4659.7     .16       0
Bank Sta=4986.7,5016.4
XS Rating Curve= 0 ,0
Exp/Cntr=0.3,0.1

Type RM Length L Ch R = 1 ,938     ,265,265,265
BEGIN DESCRIPTION:
UNT 078 IN BOCR 2.0
END DESCRIPTION:
XS GIS Cut Line= 3
       3763849.6     10568010.18      3763749.61     10567910.19
      3763549.62      10567810.2
#Sta/Elev= 30
  4836.9  298.51  4840.4  298.51    4851  297.64  4879.3  294.42  4893.5  292.47
  4921.7  289.52    4950  287.17  4964.2  286.74  4974.8  285.92  4981.1  285.92
  4986.7  285.65  4997.7  281.93  5000.4  281.43  5003.7  281.93  5009.1  284.35
  5031.4  285.45  5059.4  285.27  5067.8  285.48  5076.1  287.66  5081.7  288.66
  5090.1  292.46  5098.5   294.5  5112.5  297.24  5120.9  297.51  5126.4  298.58
  5134.8  299.48  5148.8  300.11  5165.6  302.23  5187.9  303.67  5201.9  303.83
#Mann= 1 ,-1 , 0
  4836.9     .16       0
Bank Sta=4986.7,5031.4
XS Rating Curve= 0 ,0
Exp/Cntr=0.3,0.1

Type RM Length L Ch R = 1 ,673     ,455,455,455
BEGIN DESCRIPTION:
Mapping XS d417c1e0
END DESCRIPTION:
XS GIS Cut Line= 2
      3763906.52     10567603.14      3763500.31     10567722.92
#Sta/Elev= 30
  4800.9  296.48    4829   293.8  4860.2  289.66  4870.7  288.96  4877.4  287.48
  4891.5   286.7  4901.9  285.48  4915.9  284.56  4943.6  281.75  4987.7  281.29
  4995.8  279.22  5005.9  278.06  5009.2  278.56  5015.8  281.19  5021.1  281.58
  5037.5  284.42  5047.9  285.23  5054.4  286.95  5068.7  288.39  5079.2  290.04
  5092.9  291.33    5100  292.93  5110.4  293.71  5120.9  296.35  5131.4  297.48
    5173  298.94  5192.9  300.15  5204.3  301.48  5214.7  301.49  5224.4  302.24
#Mann= 1 ,-1 , 0
  4800.9     .16       0
Bank Sta=4987.7,5021.1
XS Rating Curve= 0 ,0
Exp/Cntr=0.3,0.1

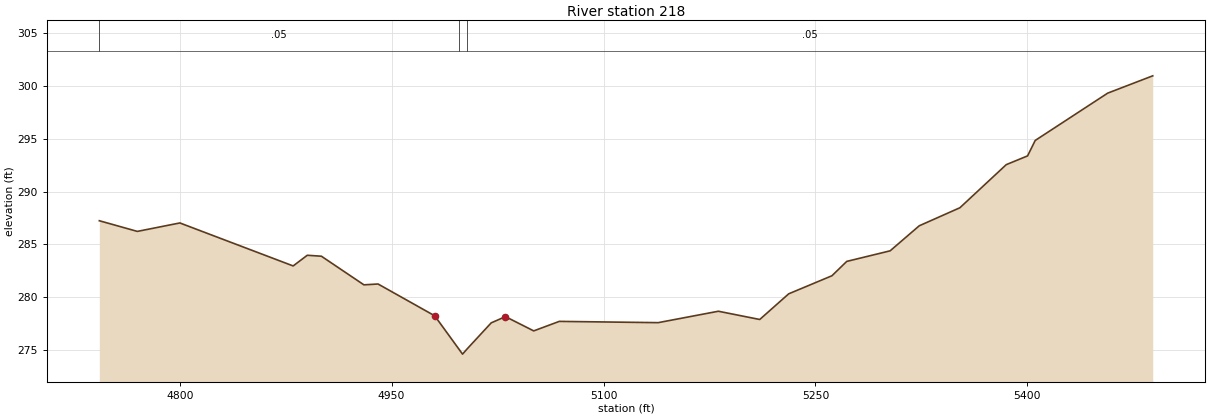
Type RM Length L Ch R = 1 ,218     ,0,0,0
BEGIN DESCRIPTION:
UNT 078 IN BOCR 1.0
END DESCRIPTION:
XS GIS Cut Line= 3
      3763906.49     10567254.19      3763578.39     10567275.02
      3763484.63     10567681.28
#Sta/Elev= 30
  4743.1  287.24    4770  286.23  4800.1  287.03  4880.3  282.96  4890.3  283.97
  4900.3  283.88  4930.4  281.17  4940.4  281.25  4980.5  278.24  4997.5  275.11
  5000.2  274.61  5003.5  275.11  5020.5  277.57  5030.6  278.16  5050.6  276.81
  5068.7  277.71  5138.7  277.59  5181.3  278.67  5210.6  277.89  5231.1  280.32
  5261.7  282.03  5272.2  283.39  5302.9  284.39  5323.5  286.76  5352.3  288.47
  5385.1  292.55  5400.2  293.38  5405.6  294.84  5456.9  299.32  5488.8  300.96
#Mann= 3 ,-1 , 0
  4743.1     .05       0  4997.5     .03       0  5003.5     .05       0
Bank Sta=4980.5,5030.6
XS Rating Curve= 0 ,0
Exp/Cntr=0.3,0.1

Chan Stop Cuts=-1
Use User Specified Reach Order=0
Composite Channel Slope=5