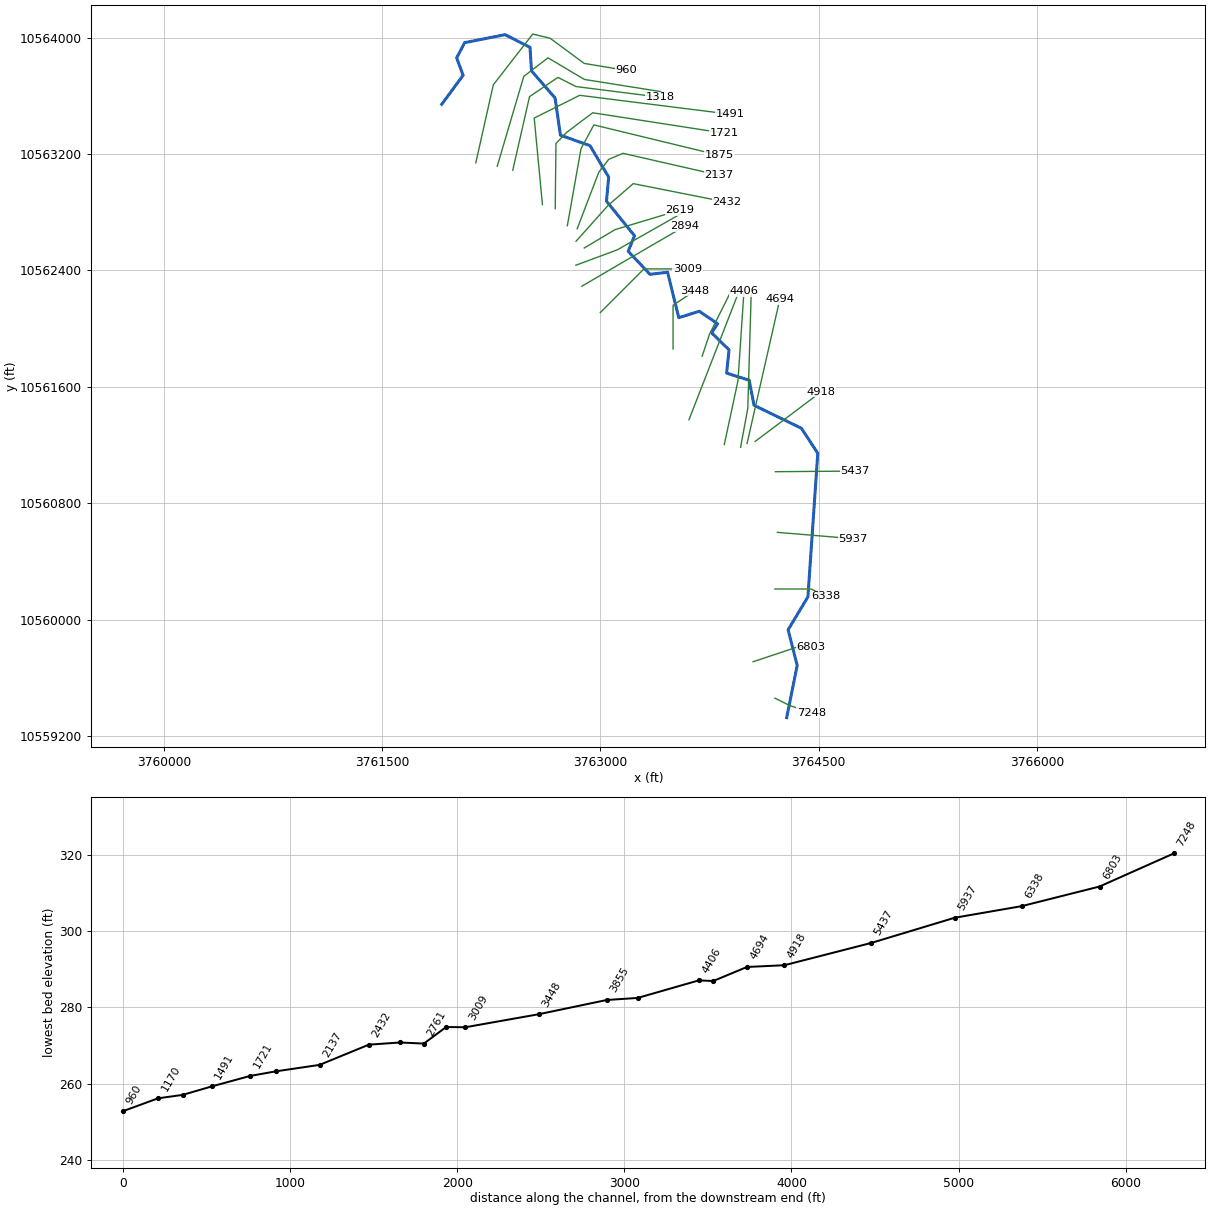
--- UNT 079 IN BOCR.prj (project) ---

Proj Title=UNT 079 IN BOCR Base Level Engineering
Current Plan=p01
Default Exp/Contr=0.3,0.1
English Units
Geom File=g01
Flow File=f01
Plan File=p01
BEGIN DESCRIPTION:
UNT 079 IN BOCR
END DESCRIPTION:

--- UNT 079 IN BOCR.p01 (plan) ---

Plan Title=Multiple Run
Short Identifier=Multiple
Geom File=g01
Flow File=f01
Subcritical Flow
K Sum by GR= 0
Std Step Tol= 0.01
Critical Tol= 0.01
Num of Std Step Trials= 20
Max Error Tol= 0.3
Flow Tol Ratio= 0.001
Split Flow NTrial= 30
Split Flow Tol= 0.02
Split Flow Ratio= 0.02
Log Output Level= 0
Friction Slope Method= 1
Unsteady Friction Slope Method= 2
Unsteady Bridges Friction Slope Method= 1
Parabolic Critical Depth
Global Vel Dist=  1 , 1 , 1
Global Log Level= 0
CheckData=True
Encroach Param= -1, 0, 0, 0
BEGIN DESCRIPTION:
Multiple Run
END DESCRIPTION:

--- UNT 079 IN BOCR.f01 (steady flow) ---

Flow Title=Multiple
Number of Profiles=7
Profile Names=10-year,25-year,50-year,1pct_min,100-year,1pct_plu,500-year
River Rch & RM= UNT 079 IN BOCR,Reach-1,7248
     582     794     972     876    1184    1601    1763
Boundary for River Rch & Prof#=UNT 079 IN BOCR,Reach-1,1
Up Type=0
Dn Type=3
Dn Slope=0.005
Boundary for River Rch & Prof#=UNT 079 IN BOCR,Reach-1,2
Up Type=0
Dn Type=3
Dn Slope=0.005
Boundary for River Rch & Prof#=UNT 079 IN BOCR,Reach-1,3
Up Type=0
Dn Type=3
Dn Slope=0.005
Boundary for River Rch & Prof#=UNT 079 IN BOCR,Reach-1,4
Up Type=0
Dn Type=3
Dn Slope=0.005
Boundary for River Rch & Prof#=UNT 079 IN BOCR,Reach-1,5
Up Type=0
Dn Type=3
Dn Slope=0.005
Boundary for River Rch & Prof#=UNT 079 IN BOCR,Reach-1,6
Up Type=0
Dn Type=3
Dn Slope=0.005
Boundary for River Rch & Prof#=UNT 079 IN BOCR,Reach-1,7
Up Type=0
Dn Type=3
Dn Slope=0.005

--- UNT 079 IN BOCR.g01 (geometry) ---

Geom Title=Existing Conditions

River Reach=UNT 079 IN BOCR,Reach-1
Reach XY= 30
      3764280.50     10559326.00      3764352.75     10559685.00
      3764290.50     10559930.00      3764426.50     10560156.00
      3764494.25     10561143.00      3764381.50     10561315.00
      3764056.00     10561473.00      3764022.75     10561645.00
      3763867.75     10561694.00      3763884.50     10561854.00
      3763764.50     10561971.00      3763806.25     10562033.00
      3763680.25     10562119.00      3763539.00     10562075.00
      3763462.00     10562387.00      3763341.25     10562373.00
      3763191.32     10562531.32      3763234.75     10562638.00
      3763041.99     10562875.81      3763057.10     10563041.18
      3762928.97     10563257.06      3762725.50     10563329.00
      3762688.75     10563585.00      3762526.75     10563771.00
      3762516.50     10563933.00      3762345.00     10564020.00
      3762067.25     10563965.00      3762012.25     10563860.00
      3762057.00     10563741.00      3761909.50     10563541.00

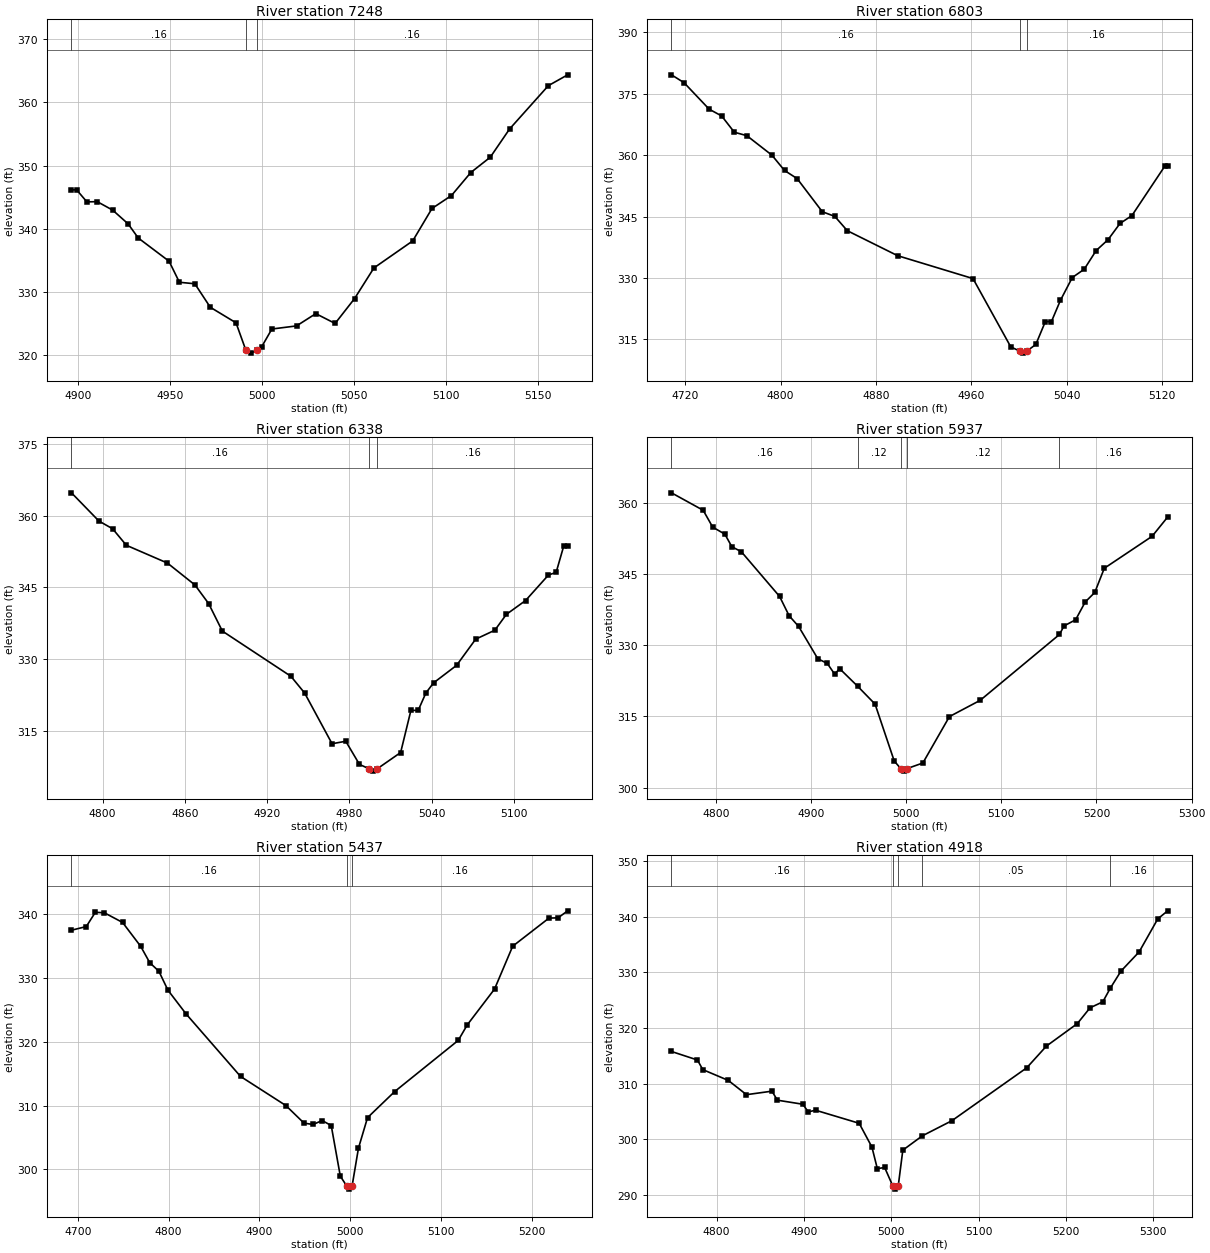
Type RM Length L Ch R = 1,7248,445,445,445
BEGIN DESCRIPTION:
UNT 079 IN BOCR 11.0
END DESCRIPTION:
XS GIS Cut Line= 3
      3764199.60     10559460.19      3764299.61     10559410.19
      3764449.58     10559360.20
#Sta/Elev= 30
  4896.2  346.15  4899.0  346.15  4904.6  344.25  4910.2  344.29  4918.6  342.95
  4927.0  340.78  4932.5  338.55  4949.3  334.87  4954.9  331.55  4963.3  331.31
  4971.7  327.60  4985.7  325.14  4991.0  320.85  4993.8  320.35  4997.0  320.85
  4999.6  321.32  5005.2  324.16  5018.6  324.65  5029.1  326.59  5039.6  325.04
  5050.2  328.98  5060.7  333.81  5081.8  338.08  5092.3  343.21  5102.9  345.26
  5113.4  348.89  5124.0  351.31  5134.5  355.77  5155.6  362.62  5166.1  364.33
#Mann=3,-1,0
  4896.2    0.16       0  4991.0    0.07       0  4997.0    0.16       0
Bank Sta=4991,4997
Exp/Cntr=0.3,0.1

Type RM Length L Ch R = 1,6803,465,465,465
BEGIN DESCRIPTION:
UNT 079 IN BOCR 10.0
END DESCRIPTION:
XS GIS Cut Line= 3
      3764049.65     10559710.20      3764349.61     10559810.19
      3764449.62     10559810.19
#Sta/Elev= 30
  4708.4  379.65  4718.9  377.74  4740.0  371.26  4750.5  369.60  4761.1  365.63
  4771.6  364.79  4792.7  360.01  4803.2  356.29  4813.8  354.30  4834.9  346.21
  4845.4  345.07  4855.9  341.57  4898.1  335.47  4961.3  329.88  4993.0  313.19
  5000.5  312.17  5003.3  311.67  5006.5  312.17  5014.0  313.79  5022.0  319.38
  5027.1  319.38  5034.6  324.54  5044.6  330.14  5054.6  332.16  5064.6  336.72
  5074.6  339.39  5084.6  343.34  5094.6  345.27  5122.1  357.30  5124.6  357.30
#Mann=3,-1,0
  4708.4    0.16       0  5000.5    0.07       0  5006.5    0.16       0
Bank Sta=5000.5,5006.5
Exp/Cntr=0.3,0.1

Type RM Length L Ch R = 1,6338,401,401,401
BEGIN DESCRIPTION:
UNT 079 IN BOCR 9.0
END DESCRIPTION:
XS GIS Cut Line= 3
      3764199.60     10560210.19      3764449.61     10560210.19
      3764549.60     10560160.19
#Sta/Elev= 30
  4777.3  364.76  4797.3  358.86  4807.3  357.24  4817.3  353.79  4847.3  350.06
  4867.3  345.49  4877.3  341.60  4887.3  335.84  4937.3  326.38  4947.3  322.88
  4967.3  312.27  4977.3  312.79  4987.3  307.94  4994.3  307.04  4997.1  306.54
  5000.3  307.04  5017.3  310.43  5024.8  319.25  5030.1  319.25  5035.7  322.88
  5041.3  325.00  5058.1  328.67  5072.0  334.14  5086.0  336.02  5094.4  339.33
  5108.4  342.23  5125.1  347.57  5130.7  348.12  5136.3  353.71  5139.1  353.71
#Mann=3,-1,0
  4777.3    0.16       0  4994.3    0.07       0  5000.3    0.16       0
Bank Sta=4994.3,5000.3
Exp/Cntr=0.3,0.1

Type RM Length L Ch R = 1,5937,500,500,500
BEGIN DESCRIPTION:
UNT 079 IN BOCR 8.0
END DESCRIPTION:
XS GIS Cut Line= 2
      3764216.45     10560599.67      3764735.95     10560556.38
#Sta/Elev= 30
  4753.5  362.04  4786.8  358.37  4796.8  354.83  4809.6  353.34  4816.9  350.71
  4826.9  349.65  4867.1  340.24  4877.1  336.18  4887.1  333.93  4907.2  327.15
  4917.2  326.15  4925.0  323.88  4930.1  325.07  4949.2  321.33  4967.4  317.59
  4987.5  305.64  4994.5  304.00  4997.3  303.50  5000.5  304.00  5017.6  305.21
  5045.5  314.97  5077.8  318.39  5161.1  332.24  5165.9  334.04  5178.1  335.34
  5188.2  339.09  5198.2  341.08  5208.2  346.17  5258.4  352.89  5274.8  356.95
#Mann=5,-1,0
  4753.5    0.16       0  4949.2    0.12       0  4994.5    0.07       0
  5000.5    0.12       0  5161.1    0.16       0
Bank Sta=4994.5,5000.5
Exp/Cntr=0.3,0.1

Type RM Length L Ch R = 1,5437,519,519,519
BEGIN DESCRIPTION:
UNT 079 IN BOCR 7.0
END DESCRIPTION:
XS GIS Cut Line= 2
      3764203.34     10561016.34      3764750.23     10561020.68
#Sta/Elev= 30
  4692.9  337.50  4709.2  338.07  4719.2  340.31  4729.2  340.23  4749.2  338.72
  4769.2  334.97  4779.2  332.40  4789.2  331.07  4799.2  328.10  4819.2  324.37
  4879.2  314.57  4929.2  310.00  4949.2  307.24  4959.2  307.03  4969.2  307.65
  4979.2  306.86  4989.2  298.93  4996.2  297.39  4998.9  296.89  5002.2  297.39
  5009.2  303.31  5019.2  308.10  5049.2  312.20  5119.2  320.22  5129.2  322.67
  5159.2  328.27  5179.2  334.99  5219.2  339.40  5229.2  339.44  5239.8  340.54
#Mann=3,-1,0
  4692.9    0.16       0  4996.2    0.07       0  5002.2    0.16       0
Bank Sta=4996.2,5002.2
Exp/Cntr=0.3,0.1

Type RM Length L Ch R = 1,4918,224,224,224
BEGIN DESCRIPTION:
UNT 079 IN BOCR 6.0
END DESCRIPTION:
XS GIS Cut Line= 2
      3764064.47     10561224.65      3764518.67     10561566.38
#Sta/Elev= 30
  4748.3  315.79  4778.0  314.26  4784.2  312.53  4813.4  310.59  4834.2  308.03
  4863.4  308.66  4869.6  307.04  4898.8  306.31  4905.0  304.93  4913.3  305.24
  4963.3  302.89  4977.9  298.62  4984.1  294.74  4992.5  294.95  5002.0  291.56
  5004.8  291.06  5008.0  291.56  5013.3  298.06  5035.6  300.63  5069.5  303.35
  5155.2  312.85  5177.8  316.76  5213.2  320.80  5227.8  323.64  5242.4  324.71
  5250.9  327.14  5263.2  330.23  5284.0  333.68  5305.4  339.62  5316.7  341.06
#Mann=5,-1,0
  4748.3    0.16       0  5002.0    0.07       0  5008.0    0.16       0
  5035.6    0.05       0  5250.9    0.16       0
Bank Sta=5002,5008
Exp/Cntr=0.3,0.1

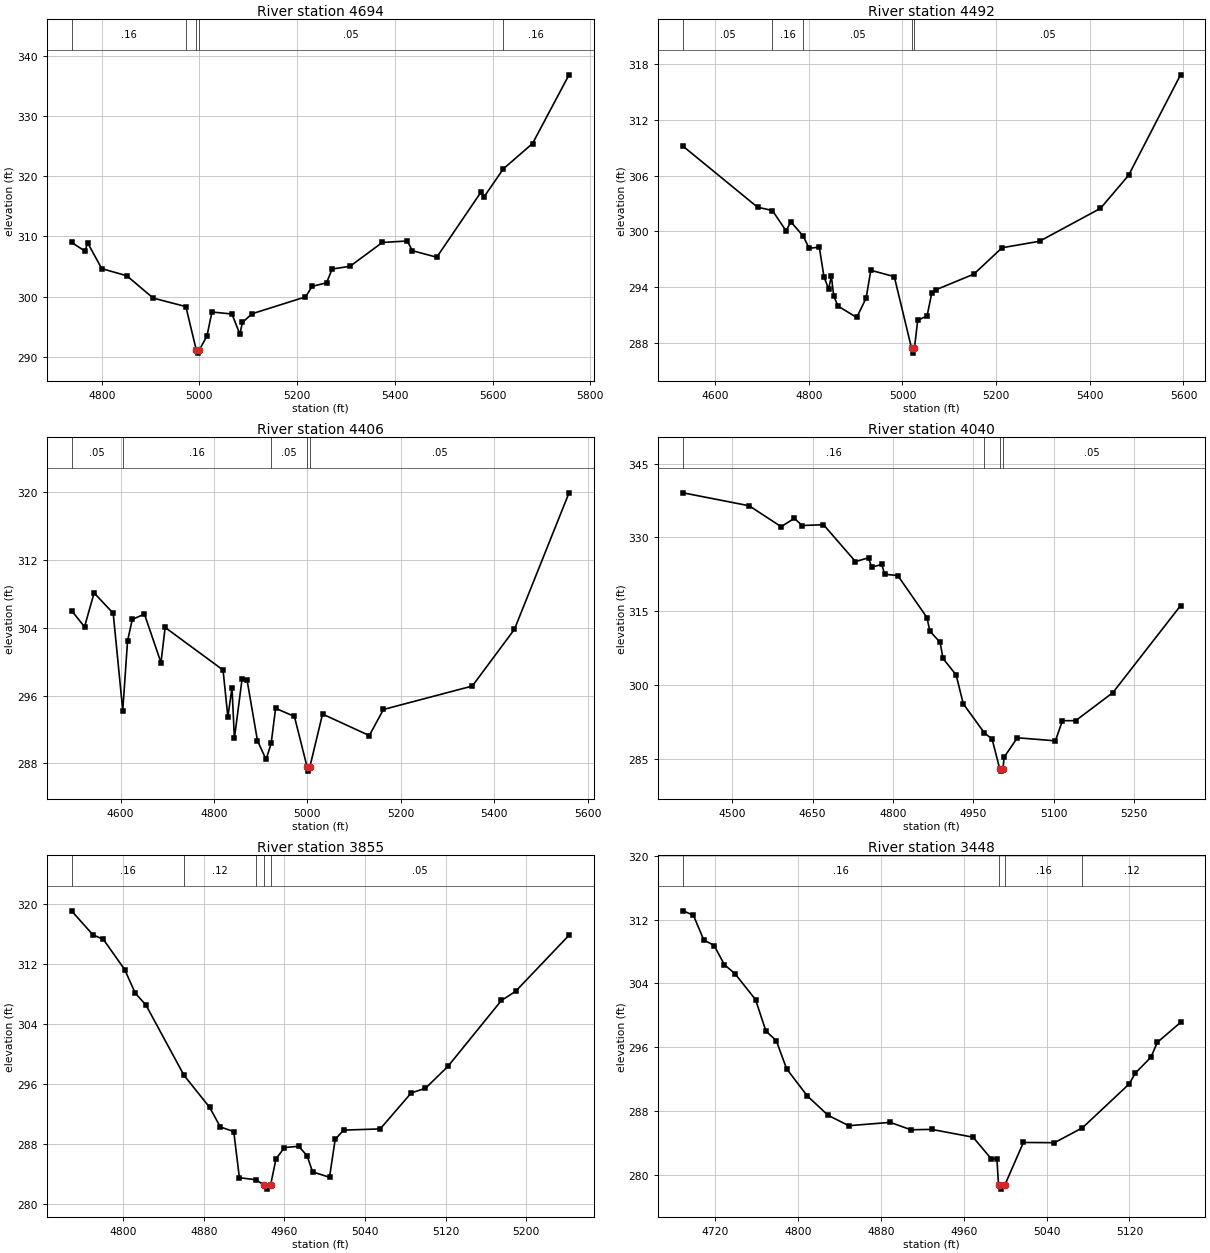
Type RM Length L Ch R = 1,4694,202,202,202
BEGIN DESCRIPTION:
Mapping XS a3d13a2e
END DESCRIPTION:
XS GIS Cut Line= 2
      3764008.08     10561209.92      3764233.78     10562202.99
#Sta/Elev= 30
  4738.2  308.99  4765.9  307.54  4771.0  308.94  4800.0  304.64  4851.3  303.45
  4905.4  299.74  4972.2  298.33  4993.6  291.10  4996.4  290.60  4999.6  291.10
  5015.4  293.44  5025.6  297.43  5066.6  297.10  5082.8  293.74  5087.9  295.69
  5107.7  297.14  5217.1  299.94  5230.7  301.69  5260.2  302.28  5271.7  304.57
  5308.4  305.03  5374.3  308.98  5425.6  309.23  5435.8  307.62  5485.8  306.53
  5577.1  317.43  5582.2  316.51  5622.2  321.22  5681.9  325.42  5756.6  336.83
#Mann=5,-1,0
  4738.2    0.16       0  4972.2    0.05       0  4993.6    0.04       0
  4999.6    0.05       0  5622.2    0.16       0
Bank Sta=4993.6,4999.6
Exp/Cntr=0.3,0.1

Type RM Length L Ch R = 1,4492,86,86,86
BEGIN DESCRIPTION:
UNT 079 IN BOCR 5.0
END DESCRIPTION:
XS GIS Cut Line= 3
      3763963.80     10561183.84      3764013.28     10561452.10
      3764036.72     10562241.16
#Sta/Elev= 30
  4531.5  309.15  4690.5  302.60  4722.3  302.24  4751.4  300.06  4761.7  301.03
  4788.1  299.49  4800.8  298.18  4822.4  298.31  4832.4  295.12  4842.4  293.79
  4848.2  295.19  4853.2  293.06  4862.4  291.97  4902.4  290.75  4922.4  292.84
  4932.4  295.82  4982.5  295.14  5019.5  287.42  5022.2  286.92  5025.5  287.42
  5032.5  290.45  5052.5  290.91  5062.5  293.37  5072.5  293.75  5152.5  295.41
  5212.6  298.24  5292.6  298.94  5422.7  302.47  5482.7  306.02  5593.7  316.82
#Mann=5,-1,0
  4531.5    0.05       0  4722.3    0.16       0  4788.1    0.05       0
  5019.5    0.04       0  5025.5    0.05       0
Bank Sta=5019.5,5025.5
Exp/Cntr=0.3,0.1

Type RM Length L Ch R = 1,4406,366,366,366
BEGIN DESCRIPTION:
Mapping XS c013dd6c
END DESCRIPTION:
XS GIS Cut Line= 3
      3763851.82     10561202.96      3763945.58     10561640.47
      3763987.13     10562256.83
#Sta/Elev= 30
  4495.1  306.06  4522.9  304.13  4543.4  308.14  4584.3  305.73  4604.8  294.24
  4615.0  302.47  4625.2  305.01  4651.2  305.64  4686.6  299.90  4695.5  304.06
  4819.5  299.03  4829.8  293.50  4838.7  296.94  4843.8  290.96  4860.4  298.03
  4870.7  297.91  4893.2  290.68  4911.6  288.47  4922.5  290.36  4932.0  294.51
  4972.3  293.55  4999.4  287.59  5002.1  287.09  5005.4  287.59  5032.5  293.83
  5132.7  291.29  5162.8  294.37  5353.2  297.14  5443.4  303.84  5560.3  319.96
#Mann=5,-1,0
  4495.1    0.05       0  4604.8    0.16       0  4922.5    0.05       0
  4999.4    0.04       0  5005.4    0.05       0
Bank Sta=4999.4,5005.4
Exp/Cntr=0.3,0.1

Type RM Length L Ch R = 1,4040,185,185,185
BEGIN DESCRIPTION:
Mapping XS 6c7f3e92
END DESCRIPTION:
XS GIS Cut Line= 2
      3763608.78     10561373.14      3763945.56     10562237.66
#Sta/Elev= 30
  4408.4  339.07  4531.6  336.44  4591.4  332.19  4615.9  333.88  4630.6  332.42
  4670.3  332.59  4730.0  325.09  4754.5  325.87  4759.9  323.95  4779.0  324.51
  4784.4  322.52  4808.9  322.25  4863.3  313.71  4868.7  310.95  4887.8  308.68
  4893.2  305.40  4917.7  302.04  4931.1  296.15  4970.5  290.25  4984.8  289.01
  4998.9  282.99  5001.7  282.49  5004.9  282.99  5007.3  285.34  5031.8  289.27
  5102.8  288.65  5116.0  292.75  5140.5  292.74  5210.1  298.46  5336.2  316.12
#Mann=4,-1,0
  4408.4    0.16       0  4970.5    0.05       0  4998.9    0.04       0
  5004.9    0.05       0
Bank Sta=4998.9,5004.9
Exp/Cntr=0.3,0.1

Type RM Length L Ch R = 1,3855,407,407,407
BEGIN DESCRIPTION:
UNT 079 IN BOCR 4.0
END DESCRIPTION:
XS GIS Cut Line= 3
      3763699.62     10561810.21      3763749.61     10561960.19
      3763899.61     10562260.19
#Sta/Elev= 30
  4748.9  319.11  4770.0  315.92  4780.5  315.29  4801.6  311.27  4812.1  308.12
  4822.7  306.53  4860.5  297.14  4885.9  292.87  4896.5  290.25  4909.8  289.64
  4915.4  283.47  4931.8  283.21  4940.3  282.45  4943.1  281.95  4946.3  282.45
  4951.7  285.99  4960.1  287.50  4974.1  287.67  4982.5  286.43  4988.0  284.26
  5004.8  283.53  5010.4  288.58  5018.8  289.83  5055.1  289.99  5085.9  294.80
  5099.9  295.41  5122.2  298.33  5175.3  307.14  5189.3  308.35  5242.4  315.85
#Mann=5,-1,0
  4748.9    0.16       0  4860.5    0.12       0  4931.8    0.05       0
  4940.3    0.04       0  4946.3    0.05       0
Bank Sta=4940.3,4946.3
Exp/Cntr=0.3,0.1

Type RM Length L Ch R = 1,3448,439,439,439
BEGIN DESCRIPTION:
UNT 079 IN BOCR 3.0
END DESCRIPTION:
XS GIS Cut Line= 3
      3763499.61     10561860.15      3763499.61     10562160.19
      3763649.60     10562260.18
#Sta/Elev= 30
  4689.0  313.11  4699.0  312.55  4709.0  309.46  4719.0  308.76  4729.0  306.34
  4739.0  305.25  4759.0  301.98  4769.0  298.03  4779.0  296.84  4789.0  293.30
  4809.0  289.90  4829.0  287.48  4849.0  286.17  4889.0  286.59  4909.0  285.66
  4929.0  285.71  4969.0  284.73  4986.5  282.03  4992.0  282.03  4993.6  278.72
  4996.3  278.22  4999.6  278.72  5017.6  284.07  5047.6  284.04  5074.6  285.91
  5119.7  291.40  5125.7  292.77  5140.8  294.77  5146.8  296.61  5169.3  299.12
#Mann=4,-1,0
  4689.0    0.16       0  4993.6    0.07       0  4999.6    0.16       0
  5074.6    0.12       0
Bank Sta=4993.6,4999.6
Exp/Cntr=0.3,0.1

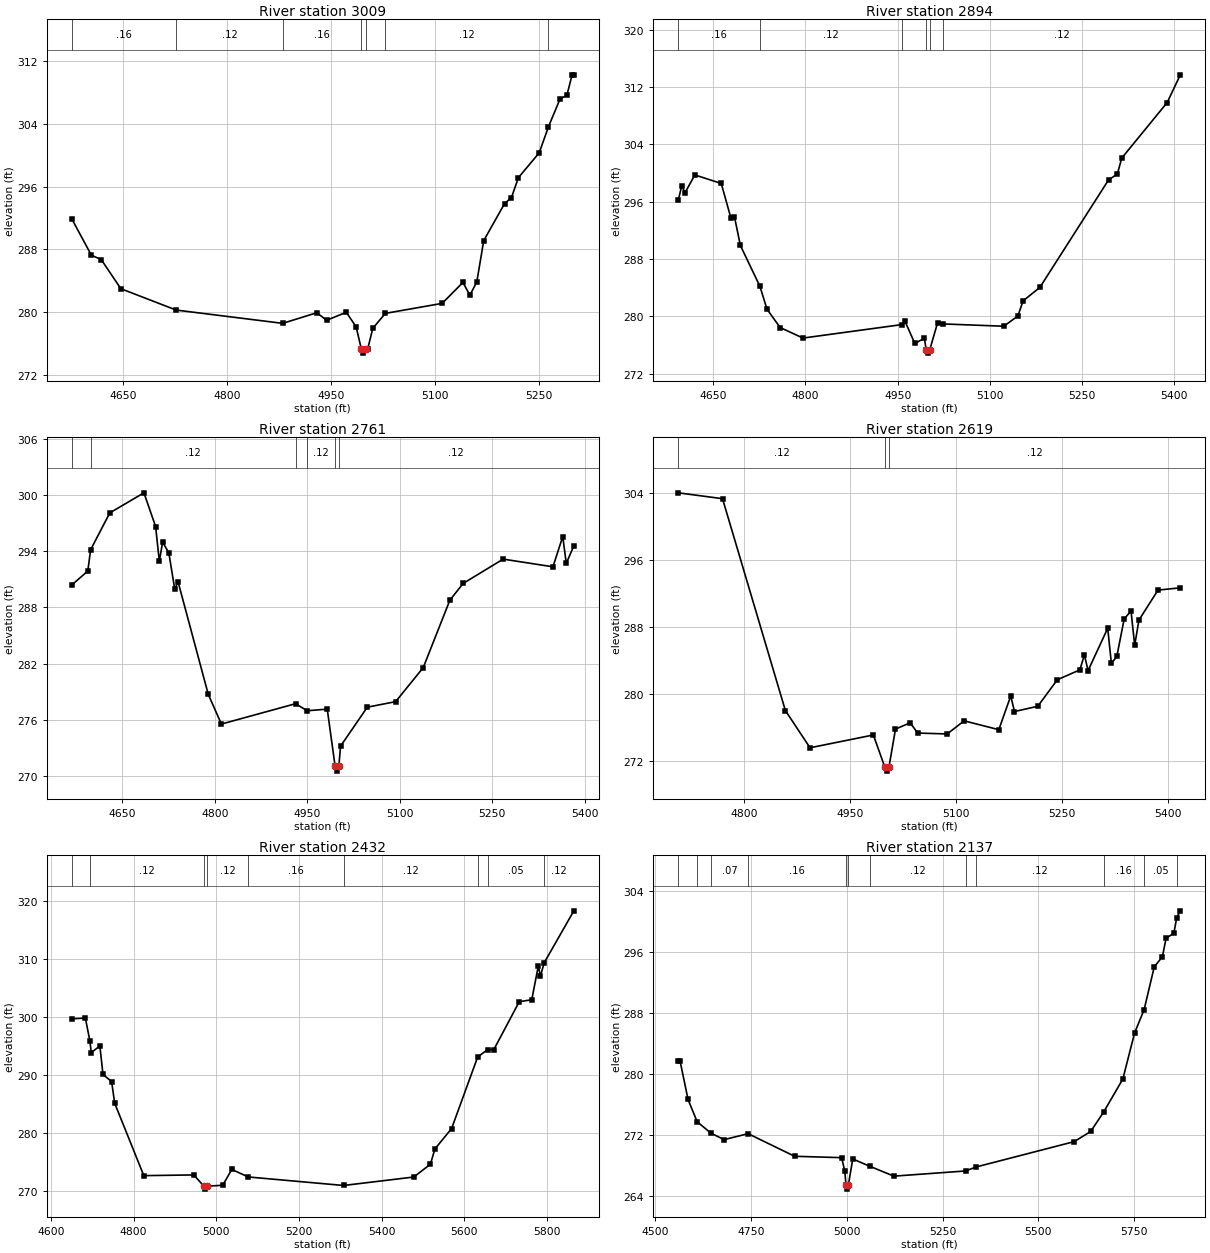
Type RM Length L Ch R = 1,3009,115,115,115
BEGIN DESCRIPTION:
UNT 079 IN BOCR 2.0
END DESCRIPTION:
XS GIS Cut Line= 3
      3762999.58     10562110.16      3763299.61     10562410.19
      3763599.60     10562410.19
#Sta/Elev= 30
  4576.0  291.90  4604.3  287.27  4618.5  286.72  4646.8  283.01  4726.6  280.29
  4880.2  278.60  4929.6  279.95  4943.7  278.99  4972.0  280.01  4986.2  278.16
  4993.8  275.31  4996.5  274.81  4999.8  275.31  5002.8  275.31  5010.3  277.97
  5028.4  279.87  5110.3  281.14  5140.3  283.81  5150.3  282.18  5160.3  283.87
  5170.3  289.13  5200.3  293.83  5210.3  294.61  5220.3  297.14  5250.3  300.30
  5263.7  303.62  5280.3  307.15  5290.3  307.64  5297.8  310.23  5300.3  310.23
#Mann=7,-1,0
  4576.0    0.16       0  4726.6    0.12       0  4880.2    0.16       0
  4993.8    0.07       0  4999.8    0.16       0  5028.4    0.12       0
  5263.7    0.16       0
Bank Sta=4993.8,4999.8
Exp/Cntr=0.3,0.1

Type RM Length L Ch R = 1,2894,133,133,133
BEGIN DESCRIPTION:
Mapping XS a59513a9
END DESCRIPTION:
XS GIS Cut Line= 3
      3762872.34     10562290.92      3763170.56     10562465.42
      3763578.14     10562702.42
#Sta/Elev= 30
  4593.0  296.17  4598.5  298.14  4604.3  297.27  4620.0  299.72  4663.0  298.53
  4678.7  293.71  4684.5  293.88  4694.1  289.89  4725.9  284.19  4737.4  281.00
  4758.8  278.44  4796.0  276.97  4957.0  278.85  4962.1  279.29  4977.9  276.23
  4993.6  276.93  4996.4  275.37  4999.1  274.87  5002.4  275.37  5015.1  279.13
  5024.4  278.94  5122.7  278.62  5145.6  280.04  5154.2  282.16  5181.5  284.04
  5293.2  299.02  5307.6  299.85  5314.7  302.07  5388.6  309.81  5410.0  313.68
#Mann=6,-1,0
  4593.0    0.16       0  4725.9    0.12       0  4957.0    0.16       0
  4996.4    0.07       0  5002.4    0.16       0  5024.4    0.12       0
Bank Sta=4996.4,5002.4
Exp/Cntr=0.3,0.1

Type RM Length L Ch R = 1,2761,142,142,142
BEGIN DESCRIPTION:
Mapping XS ecbf56e8
END DESCRIPTION:
XS GIS Cut Line= 3
      3762832.01     10562435.47      3763115.87     10562540.94
      3763561.19     10562793.55
#Sta/Elev= 30
  4567.9  290.38  4593.9  291.87  4598.5  294.14  4629.6  298.07  4685.0  300.21
  4704.0  296.61  4710.0  292.90  4715.3  294.95  4725.4  293.81  4735.0  289.94
  4740.4  290.72  4789.4  278.72  4810.7  275.55  4931.1  277.72  4949.9  276.97
  4982.5  277.14  4995.3  271.03  4998.1  270.53  5001.3  271.03  5004.1  273.19
  5047.5  277.35  5093.5  277.94  5138.3  281.57  5181.5  288.76  5203.1  290.55
  5268.0  293.14  5348.8  292.32  5364.7  295.55  5370.4  292.69  5382.7  294.56
#Mann=6,-1,0
  4567.9    0.16       0  4598.5    0.12       0  4931.1    0.16       0
  4949.9    0.12       0  4995.3    0.07       0  5001.3    0.12       0
Bank Sta=4995.3,5001.3
Exp/Cntr=0.3,0.1

Type RM Length L Ch R = 1,2619,187,187,187
BEGIN DESCRIPTION:
Mapping XS 28ab1386
END DESCRIPTION:
XS GIS Cut Line= 3
      3762889.28     10562553.95      3763101.55     10562680.27
      3763545.73     10562814.04
#Sta/Elev= 30
  4706.3  304.07  4769.0  303.37  4858.0  278.06  4892.9  273.61  4982.6  275.14
  4998.7  271.32  5001.4  270.82  5004.7  271.32  5013.9  275.84  5034.7  276.60
  5045.3  275.37  5087.1  275.26  5111.1  276.83  5160.2  275.77  5177.1  279.80
  5182.4  277.94  5215.4  278.57  5243.1  281.74  5275.0  282.92  5281.4  284.71
  5286.6  282.83  5314.4  287.89  5319.6  283.69  5327.3  284.52  5337.7  288.99
  5347.4  289.96  5352.6  285.85  5358.6  288.86  5385.6  292.45  5417.2  292.72
#Mann=3,-1,0
  4706.3    0.12       0  4998.7    0.07       0  5004.7    0.12       0
Bank Sta=4998.7,5004.7
Exp/Cntr=0.3,0.1

Type RM Length L Ch R = 1,2432,295,295,295
BEGIN DESCRIPTION:
Mapping XS f7848c04
END DESCRIPTION:
XS GIS Cut Line= 4
      3762833.00     10562600.33      3763054.34     10562847.72
      3763226.22     10562996.16      3763869.42     10562868.56
#Sta/Elev= 30
  4650.5  299.65  4683.4  299.79  4694.3  295.85  4697.6  293.82  4718.5  294.97
  4726.0  290.05  4746.9  288.82  4754.4  285.07  4824.8  272.58  4945.5  272.70
  4970.5  270.75  4973.2  270.25  4976.5  270.75  5015.8  270.92  5037.7  273.65
  5077.5  272.35  5308.1  270.88  5478.1  272.34  5518.3  274.56  5529.1  277.18
  5569.5  280.71  5632.5  293.04  5656.4  294.34  5671.8  294.35  5733.2  302.61
  5763.5  302.95  5779.3  308.77  5784.4  307.01  5793.5  309.33  5865.3  318.30
#Mann=9,-1,0
  4650.5    0.07       0  4694.3    0.12       0  4970.5    0.07       0
  4976.5    0.12       0  5077.5    0.16       0  5308.1    0.12       0
  5632.5    0.16       0  5656.4    0.05       0  5793.5    0.12       0
Bank Sta=4970.5,4976.5
Exp/Cntr=0.3,0.1

Type RM Length L Ch R = 1,2137,262,262,262
BEGIN DESCRIPTION:
Mapping XS 8eb7bfab
END DESCRIPTION:
XS GIS Cut Line= 5
      3762840.80     10562686.27      3762989.24     10563074.28
      3763056.95     10563162.82      3763155.91     10563204.49
      3763815.94     10563053.77
#Sta/Elev= 30
  4559.8  281.73  4564.6  281.73  4585.4  276.69  4609.1  273.78  4644.9  272.29
  4679.4  271.43  4742.3  272.21  4863.8  269.25  4986.5  269.07  4994.8  267.32
  4998.0  265.45  5000.8  264.95  5004.0  265.45  5015.6  268.90  5059.6  267.95
  5123.1  266.65  5310.6  267.33  5336.2  267.83  5594.0  271.17  5637.0  272.50
  5670.7  275.03  5721.0  279.37  5751.8  285.42  5776.5  288.43  5803.1  294.07
  5824.3  295.37  5833.8  297.78  5854.3  298.48  5861.8  300.51  5871.1  301.39
#Mann=12,-1,0
  4559.8    0.16       0  4609.1    0.12       0  4644.9    0.07       0
  4742.3    0.16       0  4998.0    0.07       0  5004.0    0.16       0
  5059.6    0.12       0  5310.6    0.16       0  5336.2    0.12       0
  5670.7    0.16       0  5776.5    0.05       0  5861.8    0.12       0
Bank Sta=4998,5004
Exp/Cntr=0.3,0.1

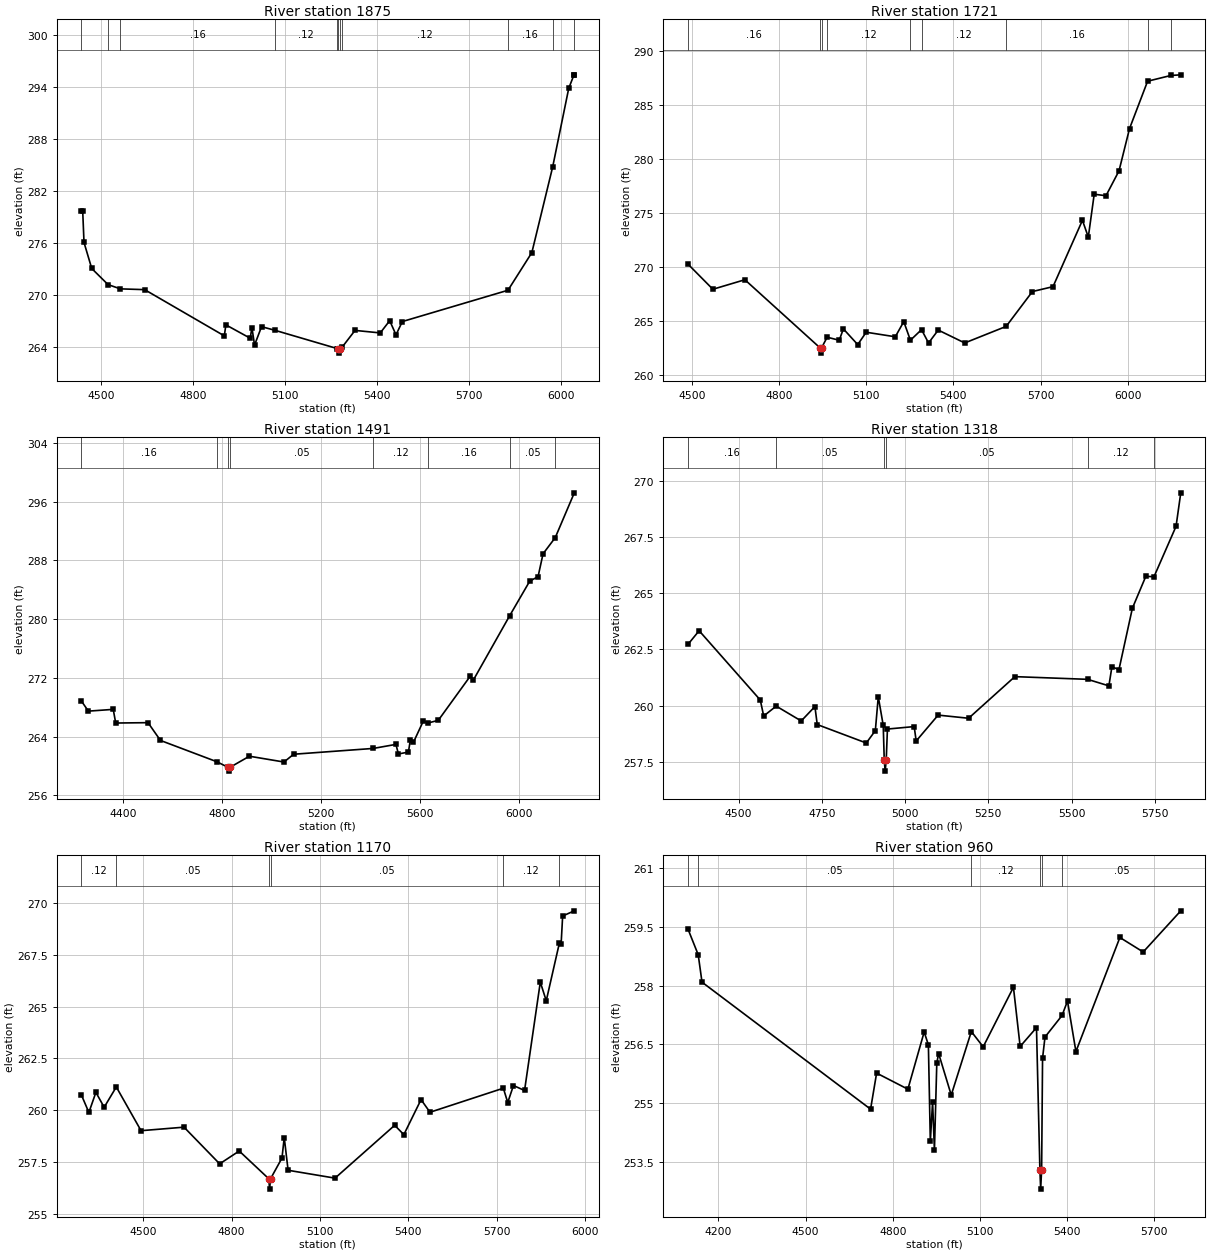
Type RM Length L Ch R = 1,1875,154,154,154
BEGIN DESCRIPTION:
Mapping XS 6f5110f8
END DESCRIPTION:
XS GIS Cut Line= 4
      3762773.10     10562707.14      3762866.84     10563235.74
      3762955.39     10563399.80      3763814.71     10563191.48
#Sta/Elev= 30
  4434.9  279.68  4439.0  279.68  4443.3  276.02  4468.5  273.02  4521.7  271.16
  4562.0  270.67  4641.1  270.58  4900.9  265.25  4906.0  266.52  4985.3  264.98
  4991.0  266.20  4999.5  264.18  5022.3  266.31  5065.3  265.90  5268.7  263.79
  5272.7  263.76  5275.5  263.26  5278.7  263.76  5286.3  264.00  5327.2  265.88
  5409.5  265.59  5440.3  267.00  5460.9  265.37  5481.5  266.90  5826.1  270.51
  5903.9  274.85  5971.9  284.74  6024.2  293.79  6040.7  295.29  6042.4  295.35
#Mann=11,-1,0
  4434.9    0.16       0  4521.7    0.07       0  4562.0    0.16       0
  5065.3    0.12       0  5268.7    0.16       0  5272.7    0.07       0
  5278.7    0.16       0  5286.3    0.12       0  5826.1    0.16       0
  5971.9    0.05       0  6040.7    0.12       0
Bank Sta=5272.7,5278.7
Exp/Cntr=0.3,0.1

Type RM Length L Ch R = 1,1721,230,230,230
BEGIN DESCRIPTION:
Mapping XS 17f38b3f
END DESCRIPTION:
XS GIS Cut Line= 5
      3762689.76     10562824.33      3762694.97     10563272.20
      3762770.49     10563350.32      3762947.57     10563483.14
      3763853.81     10563342.51
#Sta/Elev= 30
  4486.9  270.28  4572.8  267.95  4682.8  268.83  4940.8  262.55  4943.6  262.05
  4946.8  262.55  4965.8  263.52  5007.4  263.24  5021.5  264.29  5070.9  262.84
  5100.1  263.98  5200.1  263.56  5229.3  264.96  5252.1  263.24  5290.3  264.22
  5314.5  262.99  5347.8  264.18  5438.9  262.99  5581.4  264.52  5671.7  267.74
  5742.5  268.19  5843.7  274.32  5863.9  272.77  5884.2  276.73  5924.7  276.59
  5969.5  278.89  6005.6  282.79  6067.8  287.17  6147.8  287.70  6181.9  287.76
#Mann=9,-1,0
  4486.9    0.16       0  4940.8    0.07       0  4946.8    0.16       0
  4965.8    0.12       0  5252.1    0.05       0  5290.3    0.12       0
  5581.4    0.16       0  6067.8    0.05       0  6147.8    0.12       0
Bank Sta=4940.8,4946.8
Exp/Cntr=0.3,0.1

Type RM Length L Ch R = 1,1491,173,173,173
BEGIN DESCRIPTION:
UNT 079 IN BOCR 1.0
END DESCRIPTION:
XS GIS Cut Line= 4
      3762601.82     10562852.31      3762545.40     10563446.89
      3762857.90     10563603.14      3763894.92     10563472.97
#Sta/Elev= 30
  4232.8  268.84  4260.8  267.47  4361.3  267.71  4371.3  265.85  4501.9  265.90
  4552.1  263.48  4780.7  260.57  4826.2  259.80  4829.0  259.30  4832.2  259.80
  4911.6  261.33  5051.3  260.54  5090.4  261.60  5411.9  262.39  5503.7  262.94
  5513.8  261.64  5554.1  261.89  5561.8  263.49  5574.2  263.20  5614.5  266.13
  5635.3  265.87  5675.0  266.22  5803.2  272.19  5816.1  271.67  5963.5  280.47
  6044.6  285.18  6078.1  285.78  6098.3  288.90  6147.6  291.10  6224.6  297.20
#Mann=8,-1,0
  4232.8    0.16       0  4780.7    0.05       0  4826.2    0.03       0
  4832.2    0.05       0  5411.9    0.12       0  5635.3    0.16       0
  5963.5    0.05       0  6147.6    0.16       0
Bank Sta=4826.2,4832.2
Exp/Cntr=0.3,0.1

Type RM Length L Ch R = 1,1318,148,148,148
BEGIN DESCRIPTION:
Mapping XS 8798792d
END DESCRIPTION:
XS GIS Cut Line= 5
      3762398.06     10563088.35      3762513.09     10563594.02
      3762708.40     10563726.40      3762832.10     10563663.47
      3763413.70     10563589.68
#Sta/Elev= 30
  4348.1  262.72  4381.8  263.33  4565.4  260.25  4575.6  259.54  4613.2  259.98
  4688.3  259.32  4729.4  259.96  4736.4  259.16  4883.6  258.34  4910.8  258.89
  4919.6  260.40  4934.5  259.12  4937.5  257.59  4940.3  257.09  4943.5  257.59
  4947.1  258.96  5027.4  259.07  5033.4  258.43  5099.3  259.58  5190.8  259.44
  5329.6  261.29  5548.0  261.17  5611.9  260.88  5621.0  261.73  5642.1  261.60
  5682.4  264.33  5722.8  265.75  5747.3  265.73  5813.5  267.97  5827.7  269.46
#Mann=6,-1,0
  4348.1    0.16       0  4613.2    0.05       0  4937.5    0.03       0
  4943.5    0.05       0  5548.0    0.12       0  5747.3    0.16       0
Bank Sta=4937.5,4943.5
Exp/Cntr=0.3,0.1

Type RM Length L Ch R = 1,1170,210,210,210
BEGIN DESCRIPTION:
Mapping XS 9449a003
END DESCRIPTION:
XS GIS Cut Line= 5
      3762291.33     10563115.96      3762473.62     10563733.14
      3762640.28     10563860.74      3762890.28     10563712.30
      3763413.71     10563628.97
#Sta/Elev= 30
  4289.7  260.73  4315.0  259.89  4338.8  260.86  4366.9  260.14  4408.1  261.12
  4492.2  259.01  4638.2  259.18  4759.2  257.41  4825.7  258.03  4926.1  256.69
  4928.8  256.19  4932.1  256.69  4970.9  257.69  4978.6  258.68  4991.7  257.10
  5151.1  256.72  5353.7  259.27  5384.9  258.82  5443.3  260.51  5473.7  259.90
  5722.9  261.06  5737.8  260.37  5757.2  261.19  5794.9  260.95  5848.4  266.18
  5868.6  265.28  5913.1  268.06  5919.2  268.04  5924.3  269.37  5963.9  269.62
#Mann=6,-1,0
  4289.7    0.12       0  4408.1    0.05       0  4926.1    0.03       0
  4932.1    0.05       0  5722.9    0.12       0  5913.1    0.16       0
Bank Sta=4926.1,4932.1
Exp/Cntr=0.3,0.1

Type RM Length L Ch R = 1,960,0,0,0
BEGIN DESCRIPTION:
Mapping XS 4a8ce3fd
END DESCRIPTION:
XS GIS Cut Line= 6
      3762143.82     10563138.49      3762264.28     10563675.25
      3762535.29     10564024.20      3762653.97     10563995.86
      3762889.56     10563822.27      3763176.45     10563774.75
#Sta/Elev= 30
  4094.7  259.45  4130.2  258.79  4143.3  258.09  4723.8  254.85  4744.6  255.77
  4852.3  255.36  4908.4  256.82  4922.9  256.49  4929.6  254.03  4937.4  255.04
  4943.7  253.80  4951.9  256.03  4958.2  256.27  5001.6  255.21  5070.8  256.83
  5111.6  256.44  5215.8  257.96  5238.9  256.45  5295.2  256.93  5306.9  253.31
  5309.6  252.81  5312.9  253.31  5316.1  256.15  5324.5  256.69  5383.2  257.24
  5402.0  257.61  5431.0  256.32  5582.4  259.23  5662.7  258.86  5792.1  259.91
#Mann=6,-1,0
  4094.7    0.12       0  4130.2    0.05       0  5070.8    0.12       0
  5306.9    0.03       0  5312.9    0.12       0  5383.2    0.05       0
Bank Sta=5306.9,5312.9
Exp/Cntr=0.3,0.1

Chan Stop Cuts=-1