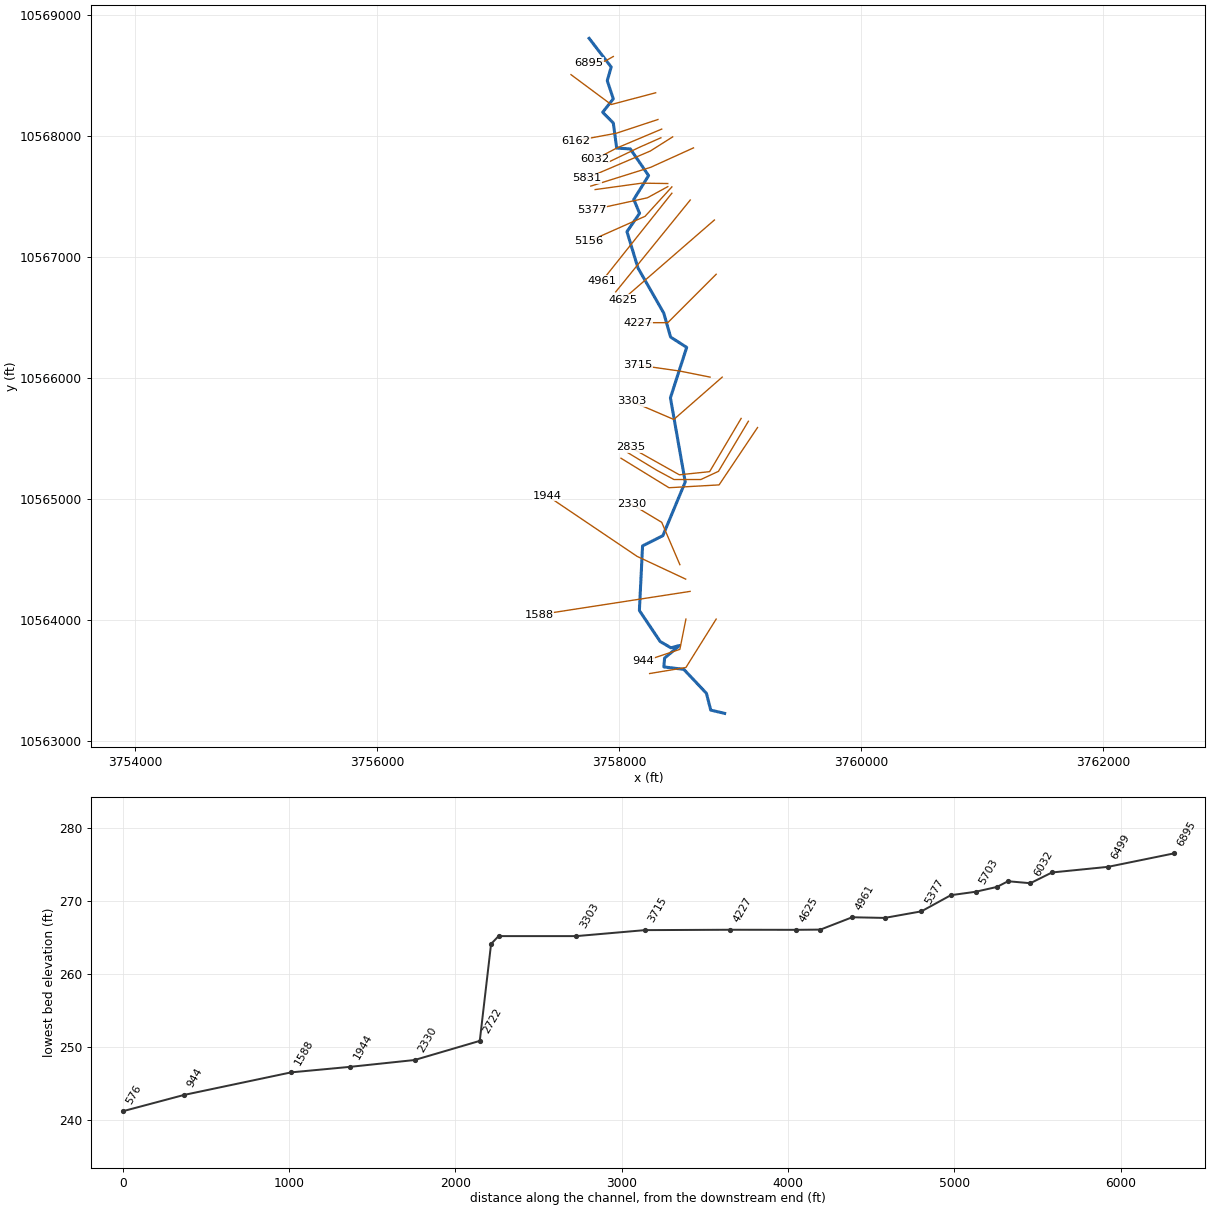
--- UNT 080 IN BOCR.prj (project) ---

Proj Title=UNT 080 IN BOCR Base Level Engineering
Current Plan=p01
Default Exp/Contr=0.3,0.1
English Units
Geom File=g01
Flow File=f01
Plan File=p01
BEGIN DESCRIPTION:
UNT 080 IN BOCR
END DESCRIPTION:

--- UNT 080 IN BOCR.p01 (plan) ---

Plan Title=Multiple Run
Short Identifier=Multiple
Geom File=g01
Flow File=f01
Subcritical Flow
K Sum by GR= 0
Std Step Tol= 0.01
Critical Tol= 0.01
Num of Std Step Trials= 20
Max Error Tol= 0.3
Flow Tol Ratio= 0.001
Split Flow NTrial= 30
Split Flow Tol= 0.02
Split Flow Ratio= 0.02
Log Output Level= 0
Friction Slope Method= 1
Unsteady Friction Slope Method= 2
Unsteady Bridges Friction Slope Method= 1
Parabolic Critical Depth
Global Vel Dist=  1 , 1 , 1
Global Log Level= 0
CheckData=True
Encroach Param= -1, 0, 0, 0
BEGIN DESCRIPTION:
Multiple Run
END DESCRIPTION:

--- UNT 080 IN BOCR.f01 (steady flow) ---

Flow Title=Multiple
Number of Profiles=7
Profile Names=10-year,25-year,50-year,1pct_min,100-year,1pct_plu,500-year
River Rch & RM= UNT 080 IN BOCR,Reach-1,6895
     802    1103    1354    1221    1652    2234    2467
Boundary for River Rch & Prof#=UNT 080 IN BOCR,Reach-1,1
Up Type=0
Dn Type=3
Dn Slope=0.005
Boundary for River Rch & Prof#=UNT 080 IN BOCR,Reach-1,2
Up Type=0
Dn Type=3
Dn Slope=0.005
Boundary for River Rch & Prof#=UNT 080 IN BOCR,Reach-1,3
Up Type=0
Dn Type=3
Dn Slope=0.005
Boundary for River Rch & Prof#=UNT 080 IN BOCR,Reach-1,4
Up Type=0
Dn Type=3
Dn Slope=0.005
Boundary for River Rch & Prof#=UNT 080 IN BOCR,Reach-1,5
Up Type=0
Dn Type=3
Dn Slope=0.005
Boundary for River Rch & Prof#=UNT 080 IN BOCR,Reach-1,6
Up Type=0
Dn Type=3
Dn Slope=0.005
Boundary for River Rch & Prof#=UNT 080 IN BOCR,Reach-1,7
Up Type=0
Dn Type=3
Dn Slope=0.005

--- UNT 080 IN BOCR.g01 (geometry) ---

Geom Title=Existing Conditions

River Reach=UNT 080 IN BOCR,Reach-1
Reach XY= 30
      3757749.61     10568810.19      3757932.00     10568573.06
      3757899.61     10568460.19      3757949.61     10568310.19
      3757861.69     10568199.36      3757949.61     10568110.19
      3757977.31     10567903.18      3758090.16     10567896.23
      3758241.20     10567675.75      3758118.80     10567478.70
      3758166.55     10567364.11      3758062.38     10567212.20
      3758153.50     10566912.00      3758366.50     10566539.00
      3758423.00     10566341.00      3758556.00     10566256.00
      3758421.50     10565839.00      3758544.00     10565144.00
      3758359.25     10564700.00      3758191.25     10564615.00
      3758165.00     10564081.00      3758336.75     10563825.00
      3758425.50     10563773.00      3758497.25     10563792.00
      3758373.25     10563688.00      3758367.25     10563615.00
      3758532.00     10563595.00      3758719.00     10563397.00
      3758754.75     10563258.00      3758869.75     10563231.00

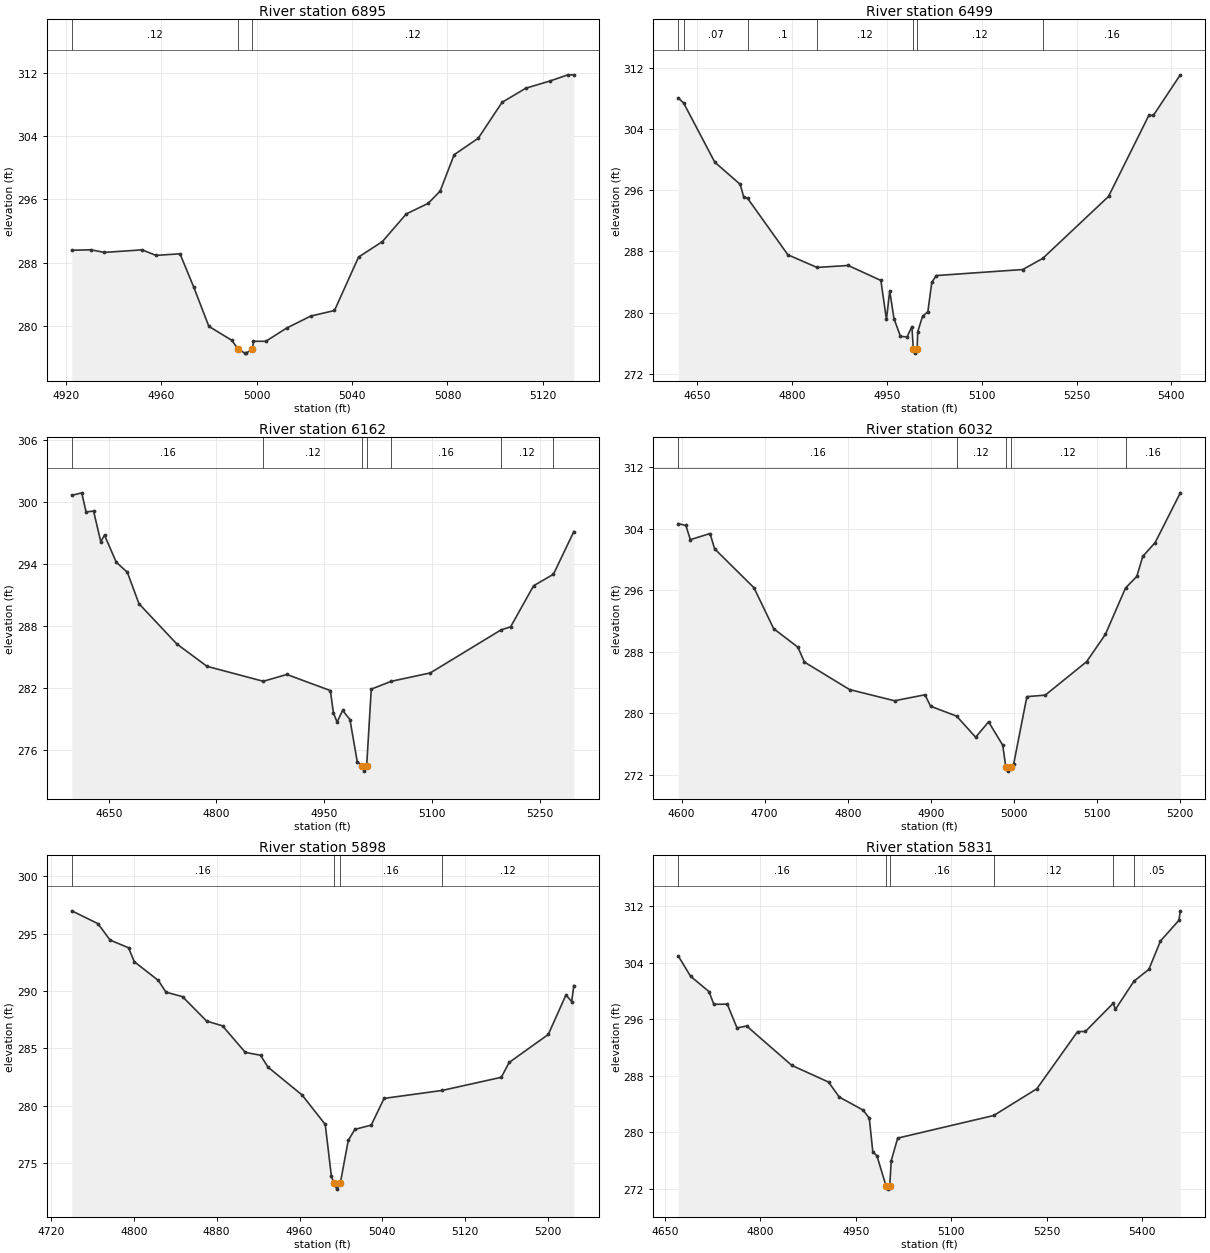
Type RM Length L Ch R = 1,6895,396,396,396
BEGIN DESCRIPTION:
UNT 080 IN BOCR 15.0
END DESCRIPTION:
XS GIS Cut Line= 3
      3757949.59     10568660.18      3757882.11     10568621.87
      3757749.62     10568610.19
#Sta/Elev= 30
  4922.4  289.57  4930.3  289.63  4936.1  289.30  4951.9  289.62  4957.7  288.92
  4967.8  289.12  4973.6  284.88  4979.9  279.93  4989.5  278.17  4992.2  277.04
  4995.0  276.54  4995.5  276.54  4998.2  277.04  4998.6  278.04  5003.8  278.04
  5012.5  279.71  5022.6  281.23  5032.6  281.94  5042.7  288.71  5052.7  290.67
  5062.7  294.17  5071.9  295.51  5076.9  297.06  5082.8  301.67  5092.9  303.76
  5102.9  308.31  5112.9  310.10  5123.0  311.01  5130.5  311.79  5133.0  311.79
#Mann=3,-1,0
  4922.4    0.12       0  4992.2    0.07       0  4998.2    0.12       0
Bank Sta=4992.2,4998.2
Exp/Cntr=0.3,0.1

Type RM Length L Ch R = 1,6499,337,337,337
BEGIN DESCRIPTION:
UNT 080 IN BOCR 14.0
END DESCRIPTION:
XS GIS Cut Line= 3
      3758299.61     10568360.19      3757932.00     10568263.16
      3757599.64     10568510.17
#Sta/Elev= 30
  4619.8  308.07  4628.4  307.39  4677.6  299.66  4717.9  296.76  4723.2  295.16
  4729.7  294.92  4793.3  287.55  4839.4  285.90  4888.7  286.16  4940.4  284.20
  4949.2  279.10  4954.4  282.85  4961.1  279.21  4971.4  276.89  4981.8  276.82
  4989.5  278.18  4991.7  275.20  4994.4  274.70  4997.7  275.20  4998.7  277.50
  5006.3  279.51  5014.7  280.11  5020.9  283.94  5027.9  284.84  5164.9  285.63
  5196.4  287.08  5300.5  295.18  5364.3  305.78  5371.4  305.77  5414.1  311.08
#Mann=7,-1,0
  4619.8    0.12       0  4628.4    0.07       0  4729.7     0.1       0
  4839.4    0.12       0  4991.7    0.07       0  4997.7    0.12       0
  5196.4    0.16       0
Bank Sta=4991.7,4997.7
Exp/Cntr=0.3,0.1

Type RM Length L Ch R = 1,6162,130,130,130
BEGIN DESCRIPTION:
Mapping XS b46729d5
END DESCRIPTION:
XS GIS Cut Line= 3
      3758318.50     10568139.29      3757976.48     10568026.44
      3757642.99     10567964.24
#Sta/Elev= 30
  4598.4  300.66  4612.3  300.91  4618.3  299.06  4628.8  299.14  4638.8  296.17
  4644.0  296.81  4660.4  294.18  4675.8  293.21  4692.0  290.16  4744.7  286.26
  4786.8  284.09  4865.2  282.64  4898.0  283.30  4958.6  281.74  4962.9  279.58
  4968.0  278.68  4975.7  279.82  4985.9  278.93  4996.1  274.84  5003.2  274.43
  5006.0  273.93  5009.2  274.43  5015.6  281.88  5043.6  282.64  5097.8  283.45
  5196.3  287.62  5209.7  287.92  5241.7  291.90  5269.4  293.02  5297.8  297.16
#Mann=7,-1,0
  4598.4    0.16       0  4865.2    0.12       0  5003.2    0.07       0
  5009.2    0.12       0  5043.6    0.16       0  5196.3    0.12       0
  5269.4    0.16       0
Bank Sta=5003.2,5009.2
Exp/Cntr=0.3,0.1

Type RM Length L Ch R = 1,6032,134,134,134
BEGIN DESCRIPTION:
UNT 080 IN BOCR 13.0
END DESCRIPTION:
XS GIS Cut Line= 3
      3758349.65     10568060.21      3757977.31     10567903.18
      3757799.58     10567810.17
#Sta/Elev= 30
  4595.9  304.64  4605.1  304.41  4610.5  302.56  4634.2  303.36  4639.7  301.37
  4687.1  296.31  4710.8  290.99  4740.0  288.58  4747.9  286.64  4802.2  283.07
  4856.4  281.61  4893.1  282.39  4899.8  280.90  4931.2  279.61  4954.1  276.87
  4969.7  278.87  4986.7  275.84  4990.5  272.96  4993.2  272.46  4996.5  272.96
  5000.0  273.44  5015.8  282.15  5037.9  282.34  5087.7  286.69  5110.3  290.23
  5134.6  296.27  5148.2  297.78  5155.4  300.39  5170.3  302.18  5200.6  308.65
#Mann=5,-1,0
  4595.9    0.16       0  4931.2    0.12       0  4990.5    0.07       0
  4996.5    0.12       0  5134.6    0.16       0
Bank Sta=4990.5,4996.5
Exp/Cntr=0.3,0.1

Type RM Length L Ch R = 1,5898,67,67,67
BEGIN DESCRIPTION:
Mapping XS baf05fd8
END DESCRIPTION:
XS GIS Cut Line= 3
      3758342.78     10567988.24      3758162.24     10567908.39
      3757903.24     10567784.07
#Sta/Elev= 30
  4740.1  296.99  4765.4  295.87  4777.1  294.44  4794.9  293.77  4800.4  292.56
  4823.7  290.92  4831.0  289.90  4847.0  289.51  4870.3  287.38  4885.7  286.96
  4907.6  284.65  4922.3  284.40  4929.5  283.37  4962.5  280.93  4984.8  278.37
  4990.7  273.88  4993.3  273.23  4996.0  272.73  4999.3  273.23  5007.0  276.97
  5013.4  277.94  5029.2  278.31  5041.6  280.64  5097.5  281.33  5154.8  282.48
  5162.3  283.77  5200.1  286.21  5217.2  289.66  5222.7  289.08  5224.8  290.48
#Mann=4,-1,0
  4740.1    0.16       0  4993.3    0.07       0  4999.3    0.16       0
  5097.5    0.12       0
Bank Sta=4993.3,4999.3
Exp/Cntr=0.3,0.1

Type RM Length L Ch R = 1,5831,128,128,128
BEGIN DESCRIPTION:
Mapping XS b4bd3cb4
END DESCRIPTION:
XS GIS Cut Line= 3
      3758440.42     10567996.03      3758255.50     10567878.83
      3757731.10     10567655.01
#Sta/Elev= 30
  4671.0  304.95  4690.5  302.06  4719.3  299.91  4726.9  298.11  4748.1  298.12
  4763.4  294.76  4778.5  295.03  4849.5  289.46  4907.2  287.10  4924.1  284.98
  4961.6  283.13  4971.3  281.98  4976.8  277.22  4983.3  276.67  4997.4  272.45
  5000.1  271.95  5003.4  272.45  5005.8  275.99  5015.9  279.17  5166.9  282.37
  5234.6  286.15  5298.6  294.24  5310.9  294.26  5354.6  298.25  5358.1  297.39
  5387.3  301.38  5410.7  303.05  5428.9  307.06  5458.0  310.00  5460.1  311.33
#Mann=6,-1,0
  4671.0    0.16       0  4997.4    0.07       0  5003.4    0.16       0
  5166.9    0.12       0  5354.6    0.16       0  5387.3    0.05       0
Bank Sta=4997.4,5003.4
Exp/Cntr=0.3,0.1

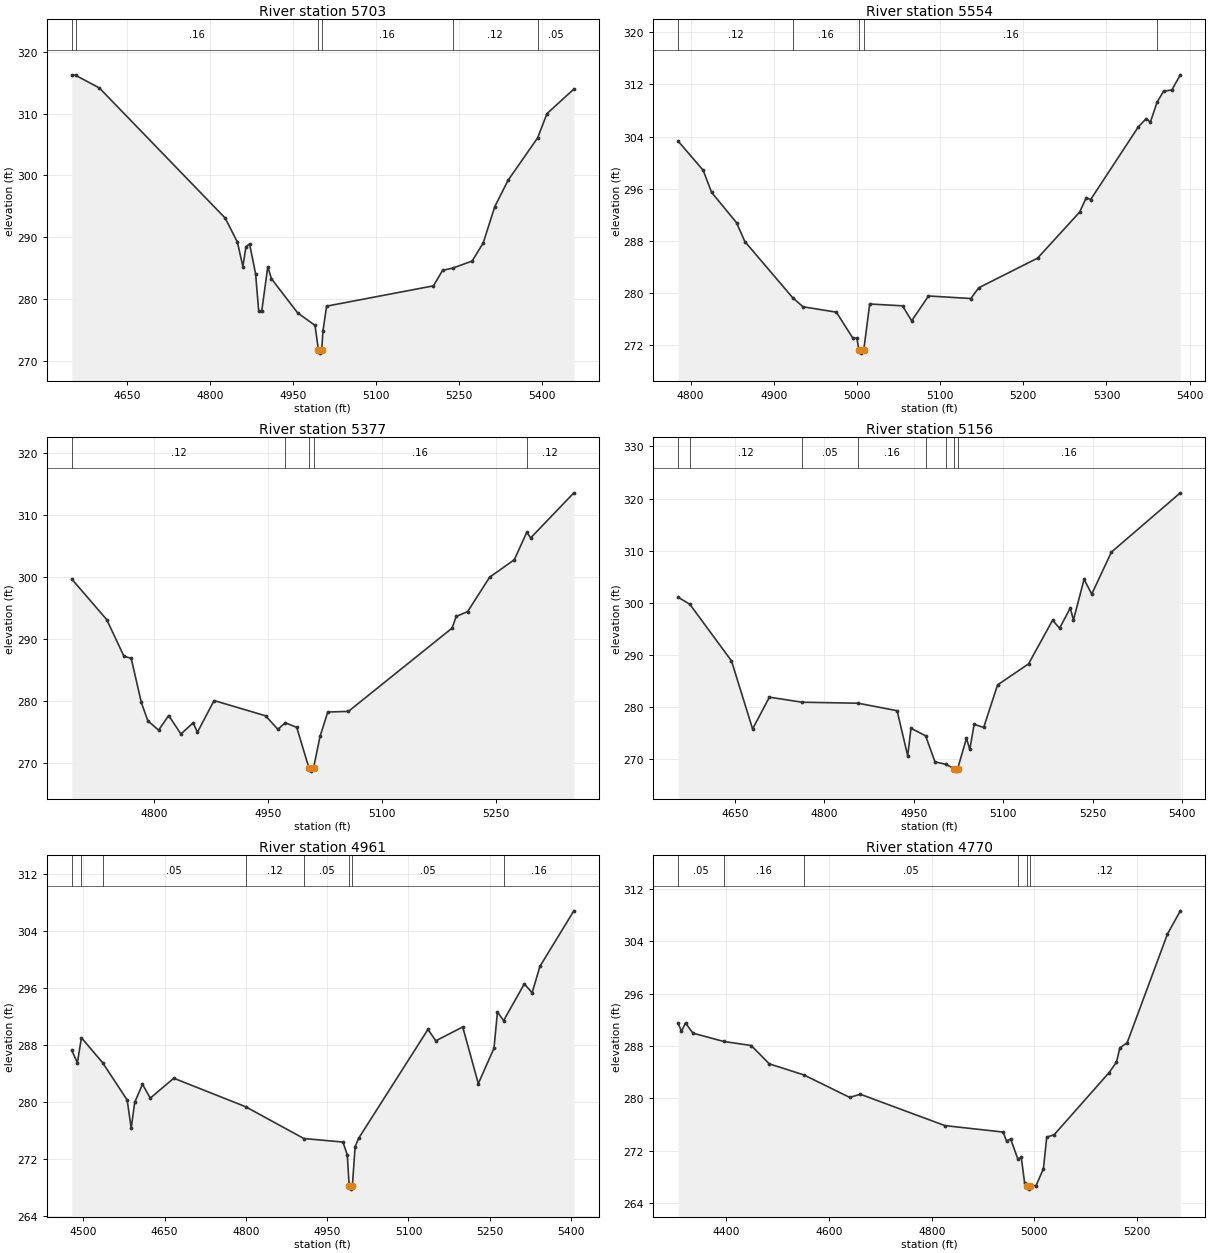
Type RM Length L Ch R = 1,5703,149,149,149
BEGIN DESCRIPTION:
Mapping XS 7593dd5b
END DESCRIPTION:
XS GIS Cut Line= 3
      3758612.23     10567904.85      3758259.41     10567744.72
      3757763.28     10567588.86
#Sta/Elev= 30
  4550.3  316.25  4557.7  316.15  4600.2  314.13  4827.7  293.10  4849.7  289.22
  4859.6  285.27  4865.1  288.48  4871.7  288.93  4882.6  284.09  4888.2  278.06
  4893.7  278.11  4904.6  285.25  4911.3  283.30  4958.5  277.80  4990.0  275.77
  4996.1  271.79  4998.8  271.29  5002.1  271.79  5004.3  274.85  5010.9  278.88
  5204.0  282.16  5220.6  284.67  5239.1  285.03  5274.0  286.17  5293.9  289.08
  5314.9  294.95  5338.8  299.20  5392.5  306.09  5409.2  309.98  5457.8  313.95
#Mann=6,-1,0
  4550.3    0.05       0  4557.7    0.16       0  4996.1    0.07       0
  5002.1    0.16       0  5239.1    0.12       0  5392.5    0.05       0
Bank Sta=4996.1,5002.1
Exp/Cntr=0.3,0.1

Type RM Length L Ch R = 1,5554,177,177,177
BEGIN DESCRIPTION:
UNT 080 IN BOCR 12.0
END DESCRIPTION:
XS GIS Cut Line= 3
      3758399.66     10567610.19      3758184.78     10567613.25
      3757799.61     10567560.19
#Sta/Elev= 30
  4785.1  303.29  4815.1  298.84  4825.2  295.46  4855.2  290.81  4865.2  287.92
  4922.9  279.29  4935.2  277.92  4975.2  277.10  4995.1  273.11  5000.0  273.11
  5002.2  271.32  5005.0  270.82  5008.2  271.32  5015.3  278.35  5054.8  278.07
  5065.8  275.77  5086.0  279.58  5136.9  279.19  5146.5  280.84  5217.2  285.38
  5267.7  292.43  5275.8  294.66  5280.9  294.34  5338.3  305.49  5347.8  306.76
  5352.8  306.21  5360.9  309.30  5368.6  310.93  5378.7  311.17  5388.8  313.47
#Mann=5,-1,0
  4785.1    0.12       0  4922.9    0.16       0  5002.2    0.07       0
  5008.2    0.16       0  5360.9    0.05       0
Bank Sta=5002.2,5008.2
Exp/Cntr=0.3,0.1

Type RM Length L Ch R = 1,5377,221,221,221
BEGIN DESCRIPTION:
Mapping XS f524b094
END DESCRIPTION:
XS GIS Cut Line= 3
      3758400.02     10567584.55      3758230.76     10567492.11
      3757772.88     10567392.23
#Sta/Elev= 30
  4691.3  299.66  4737.4  293.09  4760.1  287.17  4769.6  286.85  4782.9  279.72
  4791.5  276.75  4805.7  275.23  4819.0  277.60  4835.1  274.61  4851.2  276.41
  4856.9  274.90  4878.8  280.02  4946.7  277.55  4962.8  275.37  4972.6  276.43
  4987.7  275.68  5003.8  269.11  5006.5  268.61  5009.8  269.11  5018.4  274.22
  5028.6  278.16  5055.8  278.27  5192.4  291.73  5197.8  293.61  5212.9  294.40
  5241.8  299.95  5274.3  302.77  5290.9  307.24  5295.9  306.30  5352.8  313.59
#Mann=5,-1,0
  4691.3    0.12       0  4972.6    0.16       0  5003.8    0.07       0
  5009.8    0.16       0  5290.9    0.12       0
Bank Sta=5003.8,5009.8
Exp/Cntr=0.3,0.1

Type RM Length L Ch R = 1,5156,195,195,195
BEGIN DESCRIPTION:
Mapping XS 8c0d6f3a
END DESCRIPTION:
XS GIS Cut Line= 3
      3758433.57     10567582.33      3758212.21     10567339.27
      3757744.02     10567131.18
#Sta/Elev= 30
  4555.4  301.06  4574.8  299.73  4644.6  288.86  4680.0  275.80  4708.1  281.90
  4762.9  280.93  4856.7  280.74  4922.1  279.30  4939.8  270.65  4945.3  275.93
  4969.8  274.49  4985.5  269.50  5003.4  269.02  5017.5  268.21  5020.3  267.71
  5023.5  268.21  5038.3  274.01  5043.8  271.86  5051.1  276.69  5067.1  276.09
  5090.3  284.24  5142.3  288.29  5182.5  296.66  5194.3  295.13  5212.1  299.00
  5217.5  296.72  5235.3  304.52  5248.1  301.67  5281.0  309.72  5396.5  321.10
#Mann=8,-1,0
  4555.4    0.16       0  4574.8    0.12       0  4762.9    0.05       0
  4856.7    0.16       0  4969.8    0.12       0  5003.4    0.16       0
  5017.5    0.07       0  5023.5    0.16       0
Bank Sta=5017.5,5023.5
Exp/Cntr=0.3,0.1

Type RM Length L Ch R = 1,4961,191,191,191
BEGIN DESCRIPTION:
UNT 080 IN BOCR 11.0
END DESCRIPTION:
XS GIS Cut Line= 2
      3758433.56     10567530.23      3757856.31     10566805.41
#Sta/Elev= 30
  4478.6  287.28  4489.0  285.55  4496.4  289.07  4535.6  285.55  4580.9  280.31
  4588.3  276.33  4594.7  279.98  4609.1  282.53  4623.5  280.58  4666.8  283.38
  4799.3  279.38  4906.9  274.91  4979.1  274.41  4987.1  272.59  4990.5  268.30
  4993.2  267.80  4996.5  268.30  5001.5  273.74  5007.9  274.93  5136.0  290.24
  5150.4  288.63  5200.1  290.58  5228.9  282.62  5257.8  287.59  5264.2  292.67
  5275.6  291.47  5313.8  296.63  5328.2  295.38  5342.6  299.09  5405.2  306.89
#Mann=8,-1,0
  4478.6    0.16       0  4496.4    0.12       0  4535.6    0.05       0
  4799.3    0.12       0  4906.9    0.05       0  4990.5    0.04       0
  4996.5    0.05       0  5275.6    0.16       0
Bank Sta=4990.5,4996.5
Exp/Cntr=0.3,0.1

Type RM Length L Ch R = 1,4770,145,145,145
BEGIN DESCRIPTION:
UNT 080 IN BOCR 10.0
END DESCRIPTION:
XS GIS Cut Line= 2
      3758585.50     10567473.85      3757969.53     10566714.72
#Sta/Elev= 30
  4306.5  291.43  4312.8  290.23  4320.7  291.51  4335.1  289.95  4394.7  288.69
  4448.6  288.06  4483.8  285.26  4551.1  283.57  4640.4  280.13  4661.2  280.61
  4825.8  275.82  4939.3  274.83  4945.7  273.45  4953.6  273.78  4967.8  270.72
  4974.5  270.95  4980.9  267.07  4985.8  266.61  4988.6  266.11  4991.8  266.61
  5003.2  266.65  5017.6  269.24  5024.0  274.06  5038.4  274.42  5145.5  283.93
  5159.8  285.51  5166.3  287.69  5180.6  288.49  5259.0  305.09  5284.1  308.65
#Mann=6,-1,0
  4306.5    0.05       0  4394.7    0.16       0  4551.1    0.05       0
  4967.8    0.12       0  4985.8    0.07       0  4991.8    0.12       0
Bank Sta=4985.8,4991.8
Exp/Cntr=0.3,0.1

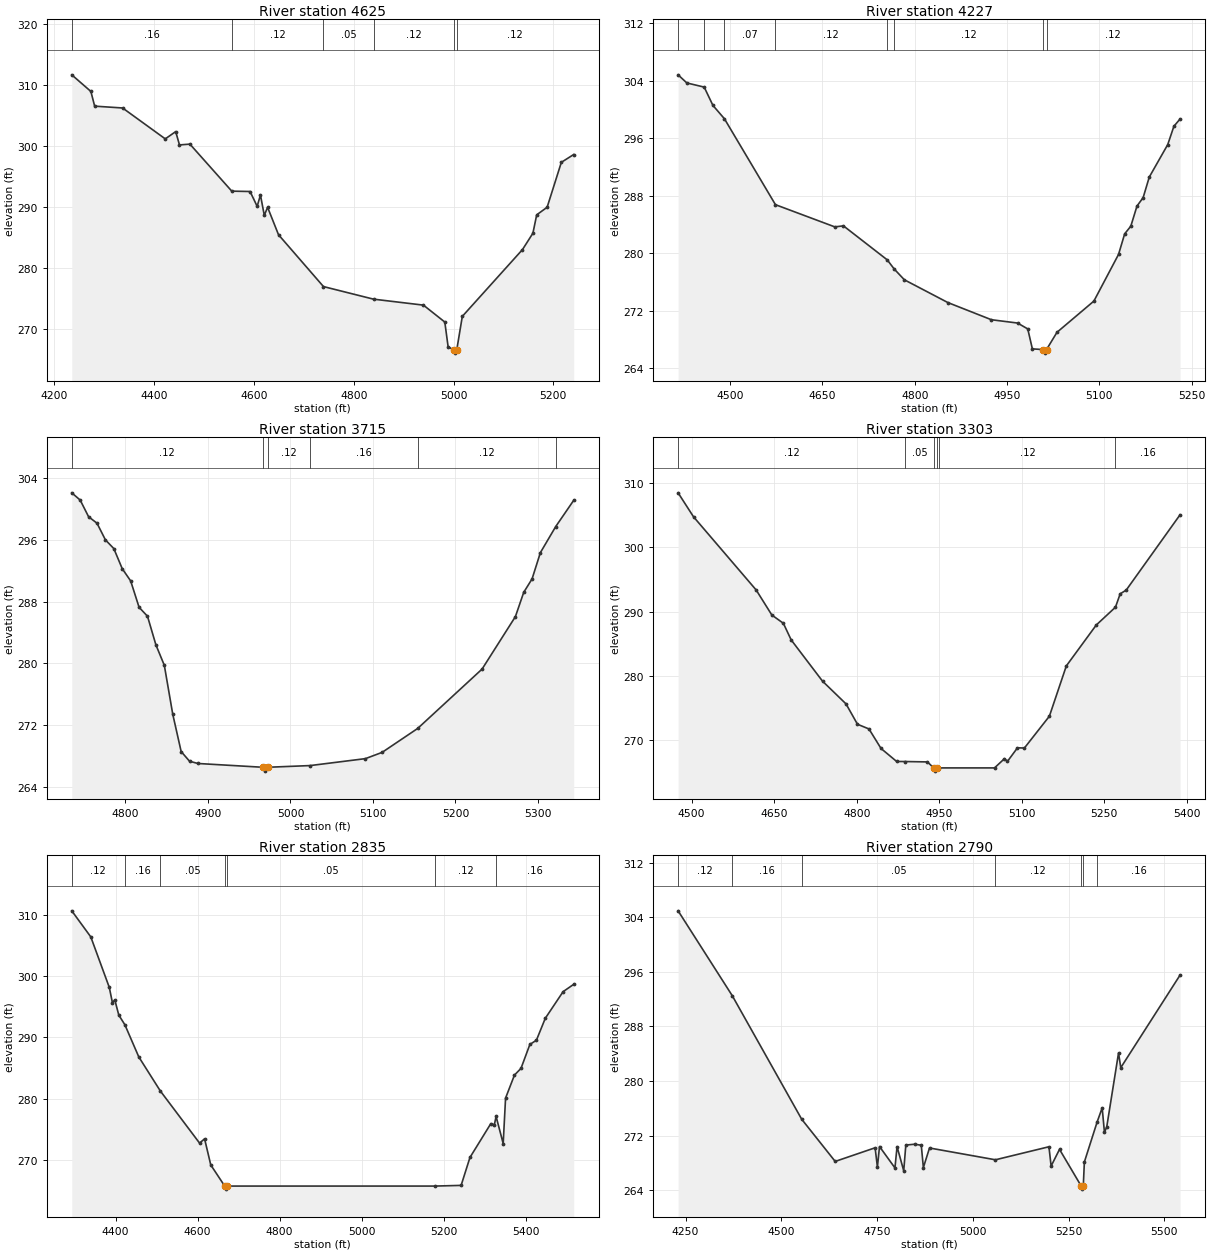
Type RM Length L Ch R = 1,4625,398,398,398
BEGIN DESCRIPTION:
Mapping XS 030f802c
END DESCRIPTION:
XS GIS Cut Line= 2
      3758785.15     10567308.90      3758025.57     10566649.15
#Sta/Elev= 30
  4234.8  311.66  4273.1  308.94  4280.7  306.53  4336.7  306.23  4422.2  301.17
  4443.1  302.36  4450.7  300.18  4471.6  300.31  4555.5  292.61  4592.2  292.55
  4606.4  290.12  4613.0  291.98  4620.7  288.64  4627.3  289.97  4649.2  285.47
  4739.3  276.98  4839.6  274.92  4939.7  273.94  4982.5  271.17  4989.1  267.15
  5000.4  266.58  5003.1  266.08  5006.4  266.58  5017.6  272.10  5138.2  283.04
  5159.1  285.72  5166.7  288.73  5187.6  289.97  5216.1  297.33  5240.9  298.61
#Mann=6,-1,0
  4234.8    0.16       0  4555.5    0.12       0  4739.3    0.05       0
  4839.6    0.12       0  5000.4    0.07       0  5006.4    0.12       0
Bank Sta=5000.4,5006.4
Exp/Cntr=0.3,0.1

Type RM Length L Ch R = 1,4227,512,512,512
BEGIN DESCRIPTION:
UNT 080 IN BOCR 9.0
END DESCRIPTION:
XS GIS Cut Line= 3
      3758799.63     10566860.21      3758399.61     10566460.19
      3758149.63     10566460.19
#Sta/Elev= 30
  4415.4  304.84  4429.6  303.71  4457.8  303.13  4472.0  300.58  4490.7  298.72
  4573.6  286.76  4670.0  283.67  4684.1  283.81  4755.2  279.08  4766.6  277.80
  4783.1  276.30  4853.8  273.13  4924.5  270.74  4967.0  270.28  4983.6  269.46
  4991.1  266.68  5008.1  266.59  5010.9  266.09  5014.1  266.59  5031.1  268.99
  5091.1  273.34  5131.1  279.83  5141.1  282.70  5151.1  283.77  5161.1  286.57
  5171.1  287.74  5181.1  290.61  5211.1  295.13  5221.1  297.68  5231.1  298.69
#Mann=8,-1,0
  4415.4    0.07       0  4457.8    0.12       0  4490.7    0.07       0
  4573.6    0.12       0  4755.2    0.16       0  4766.6    0.12       0
  5008.1    0.07       0  5014.1    0.12       0
Bank Sta=5008.1,5014.1
Exp/Cntr=0.3,0.1

Type RM Length L Ch R = 1,3715,412,412,412
BEGIN DESCRIPTION:
UNT 080 IN BOCR 8.0
END DESCRIPTION:
XS GIS Cut Line= 3
      3758749.64     10566010.18      3758499.61     10566060.19
      3758149.65     10566110.18
#Sta/Elev= 30
  4734.9  302.12  4745.1  301.18  4755.3  299.02  4765.5  298.18  4775.7  296.02
  4785.9  294.89  4796.1  292.28  4806.3  290.70  4816.5  287.28  4826.7  286.12
  4836.9  282.41  4847.1  279.76  4857.3  273.43  4867.5  268.58  4877.7  267.32
  4887.9  267.03  4966.5  266.54  4969.2  266.04  4972.5  266.54  5023.9  266.76
  5090.9  267.66  5111.1  268.47  5154.2  271.57  5232.3  279.27  5272.7  286.07
  5282.8  289.22  5292.9  290.96  5303.0  294.37  5321.6  297.75  5343.4  301.15
#Mann=6,-1,0
  4734.9    0.12       0  4966.5    0.07       0  4972.5    0.12       0
  5023.9    0.16       0  5154.2    0.12       0  5321.6    0.16       0
Bank Sta=4966.5,4972.5
Exp/Cntr=0.3,0.1

Type RM Length L Ch R = 1,3303,468,468,468
BEGIN DESCRIPTION:
UNT 080 IN BOCR 7.0
END DESCRIPTION:
XS GIS Cut Line= 3
      3758849.63     10566010.20      3758449.61     10565660.19
      3758099.63     10565810.18
#Sta/Elev= 30
  4475.4  308.44  4503.4  304.72  4617.3  293.35  4645.8  289.46  4666.7  288.18
  4680.9  285.60  4737.9  279.19  4780.6  275.66  4801.4  272.50  4822.3  271.77
  4844.2  268.74  4872.6  266.72  4888.6  266.71  4928.6  266.65  4939.9  265.72
  4942.6  265.22  4945.9  265.72  4950.2  265.72  5050.5  265.72  5068.6  267.16
  5074.0  266.73  5092.2  268.84  5104.8  268.81  5150.2  273.75  5181.0  281.56
  5235.4  287.91  5270.3  290.68  5278.9  292.76  5289.8  293.33  5387.7  305.03
#Mann=6,-1,0
  4475.4    0.12       0  4888.6    0.05       0  4939.9    0.07       0
  4945.9    0.05       0  4950.2    0.12       0  5270.3    0.16       0
Bank Sta=4939.9,4945.9
Exp/Cntr=0.3,0.1

Type RM Length L Ch R = 1,2835,45,45,45
BEGIN DESCRIPTION:
UNT 080 IN BOCR 6.0
END DESCRIPTION:
XS GIS Cut Line= 4
      3759006.05     10565668.90      3758745.63     10565228.81
      3758495.63     10565202.77      3758093.30     10565428.59
#Sta/Elev= 30
  4293.3  310.70  4339.7  306.44  4384.8  298.19  4392.4  295.70  4398.2  296.15
  4408.0  293.66  4422.9  292.07  4456.8  286.82  4509.2  281.27  4605.0  272.74
  4617.2  273.44  4632.3  269.17  4666.3  265.72  4669.1  265.22  4672.3  265.72
  5179.2  265.72  5242.8  265.83  5264.4  270.40  5315.2  275.92  5323.8  275.74
  5328.1  277.09  5345.4  272.67  5351.2  280.10  5372.9  283.86  5388.8  284.95
  5410.5  288.87  5426.4  289.55  5448.1  293.14  5491.5  297.49  5517.4  298.69
#Mann=7,-1,0
  4293.3    0.12       0  4422.9    0.16       0  4509.2    0.05       0
  4666.3   0.033       0  4672.3    0.05       0  5179.2    0.12       0
  5328.1    0.16       0
Bank Sta=4666.3,4672.3
Exp/Cntr=0.3,0.1

Type RM Length L Ch R = 1,2790,68,68,68
BEGIN DESCRIPTION:
Mapping XS e99596f5
END DESCRIPTION:
XS GIS Cut Line= 6
      3759065.96     10565645.49      3758818.55     10565231.41
      3758672.72     10565163.70      3758451.36     10565163.70
      3758310.74     10565239.23      3758065.95     10565387.66
#Sta/Elev= 30
  4230.6  304.94  4372.0  292.50  4553.2  274.40  4640.7  268.21  4744.9  270.21
  4750.9  267.39  4756.4  270.39  4796.7  267.26  4802.2  270.38  4819.6  266.84
  4825.1  270.61  4848.0  270.73  4865.4  270.59  4870.9  267.31  4886.9  270.18
  5059.0  268.45  5198.7  270.36  5204.4  267.53  5226.3  269.98  5282.4  264.65
  5285.1  264.15  5288.4  264.65  5291.2  268.13  5324.8  274.04  5337.7  276.06
  5343.6  272.48  5349.6  273.27  5380.4  284.11  5386.2  281.95  5541.0  295.52
#Mann=7,-1,0
  4230.6    0.12       0  4372.0    0.16       0  4553.2    0.05       0
  5059.0    0.12       0  5282.4   0.033       0  5288.4    0.12       0
  5324.8    0.16       0
Bank Sta=5282.4,5288.4
Exp/Cntr=0.3,0.1

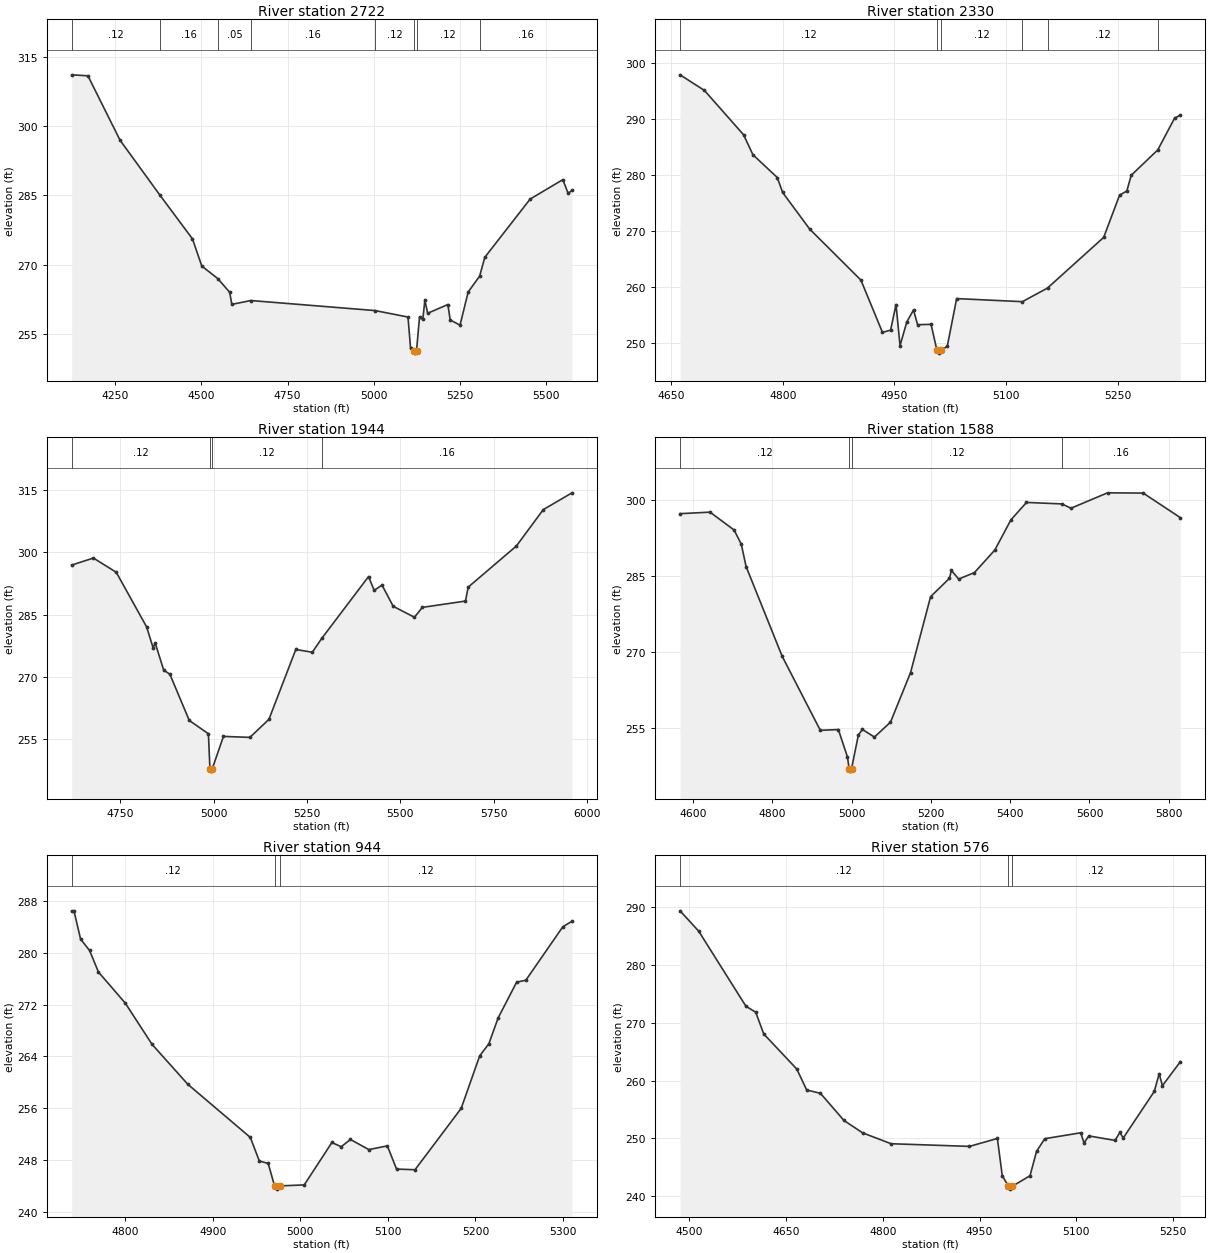
Type RM Length L Ch R = 1,2722,392,392,392
BEGIN DESCRIPTION:
Mapping XS d356a3e7
END DESCRIPTION:
XS GIS Cut Line= 4
      3759141.48     10565593.41      3758823.76     10565119.43
      3758409.70     10565096.00      3758012.93     10565339.76
#Sta/Elev= 30
  4124.0  311.10  4171.1  310.89  4264.2  296.96  4380.0  285.06  4474.3  275.60
  4501.3  269.73  4548.0  266.99  4582.3  264.04  4588.4  261.43  4643.8  262.26
  5003.7  260.09  5099.4  258.69  5106.9  251.89  5118.1  251.38  5120.9  250.88
  5124.1  251.38  5132.9  258.75  5142.4  258.16  5148.3  262.38  5156.4  259.50
  5215.1  261.40  5221.7  258.06  5250.3  256.93  5273.8  264.09  5307.1  267.54
  5322.2  271.62  5453.7  284.22  5548.4  288.42  5563.8  285.45  5575.0  286.09
#Mann=8,-1,0
  4124.0    0.12       0  4380.0    0.16       0  4548.0    0.05       0
  4643.8    0.16       0  5003.7    0.12       0  5118.1    0.07       0
  5124.1    0.12       0  5307.1    0.16       0
Bank Sta=5118.1,5124.1
Exp/Cntr=0.3,0.1

Type RM Length L Ch R = 1,2330,386,386,386
BEGIN DESCRIPTION:
UNT 080 IN BOCR 5.0
END DESCRIPTION:
XS GIS Cut Line= 3
      3758499.62     10564460.16      3758349.61     10564810.19
      3758099.58     10564960.21
#Sta/Elev= 30
  4662.1  297.86  4694.8  295.08  4747.4  287.18  4760.0  283.62  4792.7  279.56
  4799.9  276.90  4836.2  270.38  4905.1  261.28  4934.1  251.95  4945.0  252.36
  4952.3  256.91  4957.7  249.60  4966.8  253.82  4975.8  255.94  4981.3  253.33
  4999.4  253.39  5007.3  248.76  5010.0  248.26  5013.3  248.76  5021.2  249.50
  5033.8  257.98  5122.2  257.43  5155.9  259.86  5231.4  268.89  5252.8  276.43
  5262.5  277.15  5268.4  279.96  5304.1  284.48  5326.7  290.14  5334.5  290.68
#Mann=6,-1,0
  4662.1    0.12       0  5007.3    0.07       0  5013.3    0.12       0
  5122.2    0.16       0  5155.9    0.12       0  5304.1    0.16       0
Bank Sta=5007.3,5013.3
Exp/Cntr=0.3,0.1

Type RM Length L Ch R = 1,1944,356,356,356
BEGIN DESCRIPTION:
Mapping XS f0d9fd7e
END DESCRIPTION:
XS GIS Cut Line= 3
      3758547.72     10564340.78      3758146.68     10564528.29
      3757403.23     10565029.98
#Sta/Elev= 30
  4619.9  296.96  4678.0  298.65  4739.2  295.23  4820.6  282.06  4837.9  277.04
  4843.5  278.18  4866.3  271.66  4882.8  270.67  4934.8  259.53  4986.0  256.33
  4990.1  247.83  4992.9  247.33  4996.1  247.83  5026.2  255.69  5097.1  255.46
  5148.0  259.80  5220.0  276.63  5264.2  275.96  5289.7  279.33  5414.8  294.19
  5429.8  290.86  5450.8  292.15  5480.7  287.04  5537.7  284.38  5558.7  286.77
  5674.3  288.29  5681.6  291.65  5810.5  301.54  5882.4  310.30  5959.5  314.36
#Mann=4,-1,0
  4619.9    0.12       0  4990.1    0.07       0  4996.1    0.12       0
  5289.7    0.16       0
Bank Sta=4990.1,4996.1
Exp/Cntr=0.3,0.1

Type RM Length L Ch R = 1,1588,644,644,644
BEGIN DESCRIPTION:
Mapping XS 0325a96f
END DESCRIPTION:
XS GIS Cut Line= 2
      3758584.20     10564239.23      3757336.80     10564046.52
#Sta/Elev= 30
  4567.2  297.22  4642.7  297.52  4703.4  294.01  4721.6  291.22  4733.7  286.82
  4824.8  269.15  4921.0  254.59  4966.5  254.75  4989.2  249.42  4993.8  247.07
  4996.6  246.57  4999.8  247.07  5017.1  253.73  5027.2  254.77  5057.5  253.27
  5098.0  256.20  5148.6  265.95  5199.2  280.89  5246.7  284.50  5251.7  286.06
  5270.0  284.35  5309.8  285.63  5361.1  290.05  5401.6  295.98  5441.1  299.43
  5530.5  299.14  5553.4  298.29  5645.6  301.32  5735.5  301.27  5829.4  296.43
#Mann=4,-1,0
  4567.2    0.12       0  4993.8    0.07       0  4999.8    0.12       0
  5530.5    0.16       0
Bank Sta=4993.8,4999.8
Exp/Cntr=0.3,0.1

Type RM Length L Ch R = 1,944,368,368,368
BEGIN DESCRIPTION:
UNT 080 IN BOCR 2.0
END DESCRIPTION:
XS GIS Cut Line= 3
      3758549.61     10564010.21      3758499.61     10563760.19
      3758199.61     10563660.19
#Sta/Elev= 30
  4739.0  286.51  4741.6  286.51  4749.2  282.13  4759.4  280.38  4769.6  277.04
  4800.2  272.24  4830.8  265.86  4871.6  259.69  4943.0  251.47  4953.2  247.83
  4963.4  247.45  4970.6  243.98  4973.3  243.48  4976.6  243.98  5004.5  244.13
  5036.1  250.69  5046.7  250.03  5057.2  251.16  5078.3  249.59  5099.4  250.17
  5109.9  246.58  5131.0  246.48  5183.7  255.97  5204.8  264.08  5215.3  265.96
  5225.9  269.96  5247.0  275.48  5257.5  275.78  5299.7  284.04  5310.2  284.90
#Mann=3,-1,0
  4739.0    0.12       0  4970.6    0.07       0  4976.6    0.12       0
Bank Sta=4970.6,4976.6
Exp/Cntr=0.3,0.1

Type RM Length L Ch R = 1,576,0,0,0
BEGIN DESCRIPTION:
UNT 080 IN BOCR 1.0
END DESCRIPTION:
XS GIS Cut Line= 3
      3758799.60     10564010.18      3758549.61     10563610.19
      3758249.63     10563560.19
#Sta/Elev= 30
  4485.7  289.31  4514.6  285.79  4587.7  272.85  4603.0  271.79  4615.4  268.05
  4666.7  261.98  4682.0  258.37  4703.3  257.80  4739.8  253.11  4768.7  250.97
  4812.9  249.09  4934.4  248.63  4977.7  250.00  4985.3  243.56  4994.9  241.75
  4997.7  241.25  5000.9  241.75  5028.3  243.56  5038.5  247.79  5051.2  249.96
  5106.9  250.98  5112.0  249.24  5119.6  250.44  5160.1  249.66  5167.7  251.05
  5172.8  250.07  5221.0  258.12  5228.6  261.19  5233.6  259.11  5261.5  263.27
#Mann=3,-1,0
  4485.7    0.12       0  4994.9    0.07       0  5000.9    0.12       0
Bank Sta=4994.9,5000.9
Exp/Cntr=0.3,0.1

Chan Stop Cuts=-1