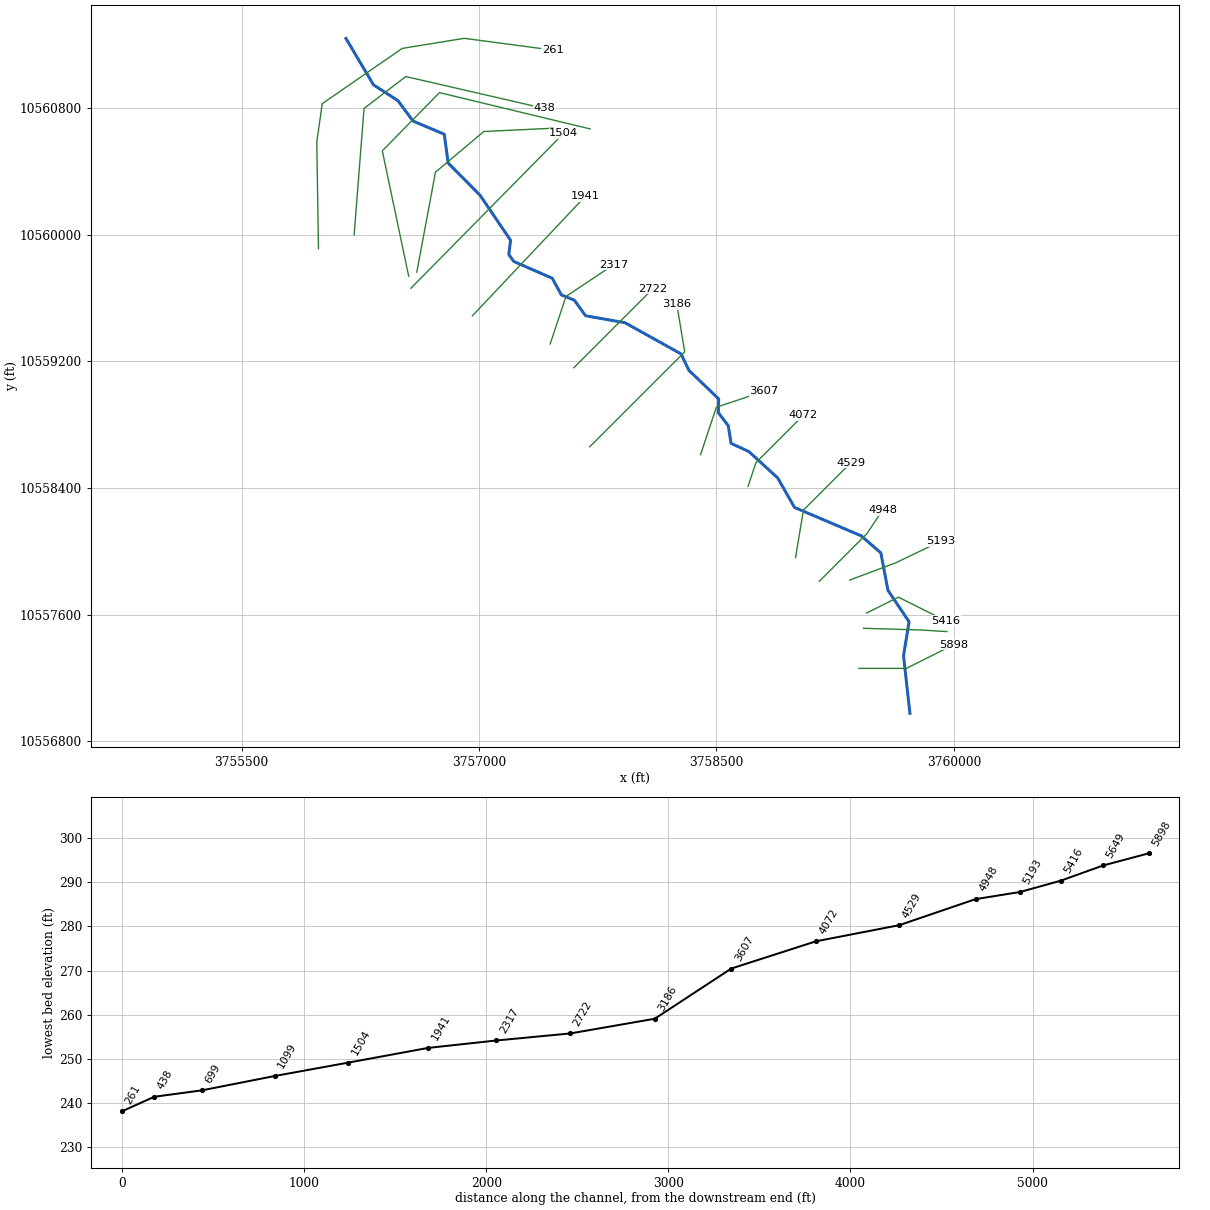
--- UNT 081 IN BOCR.prj (project) ---

Proj Title=UNT 081 IN BOCR Base Level Engineering
Current Plan=p01
Default Exp/Contr=0.3,0.1
English Units
Geom File=g01
Flow File=f01
Plan File=p01
BEGIN DESCRIPTION:
UNT 081 IN BOCR
END DESCRIPTION:

--- UNT 081 IN BOCR.p01 (plan) ---

Plan Title=Multiple Run
Short Identifier=Multiple
Geom File=g01
Flow File=f01
Subcritical Flow
K Sum by GR= 0
Std Step Tol= 0.01
Critical Tol= 0.01
Num of Std Step Trials= 20
Max Error Tol= 0.3
Flow Tol Ratio= 0.001
Split Flow NTrial= 30
Split Flow Tol= 0.02
Split Flow Ratio= 0.02
Log Output Level= 0
Friction Slope Method= 1
Unsteady Friction Slope Method= 2
Unsteady Bridges Friction Slope Method= 1
Parabolic Critical Depth
Global Vel Dist=  1 , 1 , 1
Global Log Level= 0
CheckData=True
Encroach Param= -1, 0, 0, 0
BEGIN DESCRIPTION:
Multiple Run
END DESCRIPTION:

--- UNT 081 IN BOCR.f01 (steady flow) ---

Flow Title=Multiple
Number of Profiles=7
Profile Names=10-year,25-year,50-year,1pct_min,100-year,1pct_plu,500-year
River Rch & RM= UNT 081 IN BOCR,Reach-1,5898
     732    1018    1261    1150    1555    2102    2371
Boundary for River Rch & Prof#=UNT 081 IN BOCR,Reach-1,1
Up Type=0
Dn Type=3
Dn Slope=0.005
Boundary for River Rch & Prof#=UNT 081 IN BOCR,Reach-1,2
Up Type=0
Dn Type=3
Dn Slope=0.005
Boundary for River Rch & Prof#=UNT 081 IN BOCR,Reach-1,3
Up Type=0
Dn Type=3
Dn Slope=0.005
Boundary for River Rch & Prof#=UNT 081 IN BOCR,Reach-1,4
Up Type=0
Dn Type=3
Dn Slope=0.005
Boundary for River Rch & Prof#=UNT 081 IN BOCR,Reach-1,5
Up Type=0
Dn Type=3
Dn Slope=0.005
Boundary for River Rch & Prof#=UNT 081 IN BOCR,Reach-1,6
Up Type=0
Dn Type=3
Dn Slope=0.005
Boundary for River Rch & Prof#=UNT 081 IN BOCR,Reach-1,7
Up Type=0
Dn Type=3
Dn Slope=0.005

--- UNT 081 IN BOCR.g01 (geometry) ---

Geom Title=Existing Conditions

River Reach=UNT 081 IN BOCR,Reach-1
Reach XY= 30
      3759722.50     10556976.00      3759682.00     10557340.00
      3759717.00     10557555.00      3759583.75     10557753.00
      3759538.75     10557990.00      3759414.00     10558098.00
      3758993.25     10558277.00      3758886.75     10558464.00
      3758704.75     10558630.00      3758592.34     10558682.14
      3758575.00     10558793.00      3758512.00     10558876.00
      3758514.00     10558963.00      3758326.25     10559143.00
      3758276.50     10559247.00      3757922.25     10559444.00
      3757673.25     10559488.00      3757602.75     10559586.00
      3757520.25     10559620.00      3757462.75     10559725.00
      3757220.00     10559831.00      3757188.25     10559875.00
      3757199.50     10559965.00      3757007.00     10560249.00
      3756805.25     10560453.00      3756780.50     10560635.00
      3756583.25     10560718.00      3756487.75     10560847.00
      3756333.25     10560947.00      3756159.50     10561240.00

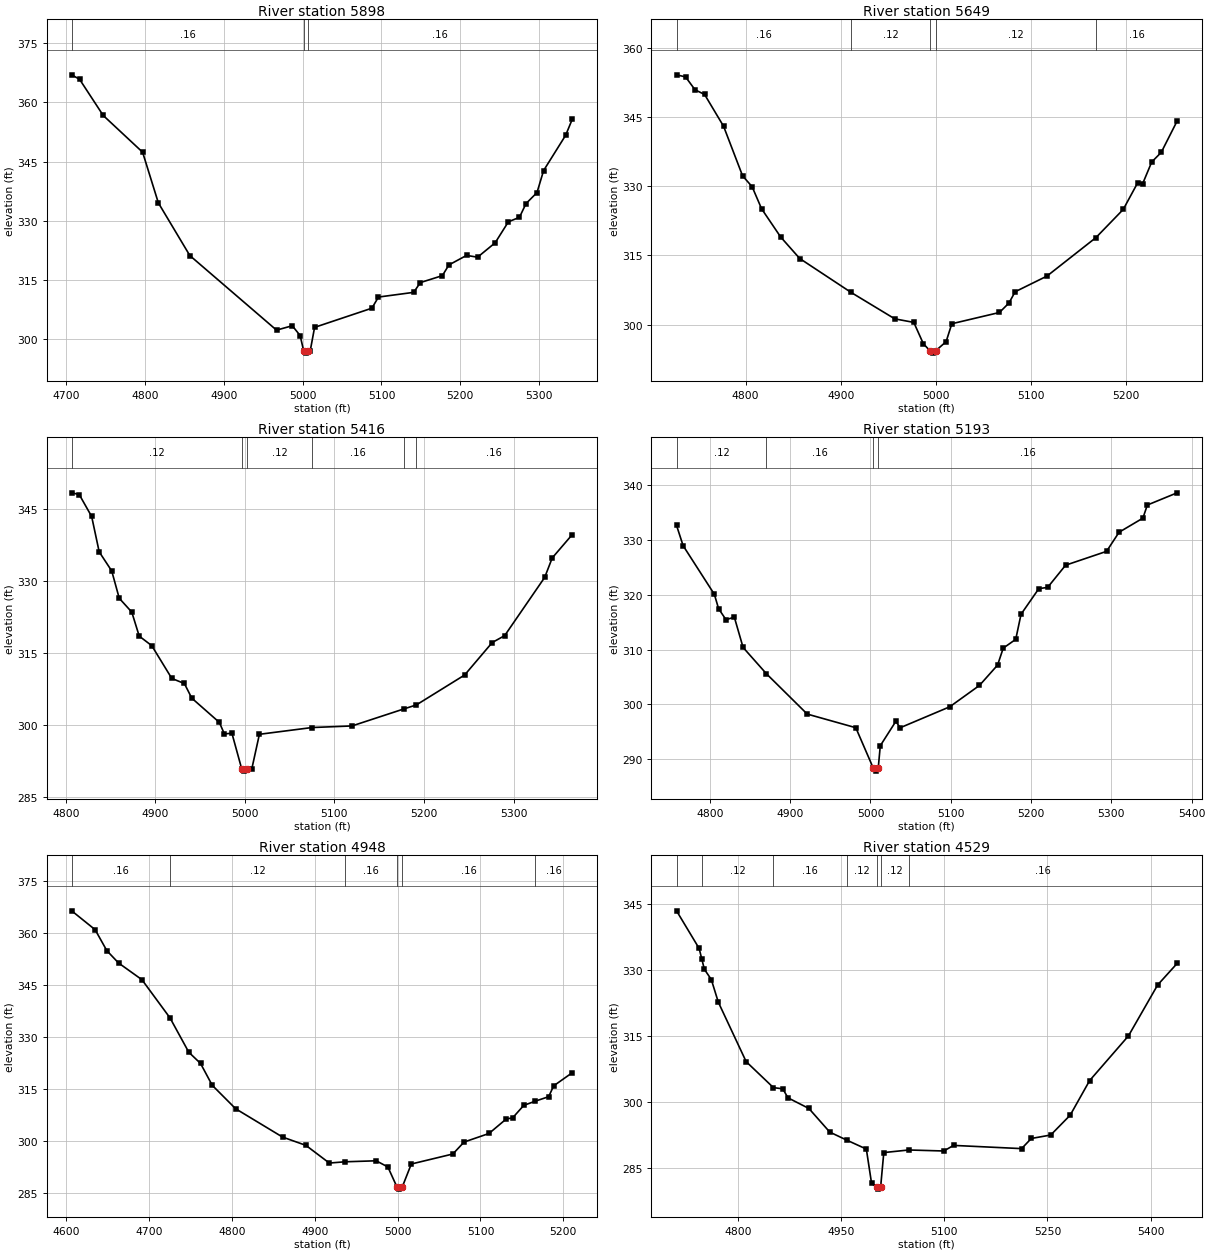
Type RM Length L Ch R = 1,5898,249,249,249
BEGIN DESCRIPTION:
UNT 081 IN BOCR 10.0
END DESCRIPTION:
XS GIS Cut Line= 3
      3759399.66     10557260.19      3759699.61     10557260.19
      3759999.64     10557410.21
#Sta/Elev= 30
  4706.8  366.96  4716.8  365.83  4746.8  356.68  4796.8  347.38  4816.8  334.55
  4856.8  321.21  4966.8  302.35  4986.8  303.46  4996.8  300.97  5001.3  297.03
  5004.0  296.53  5007.3  297.03  5009.5  297.03  5015.1  303.05  5087.8  307.90
  5096.2  310.72  5140.9  311.91  5149.3  314.38  5177.3  316.14  5185.6  318.85
  5208.0  321.26  5222.0  320.81  5244.3  324.45  5261.1  329.77  5275.1  330.89
  5283.5  334.38  5297.4  337.16  5305.8  342.74  5333.8  351.67  5342.2  355.73
#Mann=3,-1,0
  4706.8    0.16       0  5001.3    0.07       0  5007.3    0.16       0
Bank Sta=5001.3,5007.3
Exp/Cntr=0.3,0.1

Type RM Length L Ch R = 1,5649,233,233,233
BEGIN DESCRIPTION:
Mapping XS c7f792da
END DESCRIPTION:
XS GIS Cut Line= 3
      3759430.10     10557513.42      3759787.72     10557503.00
      3759956.23     10557492.68
#Sta/Elev= 30
  4727.3  354.12  4736.8  353.67  4746.8  350.87  4756.8  349.87  4776.8  342.97
  4796.8  332.22  4806.8  329.88  4816.8  325.08  4836.9  318.96  4856.9  314.31
  4911.0  306.95  4956.9  301.23  4976.9  300.46  4986.9  295.86  4993.9  294.30
  4996.7  293.80  4999.9  294.30  5010.9  296.29  5016.9  300.17  5067.0  302.61
  5077.0  304.66  5083.5  307.10  5117.0  310.50  5168.5  318.84  5197.2  324.94
  5212.5  330.75  5217.6  330.49  5227.2  335.23  5237.2  337.31  5253.9  344.10
#Mann=5,-1,0
  4727.3    0.16       0  4911.0    0.12       0  4993.9    0.07       0
  4999.9    0.12       0  5168.5    0.16       0
Bank Sta=4993.9,4999.9
Exp/Cntr=0.3,0.1

Type RM Length L Ch R = 1,5416,223,223,223
BEGIN DESCRIPTION:
UNT 081 IN BOCR 9.0
END DESCRIPTION:
XS GIS Cut Line= 3
      3759449.63     10557610.20      3759649.61     10557710.19
      3759949.61     10557560.19
#Sta/Elev= 30
  4806.6  348.31  4815.0  347.96  4828.9  343.38  4837.3  336.02  4851.3  332.04
  4859.7  326.35  4873.7  323.47  4882.0  318.47  4896.0  316.48  4918.4  309.65
  4932.4  308.60  4940.7  305.55  4971.5  300.50  4977.1  298.09  4985.5  298.25
  4996.4  290.85  4999.2  290.35  5002.4  290.85  5007.8  290.88  5016.2  298.02
  5075.0  299.43  5119.6  299.76  5177.8  303.32  5191.5  304.14  5245.4  310.37
  5276.2  317.13  5290.1  318.57  5334.8  330.70  5343.2  334.75  5365.6  339.62
#Mann=6,-1,0
  4806.6    0.12       0  4996.4    0.07       0  5002.4    0.12       0
  5075.0    0.16       0  5177.8    0.12       0  5191.5    0.16       0
Bank Sta=4996.4,5002.4
Exp/Cntr=0.3,0.1

Type RM Length L Ch R = 1,5193,245,245,245
BEGIN DESCRIPTION:
Mapping XS 02661d4b
END DESCRIPTION:
XS GIS Cut Line= 3
      3759341.98     10557818.10      3759633.64     10557927.48
      3759914.76     10558062.83
#Sta/Elev= 30
  4758.4  332.68  4766.6  328.97  4805.5  320.09  4810.8  317.46  4820.0  315.45
  4830.4  315.91  4841.3  310.38  4870.4  305.57  4921.2  298.21  4981.7  295.72
  5003.6  288.29  5006.4  287.79  5009.6  288.29  5012.2  292.43  5031.6  296.89
  5036.9  295.71  5098.7  299.54  5135.7  303.44  5158.3  307.16  5165.3  310.25
  5180.9  311.86  5187.5  316.44  5209.7  321.13  5220.6  321.34  5243.0  325.40
  5294.0  327.93  5309.6  331.42  5339.3  334.00  5344.8  336.39  5381.9  338.62
#Mann=4,-1,0
  4758.4    0.12       0  4870.4    0.16       0  5003.6    0.07       0
  5009.6    0.16       0
Bank Sta=5003.6,5009.6
Exp/Cntr=0.3,0.1

Type RM Length L Ch R = 1,4948,419,419,419
BEGIN DESCRIPTION:
UNT 081 IN BOCR 8.0
END DESCRIPTION:
XS GIS Cut Line= 3
      3759149.61     10557810.19      3759449.61     10558110.19
      3759549.59     10558260.16
#Sta/Elev= 30
  4606.4  366.40  4634.7  360.96  4648.8  354.93  4663.0  351.36  4691.2  346.55
  4725.1  335.54  4747.8  325.64  4762.0  322.40  4776.1  316.11  4804.4  309.34
  4861.0  301.18  4889.2  298.79  4917.5  293.69  4936.6  294.05  4974.1  294.34
  4988.2  292.56  4999.4  286.67  5002.1  286.17  5005.4  286.67  5016.5  293.41
  5066.7  296.30  5080.2  299.74  5110.3  302.21  5131.3  306.42  5138.8  306.70
  5152.3  310.31  5166.1  311.52  5182.4  312.82  5188.4  315.94  5210.9  319.74
#Mann=6,-1,0
  4606.4    0.16       0  4725.1    0.12       0  4936.6    0.16       0
  4999.4    0.07       0  5005.4    0.16       0  5166.1    0.16       0
Bank Sta=4999.4,5005.4
Exp/Cntr=0.3,0.1

Type RM Length L Ch R = 1,4529,457,457,457
BEGIN DESCRIPTION:
UNT 081 IN BOCR 7.0
END DESCRIPTION:
XS GIS Cut Line= 3
      3758999.62     10557960.23      3759049.61     10558260.19
      3759349.64     10558560.22
#Sta/Elev= 30
  4710.3  343.47  4743.2  334.93  4747.2  332.44  4750.8  330.20  4760.9  327.87
  4771.1  322.73  4811.6  309.23  4851.3  303.32  4864.9  303.05  4872.5  301.00
  4902.9  298.59  4933.3  293.22  4957.7  291.42  4986.5  289.37  4994.1  281.59
  5001.3  280.77  5004.0  280.27  5007.3  280.77  5011.9  288.57  5048.3  289.16
  5099.2  288.93  5113.4  290.20  5212.4  289.47  5226.5  291.77  5254.8  292.56
  5283.1  297.06  5311.4  304.92  5367.9  315.07  5410.4  326.64  5438.7  331.52
#Mann=7,-1,0
  4710.3    0.16       0  4747.2    0.12       0  4851.3    0.16       0
  4957.7    0.12       0  5001.3    0.07       0  5007.3    0.12       0
  5048.3    0.16       0
Bank Sta=5001.3,5007.3
Exp/Cntr=0.3,0.1

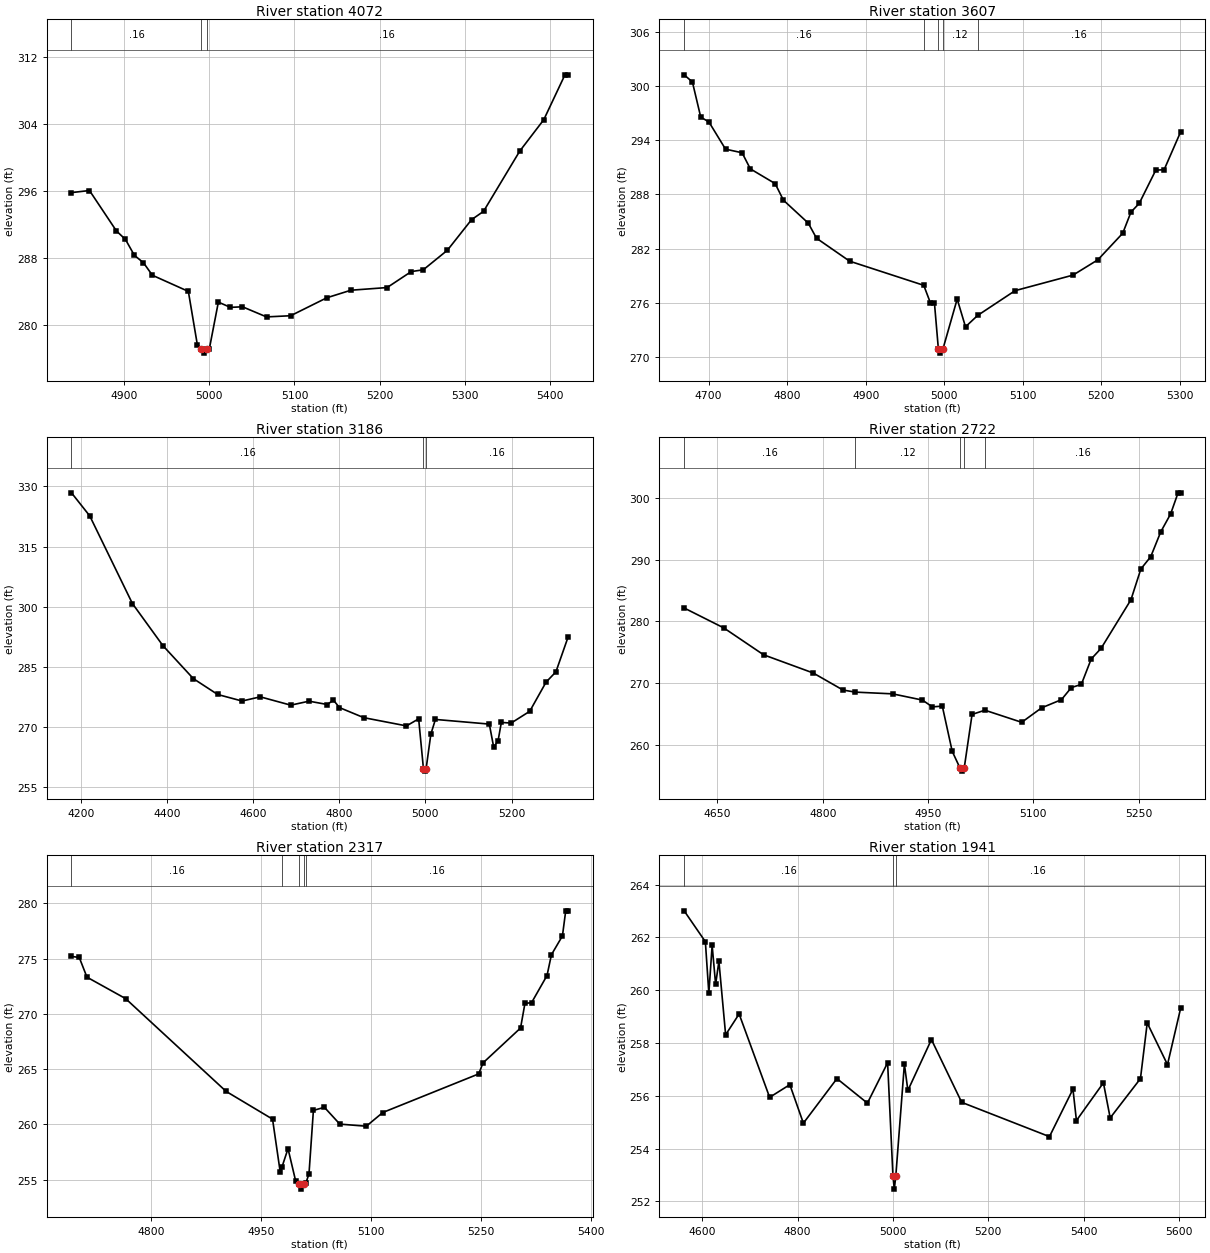
Type RM Length L Ch R = 1,4072,465,465,465
BEGIN DESCRIPTION:
UNT 081 IN BOCR 6.0
END DESCRIPTION:
XS GIS Cut Line= 3
      3758699.60     10558410.16      3758749.61     10558560.19
      3759049.61     10558860.19
#Sta/Elev= 30
  4838.4  295.81  4859.5  296.06  4891.1  291.23  4901.7  290.21  4912.2  288.31
  4922.8  287.43  4933.3  285.93  4975.5  284.00  4986.0  277.65  4990.9  277.12
  4993.7  276.62  4996.9  277.12  5000.1  277.12  5010.7  282.72  5024.8  282.09
  5039.0  282.16  5067.2  280.95  5095.5  281.09  5138.0  283.24  5166.2  284.14
  5208.7  284.46  5237.0  286.37  5251.1  286.58  5279.4  288.92  5307.7  292.57
  5321.8  293.57  5364.2  300.76  5392.5  304.53  5417.3  309.89  5420.8  309.89
#Mann=3,-1,0
  4838.4    0.16       0  4990.9    0.07       0  4996.9    0.16       0
Bank Sta=4990.9,4996.9
Exp/Cntr=0.3,0.1

Type RM Length L Ch R = 1,3607,421,421,421
BEGIN DESCRIPTION:
UNT 081 IN BOCR 5.0
END DESCRIPTION:
XS GIS Cut Line= 3
      3758399.61     10558610.20      3758499.61     10558910.19
      3758799.57     10559010.18
#Sta/Elev= 30
  4668.8  301.23  4679.3  300.44  4689.9  296.56  4700.4  296.01  4721.5  293.01
  4742.6  292.61  4753.1  290.83  4784.7  289.20  4795.3  287.36  4826.9  284.83
  4837.4  283.16  4879.6  280.62  4974.0  277.95  4982.4  276.03  4987.6  276.03
  4992.6  270.95  4995.3  270.45  4998.6  270.95  5016.6  276.43  5027.2  273.36
  5042.7  274.62  5090.4  277.36  5164.2  279.08  5195.8  280.77  5227.5  283.71
  5238.0  286.05  5248.5  287.01  5269.6  290.69  5280.2  290.73  5301.2  294.91
#Mann=5,-1,0
  4668.8    0.16       0  4974.0    0.12       0  4992.6    0.07       0
  4998.6    0.12       0  5042.7    0.16       0
Bank Sta=4992.6,4998.6
Exp/Cntr=0.3,0.1

Type RM Length L Ch R = 1,3186,464,464,464
BEGIN DESCRIPTION:
UNT 081 IN BOCR 4.0
END DESCRIPTION:
XS GIS Cut Line= 3
      3757699.59     10558660.17      3758299.61     10559260.19
      3758249.61     10559560.20
#Sta/Elev= 30
  4178.3  328.42  4220.7  322.67  4319.7  300.84  4390.5  290.35  4461.2  282.12
  4517.7  278.17  4574.3  276.54  4616.7  277.58  4687.4  275.51  4729.9  276.50
  4772.3  275.67  4786.4  276.77  4800.6  274.90  4857.1  272.39  4956.1  270.34
  4984.4  272.10  4995.6  259.57  4998.3  259.07  5001.6  259.57  5012.7  268.28
  5023.3  271.95  5148.5  270.79  5158.6  265.05  5168.8  266.64  5176.4  271.20
  5199.2  271.05  5242.3  273.98  5280.3  281.25  5303.1  283.81  5331.0  292.37
#Mann=3,-1,0
  4178.3    0.16       0  4995.6    0.07       0  5001.6    0.16       0
Bank Sta=4995.6,5001.6
Exp/Cntr=0.3,0.1

Type RM Length L Ch R = 1,2722,405,405,405
BEGIN DESCRIPTION:
UNT 081 IN BOCR 3.0
END DESCRIPTION:
XS GIS Cut Line= 3
      3757599.63     10559160.21      3757899.61     10559460.19
      3758099.63     10559660.21
#Sta/Elev= 30
  4602.6  282.17  4659.1  278.94  4715.7  274.59  4786.4  271.64  4828.8  268.88
  4846.4  268.54  4899.5  268.26  4942.0  267.25  4956.1  266.15  4970.3  266.27
  4984.4  258.95  4995.5  256.24  4998.3  255.74  5001.5  256.24  5012.7  264.93
  5031.0  265.61  5083.4  263.65  5111.7  265.99  5140.0  267.32  5154.1  269.28
  5168.3  269.79  5182.4  273.91  5196.5  275.64  5239.0  283.51  5253.1  288.49
  5267.2  290.49  5281.4  294.50  5295.5  297.41  5306.1  300.83  5309.7  300.83
#Mann=5,-1,0
  4602.6    0.16       0  4846.4    0.12       0  4995.5    0.07       0
  5001.5    0.12       0  5031.0    0.16       0
Bank Sta=4995.5,5001.5
Exp/Cntr=0.3,0.1

Type RM Length L Ch R = 1,2317,376,376,376
BEGIN DESCRIPTION:
UNT 081 IN BOCR 2.0
END DESCRIPTION:
XS GIS Cut Line= 3
      3757449.60     10559310.17      3757549.61     10559610.19
      3757849.61     10559810.19
#Sta/Elev= 30
  4691.2  275.20  4701.8  275.10  4712.3  273.32  4765.0  271.38  4902.0  262.99
  4965.3  260.48  4975.8  255.68  4978.3  256.18  4986.4  257.81  4996.9  254.86
  5001.8  254.65  5004.6  254.15  5007.8  254.65  5010.7  254.69  5015.0  255.54
  5021.0  261.27  5036.0  261.55  5057.0  260.03  5093.1  259.84  5115.6  261.08
  5246.3  264.57  5252.3  265.57  5303.4  268.72  5309.4  270.95  5318.4  271.01
  5339.5  273.47  5345.5  275.35  5360.5  277.05  5365.0  279.32  5368.0  279.32
#Mann=5,-1,0
  4691.2    0.16       0  4978.3    0.12       0  5001.8    0.07       0
  5007.8    0.12       0  5010.7    0.16       0
Bank Sta=5001.8,5007.8
Exp/Cntr=0.3,0.1

Type RM Length L Ch R = 1,1941,437,437,437
BEGIN DESCRIPTION:
Mapping XS 64f60cd2
END DESCRIPTION:
XS GIS Cut Line= 2
      3756958.51     10559488.04      3757673.77     10560244.96
#Sta/Elev= 30
  4562.0  263.01  4606.5  261.84  4613.8  259.88  4620.7  261.70  4628.0  260.22
  4634.9  261.10  4649.0  258.31  4677.3  259.10  4741.3  255.94  4783.7  256.42
  4812.1  254.96  4882.5  256.65  4946.4  255.72  4988.8  257.25  5000.0  252.96
  5002.8  252.46  5006.0  252.96  5024.0  257.20  5031.3  256.20  5080.7  258.13
  5144.2  255.75  5328.3  254.45  5377.6  256.25  5384.9  255.06  5441.5  256.49
  5455.7  255.16  5519.2  256.65  5533.4  258.76  5575.9  257.18  5603.4  259.31
#Mann=3,-1,0
  4562.0    0.16       0  5000.0    0.07       0  5006.0    0.16       0
Bank Sta=5000,5006
Exp/Cntr=0.3,0.1

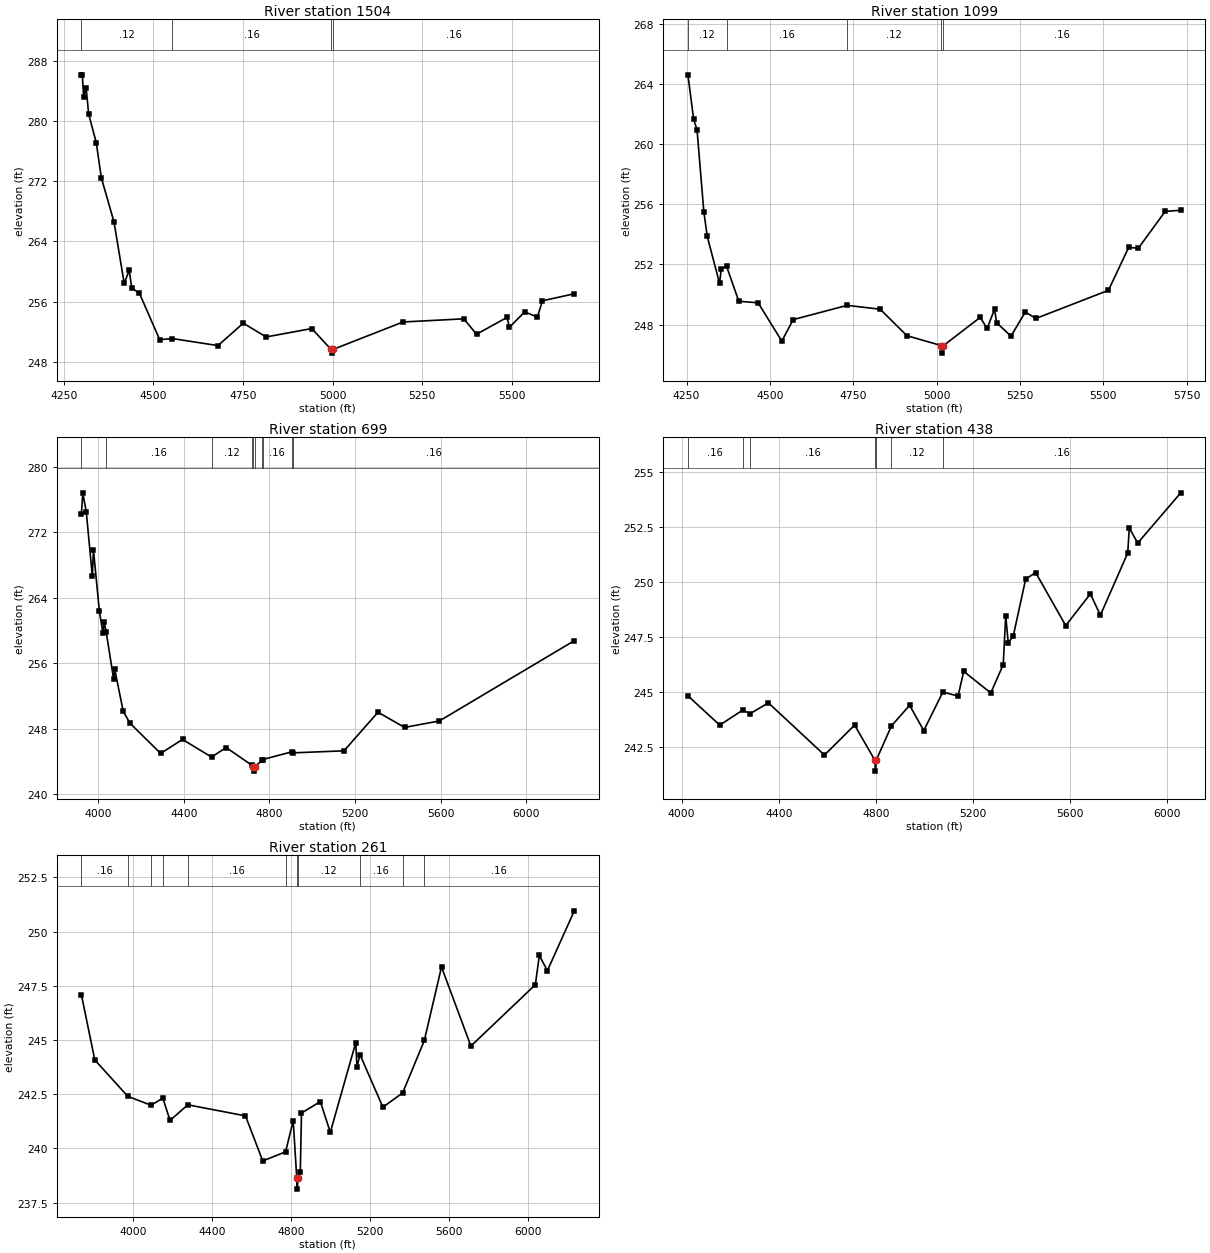
Type RM Length L Ch R = 1,1504,405,405,405
BEGIN DESCRIPTION:
Mapping XS 92e49671
END DESCRIPTION:
XS GIS Cut Line= 2
      3756569.59     10559661.62      3757534.75     10560640.67
#Sta/Elev= 30
  4299.5  286.14  4302.0  286.14  4305.6  283.23  4312.6  284.36  4319.7  280.91
  4340.9  277.11  4355.0  272.46  4390.4  266.57  4418.7  258.43  4432.9  260.14
  4439.9  257.79  4461.2  257.11  4517.7  250.93  4552.8  251.08  4680.3  250.14
  4751.0  253.12  4814.7  251.29  4942.0  252.41  4995.6  249.64  4998.3  249.14
  5001.6  249.64  5196.5  253.28  5366.2  253.70  5401.6  251.65  5486.5  253.89
  5493.5  252.58  5535.9  254.62  5571.3  253.94  5585.5  256.10  5674.3  257.03
#Mann=4,-1,0
  4299.5    0.12       0  4552.8    0.16       0  4995.6    0.07       0
  5001.6    0.16       0
Bank Sta=4995.6,5001.6
Exp/Cntr=0.3,0.1

Type RM Length L Ch R = 1,1099,400,400,400
BEGIN DESCRIPTION:
Mapping XS a4cafc7c
END DESCRIPTION:
XS GIS Cut Line= 4
      3756606.92     10559763.22      3756724.97     10560395.14
      3757030.52     10560652.09      3757466.34     10560672.84
#Sta/Elev= 30
  4253.9  264.62  4271.2  261.65  4281.3  260.96  4301.7  255.51  4311.9  253.87
  4348.9  250.74  4353.9  251.71  4369.9  251.88  4406.6  249.55  4464.5  249.45
  4535.7  246.90  4569.7  248.33  4731.9  249.28  4830.7  249.02  4910.9  247.26
  5014.5  246.60  5017.3  246.10  5020.5  246.60  5130.7  248.48  5151.5  247.74
  5173.6  249.02  5180.1  248.12  5223.0  247.23  5265.9  248.83  5298.0  248.41
  5515.3  250.28  5575.9  253.13  5605.4  253.09  5685.5  255.53  5732.3  255.61
#Mann=5,-1,0
  4253.9    0.12       0  4369.9    0.16       0  4731.9    0.12       0
  5014.5    0.07       0  5020.5    0.16       0
Bank Sta=5014.5,5020.5
Exp/Cntr=0.3,0.1

Type RM Length L Ch R = 1,699,261,261,261
BEGIN DESCRIPTION:
UNT 081 IN BOCR 1.0
END DESCRIPTION:
XS GIS Cut Line= 4
      3756555.69     10559738.06      3756389.04     10560529.68
      3756750.15     10560897.73      3757701.54     10560668.56
#Sta/Elev= 30
  3921.4  274.28  3927.7  276.84  3944.0  274.53  3972.4  266.65  3977.5  269.87
  4005.3  262.38  4022.2  259.68  4027.3  261.10  4037.3  259.82  4072.0  254.06
  4077.1  255.27  4116.7  250.15  4148.4  248.70  4291.5  245.01  4393.7  246.72
  4529.3  244.57  4598.0  245.73  4717.6  243.57  4725.1  243.35  4727.8  242.85
  4731.1  243.35  4767.0  244.23  4767.7  244.26  4903.6  245.20  4909.6  245.08
  5148.4  245.33  5307.2  250.04  5431.7  248.19  5594.2  248.98  6224.6  258.78
#Mann=10,-1,0
  3921.4    0.12       0  4037.3    0.16       0  4529.3    0.12       0
  4717.6    0.16       0  4725.1    0.07       0  4731.1    0.16       0
  4767.0    0.12       0  4767.7    0.16       0  4903.6    0.12       0
  4909.6    0.16       0
Bank Sta=4725.1,4731.1
Exp/Cntr=0.3,0.1

Type RM Length L Ch R = 1,438,177,177,177
BEGIN DESCRIPTION:
Mapping XS 2212a58f
END DESCRIPTION:
XS GIS Cut Line= 4
      3756211.08     10559999.34      3756273.58     10560797.92
      3756537.47     10560999.31      3757412.52     10560797.91
#Sta/Elev= 30
  4025.8  244.82  4157.0  243.49  4251.6  244.17  4282.1  244.01  4357.7  244.50
  4588.5  242.13  4712.8  243.49  4796.0  241.90  4798.8  241.40  4802.0  241.90
  4864.2  243.45  4939.5  244.39  4997.6  243.24  5076.3  244.99  5139.0  244.81
  5162.4  245.93  5273.8  244.95  5325.2  246.24  5335.4  248.46  5345.7  247.24
  5366.2  247.52  5417.5  250.12  5458.6  250.42  5582.6  248.01  5684.3  249.45
  5725.4  248.48  5838.2  251.31  5844.6  252.44  5879.3  251.76  6056.7  254.04
#Mann=7,-1,0
  4025.8    0.16       0  4251.6    0.12       0  4282.1    0.16       0
  4796.0    0.07       0  4802.0    0.16       0  4864.2    0.12       0
  5076.3    0.16       0
Bank Sta=4796,4802
Exp/Cntr=0.3,0.1

Type RM Length L Ch R = 1,261,0,0,0
BEGIN DESCRIPTION:
Mapping XS 97829f13
END DESCRIPTION:
XS GIS Cut Line= 6
      3755985.74     10559912.15      3755975.15     10560587.00
      3756009.56     10560827.85      3756515.07     10561177.20
      3756906.77     10561240.72      3757464.95     10561166.65
#Sta/Elev= 30
  3740.0  247.08  3807.6  244.08  3974.5  242.40  4092.2  241.99  4151.5  242.32
  4188.1  241.29  4277.9  242.01  4569.7  241.50  4656.9  239.42  4772.4  239.84
  4811.0  241.28  4829.0  238.62  4831.7  238.12  4835.0  238.62  4846.9  238.89
  4852.9  241.63  4948.3  242.16  4998.6  240.74  5127.4  244.88  5133.4  243.74
  5148.5  244.33  5264.6  241.90  5364.5  242.56  5474.2  244.98  5561.0  248.37
  5709.6  244.72  6035.5  247.55  6055.7  248.90  6096.4  248.20  6232.6  250.96
#Mann=11,-1,0
  3740.0    0.16       0  3974.5    0.12       0  4092.2    0.16       0
  4151.5    0.12       0  4277.9    0.16       0  4772.4    0.12       0
  4829.0    0.07       0  4835.0    0.12       0  5148.5    0.16       0
  5364.5    0.12       0  5474.2    0.16       0
Bank Sta=4829,4835
Exp/Cntr=0.3,0.1

Chan Stop Cuts=-1