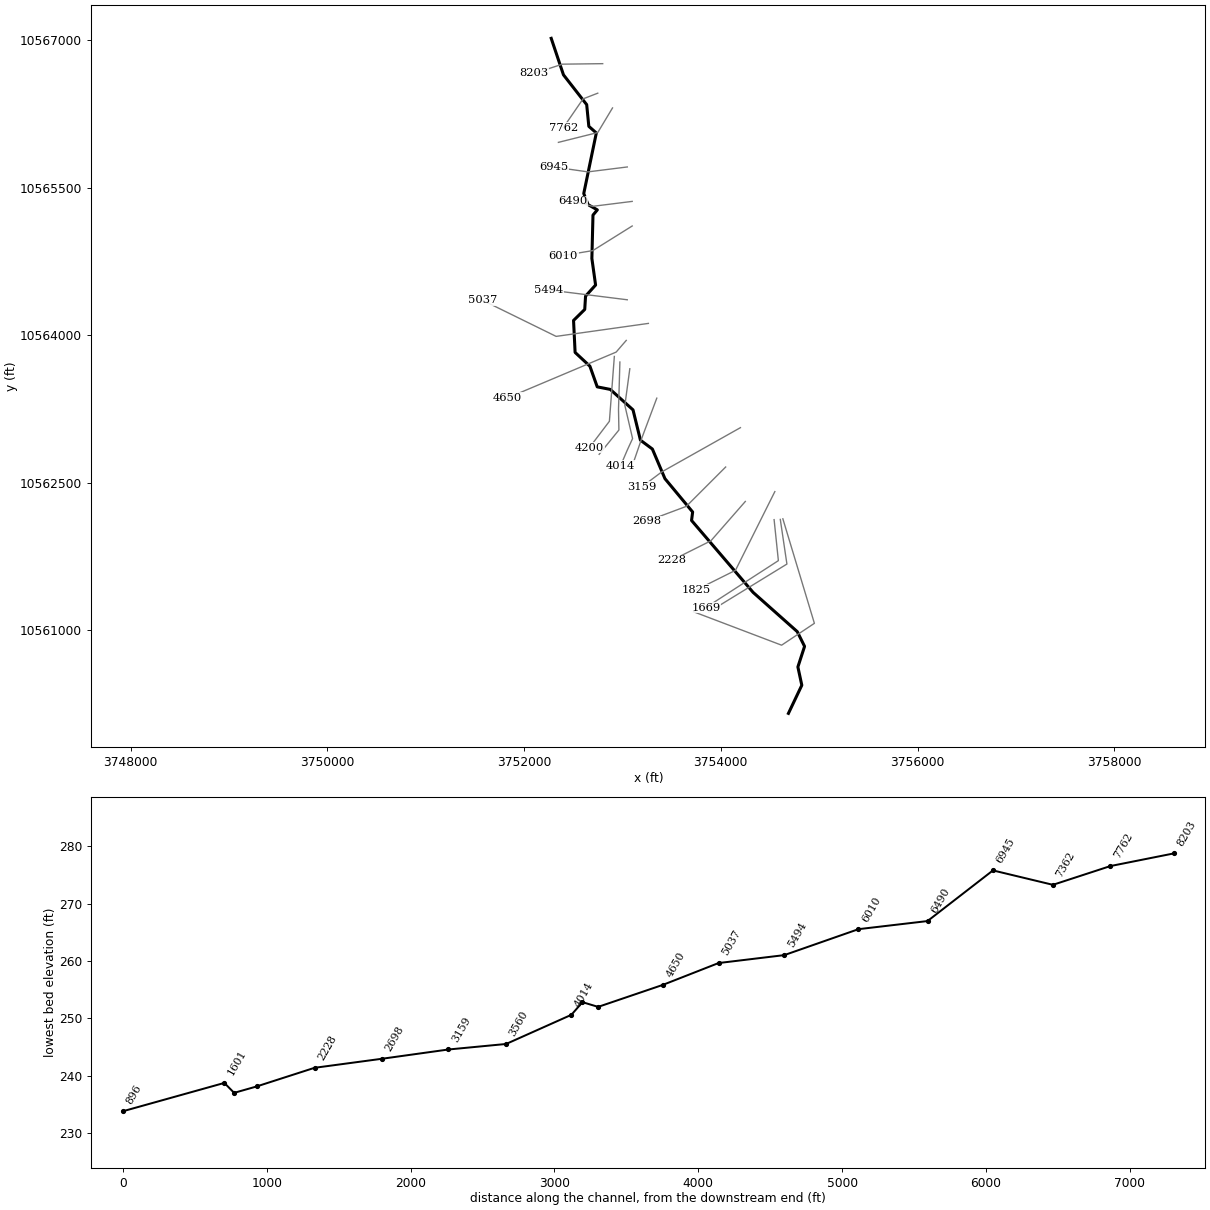
--- UNT 082 IN BOCR.prj (project) ---

Proj Title=UNT 082 IN BOCR Base Level Engineering
Current Plan=p01
Default Exp/Contr=0.3,0.1
English Units
Geom File=g01
Flow File=f01
Plan File=p01
BEGIN DESCRIPTION:
UNT 082 IN BOCR
END DESCRIPTION:

--- UNT 082 IN BOCR.p01 (plan) ---

Plan Title=Multiple Run
Short Identifier=Multiple
Geom File=g01
Flow File=f01
Subcritical Flow
K Sum by GR= 0
Std Step Tol= 0.01
Critical Tol= 0.01
Num of Std Step Trials= 20
Max Error Tol= 0.3
Flow Tol Ratio= 0.001
Split Flow NTrial= 30
Split Flow Tol= 0.02
Split Flow Ratio= 0.02
Log Output Level= 0
Friction Slope Method= 1
Unsteady Friction Slope Method= 2
Unsteady Bridges Friction Slope Method= 1
Parabolic Critical Depth
Global Vel Dist=  1 , 1 , 1
Global Log Level= 0
CheckData=True
Encroach Param= -1, 0, 0, 0
BEGIN DESCRIPTION:
Multiple Run
END DESCRIPTION:

--- UNT 082 IN BOCR.f01 (steady flow) ---

Flow Title=Multiple
Number of Profiles=7
Profile Names=10-year,25-year,50-year,1pct_min,100-year,1pct_plu,500-year
River Rch & RM= UNT 082 IN BOCR,Reach-1,8203
     723     997    1229    1114    1506    2037    2269
River Rch & RM= UNT 082 IN BOCR,Reach-1,5037
    1085    1526    1905    1745    2360    3191    3637
Boundary for River Rch & Prof#=UNT 082 IN BOCR,Reach-1,1
Up Type=0
Dn Type=3
Dn Slope=0.005
Boundary for River Rch & Prof#=UNT 082 IN BOCR,Reach-1,2
Up Type=0
Dn Type=3
Dn Slope=0.005
Boundary for River Rch & Prof#=UNT 082 IN BOCR,Reach-1,3
Up Type=0
Dn Type=3
Dn Slope=0.005
Boundary for River Rch & Prof#=UNT 082 IN BOCR,Reach-1,4
Up Type=0
Dn Type=3
Dn Slope=0.005
Boundary for River Rch & Prof#=UNT 082 IN BOCR,Reach-1,5
Up Type=0
Dn Type=3
Dn Slope=0.005
Boundary for River Rch & Prof#=UNT 082 IN BOCR,Reach-1,6
Up Type=0
Dn Type=3
Dn Slope=0.005
Boundary for River Rch & Prof#=UNT 082 IN BOCR,Reach-1,7
Up Type=0
Dn Type=3
Dn Slope=0.005

--- UNT 082 IN BOCR.g01 (geometry) ---

Geom Title=Existing Conditions

River Reach=UNT 082 IN BOCR,Reach-1
Reach XY= 30
      3752276.44     10567017.63      3752401.08     10566646.42
      3752637.11     10566343.59      3752658.75     10566123.00
      3752735.00     10566056.00      3752607.25     10565440.00
      3752651.50     10565327.00      3752745.25     10565274.00
      3752701.00     10565221.00      3752689.75     10564780.00
      3752727.50     10564510.00      3752625.50     10564397.00
      3752617.25     10564262.00      3752503.50     10564150.00
      3752519.25     10563825.00      3752669.75     10563685.00
      3752744.25     10563475.00      3752877.00     10563449.00
      3753108.00     10563241.00      3753183.50     10562933.00
      3753304.75     10562843.00      3753432.50     10562542.00
      3753714.00     10562203.00      3753703.00     10562117.00
      3754328.50     10561386.00      3754777.25     10560987.00
      3754851.75     10560837.00      3754783.75     10560628.00
      3754823.75     10560442.00      3754687.75     10560156.00

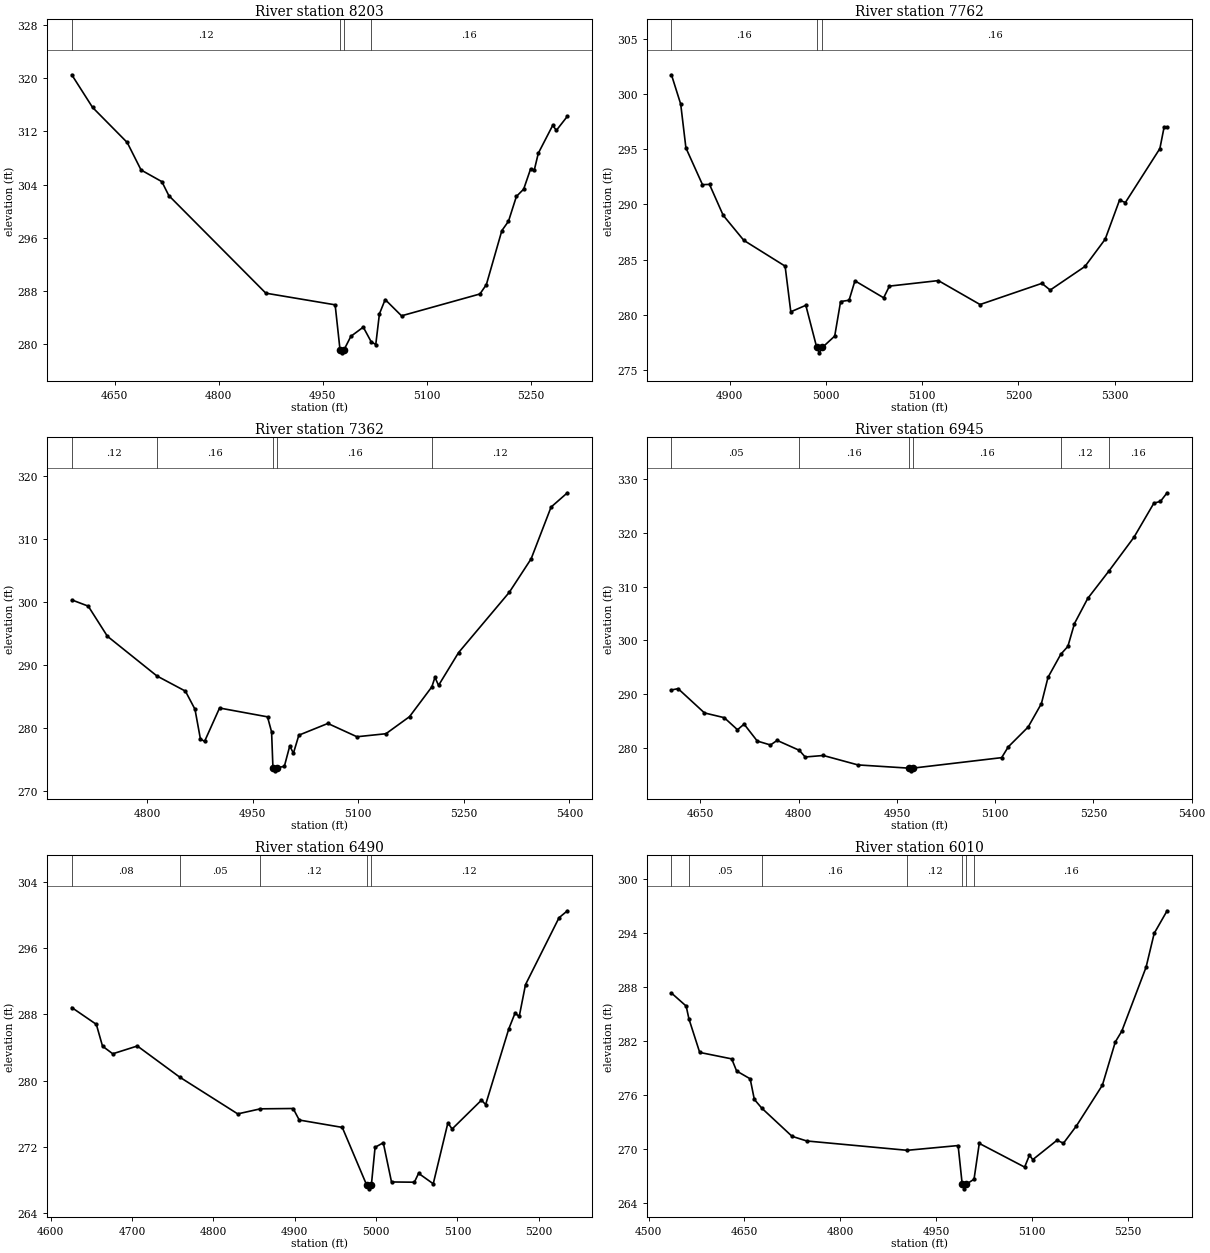
Type RM Length L Ch R = 1,8203,441,441,441
BEGIN DESCRIPTION:
UNT 082 IN BOCR 16.0
END DESCRIPTION:
XS GIS Cut Line= 3
      3752799.63     10566760.19      3752390.71     10566755.08
      3752099.64     10566660.20
#Sta/Elev= 30
  4587.9  320.50  4617.9  315.60  4667.9  310.33  4687.9  306.20  4717.9  304.45
  4727.9  302.36  4867.9  287.70  4967.9  285.95  4974.9  279.24  4977.7  278.74
  4980.9  279.24  4990.6  281.22  5008.5  282.60  5019.8  280.42  5026.5  279.98
  5031.8  284.60  5040.1  286.74  5063.7  284.30  5176.8  287.58  5186.1  288.99
  5208.4  297.09  5218.0  298.50  5229.4  302.23  5239.9  303.32  5249.9  306.36
  5255.2  306.18  5261.0  308.71  5281.8  312.90  5287.1  312.15  5303.0  314.27
#Mann=4,-1,0
  4587.9    0.12       0  4974.9    0.07       0  4980.9    0.12       0
  5019.8    0.16       0
Bank Sta=4974.9,4980.9
Exp/Cntr=0.3,0.1

Type RM Length L Ch R = 1,7762,400,400,400
BEGIN DESCRIPTION:
UNT 082 IN BOCR 15.0
END DESCRIPTION:
XS GIS Cut Line= 3
      3752749.65     10566460.20      3752600.21     10566402.19
      3752399.59     10566110.16
#Sta/Elev= 30
  4839.7  301.75  4849.3  299.09  4854.7  295.12  4871.9  291.79  4879.2  291.81
  4893.4  289.01  4914.8  286.74  4957.7  284.40  4963.6  280.26  4979.2  280.85
  4990.5  277.04  4993.2  276.54  4996.5  277.04  5009.2  278.06  5015.3  281.19
  5024.1  281.31  5030.2  283.07  5060.0  281.53  5066.0  282.59  5116.8  283.09
  5160.1  280.92  5224.3  282.84  5232.9  282.23  5269.0  284.37  5290.0  286.84
  5304.9  290.38  5311.0  290.17  5346.8  295.06  5351.2  297.01  5354.3  297.01
#Mann=3,-1,0
  4839.7    0.16       0  4990.5    0.07       0  4996.5    0.16       0
Bank Sta=4990.5,4996.5
Exp/Cntr=0.3,0.1

Type RM Length L Ch R = 1,7362,417,417,417
BEGIN DESCRIPTION:
UNT 082 IN BOCR 14.0
END DESCRIPTION:
XS GIS Cut Line= 3
      3752899.62     10566310.22      3752749.61     10566060.19
      3752349.60     10565960.19
#Sta/Elev= 30
  4693.2  300.40  4716.6  299.41  4743.8  294.63  4814.1  288.33  4854.6  285.92
  4868.2  283.04  4875.9  278.33  4881.8  277.94  4903.1  283.24  4971.2  281.84
  4977.0  279.44  4978.9  273.77  4981.6  273.27  4984.9  273.77  4995.1  273.98
  5002.8  277.22  5008.0  276.06  5015.7  278.93  5056.9  280.79  5098.2  278.68
  5139.4  279.16  5172.9  281.87  5204.6  286.60  5209.0  288.11  5214.1  286.83
  5242.5  292.03  5314.6  301.61  5345.6  306.92  5373.9  315.13  5397.1  317.40
#Mann=5,-1,0
  4693.2    0.12       0  4814.1    0.16       0  4978.9    0.07       0
  4984.9    0.16       0  5204.6    0.12       0
Bank Sta=4978.9,4984.9
Exp/Cntr=0.3,0.1

Type RM Length L Ch R = 1,6945,455,455,455
BEGIN DESCRIPTION:
UNT 082 IN BOCR 13.0
END DESCRIPTION:
XS GIS Cut Line= 3
      3753049.63     10565710.19      3752649.61     10565660.19
      3752299.59     10565710.19
#Sta/Elev= 30
  4605.7  290.79  4615.8  291.04  4656.1  286.53  4686.3  285.65  4706.5  283.41
  4716.6  284.45  4736.7  281.31  4756.9  280.58  4767.0  281.43  4800.9  279.59
  4809.8  278.35  4837.5  278.63  4890.4  276.88  4968.0  276.28  4970.8  275.78
  4974.0  276.28  5109.8  278.23  5119.9  280.23  5150.3  283.92  5170.5  288.26
  5180.6  293.14  5200.1  297.42  5210.9  298.88  5221.0  303.13  5241.2  307.78
  5274.1  312.96  5311.9  319.16  5342.2  325.47  5352.3  325.81  5362.4  327.40
#Mann=6,-1,0
  4605.7    0.05       0  4800.9    0.16       0  4968.0    0.07       0
  4974.0    0.16       0  5200.1    0.12       0  5274.1    0.16       0
Bank Sta=4968,4974
Exp/Cntr=0.3,0.1

Type RM Length L Ch R = 1,6490,480,480,480
BEGIN DESCRIPTION:
UNT 082 IN BOCR 12.0
END DESCRIPTION:
XS GIS Cut Line= 3
      3753099.57     10565360.18      3752699.61     10565310.19
      3752499.64     10565360.18
#Sta/Elev= 30
  4625.9  288.83  4656.1  286.80  4663.7  284.17  4676.3  283.25  4706.5  284.19
  4758.5  280.44  4829.9  276.00  4857.7  276.61  4898.0  276.65  4905.5  275.26
  4958.4  274.37  4988.2  267.46  4990.9  266.96  4994.2  267.46  4998.7  271.97
  5008.8  272.52  5018.9  267.79  5047.0  267.76  5052.2  268.83  5070.2  267.57
  5088.2  274.91  5093.4  274.18  5129.5  277.66  5134.6  277.12  5163.0  286.24
  5170.7  288.14  5175.9  287.76  5183.6  291.59  5224.8  299.66  5235.1  300.50
#Mann=5,-1,0
  4625.9    0.08       0  4758.5    0.05       0  4857.7    0.12       0
  4988.2    0.07       0  4994.2    0.12       0
Bank Sta=4988.2,4994.2
Exp/Cntr=0.3,0.1

Type RM Length L Ch R = 1,6010,516,516,516
BEGIN DESCRIPTION:
UNT 082 IN BOCR 11.0
END DESCRIPTION:
XS GIS Cut Line= 3
      3753099.60     10565110.18      3752699.61     10564860.19
      3752399.64     10564810.19
#Sta/Elev= 30
  4535.7  287.35  4558.7  285.90  4563.1  284.46  4579.9  280.74  4630.0  280.02
  4637.7  278.67  4658.9  277.80  4665.4  275.51  4677.0  274.54  4724.4  271.40
  4747.4  270.88  4904.7  269.84  4984.4  270.37  4990.8  266.05  4993.6  265.55
  4996.8  266.05  5009.3  266.62  5017.5  270.61  5088.5  267.97  5096.1  269.31
  5101.2  268.80  5139.2  270.96  5149.3  270.63  5169.6  272.56  5210.2  277.09
  5230.4  281.90  5240.6  283.11  5278.6  290.23  5291.3  294.00  5311.5  296.51
#Mann=7,-1,0
  4535.7    0.16       0  4563.1    0.05       0  4677.0    0.16       0
  4904.7    0.12       0  4990.8    0.07       0  4996.8    0.12       0
  5009.3    0.16       0
Bank Sta=4990.8,4996.8
Exp/Cntr=0.3,0.1

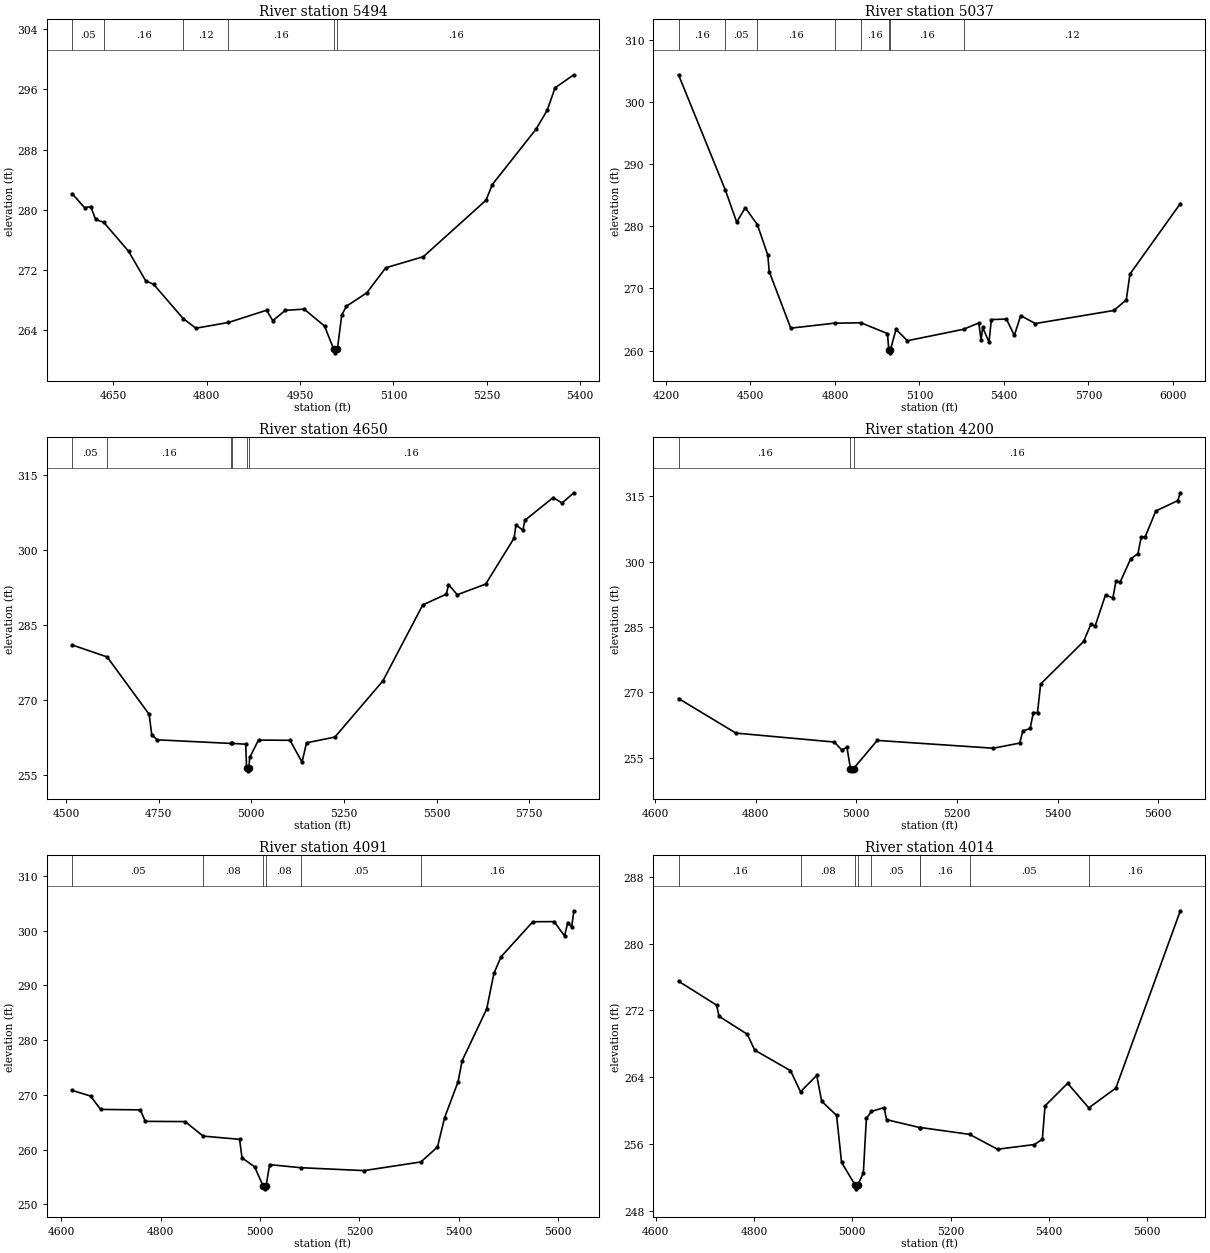
Type RM Length L Ch R = 1,5494,457,457,457
BEGIN DESCRIPTION:
UNT 082 IN BOCR 10.0
END DESCRIPTION:
XS GIS Cut Line= 3
      3753049.60     10564360.19      3752649.61     10564410.19
      3752249.62     10564460.19
#Sta/Elev= 30
  4583.6  282.16  4603.7  280.31  4613.8  280.43  4621.4  278.73  4634.5  278.35
  4674.3  274.52  4702.0  270.58  4714.6  270.13  4762.1  265.58  4782.6  264.30
  4834.8  265.06  4896.0  266.68  4906.1  265.30  4926.2  266.67  4956.5  266.83
  4989.2  264.59  5003.9  261.53  5006.6  261.03  5009.9  261.53  5016.9  266.07
  5024.5  267.22  5057.2  269.00  5087.5  272.32  5147.9  273.79  5248.7  281.29
  5258.8  283.37  5329.3  290.75  5347.0  293.24  5359.6  296.21  5389.8  297.94
#Mann=6,-1,0
  4583.6    0.05       0  4634.5    0.16       0  4762.1    0.12       0
  4834.8    0.16       0  5003.9    0.07       0  5009.9    0.16       0
Bank Sta=5003.9,5009.9
Exp/Cntr=0.3,0.1

Type RM Length L Ch R = 1,5037,387,387,387
BEGIN DESCRIPTION:
UNT 082 IN BOCR 9.0
END DESCRIPTION:
XS GIS Cut Line= 3
      3753264.07     10564119.96      3752326.54     10563988.01
      3751577.45     10564355.62
#Sta/Elev= 30
  4244.9  304.36  4411.1  285.82  4451.4  280.66  4481.7  282.99  4524.7  280.26
  4561.8  275.36  4566.8  272.70  4643.3  263.62  4798.6  264.42  4892.4  264.48
  4986.6  262.75  4991.2  260.15  4993.9  259.65  4997.2  260.15  5016.9  263.42
  5057.3  261.60  5256.7  263.44  5310.8  264.46  5318.9  261.65  5324.5  263.74
  5347.0  261.38  5355.3  265.00  5408.9  265.08  5436.9  262.44  5459.4  265.64
  5511.3  264.36  5789.8  266.46  5834.3  268.16  5847.3  272.32  6026.1  283.65
#Mann=8,-1,0
  4244.9    0.16       0  4411.1    0.05       0  4524.7    0.16       0
  4798.6    0.08       0  4892.4    0.16       0  4991.2    0.07       0
  4997.2    0.16       0  5256.7    0.12       0
Bank Sta=4991.2,4997.2
Exp/Cntr=0.3,0.1

Type RM Length L Ch R = 1,4650,450,450,450
BEGIN DESCRIPTION:
UNT 082 IN BOCR 8.0
END DESCRIPTION:
XS GIS Cut Line= 3
      3753039.11     10563947.15      3752936.32     10563828.23
      3751834.07     10563363.26
#Sta/Elev= 30
  4516.5  281.05  4611.1  278.65  4724.4  267.16  4731.4  263.08  4746.1  262.06
  4946.4  261.33  4948.2  261.35  4984.9  261.18  4987.3  256.35  4990.0  255.85
  4993.3  256.35  4995.7  258.55  5019.4  262.01  5104.3  261.96  5136.8  257.60
  5148.9  261.45  5225.4  262.61  5354.9  273.85  5462.4  289.06  5526.3  291.23
  5531.8  293.14  5555.5  291.10  5632.1  293.23  5708.6  302.41  5714.1  305.11
  5732.4  303.99  5737.8  305.99  5814.4  310.56  5838.1  309.45  5870.0  311.51
#Mann=6,-1,0
  4516.5    0.05       0  4611.1    0.16       0  4946.4     0.1       0
  4948.2    0.16       0  4987.3    0.07       0  4993.3    0.16       0
Bank Sta=4987.3,4993.3
Exp/Cntr=0.3,0.1

Type RM Length L Ch R = 1,4200,109,109,109
BEGIN DESCRIPTION:
Mapping XS a3f39a68
END DESCRIPTION:
XS GIS Cut Line= 3
      3752918.18     10563783.86      3752867.80     10563124.91
      3752664.45     10562857.14
#Sta/Elev= 30
  4646.7  268.61  4760.7  260.68  4956.1  258.63  4971.3  256.79  4981.3  257.43
  4988.4  252.52  4991.1  252.02  4994.4  252.52  5041.5  259.00  5272.2  257.21
  5324.6  258.39  5330.9  261.17  5345.4  261.74  5351.7  265.39  5360.0  265.37
  5366.2  271.94  5451.6  281.70  5466.1  285.67  5474.3  285.18  5495.2  292.39
  5509.7  291.66  5516.0  295.59  5524.2  295.32  5545.1  300.65  5559.6  301.85
  5565.9  305.57  5574.2  305.77  5595.0  311.63  5638.6  314.02  5643.8  315.82
#Mann=3,-1,0
  4646.7    0.16       0  4988.4    0.07       0  4994.4    0.16       0
Bank Sta=4988.4,4994.4
Exp/Cntr=0.3,0.1

Type RM Length L Ch R = 1,4091,77,77,77
BEGIN DESCRIPTION:
Mapping XS 5d3f4ae8
END DESCRIPTION:
XS GIS Cut Line= 4
      3752974.61     10563727.45      3752960.50     10563245.83
      3752964.53     10563036.24      3752763.83     10562789.39
#Sta/Elev= 30
  4622.0  270.82  4659.3  269.78  4679.3  267.34  4759.3  267.26  4769.3  265.16
  4849.4  265.12  4885.7  262.47  4959.0  261.88  4964.0  258.49  4989.4  256.85
  5006.4  253.34  5009.2  252.84  5012.4  253.34  5019.4  257.26  5082.2  256.70
  5209.5  256.17  5323.8  257.75  5357.2  260.47  5371.5  265.83  5398.8  272.43
  5406.7  276.21  5456.3  285.70  5470.7  292.16  5485.0  295.20  5549.0  301.61
  5591.9  301.63  5612.9  299.01  5619.3  301.44  5627.2  300.67  5631.6  303.61
#Mann=6,-1,0
  4622.0    0.05       0  4885.7    0.08       0  5006.4    0.07       0
  5012.4    0.08       0  5082.2    0.05       0  5323.8    0.16       0
Bank Sta=5006.4,5012.4
Exp/Cntr=0.3,0.1

Type RM Length L Ch R = 1,4014,454,454,454
BEGIN DESCRIPTION:
Mapping XS b4c5cf34
END DESCRIPTION:
XS GIS Cut Line= 5
      3753075.37     10563658.97      3753024.99     10563286.13
      3753103.58     10562949.59      3753047.16     10562826.66
      3752982.67     10562675.53
#Sta/Elev= 30
  4646.4  275.49  4723.8  272.63  4728.9  271.29  4786.4  269.14  4801.5  267.24
  4874.2  264.79  4894.7  262.26  4927.7  264.22  4937.8  261.12  4968.1  259.43
  4978.2  253.81  5005.4  251.14  5008.2  250.64  5011.4  251.14  5022.6  252.53
  5028.7  259.07  5039.1  259.91  5064.8  260.36  5069.9  258.92  5138.4  257.96
  5138.9  257.98  5238.8  257.16  5295.7  255.38  5370.6  255.94  5386.9  256.56
  5392.4  260.57  5438.4  263.27  5481.5  260.33  5536.6  262.70  5667.8  283.92
#Mann=9,-1,0
  4646.4    0.16       0  4894.7    0.08       0  5005.4    0.07       0
  5011.4    0.08       0  5039.1    0.05       0  5138.4    0.12       0
  5138.9    0.16       0  5238.8    0.05       0  5481.5    0.16       0
Bank Sta=5005.4,5011.4
Exp/Cntr=0.3,0.1

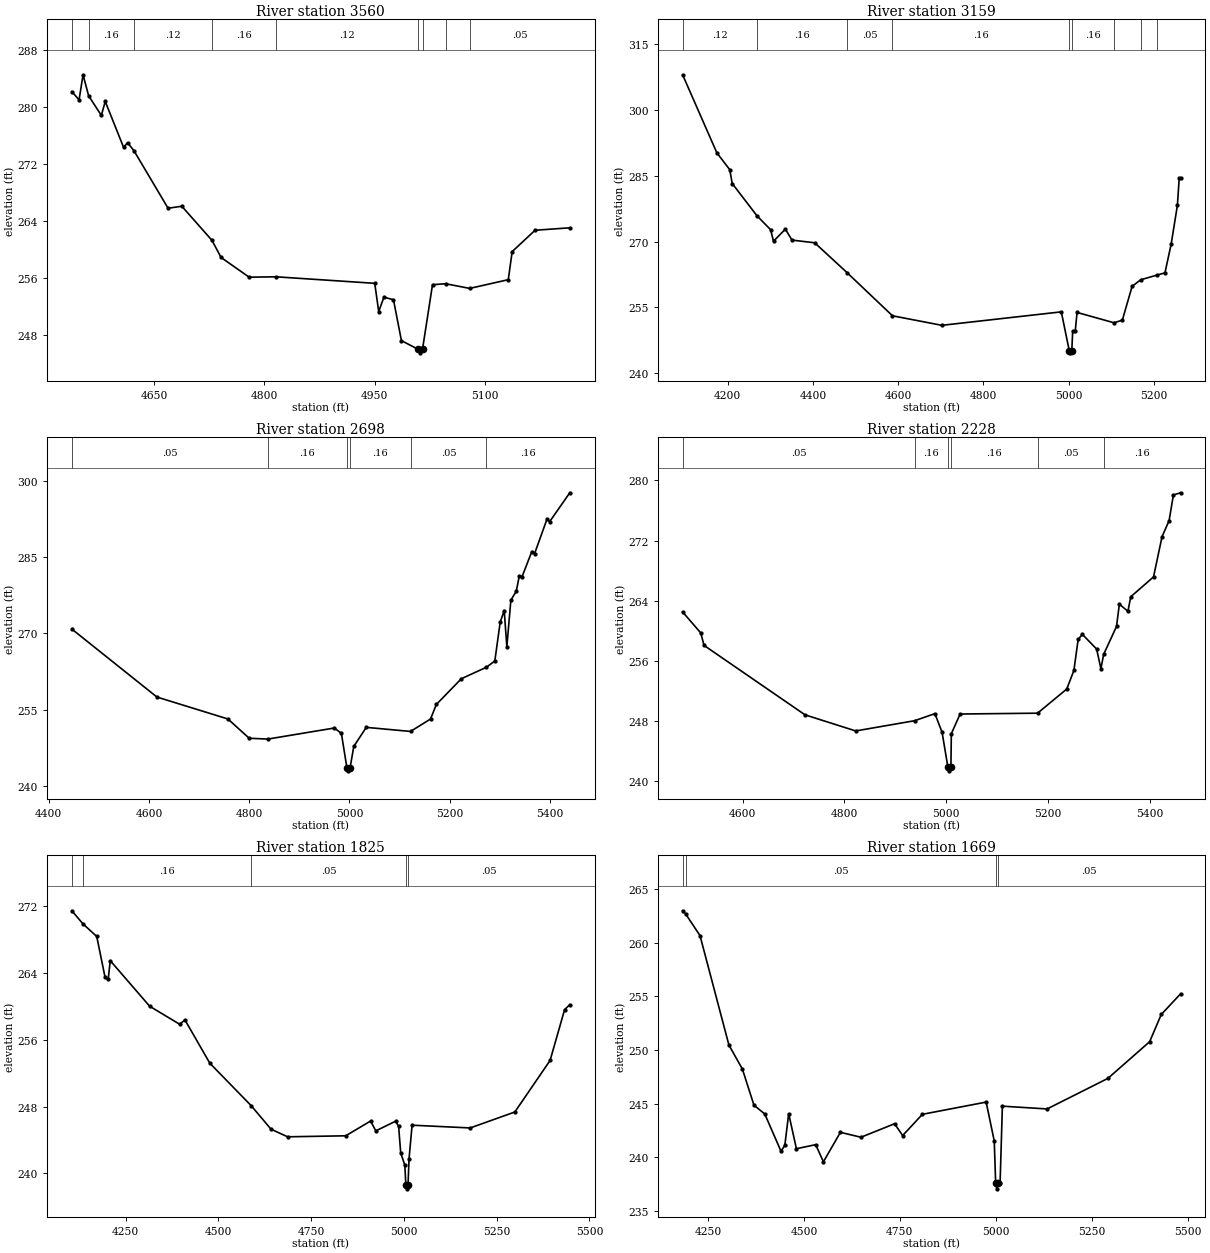
Type RM Length L Ch R = 1,3560,401,401,401
BEGIN DESCRIPTION:
UNT 082 IN BOCR 6.0
END DESCRIPTION:
XS GIS Cut Line= 3
      3753349.63     10563360.23      3753199.61     10562960.19
      3753118.26     10562723.53
#Sta/Elev= 30
  4538.2  282.12  4548.0  280.97  4553.4  284.48  4561.0  281.54  4578.3  278.79
  4583.6  280.75  4608.6  274.31  4613.9  274.98  4622.5  273.88  4669.1  265.80
  4687.8  266.08  4728.8  261.31  4741.2  258.91  4779.4  256.15  4816.4  256.20
  4950.3  255.29  4955.7  251.34  4962.8  253.35  4975.8  252.99  4986.6  247.27
  5009.3  246.06  5012.1  245.56  5015.3  246.06  5028.9  255.10  5046.8  255.23
  5079.5  254.58  5132.0  255.80  5137.3  259.73  5168.5  262.72  5215.7  263.06
#Mann=9,-1,0
  4538.2    0.05       0  4561.0    0.16       0  4622.5    0.12       0
  4728.8    0.16       0  4816.4    0.12       0  5009.3    0.07       0
  5015.3    0.12       0  5046.8    0.16       0  5079.5    0.05       0
Bank Sta=5009.3,5015.3
Exp/Cntr=0.3,0.1

Type RM Length L Ch R = 1,3159,461,461,461
BEGIN DESCRIPTION:
UNT 082 IN BOCR 5.0
END DESCRIPTION:
XS GIS Cut Line= 3
      3754199.63     10563060.20      3753399.61     10562610.19
      3753199.61     10562460.19
#Sta/Elev= 30
  4094.3  308.04  4174.6  290.24  4204.9  286.39  4210.7  283.23  4268.4  275.91
  4300.8  272.68  4307.5  270.06  4335.3  272.82  4350.9  270.32  4404.1  269.71
  4480.0  262.90  4586.6  253.05  4702.4  250.88  4982.6  253.95  5001.2  245.10
  5004.0  244.60  5007.2  245.10  5009.3  249.58  5015.3  249.58  5019.5  253.82
  5106.1  251.46  5125.7  252.05  5148.7  259.78  5168.8  261.27  5206.4  262.32
  5225.7  262.85  5240.3  269.43  5254.9  278.27  5259.1  284.41  5262.2  284.41
#Mann=9,-1,0
  4094.3    0.12       0  4268.4    0.16       0  4480.0    0.05       0
  4586.6    0.16       0  5001.2    0.07       0  5007.2    0.16       0
  5106.1    0.05       0  5168.8    0.08       0  5206.4    0.16       0
Bank Sta=5001.2,5007.2
Exp/Cntr=0.3,0.1

Type RM Length L Ch R = 1,2698,470,470,470
BEGIN DESCRIPTION:
UNT 082 IN BOCR 4.0
END DESCRIPTION:
XS GIS Cut Line= 3
      3754049.62     10562660.19      3753649.61     10562260.19
      3753249.60     10562110.19
#Sta/Elev= 30
  4446.4  270.83  4616.1  257.48  4757.5  253.18  4800.0  249.39  4837.2  249.23
  4969.7  251.40  4983.8  250.36  4995.0  243.49  4997.7  242.99  5001.0  243.49
  5008.6  247.80  5033.5  251.53  5121.7  250.73  5161.6  253.17  5173.2  256.03
  5223.0  261.08  5273.1  263.34  5289.8  264.57  5300.5  272.19  5308.5  274.48
  5313.8  267.37  5321.8  276.52  5332.5  278.25  5338.7  281.30  5344.1  281.12
  5363.6  286.07  5369.0  285.63  5393.9  292.45  5399.2  291.94  5439.3  297.61
#Mann=6,-1,0
  4446.4    0.05       0  4837.2    0.16       0  4995.0    0.07       0
  5001.0    0.16       0  5121.7    0.05       0  5273.1    0.16       0
Bank Sta=4995,5001
Exp/Cntr=0.3,0.1

Type RM Length L Ch R = 1,2228,403,403,403
BEGIN DESCRIPTION:
UNT 082 IN BOCR 3.0
END DESCRIPTION:
XS GIS Cut Line= 3
      3754249.59     10562310.17      3753899.61     10561910.19
      3753499.61     10561710.19
#Sta/Elev= 30
  4482.2  262.52  4517.8  259.74  4524.4  258.07  4722.8  248.85  4822.4  246.71
  4938.3  248.07  4978.1  249.01  4992.3  246.51  5003.6  241.91  5006.3  241.41
  5009.6  241.91  5010.4  246.34  5027.7  248.96  5179.9  249.07  5237.3  252.28
  5251.3  254.74  5259.7  258.87  5268.0  259.54  5296.0  257.59  5304.4  254.98
  5309.9  256.90  5335.1  260.59  5340.7  263.56  5357.5  262.60  5363.1  264.54
  5407.8  267.17  5424.6  272.52  5438.5  274.66  5446.9  278.06  5460.9  278.35
#Mann=6,-1,0
  4482.2    0.05       0  4938.3    0.16       0  5003.6    0.07       0
  5009.6    0.16       0  5179.9    0.05       0  5309.9    0.16       0
Bank Sta=5003.6,5009.6
Exp/Cntr=0.3,0.1

Type RM Length L Ch R = 1,1825,156,156,156
BEGIN DESCRIPTION:
UNT 082 IN BOCR 2.0
END DESCRIPTION:
XS GIS Cut Line= 3
      3754549.59     10562410.14      3754149.61     10561610.19
      3753749.60     10561410.18
#Sta/Elev= 30
  4105.4  271.45  4135.5  269.87  4172.4  268.38  4194.8  263.49  4203.2  263.23
  4208.8  265.48  4315.0  260.02  4396.0  257.86  4410.0  258.39  4477.1  253.20
  4588.5  248.12  4642.0  245.30  4686.7  244.39  4843.3  244.51  4910.3  246.28
  4924.3  245.10  4977.4  246.25  4985.8  245.65  4991.4  242.46  5002.6  240.98
  5005.2  238.66  5007.9  238.16  5011.2  238.66  5013.8  241.73  5022.1  245.78
  5178.7  245.45  5298.9  247.36  5393.9  253.53  5433.0  259.61  5447.0  260.21
#Mann=5,-1,0
  4105.4    0.05       0  4135.5    0.16       0  4588.5    0.05       0
  5005.2    0.03       0  5011.2    0.05       0
Bank Sta=5005.2,5011.2
Exp/Cntr=0.3,0.1

Type RM Length L Ch R = 1,1669,68,68,68
BEGIN DESCRIPTION:
Mapping XS 30ee38ee
END DESCRIPTION:
XS GIS Cut Line= 3
      3754542.10     10562125.20      3754585.51     10561708.51
      3753847.64     10561231.07
#Sta/Elev= 30
  4183.8  262.98  4192.0  262.67  4229.1  260.67  4304.5  250.46  4339.6  248.22
  4369.8  244.85  4398.0  244.03  4440.2  240.56  4450.2  241.10  4460.3  244.06
  4480.4  240.79  4530.7  241.17  4550.8  239.57  4595.1  242.32  4648.6  241.86
  4736.3  243.12  4757.4  242.02  4808.8  244.00  4975.0  245.14  4996.1  241.51
  4999.8  237.55  5002.6  237.05  5005.8  237.55  5011.3  237.57  5017.3  244.76
  5133.8  244.50  5292.3  247.35  5401.1  250.77  5431.4  253.31  5481.6  255.23
#Mann=4,-1,0
  4183.8    0.16       0  4192.0    0.05       0  4999.8    0.03       0
  5005.8    0.05       0
Bank Sta=4999.8,5005.8
Exp/Cntr=0.3,0.1

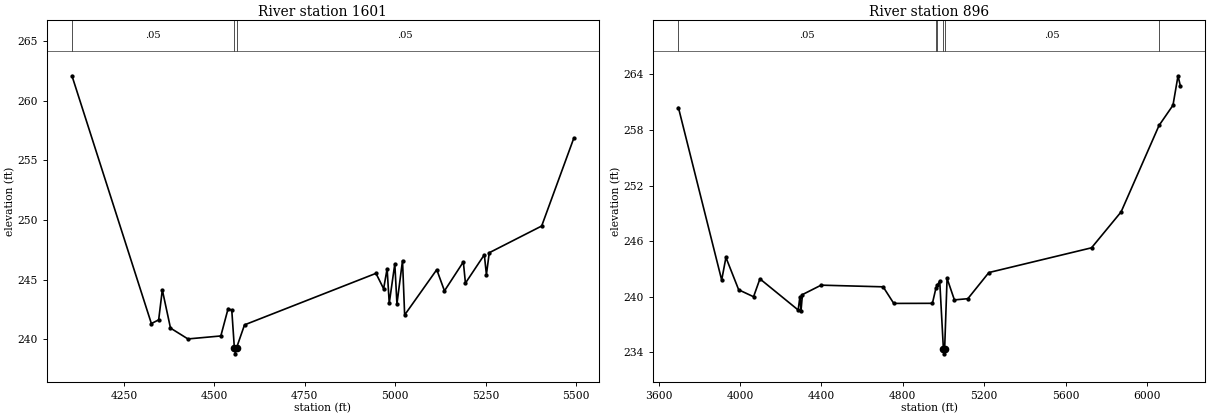
Type RM Length L Ch R = 1,1601,705,705,705
BEGIN DESCRIPTION:
Mapping XS d4180638
END DESCRIPTION:
XS GIS Cut Line= 3
      3754605.03     10562127.39      3754672.31     10561673.79
      3753880.24     10561187.69
#Sta/Elev= 30
  4106.4  262.10  4326.0  241.32  4346.2  241.63  4356.3  244.14  4378.9  240.94
  4427.1  240.03  4518.1  240.28  4538.3  242.58  4548.4  242.43  4555.5  239.28
  4558.2  238.78  4561.5  239.28  4583.6  241.21  4947.1  245.53  4968.3  244.24
  4977.9  245.92  4983.8  243.02  4999.2  246.33  5005.1  242.97  5020.5  246.60
  5026.4  242.04  5115.2  245.84  5136.5  244.06  5188.7  246.49  5194.5  244.71
  5246.7  247.09  5252.5  245.43  5260.4  247.26  5405.3  249.50  5494.3  256.88
#Mann=3,-1,0
  4106.4    0.05       0  4555.5    0.03       0  4561.5    0.05       0
Bank Sta=4555.5,4561.5
Exp/Cntr=0.3,0.1

Type RM Length L Ch R = 1,896,0,0,0
BEGIN DESCRIPTION:
UNT 082 IN BOCR 1.0
END DESCRIPTION:
XS GIS Cut Line= 4
      3754631.09     10562133.83      3754951.54     10561071.34
      3754618.20     10560849.12      3753723.45     10561188.99
#Sta/Elev= 30
  3696.7  260.42  3909.4  241.81  3930.3  244.25  3993.0  240.76  4066.1  240.01
  4097.4  241.94  4285.4  238.58  4294.1  240.02  4299.4  238.48  4306.3  240.24
  4398.3  241.26  4703.2  241.08  4755.4  239.29  4945.4  239.30  4962.4  240.91
  4969.4  241.25  4981.4  241.70  4999.5  234.35  5002.2  233.85  5005.5  234.35
  5017.5  241.99  5053.5  239.67  5119.6  239.80  5222.9  242.62  5727.7  245.29
  5873.0  249.16  6059.6  258.49  6128.1  260.67  6152.9  263.85  6164.2  262.77
#Mann=6,-1,0
  3696.7    0.05       0  4962.4    0.16       0  4969.4    0.05       0
  4999.5    0.03       0  5005.5    0.05       0  6059.6    0.08       0
Bank Sta=4999.5,5005.5
Exp/Cntr=0.3,0.1

Chan Stop Cuts=-1