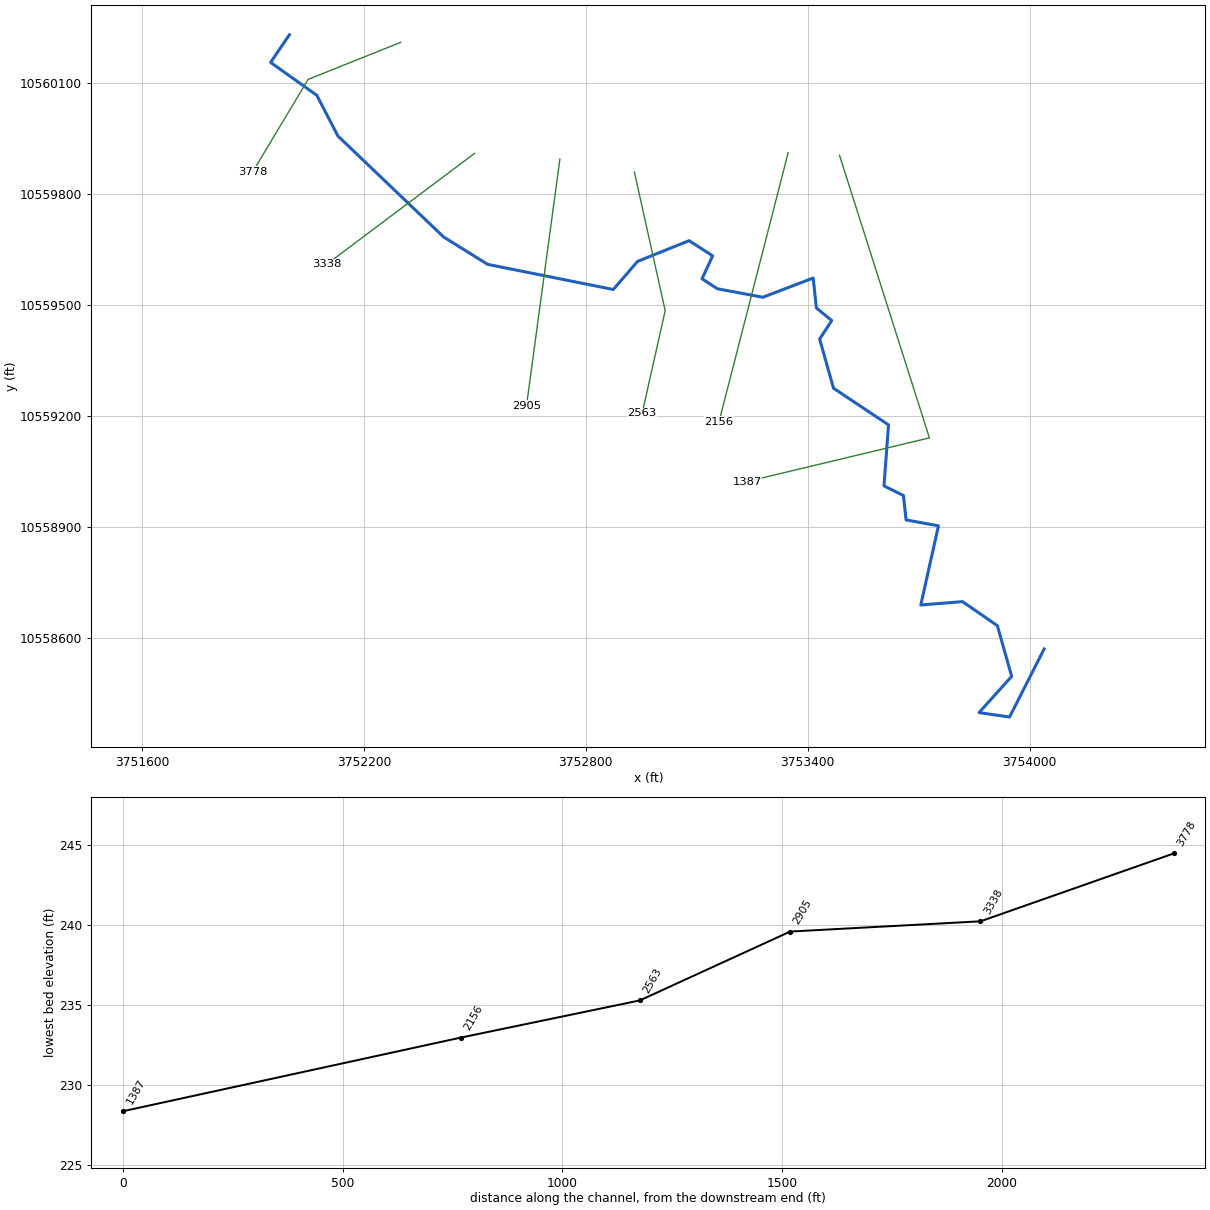
--- UNT 083 IN BOCR.prj (project) ---

Proj Title=UNT 083 IN BOCR Base Level Engineering
Current Plan=p01
Default Exp/Contr=0.3,0.1
English Units
Geom File=g01
Flow File=f01
Plan File=p01
Y Axis Title=Elevation
X Axis Title(PF)=Main Channel Distance
X Axis Title(XS)=Station
BEGIN DESCRIPTION:
UNT 083 IN BOCR
END DESCRIPTION:
DSS Export Rating Curves= 0
DSS Export Rating Curve Sorted= 0
DSS Export Volume Flow Curves= 0
DXF OffsetX= 0
DXF OffsetY= 0
DXF ScaleX= 1
DXF ScaleY= 10

--- UNT 083 IN BOCR.p01 (plan) ---

Plan Title=Multiple Run
Short Identifier=Multiple
Geom File=g01
Flow File=f01
Subcritical Flow
K Sum by GR= 0
Std Step Tol= 0.01
Critical Tol= 0.01
Num of Std Step Trials= 20
Max Error Tol= 0.3
Flow Tol Ratio= 0.001
Split Flow NTrial= 30
Split Flow Tol= 0.02
Split Flow Ratio= 0.02
Log Output Level= 0
Friction Slope Method= 1
Unsteady Friction Slope Method= 2
Unsteady Bridges Friction Slope Method= 1
Parabolic Critical Depth
Global Vel Dist=  1 , 1 , 1
Global Log Level= 0
CheckData=True
Encroach Param= -1, 0, 0, 0
BEGIN DESCRIPTION:
Multiple Run
END DESCRIPTION:

--- UNT 083 IN BOCR.f01 (steady flow) ---

Flow Title=Multiple
Program Version=4.10
Number of Profiles= 7
Profile Names=10-year,25-year,50-year,1pct_min,100-year,1pct_plu,500-year
River Rch & RM=UNT 083 IN BOCR,Reach-1         ,3778
     439     589     712     635     859    1162    1251
Boundary for River Rch & Prof#=UNT 083 IN BOCR,Reach-1         , 1
Up Type= 0
Dn Type= 3
Dn Slope=0.005
Boundary for River Rch & Prof#=UNT 083 IN BOCR,Reach-1         , 2
Up Type= 0
Dn Type= 3
Dn Slope=0.005
Boundary for River Rch & Prof#=UNT 083 IN BOCR,Reach-1         , 3
Up Type= 0
Dn Type= 3
Dn Slope=0.005
Boundary for River Rch & Prof#=UNT 083 IN BOCR,Reach-1         , 4
Up Type= 0
Dn Type= 3
Dn Slope=0.005
Boundary for River Rch & Prof#=UNT 083 IN BOCR,Reach-1         , 5
Up Type= 0
Dn Type= 3
Dn Slope=0.005
Boundary for River Rch & Prof#=UNT 083 IN BOCR,Reach-1         , 6
Up Type= 0
Dn Type= 3
Dn Slope=0.005
Boundary for River Rch & Prof#=UNT 083 IN BOCR,Reach-1         , 7
Up Type= 0
Dn Type= 3
Dn Slope=0.005
DSS Import GetInterval= 0
DSS Import GetPeak= 0
DSS Import FillOption= 0

--- UNT 083 IN BOCR.g01 (geometry) ---

Geom Title=Existing Conditions

River Reach=UNT 083 IN BOCR,Reach-1
Reach XY= 30
      3751999.00     10560231.00      3751948.00     10560156.00
      3752073.00     10560067.00      3752130.00     10559957.00
      3752415.75     10559684.00      3752534.75     10559610.00
      3752874.50     10559542.00      3752940.25     10559618.00
      3753079.50     10559674.00      3753143.25     10559633.00
      3753114.50     10559571.00      3753156.00     10559544.00
      3753279.00     10559521.00      3753415.00     10559573.00
      3753423.75     10559492.00      3753465.25     10559458.00
      3753432.50     10559408.00      3753470.00     10559275.00
      3753618.75     10559176.00      3753606.50     10559011.00
      3753659.00     10558985.00      3753666.25     10558919.00
      3753753.75     10558903.00      3753706.00     10558689.00
      3753819.00     10558698.00      3753913.00     10558633.00
      3753951.75     10558496.00      3753863.50     10558398.00
      3753946.00     10558386.00      3754039.50     10558570.00

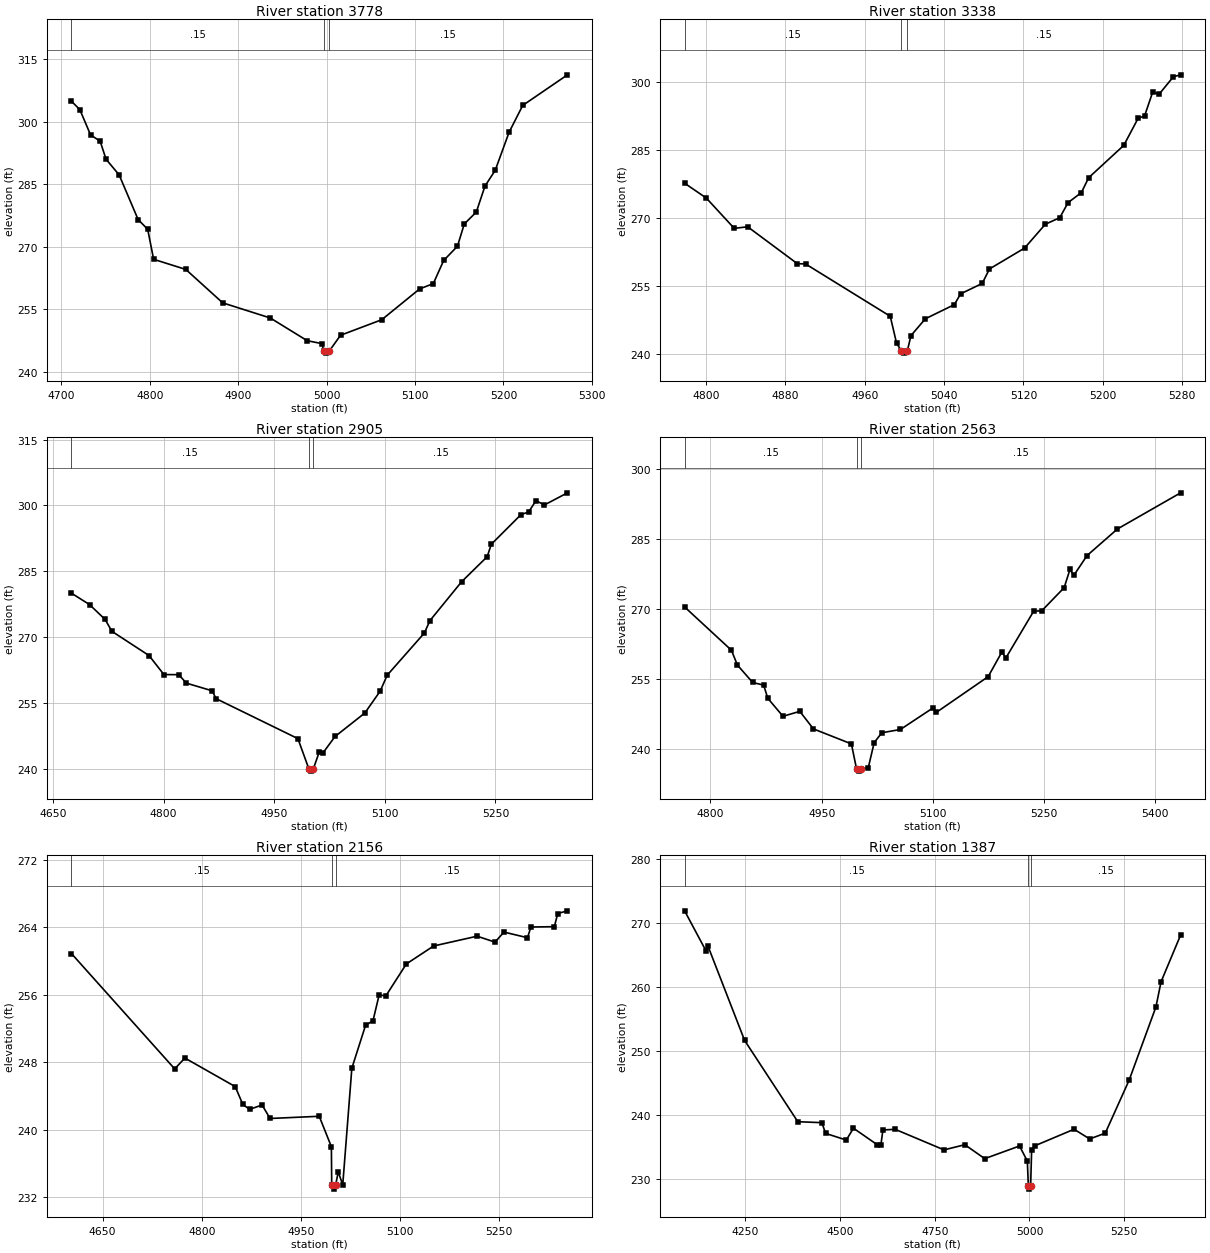
Type RM Length L Ch R = 1,3778,440,440,440
BEGIN DESCRIPTION:
UNT 083 IN BOCR 5.0
END DESCRIPTION:
XS GIS Cut Line= 3
      3752299.65     10560210.21      3752049.61     10560110.19
      3751899.58     10559860.15
#Sta/Elev= 30
  4711.5  304.92  4721.0  302.89  4733.1  296.84  4743.9  295.34  4750.6  291.01
  4765.4  287.24  4786.9  276.51  4797.7  274.19  4804.4  266.98  4840.8  264.55
  4882.5  256.53  4936.4  252.89  4978.1  247.44  4994.4  246.76  4997.0  244.96
  4999.8  244.46  5003.0  244.96  5015.8  248.75  5062.4  252.48  5105.2  259.87
  5120.7  261.15  5132.4  266.70  5148.0  270.12  5155.7  275.46  5169.3  278.32
  5179.1  284.55  5190.7  288.34  5206.3  297.44  5221.8  303.92  5272.4  311.26
#Mann=3,-1,0
  4711.5    0.15       0  4997.0    0.05       0  5003.0    0.15       0
Bank Sta=4997,5003
Exp/Cntr=0.3,0.1

Type RM Length L Ch R = 1,3338,433,433,433
BEGIN DESCRIPTION:
UNT 083 IN BOCR 4.0
END DESCRIPTION:
XS GIS Cut Line= 3
      3752499.64     10559910.21      3752299.61     10559760.19
      3752099.64     10559610.21
#Sta/Elev= 30
  4778.5  277.65  4800.4  274.38  4828.5  267.71  4842.1  268.05  4892.1  259.93
  4900.4  259.87  4985.8  248.34  4992.1  242.46  4997.0  240.72  4999.8  240.22
  5003.0  240.72  5006.7  244.09  5021.2  247.79  5050.4  250.90  5056.7  253.28
  5078.5  255.57  5085.8  258.76  5121.2  263.36  5142.1  268.61  5156.7  270.06
  5165.0  273.36  5178.5  275.60  5185.8  278.86  5221.2  285.99  5235.8  292.01
  5242.1  292.43  5250.4  297.77  5256.7  297.23  5271.2  301.10  5278.5  301.53
#Mann=3,-1,0
  4778.5    0.15       0  4997.0    0.05       0  5003.0    0.15       0
Bank Sta=4997,5003
Exp/Cntr=0.3,0.1

Type RM Length L Ch R = 1,2905,342,342,342
BEGIN DESCRIPTION:
UNT 083 IN BOCR 3.0
END DESCRIPTION:
XS GIS Cut Line= 2
      3752730.19     10559894.47      3752639.92     10559227.86
#Sta/Elev= 30
  4675.0  280.05  4699.5  277.46  4720.7  274.07  4729.8  271.38  4780.2  265.87
  4800.4  261.54  4820.6  261.52  4830.7  259.60  4865.8  257.85  4871.1  256.07
  4982.1  246.97  4997.0  240.08  4999.8  239.58  5003.0  240.08  5011.0  243.91
  5016.0  243.70  5032.5  247.46  5072.9  252.80  5093.7  257.78  5103.2  261.40
  5153.6  270.99  5161.2  273.82  5204.1  282.65  5238.8  288.35  5244.4  291.18
  5284.8  297.95  5294.9  298.50  5305.0  301.10  5316.4  300.12  5347.7  302.88
#Mann=3,-1,0
  4675.0    0.15       0  4997.0    0.05       0  5003.0    0.15       0
Bank Sta=4997,5003
Exp/Cntr=0.3,0.1

Type RM Length L Ch R = 1,2563,407,407,407
BEGIN DESCRIPTION:
UNT 083 IN BOCR 2.0
END DESCRIPTION:
XS GIS Cut Line= 3
      3752931.59     10559859.74      3753014.92     10559484.78
      3752952.42     10559207.03
#Sta/Elev= 30
  4765.2  270.43  4828.3  261.17  4836.4  257.99  4856.9  254.27  4871.8  253.69
  4877.4  250.86  4897.9  247.02  4920.5  248.08  4938.9  244.32  4990.1  241.11
  4997.0  235.78  4999.8  235.28  5003.0  235.78  5012.7  235.92  5020.8  241.38
  5031.1  243.49  5056.2  244.20  5099.7  248.77  5104.8  247.88  5174.5  255.51
  5193.1  260.82  5198.2  259.47  5236.0  269.56  5246.6  269.58  5277.0  274.57
  5284.8  278.47  5289.9  277.17  5307.8  281.43  5348.8  287.13  5434.0  294.87
#Mann=3,-1,0
  4765.2    0.15       0  4997.0    0.05       0  5003.0    0.15       0
Bank Sta=4997,5003
Exp/Cntr=0.3,0.1

Type RM Length L Ch R = 1,2156,769,769,769
BEGIN DESCRIPTION:
Mapping XS ef61787d
END DESCRIPTION:
XS GIS Cut Line= 2
      3753347.37     10559911.62      3753160.22     10559183.80
#Sta/Elev= 30
  4602.7  260.90  4759.1  247.22  4774.5  248.51  4850.8  245.12  4862.3  243.01
  4872.6  242.42  4891.5  242.94  4903.6  241.34  4978.1  241.60  4996.5  237.99
  4997.0  233.46  4999.8  232.96  5003.0  233.46  5006.9  235.01  5013.7  233.46
  5027.5  247.30  5048.2  252.37  5059.6  252.95  5068.8  255.98  5079.1  255.89
  5110.1  259.67  5151.4  261.80  5217.3  262.96  5244.4  262.26  5258.0  263.45
  5293.6  262.78  5298.8  264.05  5334.3  264.09  5339.5  265.65  5354.2  265.97
#Mann=3,-1,0
  4602.7    0.15       0  4997.0    0.05       0  5003.0    0.15       0
Bank Sta=4997,5003
Exp/Cntr=0.3,0.1

Type RM Length L Ch R = 1,1387,0,0,0
BEGIN DESCRIPTION:
UNT 083 IN BOCR 1.0
END DESCRIPTION:
XS GIS Cut Line= 3
      3753486.26     10559904.69      3753729.31     10559140.79
      3753236.28     10559022.74
#Sta/Elev= 30
  4090.1  271.91  4146.3  265.67  4151.6  266.41  4248.3  251.64  4388.7  238.91
  4452.2  238.76  4462.1  237.08  4516.6  236.04  4535.6  237.89  4598.5  235.30
  4608.1  235.34  4613.3  237.62  4645.6  237.72  4774.5  234.50  4829.4  235.31
  4881.9  233.13  4973.7  235.11  4994.3  232.75  4997.0  228.86  4999.8  228.36
  5003.0  228.86  5005.7  234.56  5014.8  235.16  5117.6  237.73  5158.8  236.21
  5199.9  237.12  5263.0  245.43  5333.6  256.88  5347.1  260.81  5398.7  268.12
#Mann=3,-1,0
  4090.1    0.15       0  4997.0    0.05       0  5003.0    0.15       0
Bank Sta=4997,5003
Exp/Cntr=0.3,0.1

Chan Stop Cuts=-1