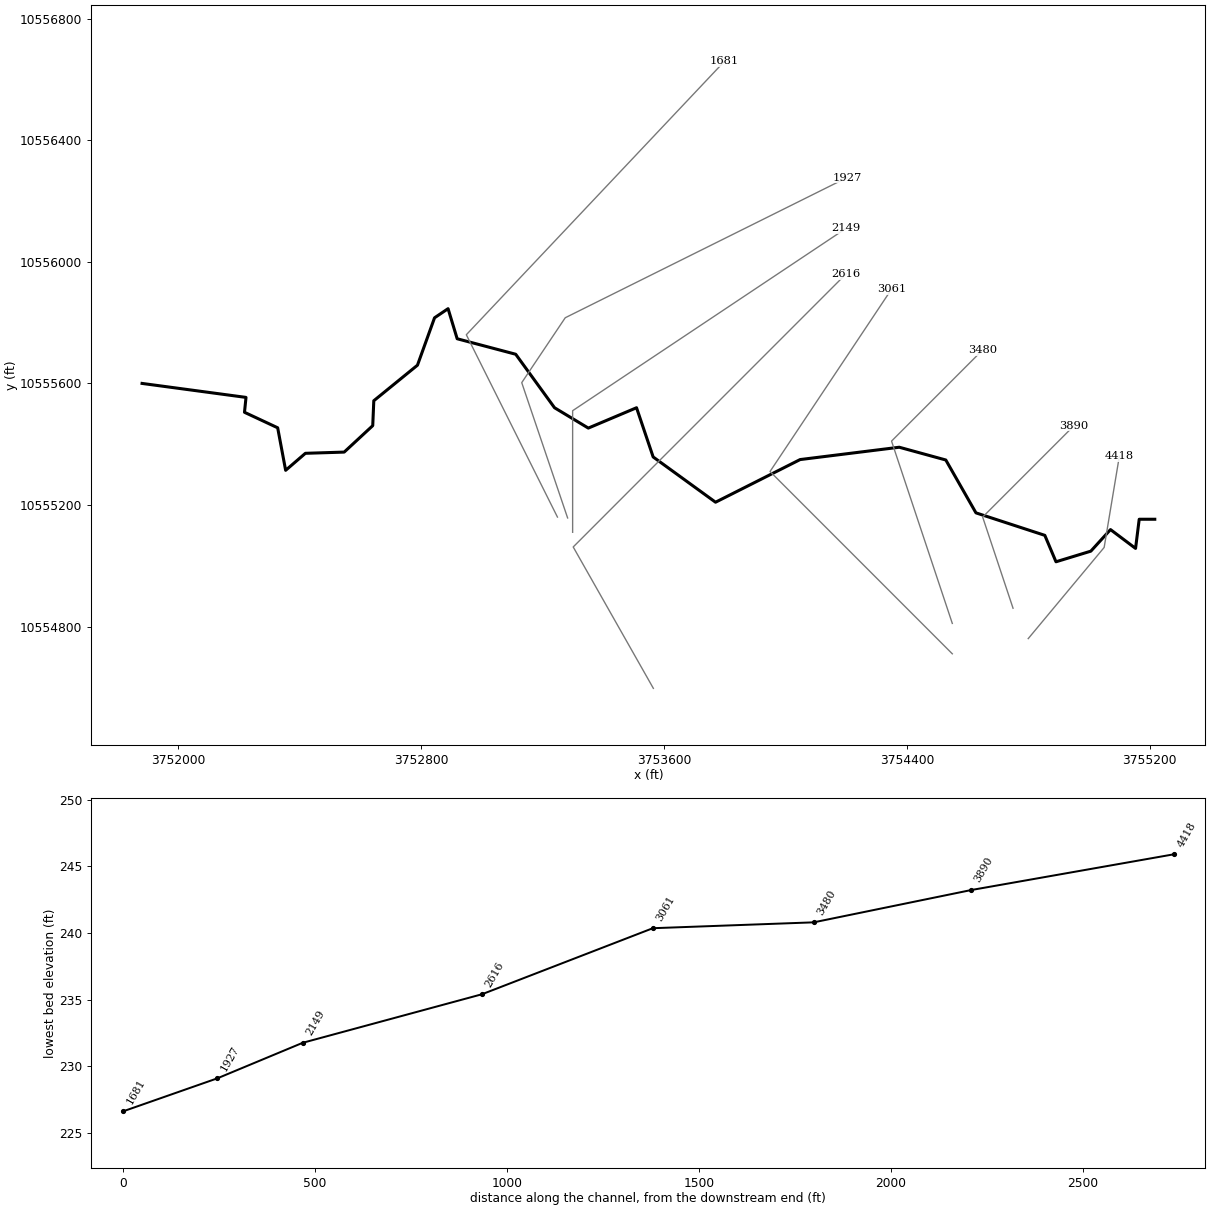
--- UNT 084 IN BOCR.prj (project) ---

Proj Title=UNT 084 IN BOCR Base Level Engineering
Current Plan=p01
Default Exp/Contr=0.3,0.1
English Units
Geom File=g01
Flow File=f01
Plan File=p01
Y Axis Title=Elevation
X Axis Title(PF)=Main Channel Distance
X Axis Title(XS)=Station
BEGIN DESCRIPTION:
UNT 084 IN BOCR
END DESCRIPTION:
DSS Export Rating Curves= 0
DSS Export Rating Curve Sorted= 0
DSS Export Volume Flow Curves= 0
DXF OffsetX= 0
DXF OffsetY= 0
DXF ScaleX= 1
DXF ScaleY= 10

--- UNT 084 IN BOCR.p01 (plan) ---

Plan Title=Multiple Run
Short Identifier=Multiple
Geom File=g01
Flow File=f01
Subcritical Flow
K Sum by GR= 0
Std Step Tol= 0.01
Critical Tol= 0.01
Num of Std Step Trials= 20
Max Error Tol= 0.3
Flow Tol Ratio= 0.001
Split Flow NTrial= 30
Split Flow Tol= 0.02
Split Flow Ratio= 0.02
Log Output Level= 0
Friction Slope Method= 1
Unsteady Friction Slope Method= 2
Unsteady Bridges Friction Slope Method= 1
Parabolic Critical Depth
Global Vel Dist=  1 , 1 , 1
Global Log Level= 0
CheckData=True
Encroach Param= -1, 0, 0, 0
BEGIN DESCRIPTION:
Multiple Run
END DESCRIPTION:

--- UNT 084 IN BOCR.f01 (steady flow) ---

Flow Title=Multiple
Number of Profiles=7
Profile Names=10-year,25-year,50-year,1pct_min,100-year,1pct_plu,500-year
River Rch & RM= UNT 084 IN BOCR,Reach-1,4418
     689     953    1177    1070    1447    1956    2192
Boundary for River Rch & Prof#=UNT 084 IN BOCR,Reach-1,1
Up Type=0
Dn Type=3
Dn Slope=0.005
Boundary for River Rch & Prof#=UNT 084 IN BOCR,Reach-1,2
Up Type=0
Dn Type=3
Dn Slope=0.005
Boundary for River Rch & Prof#=UNT 084 IN BOCR,Reach-1,3
Up Type=0
Dn Type=3
Dn Slope=0.005
Boundary for River Rch & Prof#=UNT 084 IN BOCR,Reach-1,4
Up Type=0
Dn Type=3
Dn Slope=0.005
Boundary for River Rch & Prof#=UNT 084 IN BOCR,Reach-1,5
Up Type=0
Dn Type=3
Dn Slope=0.005
Boundary for River Rch & Prof#=UNT 084 IN BOCR,Reach-1,6
Up Type=0
Dn Type=3
Dn Slope=0.005
Boundary for River Rch & Prof#=UNT 084 IN BOCR,Reach-1,7
Up Type=0
Dn Type=3
Dn Slope=0.005

--- UNT 084 IN BOCR.g01 (geometry) ---

Geom Title=Existing Conditions
Program Version=4.10

River Reach=UNT 084 IN BOCR ,Reach-1
Reach XY= 30
      3755216.27       10555153.        3755165.       10555153.
        3755153.       10555057.       3755070.5       10555119.
      3755005.75       10555048.        3754891.       10555013.
      3754854.25       10555100.       3754627.5       10555174.
      3754528.25       10555348.        3754375.       10555390.
      3754048.61     10555349.41      3753770.14     10555209.05
      3753564.75       10555358.        3753510.       10555520.
      3753351.25       10555453.        3753240.       10555520.
      3753112.25       10555696.       3752919.5       10555747.
       3752889.5       10555846.        3752845.       10555816.
      3752788.75       10555660.        3752645.       10555543.
       3752641.5       10555461.       3752547.5       10555374.
      3752419.75       10555370.      3752354.75       10555314.
       3752328.5       10555454.      3752219.25       10555505.
      3752224.25       10555554.        3751882.       10555600.

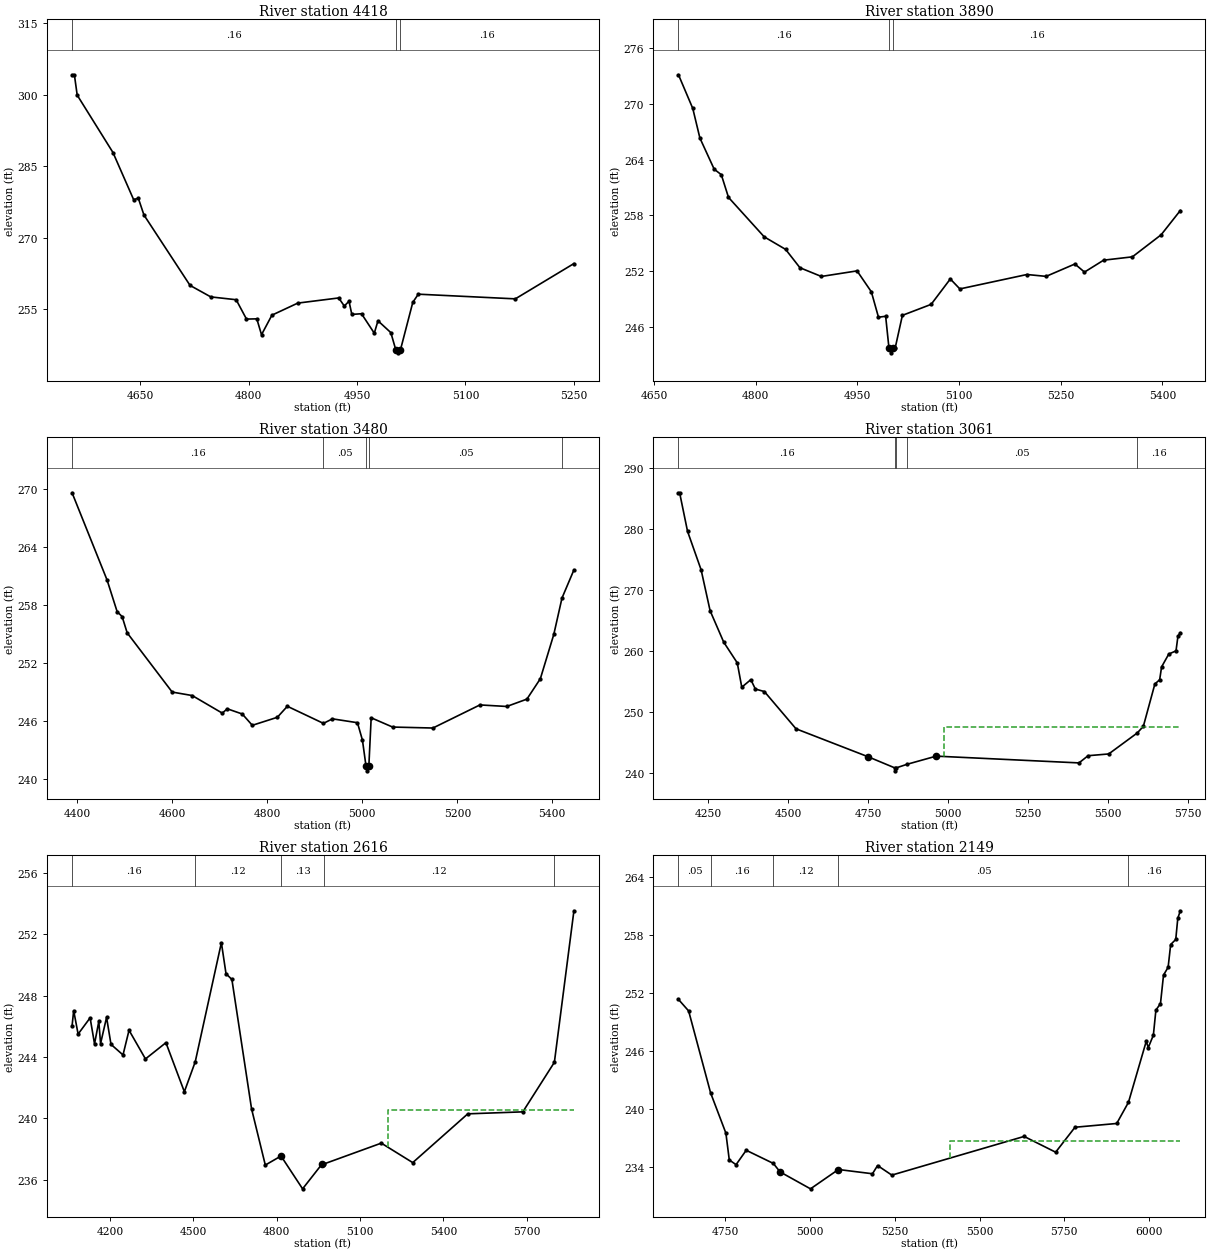
Type RM Length L Ch R = 1 ,4418    ,528,528,528
BEGIN DESCRIPTION:
UNT 084 IN BOCR 7.0
END DESCRIPTION:
XS GIS Cut Line= 3
      3754799.64     10554760.22      3755049.61     10555060.19
      3755099.61     10555360.18
#Sta/Elev= 30
  4555.6  304.21  4558.8  304.21  4562.7  299.94  4612.2  287.91  4640.8  278.03
  4647.3  278.32  4655.1   274.8  4718.9  260.04  4747.6  257.63  4782.7  257.04
    4797  252.98  4811.3  253.03  4817.8   249.7  4832.2   253.8    4868  256.33
  4924.6  257.41  4932.4  255.72  4938.9  256.72  4942.8  253.96  4956.2   254.1
  4973.9  250.02    4979  252.62  4996.8  250.14  5003.9   246.4  5006.6   245.9
  5009.9   246.4  5027.2  256.49  5034.8   258.2  5169.1  257.22  5250.2  264.62
#Mann= 3 ,-1 , 0
  4555.6     .16       0  5003.9     .07       0  5009.9     .16       0
Bank Sta=5003.9,5009.9
XS Rating Curve= 0 ,0
Exp/Cntr=0.3,0.1

Type RM Length L Ch R = 1 ,3890    ,410,410,410
BEGIN DESCRIPTION:
UNT 084 IN BOCR 6.0
END DESCRIPTION:
XS GIS Cut Line= 3
       3754749.6      10554860.2      3754649.61     10555160.19
      3754949.63     10555460.21
#Sta/Elev= 30
    4686  273.11  4707.1  269.49  4717.6  266.31  4738.7  262.96  4749.2  262.37
  4759.8  259.93  4812.5  255.69  4844.1  254.34  4865.2  252.37  4896.8  251.43
  4949.5  252.03  4970.6  249.78  4981.1  247.05  4991.7  247.15  4996.6  243.72
  4999.3  243.22  5002.6  243.72  5005.7  243.72  5016.4  247.25  5058.8  248.43
  5087.1  251.16  5101.2  250.09  5200.2  251.64  5228.5  251.44  5270.9  252.77
  5285.1   251.9  5313.3  253.18  5355.8  253.54  5398.2  255.91  5426.5  258.52
#Mann= 3 ,-1 , 0
    4686     .16       0  4996.6     .07       0  5002.6     .16       0
Bank Sta=4996.6,5002.6
XS Rating Curve= 0 ,0
Exp/Cntr=0.3,0.1

Type RM Length L Ch R = 1 ,3480    ,419,419,419
BEGIN DESCRIPTION:
UNT 084 IN BOCR 5.0
END DESCRIPTION:
XS GIS Cut Line= 3
      3754549.62     10554810.16      3754349.61     10555410.19
      3754649.58     10555710.16
#Sta/Elev= 30
  4388.8  269.57  4462.6  260.53  4483.7  257.27  4494.2  256.76  4504.8  255.08
  4599.6  248.95  4641.8  248.59  4705.1  246.77  4715.6  247.22  4747.2  246.68
  4768.3  245.51    4821  246.34  4842.1  247.48  4918.1  245.71    4937  246.18
  4989.7  245.78  5000.2  243.98  5007.7   241.3  5010.5   240.8  5013.7   241.3
  5018.6  246.29  5063.7  245.33  5148.6  245.23  5247.6  247.62  5304.1  247.46
  5346.5  248.22  5374.8  250.33  5403.1  254.91  5420.4  258.68  5445.5  261.59
#Mann= 5 ,-1 , 0
  4388.8     .16       0  4918.1     .05       0  5007.7     .03       0
  5013.7     .05       0  5420.4     .16       0
Bank Sta=5007.7,5013.7
XS Rating Curve= 0 ,0
Exp/Cntr=0.3,0.1

Type RM Length L Ch R = 1 ,3061    ,445,445,445
BEGIN DESCRIPTION:
UNT 084 IN BOCR 4.0
END DESCRIPTION:
XS GIS Cut Line= 3
      3754549.64     10554710.16      3753949.61     10555310.19
      3754349.62     10555910.21
#Sta/Elev= 30
  4156.2  285.95  4159.8  285.95  4184.5  279.64    4227  273.32  4255.2   266.6
  4297.7  261.46  4340.1  258.06  4354.2  254.07  4382.5  255.31  4396.7  253.77
  4424.9  253.36  4523.9  247.25  4750.2  242.65  4832.1  240.86  4834.8  240.36
  4838.1  240.86  4871.5  241.44  4962.3  242.77  5408.9  241.66  5437.4  242.84
    5502  243.13    5591  246.56  5610.2  247.65  5646.3   254.6  5661.3   255.3
  5667.3   257.4  5689.8  259.51  5712.4  260.03  5718.4  262.41  5725.9     263
#Mann= 5 ,-1 , 0
  4156.2     .16       0  4832.1     .03       0  4838.1     .16       0
  4871.5     .05       0    5591     .16       0
#XS Ineff= 2 , 0
                         4987.95          247.51
Permanent Ineff=
       F       F
Bank Sta=4750.2,4962.3
XS Rating Curve= 0 ,0
Exp/Cntr=0.3,0.1

Type RM Length L Ch R = 1 ,2616    ,467,467,467
BEGIN DESCRIPTION:
UNT 084 IN BOCR 3.0
END DESCRIPTION:
XS GIS Cut Line= 4
       3753565.4      10554596.5      3753301.51     10555061.78
      3753599.61     10555360.19      3754199.59     10555960.17
#Sta/Elev= 30
  4064.1  246.03  4069.9  247.03  4085.8   245.5    4129  246.56  4144.9  244.86
  4160.3  246.33  4166.6  244.88  4188.2  246.59  4204.1  244.83  4247.3  244.14
    4269  245.75  4328.1  243.88  4401.7  244.94    4468  241.74  4507.1  243.69
  4601.2  251.46  4617.8  249.44    4639  249.06  4709.7  240.63  4759.2  236.96
  4815.7  237.55  4893.3  235.41  4964.2  237.05  4971.3  237.04  5176.4  238.39
  5289.5  237.12  5487.5   240.3  5685.5  240.43    5799  243.66  5869.3  253.54
#Mann= 5 ,-1 , 0
  4064.1     .16       0  4507.1     .12       0  4815.7     .13       0
  4971.3     .12       0    5799     .16       0
#XS Ineff= 2 , 0
                         5198.86          240.56
Permanent Ineff=
       F       F
Bank Sta=4815.7,4964.2
XS Rating Curve= 0 ,0
Exp/Cntr=0.3,0.1

Type RM Length L Ch R = 1 ,2149    ,222,222,222
BEGIN DESCRIPTION:
UNT 084 IN BOCR 2.0
END DESCRIPTION:
XS GIS Cut Line= 3
      3753299.61     10555110.14      3753299.61     10555510.19
       3754199.6     10556110.18
#Sta/Elev= 30
  4611.2  251.36  4641.2  250.17  4706.1  241.69  4751.2  237.53  4761.2  234.76
  4781.2  234.27  4811.2  235.76  4891.2   234.4  4911.2  233.52    5001  231.77
  5083.4  233.77    5184  233.33    5199  234.18  5241.1  233.19  5631.7  237.19
  5724.8  235.56  5781.9  238.14  5905.1  238.53  5939.8  240.72  5992.3  247.03
  5998.3  246.38  6013.3  247.66  6020.8  250.26  6034.3  250.93  6043.3  253.88
  6056.9  254.69  6064.4  257.04  6079.4  257.56  6085.4  259.75  6092.9  260.53
#Mann= 5 ,-1 , 0
  4611.2     .05       0  4706.1     .16       0  4891.2     .12       0
  5083.4     .05       0  5939.8     .16       0
#XS Ineff= 2 , 0
                         5411.82          236.75
Permanent Ineff=
       F       F
Bank Sta=4911.2,5083.4
XS Rating Curve= 0 ,0
Exp/Cntr=0.3,0.1

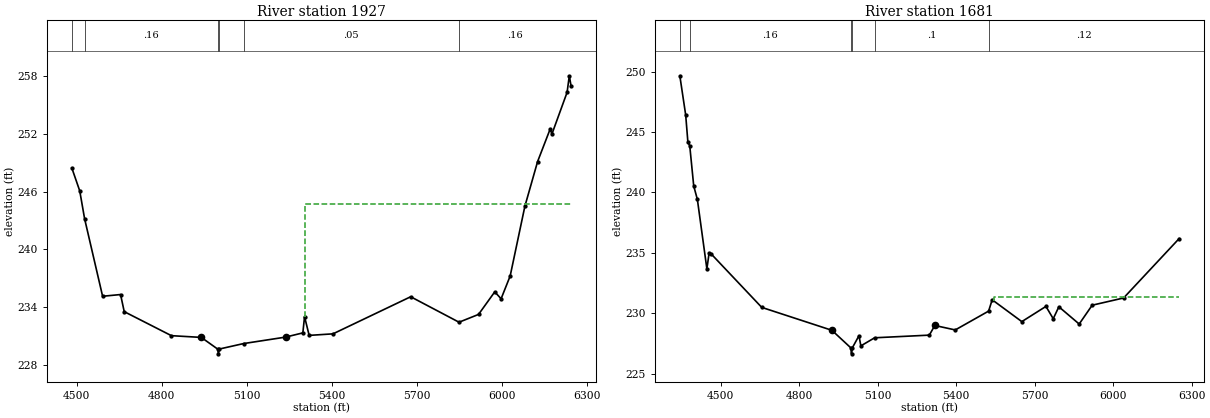
Type RM Length L Ch R = 1 ,1927    ,246,246,246
BEGIN DESCRIPTION:
Mapping XS d63312b4
END DESCRIPTION:
XS GIS Cut Line= 4
      3753283.12     10555157.24      3753132.06     10555602.58
      3753275.29     10555816.13      3754202.34     10556277.05
#Sta/Elev= 30
  4482.3  248.45  4510.3  246.06  4527.4  243.17    4591   235.1  4654.4  235.28
  4667.3   233.5  4833.9     231  4939.4  230.82    4997  229.61  4999.8  229.11
    5003  229.61  5088.9  230.18  5236.8  230.85  5297.9  231.29  5303.9  232.98
  5320.2  231.03  5404.3  231.19  5678.6  235.05  5849.3   232.4  5918.1  233.21
  5975.4  235.56  5997.8  234.84  6029.8  237.21  6081.8  244.47  6126.6  249.11
  6171.4  252.53    6177  251.96  6230.8  256.32  6238.6  258.04    6245  256.95
#Mann= 6 ,-1 , 0
  4482.3     .05       0  4527.4     .16       0    4997     .07       0
    5003     .16       0  5088.9     .05       0  5849.3     .16       0
#XS Ineff= 2 , 0
                         5303.98          244.67
Permanent Ineff=
       F       F
Bank Sta=4939.4,5236.8
XS Rating Curve= 0 ,0
Exp/Cntr=0.3,0.1

Type RM Length L Ch R = 1 ,1681    ,0,0,0
BEGIN DESCRIPTION:
UNT 084 IN BOCR 1.0
END DESCRIPTION:
XS GIS Cut Line= 3
      3753249.61     10555160.19      3752949.61     10555760.19
      3753799.63     10556660.21
#Sta/Elev= 30
  4343.5  249.67  4365.9  246.42  4374.2   244.2  4381.5  243.85  4396.6  240.54
  4410.6  239.42  4446.9  233.67  4455.3  234.96  4463.7   234.9  4656.6  230.48
  4924.9  228.58    4997  227.13  4999.8  226.63    5003  227.13  5028.3  228.13
  5035.6  227.29  5088.2  227.96  5297.3  228.18  5318.3  228.98  5396.4  228.61
  5523.9  230.17  5537.6  231.11  5650.9   229.3  5743.1  230.56    5771  229.54
  5792.5  230.53  5870.2   229.1  5919.9  230.66  6040.1  231.26  6252.3  236.18
#Mann= 6 ,-1 , 0
  4343.5     .05       0  4381.5     .16       0    4997     .07       0
    5003     .16       0  5088.2      .1       0  5523.9     .12       0
#XS Ineff= 2 , 0
                         5545.45          231.38
Permanent Ineff=
       F       F
Bank Sta=4924.9,5318.3
XS Rating Curve= 0 ,0
Exp/Cntr=0.3,0.1

Chan Stop Cuts=-1
Use User Specified Reach Order=0
Composite Channel Slope=5