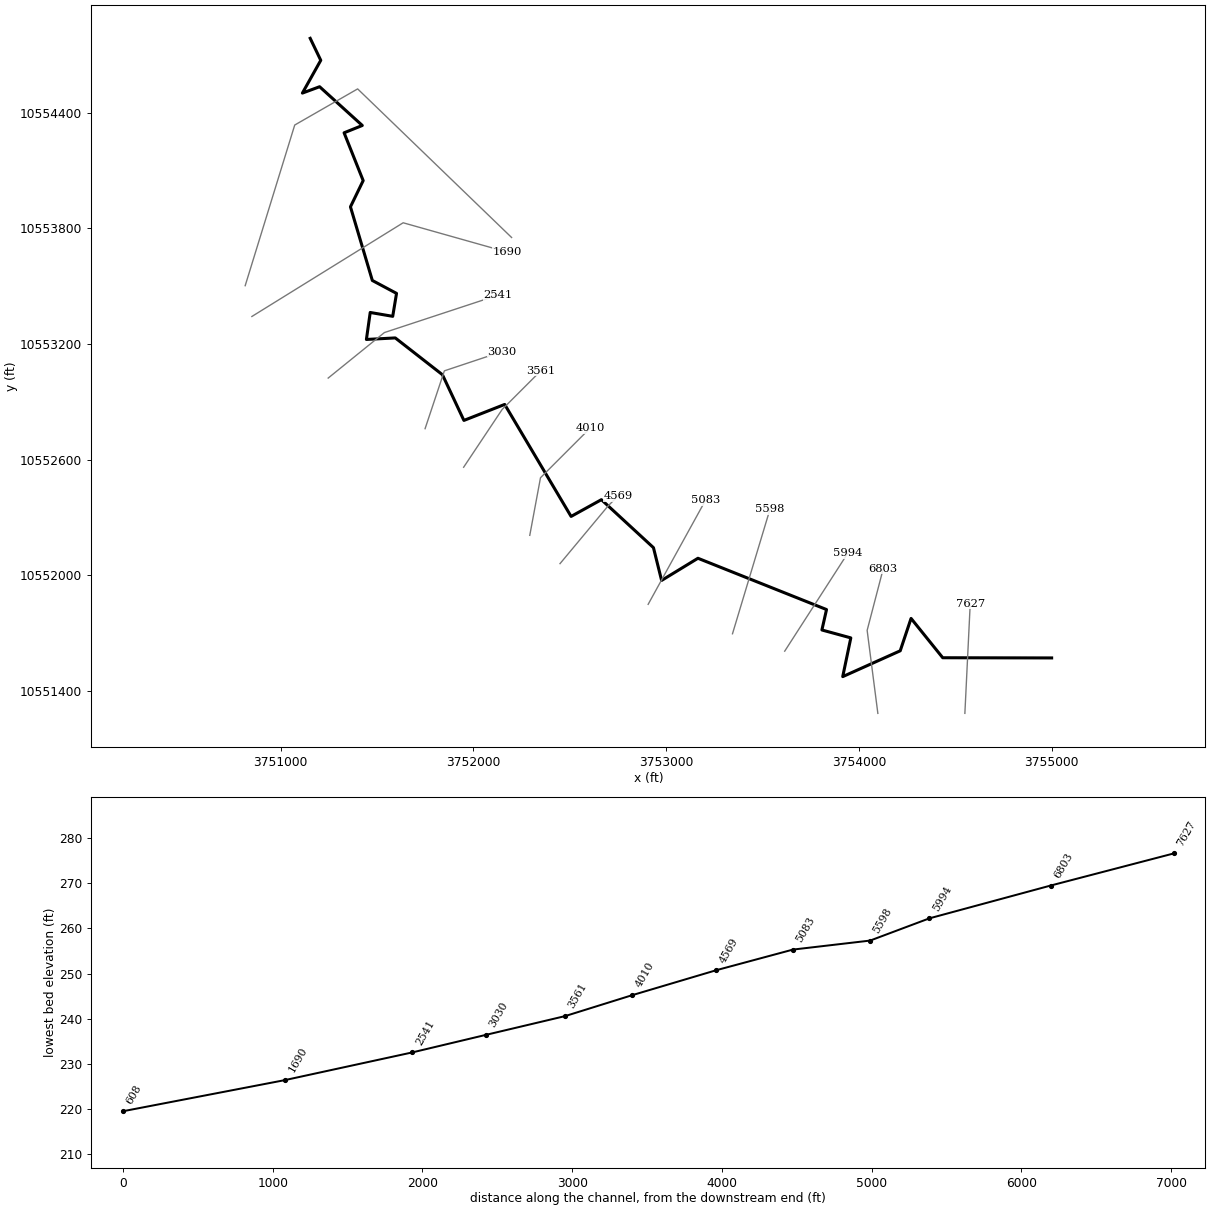
--- UNT 085 IN BOCR.prj (project) ---

Proj Title=UNT 085 IN BOCR Base Level Engineering
Current Plan=p01
Default Exp/Contr=0.3,0.1
English Units
Geom File=g01
Flow File=f01
Plan File=p01
BEGIN DESCRIPTION:
UNT 085 IN BOCR
END DESCRIPTION:

--- UNT 085 IN BOCR.p01 (plan) ---

Plan Title=Multiple Run
Short Identifier=Multiple
Geom File=g01
Flow File=f01
Subcritical Flow
K Sum by GR= 0
Std Step Tol= 0.01
Critical Tol= 0.01
Num of Std Step Trials= 20
Max Error Tol= 0.3
Flow Tol Ratio= 0.001
Split Flow NTrial= 30
Split Flow Tol= 0.02
Split Flow Ratio= 0.02
Log Output Level= 0
Friction Slope Method= 1
Unsteady Friction Slope Method= 2
Unsteady Bridges Friction Slope Method= 1
Parabolic Critical Depth
Global Vel Dist=  1 , 1 , 1
Global Log Level= 0
CheckData=True
Encroach Param= -1, 0, 0, 0
BEGIN DESCRIPTION:
Multiple Run
END DESCRIPTION:

--- UNT 085 IN BOCR.f01 (steady flow) ---

Flow Title=Multiple
Number of Profiles=7
Profile Names=10-year,25-year,50-year,1pct_min,100-year,1pct_plu,500-year
River Rch & RM= UNT 085 IN BOCR,Reach-1,7627
     551     749     914     821    1111    1502    1645
Boundary for River Rch & Prof#=UNT 085 IN BOCR,Reach-1,1
Up Type=0
Dn Type=3
Dn Slope=0.005
Boundary for River Rch & Prof#=UNT 085 IN BOCR,Reach-1,2
Up Type=0
Dn Type=3
Dn Slope=0.005
Boundary for River Rch & Prof#=UNT 085 IN BOCR,Reach-1,3
Up Type=0
Dn Type=3
Dn Slope=0.005
Boundary for River Rch & Prof#=UNT 085 IN BOCR,Reach-1,4
Up Type=0
Dn Type=3
Dn Slope=0.005
Boundary for River Rch & Prof#=UNT 085 IN BOCR,Reach-1,5
Up Type=0
Dn Type=3
Dn Slope=0.005
Boundary for River Rch & Prof#=UNT 085 IN BOCR,Reach-1,6
Up Type=0
Dn Type=3
Dn Slope=0.005
Boundary for River Rch & Prof#=UNT 085 IN BOCR,Reach-1,7
Up Type=0
Dn Type=3
Dn Slope=0.005

--- UNT 085 IN BOCR.g01 (geometry) ---

Geom Title=Existing Conditions

River Reach=UNT 085 IN BOCR,Reach-1
Reach XY= 30
      3754999.75     10551571.00      3754434.75     10551572.00
      3754270.50     10551776.00      3754214.25     10551608.00
      3753916.00     10551474.00      3753958.00     10551675.00
      3753808.00     10551716.00      3753832.00     10551822.00
      3753165.00     10552088.00      3752976.50     10551973.00
      3752934.25     10552143.00      3752664.25     10552392.00
      3752507.00     10552305.00      3752162.50     10552886.00
      3751951.00     10552803.00      3751839.75     10553040.00
      3751595.00     10553231.00      3751445.25     10553223.00
      3751465.00     10553363.00      3751581.75     10553343.00
      3751601.50     10553462.00      3751476.00     10553529.00
      3751362.50     10553911.00      3751428.50     10554047.00
      3751329.50     10554295.00      3751424.00     10554333.00
      3751202.50     10554534.00      3751113.25     10554501.00
      3751208.50     10554671.00      3751153.75     10554785.00

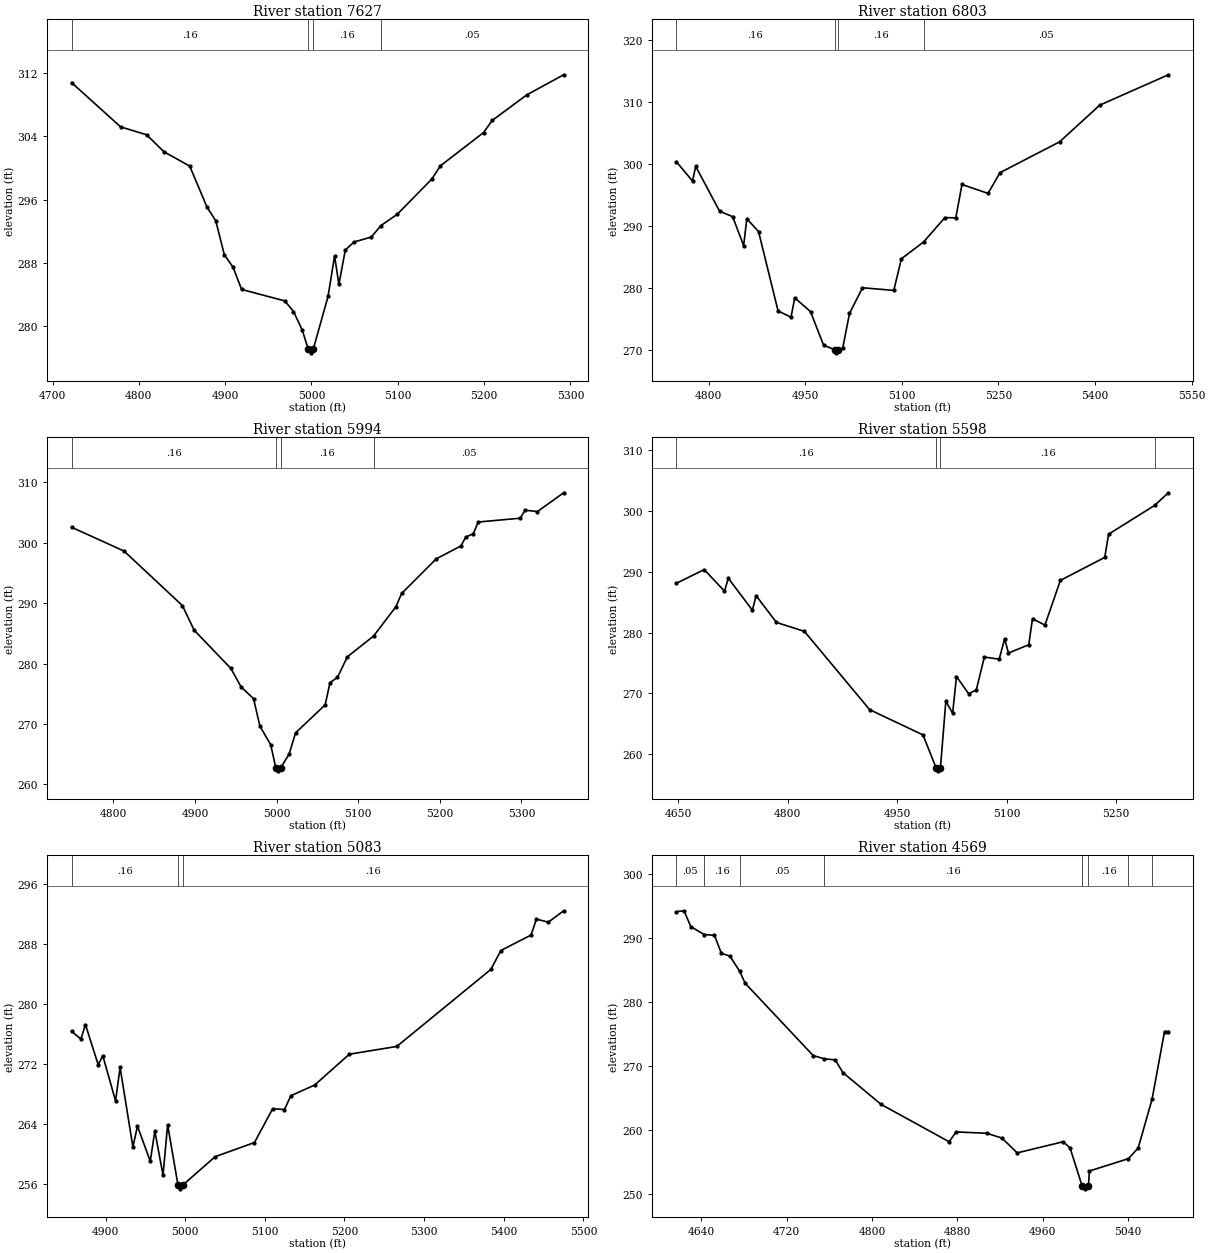
Type RM Length L Ch R = 1,7627,824,824,824
BEGIN DESCRIPTION:
UNT 085 IN BOCR 13.0
END DESCRIPTION:
XS GIS Cut Line= 2
      3754549.64     10551283.43      3754577.42     10551852.85
#Sta/Elev= 30
  4722.1  310.79  4778.9  305.19  4809.0  304.19  4829.0  302.05  4859.0  300.22
  4879.0  295.04  4889.1  293.31  4899.1  289.00  4909.1  287.45  4919.1  284.62
  4969.2  283.17  4979.2  281.83  4989.2  279.52  4996.2  277.10  4998.9  276.60
  5002.2  277.10  5019.2  283.73  5026.8  288.86  5031.8  285.26  5039.2  289.60
  5049.2  290.62  5069.3  291.25  5080.6  292.71  5099.3  294.12  5139.4  298.58
  5149.4  300.26  5199.4  304.47  5209.4  306.00  5249.5  309.24  5292.2  311.78
#Mann=4,-1,0
  4722.1    0.16       0  4996.2    0.07       0  5002.2    0.16       0
  5080.6    0.05       0
Bank Sta=4996.2,5002.2
Exp/Cntr=0.3,0.1

Type RM Length L Ch R = 1,6803,809,809,809
BEGIN DESCRIPTION:
UNT 085 IN BOCR 12.0
END DESCRIPTION:
XS GIS Cut Line= 3
      3754098.25     10551283.42      3754042.70     10551713.95
      3754126.02     10552033.36
#Sta/Elev= 30
  4749.6  300.38  4774.8  297.25  4779.8  299.61  4816.9  292.37  4837.1  291.49
  4854.2  286.82  4859.2  291.15  4877.4  289.07  4907.7  276.25  4927.8  275.24
  4933.6  278.37  4958.1  276.14  4978.3  270.73  4995.4  269.98  4998.2  269.48
  5001.4  269.98  5008.0  270.19  5018.6  275.84  5038.8  280.00  5087.4  279.57
  5099.2  284.68  5133.8  287.41  5166.8  291.34  5183.7  291.29  5193.3  296.69
  5233.8  295.25  5252.2  298.59  5344.9  303.58  5407.2  309.51  5513.8  314.42
#Mann=4,-1,0
  4749.6    0.16       0  4995.4    0.07       0  5001.4    0.16       0
  5133.8    0.05       0
Bank Sta=4995.4,5001.4
Exp/Cntr=0.3,0.1

Type RM Length L Ch R = 1,5994,396,396,396
BEGIN DESCRIPTION:
Mapping XS 5fbf2d97
END DESCRIPTION:
XS GIS Cut Line= 2
      3753615.07     10551606.09      3753941.45     10552113.01
#Sta/Elev= 30
  4748.9  302.56  4813.2  298.62  4884.6  289.60  4899.1  285.51  4944.1  279.18
  4956.6  276.12  4971.8  274.19  4979.7  269.61  4992.9  266.55  4999.1  262.73
  5001.9  262.23  5005.1  262.73  5015.4  264.99  5023.3  268.51  5059.6  273.16
  5065.5  276.83  5074.7  277.72  5086.8  281.11  5119.0  284.56  5146.3  289.41
  5153.3  291.60  5195.6  297.32  5225.9  299.47  5231.9  300.94  5241.1  301.49
  5247.1  303.43  5298.6  304.06  5304.5  305.39  5319.7  305.16  5351.8  308.27
#Mann=4,-1,0
  4748.9    0.16       0  4999.1    0.07       0  5005.1    0.16       0
  5119.0    0.05       0
Bank Sta=4999.1,5005.1
Exp/Cntr=0.3,0.1

Type RM Length L Ch R = 1,5598,515,515,515
BEGIN DESCRIPTION:
Mapping XS 0ae7bd39
END DESCRIPTION:
XS GIS Cut Line= 2
      3753344.22     10551696.34      3753538.67     10552342.20
#Sta/Elev= 30
  4647.3  288.06  4685.6  290.32  4713.4  286.78  4718.6  288.90  4751.6  283.67
  4756.8  286.04  4784.6  281.65  4822.9  280.19  4912.4  267.34  4985.5  263.20
  5003.4  257.81  5006.1  257.31  5009.4  257.81  5016.8  268.74  5026.1  266.76
  5031.4  272.78  5048.2  269.93  5058.6  270.61  5069.6  275.98  5089.9  275.62
  5097.4  278.97  5102.6  276.63  5130.4  277.99  5135.6  282.28  5152.6  281.21
  5173.8  288.55  5234.6  292.32  5239.9  296.13  5303.0  300.85  5321.8  302.92
#Mann=4,-1,0
  4647.3    0.16       0  5003.4    0.07       0  5009.4    0.16       0
  5303.0    0.05       0
Bank Sta=5003.4,5009.4
Exp/Cntr=0.3,0.1

Type RM Length L Ch R = 1,5083,514,514,514
BEGIN DESCRIPTION:
Mapping XS be07305c
END DESCRIPTION:
XS GIS Cut Line= 2
      3752906.70     10551849.08      3753204.96     10552390.12
#Sta/Elev= 30
  4857.4  276.36  4869.1  275.31  4874.8  277.25  4890.8  271.89  4896.6  273.09
  4912.6  267.06  4918.3  271.52  4934.4  260.90  4940.1  263.69  4956.2  259.00
  4961.9  263.04  4972.2  257.15  4978.0  263.87  4991.0  255.82  4993.8  255.32
  4997.0  255.82  5037.6  259.61  5087.0  261.50  5109.9  266.02  5124.7  265.91
  5132.7  267.75  5162.5  269.17  5206.1  273.29  5265.7  274.33  5383.9  284.62
  5396.3  287.13  5434.2  289.20  5441.0  291.32  5456.0  290.92  5475.2  292.44
#Mann=3,-1,0
  4857.4    0.16       0  4991.0    0.07       0  4997.0    0.16       0
Bank Sta=4991,4997
Exp/Cntr=0.3,0.1

Type RM Length L Ch R = 1,4569,559,559,559
BEGIN DESCRIPTION:
UNT 085 IN BOCR 7.0
END DESCRIPTION:
XS GIS Cut Line= 3
      3752449.58     10552060.16      3752699.61     10552360.19
      3752749.63     10552410.21
#Sta/Elev= 30
  4616.4  294.13  4623.6  294.27  4630.1  291.78  4642.6  290.55  4652.2  290.43
  4658.7  287.60  4666.6  287.19  4675.9  284.78  4680.9  282.94  4744.7  271.61
  4754.9  271.11  4765.5  270.92  4772.6  268.94  4808.4  263.96  4872.2  258.11
  4878.7  259.65  4907.4  259.44  4921.7  258.69  4936.0  256.37  4979.0  258.11
  4985.5  257.17  4996.8  251.24  4999.5  250.74  5002.8  251.24  5003.7  253.53
  5040.3  255.47  5049.4  257.13  5062.4  264.75  5074.1  275.36  5077.7  275.36
#Mann=8,-1,0
  4616.4    0.05       0  4642.6    0.16       0  4675.9    0.05       0
  4754.9    0.16       0  4996.8    0.07       0  5002.8    0.16       0
  5040.3    0.12       0  5062.4    0.16       0
Bank Sta=4996.8,5002.8
Exp/Cntr=0.3,0.1

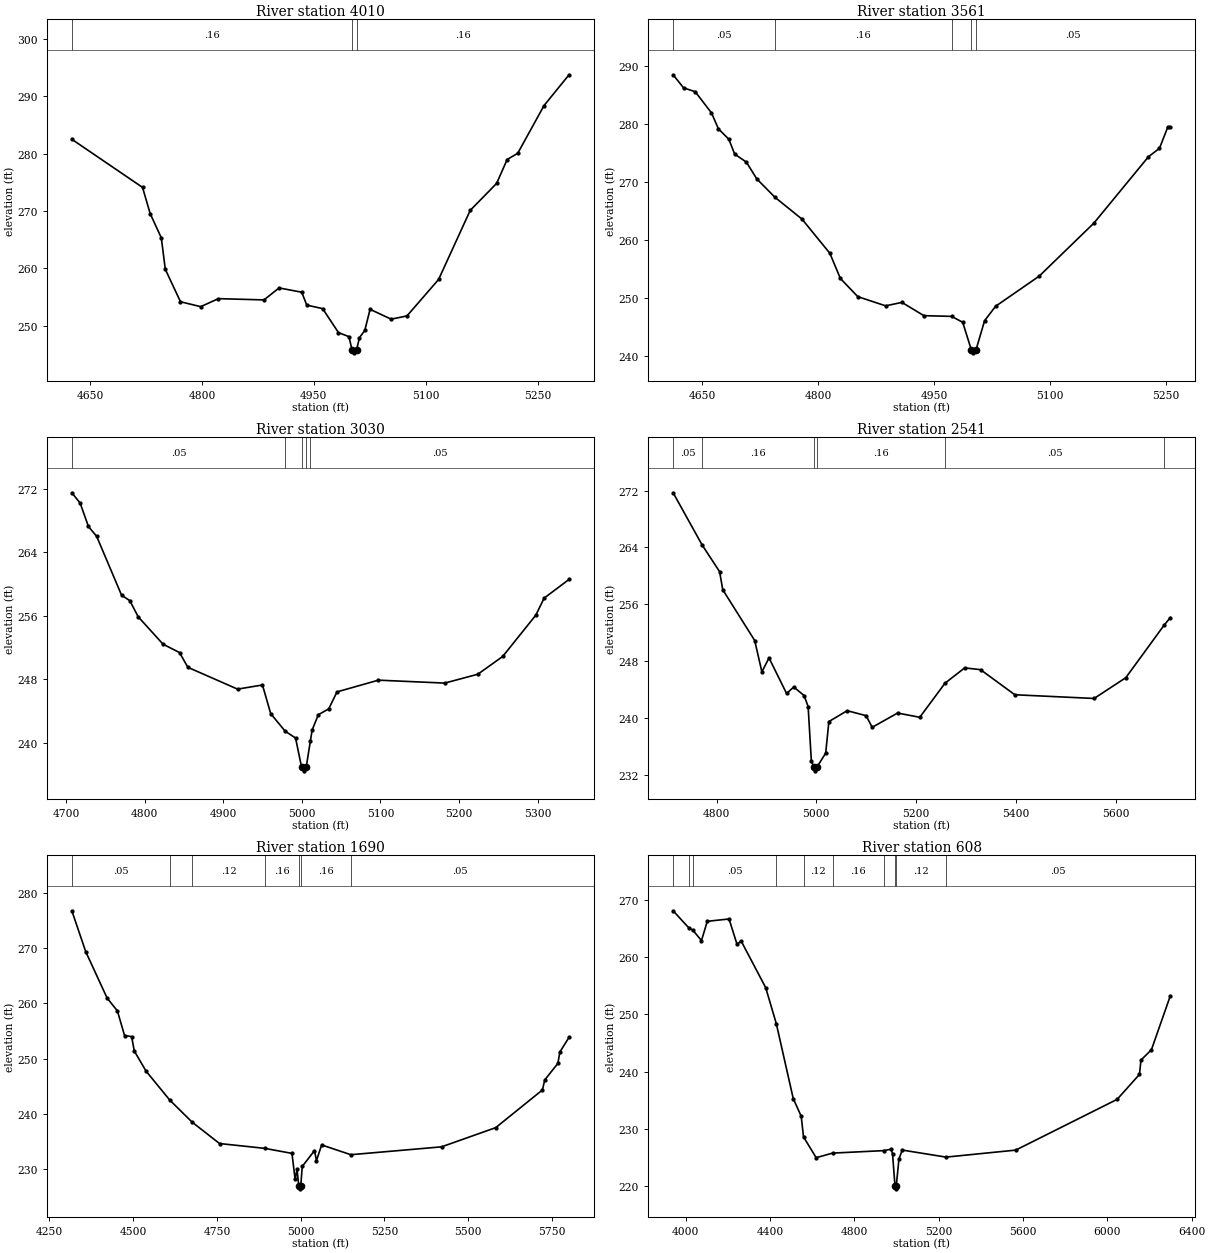
Type RM Length L Ch R = 1,4010,449,449,449
BEGIN DESCRIPTION:
UNT 085 IN BOCR 6.0
END DESCRIPTION:
XS GIS Cut Line= 3
      3752292.69     10552206.97      3752348.25     10552505.61
      3752604.88     10552762.24
#Sta/Elev= 30
  4625.6  282.48  4720.4  274.09  4730.6  269.53  4745.6  265.28  4750.9  259.81
  4771.3  254.15  4798.4  253.29  4822.1  254.69  4883.2  254.47  4903.5  256.56
  4933.9  255.81  4940.6  253.56  4961.9  252.95  4983.1  248.77  4997.2  248.06
  5001.3  245.74  5004.0  245.24  5007.3  245.74  5011.3  247.89  5018.4  249.14
  5025.5  252.83  5053.8  251.11  5075.0  251.68  5117.4  258.04  5159.8  270.09
  5195.2  274.79  5209.3  278.95  5223.5  280.04  5258.8  288.37  5292.3  293.73
#Mann=3,-1,0
  4625.6    0.16       0  5001.3    0.07       0  5007.3    0.16       0
Bank Sta=5001.3,5007.3
Exp/Cntr=0.3,0.1

Type RM Length L Ch R = 1,3561,531,531,531
BEGIN DESCRIPTION:
UNT 085 IN BOCR 5.0
END DESCRIPTION:
XS GIS Cut Line= 3
      3751949.59     10552560.17      3752149.61     10552860.19
      3752349.59     10553060.17
#Sta/Elev= 30
  4612.5  288.48  4626.0  286.23  4641.1  285.56  4662.1  281.92  4671.1  279.17
  4684.6  277.38  4692.1  274.82  4707.2  273.45  4720.7  270.56  4744.3  267.38
  4779.3  263.62  4815.3  257.74  4828.9  253.41  4851.4  250.28  4887.5  248.69
  4908.5  249.29  4937.0  247.00  4972.9  246.88  4987.2  245.86  4998.4  241.10
  5001.1  240.60  5004.4  241.10  5015.5  246.13  5029.7  248.61  5086.2  253.81
  5156.9  262.93  5227.6  274.37  5241.8  275.81  5252.4  279.41  5255.9  279.41
#Mann=5,-1,0
  4612.5    0.05       0  4744.3    0.16       0  4972.9    0.05       0
  4998.4    0.03       0  5004.4    0.05       0
Bank Sta=4998.4,5004.4
Exp/Cntr=0.3,0.1

Type RM Length L Ch R = 1,3030,489,489,489
BEGIN DESCRIPTION:
UNT 085 IN BOCR 4.0
END DESCRIPTION:
XS GIS Cut Line= 3
      3751749.61     10552760.18      3751849.61     10553060.19
      3752149.64     10553160.20
#Sta/Elev= 30
  4707.5  271.51  4718.0  270.22  4728.6  267.26  4739.1  266.01  4770.8  258.58
  4781.3  257.90  4791.8  255.88  4823.5  252.41  4844.5  251.35  4855.1  249.49
  4918.3  246.74  4950.0  247.26  4960.5  243.64  4978.9  241.43  4992.1  240.57
  4999.7  236.93  5002.4  236.43  5005.7  236.93  5010.9  240.16  5013.2  241.59
  5021.1  243.51  5034.3  244.25  5044.8  246.39  5097.5  247.87  5181.9  247.50
  5224.0  248.62  5255.6  250.86  5297.8  256.08  5308.3  258.22  5340.0  260.58
#Mann=5,-1,0
  4707.5    0.05       0  4978.9    0.16       0  4999.7    0.07       0
  5005.7    0.16       0  5010.9    0.05       0
Bank Sta=4999.7,5005.7
Exp/Cntr=0.3,0.1

Type RM Length L Ch R = 1,2541,851,851,851
BEGIN DESCRIPTION:
Mapping XS 11a86013
END DESCRIPTION:
XS GIS Cut Line= 3
      3751247.02     10553022.75      3751538.67     10553258.84
      3752128.93     10553453.28
#Sta/Elev= 30
  4713.0  271.68  4771.1  264.34  4806.1  260.59  4812.5  258.04  4876.5  250.90
  4890.9  246.49  4905.2  248.45  4940.4  243.45  4954.8  244.36  4975.6  243.15
  4983.6  241.61  4990.0  234.01  4995.0  233.07  4997.7  232.57  5001.0  233.07
  5018.8  235.06  5025.2  239.50  5061.9  241.03  5099.8  240.33  5112.0  238.69
  5162.9  240.70  5207.4  240.10  5257.9  244.89  5297.4  247.05  5329.2  246.80
  5398.0  243.27  5556.9  242.75  5620.4  245.67  5696.8  253.02  5709.7  254.13
#Mann=6,-1,0
  4713.0    0.05       0  4771.1    0.16       0  4995.0    0.07       0
  5001.0    0.16       0  5257.9    0.05       0  5696.8    0.16       0
Bank Sta=4995,5001
Exp/Cntr=0.3,0.1

Type RM Length L Ch R = 1,1690,1082,1082,1082
BEGIN DESCRIPTION:
Mapping XS 70fa7bcc
END DESCRIPTION:
XS GIS Cut Line= 3
      3750851.18     10553342.18      3751635.89     10553828.29
      3752176.04     10553675.94
#Sta/Elev= 30
  4317.0  276.71  4358.5  269.31  4422.3  260.93  4453.0  258.61  4474.3  254.16
  4495.5  253.96  4503.4  251.36  4538.7  247.71  4609.1  242.50  4676.1  238.50
  4757.9  234.63  4892.9  233.76  4974.1  232.85  4983.6  228.14  4989.4  229.96
  4994.4  226.94  4997.2  226.44  5000.4  226.94  5004.8  230.49  5041.4  233.35
  5047.3  231.54  5062.7  234.38  5149.8  232.61  5420.6  234.03  5582.3  237.50
  5721.9  244.32  5728.7  246.13  5767.9  249.11  5773.8  251.17  5801.3  253.83
#Mann=7,-1,0
  4317.0    0.05       0  4609.1    0.16       0  4676.1    0.12       0
  4892.9    0.16       0  4994.4    0.07       0  5000.4    0.16       0
  5149.8    0.05       0
Bank Sta=4994.4,5000.4
Exp/Cntr=0.3,0.1

Type RM Length L Ch R = 1,608,0,0,0
BEGIN DESCRIPTION:
UNT 085 IN BOCR 1.0
END DESCRIPTION:
XS GIS Cut Line= 4
      3750816.45     10553501.91      3751073.39     10554335.23
      3751399.78     10554522.73      3752198.40     10553751.89
#Sta/Elev= 30
  3940.2  268.10  4017.1  265.01  4032.3  264.77  4074.7  262.90  4102.1  266.26
  4205.4  266.67  4243.3  262.24  4262.8  262.82  4379.2  254.68  4429.7  248.37
  4509.8  235.32  4547.7  232.22  4558.6  228.62  4618.6  224.99  4696.5  225.79
  4938.1  226.22  4973.9  226.47  4980.9  225.67  4992.5  220.05  4995.2  219.55
  4998.5  220.05  5011.3  224.76  5027.0  226.32  5234.5  225.09  5565.1  226.31
  6046.1  235.17  6152.1  239.53  6159.3  242.04  6208.7  243.82  6298.6  253.26
#Mann=10,-1,0
  3940.2    0.05       0  4017.1    0.16       0  4032.3    0.05       0
  4429.7    0.16       0  4558.6    0.12       0  4696.5    0.16       0
  4938.1    0.12       0  4992.5    0.07       0  4998.5    0.12       0
  5234.5    0.05       0
Bank Sta=4992.5,4998.5
Exp/Cntr=0.3,0.1

Chan Stop Cuts=-1