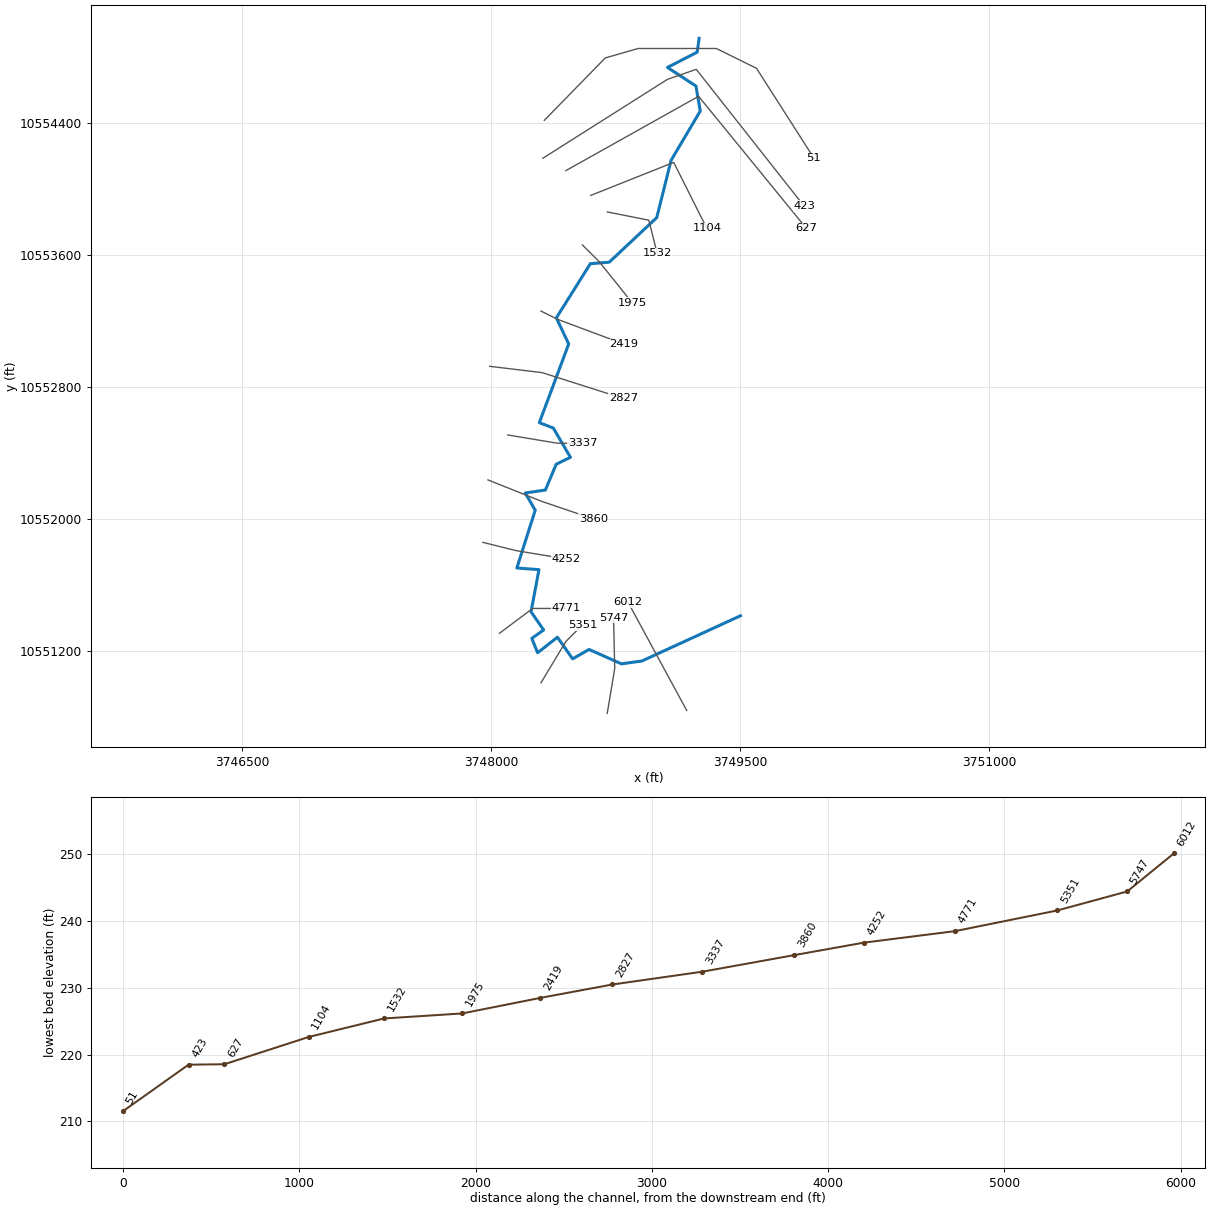
--- UNT 086 IN BOCR.prj (project) ---

Proj Title=UNT 086 IN BOCR Base Level Engineering
Current Plan=p01
Default Exp/Contr=0.3,0.1
English Units
Geom File=g01
Flow File=f01
Plan File=p01
Y Axis Title=Elevation
X Axis Title(PF)=Main Channel Distance
X Axis Title(XS)=Station
BEGIN DESCRIPTION:
UNT 086 IN BOCR
END DESCRIPTION:
DSS Export Rating Curves= 0
DSS Export Rating Curve Sorted= 0
DSS Export Volume Flow Curves= 0
DXF OffsetX= 0
DXF OffsetY= 0
DXF ScaleX= 1
DXF ScaleY= 10

--- UNT 086 IN BOCR.p01 (plan) ---

Plan Title=Multiple Run
Short Identifier=Multiple
Geom File=g01
Flow File=f01
Subcritical Flow
K Sum by GR= 0
Std Step Tol= 0.01
Critical Tol= 0.01
Num of Std Step Trials= 20
Max Error Tol= 0.3
Flow Tol Ratio= 0.001
Split Flow NTrial= 30
Split Flow Tol= 0.02
Split Flow Ratio= 0.02
Log Output Level= 0
Friction Slope Method= 1
Unsteady Friction Slope Method= 2
Unsteady Bridges Friction Slope Method= 1
Parabolic Critical Depth
Global Vel Dist=  1 , 1 , 1
Global Log Level= 0
CheckData=True
Encroach Param= -1, 0, 0, 0
BEGIN DESCRIPTION:
Multiple Run
END DESCRIPTION:

--- UNT 086 IN BOCR.f01 (steady flow) ---

Flow Title=Multiple
Program Version=4.10
Number of Profiles= 7
Profile Names=10-year,25-year,50-year,1pct_min,100-year,1pct_plu,500-year
River Rch & RM=UNT 086 IN BOCR,Reach-1         ,6012
     636     866    1057     949    1283    1736    1898
Boundary for River Rch & Prof#=UNT 086 IN BOCR,Reach-1         , 1
Up Type= 0
Dn Type= 3
Dn Slope=0.006
Boundary for River Rch & Prof#=UNT 086 IN BOCR,Reach-1         , 2
Up Type= 0
Dn Type= 3
Dn Slope=0.006
Boundary for River Rch & Prof#=UNT 086 IN BOCR,Reach-1         , 3
Up Type= 0
Dn Type= 3
Dn Slope=0.006
Boundary for River Rch & Prof#=UNT 086 IN BOCR,Reach-1         , 4
Up Type= 0
Dn Type= 3
Dn Slope=0.006
Boundary for River Rch & Prof#=UNT 086 IN BOCR,Reach-1         , 5
Up Type= 0
Dn Type= 3
Dn Slope=0.006
Boundary for River Rch & Prof#=UNT 086 IN BOCR,Reach-1         , 6
Up Type= 0
Dn Type= 3
Dn Slope=0.006
Boundary for River Rch & Prof#=UNT 086 IN BOCR,Reach-1         , 7
Up Type= 0
Dn Type= 3
Dn Slope=0.006
DSS Import GetInterval= 0
DSS Import GetPeak= 0
DSS Import FillOption= 0

--- UNT 086 IN BOCR.g01 (geometry) ---

Geom Title=Existing Conditions
Program Version=4.10

River Reach=UNT 086 IN BOCR ,Reach-1
Reach XY= 30
      3749502.25       10551416.      3748907.75       10551142.
       3748784.5       10551125.      3748589.25       10551212.
       3748490.5       10551155.      3748398.75       10551286.
      3748279.25       10551192.      3748244.25       10551279.
      3748315.75       10551330.      3748239.75       10551440.
       3748287.5       10551695.      3748154.25       10551705.
        3748265.       10552055.       3748204.5       10552159.
      3748326.25       10552177.      3748391.25       10552333.
      3748477.25       10552375.        3748374.       10552552.
      3748289.75       10552585.      3748466.75       10553061.
      3748392.25       10553219.      3748597.25       10553547.
        3748711.       10553556.       3748997.5       10553826.
        3749084.       10554173.      3749259.75       10554471.
      3749233.75       10554622.        3749062.       10554735.
        3749241.       10554827.      3749252.75       10554911.

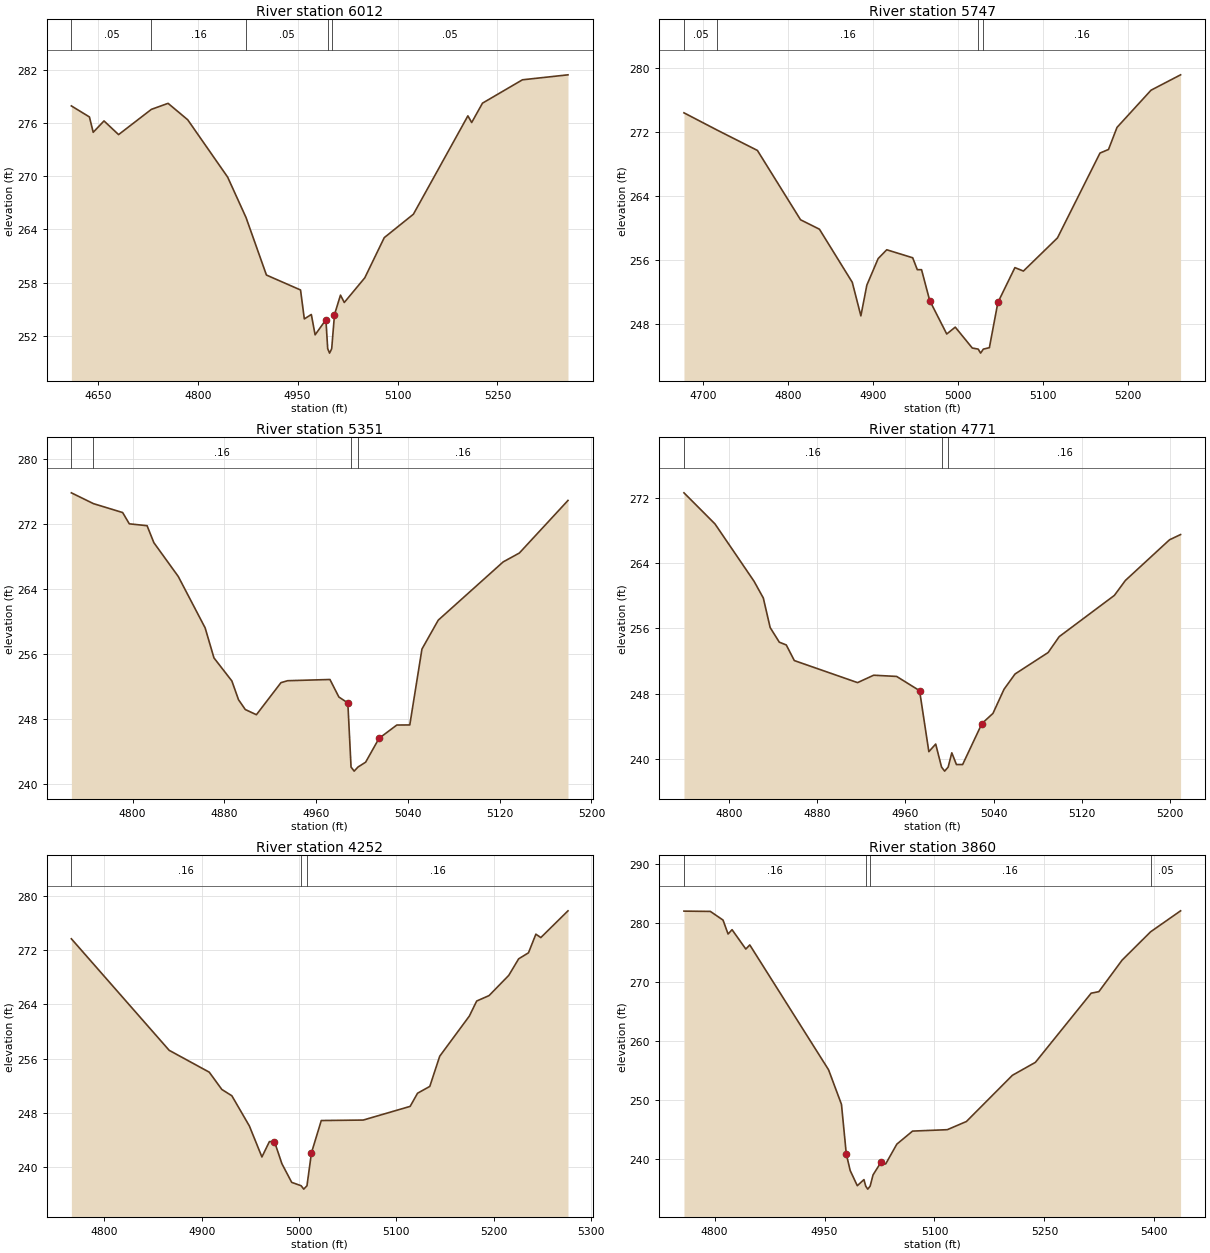
Type RM Length L Ch R = 1 ,6012    ,265,265,265
BEGIN DESCRIPTION:
Mapping XS e13a888c
END DESCRIPTION:
XS GIS Cut Line= 2
      3749178.09     10550842.45      3748823.94     10551498.68
#Sta/Elev= 30
  4610.3  277.91  4637.4  276.67  4643.1  274.94  4659.3  276.22  4681.2  274.68
  4730.4  277.52  4755.5   278.2    4785  276.35    4845  269.89  4872.6  265.34
  4903.2  258.87  4954.4  257.19  4960.1  253.93  4970.6  254.43  4976.3  252.14
  4992.5  253.84  4995.2  250.58    4998  250.08  5001.2  250.58  5005.4  254.42
  5014.4  256.61  5020.1  255.78  5050.9  258.56  5080.1  263.08  5123.9  265.72
  5205.7  276.79  5211.4  276.04  5227.6  278.22  5287.6  280.85    5356  281.41
#Mann= 5 ,-1 , 0
  4610.3     .05       0  4730.4     .16       0  4872.6     .05       0
  4995.2     .03       0  5001.2     .05       0
Bank Sta=4992.5,5005.4
XS Rating Curve= 0 ,0
Exp/Cntr=0.3,0.1

Type RM Length L Ch R = 1 ,5747    ,396,396,396
BEGIN DESCRIPTION:
UNT 086 IN BOCR 12.0
END DESCRIPTION:
XS GIS Cut Line= 3
      3748698.95     10550825.09      3748744.08     10551095.89
      3748737.14     10551404.88
#Sta/Elev= 30
  4677.8  274.43  4717.2  272.25  4764.1  269.73  4814.8  261.06    4837  259.88
  4875.6  253.24  4885.7  249.05  4892.7  252.89    4906  256.21  4916.1  257.31
  4946.6  256.31    4952  254.82    4957  254.82  4966.6  250.96  4986.6  246.78
  4996.6  247.64  5016.6  245.03  5023.6  244.89  5026.4  244.39  5029.6  244.89
  5036.7  245.07  5046.7  250.72  5066.7  255.08  5076.7  254.65  5116.7  258.79
  5166.7   269.4  5176.7  269.85  5186.7  272.61  5226.7  277.26  5261.4  279.18
#Mann= 4 ,-1 , 0
  4677.8     .05       0  4717.2     .16       0  5023.6     .07       0
  5029.6     .16       0
Bank Sta=4966.6,5046.7
XS Rating Curve= 0 ,0
Exp/Cntr=0.3,0.1

Type RM Length L Ch R = 1 ,5351    ,580,580,580
BEGIN DESCRIPTION:
UNT 086 IN BOCR 11.0
END DESCRIPTION:
XS GIS Cut Line= 3
      3748299.63     10551010.23      3748449.61     10551260.19
      3748549.59     10551360.17
#Sta/Elev= 30
  4746.7  275.84  4765.9  274.51  4791.4  273.41  4797.2  272.02  4812.7  271.79
  4818.6   269.7  4839.9  265.53  4863.3   259.2    4871   255.5  4886.6  252.66
  4892.4  250.35  4898.3  249.14    4908   248.5  4929.4  252.45  4935.2  252.69
  4972.1  252.84  4979.9  250.68  4987.7  249.95  4990.5  242.05  4993.2  241.55
  4996.5  242.05  5003.2  242.65  5014.9  245.59  5030.4  247.23  5041.7  247.24
  5052.3  256.59  5066.5  260.15  5123.1  267.33  5137.2  268.42  5179.6   274.9
#Mann= 4 ,-1 , 0
  4746.7     .05       0  4765.9     .16       0  4990.5     .07       0
  4996.5     .16       0
Bank Sta=4987.7,5014.9
XS Rating Curve= 0 ,0
Exp/Cntr=0.3,0.1

Type RM Length L Ch R = 1 ,4771    ,519,519,519
BEGIN DESCRIPTION:
UNT 086 IN BOCR 10.0
END DESCRIPTION:
XS GIS Cut Line= 3
      3748049.63      10551310.2      3748249.61     10551460.19
      3748449.63     10551460.19
#Sta/Elev= 30
  4759.3  272.67  4787.4  268.85  4822.8   261.8  4831.2  259.74  4837.4  256.11
  4845.7  254.31    4852  253.97  4859.3  252.05  4916.6  249.34  4931.2  250.25
    4952   250.1  4972.8  248.35  4981.2  240.85  4987.4  241.79  4992.7  238.96
  4995.5  238.46  4998.7  238.96    5002  240.71  5006.2  239.27  5011.8  239.27
  5029.3  244.31  5039.3  245.56  5049.3  248.52  5059.3   250.4  5089.3  253.04
  5099.3  254.99  5149.3  260.06  5159.3   261.9  5199.3   266.9  5209.3  267.54
#Mann= 3 ,-1 , 0
  4759.3     .16       0  4992.7     .07       0  4998.7     .16       0
Bank Sta=4972.8,5029.3
XS Rating Curve= 0 ,0
Exp/Cntr=0.3,0.1

Type RM Length L Ch R = 1 ,4252    ,392,392,392
BEGIN DESCRIPTION:
UNT 086 IN BOCR 9.0
END DESCRIPTION:
XS GIS Cut Line= 3
      3747949.64     10551860.18      3748149.61     10551810.19
      3748449.65     10551760.18
#Sta/Elev= 30
  4766.1   273.7  4866.6  257.23  4907.8     254  4920.7  251.45    4931  250.52
    4949  246.06  4961.9  241.48  4969.6  243.75  4974.8  243.75  4982.4  240.49
  4992.5  237.73  5002.2  237.23  5004.9  236.73  5008.2  237.23  5012.8  242.09
  5022.9  246.86    5066  246.93  5114.2  248.95  5121.8  250.89  5134.4   251.9
  5144.6  256.36    5175  262.28  5182.6  264.51  5195.3  265.31  5215.5  268.29
  5225.7  270.74  5235.8  271.63  5243.4  274.38  5248.5  273.88  5276.4  277.83
#Mann= 3 ,-1 , 0
  4766.1     .16       0  5002.2     .07       0  5008.2     .16       0
Bank Sta=4974.8,5012.8
XS Rating Curve= 0 ,0
Exp/Cntr=0.3,0.1

Type RM Length L Ch R = 1 ,3860    ,523,523,523
BEGIN DESCRIPTION:
UNT 086 IN BOCR 8.0
END DESCRIPTION:
XS GIS Cut Line= 3
       3747980.2     10552238.25      3748299.64     10552109.78
      3748615.13      10552002.3
#Sta/Elev= 30
  4758.2  282.07  4794.2  282.02  4811.5  280.55  4818.4  278.18  4823.8  278.92
  4842.6  275.63    4848  276.33  4955.5  255.14  4973.1  249.27  4979.7  240.83
    4985  238.04  4994.7  235.46  5003.8   236.5  5006.2  235.38    5009  234.88
  5012.2  235.38  5016.2   237.3    5027  239.44  5033.4  239.15  5048.6  242.51
  5070.1  244.73  5117.5  244.97  5143.6  246.36  5206.3   254.2  5237.7   256.4
  5313.8  268.14  5324.3   268.4    5356  273.75  5394.9  278.56  5435.8  282.12
#Mann= 4 ,-1 , 0
  4758.2     .16       0  5006.2     .07       0  5012.2     .16       0
  5394.9     .05       0
Bank Sta=4979.7,5027
XS Rating Curve= 0 ,0
Exp/Cntr=0.3,0.1

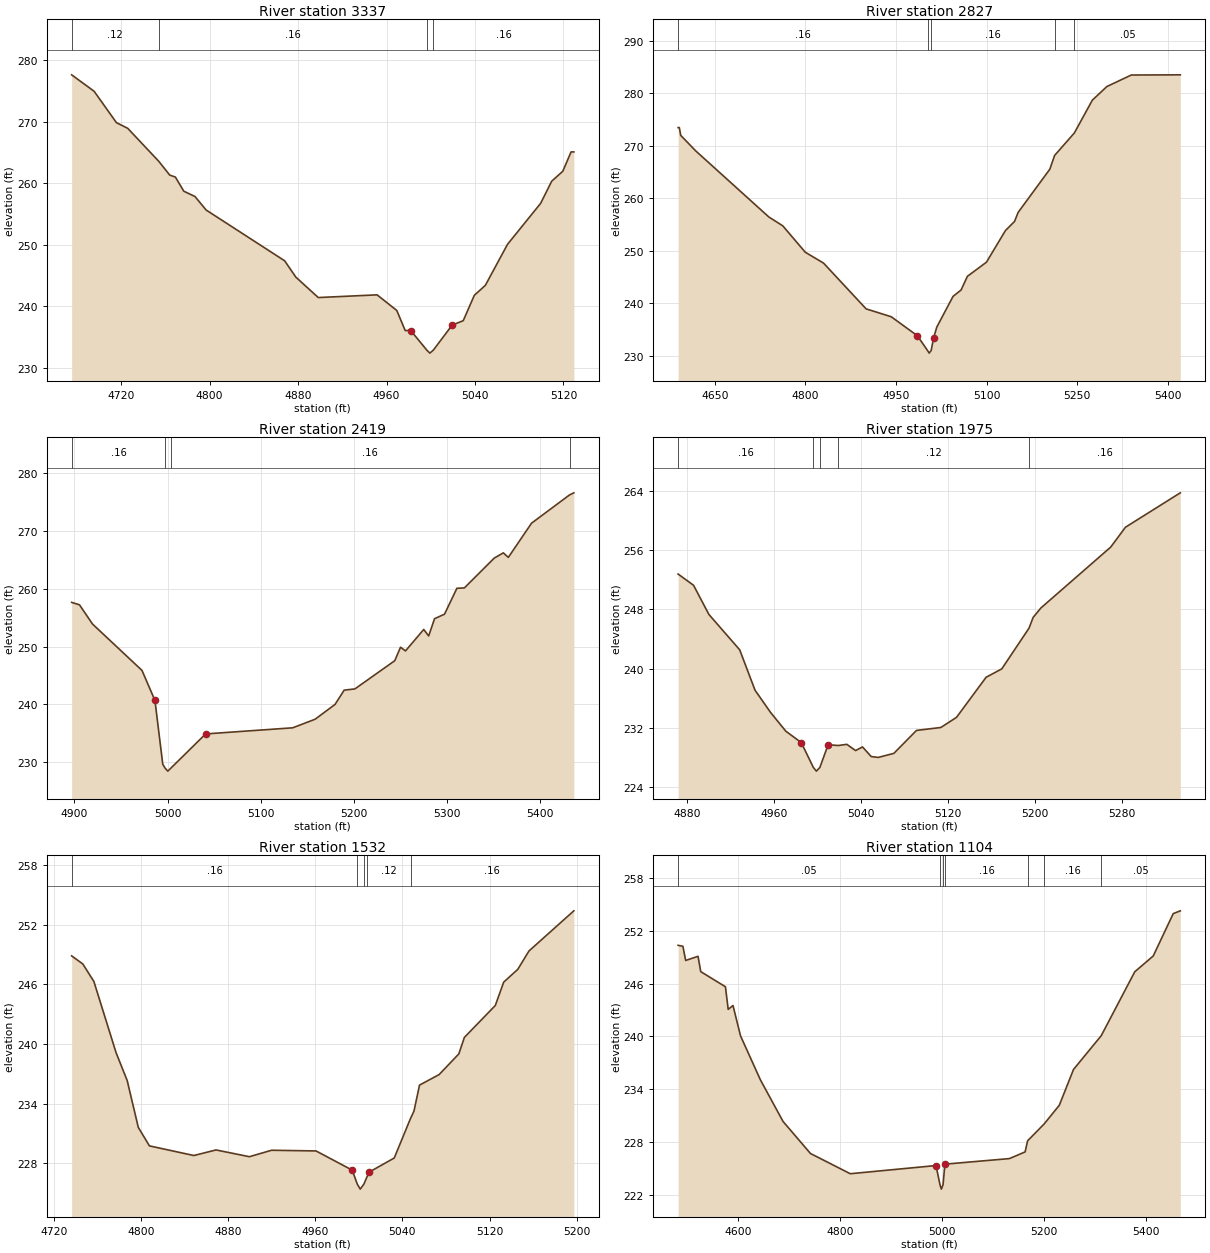
Type RM Length L Ch R = 1 ,3337    ,510,510,510
BEGIN DESCRIPTION:
UNT 086 IN BOCR 7.0
END DESCRIPTION:
XS GIS Cut Line= 3
      3748099.62     10552510.19      3748399.61     10552460.19
      3748549.58     10552460.19
#Sta/Elev= 30
  4675.3  277.66  4695.6  274.99  4715.8  269.88    4726  268.96  4754.2  263.57
    4764  261.35  4769.1  261.03  4776.7  258.73  4786.8  257.87  4796.9  255.67
  4867.9  247.41    4878  244.76  4898.3  241.43  4951.5  241.87  4969.3  239.33
  4976.9  236.07  4981.9  236.07  4996.4  232.89  4999.2  232.39  5002.4  232.89
  5019.4  236.95  5029.4  237.67  5039.4  241.79  5049.4  243.42  5069.4  250.08
  5099.4  256.76  5109.4  260.36  5119.4  261.97  5126.9  265.12  5129.4  265.12
#Mann= 4 ,-1 , 0
  4675.3     .12       0  4754.2     .16       0  4996.4     .07       0
  5002.4     .16       0
Bank Sta=4981.9,5019.4
XS Rating Curve= 0 ,0
Exp/Cntr=0.3,0.1

Type RM Length L Ch R = 1 ,2827    ,408,408,408
BEGIN DESCRIPTION:
UNT 086 IN BOCR 6.0
END DESCRIPTION:
XS GIS Cut Line= 3
      3747990.63     10552925.75      3748306.58     10552887.56
      3748795.35     10552731.57
#Sta/Elev= 30
  4589.4  273.49  4591.4  273.49  4593.7  272.01  4618.6  269.04  4739.5  256.45
  4762.7  254.75  4799.9  249.72  4830.1  247.65  4900.6  238.92  4942.3  237.41
  4985.4   233.8  5002.3  230.98    5005  230.48  5008.3  230.98  5012.3  233.37
  5017.6  235.44  5044.5   241.3  5057.8  242.51  5068.3  245.13  5099.8  247.82
  5131.3  253.86  5146.3  255.59  5152.3  257.32  5204.7  265.55  5212.6  268.17
  5245.3  272.46  5275.1  278.72  5299.2  281.32  5339.5  283.51  5420.7  283.55
#Mann= 5 ,-1 , 0
  4589.4     .16       0  5002.3     .07       0  5008.3     .16       0
  5212.6      .1       0  5245.3     .05       0
Bank Sta=4985.4,5012.3
XS Rating Curve= 0 ,0
Exp/Cntr=0.3,0.1

Type RM Length L Ch R = 1 ,2419    ,444,444,444
BEGIN DESCRIPTION:
UNT 086 IN BOCR 5.0
END DESCRIPTION:
XS GIS Cut Line= 3
      3748299.62     10553260.19      3748399.61     10553210.19
      3748799.61     10553060.19
#Sta/Elev= 30
    4897  257.65  4905.4  257.23  4919.4  253.91  4972.5  245.89  4986.4   240.7
  4994.8  229.67  4997.4  228.98  5000.2  228.48  5003.4  228.98  5040.8  234.91
  5134.3  235.97  5158.3  237.45  5179.7  240.01  5189.5  242.48    5201  242.69
  5243.8  247.57    5250   249.9  5255.3  249.26  5274.9  252.97  5280.2  251.85
  5286.5  254.83  5297.2  255.61  5310.5  260.09  5318.5  260.15  5350.6  265.31
  5360.3  266.21  5365.7  265.43  5390.6  271.34  5431.4  276.23    5436  276.59
#Mann= 4 ,-1 , 0
    4897     .16       0  4997.4     .07       0  5003.4     .16       0
  5431.4     .05       0
Bank Sta=4986.4,5040.8
XS Rating Curve= 0 ,0
Exp/Cntr=0.3,0.1

Type RM Length L Ch R = 1 ,1975    ,443,443,443
BEGIN DESCRIPTION:
UNT 086 IN BOCR 4.0
END DESCRIPTION:
XS GIS Cut Line= 3
      3748549.59     10553660.21      3748649.61     10553560.19
      3748849.61     10553310.19
#Sta/Elev= 30
  4872.1  252.79  4886.3  251.27  4900.4  247.33  4928.7  242.55  4942.8  237.09
    4957   234.1  4971.1  231.55  4985.3  230.01  4996.4  226.65  4999.2  226.15
  5002.4  226.65    5010  229.72  5019.1  229.61  5027.2  229.77  5035.2  228.93
  5041.6  229.42  5049.6  228.12    5056     228  5070.4  228.55  5091.2  231.65
  5113.6  232.05    5128  233.42  5155.2  238.84  5169.6  239.97  5194.7  245.49
  5198.4  246.92  5205.6  248.21  5269.7  256.43  5283.3  259.12  5333.7  263.77
#Mann= 5 ,-1 , 0
  4872.1     .16       0  4996.4     .07       0  5002.4     .16       0
  5019.1     .12       0  5194.7     .16       0
Bank Sta=4985.3,5010
XS Rating Curve= 0 ,0
Exp/Cntr=0.3,0.1

Type RM Length L Ch R = 1 ,1532    ,428,428,428
BEGIN DESCRIPTION:
UNT 086 IN BOCR 3.0
END DESCRIPTION:
XS GIS Cut Line= 3
      3748699.57      10553860.2      3748949.61     10553810.19
       3748999.6     10553610.23
#Sta/Elev= 30
  4736.3  248.86  4746.5  248.05  4756.7  246.29  4777.1  239.12  4787.3  236.32
  4797.5  231.61  4807.7  229.75  4848.5  228.78  4868.9  229.34  4899.5  228.66
  4919.9  229.31  4960.7  229.24  4993.9  227.31  4998.6   225.9  5001.3   225.4
  5004.6   225.9  5007.7  226.69  5009.3   227.1  5032.5  228.53  5047.5  232.52
  5050.6  233.24  5055.7  235.86  5073.7  236.92  5091.8     239  5096.9  240.66
  5125.3  243.87    5133  246.22  5145.9   247.5  5156.2  249.35  5197.4  253.39
#Mann= 5 ,-1 , 0
  4736.3     .16       0  4998.6     .07       0  5004.6     .16       0
  5007.7     .12       0  5047.5     .16       0
Bank Sta=4993.9,5009.3
XS Rating Curve= 0 ,0
Exp/Cntr=0.3,0.1

Type RM Length L Ch R = 1 ,1104    ,477,477,477
BEGIN DESCRIPTION:
UNT 086 IN BOCR 2.0
END DESCRIPTION:
XS GIS Cut Line= 3
       3748599.6     10553960.18      3749099.61     10554160.19
      3749299.59     10553760.23
#Sta/Elev= 30
  4482.5  250.34  4491.9  250.23  4497.3  248.62  4521.6  249.09  4526.9  247.35
  4575.4  245.63  4580.8  243.06  4590.2   243.5    4605  240.05  4644.1  235.04
  4688.5  230.32  4742.3  226.68  4820.4  224.38  4988.7  225.31  4996.5  223.13
  4999.2  222.63  5002.5  223.13  5006.2  225.51  5006.6  225.47  5132.8   226.1
  5163.6  226.86  5168.5  228.12    5201  230.04  5230.7  232.16  5258.6  236.23
    5313  240.07  5378.8  247.33  5415.1  249.13  5454.3  253.94  5468.2  254.26
#Mann= 7 ,-1 , 0
  4482.5     .05       0  4996.5     .03       0  5002.5     .05       0
  5006.6     .16       0  5168.5     .12       0    5201     .16       0
    5313     .05       0
Bank Sta=4988.7,5006.2
XS Rating Curve= 0 ,0
Exp/Cntr=0.3,0.1

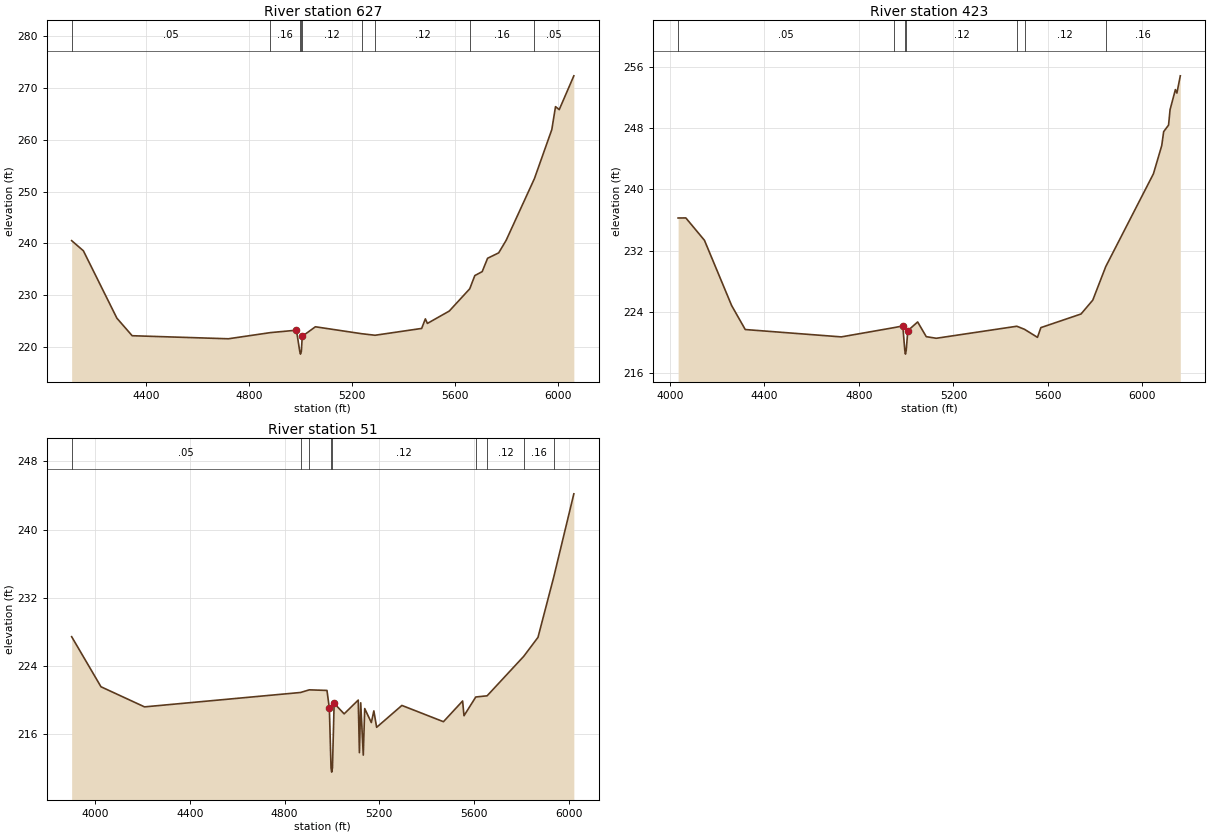
Type RM Length L Ch R = 1 ,627     ,204,204,204
BEGIN DESCRIPTION:
UNT 086 IN BOCR 1.0
END DESCRIPTION:
XS GIS Cut Line= 3
      3748449.65     10554110.21      3749249.61     10554560.19
       3749899.6      10553760.2
#Sta/Elev= 30
  4112.1  240.51  4157.6  238.55  4287.7  225.51  4346.9  222.12  4720.2  221.53
  4883.2  222.72  4984.4  223.19  4997.3  219.06    5000  218.56  5003.3  219.06
  5006.8  221.85    5007  222.01  5057.9  223.85  5237.2  222.51  5289.4  222.21
  5470.2  223.53  5484.6  225.38  5492.5   224.5  5577.3  226.89  5656.8   231.2
  5676.4  233.75  5705.1  234.52    5726   237.1  5769.1  238.15  5797.8  240.55
  5907.7   252.5  5975.2  261.99  5989.6  266.43    6004  265.85  6060.7  272.39
#Mann= 9 ,-1 , 0
  4112.1     .05       0  4883.2     .16       0  4997.3     .07       0
  5003.3     .16       0  5006.8     .12       0  5237.2     .16       0
  5289.4     .12       0  5656.8     .16       0  5907.7     .05       0
Bank Sta=4984.4,5007
XS Rating Curve= 0 ,0
Exp/Cntr=0.3,0.1

Type RM Length L Ch R = 1 ,423     ,372,372,372
BEGIN DESCRIPTION:
Mapping XS e69efcfc
END DESCRIPTION:
XS GIS Cut Line= 4
      3748310.88     10554185.18      3749061.75     10554662.61
      3749235.36     10554723.37      3749885.16     10553895.97
#Sta/Elev= 30
  4034.6  236.26  4067.3  236.27  4146.1  233.35  4261.2  224.83  4318.8   221.7
  4725.3  220.74  4946.7  221.94  4985.7  222.17  4994.2  218.99  4996.9  218.49
  5000.2  218.99  5006.9  221.55  5048.6  222.69    5085  220.77  5127.4  220.56
  5468.4  222.13  5500.9  221.73  5555.8  220.68  5570.1  221.95  5740.2  223.73
  5789.9  225.54  5844.7  229.91  6046.6  242.03  6081.8  245.71  6089.9  247.53
  6110.7  248.39  6117.1  250.41  6139.6  253.02    6146  252.57  6160.4  254.82
#Mann= 7 ,-1 , 0
  4034.6     .05       0  4946.7     .12       0  4994.2     .07       0
  5000.2     .12       0  5468.4     .16       0  5500.9     .12       0
  5844.7     .16       0
Bank Sta=4985.7,5006.9
XS Rating Curve= 0 ,0
Exp/Cntr=0.3,0.1

Type RM Length L Ch R = 1 ,51      ,0,0,0
BEGIN DESCRIPTION:
Mapping XS b81adeb1
END DESCRIPTION:
XS GIS Cut Line= 6
      3748319.89     10554414.64      3748687.07     10554792.24
      3748884.99     10554849.53      3749356.35     10554849.53
      3749598.53     10554729.74      3749944.73     10554185.71
#Sta/Elev= 30
  3901.1  227.43    4025  221.55  4208.9  219.19  4867.7  220.88  4904.8  221.19
  4979.3  221.12  4989.4  219.01  4996.4  212.03  4999.2  211.53  5002.4  212.03
  5009.5  219.61  5051.8  218.37  5111.3  219.99  5116.2  213.82  5121.7  219.67
  5132.6  213.53  5138.6  218.99  5166.6  217.35  5177.2  218.72    5189  216.79
  5295.6  219.36  5471.1  217.45    5552  219.88  5557.9  218.15  5607.6  220.35
  5655.5  220.49    5810  225.12  5870.3  227.35  5936.9  234.44  6021.7   244.2
#Mann= 9 ,-1 , 0
  3901.1     .05       0  4867.7     .16       0  4904.8     .12       0
  4996.4     .07       0  5002.4     .12       0  5607.6     .16       0
  5655.5     .12       0    5810     .16       0  5936.9     .05       0
Bank Sta=4989.4,5009.5
XS Rating Curve= 0 ,0
Exp/Cntr=0.3,0.1

Chan Stop Cuts=-1
Use User Specified Reach Order=0
Composite Channel Slope=5