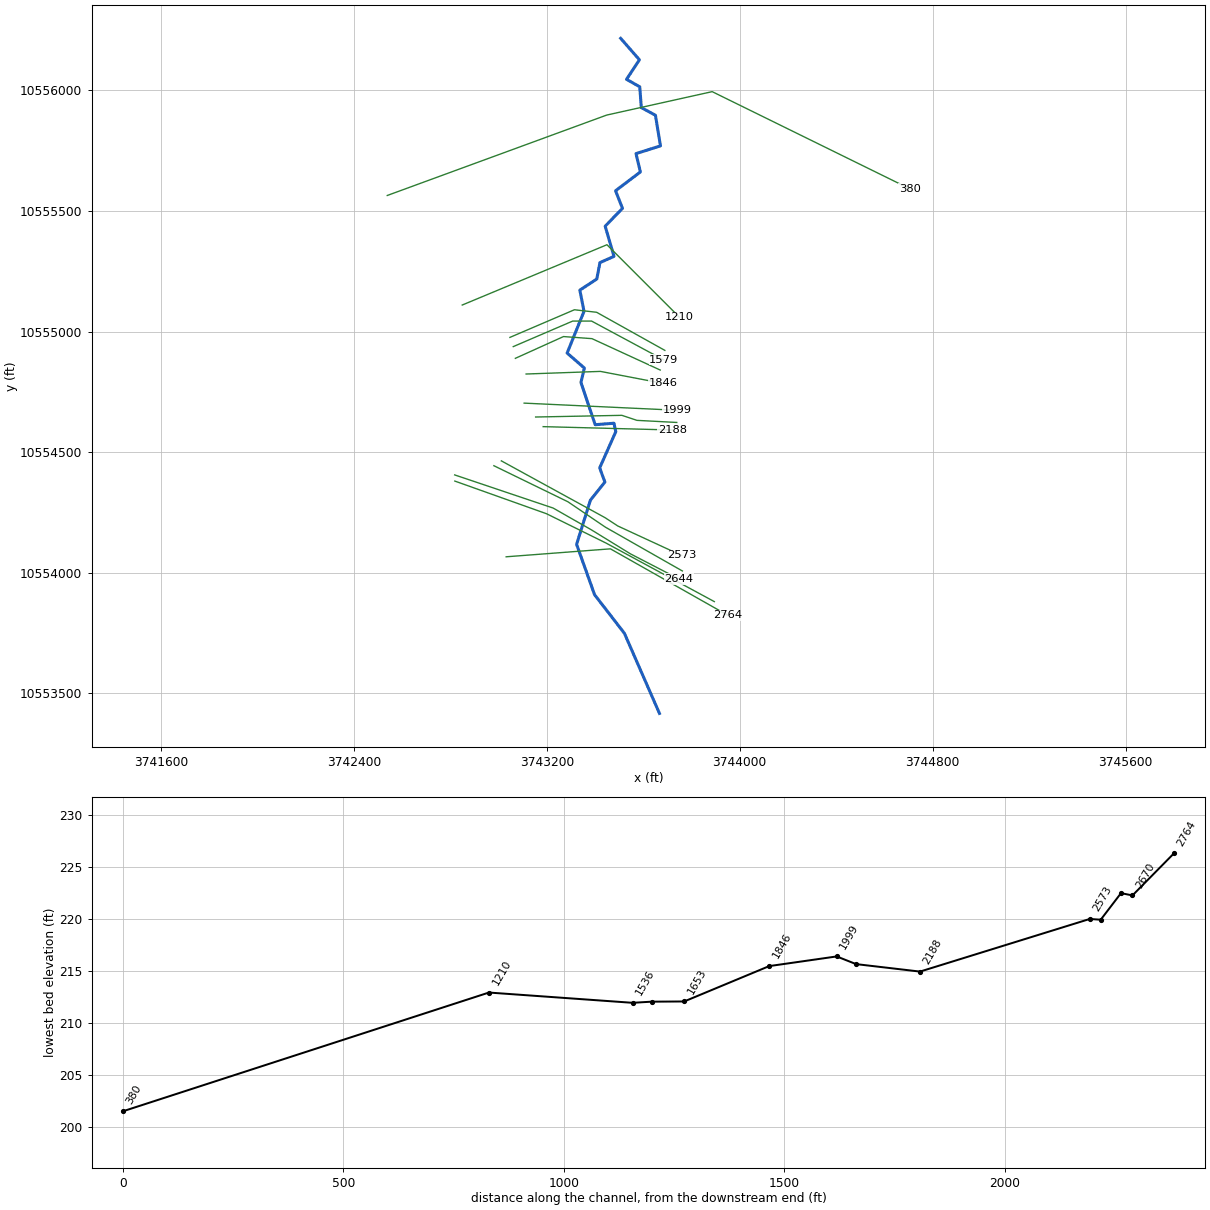
--- UNT 087 IN BOCR.prj (project) ---

Proj Title=UNT 087 IN BOCR Base Level Engineering
Current Plan=p01
Default Exp/Contr=0.3,0.1
English Units
Geom File=g01
Flow File=f01
Plan File=p01
Y Axis Title=Elevation
X Axis Title(PF)=Main Channel Distance
X Axis Title(XS)=Station
BEGIN DESCRIPTION:
UNT 087 IN BOCR
END DESCRIPTION:
DSS File=dss
DSS Export Rating Curves= 0
DSS Export Rating Curve Sorted= 0
DSS Export Volume Flow Curves= 0
DXF OffsetX= 0
DXF OffsetY= 0
DXF ScaleX= 1
DXF ScaleY= 10

--- UNT 087 IN BOCR.p01 (plan) ---

Plan Title=Multiple Run
Program Version=4.10
Short Identifier=Multiple Run
Geom File=g01
Flow File=f01
Subcritical Flow
K Sum by GR= 0
Std Step Tol= 0.01
Critical Tol= 0.01
Num of Std Step Trials= 20
Max Error Tol= 0.3
Flow Tol Ratio= 0.001
Split Flow NTrial= 30
Split Flow Tol= 0.02
Split Flow Ratio= 0.02
Log Output Level= 0
Friction Slope Method= 1
Unsteady Friction Slope Method= 2
Unsteady Bridges Friction Slope Method= 1
Parabolic Critical Depth
Global Vel Dist= 1 , 1 , 1
Global Log Level= 0
CheckData=True
Encroach Param=-1 ,0,0, 0
BEGIN DESCRIPTION:
Multiple Run
END DESCRIPTION:
Computation Interval=1HOUR
Output Interval=1HOUR
Run HTab= 0
Run UNet= 0
Run PostProcess= 0
Run WQNet= 0
UNET Theta= 1
UNET Theta Warmup= 1
UNET ZTol= 0.02
UNET ZSATol= 0.05
UNET MxIter= 20
UNET MaxInSteps= 0
UNET DtIC= 0
UNET DtMin= 0
UNET MaxCRTS= 20
UNET WFStab= 2
UNET SFStab= 1
UNET WFX= 1
UNET SFX= 1
UNET DSS MLevel= 4
UNET DZMax Abort= 100
UNET Convert EG Bridges= 0
UNET Use Existing IB Tables=-1
UNET Froude Reduction=False
UNET Froude Limit= 1
UNET Froude Power= 10
UNET Time Slicing=0,0, 5
UNET Junction Losses=0
Instantaneous Interval=1HOUR
DSS File=dss
Write IC File= 0
Write IC File at Sim End=0
Echo Input=False
Echo Parameters=False
Echo Output=False
Write Detailed= 0
WQ AD Non Conservative
WQ ULTIMATE=-1
WQ Max Comp Step=1HOUR
WQ Output Interval=15MIN
WQ Output Selected Increments= 0
WQ Output face flow=0
WQ Output face velocity=0
WQ Output face area=0
WQ Output face dispersion=0
WQ Output cell volume=0
WQ Output cell surface area=0
WQ Output cell continuity=0
WQ Output cumulative cell continuity=0
WQ Output face conc=0
WQ Output face dconc_dx=0
WQ Output face courant=0
WQ Output face peclet=0
WQ Output face adv mass=0
WQ Output face disp mass=0
WQ Output cell mass=0
WQ Output cell source sink temp=0
WQ Output cell source sink nsm=0
WQ Output MaxMinRange=-1
WQ Daily Max Min Mean=-1
WQ Daily Range=0
WQ Daily Time=0
WQ Create Restart=0
WQ Fixed Restart=0
WQ System Summary=0
WQ Use Fixed Temperature=0
Sorting and Armoring Iterations= 10
XS Update Threshold= 0.02
Hydraulics Update Threshold= 0.02
Energy Slope Method= 1
Volume Change Method= 0
XS Weighting Method= 0
Number of US Weighted Cross Sections= 1
Number of DS Weighted Cross Sections= 1
Upstream XS Weight=0.25
Main XS Weight=0.5
Downstream XS Weight=0.25
Number of DS XS's Weighted with US Boundary= 1
Upstream Boundary Weight= 1
Weight of XSs Associated with US Boundary= 0
Number of US XS's Weighted with DS Boundary= 1
Downstream Boundary Weight= 0.5
Weight of XSs Associated with DS Boundary= 0.5
Sediment Output Level= 4
Mass or Volume Output= 0
Output Increment Type= 1
Profile and TS Output Increment= 10
XS Output Flag= 0
XS Output Increment= 10
Disregard all LS=0
Disregard all Conn=0
Disregard all Breaches=0
Disregard all Pumps=0

--- UNT 087 IN BOCR.f01 (steady flow) ---

Flow Title=Multiple
Program Version=4.10
Number of Profiles= 7
Profile Names=10-year,25-year,50-year,1pct_min,100-year,1pct_plu,500-year
River Rch & RM=UNT 087 IN BOCR,Reach-1         ,2764
     267     344     404     351     474     642     654
Boundary for River Rch & Prof#=UNT 087 IN BOCR,Reach-1         , 1
Up Type= 0
Dn Type= 3
Dn Slope=0.005
Boundary for River Rch & Prof#=UNT 087 IN BOCR,Reach-1         , 2
Up Type= 0
Dn Type= 3
Dn Slope=0.005
Boundary for River Rch & Prof#=UNT 087 IN BOCR,Reach-1         , 3
Up Type= 0
Dn Type= 3
Dn Slope=0.005
Boundary for River Rch & Prof#=UNT 087 IN BOCR,Reach-1         , 4
Up Type= 0
Dn Type= 3
Dn Slope=0.005
Boundary for River Rch & Prof#=UNT 087 IN BOCR,Reach-1         , 5
Up Type= 0
Dn Type= 3
Dn Slope=0.005
Boundary for River Rch & Prof#=UNT 087 IN BOCR,Reach-1         , 6
Up Type= 0
Dn Type= 3
Dn Slope=0.005
Boundary for River Rch & Prof#=UNT 087 IN BOCR,Reach-1         , 7
Up Type= 0
Dn Type= 3
Dn Slope=0.005
DSS Import GetInterval= 0
DSS Import GetPeak= 0
DSS Import FillOption= 0

--- UNT 087 IN BOCR.g01 (geometry) ---

Geom Title=Existing Conditions
Program Version=4.10

River Reach=UNT 087 IN BOCR ,Reach-1
Reach XY= 30
      3743667.25       10553417.        3743522.       10553749.
      3743398.25       10553909.      3743323.75       10554118.
        3743381.       10554301.        3743441.       10554376.
       3743419.5       10554435.      3743486.25       10554585.
      3743478.65     10554620.14      3743400.84     10554613.91
      3743341.75       10554789.        3743356.       10554849.
       3743284.5       10554911.       3743354.5       10555084.
      3743337.25       10555172.       3743407.5       10555218.
       3743420.5       10555286.      3743478.75       10555312.
      3743442.25       10555437.        3743514.       10555511.
      3743485.25       10555584.      3743588.25       10555662.
        3743570.       10555738.       3743671.5       10555770.
      3743650.75       10555897.        3743592.       10555929.
      3743585.75       10556015.      3743530.75       10556046.
      3743584.25       10556127.       3743506.5       10556216.

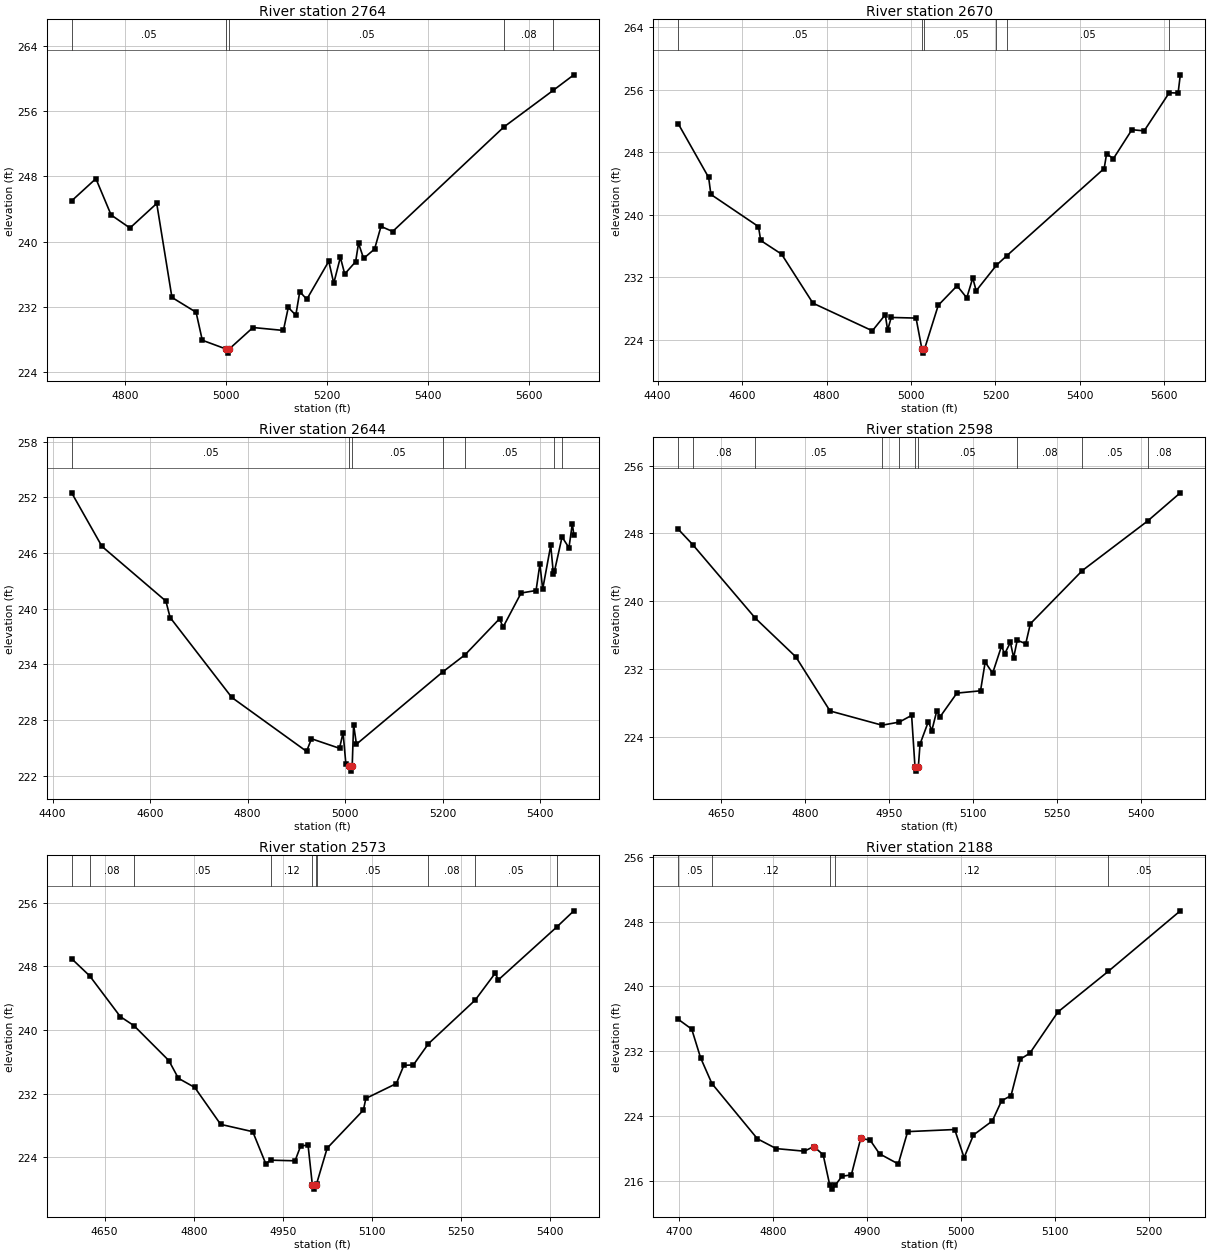
Type RM Length L Ch R = 1 ,2764    ,94,94,94
BEGIN DESCRIPTION:
Mapping XS a3ded421
END DESCRIPTION:
XS GIS Cut Line= 3
      3743031.71     10554066.25      3743463.96     10554099.23
      3743951.78     10553823.21
#Sta/Elev= 30
  4693.9     245  4741.9  247.72    4772  243.27  4809.3  241.67  4862.3  244.68
  4892.4  233.16  4940.2  231.34  4952.5  227.91  4999.7  226.83  5002.4  226.33
  5005.7  226.83  5052.8  229.47    5113  229.11  5122.7  231.93  5137.6  230.98
  5145.4  233.87  5159.3  232.93  5202.8  237.59  5212.7   234.9  5225.8  238.08
  5234.4  236.03    5256  237.54  5261.7   239.8  5271.8  237.94  5293.5  239.09
  5306.2  241.87  5329.2  241.24  5549.5  254.06  5647.6  258.57  5687.9  260.45
#Mann= 5 ,-1 , 0
  4693.9     .05       0  4999.7     .03       0  5005.7     .05       0
  5549.5     .08       0  5647.6     .05       0
Bank Sta=4999.7,5005.7
XS Rating Curve= 0 ,0
Exp/Cntr=0.3,0.1

Type RM Length L Ch R = 1 ,2670    ,26,26,26
BEGIN DESCRIPTION:
Mapping XS ca631b58
END DESCRIPTION:
XS GIS Cut Line= 4
      3742818.78     10554380.24      3743199.02     10554244.81
      3743445.55     10554123.29      3743894.91     10553880.39
#Sta/Elev= 30
  4448.5  251.69  4520.8  244.78  4526.1  242.61  4638.8  238.49  4644.1  236.71
  4693.5  234.96  4767.8  228.68  4908.5  225.14  4939.1   227.2  4944.7  225.21
  4953.1  226.85    5012  226.77  5025.9  222.78  5028.7  222.28  5031.9  222.78
  5064.6  228.41  5109.2  230.91  5132.1  229.36  5146.3  231.92  5154.3  230.26
  5202.2  233.53  5226.3  234.73  5457.5  245.93  5463.2  247.81  5479.4   247.2
  5523.2   250.9  5552.2  250.75  5611.5  255.63  5632.6   255.6  5637.8  257.93
#Mann= 6 ,-1 , 0
  4448.5     .05       0  5025.9     .04       0  5031.9     .05       0
  5202.2     .08       0  5226.3     .05       0  5611.5     .08       0
Bank Sta=5025.9,5031.9
XS Rating Curve= 0 ,0
Exp/Cntr=0.3,0.1

Type RM Length L Ch R = 1 ,2644    ,46,46,46
BEGIN DESCRIPTION:
Mapping XS 7e63e4eb
END DESCRIPTION:
XS GIS Cut Line= 5
      3742818.18     10554405.78       3743226.5     10554268.34
      3743385.02     10554178.04      3743546.56     10554078.72
      3743748.45     10553974.29
#Sta/Elev= 30
  4439.1   252.5  4501.2  246.73  4632.4  240.83  4641.1  239.06  4767.7  230.44
    4921  224.63  4931.1  225.99  4988.6  224.96  4995.9  226.64  5001.7  223.24
  5008.6     223  5011.4   222.5  5014.6     223  5017.5  227.52  5023.3   225.4
  5200.5   233.2  5246.3  235.05  5316.8  238.92  5324.2  238.03  5361.1   241.7
  5391.8  241.97  5399.7  244.83  5405.4  242.12  5421.9  246.83  5427.5   243.7
  5429.6  244.06  5445.1  247.74  5459.3  246.58  5466.2  249.19  5469.3  247.95
#Mann= 7 ,-1 , 0
  4439.1     .05       0  5008.6     .04       0  5014.6     .05       0
  5200.5     .08       0  5246.3     .05       0  5429.6     .08       0
  5445.1     .05       0
Bank Sta=5008.6,5014.6
XS Rating Curve= 0 ,0
Exp/Cntr=0.3,0.1

Type RM Length L Ch R = 1 ,2598    ,25,25,25
BEGIN DESCRIPTION:
Mapping XS df51fdb7
END DESCRIPTION:
XS GIS Cut Line= 4
      3742980.71     10554443.91       3743287.7     10554294.42
      3743443.22     10554189.08      3743762.27     10554007.48
#Sta/Elev= 30
  4573.8  248.51  4599.7  246.69  4711.8  237.98  4783.9  233.43    4845  227.04
  4937.9  225.36  4968.6  225.73  4990.6  226.52  4996.6  220.44  4999.3  219.94
  5002.6  220.44  5005.6  223.13  5020.5  225.79  5026.6  224.71  5035.5  227.05
  5041.5  226.36  5071.4  229.15  5113.6  229.42  5121.9  232.81  5135.2   231.5
    5151  234.68  5156.8   233.8  5166.9  235.14  5172.7  233.33  5179.1  235.39
  5194.3  234.98  5202.5  237.33  5295.4  243.62  5411.8  249.46  5470.2  252.79
#Mann= 10 ,-1 , 0
  4573.8     .05       0  4599.7     .08       0  4711.8     .05       0
  4937.9     .12       0  4968.6     .05       0  4996.6     .04       0
  5002.6     .05       0  5179.1     .08       0  5295.4     .05       0
  5411.8     .08       0
Bank Sta=4996.6,5002.6
XS Rating Curve= 0 ,0
Exp/Cntr=0.3,0.1

Type RM Length L Ch R = 1 ,2573    ,385,385,385
BEGIN DESCRIPTION:
Mapping XS 9d1d2429
END DESCRIPTION:
XS GIS Cut Line= 4
      3743011.76       10554464.      3743442.21     10554228.21
      3743494.38     10554194.09      3743759.24      10554071.7
#Sta/Elev= 30
  4594.5  248.97  4624.9  246.81  4676.4  241.69  4699.3  240.56    4758  236.17
  4774.1  233.94  4801.6  232.79  4845.2  228.15  4899.2  227.23    4921  223.22
  4929.6  223.65  4970.4  223.57  4979.7  225.42  4992.2  225.56  4999.5  220.51
  5002.3  220.01  5005.5  220.51  5006.5  220.65  5024.4  225.16  5085.3  229.94
  5089.5  231.41  5140.8  233.28  5153.4  235.57  5169.4  235.62  5194.8  238.29
  5273.4  243.77    5307  247.14  5312.5  246.32  5410.7  252.96  5439.4  254.99
#Mann= 10 ,-1 , 0
  4594.5     .05       0  4624.9     .08       0  4699.3     .05       0
  4929.6     .12       0  4999.5     .07       0  5005.5     .12       0
  5006.5     .05       0  5194.8     .08       0  5273.4     .05       0
  5410.7     .08       0
Bank Sta=4999.5,5005.5
XS Rating Curve= 0 ,0
Exp/Cntr=0.3,0.1

Type RM Length L Ch R = 1 ,2188    ,145,145,145
BEGIN DESCRIPTION:
Mapping XS 2c0f5511
END DESCRIPTION:
XS GIS Cut Line= 2
      3743185.15     10554605.92      3743719.87     10554592.04
#Sta/Elev= 30
  4698.8  235.95  4713.3  234.72  4722.7  231.19  4734.8  227.99  4783.3  221.16
  4803.3  219.95  4833.3  219.63  4843.3  220.21  4853.3  219.19  4860.3  215.44
  4863.1  214.94  4866.3  215.44  4873.3  216.53  4883.3   216.7  4893.3  221.22
  4903.3     221  4913.3  219.31  4933.3  218.05  4943.3  222.05  4993.4  222.31
  5003.4  218.84  5013.4  221.64  5033.4  223.36  5043.4  225.87  5053.4   226.5
  5063.4  231.02  5073.4  231.74  5103.4  236.85  5156.8  241.85  5233.7  249.35
#Mann= 5 ,-1 , 0
  4698.8     .05       0  4734.8     .12       0  4860.3     .07       0
  4866.3     .12       0  5156.8     .05       0
Bank Sta=4843.3,4893.3
XS Rating Curve= 0 ,0
Exp/Cntr=0.3,0.1

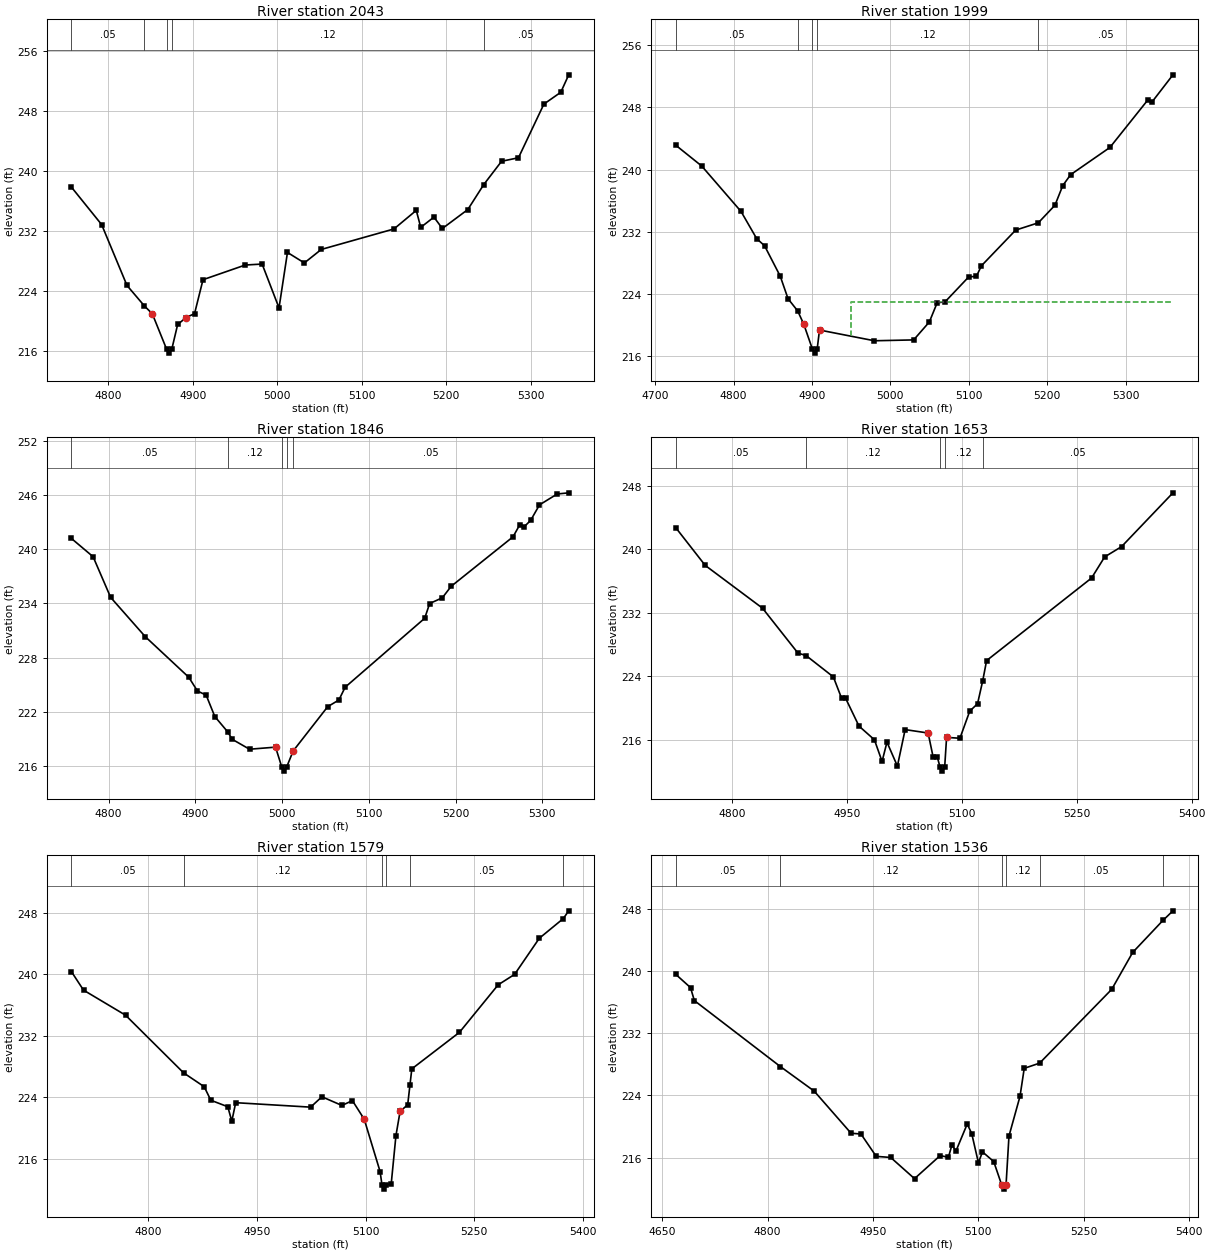
Type RM Length L Ch R = 1 ,2043    ,44,44,44
BEGIN DESCRIPTION:
Mapping XS d3c9d6aa
END DESCRIPTION:
XS GIS Cut Line= 4
      3743153.86     10554645.85      3743511.52      10554652.8
      3743574.02     10554631.97      3743738.99     10554623.28
#Sta/Elev= 30
  4756.1  237.84  4791.9  232.83  4821.9   224.7  4842.4  221.98  4851.9  220.91
  4868.9  216.16  4871.6  215.66  4874.9  216.16  4881.9  219.49  4891.9  220.41
  4901.9  220.94  4911.9  225.47  4961.9  227.43  4981.9  227.56  5001.9   221.7
  5011.9  229.11  5031.9  227.71  5051.9  229.51    5138  232.25  5164.4  234.73
  5169.7  232.46  5185.3  233.83  5195.3  232.31  5225.4  234.84  5244.3  238.18
  5265.4  241.29  5285.4  241.76  5315.5  248.93  5335.5  250.51  5344.9  252.84
#Mann= 5 ,-1 , 0
  4756.1     .05       0  4842.4     .12       0  4868.9     .07       0
  4874.9     .12       0  5244.3     .05       0
#XS Ineff= 2 , 0
                         4966.88          227.07
Permanent Ineff=
       F       F
Bank Sta=4851.9,4891.9
XS Rating Curve= 0 ,0
Exp/Cntr=0.3,0.1

Type RM Length L Ch R = 1 ,1999    ,153,153,153
BEGIN DESCRIPTION:
UNT 087 IN BOCR 4.0
END DESCRIPTION:
XS GIS Cut Line= 2
      3743106.34      10554703.4      3743739.96     10554673.89
#Sta/Elev= 30
  4726.1  243.15  4759.4  240.46  4809.5  234.62  4829.5  231.12  4839.5  230.21
  4859.5   226.3  4869.5  223.39  4881.7  221.84  4889.5  220.13  4900.6   216.9
  4903.3   216.4  4906.6   216.9  4909.6  219.37  4979.6  217.99  5029.7   218.1
  5049.7  220.41  5059.7  222.88  5069.7  222.99  5099.8  226.19  5109.8  226.29
  5116.1  227.63  5159.8  232.22  5188.7  233.16  5209.9  235.42  5219.9  237.95
  5229.9  239.35    5280  242.85  5328.7     249  5333.7   248.7  5360.4  252.19
#Mann= 5 ,-1 , 0
  4726.1     .05       0  4881.7     .12       0  4900.6     .07       0
  4906.6     .12       0  5188.7     .05       0
#XS Ineff= 2 , 0
       0                    4950       0     223
Permanent Ineff=
       F       F
Bank Sta=4889.5,4909.6
XS Rating Curve= 0 ,0
Exp/Cntr=0.3,0.1

Type RM Length L Ch R = 1 ,1846    ,193,193,193
BEGIN DESCRIPTION:
Mapping XS 32d1a365
END DESCRIPTION:
XS GIS Cut Line= 3
      3743114.41     10554824.14      3743422.57     10554834.99
      3743682.69     10554785.13
#Sta/Elev= 30
  4757.2  241.18  4782.2  239.16  4802.4  234.67  4842.4  230.32  4892.5  225.84
  4902.5  224.32  4912.5  223.87  4922.5   221.5  4937.5  219.79  4942.5  218.99
  4962.5  217.89  4992.5  218.12  4999.5  215.97  5002.3  215.47  5005.5  215.97
  5012.8   217.7  5052.6  222.59  5065.5  223.33  5072.7  224.74  5164.4  232.36
  5170.1  233.99  5184.7  234.62  5194.9  235.89  5266.2  241.36  5274.1  242.71
  5279.2  242.49  5286.5  243.17  5296.7  244.89  5317.1  246.09  5330.4  246.22
#Mann= 5 ,-1 , 0
  4757.2     .05       0  4937.5     .12       0  4999.5     .07       0
  5005.5     .12       0  5012.8     .05       0
Bank Sta=4992.5,5012.8
XS Rating Curve= 0 ,0
Exp/Cntr=0.3,0.1

Type RM Length L Ch R = 1 ,1653    ,74,74,74
BEGIN DESCRIPTION:
Mapping XS 2a44f635
END DESCRIPTION:
XS GIS Cut Line= 4
      3743069.83     10554889.15      3743269.51     10554979.44
      3743387.57     10554970.76      3743670.53     10554840.57
#Sta/Elev= 30
  4726.6  242.74  4765.2  237.97    4840  232.58  4886.2  226.93  4896.9  226.61
  4932.4  223.93  4943.1  221.26  4948.3  221.26  4965.9  217.73    4986  216.01
    4996  213.28  5002.4  215.71    5016  212.69  5026.1  217.29  5056.1  216.86
  5062.6  213.85    5068  213.85  5071.7  212.56  5074.4  212.06  5077.7  212.56
  5080.2  216.31  5097.6   216.2  5110.4  219.61  5120.6  220.55  5127.4  223.46
  5132.4  225.98  5269.4  236.38  5286.5  239.04  5308.5  240.33  5375.6  247.11
#Mann= 5 ,-1 , 0
  4726.6     .05       0  4896.9     .12       0  5071.7     .07       0
  5077.7     .12       0  5127.4     .05       0
Bank Sta=5056.1,5080.2
XS Rating Curve= 0 ,0
Exp/Cntr=0.3,0.1

Type RM Length L Ch R = 1 ,1579    ,43,43,43
BEGIN DESCRIPTION:
Mapping XS d27f8c86
END DESCRIPTION:
XS GIS Cut Line= 4
      3743061.21     10554937.79      3743307.71     10555043.68
      3743385.83     10555043.68      3743685.39     10554882.65
#Sta/Elev= 30
  4693.9  240.35  4710.6  237.94  4768.6  234.68  4848.8  227.17  4877.2  225.37
  4886.3  223.61  4909.8  222.76  4915.3  220.88  4920.7  223.29  5024.1  222.71
  5039.7  224.06  5067.3  222.93  5081.8  223.56  5098.1  221.14    5120  214.33
  5122.7  212.54  5125.4  212.04  5128.7  212.54  5135.4  212.77  5141.9  219.01
  5147.6  222.15  5158.1  223.02  5161.2  225.56  5163.8  227.69  5229.6  232.45
    5283  238.63  5305.7  239.99  5339.8  244.69  5372.9  247.25  5380.4  248.26
#Mann= 6 ,-1 , 0
  4693.9     .05       0  4848.8     .12       0  5122.7     .07       0
  5128.7     .12       0  5161.2     .05       0  5372.9     .08       0
Bank Sta=5098.1,5147.6
XS Rating Curve= 0 ,0
Exp/Cntr=0.3,0.1

Type RM Length L Ch R = 1 ,1536    ,326,326,326
BEGIN DESCRIPTION:
UNT 087 IN BOCR 3.0
END DESCRIPTION:
XS GIS Cut Line= 4
      3743047.25     10554975.95      3743314.65     10555090.55
      3743406.67     10555080.14      3743689.63     10554922.16
#Sta/Elev= 30
  4669.2  239.61  4690.4  237.89  4695.8  236.22  4818.2  227.72  4866.3  224.56
  4918.8  219.13  4932.9  219.03  4954.6  216.15  4975.2  216.01  5009.1  213.28
  5045.6  216.25  5057.3  216.03  5062.3  217.61  5068.1  216.85  5084.1  220.32
  5090.5  219.08    5100  215.33  5105.8  216.73  5121.8  215.48  5133.3  212.43
    5136  211.93  5139.3  212.43  5143.5  218.77  5159.2  223.89  5165.2  227.49
  5187.1  228.16  5289.7  237.67  5319.5  242.42  5362.5  246.54  5376.8  247.78
#Mann= 6 ,-1 , 0
  4669.2     .05       0  4818.2     .12       0  5133.3     .07       0
  5139.3     .12       0  5187.1     .05       0  5362.5     .08       0
Bank Sta=5133.3,5139.3
XS Rating Curve= 0 ,0
Exp/Cntr=0.3,0.1

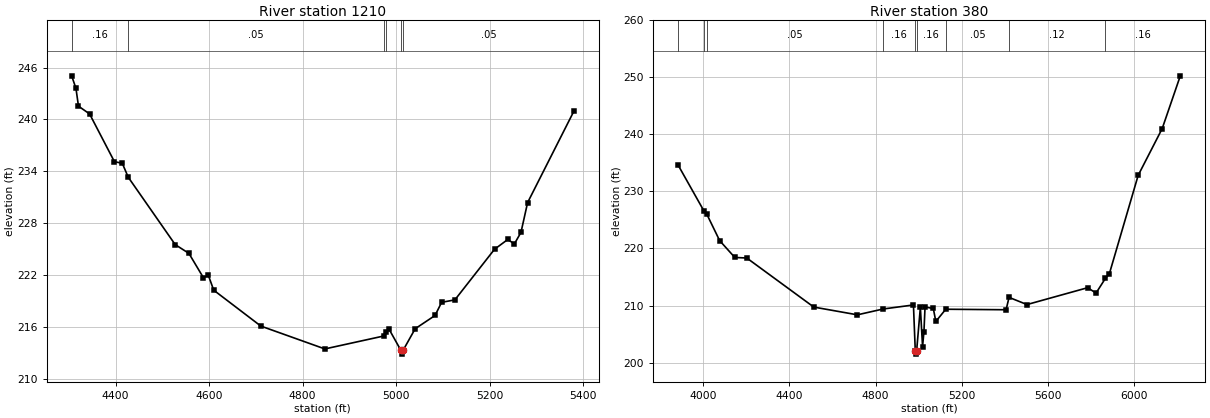
Type RM Length L Ch R = 1 ,1210    ,830,830,830
BEGIN DESCRIPTION:
UNT 087 IN BOCR 2.0
END DESCRIPTION:
XS GIS Cut Line= 3
      3742849.63      10555110.2      3743449.61     10555360.19
      3743749.58     10555060.22
#Sta/Elev= 30
  4306.1  245.04  4315.3  243.59  4320.7  241.54  4344.5  240.64  4397.6  235.13
  4414.4  234.95  4427.1  233.34  4527.6  225.56  4556.9  224.55  4587.7  221.76
  4598.6     222    4610   220.3  4710.7  216.16  4847.7  213.52  4973.5  215.01
  4978.9  215.43  4984.4  215.86  5009.7  213.42  5012.4  212.92  5015.7  213.42
  5040.9  215.85  5083.4  217.38  5097.5   218.9  5125.8  219.18  5210.6  225.02
  5238.9  226.15  5253.1  225.64  5267.2  226.97  5281.4  230.41  5380.3  240.95
#Mann= 6 ,-1 , 0
  4306.1     .16       0  4427.1     .05       0  4973.5     .12       0
  4978.9     .05       0  5009.7     .04       0  5015.7     .05       0
Bank Sta=5009.7,5015.7
XS Rating Curve= 0 ,0
Exp/Cntr=0.3,0.1

Type RM Length L Ch R = 1 ,380     ,0,0,0
BEGIN DESCRIPTION:
UNT 087 IN BOCR 1.0
END DESCRIPTION:
XS GIS Cut Line= 4
      3742538.65     10555564.39      3743448.39     10555897.73
      3743885.89     10555994.95      3744704.94     10555592.37
#Sta/Elev= 30
  3884.3  234.62  4004.4  226.56  4016.3   226.1    4077  221.38  4147.2  218.43
  4202.9  218.33  4513.7  209.73    4716  208.37  4835.1  209.39    4976   210.1
  4984.6  201.98  4987.4  201.48  4990.6  201.98  5008.1  209.66  5018.3  202.81
  5024.7  205.41  5029.8  209.75  5068.2  209.48  5079.8  207.21    5126  209.35
  5405.8  209.26  5419.5  211.43  5502.7  210.17  5784.6  213.13  5822.9  212.17
  5866.3  214.75  5884.8  215.56  6018.6  232.83  6130.1  241.03    6214  250.27
#Mann= 9 ,-1 , 0
  3884.3     .05       0  4004.4     .16       0  4016.3     .05       0
  4835.1     .16       0  4984.6     .07       0  4990.6     .16       0
    5126     .05       0  5419.5     .12       0  5866.3     .16       0
Bank Sta=4984.6,4990.6
XS Rating Curve= 0 ,0
Exp/Cntr=0.3,0.1

Chan Stop Cuts=-1
Use User Specified Reach Order=0
Composite Channel Slope=5