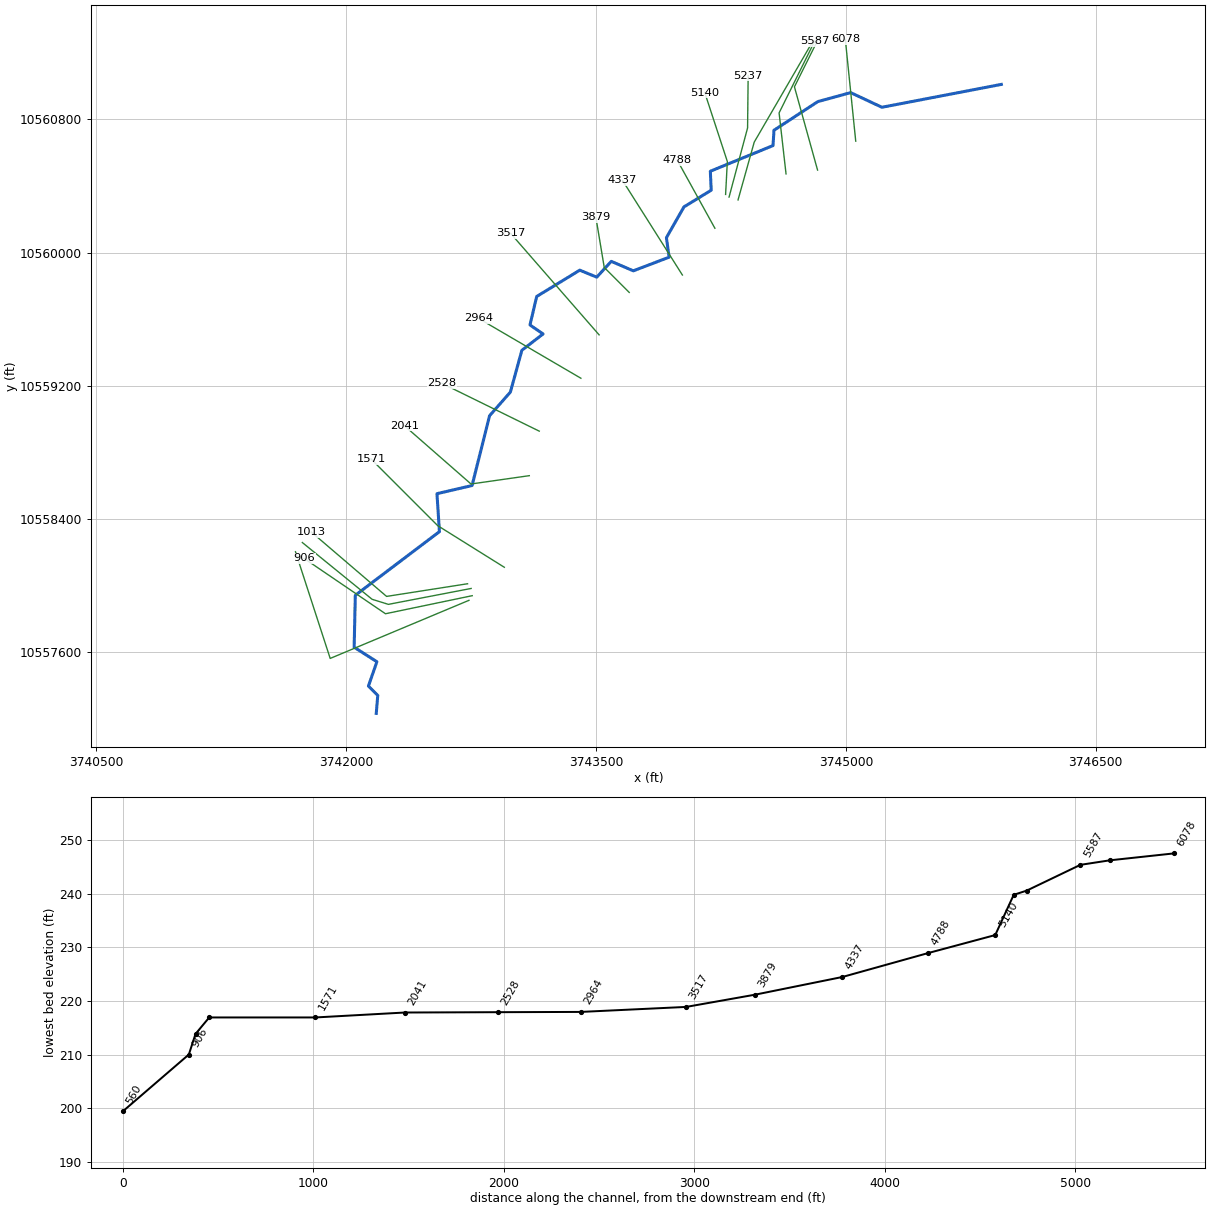
--- UNT 088 IN BOCR.prj (project) ---

Proj Title=UNT 088 IN BOCR Base Level Engineering
Current Plan=p01
Default Exp/Contr=0.3,0.1
English Units
Geom File=g01
Flow File=f01
Plan File=p01
Y Axis Title=Elevation
X Axis Title(PF)=Main Channel Distance
X Axis Title(XS)=Station
BEGIN DESCRIPTION:
UNT 088 IN BOCR
END DESCRIPTION:
DSS Export Rating Curves= 0
DSS Export Rating Curve Sorted= 0
DSS Export Volume Flow Curves= 0
DXF OffsetX= 0
DXF OffsetY= 0
DXF ScaleX= 1
DXF ScaleY= 10

--- UNT 088 IN BOCR.p01 (plan) ---

Plan Title=Multiple Run
Short Identifier=Multiple
Geom File=g01
Flow File=f01
Subcritical Flow
K Sum by GR= 0
Std Step Tol= 0.01
Critical Tol= 0.01
Num of Std Step Trials= 20
Max Error Tol= 0.3
Flow Tol Ratio= 0.001
Split Flow NTrial= 30
Split Flow Tol= 0.02
Split Flow Ratio= 0.02
Log Output Level= 0
Friction Slope Method= 1
Unsteady Friction Slope Method= 2
Unsteady Bridges Friction Slope Method= 1
Parabolic Critical Depth
Global Vel Dist=  1 , 1 , 1
Global Log Level= 0
CheckData=True
Encroach Param= -1, 0, 0, 0
BEGIN DESCRIPTION:
Multiple Run
END DESCRIPTION:

--- UNT 088 IN BOCR.f01 (steady flow) ---

Flow Title=Multiple
Program Version=4.10
Number of Profiles= 7
Profile Names=10-year,25-year,50-year,1pct_min,100-year,1pct_plu,500-year
River Rch & RM=UNT 088 IN BOCR,Reach-1         ,6078
     672     928    1144    1037    1403    1897    2117
Boundary for River Rch & Prof#=UNT 088 IN BOCR,Reach-1         , 1
Up Type= 0
Dn Type= 3
Dn Slope=0.01
Boundary for River Rch & Prof#=UNT 088 IN BOCR,Reach-1         , 2
Up Type= 0
Dn Type= 3
Dn Slope=0.01
Boundary for River Rch & Prof#=UNT 088 IN BOCR,Reach-1         , 3
Up Type= 0
Dn Type= 3
Dn Slope=0.01
Boundary for River Rch & Prof#=UNT 088 IN BOCR,Reach-1         , 4
Up Type= 0
Dn Type= 3
Dn Slope=0.01
Boundary for River Rch & Prof#=UNT 088 IN BOCR,Reach-1         , 5
Up Type= 0
Dn Type= 3
Dn Slope=0.01
Boundary for River Rch & Prof#=UNT 088 IN BOCR,Reach-1         , 6
Up Type= 0
Dn Type= 3
Dn Slope=0.01
Boundary for River Rch & Prof#=UNT 088 IN BOCR,Reach-1         , 7
Up Type= 0
Dn Type= 3
Dn Slope=0.01
DSS Import GetInterval= 0
DSS Import GetPeak= 0
DSS Import FillOption= 0

--- UNT 088 IN BOCR.g01 (geometry) ---

Geom Title=Existing Conditions
Program Version=4.10

River Reach=UNT 088 IN BOCR ,Reach-1
Reach XY= 30
      3745933.79      10561009.4      3745216.75       10560872.
        3745029.       10560960.      3744831.75       10560906.
      3744568.75       10560734.      3744562.75       10560642.
       3744186.5       10560488.      3744191.75       10560374.
      3744028.25       10560274.      3743922.75       10560089.
      3743939.25       10559972.      3743724.25       10559890.
      3743591.75       10559947.       3743504.5       10559852.
      3743402.75       10559894.        3743144.       10559736.
      3743103.75       10559565.      3743182.25       10559511.
        3743055.       10559413.        3742986.       10559162.
        3742861.       10559020.        3742756.       10558601.
      3742545.25       10558552.        3742560.       10558324.
        3742055.       10557942.        3742048.       10557630.
       3742184.5       10557543.      3742133.75       10557397.
      3742189.75       10557341.      3742180.75       10557233.

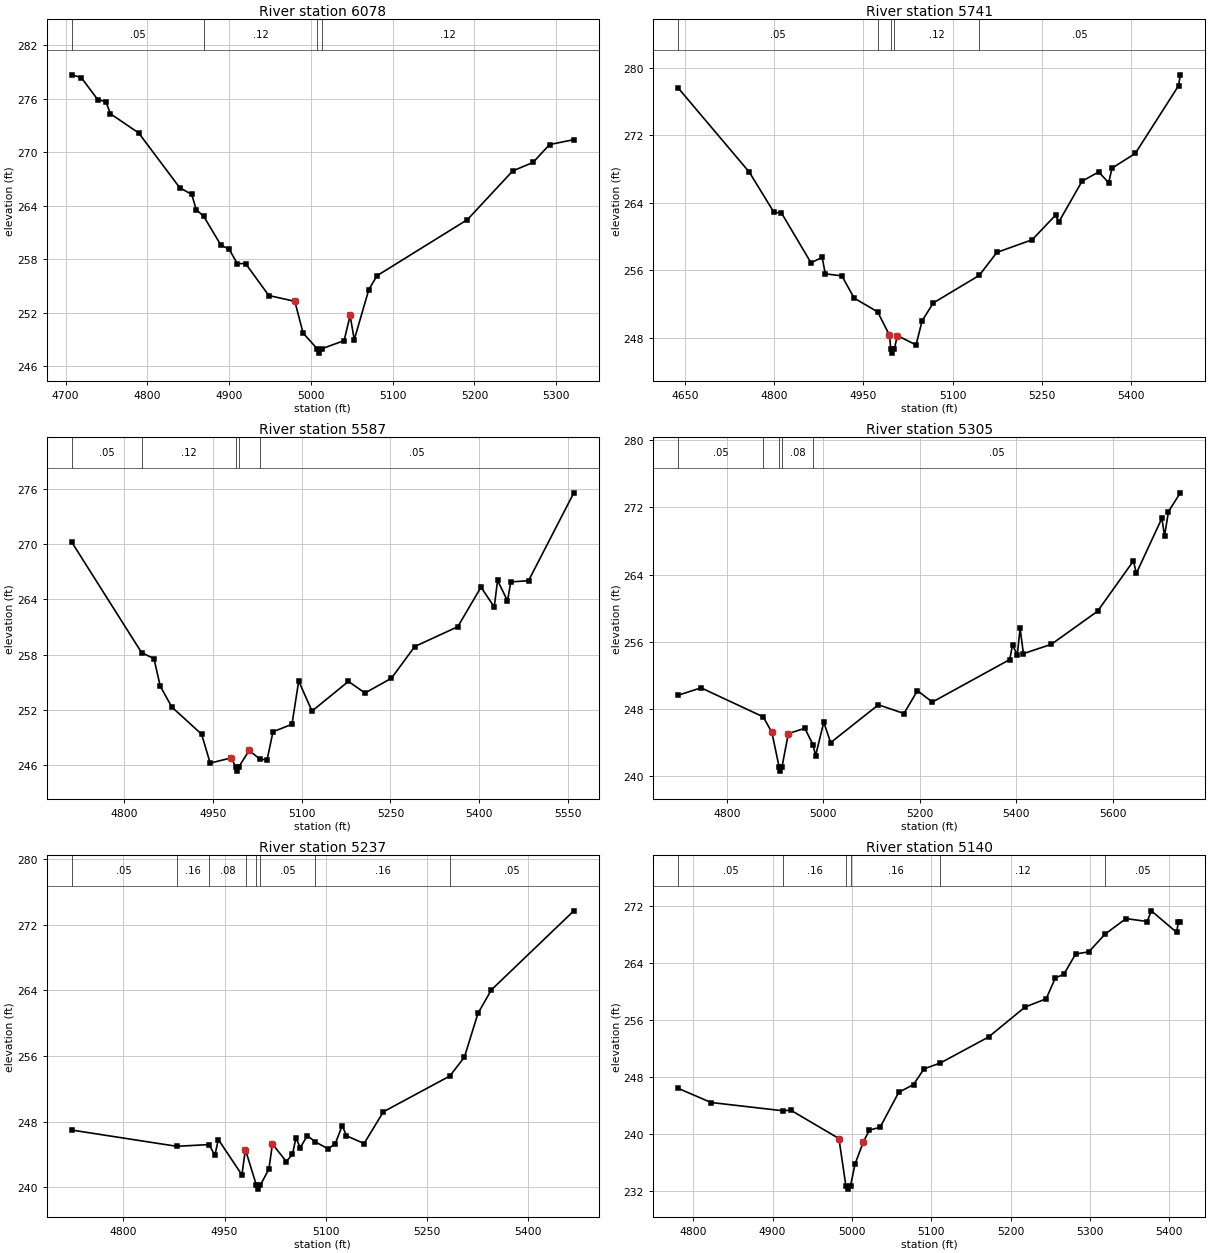
Type RM Length L Ch R = 1 ,6078    ,337,337,337
BEGIN DESCRIPTION:
UNT 088 IN BOCR 14.0
END DESCRIPTION:
XS GIS Cut Line= 2
       3745059.5     10560668.58        3744997.     10561279.69
#Sta/Elev= 30
  4707.3   278.7    4719   278.4  4739.1  275.93  4749.1  275.69  4754.8  274.33
  4789.3  272.18  4839.6  266.03  4854.2  265.29  4859.7  263.59  4868.9  262.82
  4889.9   259.6  4899.9  259.15    4910  257.52    4920  257.54  4948.5  253.95
  4980.3   253.3  4990.4  249.74  5007.5  247.99  5010.2  247.49  5013.5  247.99
  5040.6  248.89  5047.9  251.71    5053     249  5070.8  254.61  5080.8  256.17
  5191.4  262.46  5246.8  267.92  5271.8  268.88  5291.9  270.88  5321.6  271.43
#Mann= 4 ,-1 , 0
  4707.3     .05       0  4868.9     .12       0  5007.5     .07       0
  5013.5     .12       0
Bank Sta=4980.3,5047.9
XS Rating Curve= 0 ,0
Exp/Cntr=0.3,0.1

Type RM Length L Ch R = 1 ,5741    ,154,154,154
BEGIN DESCRIPTION:
UNT 088 IN BOCR 12.0
END DESCRIPTION:
XS GIS Cut Line= 3
      3744830.32     10560494.99      3744691.45     10560994.95
      3744836.93     10561285.92
#Sta/Elev= 30
  4638.4  277.64    4758  267.66  4799.5  262.89  4812.1  262.82  4861.7  256.92
  4880.6  257.54  4885.8   255.6  4913.6  255.36  4934.4  252.72  4973.8  251.09
  4993.7  248.33  4995.9   246.7  4998.7   246.2  5001.9   246.7    5007  248.28
  5038.4  247.17  5048.6  250.04  5067.4  252.15  5144.5  255.41  5174.3  258.14
  5233.6  259.64  5272.8  262.55  5278.4  261.75  5317.5  266.59  5345.4  267.67
  5362.2   266.4  5367.8  268.13  5406.9  269.87  5479.6  277.89  5482.6  279.19
#Mann= 5 ,-1 , 0
  4638.4     .05       0  4973.8     .12       0  4995.9     .07       0
  5001.9     .12       0  5144.5     .05       0
Bank Sta=4993.7,5007
XS Rating Curve= 0 ,0
Exp/Cntr=0.3,0.1

Type RM Length L Ch R = 1 ,5587    ,282,282,282
BEGIN DESCRIPTION:
Mapping XS 4c8918f0
END DESCRIPTION:
XS GIS Cut Line= 3
      3744641.04     10560471.91      3744599.38     10560838.24
      3744812.92      10561268.8
#Sta/Elev= 30
  4710.8  270.21  4829.1  258.21    4850  257.56  4860.6  254.58  4880.2  252.31
  4930.5  249.37  4945.1  246.23  4980.8   246.8  4987.9  245.86  4990.6  245.36
  4993.9  245.86    5011   247.6  5028.7  246.69  5041.2  246.55  5051.3  249.63
  5083.4  250.44  5094.8  255.13  5117.3  251.87  5178.9  255.09  5206.9  253.83
  5251.7  255.44    5291  258.87  5363.8  261.02  5403.1  265.31  5425.5  263.16
  5431.1  266.04  5447.9  263.83  5453.5  265.88  5483.5  266.01  5560.1  275.54
#Mann= 5 ,-1 , 0
  4710.8     .05       0  4829.1     .12       0  4987.9     .07       0
  4993.9     .12       0  5028.7     .05       0
Bank Sta=4980.8,5011
XS Rating Curve= 0 ,0
Exp/Cntr=0.3,0.1

Type RM Length L Ch R = 1 ,5305    ,68,68,68
BEGIN DESCRIPTION:
Mapping XS fe611a5e
END DESCRIPTION:
XS GIS Cut Line= 3
      3744352.84     10560315.64      3744450.07     10560662.89
      3744792.08     10561251.43
#Sta/Elev= 30
  4698.9  249.61  4746.4  250.49  4875.4  247.03  4893.3  245.18  4908.3  241.06
  4911.1  240.56  4914.3  241.06  4927.4  245.03  4961.6  245.67  4978.4  243.73
    4984  242.42  5000.9  246.39  5015.2  243.96  5114.2  248.47  5167.2  247.43
  5195.2  250.16  5225.9  248.79  5386.5  253.86  5392.3  255.61  5402.2  254.41
    5408  257.58  5414.9  254.57  5472.8  255.68  5568.6  259.62  5643.1  265.63
  5648.9  264.13  5701.9   270.7  5707.6  268.62  5715.6   271.5  5740.2  273.74
#Mann= 5 ,-1 , 0
  4698.9     .05       0  4875.4     .08       0  4908.3     .04       0
  4914.3     .08       0  4978.4     .05       0
Bank Sta=4893.3,4927.4
XS Rating Curve= 0 ,0
Exp/Cntr=0.3,0.1

Type RM Length L Ch R = 1 ,5237    ,97,97,97
BEGIN DESCRIPTION:
UNT 088 IN BOCR 11.0
END DESCRIPTION:
XS GIS Cut Line= 3
      3744299.02     10560332.98      3744410.14     10560747.96
      3744413.61     10561062.24
#Sta/Elev= 30
  4723.4  246.98    4879     245  4927.1  245.21  4935.5  243.88  4940.7  245.82
  4975.6  241.52  4980.7  244.56  4981.6  244.37    4997  240.28  4999.8  239.78
    5003  240.28  5015.6  242.23  5020.8  245.28  5041.4  243.14  5050.5  244.04
  5055.6  246.01  5062.1  244.84  5072.5  246.29  5084.2  245.55  5103.5  244.68
  5113.9  245.32  5124.2  247.53  5130.5  246.28  5156.6  245.34  5185.2  249.21
  5283.5  253.56  5305.2  255.86  5325.2  261.19  5345.2  264.07  5467.3   273.7
#Mann= 8 ,-1 , 0
  4723.4     .05       0    4879     .16       0  4927.1     .08       0
  4981.6     .05       0    4997     .04       0    5003     .05       0
  5084.2     .16       0  5283.5     .05       0
Bank Sta=4980.7,5020.8
XS Rating Curve= 0 ,0
Exp/Cntr=0.3,0.1

Type RM Length L Ch R = 1 ,5140    ,352,352,352
BEGIN DESCRIPTION:
Mapping XS be4065b9
END DESCRIPTION:
XS GIS Cut Line= 3
       3744278.2     10560348.67      3744288.61     10560546.57
      3744153.19     10560959.77
#Sta/Elev= 30
    4781  246.45  4822.6  244.46  4913.7  243.29  4922.7   243.4  4983.7   239.4
  4992.4  232.79  4995.1  232.29  4998.4  232.79    5004  235.82  5014.6  238.94
    5022  240.58  5035.6  240.98  5059.1  245.89  5077.7  246.98  5090.9  249.18
  5111.7  250.02  5172.4  253.67  5218.3  257.87  5244.9  259.03  5256.6  261.98
  5267.1  262.45    5282  265.32  5298.7  265.63  5319.1  268.11  5345.6   270.3
  5372.2  269.89  5377.5  271.39  5409.3  268.37  5411.7  269.86    5414  269.86
#Mann= 6 ,-1 , 0
    4781     .05       0  4913.7     .16       0  4992.4     .07       0
  4998.4     .16       0  5111.7     .12       0  5319.1     .05       0
Bank Sta=4983.7,5014.6
XS Rating Curve= 0 ,0
Exp/Cntr=0.3,0.1

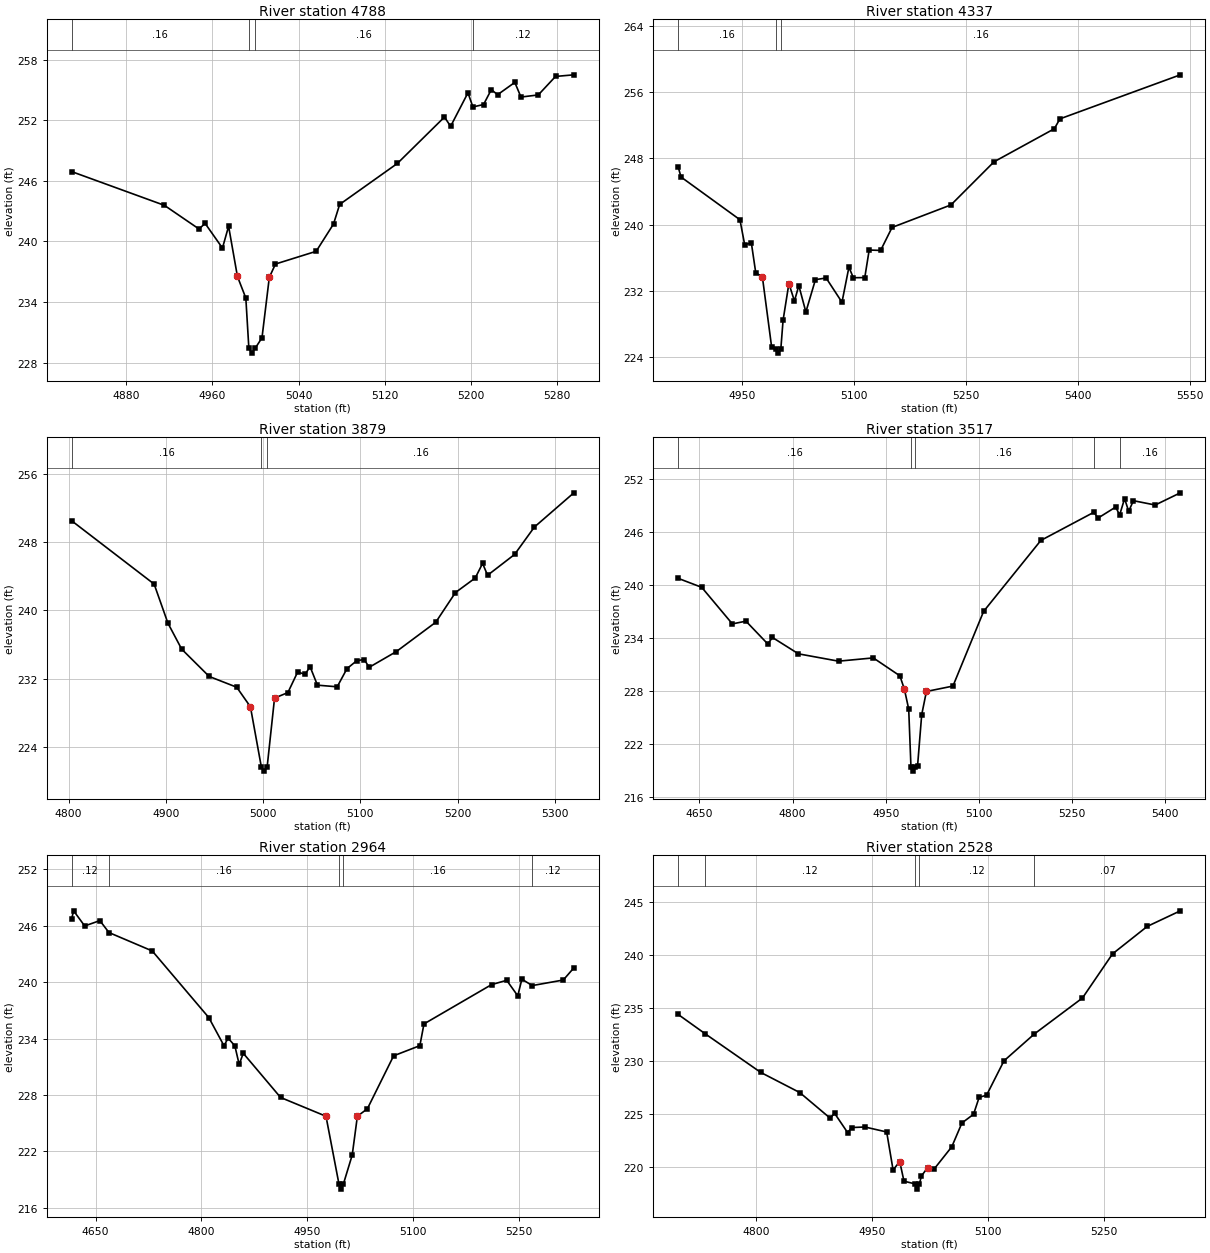
Type RM Length L Ch R = 1 ,4788    ,451,451,451
BEGIN DESCRIPTION:
UNT 088 IN BOCR 10.0
END DESCRIPTION:
XS GIS Cut Line= 2
      3744213.95     10560145.55      3743988.28     10560553.49
#Sta/Elev= 30
  4829.4  246.91  4915.5  243.57  4947.6  241.23  4953.3  241.78  4969.4  239.34
  4975.1   241.5  4983.3  236.53  4991.1  234.39  4993.9  229.44  4996.6  228.94
  4999.9  229.44  5006.1  230.46  5012.9  236.44  5018.6  237.76  5056.4  239.02
  5072.5  241.72  5078.2  243.66  5131.8  247.72  5175.5  252.31  5181.2  251.39
  5197.3  254.71  5201.9  253.31  5211.8  253.55    5219  255.03  5224.8  254.52
  5240.8  255.74  5246.5  254.29  5262.6   254.5  5278.6  256.33  5295.6  256.49
#Mann= 4 ,-1 , 0
  4829.4     .16       0  4993.9     .07       0  4999.9     .16       0
  5201.9     .12       0
Bank Sta=4983.3,5012.9
XS Rating Curve= 0 ,0
Exp/Cntr=0.3,0.1

Type RM Length L Ch R = 1 ,4337    ,458,458,458
BEGIN DESCRIPTION:
Mapping XS 9238da5e
END DESCRIPTION:
XS GIS Cut Line= 2
      3744018.68       10559865.      3743659.35     10560432.63
#Sta/Elev= 30
    4865     247  4868.9  245.76  4947.7   240.6    4954   237.6    4963  237.78
  4968.9  234.16  4977.7  233.71  4990.1  225.22  4996.4  224.98  4999.2  224.48
  5002.4  224.98  5005.4  228.45  5013.2  232.89  5020.6  230.78  5026.5  232.64
  5035.9  229.45  5048.7  233.36    5063  233.56  5084.2  230.63  5093.5  234.87
  5099.4  233.59  5114.7  233.61  5120.6  236.94  5135.9  236.89  5151.2  239.67
    5230  242.39  5287.6   247.6  5368.2  251.59  5375.8  252.79  5536.8  258.11
#Mann= 3 ,-1 , 0
    4865     .16       0  4996.4     .07       0  5002.4     .16       0
Bank Sta=4977.7,5013.2
XS Rating Curve= 0 ,0
Exp/Cntr=0.3,0.1

Type RM Length L Ch R = 1 ,3879    ,362,362,362
BEGIN DESCRIPTION:
UNT 088 IN BOCR 8.0
END DESCRIPTION:
XS GIS Cut Line= 3
       3743699.6     10559760.19      3743549.61     10559910.19
       3743499.6     10560210.23
#Sta/Elev= 30
  4803.1  250.49  4887.9  243.08  4902.1   238.5  4916.2  235.47  4944.5  232.27
  4972.8  231.01  4986.9  228.72  4998.1  221.69  5000.8  221.19  5004.1  221.69
  5011.7  229.74  5025.4  230.38  5035.5   232.8  5043.1  232.51  5048.2  233.42
  5055.8  231.25  5076.1  231.06  5086.2  233.19  5096.3  234.12  5103.9  234.25
    5109  233.34  5136.9  235.18  5177.4  238.61  5197.7  242.09    5218  243.79
  5225.6   245.5  5230.7  244.11  5258.5  246.55  5278.8  249.75  5319.4  253.76
#Mann= 3 ,-1 , 0
  4803.1     .16       0  4998.1     .07       0  5004.1     .16       0
Bank Sta=4986.9,5011.7
XS Rating Curve= 0 ,0
Exp/Cntr=0.3,0.1

Type RM Length L Ch R = 1 ,3517    ,553,553,553
BEGIN DESCRIPTION:
Mapping XS b50c4404
END DESCRIPTION:
XS GIS Cut Line= 2
      3743518.71     10559505.58      3742987.48     10560114.93
#Sta/Elev= 30
  4615.7  240.74  4653.7  239.72    4703  235.58  4724.9  235.89    4760  233.31
  4767.6  234.04  4809.4  232.19  4873.9  231.36  4929.9  231.73  4972.7   229.7
    4980  228.17  4986.9  225.93  4990.5  219.41  4993.3  218.91  4996.5  219.41
  5001.1  219.46  5007.8  225.29  5015.4  227.93  5058.1  228.54  5107.5     237
  5199.6  245.03    5285  248.22  5291.6  247.56  5320.1  248.81  5326.4  247.91
  5334.4  249.76    5341  248.33  5348.6  249.53  5383.7  249.04  5424.1  250.42
#Mann= 5 ,-1 , 0
  4615.7     .16       0  4990.5     .07       0  4996.5     .16       0
    5285     .12       0  5326.4     .16       0
Bank Sta=4980,5015.4
XS Rating Curve= 0 ,0
Exp/Cntr=0.3,0.1

Type RM Length L Ch R = 1 ,2964    ,436,436,436
BEGIN DESCRIPTION:
Mapping XS 461e11c7
END DESCRIPTION:
XS GIS Cut Line= 2
      3743409.35     10559245.16      3742794.71     10559604.56
#Sta/Elev= 30
    4616  246.73  4618.8  247.58  4634.5  245.97    4656  246.54  4668.9  245.27
  4730.3  243.31  4810.5  236.22    4832  233.23  4837.8  234.04  4847.4  233.22
  4853.5  231.24  4859.3  232.43  4912.2  227.73  4976.6  225.73  4995.1  218.48
  4997.9  217.98  5001.1  218.48  5013.8  221.61  5021.1  225.73  5035.3  226.53
  5072.5  232.16  5109.7  233.24  5115.5  235.55  5211.3  239.73  5232.8  240.19
  5248.5  238.54  5254.3  240.31    5269  239.63    5313  240.22    5328  241.51
#Mann= 5 ,-1 , 0
    4616     .12       0  4668.9     .16       0  4995.1     .07       0
  5001.1     .16       0    5269     .12       0
Bank Sta=4976.6,5021.1
XS Rating Curve= 0 ,0
Exp/Cntr=0.3,0.1

Type RM Length L Ch R = 1 ,2528    ,487,487,487
BEGIN DESCRIPTION:
Mapping XS e03a3e50
END DESCRIPTION:
XS GIS Cut Line= 2
      3743159.33     10558927.46      3742575.98     10559213.93
#Sta/Elev= 30
  4699.4  234.41  4734.5  232.58  4806.3  228.94  4856.8  227.04  4896.2  224.62
  4901.8  225.09  4918.7  223.27  4924.3  223.74  4941.2  223.79  4969.3  223.32
  4977.6  219.74  4986.2  220.53  4991.7  218.68  5005.7  218.43  5008.4  217.93
  5011.7  218.43  5014.2  219.16  5022.2  219.95  5031.1  219.86  5053.6  221.93
  5066.7  224.17  5081.7  224.99    5089  226.59  5098.6  226.79  5121.1  230.03
  5160.5  232.57  5222.7  235.96  5261.6  240.12  5306.5  242.71  5349.3  244.18
#Mann= 5 ,-1 , 0
  4699.4     .05       0  4734.5     .12       0  5005.7     .07       0
  5011.7     .12       0  5160.5     .07       0
Bank Sta=4986.2,5022.2
XS Rating Curve= 0 ,0
Exp/Cntr=0.3,0.1

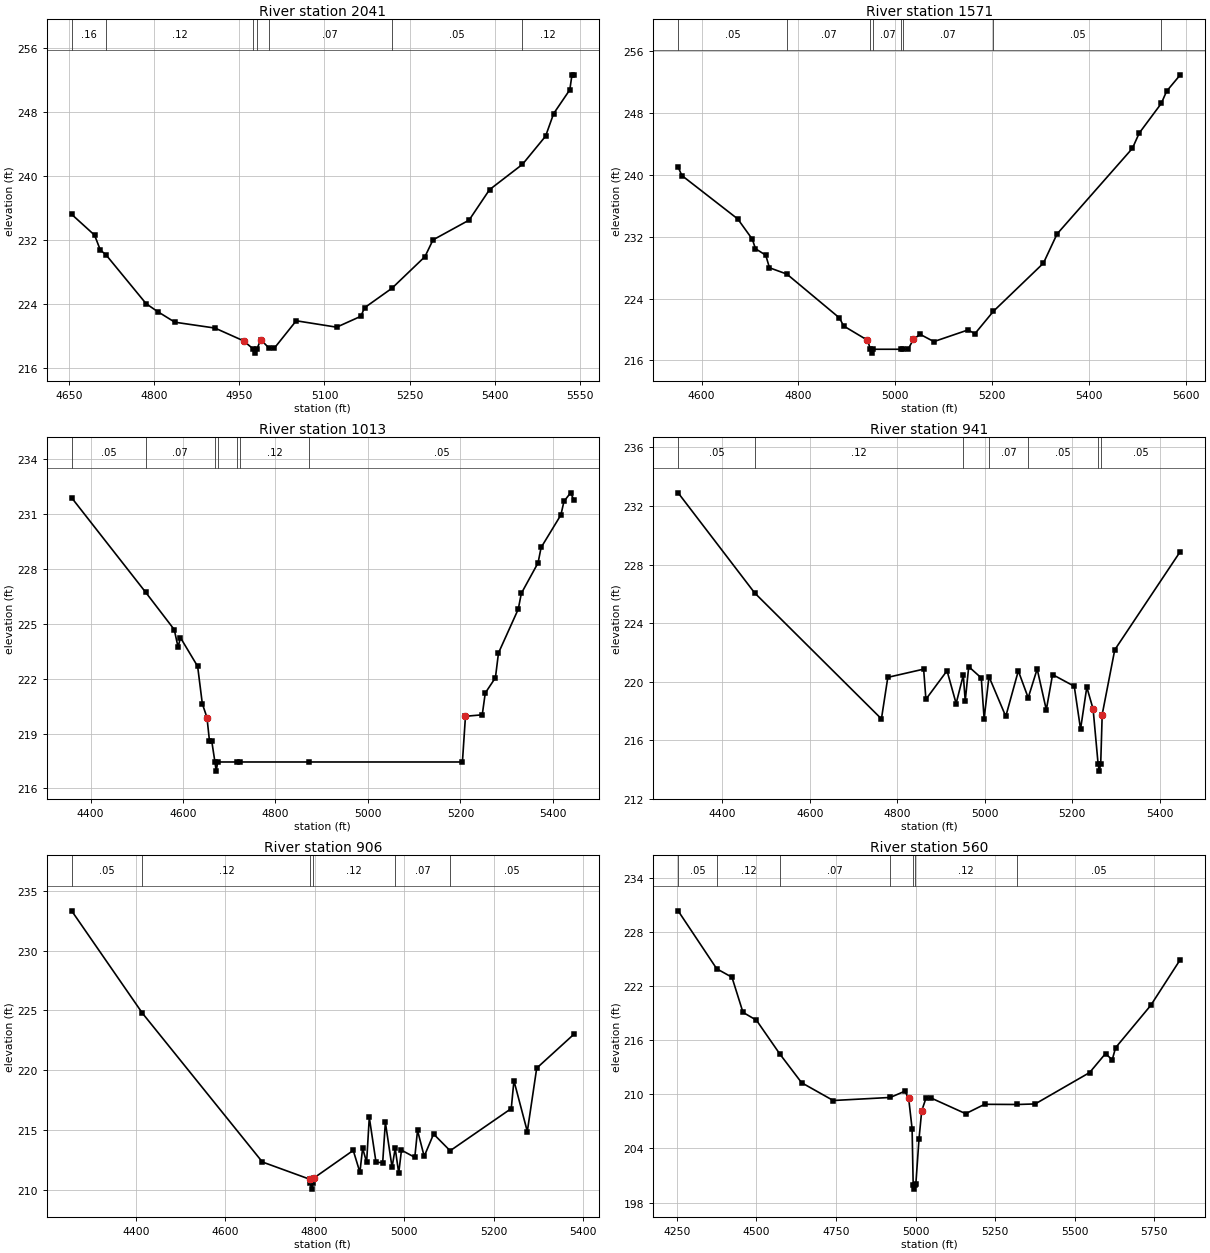
Type RM Length L Ch R = 1 ,2041    ,470,470,470
BEGIN DESCRIPTION:
UNT 088 IN BOCR 4.0
END DESCRIPTION:
XS GIS Cut Line= 3
      3743099.63     10558660.19      3742749.61     10558610.19
       3742349.6      10558960.2
#Sta/Elev= 30
  4654.4   235.2  4694.8   232.6  4704.9  230.75  4715.1  230.13  4785.7  224.04
  4805.9  223.06  4836.3  221.73    4907     221  4957.5   219.4  4974.7  218.37
  4977.4  217.87  4980.7  218.37  4987.8  219.54  5001.6  218.55  5011.3  218.46
  5050.2  221.91  5121.4  221.11  5164.1  222.47  5170.7  223.54  5218.9  225.97
  5277.1  229.92  5291.3  232.01  5354.9  234.48  5390.9  238.28  5448.9  241.44
  5489.7  244.96  5503.9  247.78  5532.4  250.75  5536.2  252.62  5539.5  252.62
#Mann= 7 ,-1 , 0
  4654.4     .16       0  4715.1     .12       0  4974.7     .07       0
  4980.7     .12       0  5001.6     .07       0  5218.9     .05       0
  5448.9     .12       0
Bank Sta=4957.5,4987.8
XS Rating Curve= 0 ,0
Exp/Cntr=0.3,0.1

Type RM Length L Ch R = 1 ,1571    ,558,558,558
BEGIN DESCRIPTION:
UNT 088 IN BOCR 3.0
END DESCRIPTION:
XS GIS Cut Line= 3
      3742949.62     10558110.18      3742549.61     10558360.19
       3742149.6     10558760.19
#Sta/Elev= 30
  4551.5  241.02  4559.2  239.92  4674.7   234.3  4704.8  231.68  4711.3  230.45
  4732.5  229.62  4740.2  227.99  4776.2  227.17  4884.6  221.51  4893.5  220.46
  4942.4  218.63  4948.9  217.45  4951.6  216.95  4954.9  217.45  5012.8  217.45
  5015.2  217.45  5026.7  217.45  5037.4  218.73  5051.5  219.38  5079.8  218.44
  5150.5  219.95  5164.6  219.46  5202.8  222.36  5306.1  228.58  5334.3  232.36
  5489.9  243.43    5504   245.4  5549.6  249.24  5560.6  250.82  5588.9  252.94
#Mann= 8 ,-1 , 0
  4551.5     .05       0  4776.2     .07       0  4948.9     .07       0
  4954.9     .07       0  5012.8     .12       0  5015.2     .07       0
  5202.8     .05       0  5549.6     .12       0
Bank Sta=4942.4,5037.4
XS Rating Curve= 0 ,0
Exp/Cntr=0.3,0.1

Type RM Length L Ch R = 1 ,1013    ,72,72,72
BEGIN DESCRIPTION:
UNT 088 IN BOCR 2.0
END DESCRIPTION:
XS GIS Cut Line= 3
       3742728.8     10558011.24      3742242.66     10557935.28
      3741791.23     10558321.59
#Sta/Elev= 30
  4359.1   231.9  4519.2  226.73    4581  224.69  4589.3  223.73  4594.4  224.25
  4631.6  222.68  4641.7  220.64  4651.8  219.88  4657.1  218.62  4662.2  218.58
    4669  217.45  4671.8  216.95    4675  217.45  4717.8  217.45  4723.2  217.45
    4873  217.45  5204.3  217.45  5210.9  219.95  5247.2  220.03  5253.7  221.22
  5275.7  222.06  5282.3  223.41  5325.1  225.81  5331.7  226.67  5367.9  228.34
  5374.5  229.18  5417.3  230.96  5423.9   231.7  5438.2  232.17  5445.3  231.79
#Mann= 7 ,-1 , 0
  4359.1     .05       0  4519.2     .07       0    4669    .033       0
    4675     .07       0  4717.8     .05       0  4723.2     .12       0
    4873     .05       0
Bank Sta=4651.8,5210.9
XS Rating Curve= 0 ,0
Exp/Cntr=0.3,0.1

Type RM Length L Ch R = 1 ,941     ,35,35,35
BEGIN DESCRIPTION:
Mapping XS 3e3df5ea
END DESCRIPTION:
XS GIS Cut Line= 4
       3742750.5     10557983.02      3742253.51     10557887.53
      3742155.85     10557917.91      3741736.99     10558258.65
#Sta/Elev= 30
  4298.6   232.9  4473.6  226.06  4763.5  217.45  4778.1  220.29    4860  220.85
  4865.2  218.79  4913.5  220.74  4934.3   218.5  4950.7  220.44  4955.1  218.68
  4963.1  221.02  4991.8  220.25  4998.3  217.45  5009.4  220.34  5047.8  217.62
  5076.5  220.73  5099.1  218.89  5119.6  220.86  5140.5  218.07  5154.8  220.48
  5204.4  219.68  5218.8  216.75  5233.1  219.62  5247.5  218.12  5258.9  214.38
  5261.6  213.88  5264.9  214.38  5268.3  217.75    5297  222.17  5446.9  228.89
#Mann= 7 ,-1 , 0
  4298.6     .05       0  4473.6     .12       0  4950.7     .05       0
  5009.4     .07       0  5099.1     .05       0  5258.9    .033       0
  5264.9     .05       0
Bank Sta=5247.5,5268.3
XS Rating Curve= 0 ,0
Exp/Cntr=0.3,0.1

Type RM Length L Ch R = 1 ,906     ,346,346,346
BEGIN DESCRIPTION:
Mapping XS f972a869
END DESCRIPTION:
XS GIS Cut Line= 3
      3742756.98     10557939.61      3742236.15     10557831.11
      3741747.86     10558163.15
#Sta/Elev= 30
  4256.8  233.33  4414.9  224.77  4683.1  212.32  4788.8  210.88  4790.4  210.55
  4793.1  210.05  4796.4  210.55  4799.4  211.01  4886.2  213.29  4901.1  211.46
  4907.2  213.47  4916.1   212.3  4922.1  216.05  4937.1   212.3    4952  212.26
    4958  215.64    4973  211.88    4980  213.46  4987.9  211.39    4994  213.31
  5023.8  212.71  5029.9  214.97  5044.8  212.79  5065.8  214.66  5102.8  213.26
  5239.4  216.79  5245.4  219.12  5275.3  214.87  5296.3  220.17  5379.3     223
#Mann= 6 ,-1 , 0
  4256.8     .05       0  4414.9     .12       0  4790.4     .07       0
  4796.4     .12       0    4980     .07       0  5102.8     .05       0
Bank Sta=4788.8,4799.4
XS Rating Curve= 0 ,0
Exp/Cntr=0.3,0.1

Type RM Length L Ch R = 1 ,560     ,0,0,0
BEGIN DESCRIPTION:
UNT 088 IN BOCR 1.0
END DESCRIPTION:
XS GIS Cut Line= 3
      3742737.42     10557911.82      3741904.12     10557562.88
      3741695.77     10558203.54
#Sta/Elev= 30
  4254.2  230.33  4375.4  223.91  4423.3  222.97  4457.9  219.08  4500.1  218.21
  4574.3  214.43  4642.1  211.28  4741.3  209.31  4920.5  209.65  4966.2  210.34
  4978.2  209.57    4989  206.18  4992.4  199.99  4995.1  199.49  4998.4  199.99
  5000.8  200.06  5010.7  205.05  5019.2  208.17  5032.4  209.55  5048.4  209.59
  5157.3  207.85  5216.7  208.89  5319.6  208.87  5375.6  208.93  5546.6  212.41
  5596.4  214.51  5617.5  213.82    5628  215.16  5738.2  219.84  5831.3  224.93
#Mann= 7 ,-1 , 0
  4254.2     .05       0  4375.4     .12       0  4574.3     .07       0
  4920.5     .12       0  4992.4     .07       0  4998.4     .12       0
  5319.6     .05       0
Bank Sta=4978.2,5019.2
XS Rating Curve= 0 ,0
Exp/Cntr=0.3,0.1

Chan Stop Cuts=-1
Use User Specified Reach Order=0
Composite Channel Slope=5