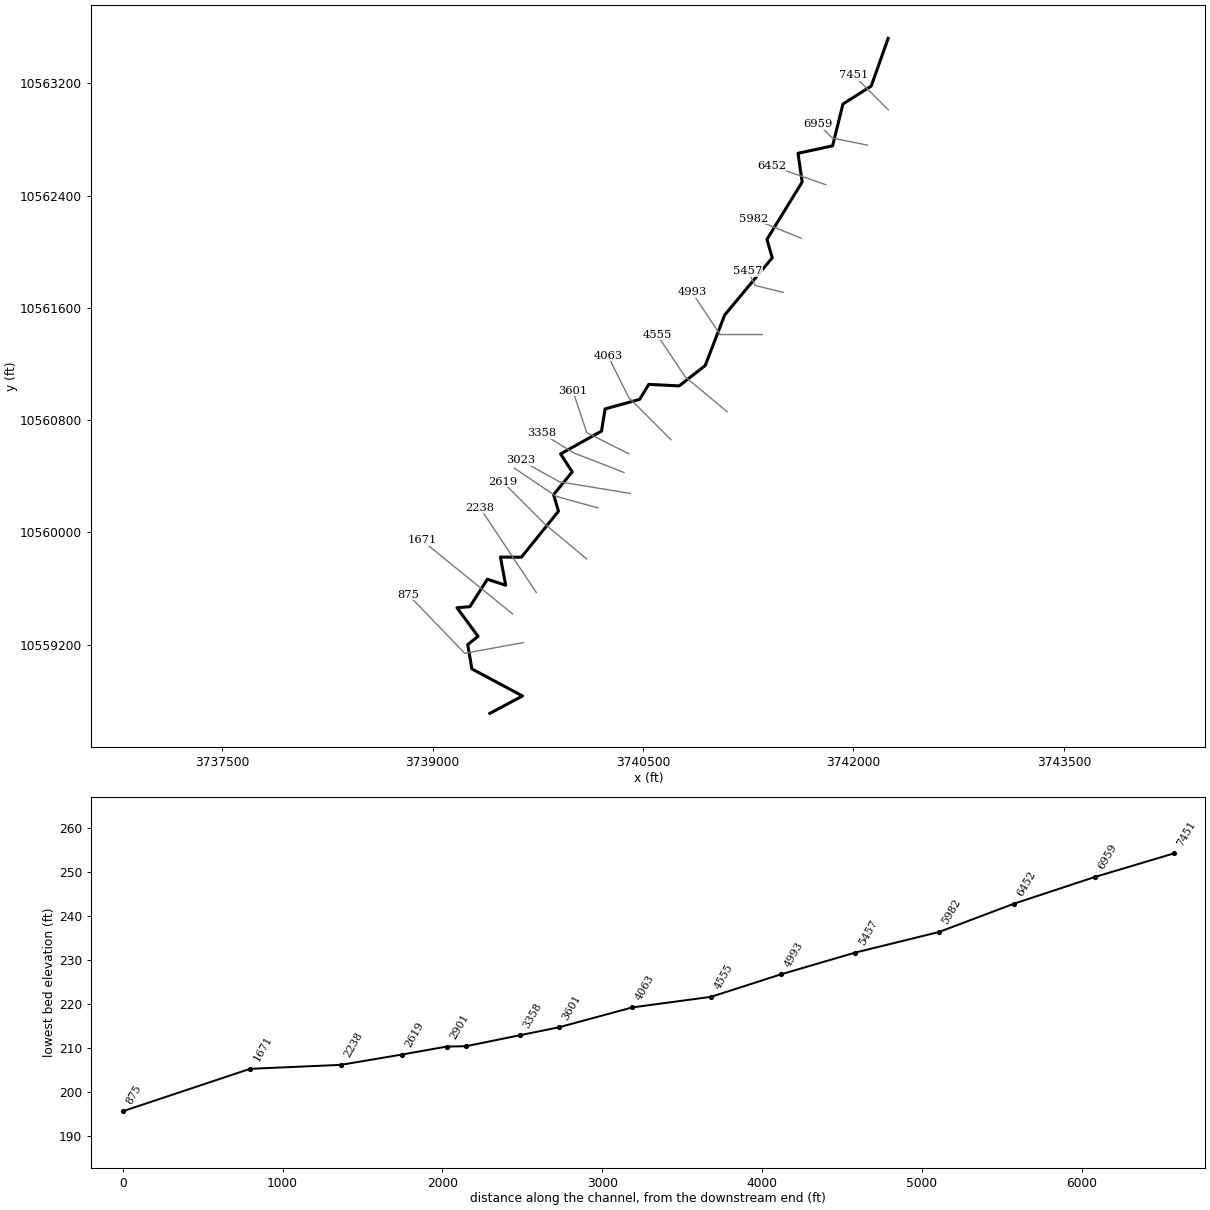
--- UNT 089 IN BOCR.prj (project) ---

Proj Title=UNT 089 IN BOCR Base Level Engineering
Current Plan=p01
Default Exp/Contr=0.3,0.1
English Units
Geom File=g01
Flow File=f01
Plan File=p01
BEGIN DESCRIPTION:
UNT 089 IN BOCR
END DESCRIPTION:

--- UNT 089 IN BOCR.p01 (plan) ---

Plan Title=Multiple Run
Short Identifier=Multiple
Geom File=g01
Flow File=f01
Subcritical Flow
K Sum by GR= 0
Std Step Tol= 0.01
Critical Tol= 0.01
Num of Std Step Trials= 20
Max Error Tol= 0.3
Flow Tol Ratio= 0.001
Split Flow NTrial= 30
Split Flow Tol= 0.02
Split Flow Ratio= 0.02
Log Output Level= 0
Friction Slope Method= 1
Unsteady Friction Slope Method= 2
Unsteady Bridges Friction Slope Method= 1
Parabolic Critical Depth
Global Vel Dist=  1 , 1 , 1
Global Log Level= 0
CheckData=True
Encroach Param= -1, 0, 0, 0
BEGIN DESCRIPTION:
Multiple Run
END DESCRIPTION:

--- UNT 089 IN BOCR.f01 (steady flow) ---

Flow Title=Multiple
Number of Profiles=7
Profile Names=10-year,25-year,50-year,1pct_min,100-year,1pct_plu,500-year
River Rch & RM= UNT 089 IN BOCR,Reach-1,7451
     520     706     861     773    1045    1413    1544
Boundary for River Rch & Prof#=UNT 089 IN BOCR,Reach-1,1
Up Type=0
Dn Type=3
Dn Slope=0.005
Boundary for River Rch & Prof#=UNT 089 IN BOCR,Reach-1,2
Up Type=0
Dn Type=3
Dn Slope=0.005
Boundary for River Rch & Prof#=UNT 089 IN BOCR,Reach-1,3
Up Type=0
Dn Type=3
Dn Slope=0.005
Boundary for River Rch & Prof#=UNT 089 IN BOCR,Reach-1,4
Up Type=0
Dn Type=3
Dn Slope=0.005
Boundary for River Rch & Prof#=UNT 089 IN BOCR,Reach-1,5
Up Type=0
Dn Type=3
Dn Slope=0.005
Boundary for River Rch & Prof#=UNT 089 IN BOCR,Reach-1,6
Up Type=0
Dn Type=3
Dn Slope=0.005
Boundary for River Rch & Prof#=UNT 089 IN BOCR,Reach-1,7
Up Type=0
Dn Type=3
Dn Slope=0.005

--- UNT 089 IN BOCR.g01 (geometry) ---

Geom Title=Existing Conditions

River Reach=UNT 089 IN BOCR,Reach-1
Reach XY= 30
      3742247.37     10563521.24      3742127.00     10563181.00
      3741925.25     10563053.00      3741851.50     10562755.00
      3741605.00     10562702.00      3741634.50     10562497.00
      3741383.50     10562088.00      3741421.50     10561957.00
      3741082.25     10561549.00      3740943.50     10561189.00
      3740758.25     10561044.00      3740541.50     10561055.00
      3740476.25     10560948.00      3740230.00     10560880.00
      3740204.50     10560722.00      3739912.75     10560559.00
      3739995.75     10560431.00      3739862.75     10560269.00
      3739897.75     10560151.00      3739633.50     10559823.00
      3739484.00     10559824.00      3739521.75     10559623.00
      3739390.75     10559666.00      3739266.52     10559470.62
      3739174.50     10559463.00      3739324.75     10559259.00
      3739251.00     10559200.00      3739280.50     10559027.00
      3739641.75     10558834.00      3739408.75     10558710.00

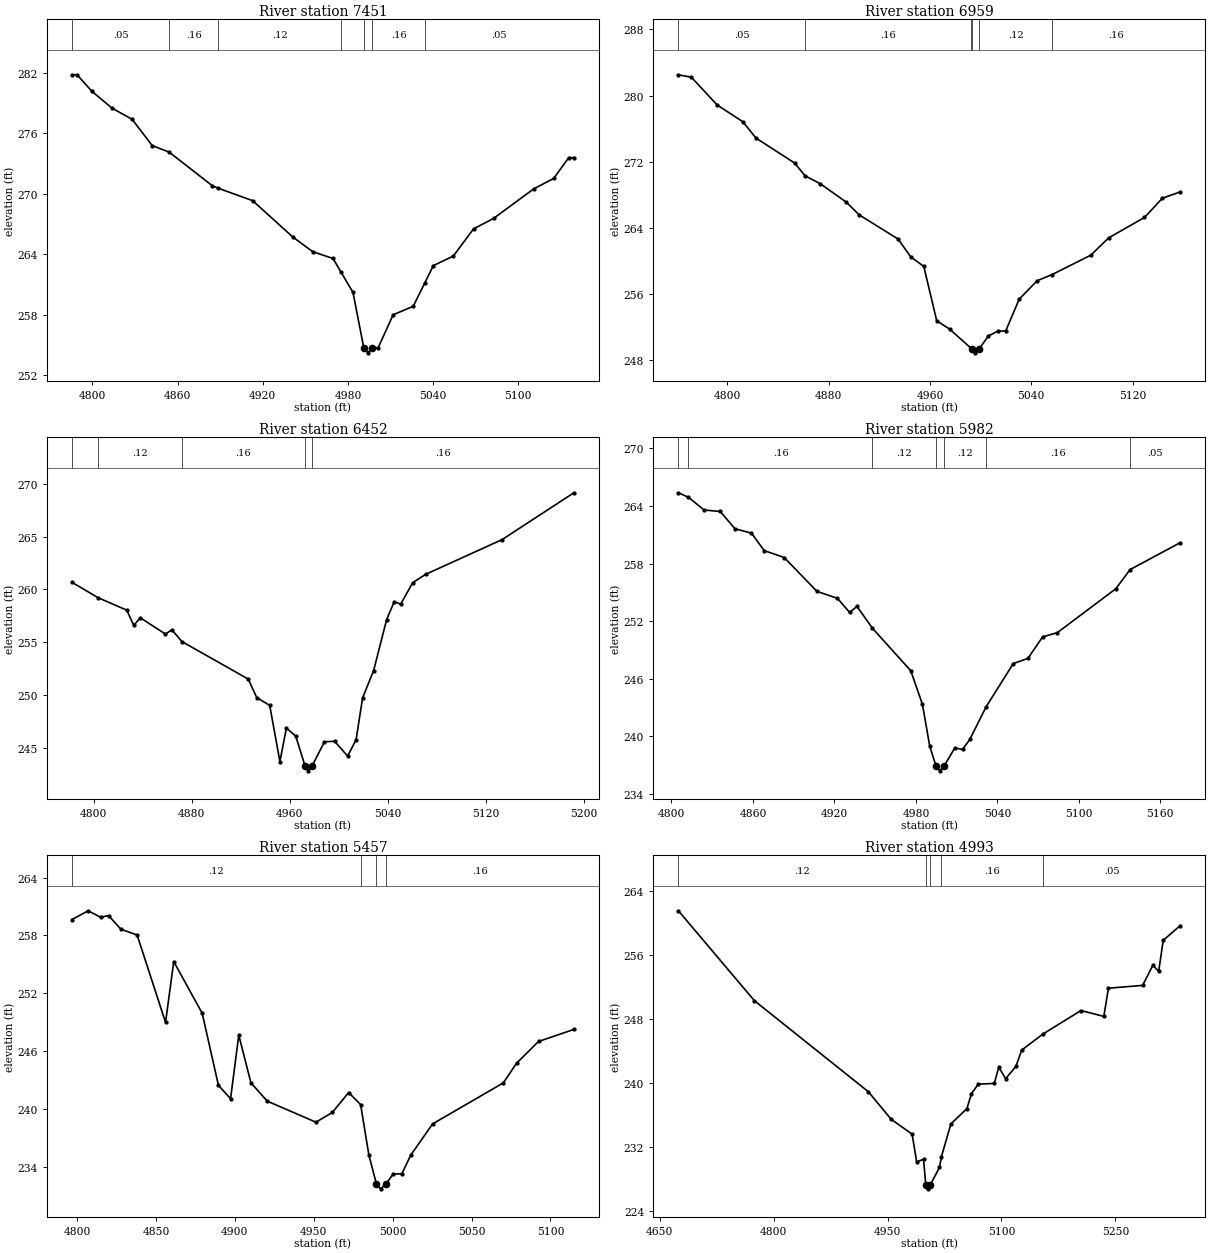
Type RM Length L Ch R = 1,7451,492,492,492
BEGIN DESCRIPTION:
UNT 089 IN BOCR 14.0
END DESCRIPTION:
XS GIS Cut Line= 3
      3742249.63     10563010.17      3742099.61     10563160.19
      3741999.59     10563260.21
#Sta/Elev= 30
  4785.6  281.83  4789.2  281.83  4799.8  280.17  4813.9  278.51  4828.0  277.41
  4842.2  274.79  4854.0  274.16  4884.6  270.80  4888.6  270.57  4912.9  269.33
  4941.2  265.72  4955.3  264.26  4969.5  263.59  4975.2  262.23  4983.6  260.22
  4991.2  254.72  4994.0  254.22  4997.2  254.72  5001.3  254.72  5011.9  258.00
  5026.0  258.84  5034.1  261.14  5040.2  262.88  5054.3  263.83  5068.5  266.53
  5082.6  267.56  5110.9  270.50  5125.0  271.54  5135.6  273.60  5139.2  273.60
#Mann=7,-1,0
  4785.6    0.05       0  4854.0    0.16       0  4888.6    0.12       0
  4975.2    0.16       0  4991.2    0.07       0  4997.2    0.16       0
  5034.1    0.05       0
Bank Sta=4991.2,4997.2
Exp/Cntr=0.3,0.1

Type RM Length L Ch R = 1,6959,507,507,507
BEGIN DESCRIPTION:
UNT 089 IN BOCR 13.0
END DESCRIPTION:
XS GIS Cut Line= 3
      3742099.65     10562760.18      3741849.61     10562810.19
      3741749.62     10562910.18
#Sta/Elev= 30
  4761.3  282.51  4771.5  282.22  4791.9  278.86  4812.3  276.82  4822.5  274.86
  4853.1  271.84  4861.3  270.30  4873.5  269.32  4893.9  267.11  4904.1  265.57
  4934.7  262.66  4944.9  260.48  4955.1  259.34  4965.3  252.77  4975.5  251.76
  4992.3  249.46  4992.9  249.39  4995.6  248.89  4998.9  249.39  5006.1  250.92
  5013.7  251.53  5019.8  251.53  5030.4  255.37  5044.6  257.61  5056.5  258.36
  5087.0  260.70  5101.1  262.79  5129.4  265.26  5143.6  267.59  5157.7  268.35
#Mann=6,-1,0
  4761.3    0.05       0  4861.3    0.16       0  4992.3    0.12       0
  4992.9    0.07       0  4998.9    0.12       0  5056.5    0.16       0
Bank Sta=4992.9,4998.9
Exp/Cntr=0.3,0.1

Type RM Length L Ch R = 1,6452,470,470,470
BEGIN DESCRIPTION:
Mapping XS ed1ebd16
END DESCRIPTION:
XS GIS Cut Line= 2
      3741801.81     10562478.46      3741415.48     10562613.02
#Sta/Elev= 30
  4782.4  260.68  4803.7  259.22  4827.1  258.04  4832.8  256.60  4838.1  257.32
  4858.6  255.78  4863.9  256.18  4872.0  255.07  4926.1  251.51  4933.0  249.76
  4943.6  249.02  4951.9  243.70  4957.2  246.87  4964.8  246.11  4972.3  243.32
  4975.1  242.82  4978.3  243.32  4988.2  245.57  4996.5  245.62  5007.1  244.22
  5014.0  245.76  5019.3  249.73  5028.3  252.32  5038.9  257.15  5045.1  258.84
  5050.4  258.61  5060.1  260.64  5070.6  261.43  5133.1  264.73  5191.5  269.16
#Mann=5,-1,0
  4782.4    0.16       0  4803.7    0.12       0  4872.0    0.16       0
  4972.3    0.07       0  4978.3    0.16       0
Bank Sta=4972.3,4978.3
Exp/Cntr=0.3,0.1

Type RM Length L Ch R = 1,5982,525,525,525
BEGIN DESCRIPTION:
Mapping XS b04903db
END DESCRIPTION:
XS GIS Cut Line= 2
      3741628.19     10562096.52      3741285.62     10562235.28
#Sta/Elev= 30
  4805.1  265.38  4812.5  264.91  4824.0  263.58  4835.9  263.43  4846.7  261.63
  4858.9  261.17  4868.3  259.35  4883.0  258.63  4907.1  255.10  4922.2  254.37
  4931.2  252.90  4936.6  253.53  4948.0  251.25  4976.2  246.82  4984.8  243.32
  4990.2  238.93  4994.8  236.88  4997.5  236.38  5000.8  236.88  5008.6  238.77
  5014.3  238.61  5019.7  239.66  5031.7  243.06  5051.7  247.57  5062.5  248.11
  5073.3  250.35  5084.1  250.79  5127.2  255.37  5137.7  257.37  5174.7  260.18
#Mann=7,-1,0
  4805.1    0.05       0  4812.5    0.16       0  4948.0    0.12       0
  4994.8    0.07       0  5000.8    0.12       0  5031.7    0.16       0
  5137.7    0.05       0
Bank Sta=4994.8,5000.8
Exp/Cntr=0.3,0.1

Type RM Length L Ch R = 1,5457,464,464,464
BEGIN DESCRIPTION:
UNT 089 IN BOCR 10.0
END DESCRIPTION:
XS GIS Cut Line= 3
      3741499.64     10561710.18      3741299.61     10561760.19
      3741249.61     10561860.20
#Sta/Elev= 30
  4796.8  259.65  4807.1  260.56  4814.9  259.89  4820.0  260.06  4827.8  258.65
  4838.1  258.04  4856.1  248.97  4861.3  255.28  4879.3  249.93  4889.6  242.44
  4897.3  241.05  4902.5  247.64  4910.2  242.70  4920.5  240.80  4951.4  238.61
  4961.8  239.62  4972.1  241.69  4979.7  240.44  4984.9  235.23  4989.7  232.19
  4992.4  231.69  4995.7  232.19  5000.4  233.24  5005.8  233.24  5011.4  235.18
  5025.3  238.43  5070.1  242.69  5078.5  244.73  5092.4  246.99  5114.8  248.24
#Mann=4,-1,0
  4796.8    0.12       0  4979.7    0.16       0  4989.7    0.07       0
  4995.7    0.16       0
Bank Sta=4989.7,4995.7
Exp/Cntr=0.3,0.1

Type RM Length L Ch R = 1,4993,438,438,438
BEGIN DESCRIPTION:
UNT 089 IN BOCR 9.0
END DESCRIPTION:
XS GIS Cut Line= 3
      3741349.66     10561410.19      3741049.61     10561410.19
      3740849.61     10561710.19
#Sta/Elev= 30
  4674.8  261.49  4774.8  250.26  4924.8  238.89  4954.8  235.45  4982.4  233.59
  4988.4  230.13  4997.4  230.45  5000.4  227.26  5003.1  226.76  5006.4  227.26
  5018.4  229.44  5021.0  230.78  5033.4  234.87  5054.5  236.78  5060.5  238.65
  5069.5  239.84  5090.5  239.92  5096.5  241.95  5105.5  240.51  5119.1  242.07
  5126.6  244.09  5154.8  246.11  5204.7  249.03  5234.7  248.30  5240.8  251.82
  5285.8  252.17  5299.3  254.69  5306.9  253.92  5312.9  257.80  5335.4  259.65
#Mann=5,-1,0
  4674.8    0.12       0  5000.4    0.07       0  5006.4    0.12       0
  5021.0    0.16       0  5154.8    0.05       0
Bank Sta=5000.4,5006.4
Exp/Cntr=0.3,0.1

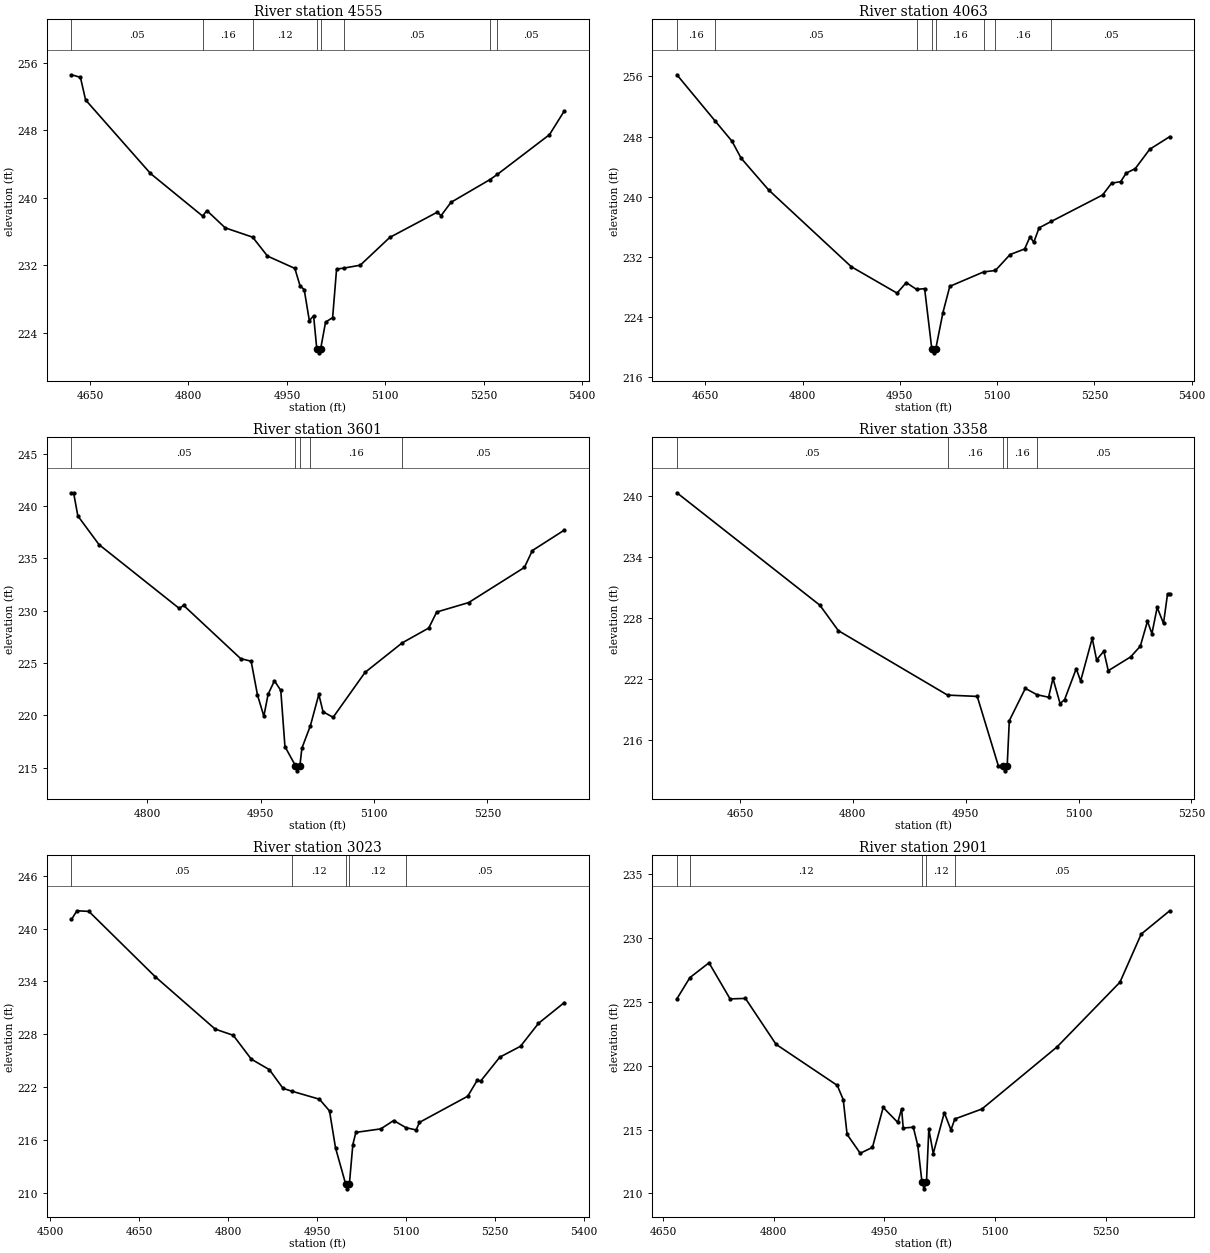
Type RM Length L Ch R = 1,4555,492,492,492
BEGIN DESCRIPTION:
UNT 089 IN BOCR 8.0
END DESCRIPTION:
XS GIS Cut Line= 3
      3741099.60     10560860.20      3740799.61     10561110.19
      3740599.64     10561410.15
#Sta/Elev= 30
  4621.7  254.58  4635.3  254.28  4643.2  251.60  4742.1  242.89  4821.5  237.85
  4828.0  238.50  4856.0  236.45  4897.8  235.35  4920.4  233.11  4962.1  231.65
  4969.9  229.62  4976.4  229.12  4984.2  225.46  4990.7  226.04  4995.5  222.15
  4998.3  221.65  5001.5  222.15  5008.9  225.28  5019.7  225.83  5025.7  231.57
  5037.3  231.69  5061.8  232.03  5106.8  235.32  5179.0  238.30  5185.0  237.90
  5200.0  239.47  5259.3  242.16  5270.7  242.78  5350.2  247.49  5372.7  250.29
#Mann=8,-1,0
  4621.7    0.05       0  4821.5    0.16       0  4897.8    0.12       0
  4995.5    0.07       0  5001.5    0.12       0  5037.3    0.05       0
  5259.3    0.16       0  5270.7    0.05       0
Bank Sta=4995.5,5001.5
Exp/Cntr=0.3,0.1

Type RM Length L Ch R = 1,4063,462,462,462
BEGIN DESCRIPTION:
UNT 089 IN BOCR 7.0
END DESCRIPTION:
XS GIS Cut Line= 3
      3740699.62     10560660.18      3740399.61     10560960.19
      3740249.61     10561260.20
#Sta/Elev= 30
  4606.3  256.22  4665.7  250.03  4691.2  247.39  4705.3  245.13  4747.7  240.91
  4875.0  230.71  4945.7  227.19  4959.9  228.59  4975.9  227.68  4988.2  227.79
  4999.3  219.75  5002.0  219.25  5005.3  219.75  5016.4  224.59  5027.0  228.09
  5079.2  230.01  5097.3  230.20  5120.0  232.32  5142.4  233.06  5150.8  234.70
  5156.4  233.93  5164.7  235.87  5183.5  236.72  5262.6  240.24  5276.5  241.81
  5290.5  242.01  5298.9  243.14  5312.9  243.74  5335.2  246.31  5366.0  247.99
#Mann=8,-1,0
  4606.3    0.16       0  4665.7    0.05       0  4975.9    0.16       0
  4999.3    0.07       0  5005.3    0.16       0  5079.2    0.05       0
  5097.3    0.16       0  5183.5    0.05       0
Bank Sta=4999.3,5005.3
Exp/Cntr=0.3,0.1

Type RM Length L Ch R = 1,3601,243,243,243
BEGIN DESCRIPTION:
UNT 089 IN BOCR 6.0
END DESCRIPTION:
XS GIS Cut Line= 3
      3740399.65     10560560.17      3740099.61     10560710.19
      3739999.60     10561010.20
#Sta/Elev= 30
  4699.9  241.27  4702.7  241.27  4708.3  239.06  4736.3  236.32  4842.5  230.22
  4848.1  230.52  4923.6  225.43  4937.5  225.18  4945.9  221.95  4954.3  219.93
  4959.9  222.02  4968.3  223.31  4976.7  222.39  4982.2  217.03  4996.0  215.21
  4998.8  214.71  5002.0  215.21  5004.6  216.87  5015.9  219.03  5027.0  222.01
  5032.6  220.35  5045.9  219.82  5088.1  224.11  5137.2  226.93  5172.4  228.35
  5182.9  229.88  5225.1  230.78  5298.9  234.14  5309.4  235.75  5351.6  237.70
#Mann=5,-1,0
  4699.9    0.05       0  4996.0    0.03       0  5002.0    0.05       0
  5015.9    0.16       0  5137.2    0.05       0
Bank Sta=4996,5002
Exp/Cntr=0.3,0.1

Type RM Length L Ch R = 1,3358,335,335,335
BEGIN DESCRIPTION:
Mapping XS ef3a67ac
END DESCRIPTION:
XS GIS Cut Line= 3
      3740364.06     10560426.91      3740004.64     10560567.55
      3739775.50     10560708.17
#Sta/Elev= 30
  4566.2  240.27  4756.2  229.21  4780.7  226.71  4925.8  220.37  4965.3  220.24
  4993.3  213.42  4999.1  213.42  5001.8  212.92  5005.1  213.42  5007.9  217.85
  5029.2  221.03  5044.6  220.41  5060.1  220.16  5065.9  222.01  5075.4  219.53
  5081.4  219.93  5096.8  222.96  5102.7  221.76  5118.1  225.96  5123.9  223.83
  5133.5  224.69  5139.4  222.77  5169.2  224.13  5182.0  225.18  5191.5  227.64
  5197.4  226.41  5204.4  229.00  5212.8  227.42  5218.2  230.34  5221.0  230.34
#Mann=5,-1,0
  4566.2    0.05       0  4925.8    0.16       0  4999.1    0.07       0
  5005.1    0.16       0  5044.6    0.05       0
Bank Sta=4999.1,5005.1
Exp/Cntr=0.3,0.1

Type RM Length L Ch R = 1,3023,122,122,122
BEGIN DESCRIPTION:
UNT 089 IN BOCR 5.0
END DESCRIPTION:
XS GIS Cut Line= 3
      3740408.55     10560277.94      3739905.10     10560360.41
      3739625.13     10560515.47
#Sta/Elev= 30
  4536.2  241.03  4545.3  242.02  4565.5  241.95  4677.0  234.55  4778.3  228.58
  4808.7  227.88  4839.1  225.17  4869.5  223.98  4892.6  221.85  4907.9  221.52
  4953.9  220.62  4970.9  219.29  4981.0  215.10  4998.3  210.94  5001.0  210.44
  5004.3  210.94  5010.2  215.46  5015.3  216.85  5057.3  217.25  5079.0  218.20
  5099.9  217.38  5116.8  217.13  5122.5  217.99  5203.8  220.96  5219.9  222.78
  5225.6  222.68  5257.7  225.39  5292.7  226.63  5322.9  229.23  5366.4  231.59
#Mann=5,-1,0
  4536.2    0.05       0  4907.9    0.12       0  4998.3    0.07       0
  5004.3    0.12       0  5099.9    0.05       0
Bank Sta=4998.3,5004.3
Exp/Cntr=0.3,0.1

Type RM Length L Ch R = 1,2901,282,282,282
BEGIN DESCRIPTION:
Mapping XS ba998832
END DESCRIPTION:
XS GIS Cut Line= 3
      3740179.11     10560174.33      3739882.25     10560256.36
      3739583.70     10560457.55
#Sta/Elev= 30
  4668.8  225.25  4686.4  226.91  4712.3  228.07  4740.9  225.24  4761.7  225.28
  4803.2  221.68  4886.2  218.46  4894.3  217.34  4899.5  214.62  4917.3  213.14
  4933.9  213.60  4948.4  216.73  4968.2  215.56  4973.4  216.63  4975.6  215.12
  4989.3  215.18  4995.3  213.75  5001.1  210.85  5003.8  210.35  5007.1  210.85
  5010.3  215.03  5016.3  213.12  5031.3  216.32  5040.3  214.97  5045.6  215.83
  5082.3  216.61  5184.2  221.48  5269.4  226.55  5298.2  230.32  5336.8  232.15
#Mann=5,-1,0
  4668.8    0.05       0  4686.4    0.12       0  5001.1    0.07       0
  5007.1    0.12       0  5045.6    0.05       0
Bank Sta=5001.1,5007.1
Exp/Cntr=0.3,0.1

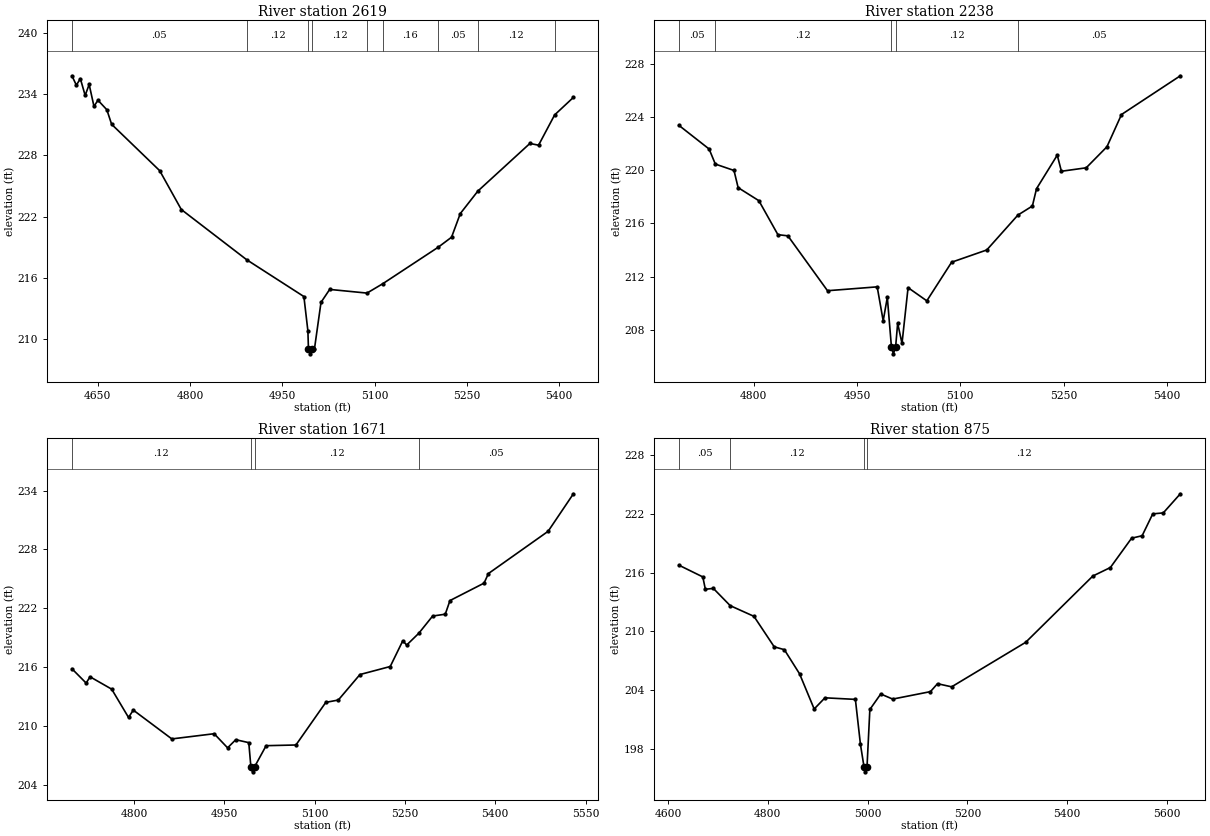
Type RM Length L Ch R = 1,2619,381,381,381
BEGIN DESCRIPTION:
UNT 089 IN BOCR 4.0
END DESCRIPTION:
XS GIS Cut Line= 3
      3740099.63     10559810.17      3739799.61     10560060.19
      3739499.61     10560360.18
#Sta/Elev= 30
  4608.3  235.81  4615.5  234.89  4622.0  235.53  4629.8  233.88  4636.3  234.96
  4644.1  232.81  4650.6  233.41  4665.0  232.48  4672.8  231.05  4750.9  226.50
  4786.0  222.69  4892.3  217.76  4985.2  214.15  4991.7  210.78  4992.6  209.03
  4995.3  208.53  4998.6  209.03  5002.4  209.03  5013.0  213.58  5027.1  214.85
  5087.7  214.49  5113.1  215.40  5203.2  218.98  5225.1  219.97  5239.3  222.29
  5267.9  224.50  5352.4  229.17  5366.5  229.00  5392.6  231.97  5423.1  233.69
#Mann=9,-1,0
  4608.3    0.05       0  4892.3    0.12       0  4992.6    0.07       0
  4998.6    0.12       0  5087.7    0.05       0  5113.1    0.16       0
  5203.2    0.05       0  5267.9    0.12       0  5392.6    0.05       0
Bank Sta=4992.6,4998.6
Exp/Cntr=0.3,0.1

Type RM Length L Ch R = 1,2238,567,567,567
BEGIN DESCRIPTION:
UNT 089 IN BOCR 3.0
END DESCRIPTION:
XS GIS Cut Line= 2
      3739740.17     10559570.48      3739337.52     10560176.63
#Sta/Elev= 30
  4691.5  223.36  4735.4  221.58  4744.4  220.45  4771.5  219.97  4777.5  218.68
  4807.6  217.70  4835.2  215.15  4849.7  215.06  4907.2  210.94  4979.3  211.23
  4988.0  208.68  4994.0  210.44  5000.0  206.70  5002.8  206.20  5006.0  206.70
  5009.0  208.50  5015.3  206.98  5024.1  211.17  5051.3  210.18  5087.3  213.08
  5138.3  214.00  5183.5  216.62  5204.5  217.30  5210.5  218.60  5240.6  221.12
  5246.6  219.91  5282.6  220.17  5312.7  221.75  5333.8  224.17  5419.2  227.08
#Mann=5,-1,0
  4691.5    0.05       0  4744.4    0.12       0  5000.0    0.07       0
  5006.0    0.12       0  5183.5    0.05       0
Bank Sta=5000,5006
Exp/Cntr=0.3,0.1

Type RM Length L Ch R = 1,1671,796,796,796
BEGIN DESCRIPTION:
UNT 089 IN BOCR 2.0
END DESCRIPTION:
XS GIS Cut Line= 2
      3739570.87     10559418.59      3738924.39     10559943.59
#Sta/Elev= 30
  4697.1  215.82  4720.7  214.36  4727.2  215.00  4763.1  213.74  4791.1  210.85
  4799.0  211.60  4863.0  208.66  4933.3  209.19  4955.6  207.75  4969.2  208.58
  4990.8  208.28  4994.3  205.80  4997.0  205.30  5000.3  205.80  5019.6  207.97
  5069.1  208.04  5118.7  212.39  5139.5  212.63  5175.4  215.23  5225.7  216.05
  5246.6  218.68  5253.0  218.24  5273.1  219.44  5296.1  221.20  5317.1  221.39
  5324.9  222.78  5381.5  224.56  5388.8  225.54  5487.9  229.85  5529.9  233.68
#Mann=4,-1,0
  4697.1    0.12       0  4994.3    0.07       0  5000.3    0.12       0
  5273.1    0.05       0
Bank Sta=4994.3,5000.3
Exp/Cntr=0.3,0.1

Type RM Length L Ch R = 1,875,0,0,0
BEGIN DESCRIPTION:
UNT 089 IN BOCR 1.0
END DESCRIPTION:
XS GIS Cut Line= 3
      3739647.61     10559214.58      3739229.24     10559138.19
      3738827.12     10559555.90
#Sta/Elev= 30
  4621.7  216.75  4669.7  215.55  4674.8  214.29  4690.8  214.38  4724.6  212.62
  4772.2  211.53  4812.8  208.42  4833.1  208.13  4863.6  205.67  4892.9  202.08
  4914.5  203.22  4975.5  203.06  4985.6  198.49  4992.8  196.17  4995.5  195.67
  4998.8  196.17  5004.5  202.03  5026.3  203.61  5050.3  203.09  5125.9  203.85
  5140.1  204.66  5168.4  204.34  5316.8  208.88  5451.4  215.64  5486.6  216.51
  5529.1  219.50  5550.2  219.75  5571.5  221.98  5592.6  222.08  5626.8  224.03
#Mann=4,-1,0
  4621.7    0.05       0  4724.6    0.12       0  4992.8    0.07       0
  4998.8    0.12       0
Bank Sta=4992.8,4998.8
Exp/Cntr=0.3,0.1

Chan Stop Cuts=-1