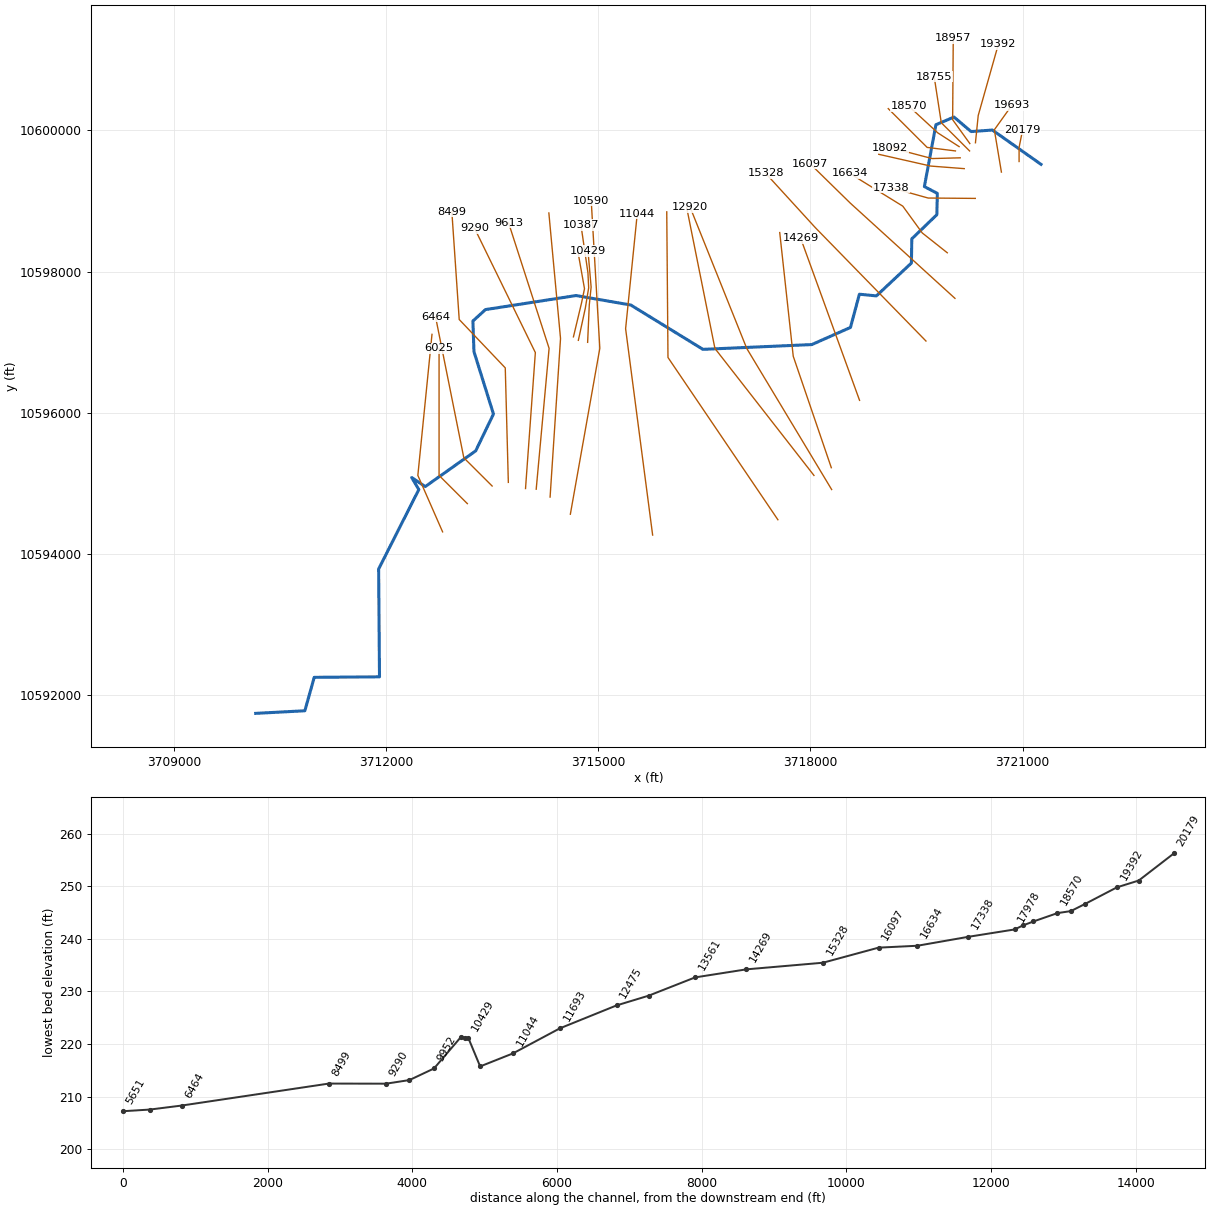
--- UNT 090 IN BOCR.prj (project) ---

Proj Title=UNT 090 IN BOCR Base Level Engineering
Current Plan=p01
Default Exp/Contr=0.3,0.1
English Units
Geom File=g01
Flow File=f01
Plan File=p01
Y Axis Title=Elevation
X Axis Title(PF)=Main Channel Distance
X Axis Title(XS)=Station
BEGIN DESCRIPTION:
UNT 090 IN BOCR
END DESCRIPTION:
DSS Export Rating Curves= 0
DSS Export Rating Curve Sorted= 0
DSS Export Volume Flow Curves= 0
DXF OffsetX= 0
DXF OffsetY= 0
DXF ScaleX= 1
DXF ScaleY= 10

--- UNT 090 IN BOCR.p01 (plan) ---

Plan Title=Multiple Run
Short Identifier=Multiple
Geom File=g01
Flow File=f01
Subcritical Flow
K Sum by GR= 0
Std Step Tol= 0.01
Critical Tol= 0.01
Num of Std Step Trials= 20
Max Error Tol= 0.3
Flow Tol Ratio= 0.001
Split Flow NTrial= 30
Split Flow Tol= 0.02
Split Flow Ratio= 0.02
Log Output Level= 0
Friction Slope Method= 1
Unsteady Friction Slope Method= 2
Unsteady Bridges Friction Slope Method= 1
Parabolic Critical Depth
Global Vel Dist=  1 , 1 , 1
Global Log Level= 0
CheckData=True
Encroach Param= -1, 0, 0, 0
BEGIN DESCRIPTION:
Multiple Run
END DESCRIPTION:

--- UNT 090 IN BOCR.f01 (steady flow) ---

Flow Title=Multiple
Program Version=4.10
Number of Profiles= 7
Profile Names=10-year,25-year,50-year,1pct_min,100-year,1pct_plu,500-year
River Rch & RM=UNT 090 IN BOCR,Reach-1         ,20179
     650     873    1054     934    1263    1708    1821
River Rch & RM=UNT 090 IN BOCR,Reach-1         ,14269
     813    1102    1340    1193    1614    2183    2353
River Rch & RM=UNT 090 IN BOCR,Reach-1         ,6464
    1008    1381    1690    1516    2050    2772    3029
River Rch & RM=UNT 090 IN BOCR,Reach-1         ,5040
    1391    1937    2398    2173    2939    3974    4434
River Rch & RM=UNT 090 IN BOCR,Reach-1         ,4109
    1391    1937    2398    2173    2939    3974    4434
Boundary for River Rch & Prof#=UNT 090 IN BOCR,Reach-1         , 1
Up Type= 0
Dn Type= 3
Dn Slope=0.006
Boundary for River Rch & Prof#=UNT 090 IN BOCR,Reach-1         , 2
Up Type= 0
Dn Type= 3
Dn Slope=0.006
Boundary for River Rch & Prof#=UNT 090 IN BOCR,Reach-1         , 3
Up Type= 0
Dn Type= 3
Dn Slope=0.006
Boundary for River Rch & Prof#=UNT 090 IN BOCR,Reach-1         , 4
Up Type= 0
Dn Type= 3
Dn Slope=0.006
Boundary for River Rch & Prof#=UNT 090 IN BOCR,Reach-1         , 5
Up Type= 0
Dn Type= 3
Dn Slope=0.006
Boundary for River Rch & Prof#=UNT 090 IN BOCR,Reach-1         , 6
Up Type= 0
Dn Type= 3
Dn Slope=0.006
Boundary for River Rch & Prof#=UNT 090 IN BOCR,Reach-1         , 7
Up Type= 0
Dn Type= 3
Dn Slope=0.006
DSS Import GetInterval= 0
DSS Import GetPeak= 0
DSS Import FillOption= 0

--- UNT 090 IN BOCR.g01 (geometry) ---

Geom Title=Existing Conditions
Program Version=4.10

River Reach=UNT 090 IN BOCR ,Reach-1
Reach XY= 30
       3721259.5       10599520.       3720572.5       10600006.
      3720270.75       10599985.      3720029.75       10600190.
        3719774.       10600082.       3719610.5       10599205.
        3719794.       10599108.      3719786.75       10598806.
      3719432.75       10598464.      3719427.25       10598121.
      3718932.25       10597655.        3718692.       10597679.
      3718565.75       10597208.       3718018.5       10596965.
      3716479.83     10596897.48        3715460.       10597526.
      3714686.43     10597660.19       3713405.5       10597461.
        3713228.       10597299.        3713243.       10596865.
      3713518.75       10595980.      3713267.25       10595458.
        3712554.       10594952.        3712363.       10595080.
       3712463.5       10594910.      3711895.25       10593783.
       3711907.5       10592255.      3710984.75       10592248.
      3710852.25       10591774.      3710157.25       10591737.

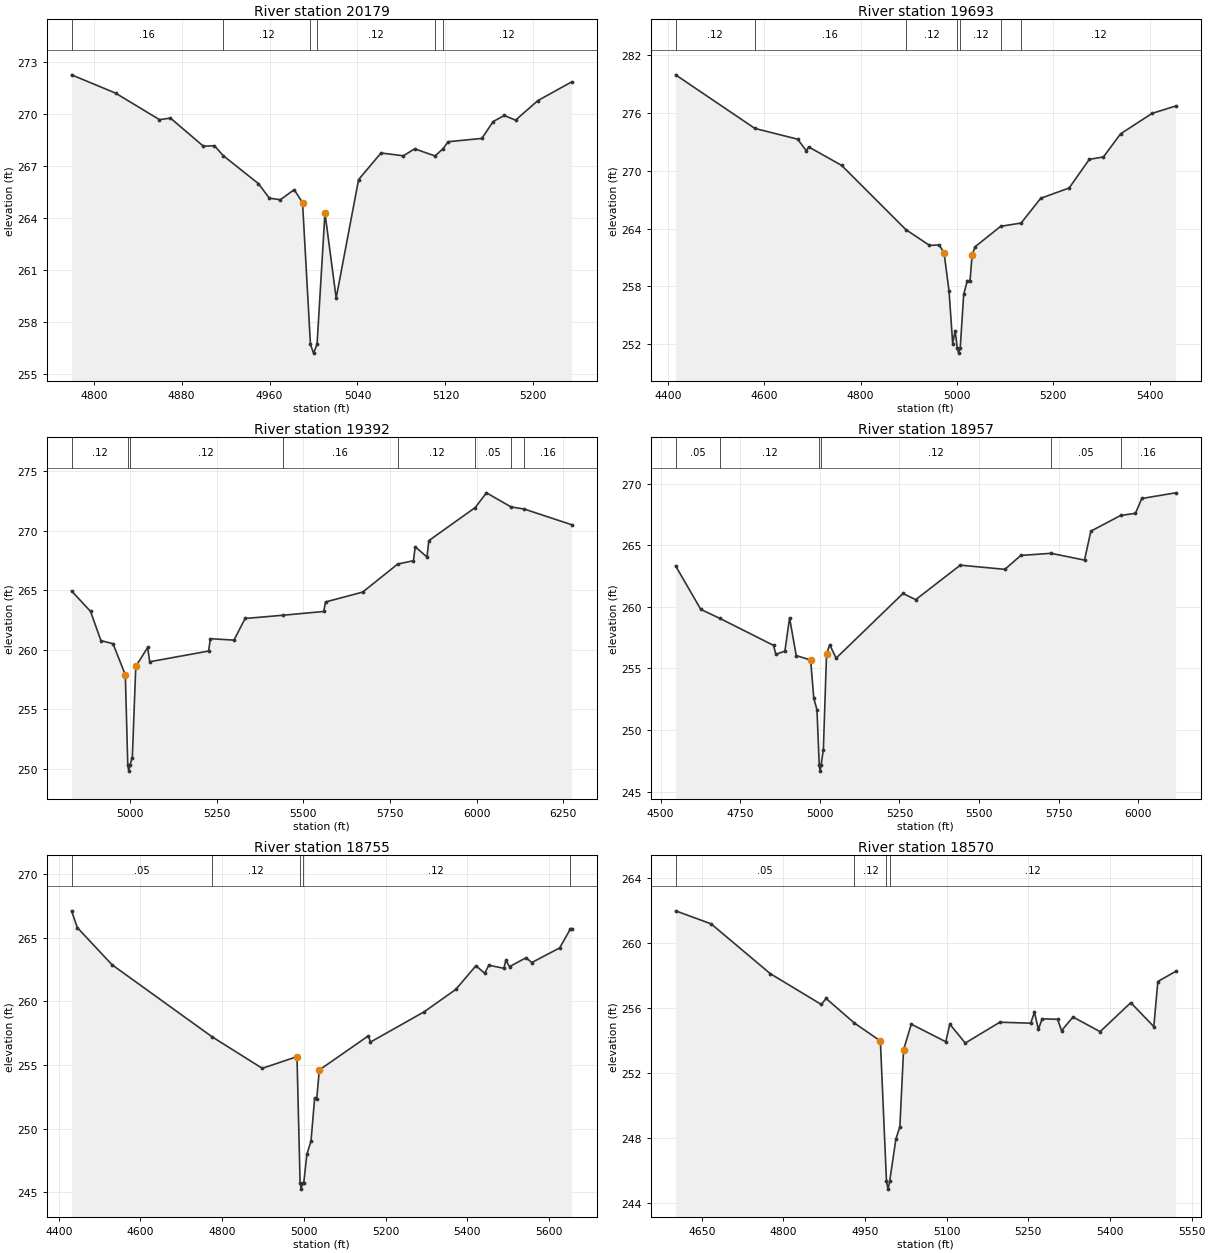
Type RM Length L Ch R = 1 ,20179   ,486,486,486
BEGIN DESCRIPTION:
UNT 090 IN BOCR 32.0
END DESCRIPTION:
XS GIS Cut Line= 3
      3720949.61     10599560.14      3720949.61     10599760.19
      3720999.61     10600010.19
#Sta/Elev= 30
  4779.8  272.25  4819.8   271.2  4859.8  269.67  4869.8  269.76  4899.8  268.14
  4909.8  268.17  4917.8   267.6  4949.8  265.99  4959.8  265.15  4969.8  265.06
  4982.4  265.64    4990  264.89  4997.2  256.73    5000  256.23  5003.2  256.73
  5010.4   264.3  5020.6   259.4    5041  266.22  5061.4  267.75  5081.8  267.59
    5092  267.99  5110.6  267.58  5117.7  267.99  5122.6   268.4  5153.2  268.59
  5163.4  269.56  5173.6  269.91  5183.8  269.64  5204.2  270.77  5234.8  271.84
#Mann= 6 ,-1 , 0
  4779.8     .16       0  4917.8     .12       0  4997.2     .07       0
  5003.2     .12       0  5110.6     .16       0  5117.7     .12       0
Bank Sta=4990,5010.4
XS Rating Curve= 0 ,0
Exp/Cntr=0.3,0.1

Type RM Length L Ch R = 1 ,19693   ,301,301,301
BEGIN DESCRIPTION:
UNT 090 IN BOCR 31.0
END DESCRIPTION:
XS GIS Cut Line= 3
      3720699.61     10599410.16      3720599.61     10600010.19
       3720849.6     10600360.17
#Sta/Elev= 30
  4415.8  279.99  4580.4  274.42  4669.3   273.3    4687  272.11  4692.1   272.5
  4760.5  270.58  4893.8  263.91    4943  262.27  4963.3  262.31  4973.4  261.45
  4983.6  257.52  4991.2  252.05  4996.2  253.41  5000.8  251.57  5003.6  251.07
  5006.8  251.57    5014  257.17  5021.6   258.6  5027.2   258.6  5031.5  261.25
  5037.6  262.12  5090.9  264.25  5133.3  264.59    5174  267.16    5233  268.23
  5274.8   271.2  5304.3  271.46  5339.9  273.86  5405.1  275.98  5454.2  276.75
#Mann= 7 ,-1 , 0
  4415.8     .12       0  4580.4     .16       0  4893.8     .12       0
  5000.8     .07       0  5006.8     .12       0  5090.9     .16       0
  5133.3     .12       0
Bank Sta=4973.4,5031.5
XS Rating Curve= 0 ,0
Exp/Cntr=0.3,0.1

Type RM Length L Ch R = 1 ,19392   ,435,435,435
BEGIN DESCRIPTION:
UNT 090 IN BOCR 30.0
END DESCRIPTION:
XS GIS Cut Line= 3
      3720332.62     10599825.81      3720371.69     10600212.14
      3720657.78     10601226.47
#Sta/Elev= 30
  4831.3  264.94    4886  263.22  4916.1  260.76  4950.9   260.5  4986.5  257.87
  4993.5  250.28  4996.3  249.78  4999.5  250.28  5006.6  250.91  5016.6  258.59
  5050.8  260.18  5056.8  258.98  5226.6  259.88  5231.8  260.92  5299.8   260.8
  5331.9  262.62  5439.8  262.89  5558.6  263.21  5563.8  264.01    5671  264.84
  5772.1   267.2  5817.4  267.48  5822.6  268.65  5856.6  267.79  5861.8  269.17
  5995.6  271.95    6028  273.19  6098.6  272.01  6137.5  271.82  6273.5  270.51
#Mann= 8 ,-1 , 0
  4831.3     .12       0  4993.5     .07       0  4999.5     .12       0
  5439.8     .16       0  5772.1     .12       0  5995.6     .05       0
  6098.6     .12       0  6137.5     .16       0
Bank Sta=4986.5,5016.6
XS Rating Curve= 0 ,0
Exp/Cntr=0.3,0.1

Type RM Length L Ch R = 1 ,18957   ,202,202,202
BEGIN DESCRIPTION:
Mapping XS 04cd43ae
END DESCRIPTION:
XS GIS Cut Line= 3
      3720253.22     10599814.49      3720010.18     10600153.01
      3720018.85     10601306.35
#Sta/Elev= 30
  4547.1  263.32  4626.1  259.79  4686.6  259.05  4854.5  256.87  4861.9  256.14
  4890.2   256.4  4904.9   259.1  4925.8  256.04    4971  255.68    4981  252.57
    4991  251.63    4998  247.16  5000.8  246.66    5004  247.16    5011  248.41
    5021  256.18    5031  256.92    5051  255.83    5261  261.08    5301  260.58
    5441  263.38    5581  263.04    5631  264.17    5726  264.34    5831  263.79
    5851  266.14  5944.2  267.41    5991  267.59    6011  268.79  6117.2  269.25
#Mann= 6 ,-1 , 0
  4547.1     .05       0  4686.6     .12       0    4998     .07       0
    5004     .12       0    5726     .05       0  5944.2     .16       0
Bank Sta=4971,5021
XS Rating Curve= 0 ,0
Exp/Cntr=0.3,0.1

Type RM Length L Ch R = 1 ,18755   ,185,185,185
BEGIN DESCRIPTION:
UNT 090 IN BOCR 29.0
END DESCRIPTION:
XS GIS Cut Line= 3
      3720249.63     10599710.17      3719849.61     10600110.19
       3719749.6     10600760.23
#Sta/Elev= 30
  4431.4   267.1  4445.6  265.78  4530.4  262.87    4775  257.22  4898.1  254.74
    4983  255.66  4990.6  245.76  4993.3  245.26  4996.6  245.76  4999.6  245.76
  5007.2  247.99  5017.3  249.03  5026.2  252.41  5031.3  252.33  5037.6  254.61
  5157.7  257.29  5162.8   256.8  5294.3  259.18  5371.5  260.93  5420.8  262.79
  5442.3   262.2  5452.4  262.83  5489.1  262.59  5494.1  263.22    5503  262.72
  5543.5  263.42  5557.4  263.04  5625.7  264.19  5651.2  265.64  5654.8  265.71
#Mann= 5 ,-1 , 0
  4431.4     .05       0    4775     .12       0  4990.6     .07       0
  4996.6     .12       0  5651.2     .05       0
Bank Sta=4983,5037.6
XS Rating Curve= 0 ,0
Exp/Cntr=0.3,0.1

Type RM Length L Ch R = 1 ,18570   ,332,332,332
BEGIN DESCRIPTION:
Mapping XS 4b7b36df
END DESCRIPTION:
XS GIS Cut Line= 3
      3720101.71     10599771.34      3719799.65     10599966.63
      3719389.09     10600346.02
#Sta/Elev= 30
  4601.9  261.97  4667.1  261.17  4775.9  258.11  4869.6  256.22  4878.3  256.59
  4930.3  255.08  4978.1  253.98  4989.3  245.38  4992.1  244.88  4995.3  245.38
  5006.5  247.94  5013.9  248.72  5020.7  253.43  5034.8  255.01  5098.3  253.93
  5105.7  255.01  5134.1  253.85  5197.6  255.13  5254.3  255.07  5261.2  255.75
  5268.4  254.69  5275.3  255.34  5303.6  255.31    5311  254.61    5332  255.45
  5381.8  254.55  5438.2  256.33  5480.5  254.86  5487.9  257.63  5520.6  258.25
#Mann= 4 ,-1 , 0
  4601.9     .05       0  4930.3     .12       0  4989.3     .07       0
  4995.3     .12       0
Bank Sta=4978.1,5020.7
XS Rating Curve= 0 ,0
Exp/Cntr=0.3,0.1

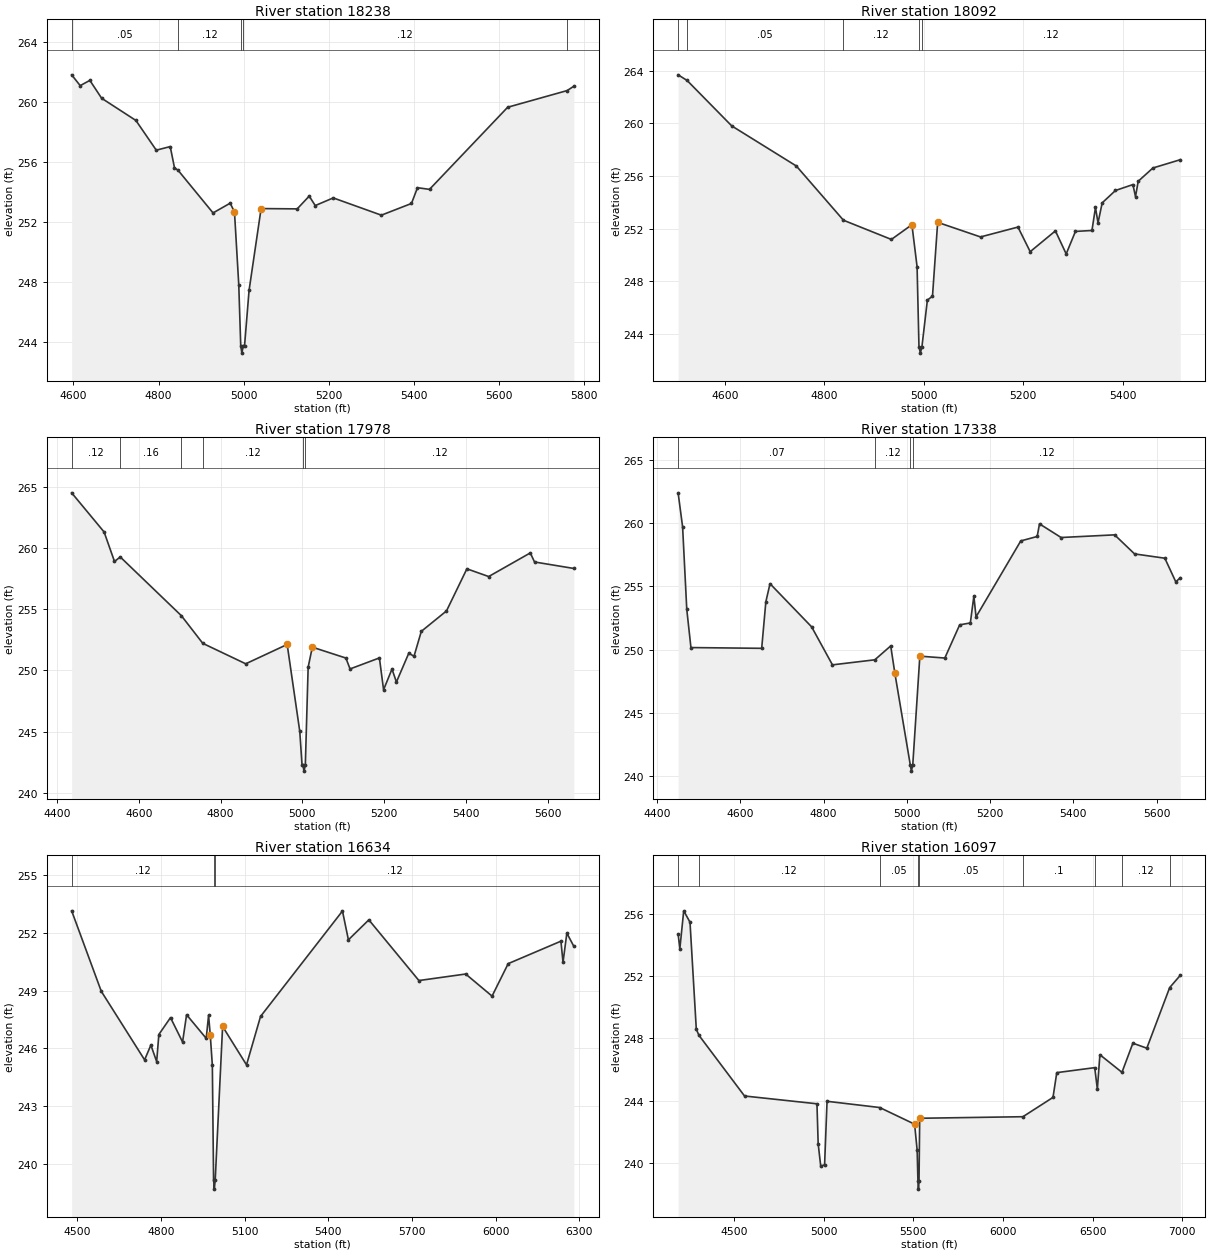
Type RM Length L Ch R = 1 ,18238   ,146,146,146
BEGIN DESCRIPTION:
UNT 090 IN BOCR 28.0
END DESCRIPTION:
XS GIS Cut Line= 3
      3720049.57     10599710.19      3719649.61     10599760.19
       3719099.6     10600310.19
#Sta/Elev= 30
  4595.7  261.83  4615.8  261.11  4638.5  261.46  4666.2  260.27  4746.8  258.79
  4794.7  256.81  4827.5  257.05  4837.5  255.64    4846  255.47  4928.2  252.63
  4968.5  253.28  4978.6  252.69  4988.7  247.83  4993.3  243.79    4996  243.29
  4999.3  243.79  5002.3  243.79  5012.9  247.47  5041.2  252.92  5126.1   252.9
  5154.3  253.75  5168.5  253.12  5210.9  253.63    5324  252.48  5394.8  253.26
  5408.9  254.31  5437.2   254.2    5621  259.67  5760.8  260.78  5776.6  261.07
#Mann= 5 ,-1 , 0
  4595.7     .05       0    4846     .12       0  4993.3     .07       0
  4999.3     .12       0  5760.8     .05       0
Bank Sta=4978.6,5041.2
XS Rating Curve= 0 ,0
Exp/Cntr=0.3,0.1

Type RM Length L Ch R = 1 ,18092   ,114,114,114
BEGIN DESCRIPTION:
Mapping XS 7c1644b0
END DESCRIPTION:
XS GIS Cut Line= 3
      3720117.33     10599612.47      3719718.93     10599602.05
      3719127.77      10599758.3
#Sta/Elev= 30
  4505.8  263.68  4523.9  263.25  4613.6   259.8  4743.6  256.75  4838.3  252.63
  4934.7  251.17    4976  252.29  4986.4   249.1  4990.2  243.03    4993  242.53
  4996.2  243.03  5007.1  246.56  5017.4  246.86  5027.8  252.47    5114  251.36
  5189.3  252.11  5213.9  250.24  5264.6  251.82  5286.3  250.07  5304.9  251.78
  5338.1  251.85  5345.2   253.6  5350.3  252.43  5358.7  253.95  5385.4  254.89
  5420.5  255.34  5425.7  254.42  5431.1  255.59  5460.7   256.6  5515.8  257.23
#Mann= 5 ,-1 , 0
  4505.8     .16       0  4523.9     .05       0  4838.3     .12       0
  4990.2     .07       0  4996.2     .12       0
Bank Sta=4976,5027.8
XS Rating Curve= 0 ,0
Exp/Cntr=0.3,0.1

Type RM Length L Ch R = 1 ,17978   ,640,640,640
BEGIN DESCRIPTION:
UNT 090 IN BOCR 27.0
END DESCRIPTION:
XS GIS Cut Line= 3
      3720174.12     10599459.13       3719700.2     10599495.58
      3718965.79     10599662.25
#Sta/Elev= 30
  4435.8  264.51  4515.2  261.31  4540.6   258.9  4554.7  259.27  4704.2  254.47
  4756.6  252.21  4861.6  250.54    4963  252.12  4993.8  245.02  4999.3  242.29
  5001.4  242.27  5004.2  241.77  5007.4  242.27  5014.3  250.26  5024.5   251.9
  5106.6  251.01  5116.8  250.12  5188.6  251.02  5198.8  248.42  5219.4  250.11
  5230.2  249.05  5260.4   251.4  5273.3  251.16  5291.1  253.19  5352.7  254.86
  5402.6   258.3  5455.9  257.67  5557.7   259.6    5568  258.86  5664.2  258.33
#Mann= 6 ,-1 , 0
  4435.8     .12       0  4554.7     .16       0  4704.2     .05       0
  4756.6     .12       0  5001.4     .07       0  5007.4     .12       0
Bank Sta=4963,5024.5
XS Rating Curve= 0 ,0
Exp/Cntr=0.3,0.1

Type RM Length L Ch R = 1 ,17338   ,704,704,704
BEGIN DESCRIPTION:
UNT 090 IN BOCR 26.0
END DESCRIPTION:
XS GIS Cut Line= 3
      3720330.38     10599037.25      3719663.74     10599042.46
       3719143.8     10599188.04
#Sta/Elev= 30
  4450.6  262.42  4461.4  259.72  4471.4  253.18  4481.4  250.16  4651.4   250.1
  4661.4  253.79  4671.4  255.22  4771.4   251.8  4821.4  248.79  4923.2  249.19
  4961.4  250.29  4971.4  248.12  5008.4  240.87  5011.1  240.37  5014.4  240.87
  5031.4  249.48  5091.4  249.33  5127.1  251.96  5152.7  252.11  5161.2  254.24
  5166.4  252.59  5273.9  258.61  5313.3  258.96  5318.9  259.96  5370.8  258.88
  5499.4  259.09  5547.3  257.58    5620  257.24  5646.3  255.37  5657.2  255.69
#Mann= 4 ,-1 , 0
  4450.6     .07       0  4923.2     .12       0  5008.4     .07       0
  5014.4     .12       0
Bank Sta=4971.4,5031.4
XS Rating Curve= 0 ,0
Exp/Cntr=0.3,0.1

Type RM Length L Ch R = 1 ,16634   ,537,537,537
BEGIN DESCRIPTION:
UNT 090 IN BOCR 25.0
END DESCRIPTION:
XS GIS Cut Line= 4
      3719934.56     10598266.42      3719580.41     10598547.66
      3719305.42     10598927.41      3718556.61     10599390.44
#Sta/Elev= 30
  4479.1  253.16  4585.4  248.97  4740.8   245.4  4763.3  246.17  4784.1  245.31
  4791.9  246.72  4833.7   247.6    4877  246.33  4891.4  247.75  4961.8  246.52
  4970.3  247.72  4976.5  246.67  4983.8  245.12  4988.2  239.17  4990.9  238.67
  4994.2  239.17  5020.6  247.14  5106.4  245.14  5156.7  247.66  5450.6  253.15
  5471.9  251.65  5545.2  252.69  5724.8  249.53  5892.6  249.87  5987.2  248.72
  6045.1  250.41  6234.3  251.58  6241.8  250.48  6255.5     252  6280.6  251.31
#Mann= 3 ,-1 , 0
  4479.1     .12       0  4988.2     .07       0  4994.2     .12       0
Bank Sta=4976.5,5020.6
XS Rating Curve= 0 ,0
Exp/Cntr=0.3,0.1

Type RM Length L Ch R = 1 ,16097   ,769,769,769
BEGIN DESCRIPTION:
Mapping XS bb78aca4
END DESCRIPTION:
XS GIS Cut Line= 3
      3720043.21     10597620.16      3718563.96     10598969.74
      3717994.37     10599529.08
#Sta/Elev= 30
  4187.9   254.7  4197.5  253.74  4219.1  256.18  4254.2  255.45  4289.3  248.58
  4303.8  248.19  4558.3  244.29  4962.2  243.79    4969  241.22  4983.2  239.79
  5004.8  239.87  5018.5  243.95  5312.1  243.55  5506.8  242.48    5521  240.81
  5525.4  238.81  5528.2  238.31  5531.4  238.81  5535.2  242.86  6110.9  242.96
  6278.6   244.2  6299.7  245.79  6511.3  246.11    6526  244.73  6540.2  246.94
  6663.2  245.81  6724.1  247.68  6801.8  247.36  6929.3  251.25  6988.6  252.04
#Mann= 9 ,-1 , 0
  4187.9     .05       0  4303.8     .12       0  5312.1     .05       0
  5525.4     .07       0  5531.4     .05       0  6110.9      .1       0
  6511.3     .05       0  6663.2     .12       0  6929.3     .05       0
Bank Sta=5506.8,5535.2
XS Rating Curve= 0 ,0
Exp/Cntr=0.3,0.1

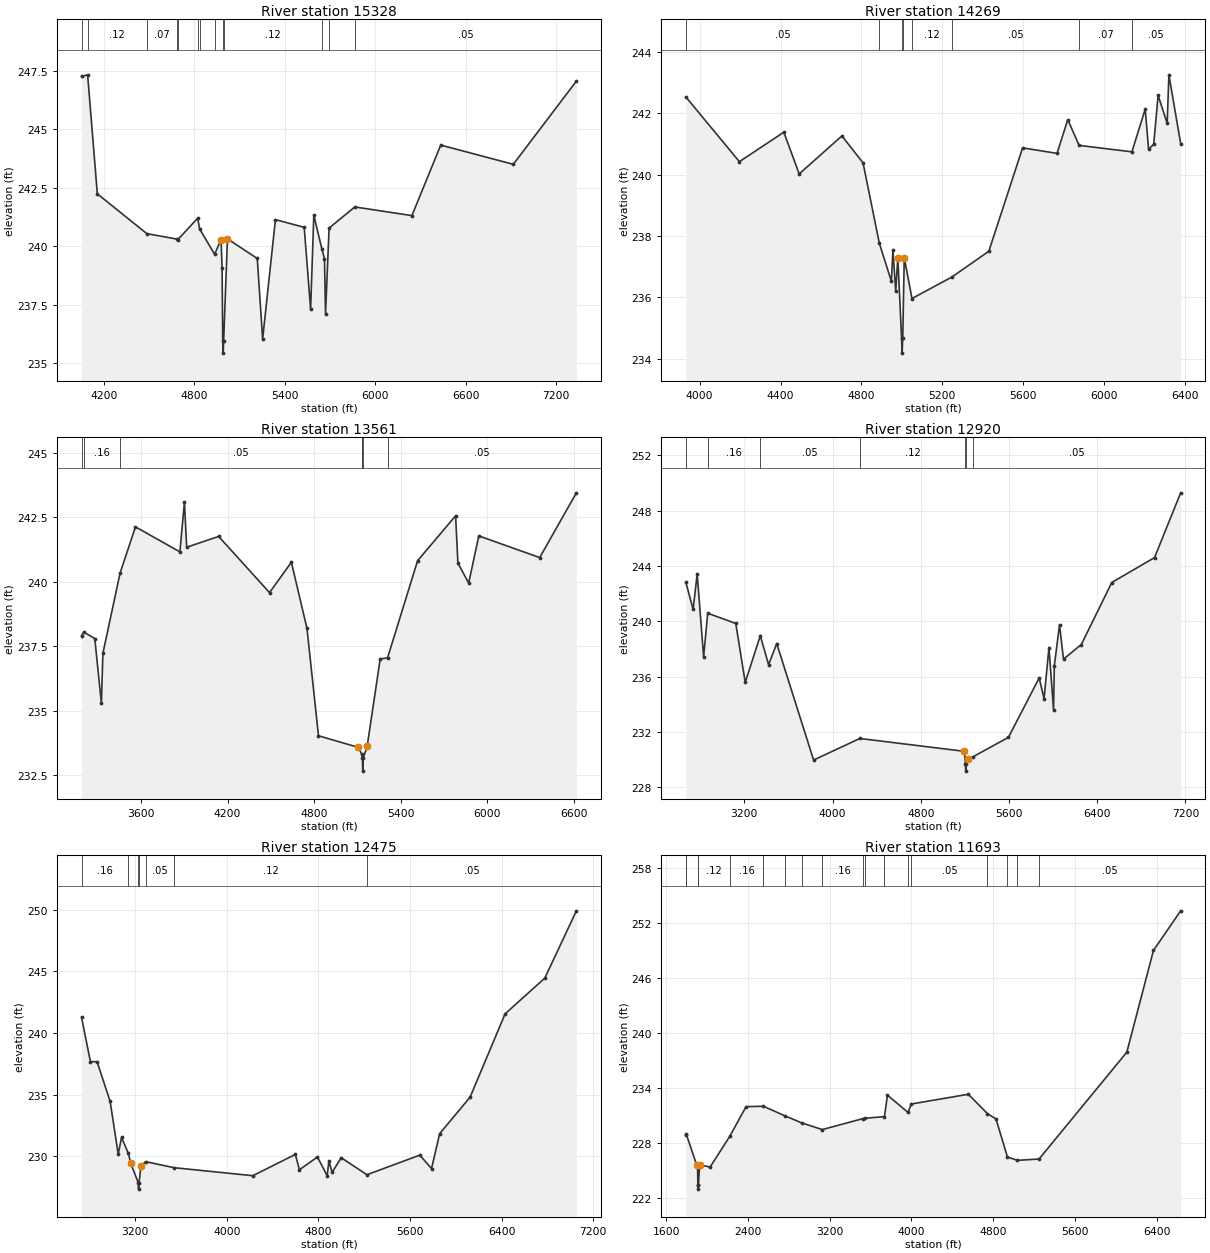
Type RM Length L Ch R = 1 ,15328   ,1059,1059,1059
BEGIN DESCRIPTION:
Mapping XS b9073c76
END DESCRIPTION:
XS GIS Cut Line= 3
      3719632.99     10597015.45      3718069.17     10598622.51
      3717369.11     10599390.45
#Sta/Elev= 30
  4053.2  247.25  4093.6  247.32  4157.9  242.24  4486.2  240.54  4684.4  240.31
  4690.8  240.28  4823.7   241.2  4836.3  240.74  4935.9  239.66  4978.3  240.29
  4985.3  239.06  4989.5  235.94  4992.2  235.44  4995.5  235.94  5020.8  240.32
  5218.6  239.48  5254.1  236.04    5339  241.14  5529.8  240.81  5572.3  237.32
  5593.6  241.33  5646.4   239.9  5664.3  239.47  5671.3  237.12  5694.9  240.78
  5865.8  241.68  6244.1  241.31  6435.2  244.32  6916.3   243.5  7334.7  247.05
#Mann= 13 ,-1 , 0
  4053.2     .05       0  4093.6     .12       0  4486.2     .07       0
  4684.4     .05       0  4690.8     .07       0  4823.7     .12       0
  4836.3     .07       0  4935.9     .12       0  4989.5     .07       0
  4995.5     .12       0  5646.4     .16       0  5694.9      .1       0
  5865.8     .05       0
Bank Sta=4978.3,5020.8
XS Rating Curve= 0 ,0
Exp/Cntr=0.3,0.1

Type RM Length L Ch R = 1 ,14269   ,708,708,708
BEGIN DESCRIPTION:
Mapping XS 3ff99e64
END DESCRIPTION:
XS GIS Cut Line= 2
      3718694.18     10596174.57      3717860.83     10598474.98
#Sta/Elev= 30
  3931.9  242.53  4196.7  240.42  4416.5  241.38  4492.4  240.02  4703.7  241.26
  4808.1  240.38  4888.7  237.76  4948.3  236.52  4955.9  237.55  4969.6   236.2
  4980.2  237.29  4998.5  234.68  5001.2  234.18  5004.5  234.68  5011.9  237.29
  5050.1  235.96  5247.3  236.66  5430.1   237.5  5597.1  240.87  5767.3  240.69
  5820.4  241.79  5876.6  240.95  6137.4  240.74  6203.3  242.13    6220  240.82
  6245.3  240.99  6267.1  242.58  6311.9  241.67  6320.3  243.25  6378.6  241.01
#Mann= 8 ,-1 , 0
  3931.9     .05       0  4888.7     .16       0  4998.5     .07       0
  5004.5     .16       0  5050.1     .12       0  5247.3     .05       0
  5876.6     .07       0  6137.4     .05       0
Bank Sta=4980.2,5011.9
XS Rating Curve= 0 ,0
Exp/Cntr=0.3,0.1

Type RM Length L Ch R = 1 ,13561   ,641,641,641
BEGIN DESCRIPTION:
UNT 090 IN BOCR 24.0
END DESCRIPTION:
XS GIS Cut Line= 3
      3718294.86     10595219.77      3717756.67      10596799.6
       3717565.7     10598553.04
#Sta/Elev= 30
  3187.1   237.9  3202.5  238.04  3279.1  237.79  3324.9  235.28  3335.4  237.22
  3454.6  240.33  3561.3  242.12  3869.5  241.15  3900.9  243.08  3916.5  241.33
  4138.3  241.75  4491.3  239.57  4642.8  240.75  4751.1  238.18  4830.9  234.02
  5108.2  233.57  5131.1   233.3  5135.3  233.15  5138.1  232.65  5141.3  233.15
  5168.5  233.61    5259     237    5310  237.04  5518.6  240.81  5782.1  242.55
    5798  240.72  5872.7  239.94  5943.1  241.77  6365.5  240.93  6619.9  243.44
#Mann= 7 ,-1 , 0
  3187.1     .05       0  3202.5     .16       0  3454.6     .05       0
  5131.1     .12       0  5135.3     .03       0  5141.3     .12       0
    5310     .05       0
Bank Sta=5108.2,5168.5
XS Rating Curve= 0 ,0
Exp/Cntr=0.3,0.1

Type RM Length L Ch R = 1 ,12920   ,445,445,445
BEGIN DESCRIPTION:
UNT 090 IN BOCR 23.0
END DESCRIPTION:
XS GIS Cut Line= 3
      3718299.62     10594910.17      3717099.61     10596910.19
       3716299.6     10598910.22
#Sta/Elev= 30
  2670.2  242.83  2736.3  240.87  2773.2  243.43  2831.5  237.43  2868.5  240.59
  3123.1  239.85  3208.6  235.59  3345.4  238.97  3420.5  236.87  3494.3   238.4
  3828.6  229.98  4247.8  231.54  5196.5  230.61  5205.6  229.68  5208.3  229.18
  5211.6  229.68  5227.4  230.06  5276.7  230.23    5595  231.62  5873.7  235.91
  5918.1  234.42  5962.5  238.11  6004.2  233.59    6011  236.78  6058.1  239.75
  6094.4  237.27    6256  238.33    6532  242.81  6919.7  244.61  7156.7  249.29
#Mann= 7 ,-1 , 0
  2670.2     .05       0  2868.5     .16       0  3345.4     .05       0
  4247.8     .12       0  5205.6     .07       0  5211.6     .12       0
  5276.7     .05       0
Bank Sta=5196.5,5227.4
XS Rating Curve= 0 ,0
Exp/Cntr=0.3,0.1

Type RM Length L Ch R = 1 ,12475   ,782,782,782
BEGIN DESCRIPTION:
UNT 090 IN BOCR 22.0
END DESCRIPTION:
XS GIS Cut Line= 3
      3718049.61     10595110.19      3716649.61     10596910.19
       3716249.6     10598910.23
#Sta/Elev= 30
    2732  241.26  2809.8  237.67  2867.7  237.66  2981.8  234.44  3052.3  230.15
  3081.3  231.52  3140.7  230.22    3160  229.47  3227.6  227.82  3230.3  227.32
  3233.6  227.82  3251.4  229.22  3291.3  229.55  3539.2  229.06  4227.8  228.41
  4598.8  230.14  4634.1  228.89  4791.6  229.93  4876.6   228.4  4891.1  229.59
    4920  228.68  4998.8  229.87  5223.6  228.49  5685.4  230.08  5787.4  228.99
  5858.8  231.83  6123.9  234.78  6429.9  241.55  6776.6  244.45    7052  249.91
#Mann= 7 ,-1 , 0
    2732     .16       0  3140.7     .12       0  3227.6     .07       0
  3233.6     .12       0  3291.3     .05       0  3539.2     .12       0
  5223.6     .05       0
Bank Sta=3160,3251.4
XS Rating Curve= 0 ,0
Exp/Cntr=0.3,0.1

Type RM Length L Ch R = 1 ,11693   ,649,649,649
BEGIN DESCRIPTION:
Mapping XS 4c1341d3
END DESCRIPTION:
XS GIS Cut Line= 3
      3717539.67     10594481.87      3715985.84     10596782.24
      3715968.49     10598846.69
#Sta/Elev= 30
  1793.8  228.88    1798  228.96  1900.4  225.59  1908.2   225.7  1911.3  223.47
    1914  222.97  1917.3  223.47  1929.2  225.63  2031.1  225.37  2223.3  228.72
  2383.1  231.96  2552.9     232  2766.4  230.94  2931.9  230.17  3128.4  229.46
  3523.8  230.65  3544.1  230.69  3736.5  230.87  3766.4  233.21  3965.9  231.34
  4001.1  232.25  4557.7  233.31  4743.9   231.2  4827.7  230.62    4940  226.46
    5038  226.11  5248.7  226.25  6107.8   237.9  6367.8  248.98  6634.3   253.3
#Mann= 18 ,-1 , 0
  1793.8     .07       0    1798     .12       0  1911.3     .07       0
  1917.3     .12       0  2223.3     .16       0  2552.9     .12       0
  2766.4     .16       0  2931.9     .05       0  3128.4     .16       0
  3523.8     .12       0  3544.1     .16       0  3736.5     .05       0
  3965.9     .12       0  4001.1     .05       0  4743.9     .16       0
    4940     .12       0    5038     .16       0  5248.7     .05       0
Bank Sta=1900.4,1929.2
XS Rating Curve= 0 ,0
Exp/Cntr=0.3,0.1

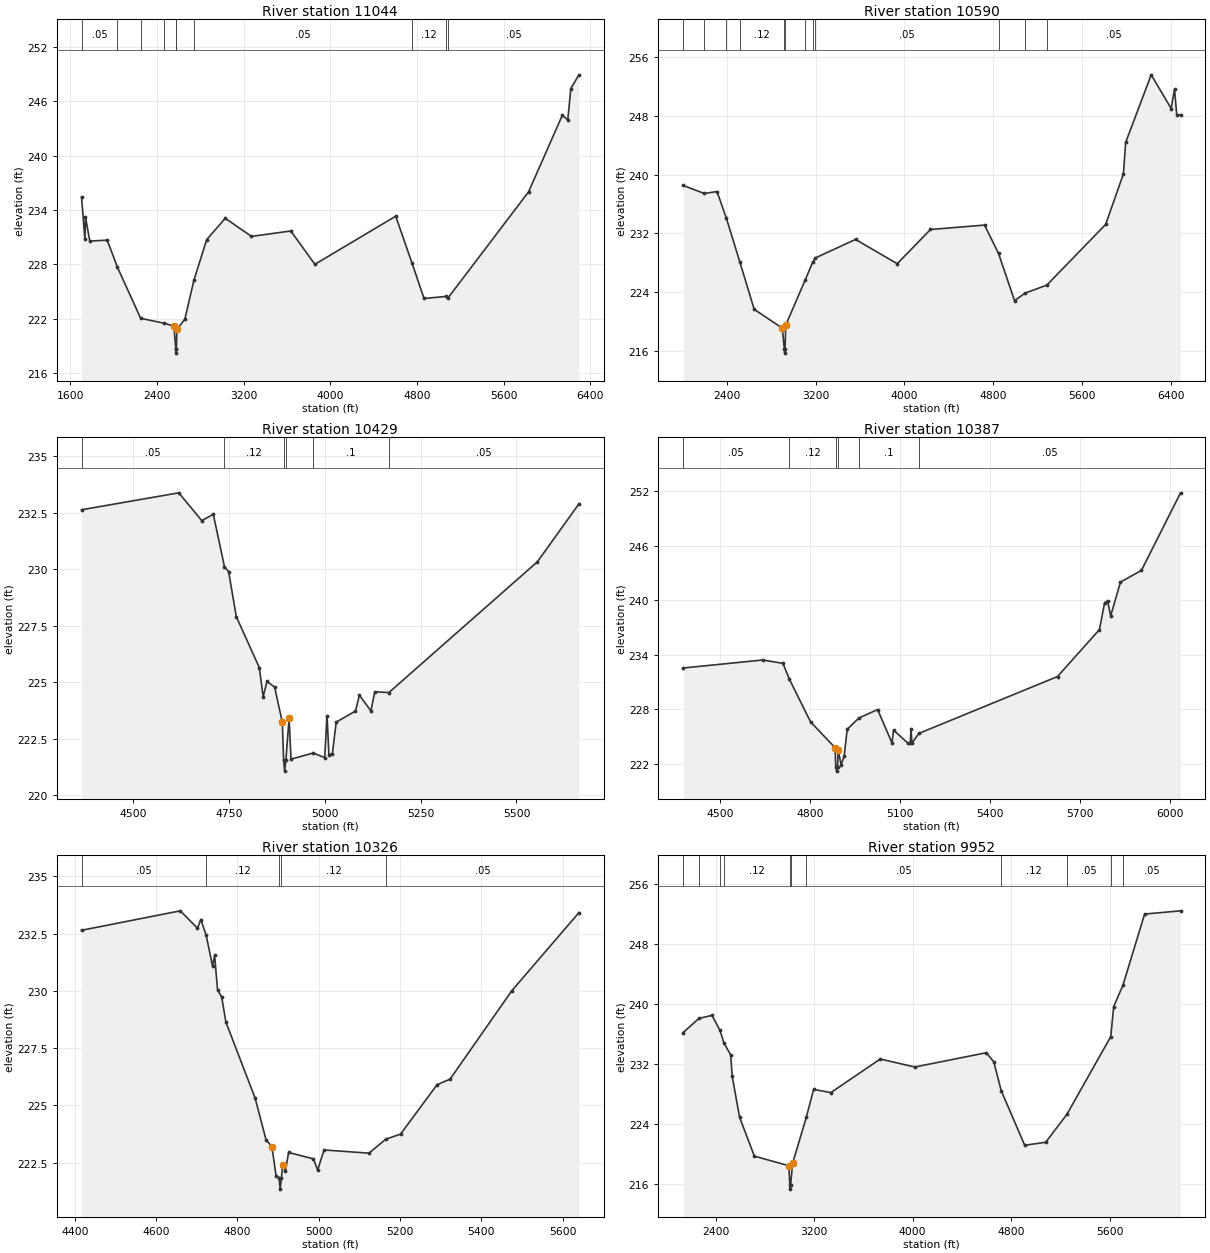
Type RM Length L Ch R = 1 ,11044   ,454,454,454
BEGIN DESCRIPTION:
Mapping XS cc1d5c60
END DESCRIPTION:
XS GIS Cut Line= 3
      3715768.83     10594264.87      3715386.88     10597190.22
      3715551.81     10598822.13
#Sta/Elev= 30
  1702.5   235.4  1734.1  230.77  1739.1  233.22  1778.5  230.56  1939.8  230.67
  2033.4  227.69  2248.4  222.04  2461.2  221.51    2555  221.18  2572.2   218.7
  2574.9   218.2  2578.2   218.7  2582.5  220.82  2655.8  221.93  2739.9  226.25
  2857.5  230.72    3029  233.08    3271  231.08  3634.1  231.68  3855.9     228
  4602.2  233.31  4753.6  228.11  4863.7  224.23  5070.6  224.46  5086.1  224.31
  5828.6     236  6140.2  244.45  6190.4  243.93  6218.4  247.39  6292.9  248.91
#Mann= 10 ,-1 , 0
  1702.5     .05       0  2033.4     .12       0  2248.4     .05       0
  2461.2     .12       0  2572.2     .07       0  2578.2     .12       0
  2739.9     .05       0  4753.6     .12       0  5070.6     .16       0
  5086.1     .05       0
Bank Sta=2555,2582.5
XS Rating Curve= 0 ,0
Exp/Cntr=0.3,0.1

Type RM Length L Ch R = 1 ,10590   ,161,161,161
BEGIN DESCRIPTION:
Mapping XS 34b37d3b
END DESCRIPTION:
XS GIS Cut Line= 3
      3714605.63     10594559.99       3715022.3     10596912.44
      3714900.77     10599004.45
#Sta/Elev= 30
  2005.2  238.52  2194.7  237.43  2310.1  237.69  2395.3  234.03  2516.4  228.09
  2645.2  221.68  2899.1  219.11  2917.6  216.22  2920.4  215.72  2923.6  216.22
  2929.6  219.52  3104.9  225.65  3175.1  228.17  3197.6  228.67  3559.2  231.18
    3935  227.88    4235  232.53  4722.6  233.13  4848.6  229.27    4993  222.85
  5087.1  223.87  5283.2  224.96  5814.4  233.22  5974.7  240.09  5994.7  244.36
  6225.1  253.56  6405.4  248.98  6435.5  251.62  6455.5  248.11  6489.8  248.14
#Mann= 12 ,-1 , 0
  2005.2     .05       0  2194.7     .16       0  2395.3     .05       0
  2516.4     .12       0  2917.6     .07       0  2923.6     .12       0
  3104.9     .05       0  3175.1     .08       0  3197.6     .05       0
  4848.6     .12       0  5087.1      .1       0  5283.2     .05       0
Bank Sta=2899.1,2929.6
XS Rating Curve= 0 ,0
Exp/Cntr=0.3,0.1

Type RM Length L Ch R = 1 ,10429   ,42,42,42
BEGIN DESCRIPTION:
Mapping XS 30d4bea8
END DESCRIPTION:
XS GIS Cut Line= 4
      3714849.89     10596996.66      3714873.32     10597527.87
      3714899.37     10597780.47       3714855.1     10598290.89
#Sta/Elev= 30
  4364.9  232.63  4618.7  233.38  4678.7  232.15  4708.8  232.43  4737.9  230.11
  4748.8  229.89  4768.8   227.9  4828.9  225.64  4838.9  224.35  4848.9  225.03
  4868.9  224.78  4888.9  223.22  4892.3  221.56    4895  221.06  4898.3  221.56
  4906.6  223.41  4911.6  221.59  4969.4  221.86  4999.5  221.66  5005.6  223.51
  5010.6  221.77  5019.6  221.84  5029.6  223.23  5079.9  223.72    5090  224.42
  5120.1  223.73  5130.2  224.57  5167.2  224.54  5554.8  230.33  5662.9  232.89
#Mann= 6 ,-1 , 0
  4364.9     .05       0  4737.9     .12       0  4892.3     .07       0
  4898.3     .12       0  4969.4      .1       0  5167.2     .05       0
Bank Sta=4888.9,4906.6
XS Rating Curve= 0 ,0
Exp/Cntr=0.3,0.1

Type RM Length L Ch R = 1 ,10387   ,61,61,61
BEGIN DESCRIPTION:
Mapping XS 43f0f75b
END DESCRIPTION:
XS GIS Cut Line= 6
      3714718.81     10597025.25      3714817.77      10597483.6
      3714849.02     10597676.31      3714864.64     10597770.06
      3714854.23      10597983.6      3714755.28     10598660.63
#Sta/Elev= 30
  4377.1  232.55  4642.3  233.43  4709.5  233.06    4731  231.31  4801.6  226.62
  4883.1  223.79  4885.4  221.71  4888.2  221.21  4891.4  221.71  4893.5  223.55
  4903.3  221.89  4913.5  222.86  4923.6  225.81  4962.4  227.05  5024.9  227.98
  5072.9  224.31  5077.9  225.72  5126.3  224.28  5133.7  224.29  5136.2  225.84
  5139.2  224.29    5162  225.35  5624.3  231.61  5764.2  236.78  5781.2  239.73
  5791.3  239.92  5801.4  238.28  5834.1  241.99  5904.1  243.29  6034.3  251.81
#Mann= 6 ,-1 , 0
  4377.1     .05       0    4731     .12       0  4885.4     .07       0
  4891.4     .12       0  4962.4      .1       0    5162     .05       0
Bank Sta=4883.1,4893.5
XS Rating Curve= 0 ,0
Exp/Cntr=0.3,0.1

Type RM Length L Ch R = 1 ,10326   ,374,374,374
BEGIN DESCRIPTION:
Mapping XS b3367fed
END DESCRIPTION:
XS GIS Cut Line= 4
      3714649.37     10597074.74      3714763.95     10597556.52
      3714805.62     10597757.04      3714714.55     10598272.23
#Sta/Elev= 30
  4416.7  232.64  4659.7  233.49  4701.8  232.73  4710.1  233.11  4723.3  232.42
  4738.9  231.08    4744  231.54  4751.2  230.05  4761.5  229.72  4771.8  228.63
  4843.7  225.31  4870.5  223.49  4884.9   223.2  4895.1  221.93  4902.4  221.84
  4905.2  221.34  4908.4  221.84  4911.2   222.4    4918  222.11  4925.9  222.94
  4987.2  222.66  4997.4  222.17  5013.1  223.05  5123.7  222.91  5164.9  223.52
  5201.2  223.74  5291.2   225.9    5323  226.14  5475.3  230.01  5639.9  233.41
#Mann= 5 ,-1 , 0
  4416.7     .05       0  4723.3     .12       0  4902.4     .07       0
  4908.4     .12       0  5164.9     .05       0
Bank Sta=4884.9,4911.2
XS Rating Curve= 0 ,0
Exp/Cntr=0.3,0.1

Type RM Length L Ch R = 1 ,9952    ,339,339,339
BEGIN DESCRIPTION:
Mapping XS 9b941182
END DESCRIPTION:
XS GIS Cut Line= 3
      3714319.17     10594803.09      3714466.74     10597051.33
      3714301.81     10598830.83
#Sta/Elev= 30
  2136.8  236.18  2264.7  238.06  2370.9  238.46  2435.1  236.47  2468.6  234.76
  2522.4   233.2  2534.8  230.36  2594.9  224.89  2715.1  219.72  2995.7  218.44
  3002.8  215.83  3005.5  215.33  3008.8  215.83  3025.8  218.77  3136.9  224.89
  3196.2  228.61  3336.5  228.18  3737.3  232.65  4017.9  231.59  4599.6  233.49
  4659.9  232.27  4720.2  228.43    4911  221.17  5081.7  221.57  5254.4   225.3
  5610.2  235.64    5634  239.64  5708.3  242.44  5885.1  251.95    6177  252.38
#Mann= 11 ,-1 , 0
  2136.8     .16       0  2264.7     .05       0  2435.1     .16       0
  2468.6     .12       0  3002.8     .07       0  3008.8     .12       0
  3136.9     .05       0  4720.2     .12       0  5254.4     .05       0
  5610.2     .08       0  5708.3     .05       0
Bank Sta=2995.7,3025.8
XS Rating Curve= 0 ,0
Exp/Cntr=0.3,0.1

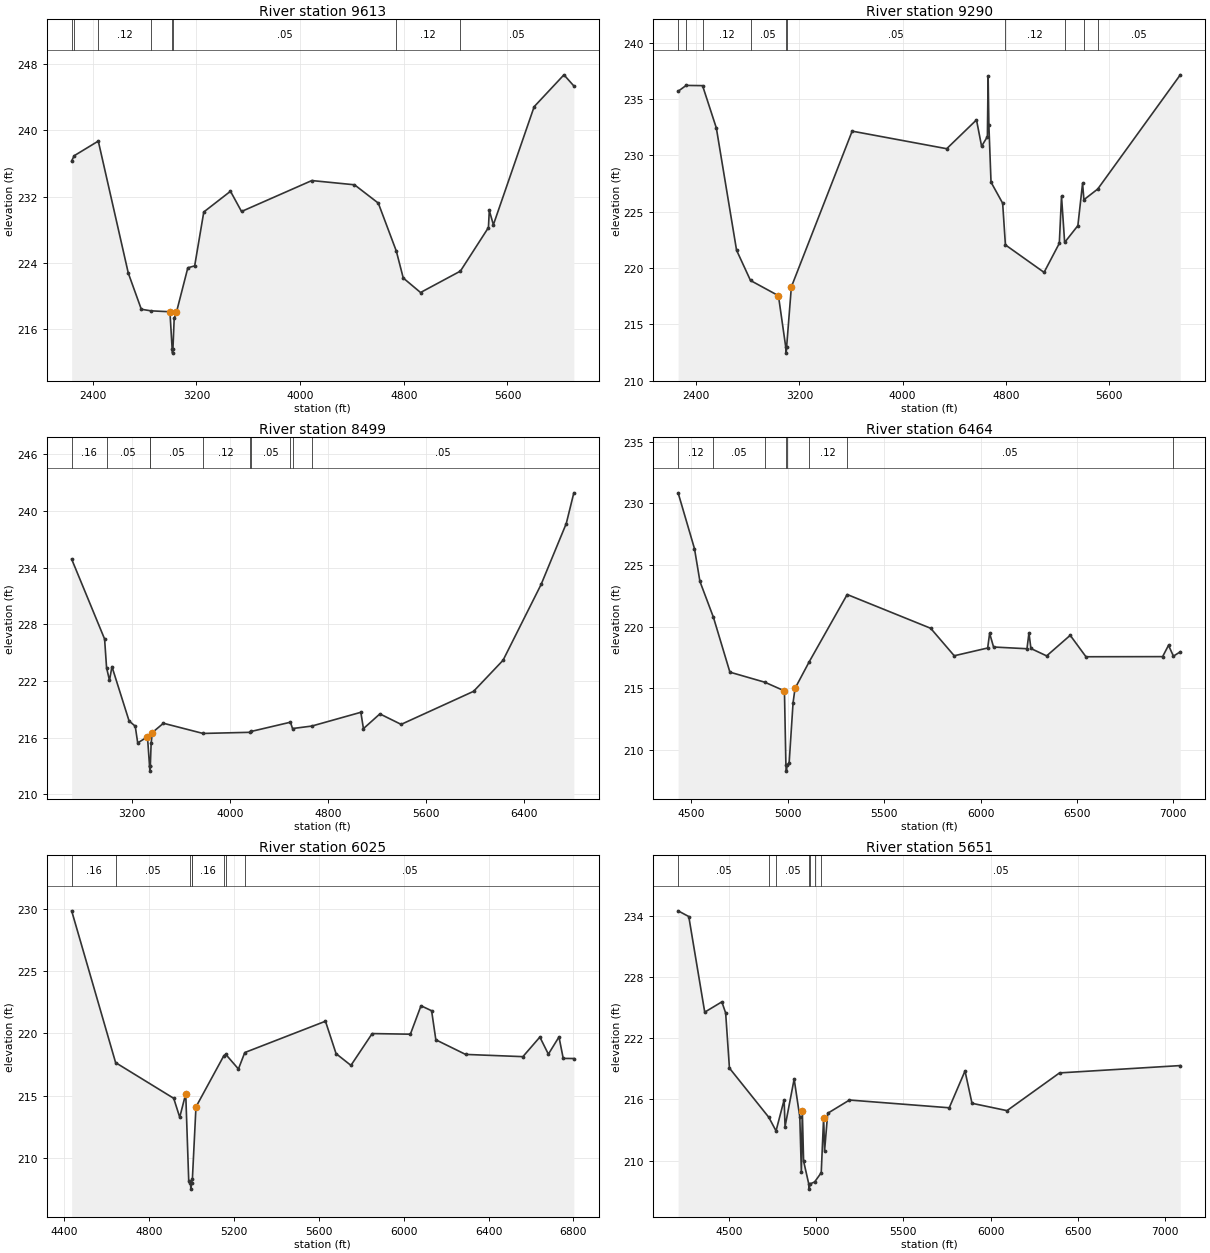
Type RM Length L Ch R = 1 ,9613    ,323,323,323
BEGIN DESCRIPTION:
Mapping XS 496b04d7
END DESCRIPTION:
XS GIS Cut Line= 3
      3714122.89     10594914.99      3714305.18      10596911.5
      3713732.26     10598691.03
#Sta/Elev= 30
  2237.8   236.3  2256.9  236.93  2443.3   238.7  2674.8  222.78  2775.2  218.42
  2849.6  218.23  2996.1  218.12  3013.2  213.63    3016  213.13  3019.2  213.63
  3028.9  217.33  3046.4  218.07  3134.1  223.42  3186.9  223.65  3257.2  230.15
  3463.1  232.65  3548.4  230.21  4090.7  233.94  4419.8  233.43  4603.6  231.22
  4742.7  225.43    4796  222.19  4929.5  220.44  5236.9  223.02  5453.2  228.27
  5459.9  230.33  5491.4  228.61    5806  242.85  6035.8  246.69  6112.1  245.35
#Mann= 8 ,-1 , 0
  2237.8     .12       0  2256.9     .05       0  2443.3     .12       0
  2849.6     .05       0  3013.2     .07       0  3019.2     .05       0
  4742.7     .12       0  5236.9     .05       0
Bank Sta=2996.1,3046.4
XS Rating Curve= 0 ,0
Exp/Cntr=0.3,0.1

Type RM Length L Ch R = 1 ,9290    ,791,791,791
BEGIN DESCRIPTION:
Mapping XS 85cb9b6a
END DESCRIPTION:
XS GIS Cut Line= 3
      3713971.95     10594924.61      3714110.84     10596851.68
      3713251.47     10598613.83
#Sta/Elev= 30
  2259.7  235.69  2322.1  236.21  2449.2  236.19    2556  232.43  2712.7  221.58
  2820.8  218.89  3037.3  217.54  3094.4  212.94  3097.2  212.44  3100.4  212.94
  3137.5  218.32  3608.8  232.15  4341.6  230.59  4572.5  233.15    4612  230.81
    4657  231.66  4662.6  237.06  4668.5  232.69  4685.1  227.62  4775.3  225.75
  4796.6  222.05  5096.3  219.61  5214.5  222.19  5231.5  226.36  5255.8  222.27
  5358.3  223.76  5394.8  227.52  5405.1  226.06  5512.2  227.01  6152.3  237.15
#Mann= 10 ,-1 , 0
  2259.7     .12       0  2322.1     .05       0  2449.2     .12       0
  2820.8     .05       0  3094.4     .07       0  3100.4     .05       0
  4796.6     .12       0  5255.8     .05       0  5405.1     .08       0
  5512.2     .05       0
Bank Sta=3037.3,3137.5
XS Rating Curve= 0 ,0
Exp/Cntr=0.3,0.1

Type RM Length L Ch R = 1 ,8499    ,2035,2035,2035
BEGIN DESCRIPTION:
Mapping XS a832fb9f
END DESCRIPTION:
XS GIS Cut Line= 4
       3713728.9     10595011.41      3713685.49     10596634.67
      3713034.45     10597320.43      3712930.39     10598846.66
#Sta/Elev= 30
  2707.8  234.91  2976.7  226.45  2992.8  223.42  3016.7  222.06  3036.7  223.53
  3176.7  217.77  3226.8  217.22    3247  215.45  3326.8  216.09  3343.8  212.96
  3346.6  212.46  3349.8  212.96  3356.8  215.45  3366.8  216.55  3456.8  217.53
  3780.2  216.45  4159.6  216.57  4172.6  216.66  4493.6  217.64  4510.8  216.97
  4667.1  217.23  5068.4  218.69  5089.5  216.96  5223.8  218.52  5397.3  217.41
  5988.6  220.91  6229.2   224.2  6539.9  232.23  6745.2  238.68    6807  241.93
#Mann= 10 ,-1 , 0
  2707.8     .16       0  2992.8     .05       0  3343.8     .03       0
  3349.8     .05       0  3780.2     .12       0  4159.6     .07       0
  4172.6     .05       0  4493.6     .07       0  4510.8     .12       0
  4667.1     .05       0
Bank Sta=3326.8,3366.8
XS Rating Curve= 0 ,0
Exp/Cntr=0.3,0.1

Type RM Length L Ch R = 1 ,6464    ,439,439,439
BEGIN DESCRIPTION:
UNT 090 IN BOCR 13.0
END DESCRIPTION:
XS GIS Cut Line= 3
      3713499.63     10594960.17      3713099.61     10595360.19
      3712699.61     10597360.16
#Sta/Elev= 30
    4431  230.86  4515.9  226.33  4544.2  223.67  4614.4  220.75  4699.7  216.31
  4881.5  215.49  4982.6  214.79  4990.2  208.78  4992.9  208.28  4996.2  208.78
  5006.9  208.92  5027.3  213.82  5037.5  214.99  5109.6  217.11  5308.1  222.61
  5741.2  219.87  5863.5  217.64  6036.9  218.27  6047.1  219.46  6067.5  218.35
  6240.9  218.21  6251.1  219.49  6261.3  218.23  6342.9  217.63  6465.2   219.3
  6546.8  217.56  6944.5  217.57  6975.1  218.49  7000.6  217.61  7036.3  217.96
#Mann= 8 ,-1 , 0
    4431     .12       0  4614.4     .05       0  4881.5     .16       0
  4990.2     .07       0  4996.2     .16       0  5109.6     .12       0
  5308.1     .05       0  7000.6     .12       0
Bank Sta=4982.6,5037.5
XS Rating Curve= 0 ,0
Exp/Cntr=0.3,0.1

Type RM Length L Ch R = 1 ,6025    ,374,374,374
BEGIN DESCRIPTION:
UNT 090 IN BOCR 12.0
END DESCRIPTION:
XS GIS Cut Line= 3
      3713149.58     10594710.22      3712749.61     10595110.19
      3712749.61     10596910.15
#Sta/Elev= 30
  4436.3  229.83  4643.4  217.66  4917.1   214.8  4945.4  213.28  4973.7  215.17
  4987.8   208.2  4995.4  208.02  4998.2  207.52  5001.4  208.02    5005  208.31
  5021.9  214.11  5153.7  218.23  5162.4  218.32  5221.9  217.15  5251.9  218.47
  5631.9  220.98  5681.9  218.38  5751.9  217.44  5851.9  219.99  6031.9  219.94
  6081.9  222.22  6131.9  221.82  6151.9  219.49  6291.9  218.32  6561.9  218.14
  6641.9  219.71  6681.9  218.34  6731.9  219.72  6751.9     218  6801.9  217.99
#Mann= 8 ,-1 , 0
  4436.3     .16       0  4643.4     .05       0  4995.4     .03       0
  5001.4     .05       0    5005     .16       0  5153.7     .05       0
  5162.4     .12       0  5251.9     .05       0
Bank Sta=4973.7,5021.9
XS Rating Curve= 0 ,0
Exp/Cntr=0.3,0.1

Type RM Length L Ch R = 1 ,5651    ,611,611,611
BEGIN DESCRIPTION:
UNT 090 IN BOCR 11.0
END DESCRIPTION:
XS GIS Cut Line= 3
      3712799.62     10594310.16      3712449.61     10595110.19
      3712649.61     10597110.17
#Sta/Elev= 30
  4206.5   234.5  4267.7  233.94  4359.3  224.56  4457.6  225.57  4479.4  224.48
  4501.2  219.07  4727.4  214.24  4768.7  212.91  4815.1  215.96  4820.5  213.33
  4872.7     218  4905.1  214.28  4914.1  208.85  4919.5  214.87  4926.9  209.95
  4956.7   207.7  4959.4   207.2  4962.7   207.7  4990.5  207.91  5028.2  208.81
  5041.9  214.22  5047.4  210.96  5065.3  214.64  5190.3  215.94  5763.1  215.18
  5853.6  218.79  5893.8  215.62  6094.8   214.9  6396.3   218.6  7089.7  219.32
#Mann= 7 ,-1 , 0
  4206.5     .05       0  4727.4     .08       0  4768.7     .05       0
  4956.7     .07       0  4962.7     .05       0  4990.5     .16       0
  5028.2     .05       0
Bank Sta=4919.5,5041.9
XS Rating Curve= 0 ,0
Exp/Cntr=0.3,0.1