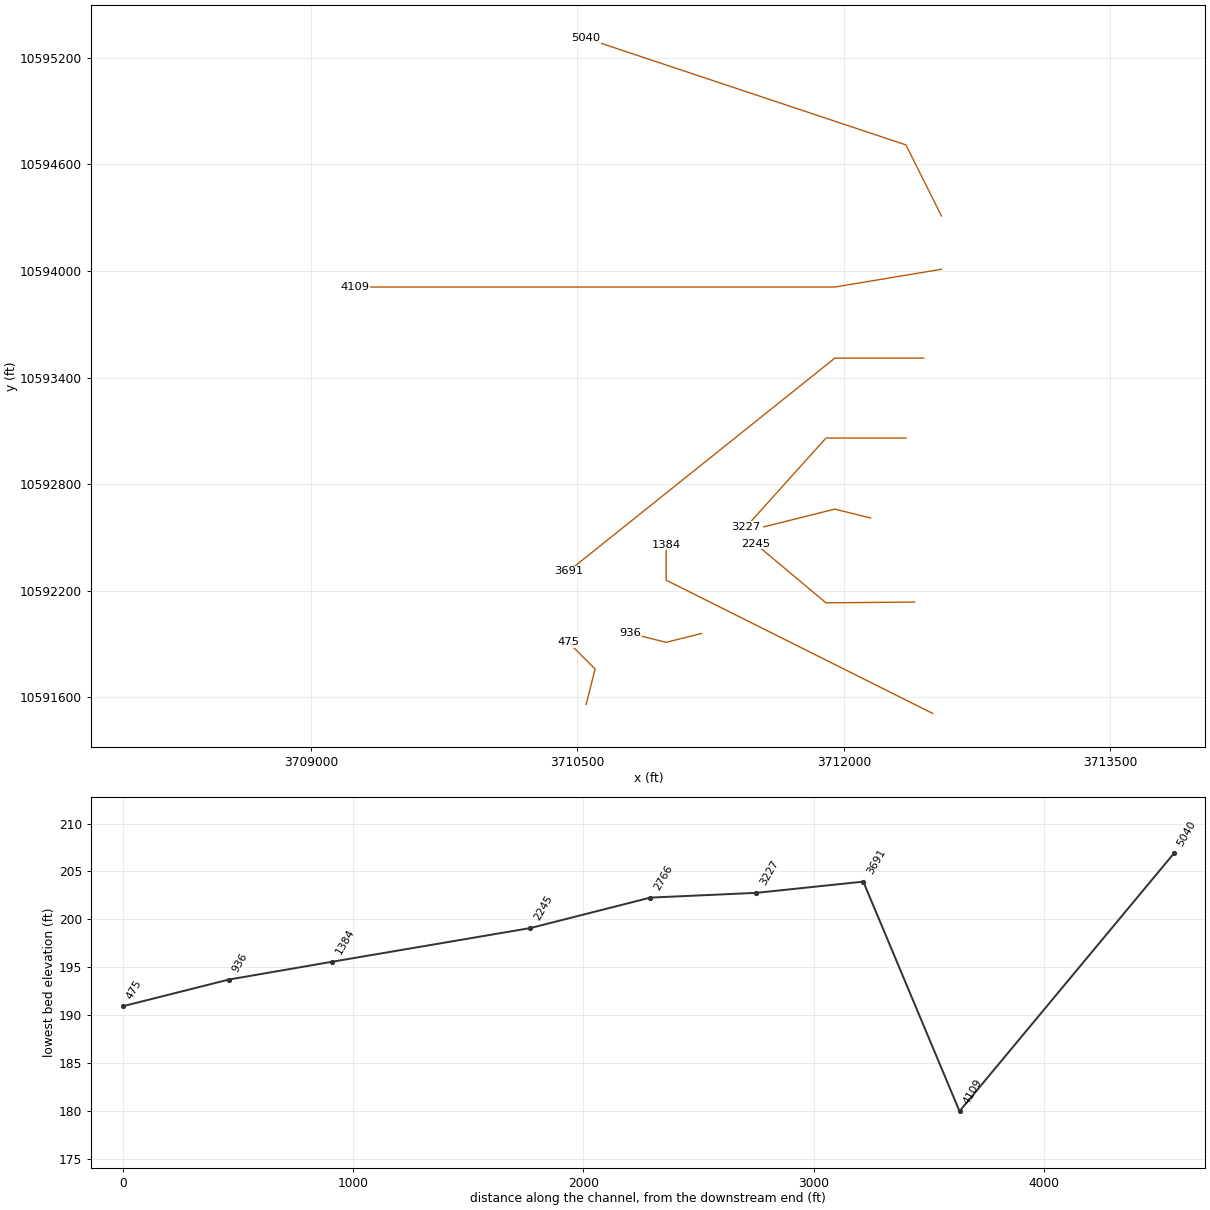
HEC-RAS study UNT 090 IN BOCR.prj: UNT 090 IN BOCR Base Level Engineering

--- UNT 090 IN BOCR.g01 (geometry) --- (continued)

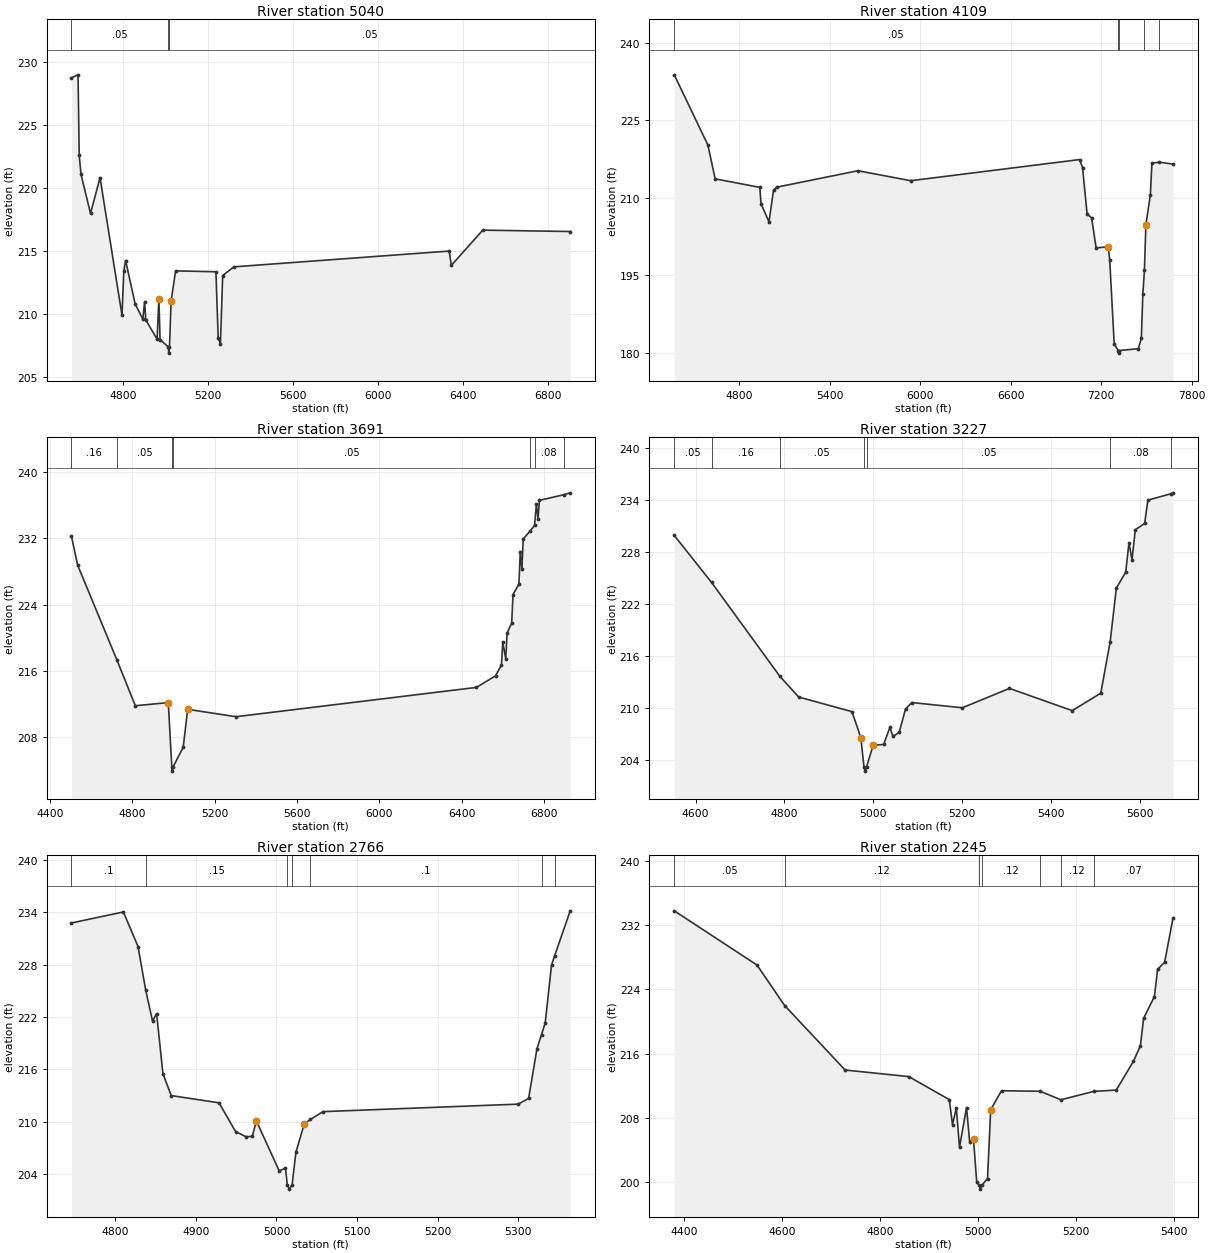
Type RM Length L Ch R = 1 ,5040    ,931,931,931
BEGIN DESCRIPTION:
UNT 090 IN BOCR 10.0
END DESCRIPTION:
XS GIS Cut Line= 3
      3712549.62     10594310.16      3712349.61     10594710.19
      3710549.62     10595310.19
#Sta/Elev= 30
    4558  228.72  4588.8  228.95  4594.4  222.56  4602.7  221.07  4647.5  217.96
  4692.2   220.8  4795.6  209.89    4804  213.39  4812.4  214.23  4857.1  210.81
  4893.4  209.58  4901.8  210.98  4907.4  209.51  4960.5     208  4968.9  211.17
  4974.5  207.96  5012.8  207.39  5015.5  206.89  5018.8  207.39  5026.3  210.99
  5047.4  213.41  5237.1  213.34  5247.7  208.08  5258.2  207.64  5268.8  213.04
  5321.5  213.73  6333.4  214.98  6343.9  213.85  6491.5  216.64  6902.6  216.53
#Mann= 3 ,-1 , 0
    4558     .05       0  5012.8     .03       0  5018.8     .05       0
Bank Sta=4968.9,5026.3
XS Rating Curve= 0 ,0
Exp/Cntr=0.3,0.1

Type RM Length L Ch R = 1 ,4109    ,418,418,418
BEGIN DESCRIPTION:
UNT 090 IN BOCR 8.0
END DESCRIPTION:
XS GIS Cut Line= 3
      3712549.61     10594010.19      3711949.61     10593910.19
      3709249.58     10593910.19
#Sta/Elev= 30
    4368  233.81    4591  220.23  4639.2  213.68  4935.7  212.03  4943.3  208.87
  4996.3  205.37  5026.3  211.47  5046.3  212.06  5586.3  215.25  5936.3  213.32
  7056.3  217.41  7076.3  215.87  7106.3  206.91  7136.3  206.12  7166.3  200.32
  7246.3  200.52  7256.3  198.04  7286.3  181.69  7313.3  180.45    7316  179.95
  7319.3  180.45  7446.3  180.81  7466.3  182.85  7476.3  191.44  7486.6  195.95
  7496.3  204.76  7526.3  210.61  7536.3  216.73  7585.5   216.9  7676.3  216.53
#Mann= 5 ,-1 , 0
    4368     .05       0  7313.3     .03       0  7319.3     .05       0
  7486.6     .16       0  7585.5     .05       0
Bank Sta=7246.3,7496.3
XS Rating Curve= 0 ,0
Exp/Cntr=0.3,0.1

Type RM Length L Ch R = 1 ,3691    ,464,464,464
BEGIN DESCRIPTION:
UNT 090 IN BOCR 7.0
END DESCRIPTION:
XS GIS Cut Line= 3
      3712449.57     10593510.19      3711949.61     10593510.19
      3710449.61     10592310.19
#Sta/Elev= 30
  4505.4  232.24  4535.4  228.76  4725.9  217.34  4815.4  211.82  4975.4   212.2
  4992.4  204.44  4995.1  203.94  4998.4  204.44  5047.8  206.82  5069.4  211.39
  5303.9   210.5  6470.9  214.03  6563.7  215.42  6592.5  216.72  6598.9  219.49
  6613.3   217.5  6619.8  220.57  6642.2  221.78  6648.6  225.21  6677.4  226.48
  6683.8  230.39  6691.8  228.25  6698.2  231.91    6730  232.83  6753.1  233.56
  6762.2  236.11  6770.2  234.35  6776.6  236.57    6895  237.25  6926.3  237.48
#Mann= 7 ,-1 , 0
  4505.4     .16       0  4725.9     .05       0  4992.4     .03       0
  4998.4     .05       0    6730      .1       0  6753.1     .08       0
    6895      .1       0
Bank Sta=4975.4,5069.4
XS Rating Curve= 0 ,0
Exp/Cntr=0.3,0.1

Type RM Length L Ch R = 1 ,3227    ,461,461,461
BEGIN DESCRIPTION:
UNT 090 IN BOCR 6.0
END DESCRIPTION:
XS GIS Cut Line= 3
      3712349.59     10593060.19      3711899.61     10593060.19
      3711449.59     10592560.16
#Sta/Elev= 30
  4552.1  229.92    4636  224.51  4789.5  213.71  4832.1  211.31  4952.1  209.62
  4972.1  206.62  4979.1  203.27  4981.8  202.77  4985.1  203.27  4999.6  205.74
  5023.4  205.85  5037.6  207.82  5044.3  206.76  5058.5  207.24  5072.7  209.94
  5086.9  210.67  5200.5  210.07  5306.7   212.3  5447.9  209.74  5512.2  211.75
  5533.3  217.67  5547.3  223.86  5568.3   225.7  5575.7  229.07  5582.5   227.1
  5589.9  230.58  5610.9   231.3  5618.3  233.99    5670  234.72  5674.8  234.83
#Mann= 7 ,-1 , 0
  4552.1     .05       0    4636     .16       0  4789.5     .05       0
  4979.1     .03       0  4985.1     .05       0  5533.3     .08       0
    5670      .1       0
Bank Sta=4972.1,4999.6
XS Rating Curve= 0 ,0
Exp/Cntr=0.3,0.1

Type RM Length L Ch R = 1 ,2766    ,521,521,521
BEGIN DESCRIPTION:
UNT 090 IN BOCR 5.0
END DESCRIPTION:
XS GIS Cut Line= 3
       3712149.6     10592610.19      3711949.61     10592660.19
      3711549.56     10592560.18
#Sta/Elev= 30
  4745.8  232.77  4810.2  234.03  4828.3  230.07  4837.9  225.05  4846.3  221.54
  4851.4  222.38  4859.2   215.5  4869.5  212.99  4928.8  212.16  4949.4  208.85
  4962.3  208.28    4970  208.31  4975.1  210.09  5003.5  204.34  5011.2  204.71
  5013.4  202.77  5016.1  202.27  5019.4  202.77  5024.1  206.47  5034.4  209.73
  5042.1  210.25  5057.6  211.15  5299.8  212.01  5312.7  212.67    5323  218.32
  5328.7  219.98  5333.3  221.32  5341.1  227.93    5345  229.02  5364.3  234.16
#Mann= 7 ,-1 , 0
  4745.8      .1       0  4837.9     .15       0  5013.4     .07       0
  5019.4     .15       0  5042.1      .1       0  5328.7     .15       0
    5345      .1       0
Bank Sta=4975.1,5034.4
XS Rating Curve= 0 ,0
Exp/Cntr=0.3,0.1

Type RM Length L Ch R = 1 ,2245    ,861,861,861
BEGIN DESCRIPTION:
UNT 090 IN BOCR 4.0
END DESCRIPTION:
XS GIS Cut Line= 3
      3712398.64     10592136.73      3711899.55     10592132.39
       3711501.1     10592465.87
#Sta/Elev= 30
  4379.7  233.79  4548.7  227.03  4605.3  221.97  4728.7  213.94  4858.8  213.12
  4941.5  210.25    4948  207.13  4955.8  209.25  4962.3  204.31  4976.6  209.26
  4983.1  204.96  4990.9  205.34  4997.4  200.02  5002.2  199.59    5005  199.09
  5008.2  199.59  5019.5  200.41    5026     209  5048.1  211.36  5126.9  211.29
  5169.4  210.23  5236.7  211.28  5282.4  211.44  5317.5  215.02  5331.8  216.97
  5338.3  220.38  5360.4   223.1    5367  226.51  5381.3  227.38  5398.4   232.9
#Mann= 7 ,-1 , 0
  4379.7     .05       0  4605.3     .12       0  5002.2     .07       0
  5008.2     .12       0  5126.9     .07       0  5169.4     .12       0
  5236.7     .07       0
Bank Sta=4990.9,5026
XS Rating Curve= 0 ,0
Exp/Cntr=0.3,0.1

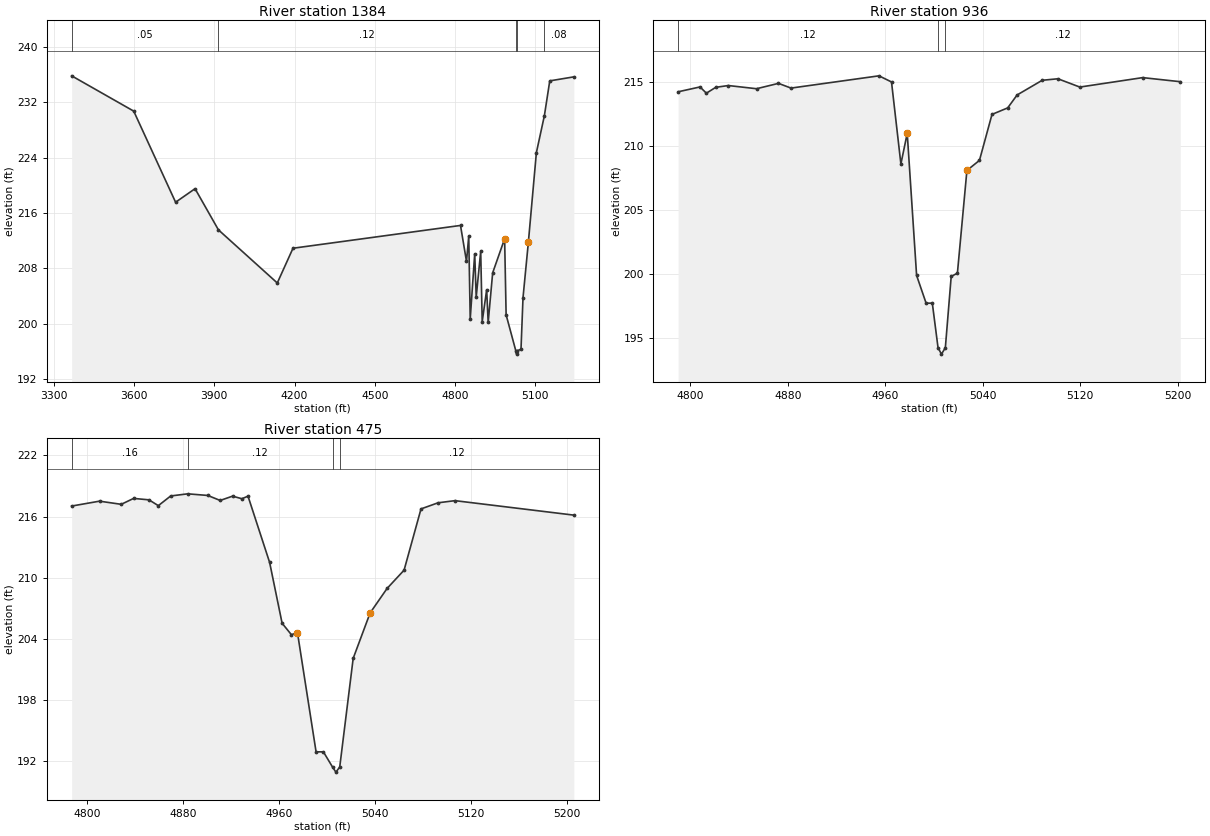
Type RM Length L Ch R = 1 ,1384    ,448,448,448
BEGIN DESCRIPTION:
UNT 090 IN BOCR 3.0
END DESCRIPTION:
XS GIS Cut Line= 3
      3712499.58      10591510.2      3710999.61     10592260.19
      3710999.61     10592460.17
#Sta/Elev= 30
  3366.7  235.86  3598.7  230.75  3755.2  217.56  3827.9  219.52  3915.3  213.56
  4135.3  205.87    4194   210.9  4820.1   214.2  4842.5  208.99  4850.9  212.65
  4856.4  200.66  4873.2   210.1  4878.8  203.84  4895.6  210.44  4901.2  200.28
  4917.9   204.9  4923.5  200.15  4940.3  207.34    4985  212.27  4990.6  201.26
  5026.7  196.07  5029.5  195.57  5032.7  196.07  5046.2  196.27  5053.7  203.73
  5073.7  211.75  5103.7  224.74  5133.6  230.09  5153.7  235.13  5243.7  235.71
#Mann= 5 ,-1 , 0
  3366.7     .05       0  3915.3     .12       0  5026.7     .07       0
  5032.7     .12       0  5133.6     .08       0
Bank Sta=4985,5073.7
XS Rating Curve= 0 ,0
Exp/Cntr=0.3,0.1

Type RM Length L Ch R = 1 ,936     ,461,461,461
BEGIN DESCRIPTION:
UNT 090 IN BOCR 2.0
END DESCRIPTION:
XS GIS Cut Line= 3
      3711199.59     10591960.18      3710999.61     10591910.19
       3710799.6     10591960.19
#Sta/Elev= 30
    4790  214.25    4808  214.63  4813.2  214.14  4820.9   214.6  4831.2  214.74
  4854.4  214.49  4872.4  214.91  4882.7  214.54  4954.9   215.5  4965.2  215.02
  4972.9   208.6  4978.1     211  4985.8  199.87  4993.6   197.7  4998.7   197.7
  5003.4  194.21  5006.2  193.71  5009.4  194.21  5014.2  199.79  5019.3  200.05
  5027.1  208.09  5037.4  208.88  5047.7  212.48  5060.6  212.99  5068.3     214
  5088.9  215.15  5101.8  215.27  5119.8  214.62  5171.4  215.36  5202.3  215.04
#Mann= 3 ,-1 , 0
    4790     .12       0  5003.4     .07       0  5009.4     .12       0
Bank Sta=4978.1,5027.1
XS Rating Curve= 0 ,0
Exp/Cntr=0.3,0.1

Type RM Length L Ch R = 1 ,475     ,0,0,0
BEGIN DESCRIPTION:
UNT 090 IN BOCR 1.0
END DESCRIPTION:
XS GIS Cut Line= 3
       3710549.6     10591560.17      3710599.61     10591760.19
      3710449.61     10591910.18
#Sta/Elev= 30
  4787.1  217.03  4810.3  217.51  4828.4   217.2  4838.7  217.78  4851.5  217.64
  4859.3  217.07  4869.6  218.02  4883.8  218.23  4900.5  218.07  4910.8  217.58
  4921.1     218  4928.9  217.75    4934     218    4952   211.5  4962.4  205.53
  4970.1  204.41  4975.2   204.6  4990.7  192.91  4996.8  192.91  5004.4  191.42
  5007.2  190.92  5010.4  191.42  5021.6  202.08  5035.7  206.54  5049.8  208.94
    5064  210.74  5078.1  216.75  5092.3  217.35  5106.4  217.56  5205.4  216.14
#Mann= 4 ,-1 , 0
  4787.1     .16       0  4883.8     .12       0  5004.4     .07       0
  5010.4     .12       0
Bank Sta=4975.2,5035.7
XS Rating Curve= 0 ,0
Exp/Cntr=0.3,0.1

Chan Stop Cuts=-1
Use User Specified Reach Order=0
Composite Channel Slope=5