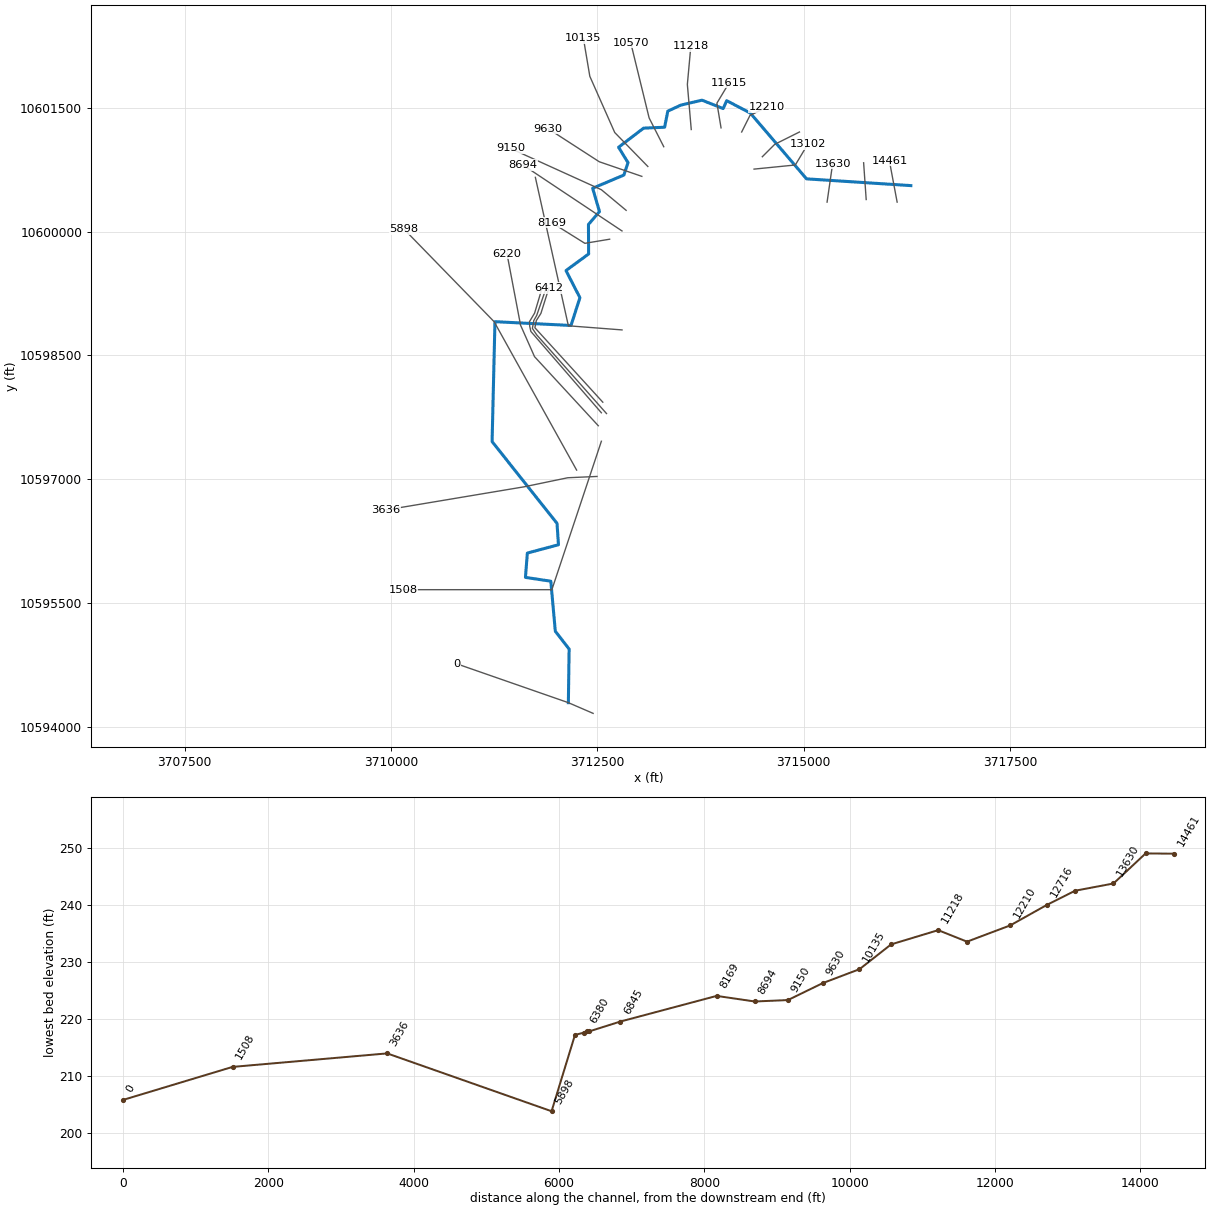
--- UNT 091 IN BOCR.prj (project) ---

Proj Title=UNT 091 IN BOCR Base Level Engineering
Current Plan=p01
Default Exp/Contr=0.3,0.1
English Units
Geom File=g01
Flow File=f01
Plan File=p01
BEGIN DESCRIPTION:
UNT 091 IN BOCR
END DESCRIPTION:

--- UNT 091 IN BOCR.p01 (plan) ---

Plan Title=Multiple Run
Short Identifier=Multiple
Geom File=g01
Flow File=f01
Subcritical Flow
K Sum by GR= 0
Std Step Tol= 0.01
Critical Tol= 0.01
Num of Std Step Trials= 20
Max Error Tol= 0.3
Flow Tol Ratio= 0.001
Split Flow NTrial= 30
Split Flow Tol= 0.02
Split Flow Ratio= 0.02
Log Output Level= 0
Friction Slope Method= 1
Unsteady Friction Slope Method= 2
Unsteady Bridges Friction Slope Method= 1
Parabolic Critical Depth
Global Vel Dist=  1 , 1 , 1
Global Log Level= 0
CheckData=True
Encroach Param= -1, 0, 0, 0
BEGIN DESCRIPTION:
Multiple Run
END DESCRIPTION:

--- UNT 091 IN BOCR.f01 (steady flow) ---

Flow Title=Multiple
Number of Profiles=7
Profile Names=10-year,25-year,50-year,1pct_min,100-year,1pct_plu,500-year
River Rch & RM= UNT 091 IN BOCR,Reach-1,14461
     430     561     664     578     781    1056    1084
River Rch & RM= UNT 091 IN BOCR,Reach-1,0
    1391    1937    2398    2173    2939    3974    4434
Boundary for River Rch & Prof#=UNT 091 IN BOCR,Reach-1,1
Up Type=0
Dn Type=3
Dn Slope=0.005
Boundary for River Rch & Prof#=UNT 091 IN BOCR,Reach-1,2
Up Type=0
Dn Type=3
Dn Slope=0.005
Boundary for River Rch & Prof#=UNT 091 IN BOCR,Reach-1,3
Up Type=0
Dn Type=3
Dn Slope=0.005
Boundary for River Rch & Prof#=UNT 091 IN BOCR,Reach-1,4
Up Type=0
Dn Type=3
Dn Slope=0.005
Boundary for River Rch & Prof#=UNT 091 IN BOCR,Reach-1,5
Up Type=0
Dn Type=3
Dn Slope=0.005
Boundary for River Rch & Prof#=UNT 091 IN BOCR,Reach-1,6
Up Type=0
Dn Type=3
Dn Slope=0.005
Boundary for River Rch & Prof#=UNT 091 IN BOCR,Reach-1,7
Up Type=0
Dn Type=3
Dn Slope=0.005

--- UNT 091 IN BOCR.g01 (geometry) ---

Geom Title=Existing Conditions

River Reach=UNT 091 IN BOCR,Reach-1
Reach XY= 30
      3716299.61     10600560.19      3715035.50     10600642.00
      3714354.00     10601440.00      3714068.25     10601590.00
      3714025.25     10601494.00      3713768.75     10601596.00
      3713511.75     10601536.00      3713354.50     10601463.00
      3713315.50     10601268.00      3713061.25     10601257.00
      3712758.00     10601025.00      3712872.25     10600839.00
      3712822.00     10600688.00      3712443.75     10600528.00
      3712526.50     10600245.00      3712393.00     10600089.00
      3712395.00     10599731.00      3712120.75     10599530.00
      3712289.50     10599201.00      3712181.50     10598864.00
      3711260.00     10598910.00      3711225.25     10597456.00
      3712012.00     10596464.00      3712029.50     10596205.00
      3711652.50     10596104.00      3711629.50     10595809.00
      3711936.75     10595763.00      3711991.50     10595156.00
      3712158.75     10594940.00      3712149.50     10594290.00

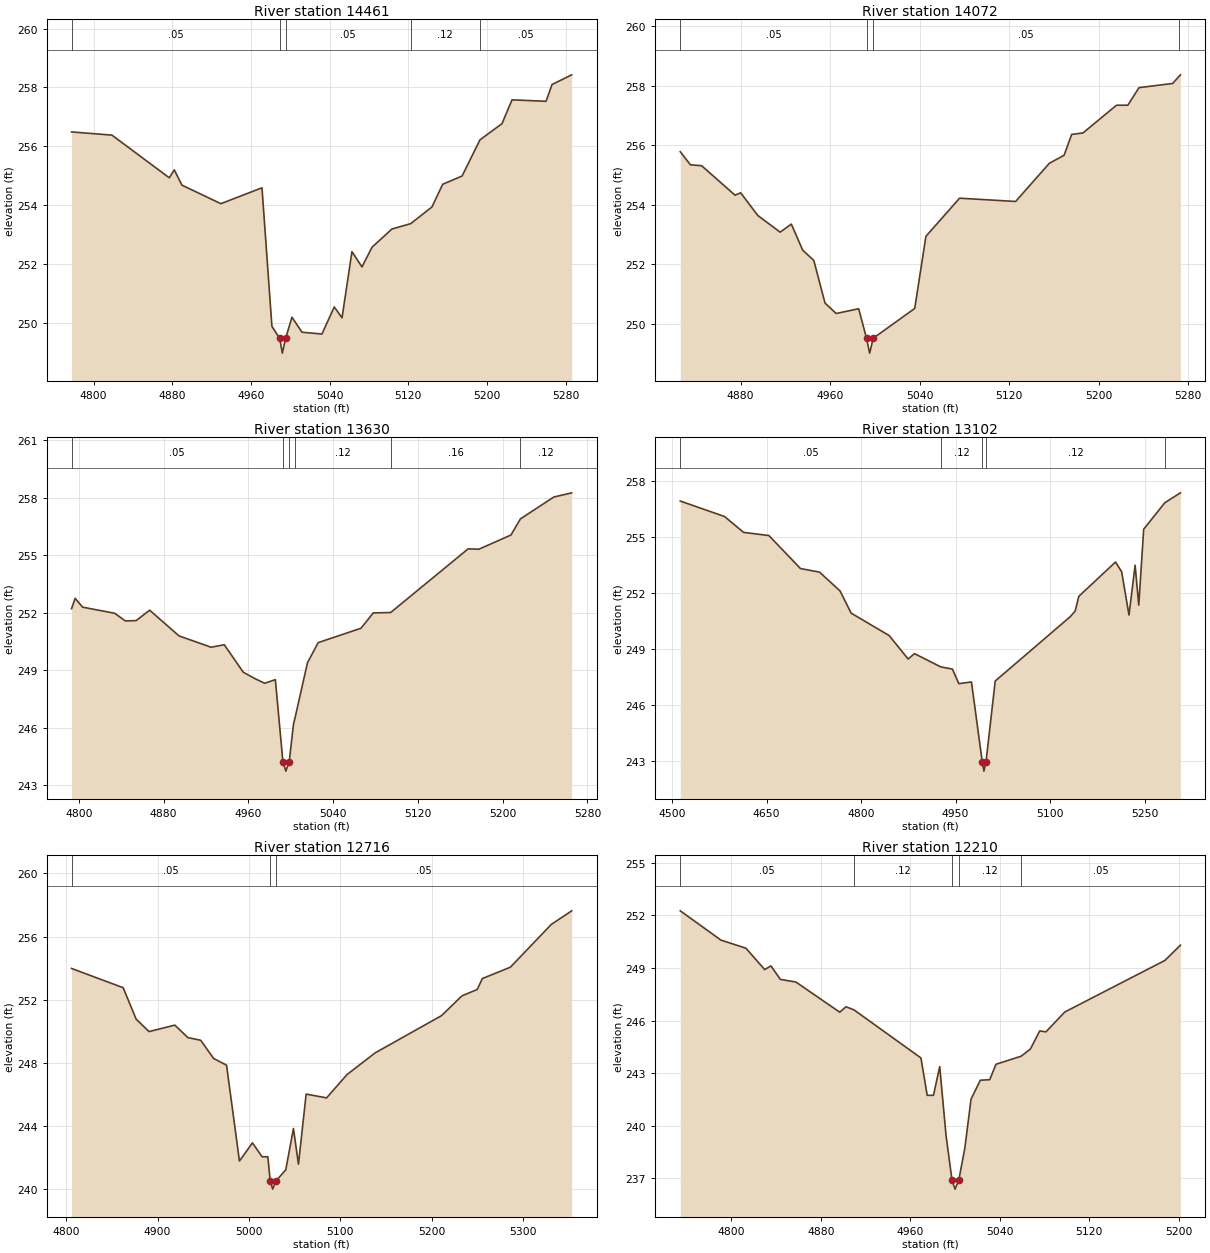
Type RM Length L Ch R = 1,14461,389,389,389
BEGIN DESCRIPTION:
UNT 091 IN BOCR 16.0
END DESCRIPTION:
XS GIS Cut Line= 2
      3716133.36     10600359.84      3716039.61     10600859.82
#Sta/Elev= 30
  4777.5  256.49  4818.6  256.38  4876.9  254.93  4882.0  255.20  4889.8  254.68
  4929.4  254.05  4971.2  254.59  4981.3  249.88  4989.2  249.47  4991.9  248.97
  4995.2  249.47  5001.7  250.19  5011.9  249.68  5032.2  249.62  5044.7  250.54
  5052.6  250.17  5062.7  252.42  5072.9  251.90  5083.1  252.57  5103.4  253.19
  5122.4  253.37  5144.1  253.94  5155.0  254.71  5174.7  254.99  5192.9  256.22
  5215.3  256.77  5225.5  257.58  5260.1  257.53  5266.2  258.10  5286.2  258.43
#Mann=5,-1,0
  4777.5    0.05       0  4989.2    0.03       0  4995.2    0.05       0
  5122.4    0.12       0  5192.9    0.05       0
Bank Sta=4989.2,4995.2
Exp/Cntr=0.3,0.1

Type RM Length L Ch R = 1,14072,442,442,442
BEGIN DESCRIPTION:
Mapping XS f9c176ae
END DESCRIPTION:
XS GIS Cut Line= 2
      3715758.36     10600391.09      3715727.24     10600837.10
#Sta/Elev= 30
  4826.0  255.78  4835.1  255.34  4845.1  255.31  4875.0  254.32  4880.0  254.40
  4895.3  253.64  4915.3  253.08  4925.3  253.35  4935.4  252.48  4945.4  252.13
  4955.4  250.70  4965.4  250.35  4985.5  250.51  4992.5  249.52  4995.3  249.02
  4998.5  249.52  5035.6  250.52  5045.6  252.94  5075.7  254.22  5125.8  254.11
  5155.9  255.39  5169.1  255.66  5175.9  256.36  5186.0  256.41  5216.0  257.34
  5226.1  257.34  5236.1  257.93  5266.2  258.07  5271.4  258.29  5273.1  258.36
#Mann=4,-1,0
  4826.0    0.05       0  4992.5    0.03       0  4998.5    0.05       0
  5271.4    0.12       0
Bank Sta=4992.5,4998.5
Exp/Cntr=0.3,0.1

Type RM Length L Ch R = 1,13630,528,528,528
BEGIN DESCRIPTION:
UNT 091 IN BOCR 15.0
END DESCRIPTION:
XS GIS Cut Line= 2
      3715284.41     10600359.86      3715351.87     10600826.91
#Sta/Elev= 30
  4793.2  252.21  4796.6  252.75  4803.6  252.29  4833.9  251.97  4844.0  251.57
  4854.2  251.59  4866.9  252.13  4894.6  250.79  4924.9  250.20  4937.3  250.33
  4955.2  248.90  4965.3  248.59  4975.4  248.32  4985.5  248.51  4992.6  244.24
  4995.4  243.74  4998.6  244.24  5002.6  246.19  5004.0  246.50  5015.8  249.39
  5025.9  250.44  5066.3  251.19  5077.9  251.99  5094.3  252.01  5167.4  255.33
  5177.5  255.31  5207.8  256.05  5216.7  256.89  5248.2  258.03  5265.1  258.25
#Mann=6,-1,0
  4793.2    0.05       0  4992.6    0.07       0  4998.6    0.05       0
  5004.0    0.12       0  5094.3    0.16       0  5216.7    0.12       0
Bank Sta=4992.6,4998.6
Exp/Cntr=0.3,0.1

Type RM Length L Ch R = 1,13102,386,386,386
BEGIN DESCRIPTION:
UNT 091 IN BOCR 14.0
END DESCRIPTION:
XS GIS Cut Line= 3
      3714399.64     10600760.19      3714899.61     10600810.19
      3715049.60     10601060.18
#Sta/Elev= 30
  4512.9  256.95  4583.2  256.12  4613.4  255.27  4653.6  255.10  4703.8  253.33
  4734.0  253.14  4766.6  252.13  4784.2  250.94  4844.5  249.74  4874.7  248.48
  4884.7  248.77  4926.3  248.06  4945.0  247.94  4955.1  247.16  4975.2  247.25
  4992.3  242.97  4995.0  242.47  4998.3  242.97  5012.9  247.30  5132.0  250.75
  5139.8  251.05  5145.6  251.84  5203.9  253.68  5213.6  253.16  5225.3  250.84
  5235.0  253.51  5240.8  251.37  5248.6  255.44  5282.2  256.86  5306.9  257.39
#Mann=5,-1,0
  4512.9    0.05       0  4926.3    0.12       0  4992.3    0.07       0
  4998.3    0.12       0  5282.2    0.05       0
Bank Sta=4992.3,4998.3
Exp/Cntr=0.3,0.1

Type RM Length L Ch R = 1,12716,506,506,506
BEGIN DESCRIPTION:
UNT 091 IN BOCR 13.0
END DESCRIPTION:
XS GIS Cut Line= 3
      3714499.62     10600910.20      3714649.61     10601060.19
      3714949.59     10601210.18
#Sta/Elev= 30
  4805.8  253.98  4862.3  252.76  4876.5  250.77  4890.6  249.98  4918.9  250.39
  4933.1  249.60  4947.2  249.43  4961.3  248.28  4975.5  247.85  4989.6  241.78
  5003.8  242.93  5014.4  242.05  5020.7  242.05  5023.3  240.50  5026.0  240.00
  5029.3  240.50  5040.3  241.22  5048.7  243.84  5054.2  241.58  5062.6  246.02
  5085.0  245.78  5107.4  247.26  5138.1  248.63  5210.8  250.99  5233.1  252.24
  5249.9  252.65  5255.5  253.34  5286.2  254.06  5331.0  256.77  5353.3  257.63
#Mann=3,-1,0
  4805.8    0.05       0  5023.3    0.03       0  5029.3    0.05       0
Bank Sta=5023.3,5029.3
Exp/Cntr=0.3,0.1

Type RM Length L Ch R = 1,12210,595,595,595
BEGIN DESCRIPTION:
UNT 091 IN BOCR 12.0
END DESCRIPTION:
XS GIS Cut Line= 3
      3714249.60     10601210.18      3714349.61     10601410.19
      3714549.58     10601510.18
#Sta/Elev= 30
  4754.2  252.26  4790.6  250.59  4812.9  250.13  4829.7  248.91  4835.3  249.12
  4843.7  248.35  4857.6  248.20  4896.8  246.48  4902.4  246.79  4909.6  246.61
  4969.4  243.87  4975.0  241.74  4980.6  241.74  4986.2  243.38  4991.8  239.48
  4997.2  236.89  4999.9  236.39  5003.2  236.89  5008.6  238.71  5014.2  241.52
  5022.5  242.60  5030.9  242.63  5036.5  243.51  5059.0  243.97  5067.3  244.38
  5075.6  245.41  5081.2  245.36  5098.0  246.49  5187.5  249.43  5201.4  250.30
#Mann=5,-1,0
  4754.2    0.05       0  4909.6    0.12       0  4997.2    0.07       0
  5003.2    0.12       0  5059.0    0.05       0
Bank Sta=4997.2,5003.2
Exp/Cntr=0.3,0.1

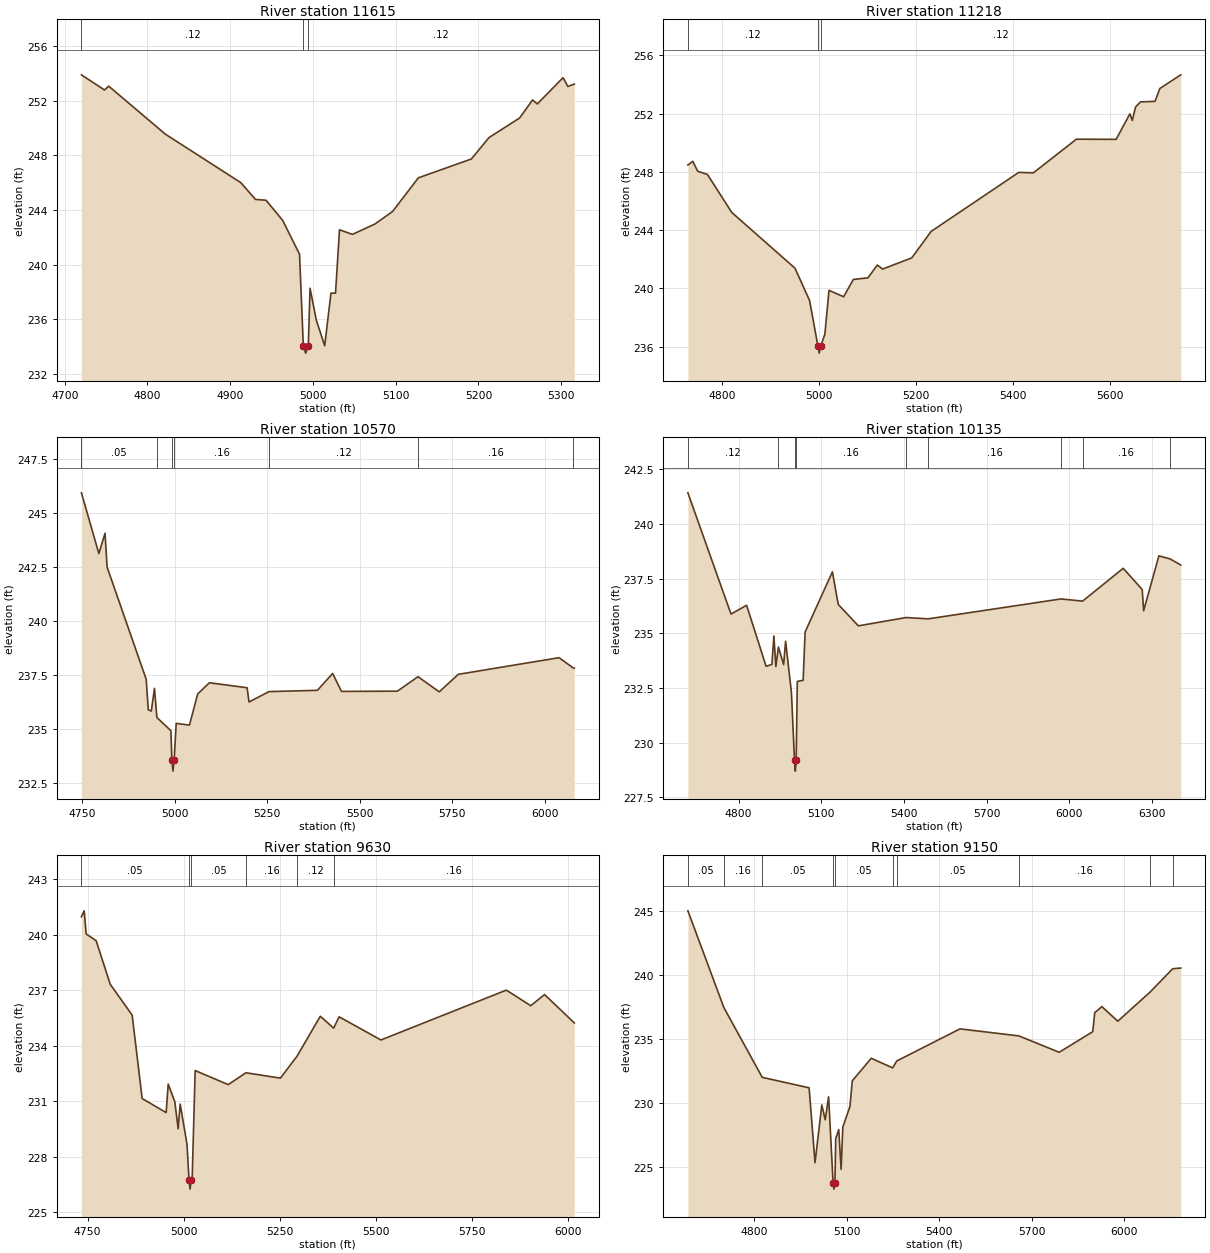
Type RM Length L Ch R = 1,11615,397,397,397
BEGIN DESCRIPTION:
UNT 091 IN BOCR 11.0
END DESCRIPTION:
XS GIS Cut Line= 3
      3713999.61     10601260.16      3713949.61     10601560.19
      3714099.60     10601810.18
#Sta/Elev= 30
  4720.2  253.90  4748.1  252.79  4753.2  253.07  4821.6  249.56  4912.8  246.01
  4930.6  244.78  4943.3  244.72  4963.5  243.24  4983.8  240.77  4988.4  234.03
  4991.2  233.53  4994.4  234.03  4996.5  238.28  5004.1  235.94  5014.2  234.07
  5021.8  237.92  5027.3  237.92  5032.1  242.56  5047.7  242.22  5074.9  242.98
  5096.3  243.90  5127.4  246.36  5191.5  247.74  5212.9  249.31  5249.8  250.74
  5265.4  252.06  5271.2  251.77  5302.3  253.69  5308.1  253.05  5315.9  253.22
#Mann=3,-1,0
  4720.2    0.12       0  4988.4    0.07       0  4994.4    0.12       0
Bank Sta=4988.4,4994.4
Exp/Cntr=0.3,0.1

Type RM Length L Ch R = 1,11218,648,648,648
BEGIN DESCRIPTION:
UNT 091 IN BOCR 10.0
END DESCRIPTION:
XS GIS Cut Line= 3
      3713638.57     10601240.03      3713591.41     10601787.07
      3713633.83     10602253.08
#Sta/Elev= 30
  4728.7  248.47  4738.9  248.72  4748.9  248.04  4769.0  247.82  4819.2  245.21
  4949.7  241.38  4979.8  239.16  4996.9  236.05  4999.6  235.55  5002.9  236.05
  5011.3  236.85  5019.9  239.86  5050.0  239.42  5070.1  240.61  5100.2  240.72
  5119.7  241.60  5130.3  241.32  5190.6  242.09  5230.7  243.91  5411.4  247.96
  5441.6  247.93  5530.3  250.24  5612.3  250.23  5640.7  251.98  5645.7  251.53
  5652.4  252.45  5662.5  252.80  5692.6  252.84  5702.6  253.72  5745.7  254.66
#Mann=3,-1,0
  4728.7    0.12       0  4996.9    0.07       0  5002.9    0.12       0
Bank Sta=4996.9,5002.9
Exp/Cntr=0.3,0.1

Type RM Length L Ch R = 1,10570,435,435,435
BEGIN DESCRIPTION:
UNT 091 IN BOCR 9.0
END DESCRIPTION:
XS GIS Cut Line= 3
      3713305.22     10601031.72      3713128.15     10601380.65
      3712904.66     10602294.73
#Sta/Elev= 30
  4747.7  245.93  4794.8  243.12  4811.5  244.06  4817.1  242.49  4922.8  237.30
  4928.4  235.89  4936.6  235.83  4945.1  236.88  4951.7  235.53  4989.6  234.92
  4992.2  233.55  4995.0  233.05  4998.2  233.55  5003.9  235.26  5039.7  235.18
  5062.0  236.62  5093.6  237.14  5195.6  236.91  5200.7  236.25  5254.7  236.73
  5385.6  236.79  5426.8  237.57  5450.6  236.74  5601.8  236.75  5657.5  237.42
  5715.0  236.72  5766.5  237.53  6038.7  238.30  6077.6  237.82  6080.0  237.82
#Mann=7,-1,0
  4747.7    0.05       0  4951.7    0.16       0  4992.2    0.07       0
  4998.2    0.16       0  5254.7    0.12       0  5657.5    0.16       0
  6077.6    0.12       0
Bank Sta=4992.2,4998.2
Exp/Cntr=0.3,0.1

Type RM Length L Ch R = 1,10135,505,505,505
BEGIN DESCRIPTION:
UNT 091 IN BOCR 8.0
END DESCRIPTION:
XS GIS Cut Line= 4
      3713112.55     10600792.08      3712711.48     10601203.57
      3712409.40     10601885.86      3712331.88     10602345.99
#Sta/Elev= 30
  4616.3  241.42  4772.6  235.88  4829.2  236.28  4899.9  233.49  4921.0  233.58
  4928.2  234.88  4935.2  233.48  4944.6  234.37  4963.5  233.57  4970.6  234.64
  4991.8  232.29  5002.9  229.20  5005.7  228.70  5008.9  229.20  5013.1  232.80
  5034.2  232.85  5041.4  235.06  5140.4  237.81  5161.5  236.32  5234.5  235.34
  5408.1  235.72  5487.3  235.66  5969.6  236.57  6047.7  236.47  6195.0  237.97
  6263.9  237.00  6269.0  236.03  6324.4  238.54  6364.9  238.40  6403.7  238.12
#Mann=9,-1,0
  4616.3    0.12       0  4944.6    0.16       0  5002.9    0.07       0
  5008.9    0.16       0  5408.1    0.12       0  5487.3    0.16       0
  5969.6    0.12       0  6047.7    0.16       0  6364.9    0.12       0
Bank Sta=5002.9,5008.9
Exp/Cntr=0.3,0.1

Type RM Length L Ch R = 1,9630,480,480,480
BEGIN DESCRIPTION:
UNT 091 IN BOCR 7.0
END DESCRIPTION:
XS GIS Cut Line= 3
      3713039.63     10600672.31      3712523.98     10600849.40
      3711904.39     10601250.31
#Sta/Elev= 30
  4733.9  240.96  4741.0  241.28  4746.3  240.03  4772.2  239.67  4808.8  237.32
  4866.0  235.65  4892.0  231.15  4954.5  230.39  4959.8  231.93  4977.1  230.97
  4985.7  229.52  4991.0  230.85  5008.8  228.68  5014.0  226.76  5016.7  226.26
  5020.0  226.76  5022.3  226.89  5030.0  232.66  5116.0  231.90  5162.2  232.54
  5252.0  232.25  5295.4  233.44  5355.8  235.59  5390.6  234.95  5404.8  235.56
  5513.6  234.31  5840.1  237.00  5903.7  236.16  5939.7  236.76  6017.1  235.23
#Mann=6,-1,0
  4733.9    0.05       0  5014.0    0.03       0  5020.0    0.05       0
  5162.2    0.16       0  5295.4    0.12       0  5390.6    0.16       0
Bank Sta=5014,5020
Exp/Cntr=0.3,0.1

Type RM Length L Ch R = 1,9150,456,456,456
BEGIN DESCRIPTION:
UNT 091 IN BOCR 6.0
END DESCRIPTION:
XS GIS Cut Line= 3
      3712849.58     10600260.21      3712549.61     10600510.19
      3711449.59     10601010.19
#Sta/Elev= 30
  4584.5  245.04  4701.1  237.48  4825.7  232.02  4977.7  231.20  4996.9  225.35
  5018.9  229.86  5029.9  228.70  5040.9  230.50  5055.5  223.78  5058.2  223.28
  5061.5  223.78  5064.0  227.24  5073.8  227.93  5081.5  224.83  5087.0  228.13
  5110.1  229.74  5117.8  231.75  5179.3  233.51  5248.8  232.76  5262.0  233.30
  5467.1  235.81  5658.2  235.26  5788.9  233.98  5897.7  235.59  5904.3  237.08
  5927.3  237.55  5979.0  236.41  6083.5  238.68  6157.0  240.51  6183.3  240.57
#Mann=10,-1,0
  4584.5    0.05       0  4701.1    0.16       0  4825.7    0.05       0
  5055.5    0.03       0  5061.5    0.05       0  5248.8    0.16       0
  5262.0    0.05       0  5658.2    0.16       0  6083.5    0.12       0
  6157.0    0.16       0
Bank Sta=5055.5,5061.5
Exp/Cntr=0.3,0.1

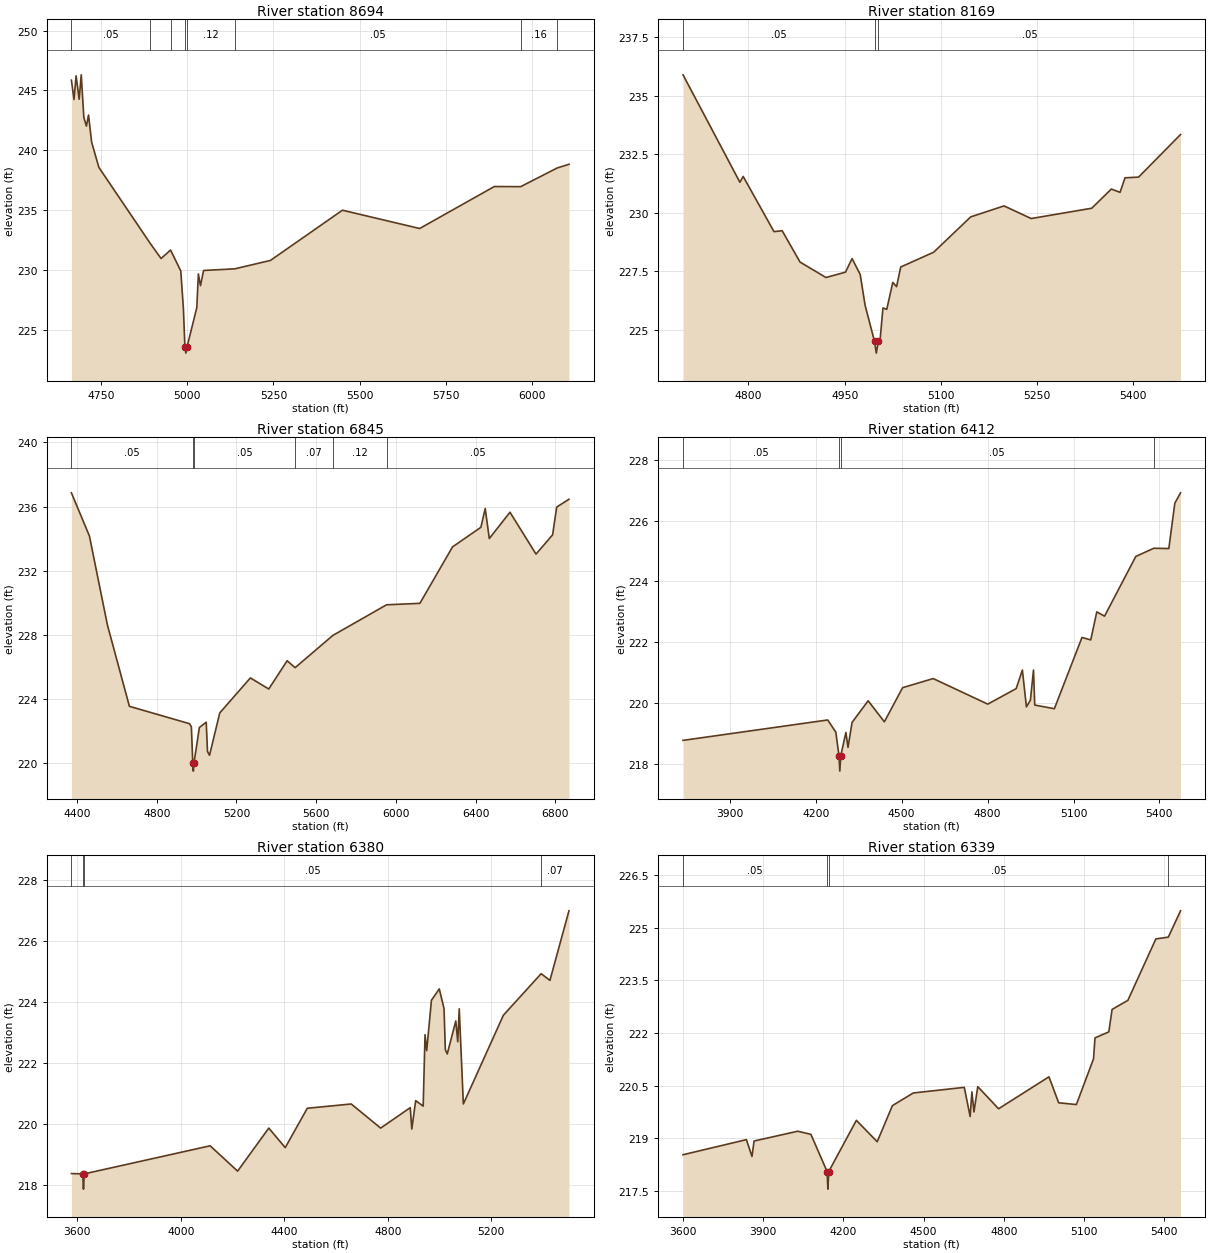
Type RM Length L Ch R = 1,8694,525,525,525
BEGIN DESCRIPTION:
UNT 091 IN BOCR 5.0
END DESCRIPTION:
XS GIS Cut Line= 3
      3712799.59     10600010.20      3712499.61     10600210.19
      3711599.61     10600810.19
#Sta/Elev= 30
  4664.4  245.85  4671.9  244.24  4677.9  246.22  4686.9  244.26  4692.9  246.30
  4700.4  242.73  4707.9  242.01  4714.0  242.94  4723.0  240.67  4744.0  238.56
  4893.0  232.20  4924.3  230.94  4951.8  231.65  4981.4  229.90  4988.9  226.82
  4993.4  223.53  4996.1  223.03  4999.4  223.53  5027.9  226.84  5032.4  229.65
  5038.5  228.67  5047.5  229.94  5138.2  230.08  5241.3  230.78  5450.1  234.98
  5673.9  233.45  5890.3  236.96  5966.7  236.95  6072.4  238.51  6106.6  238.82
#Mann=8,-1,0
  4664.4    0.05       0  4893.0    0.16       0  4951.8    0.12       0
  4993.4    0.07       0  4999.4    0.12       0  5138.2    0.05       0
  5966.7    0.16       0  6072.4    0.05       0
Bank Sta=4993.4,4999.4
Exp/Cntr=0.3,0.1

Type RM Length L Ch R = 1,8169,1324,1324,1324
BEGIN DESCRIPTION:
UNT 091 IN BOCR 4.0
END DESCRIPTION:
XS GIS Cut Line= 3
      3712649.61     10599910.19      3712349.61     10599860.19
      3711949.64     10600110.17
#Sta/Elev= 30
  4697.9  235.90  4786.6  231.31  4791.7  231.56  4839.8  229.20  4852.5  229.24
  4880.4  227.90  4920.9  227.24  4951.3  227.47  4961.5  228.05  4974.2  227.37
  4981.8  226.06  4996.5  224.51  4999.3  224.01  5002.5  224.51  5005.0  224.51
  5009.7  225.94  5015.6  225.88  5025.0  227.03  5030.9  226.85  5037.4  227.69
  5088.7  228.32  5146.5  229.83  5198.4  230.30  5240.8  229.76  5335.2  230.20
  5365.8  231.02  5379.4  230.88  5387.1  231.50  5408.3  231.53  5473.7  233.35
#Mann=3,-1,0
  4697.9    0.05       0  4996.5    0.03       0  5002.5    0.05       0
Bank Sta=4996.5,5002.5
Exp/Cntr=0.3,0.1

Type RM Length L Ch R = 1,6845,433,433,433
BEGIN DESCRIPTION:
UNT 091 IN BOCR 3.0
END DESCRIPTION:
XS GIS Cut Line= 3
      3712799.65     10598810.19      3712149.61     10598860.19
      3711749.60     10600660.22
#Sta/Elev= 30
  4372.0  236.86  4462.3  234.17  4552.6  228.62  4662.9  223.55  4963.8  222.47
  4973.8  222.28  4980.8  220.01  4983.6  219.51  4986.8  220.01  5013.9  222.23
  5048.3  222.56  5054.7  220.73  5064.9  220.50  5116.2  223.14  5269.8  225.32
  5362.0  224.63  5454.2  226.39  5494.2  225.96  5683.5  227.97  5953.1  229.88
  6120.1  229.97  6284.0  233.49  6426.1  234.71  6447.9  235.88  6468.4  234.01
  6572.1  235.65  6702.7  233.04  6785.9  234.24  6806.4  235.97  6867.9  236.46
#Mann=6,-1,0
  4372.0    0.05       0  4980.8    0.03       0  4986.8    0.05       0
  5494.2    0.07       0  5683.5    0.12       0  5953.1    0.05       0
Bank Sta=4980.8,4986.8
Exp/Cntr=0.3,0.1

Type RM Length L Ch R = 1,6412,32,32,32
BEGIN DESCRIPTION:
Mapping XS 56164c63
END DESCRIPTION:
XS GIS Cut Line= 5
      3712566.70     10597933.81      3711743.77     10598836.60
      3711761.13     10598923.41      3711816.69     10599010.21
      3711913.90     10599319.22
#Sta/Elev= 30
  3736.6  218.78  4241.8  219.45  4270.1  219.05  4281.3  218.27  4284.1  217.77
  4287.3  218.27  4305.3  219.04  4312.7  218.55  4326.9  219.37  4383.0  220.08
  4439.7  219.39  4503.3  220.51  4610.0  220.81  4800.7  219.97  4899.8  220.48
  4921.5  221.09  4935.6  219.88  4949.5  220.10  4960.3  221.09  4964.7  219.94
  5033.2  219.82  5129.6  222.16  5160.2  222.08  5181.3  223.00  5208.4  222.86
  5317.5  224.82  5380.5  225.09  5432.8  225.08  5453.8  226.57  5473.7  226.91
#Mann=4,-1,0
  3736.6    0.05       0  4281.3    0.03       0  4287.3    0.05       0
  5380.5    0.07       0
Bank Sta=4281.3,4287.3
Exp/Cntr=0.3,0.1

Type RM Length L Ch R = 1,6380,41,41,41
BEGIN DESCRIPTION:
Mapping XS eb329ee8
END DESCRIPTION:
XS GIS Cut Line= 6
      3712611.82     10597795.81      3711765.47     10598750.66
      3711713.39     10598828.79      3711730.75     10598924.27
      3711765.47     10598985.04      3711891.35     10599349.66
#Sta/Elev= 30
  3577.6  218.38  3621.4  218.37  3624.2  217.87  3627.4  218.37  4113.7  219.29
  4219.9  218.46  4340.4  219.87  4403.9  219.23  4489.2  220.52  4659.0  220.66
  4772.7  219.87  4887.1  220.54  4893.1  219.84  4908.1  220.77  4937.1  220.59
  4944.2  222.93  4950.7  222.41  4969.0  224.06  4999.3  224.43  5017.6  223.79
  5022.7  222.44  5030.1  222.30  5063.0  223.38  5070.7  222.70  5076.4  223.78
  5092.3  220.66  5247.1  223.57  5393.0  224.93  5426.9  224.71  5500.4  226.99
#Mann=4,-1,0
  3577.6    0.05       0  3621.4    0.03       0  3627.4    0.05       0
  5393.0    0.07       0
Bank Sta=3621.4,3627.4
Exp/Cntr=0.3,0.1

Type RM Length L Ch R = 1,6339,119,119,119
BEGIN DESCRIPTION:
Mapping XS 9d80aefd
END DESCRIPTION:
XS GIS Cut Line= 6
      3712549.36     10597805.32      3711695.16     10598791.46
      3711681.27     10598853.96      3711677.80     10598909.52
      3711740.30     10599013.68      3711830.49     10599315.47
#Sta/Elev= 30
  3600.1  218.53  3837.3  218.96  3858.1  218.48  3865.8  218.92  4029.1  219.20
  4078.5  219.11  4139.1  218.05  4141.9  217.55  4145.1  218.05  4248.5  219.51
  4326.4  218.90  4383.4  219.93  4461.3  220.29  4652.1  220.45  4674.0  219.62
  4680.6  220.32  4688.3  219.75  4702.5  220.47  4780.4  219.84  4968.8  220.75
  5005.1  220.01  5071.3  219.96  5135.4  221.26  5141.0  221.86  5192.6  222.03
  5204.9  222.67  5264.0  222.93  5368.6  224.68  5415.1  224.73  5460.9  225.48
#Mann=4,-1,0
  3600.1    0.05       0  4139.1    0.03       0  4145.1    0.05       0
  5415.1    0.07       0
Bank Sta=4139.1,4145.1
Exp/Cntr=0.3,0.1

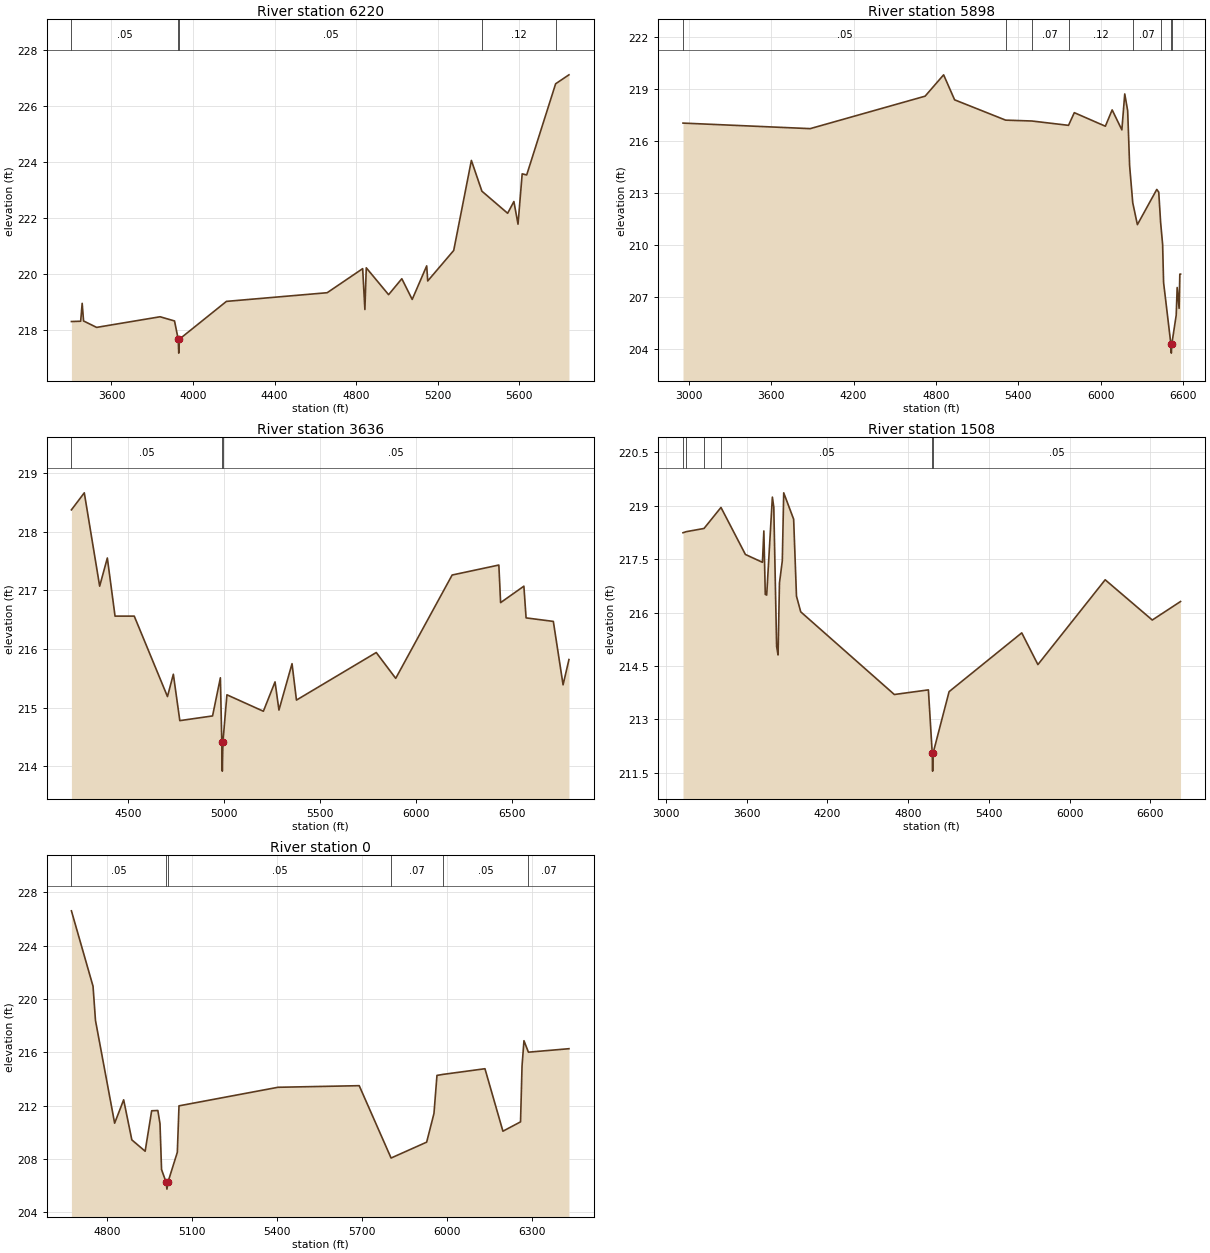
Type RM Length L Ch R = 1,6220,322,322,322
BEGIN DESCRIPTION:
Mapping XS 0a5dab4a
END DESCRIPTION:
XS GIS Cut Line= 4
      3712512.03     10597648.20      3711739.43     10598485.91
      3711570.16     10598867.85      3711405.29     10599735.57
#Sta/Elev= 30
  3403.5  218.30  3448.9  218.31  3456.3  218.95  3463.1  218.32  3527.1  218.09
  3838.5  218.47  3909.3  218.32  3927.3  217.67  3930.1  217.17  3933.3  217.67
  4164.0  219.02  4658.2  219.33  4832.2  220.19  4843.1  218.73  4849.9  220.22
  4959.4  219.26  5024.3  219.83  5075.2  219.09  5146.3  220.29  5151.4  219.75
  5278.8  220.84  5365.5  224.06  5417.1  222.96  5543.4  222.17  5574.0  222.59
  5594.3  221.78  5614.7  223.58  5636.8  223.54  5778.8  226.80  5844.1  227.12
#Mann=5,-1,0
  3403.5    0.05       0  3927.3    0.03       0  3933.3    0.05       0
  5417.1    0.12       0  5778.8    0.05       0
Bank Sta=3927.3,3933.3
Exp/Cntr=0.3,0.1

Type RM Length L Ch R = 1,5898,2262,2262,2262
BEGIN DESCRIPTION:
UNT 091 IN BOCR 2.0
END DESCRIPTION:
XS GIS Cut Line= 3
      3712249.61     10597110.18      3711249.61     10598910.19
      3710157.41     10600032.67
#Sta/Elev= 30
  2957.3  217.02  3883.9  216.70  4721.3  218.57  4856.3  219.80  4936.4  218.36
  5308.2  217.19  5499.6  217.14  5766.4  216.89  5808.5  217.62  6034.9  216.84
  6084.3  217.78  6155.0  216.63  6176.1  218.70  6197.4  217.73  6211.6  214.56
  6234.4  212.43  6268.2  211.17  6409.6  213.20  6423.8  213.04  6437.5  211.30
  6452.1  210.03  6459.0  207.84  6512.6  204.27  6515.4  203.77  6518.6  204.27
  6551.1  205.96  6558.1  207.55  6572.2  206.35  6577.4  208.32  6582.6  208.32
#Mann=8,-1,0
  2957.3    0.05       0  5308.2    0.12       0  5499.6    0.07       0
  5766.4    0.12       0  6234.4    0.07       0  6437.5    0.12       0
  6512.6    0.03       0  6518.6    0.12       0
Bank Sta=6512.6,6518.6
Exp/Cntr=0.3,0.1

Type RM Length L Ch R = 1,3636,2128,2128,2128
BEGIN DESCRIPTION:
Mapping XS 1b746f22
END DESCRIPTION:
XS GIS Cut Line= 4
      3712496.68     10597033.21      3712142.54     10597017.59
      3711616.50     10596908.21      3709939.39     10596626.96
#Sta/Elev= 30
  4205.5  218.37  4272.6  218.66  4352.7  217.07  4392.7  217.55  4432.8  216.56
  4532.9  216.56  4706.0  215.19  4736.6  215.57  4770.3  214.78  4940.9  214.86
  4981.7  215.51  4989.0  214.42  4991.7  213.92  4995.0  214.42  5015.7  215.22
  5205.7  214.94  5266.5  215.44  5286.8  214.96  5355.0  215.75  5378.0  215.13
  5793.8  215.94  5895.2  215.50  6189.2  217.26  6432.6  217.43  6441.7  216.79
  6563.0  217.07  6574.5  216.53  6716.5  216.47  6767.2  215.39  6797.8  215.82
#Mann=3,-1,0
  4205.5    0.05       0  4989.0    0.03       0  4995.0    0.05       0
Bank Sta=4989,4995
Exp/Cntr=0.3,0.1

Type RM Length L Ch R = 1,1508,1508,1508,1508
BEGIN DESCRIPTION:
UNT 091 IN BOCR 1.0
END DESCRIPTION:
XS GIS Cut Line= 3
      3712549.61     10597460.20      3711949.61     10595660.19
      3710149.59     10595660.19
#Sta/Elev= 30
  3126.9  218.24  3151.3  218.27  3283.1  218.36  3409.1  218.95  3590.7  217.63
  3717.2  217.41  3727.7  218.29  3738.3  216.51  3748.8  216.49  3791.0  219.24
  3801.5  218.96  3822.6  215.05  3833.2  214.81  3843.7  216.83  3864.8  217.45
  3875.3  219.36  3949.1  218.62  3970.2  216.46  4001.8  216.02  4697.5  213.70
  4950.5  213.83  4979.1  212.05  4981.9  211.55  4985.1  212.05  5104.3  213.78
  5644.3  215.43  5764.3  214.54  6264.3  216.92  6614.3  215.79  6824.3  216.31
#Mann=6,-1,0
  3126.9    0.05       0  3151.3    0.12       0  3283.1    0.07       0
  3409.1    0.05       0  4979.1    0.03       0  4985.1    0.05       0
Bank Sta=4979.1,4985.1
Exp/Cntr=0.3,0.1

Type RM Length L Ch R = 1,0,0,0,0
BEGIN DESCRIPTION:
UNT 090 IN BOCR 9.0
END DESCRIPTION:
XS GIS Cut Line= 3
      3712449.63     10594160.18      3712149.50     10594290.00
      3710799.64     10594760.18
#Sta/Elev= 30
  4673.0  226.60  4749.3  220.95  4758.0  218.38  4825.6  210.69  4857.4  212.44
  4886.3  209.44  4933.3  208.59  4956.3  211.62  4978.1  211.64  4985.7  210.66
  4991.2  207.22  5007.5  206.25  5010.2  205.75  5013.5  206.25  5046.9  208.51
  5052.8  211.99  5402.3  213.38  5689.0  213.50  5801.5  208.08  5927.1  209.27
  5952.9  211.42  5963.5  214.27  5986.1  214.35  6132.9  214.77  6196.3  210.09
  6258.5  210.79  6263.8  214.97  6270.6  216.87  6286.3  216.01  6429.4  216.27
#Mann=6,-1,0
  4673.0    0.05       0  5007.5    0.03       0  5013.5    0.05       0
  5801.5    0.07       0  5986.1    0.05       0  6286.3    0.07       0
Bank Sta=5007.5,5013.5
Exp/Cntr=0.3,0.1

Chan Stop Cuts=-1