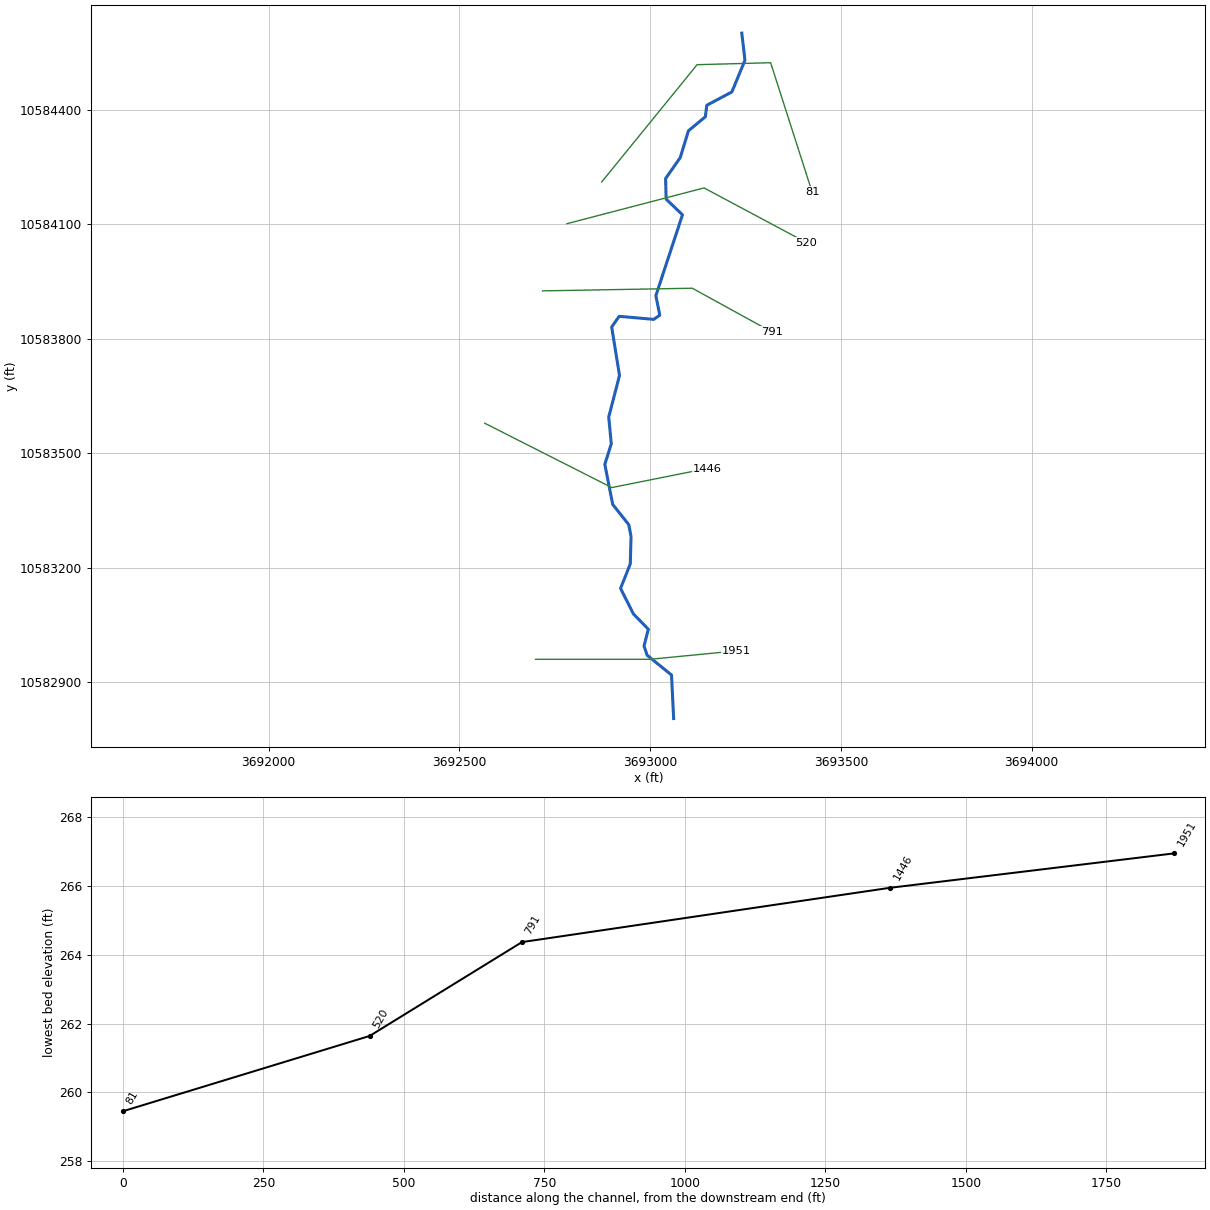
--- UNT 093 IN BOCR.prj (project) ---

Proj Title=UNT 093 IN BOCR Base Level Engineering
Current Plan=p01
Default Exp/Contr=0.3,0.1
English Units
Geom File=g01
Flow File=f01
Plan File=p01
Y Axis Title=Elevation
X Axis Title(PF)=Main Channel Distance
X Axis Title(XS)=Station
BEGIN DESCRIPTION:
UNT 093 IN BOCR
END DESCRIPTION:
DSS Export Rating Curves= 0
DSS Export Rating Curve Sorted= 0
DSS Export Volume Flow Curves= 0
DXF OffsetX= 0
DXF OffsetY= 0
DXF ScaleX= 1
DXF ScaleY= 10

--- UNT 093 IN BOCR.p01 (plan) ---

Plan Title=Multiple Run
Short Identifier=Multiple
Geom File=g01
Flow File=f01
Subcritical Flow
K Sum by GR= 0
Std Step Tol= 0.01
Critical Tol= 0.01
Num of Std Step Trials= 20
Max Error Tol= 0.3
Flow Tol Ratio= 0.001
Split Flow NTrial= 30
Split Flow Tol= 0.02
Split Flow Ratio= 0.02
Log Output Level= 0
Friction Slope Method= 1
Unsteady Friction Slope Method= 2
Unsteady Bridges Friction Slope Method= 1
Parabolic Critical Depth
Global Vel Dist=  1 , 1 , 1
Global Log Level= 0
CheckData=True
Encroach Param= -1, 0, 0, 0
BEGIN DESCRIPTION:
Multiple Run
END DESCRIPTION:

--- UNT 093 IN BOCR.f01 (steady flow) ---

Flow Title=Multiple
Program Version=4.10
Number of Profiles= 7
Profile Names=10-year,25-year,50-year,1pct_min,100-year,1pct_plu,500-year
River Rch & RM=UNT 093 IN BOCR,Reach-1         ,1951
     426     564     675     594     804    1087    1143
Boundary for River Rch & Prof#=UNT 093 IN BOCR,Reach-1         , 1
Up Type= 0
Dn Type= 3
Dn Slope=0.005
Boundary for River Rch & Prof#=UNT 093 IN BOCR,Reach-1         , 2
Up Type= 0
Dn Type= 3
Dn Slope=0.005
Boundary for River Rch & Prof#=UNT 093 IN BOCR,Reach-1         , 3
Up Type= 0
Dn Type= 3
Dn Slope=0.005
Boundary for River Rch & Prof#=UNT 093 IN BOCR,Reach-1         , 4
Up Type= 0
Dn Type= 3
Dn Slope=0.005
Boundary for River Rch & Prof#=UNT 093 IN BOCR,Reach-1         , 5
Up Type= 0
Dn Type= 3
Dn Slope=0.005
Boundary for River Rch & Prof#=UNT 093 IN BOCR,Reach-1         , 6
Up Type= 0
Dn Type= 3
Dn Slope=0.005
Boundary for River Rch & Prof#=UNT 093 IN BOCR,Reach-1         , 7
Up Type= 0
Dn Type= 3
Dn Slope=0.005
DSS Import GetInterval= 0
DSS Import GetPeak= 0
DSS Import FillOption= 0

--- UNT 093 IN BOCR.g01 (geometry) ---

Geom Title=Existing Conditions

River Reach=UNT 093 IN BOCR,Reach-1
Reach XY= 30
      3693061.65     10582804.92      3693056.00     10582919.00
      3692992.00     10582971.00      3692984.00     10582995.00
      3692995.25     10583039.00      3692956.25     10583079.00
      3692922.50     10583146.00      3692948.00     10583210.00
      3692950.00     10583282.00      3692944.00     10583313.00
      3692902.00     10583366.00      3692881.25     10583471.00
      3692898.25     10583525.00      3692891.50     10583595.00
      3692919.75     10583704.00      3692899.25     10583831.00
      3692919.00     10583859.00      3693009.50     10583851.00
      3693025.25     10583862.00      3693015.00     10583913.00
      3693084.75     10584125.00      3693042.00     10584166.00
      3693040.50     10584220.00      3693079.00     10584275.00
      3693100.25     10584345.00      3693144.75     10584382.00
      3693148.50     10584412.00      3693214.25     10584447.00
      3693248.50     10584530.00      3693240.25     10584601.00

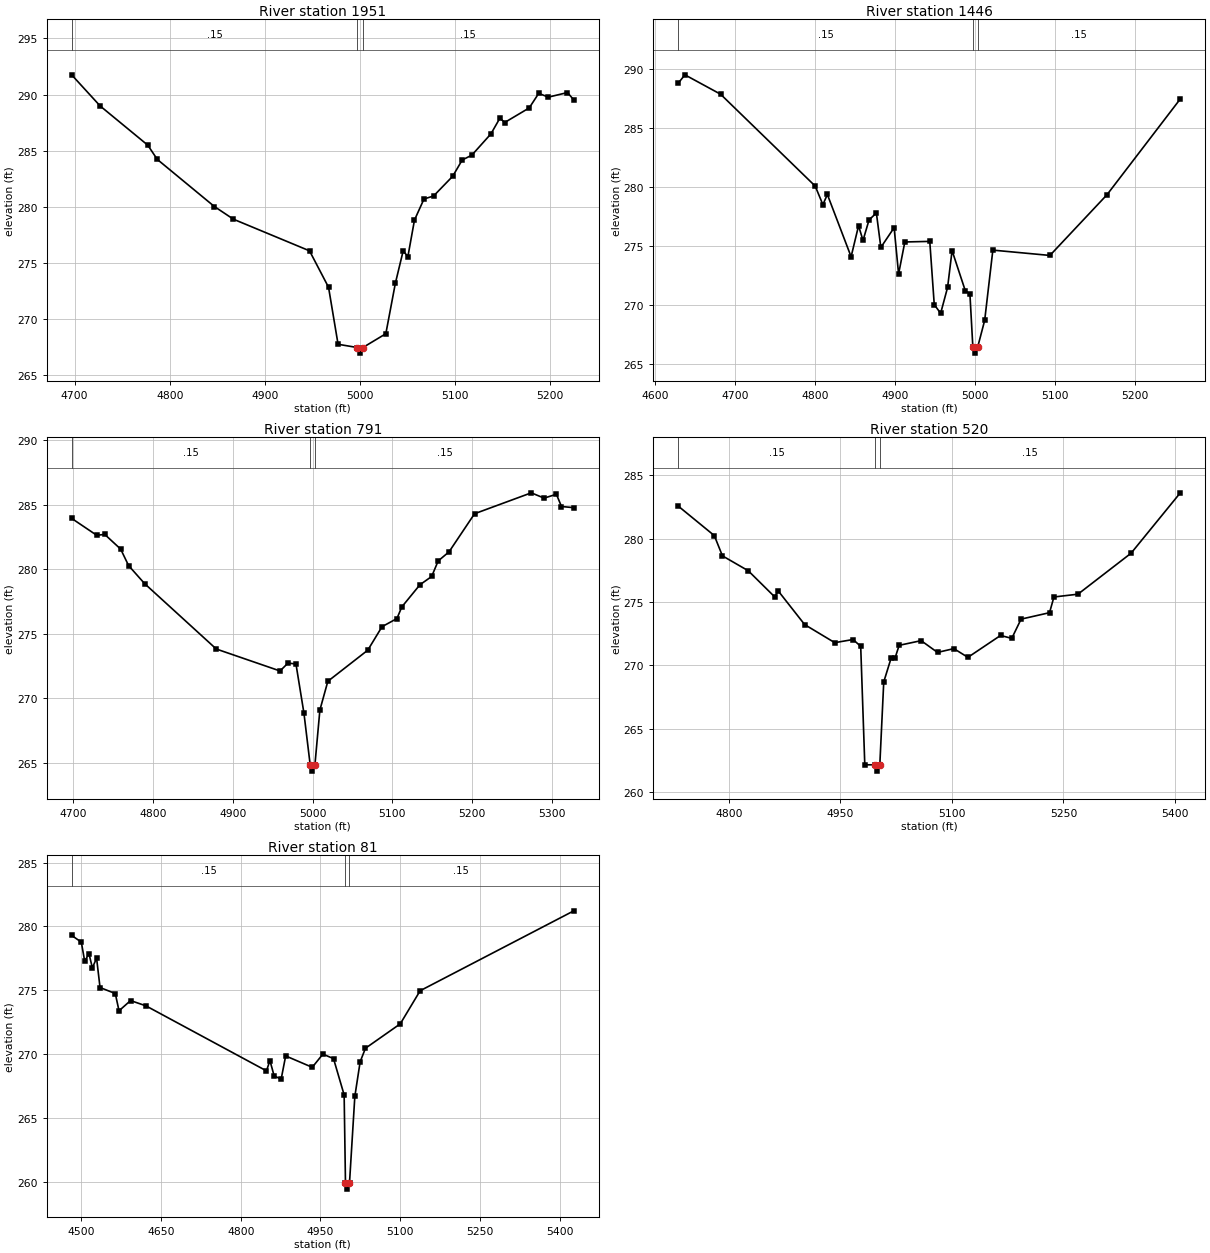
Type RM Length L Ch R = 1,1951,505,505,505
BEGIN DESCRIPTION:
UNT 093 IN BOCR 4.0
END DESCRIPTION:
XS GIS Cut Line= 3
      3692699.60     10582960.19      3692999.61     10582960.19
      3693226.32     10582982.32
#Sta/Elev= 30
  4696.9  291.76  4726.9  288.98  4776.9  285.49  4786.9  284.22  4846.9  280.02
  4866.9  278.89  4946.9  276.07  4966.9  272.82  4976.9  267.74  4997.0  267.45
  4999.8  266.95  5003.0  267.45  5027.1  268.68  5037.1  273.17  5045.3  276.06
  5050.3  275.56  5057.2  278.81  5067.2  280.69  5077.3  280.96  5097.4  282.72
  5107.4  284.17  5117.5  284.60  5137.6  286.50  5147.0  287.90  5152.0  287.51
  5177.8  288.81  5187.8  290.11  5197.9  289.77  5218.0  290.18  5224.7  289.52
#Mann=3,-1,0
  4696.9    0.15       0  4997.0    0.05       0  5003.0    0.15       0
Bank Sta=4997,5003
Exp/Cntr=0.3,0.1

Type RM Length L Ch R = 1,1446,655,655,655
BEGIN DESCRIPTION:
UNT 093 IN BOCR 3.0
END DESCRIPTION:
XS GIS Cut Line= 3
      3692566.59     10583578.84      3692899.61     10583410.19
      3693149.57     10583460.18
#Sta/Elev= 30
  4628.3  288.79  4636.8  289.51  4681.4  287.87  4799.8  280.09  4809.4  278.52
  4815.0  279.38  4844.7  274.11  4854.0  276.73  4859.6  275.49  4867.1  277.22
  4876.3  277.82  4881.9  274.90  4898.5  276.57  4904.1  272.65  4911.9  275.36
  4943.1  275.41  4948.7  270.06  4956.7  269.32  4965.4  271.52  4971.0  274.63
  4987.6  271.22  4993.3  270.98  4997.0  266.45  4999.8  265.95  5003.0  266.45
  5011.8  268.73  5022.0  274.67  5093.4  274.22  5164.8  279.36  5256.5  287.47
#Mann=3,-1,0
  4628.3    0.15       0  4997.0    0.05       0  5003.0    0.15       0
Bank Sta=4997,5003
Exp/Cntr=0.3,0.1

Type RM Length L Ch R = 1,791,271,271,271
BEGIN DESCRIPTION:
UNT 093 IN BOCR 2.0
END DESCRIPTION:
XS GIS Cut Line= 3
      3692718.11     10583925.65      3693110.52     10583932.60
      3693318.82     10583818.03
#Sta/Elev= 30
  4697.7  283.95  4729.2  282.64  4739.2  282.71  4759.2  281.57  4769.2  280.29
  4789.2  278.90  4879.2  273.83  4959.2  272.13  4969.2  272.74  4979.2  272.67
  4989.2  268.86  4997.0  264.87  4999.8  264.37  5003.0  264.87  5009.2  269.10
  5019.2  271.33  5069.3  273.74  5087.2  275.56  5105.9  276.19  5112.0  277.09
  5134.8  278.81  5149.5  279.45  5157.6  280.65  5171.3  281.36  5203.3  284.31
  5274.5  285.93  5290.6  285.52  5306.0  285.82  5312.4  284.87  5327.9  284.78
#Mann=3,-1,0
  4697.7    0.15       0  4997.0    0.05       0  5003.0    0.15       0
Bank Sta=4997,5003
Exp/Cntr=0.3,0.1

Type RM Length L Ch R = 1,520,439,439,439
BEGIN DESCRIPTION:
Mapping XS 9d46d81a
END DESCRIPTION:
XS GIS Cut Line= 3
      3692781.98     10584101.70      3693141.33     10584195.44
      3693409.60     10584052.19
#Sta/Elev= 30
  4731.7  282.59  4780.4  280.25  4791.3  278.65  4826.1  277.47  4861.4  275.42
  4866.6  275.86  4901.9  273.22  4942.4  271.79  4967.0  272.04  4977.3  271.50
  4982.8  262.14  4997.0  262.14  4999.8  261.64  5003.0  262.14  5008.3  268.69
  5018.1  270.55  5023.3  270.54  5029.0  271.58  5058.6  271.95  5080.6  271.02
  5102.6  271.32  5121.5  270.63  5165.4  272.36  5180.5  272.13  5193.0  273.65
  5231.3  274.16  5237.2  275.40  5269.5  275.62  5341.0  278.86  5407.2  283.63
#Mann=3,-1,0
  4731.7    0.15       0  4997.0    0.05       0  5003.0    0.15       0
Bank Sta=4997,5003
Exp/Cntr=0.3,0.1

Type RM Length L Ch R = 1,81,0,0,0
BEGIN DESCRIPTION:
UNT 093 IN BOCR 1.0
END DESCRIPTION:
XS GIS Cut Line= 4
      3692873.13     10584211.10      3693123.10     10584518.36
      3693315.81     10584523.57      3693424.44     10584184.74
#Sta/Elev= 30
  4481.9  279.30  4500.1  278.77  4506.5  277.26  4514.4  277.88  4520.9  276.76
  4528.8  277.52  4535.3  275.22  4564.0  274.75  4571.0  273.40  4592.7  274.20
  4621.5  273.79  4848.4  268.70  4854.9  269.51  4862.8  268.31  4876.0  268.05
  4884.5  269.87  4934.5  268.98  4954.5  270.01  4974.5  269.66  4994.5  266.82
  4997.0  259.95  4999.8  259.45  5003.0  259.95  5004.6  259.95  5014.6  266.70
  5024.6  269.41  5034.6  270.47  5100.1  272.38  5137.5  274.97  5426.6  281.22
#Mann=3,-1,0
  4481.9    0.15       0  4997.0    0.05       0  5003.0    0.15       0
Bank Sta=4997,5003
Exp/Cntr=0.3,0.1

Chan Stop Cuts=-1