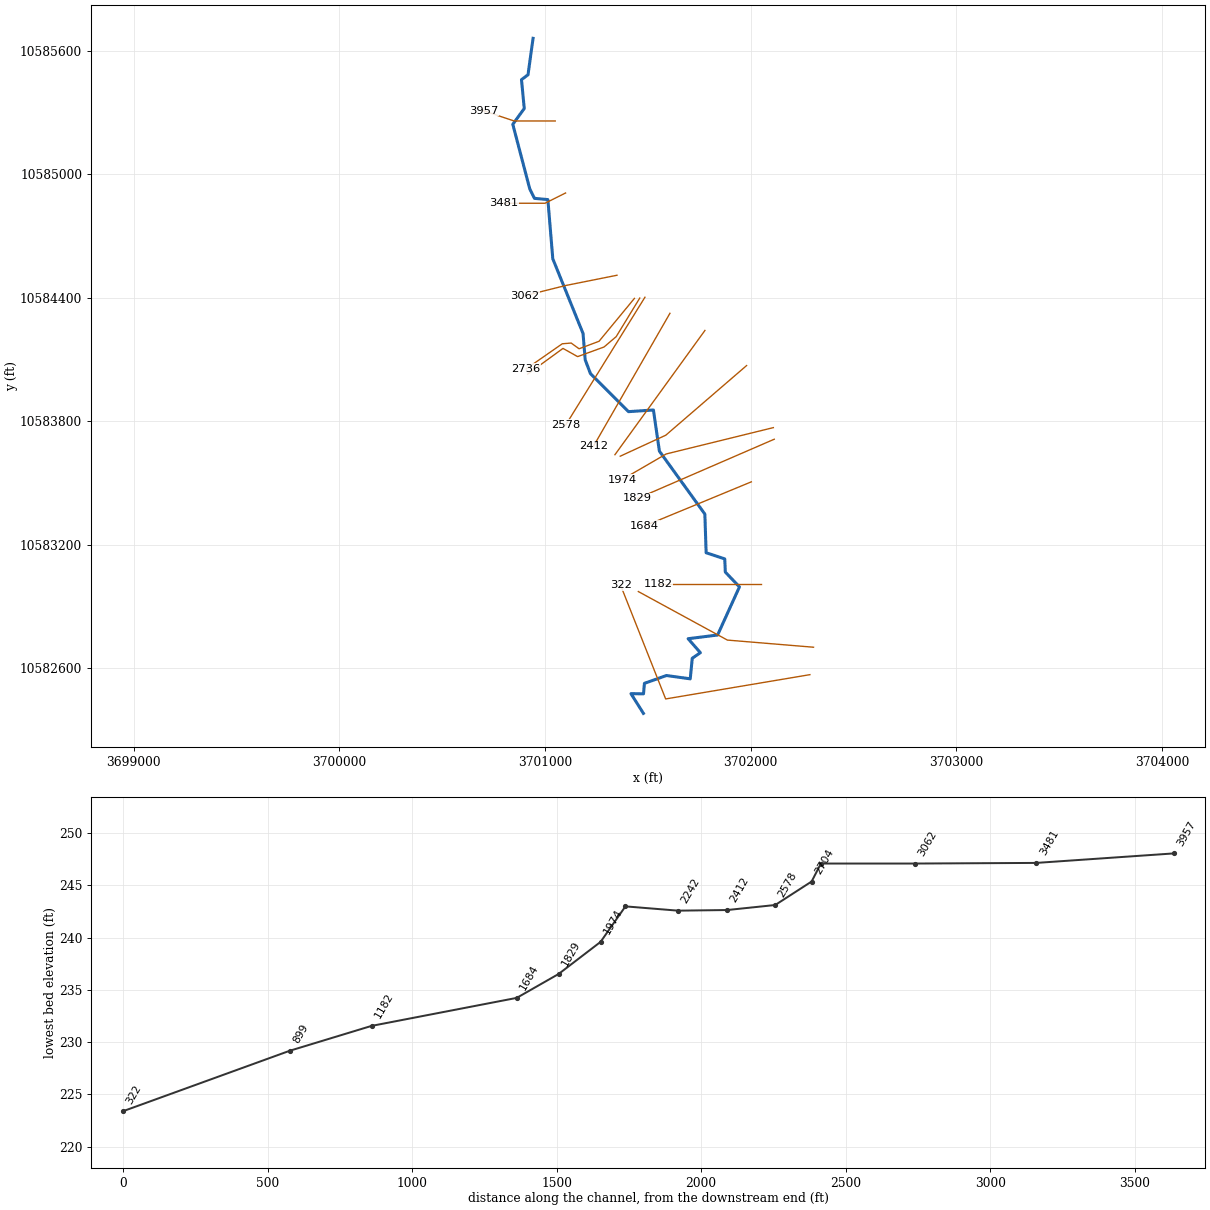
--- UNT 095 IN BOCR.prj (project) ---

Proj Title=UNT 095 IN BOCR Base Level Engineering
Current Plan=p01
Default Exp/Contr=0.3,0.1
English Units
Geom File=g01
Flow File=f01
Plan File=p01
Y Axis Title=Elevation
X Axis Title(PF)=Main Channel Distance
X Axis Title(XS)=Station
BEGIN DESCRIPTION:
UNT 095 IN BOCR
END DESCRIPTION:
DSS Export Rating Curves= 0
DSS Export Rating Curve Sorted= 0
DSS Export Volume Flow Curves= 0
DXF OffsetX= 0
DXF OffsetY= 0
DXF ScaleX= 1
DXF ScaleY= 10

--- UNT 095 IN BOCR.p01 (plan) ---

Plan Title=Multiple Run
Short Identifier=Multiple
Geom File=g01
Flow File=f01
Subcritical Flow
K Sum by GR= 0
Std Step Tol= 0.01
Critical Tol= 0.01
Num of Std Step Trials= 20
Max Error Tol= 0.3
Flow Tol Ratio= 0.001
Split Flow NTrial= 30
Split Flow Tol= 0.02
Split Flow Ratio= 0.02
Log Output Level= 0
Friction Slope Method= 1
Unsteady Friction Slope Method= 2
Unsteady Bridges Friction Slope Method= 1
Parabolic Critical Depth
Global Vel Dist=  1 , 1 , 1
Global Log Level= 0
CheckData=True
Encroach Param= -1, 0, 0, 0
BEGIN DESCRIPTION:
Multiple Run
END DESCRIPTION:

--- UNT 095 IN BOCR.f01 (steady flow) ---

Flow Title=Multiple
Program Version=4.10
Number of Profiles= 7
Profile Names=10-year,25-year,50-year,1pct_min,100-year,1pct_plu,500-year
River Rch & RM=UNT 095 IN BOCR,Reach-1         ,3957
     270     339     392     333     450     609     595
Boundary for River Rch & Prof#=UNT 095 IN BOCR,Reach-1         , 1
Up Type= 0
Dn Type= 3
Dn Slope=0.005
Boundary for River Rch & Prof#=UNT 095 IN BOCR,Reach-1         , 2
Up Type= 0
Dn Type= 3
Dn Slope=0.005
Boundary for River Rch & Prof#=UNT 095 IN BOCR,Reach-1         , 3
Up Type= 0
Dn Type= 3
Dn Slope=0.005
Boundary for River Rch & Prof#=UNT 095 IN BOCR,Reach-1         , 4
Up Type= 0
Dn Type= 3
Dn Slope=0.005
Boundary for River Rch & Prof#=UNT 095 IN BOCR,Reach-1         , 5
Up Type= 0
Dn Type= 3
Dn Slope=0.005
Boundary for River Rch & Prof#=UNT 095 IN BOCR,Reach-1         , 6
Up Type= 0
Dn Type= 3
Dn Slope=0.005
Boundary for River Rch & Prof#=UNT 095 IN BOCR,Reach-1         , 7
Up Type= 0
Dn Type= 3
Dn Slope=0.005
DSS Import GetInterval= 0
DSS Import GetPeak= 0
DSS Import FillOption= 0

--- UNT 095 IN BOCR.g01 (geometry) ---

Geom Title=Existing Conditions

River Reach=UNT 095 IN BOCR,Reach-1
Reach XY= 30
      3700941.50     10585662.00      3700917.00     10585485.00
      3700885.25     10585461.00      3700898.75     10585321.00
      3700843.00     10585244.00      3700925.50     10584930.00
      3700948.25     10584884.00      3701013.50     10584878.00
      3701037.50     10584590.00      3701184.50     10584227.00
      3701195.00     10584099.00      3701220.50     10584032.00
      3701405.50     10583847.00      3701526.75     10583855.00
      3701555.75     10583655.00      3701776.75     10583349.00
      3701783.00     10583161.00      3701873.50     10583131.00
      3701876.25     10583067.00      3701945.00     10582995.00
      3701838.75     10582761.00      3701695.50     10582743.00
      3701755.00     10582675.00      3701715.50     10582648.00
      3701705.75     10582548.00      3701590.00     10582564.00
      3701483.00     10582526.00      3701478.50     10582475.00
      3701417.50     10582476.00      3701478.00     10582380.00

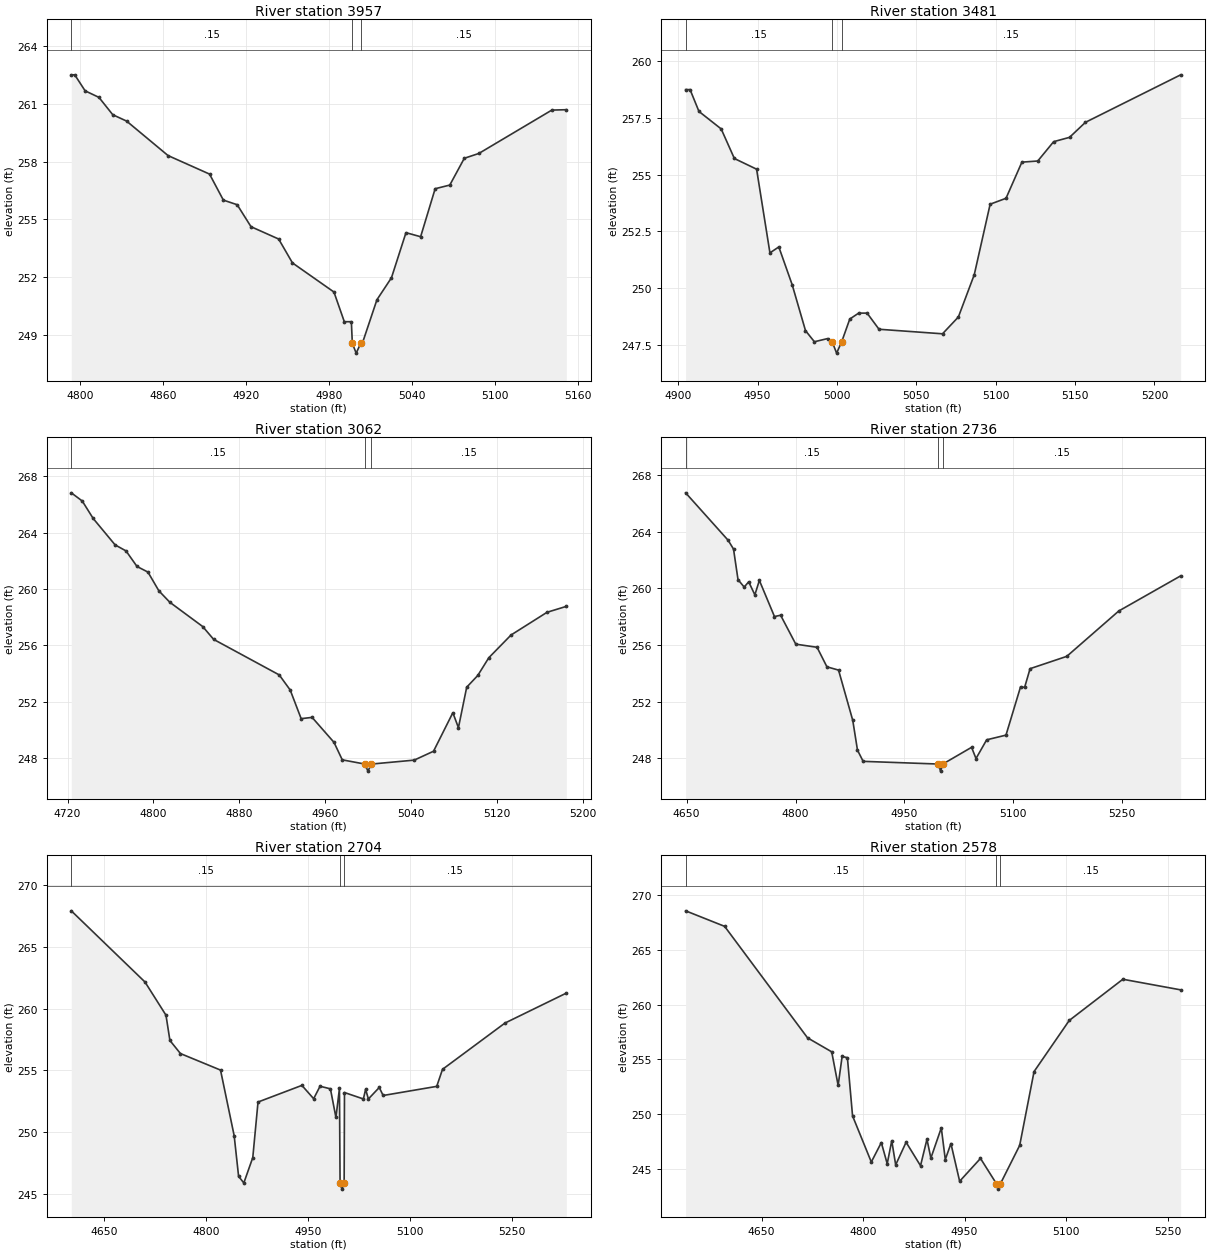
Type RM Length L Ch R = 1,3957,476,476,476
BEGIN DESCRIPTION:
UNT 095 IN BOCR 8.0
END DESCRIPTION:
XS GIS Cut Line= 3
      3701049.59     10585260.19      3700849.61     10585260.19
      3700699.60     10585310.19
#Sta/Elev= 30
  4793.7  262.50  4796.2  262.50  4803.7  261.67  4813.7  261.33  4823.7  260.43
  4833.7  260.10  4863.7  258.31  4893.7  257.35  4903.7  256.00  4913.7  255.76
  4923.7  254.62  4943.7  253.98  4953.7  252.74  4983.7  251.23  4991.2  249.69
  4996.3  249.69  4997.0  248.56  4999.8  248.06  5003.0  248.56  5004.2  248.56
  5014.8  250.83  5025.3  251.97  5035.8  254.31  5046.4  254.10  5056.9  256.59
  5067.5  256.78  5078.0  258.17  5088.5  258.42  5141.3  260.67  5151.8  260.69
#Mann=3,-1,0
  4793.7    0.15       0  4997.0    0.05       0  5003.0    0.15       0
Bank Sta=4997,5003
Exp/Cntr=0.3,0.1

Type RM Length L Ch R = 1,3481,419,419,419
BEGIN DESCRIPTION:
UNT 095 IN BOCR 7.0
END DESCRIPTION:
XS GIS Cut Line= 3
      3701099.61     10584910.19      3700999.61     10584860.19
      3700799.61     10584860.19
#Sta/Elev= 30
  4904.7  258.74  4907.5  258.74  4913.1  257.78  4927.1  257.01  4935.4  255.71
  4949.4  255.24  4957.8  251.56  4963.4  251.82  4971.8  250.16  4980.2  248.14
  4985.8  247.65  4994.1  247.79  4997.0  247.65  4999.8  247.15  5003.0  247.65
  5008.1  248.65  5013.7  248.91  5019.0  248.91  5026.5  248.20  5066.5  248.00
  5076.5  248.74  5086.5  250.60  5096.5  253.70  5106.5  253.96  5116.5  255.55
  5126.5  255.60  5136.5  256.45  5146.5  256.64  5156.5  257.30  5216.5  259.39
#Mann=3,-1,0
  4904.7    0.15       0  4997.0    0.05       0  5003.0    0.15       0
Bank Sta=4997,5003
Exp/Cntr=0.3,0.1

Type RM Length L Ch R = 1,3062,326,326,326
BEGIN DESCRIPTION:
UNT 095 IN BOCR 6.0
END DESCRIPTION:
XS GIS Cut Line= 3
      3701349.59     10584510.19      3701099.61     10584460.19
      3700899.60     10584410.19
#Sta/Elev= 30
  4723.5  266.82  4733.7  266.24  4743.9  265.00  4764.3  263.13  4774.5  262.70
  4784.7  261.60  4794.9  261.20  4805.1  259.87  4815.3  259.06  4845.9  257.34
  4856.1  256.43  4917.2  253.91  4927.4  252.84  4937.6  250.81  4947.8  250.90
  4968.2  249.13  4975.9  247.89  4997.0  247.59  4999.8  247.09  5003.0  247.59
  5042.9  247.87  5060.9  248.50  5078.9  251.23  5084.1  250.17  5091.8  253.04
  5102.1  253.87  5112.4  255.13  5133.1  256.74  5166.6  258.35  5184.6  258.77
#Mann=3,-1,0
  4723.5    0.15       0  4997.0    0.05       0  5003.0    0.15       0
Bank Sta=4997,5003
Exp/Cntr=0.3,0.1

Type RM Length L Ch R = 1,2736,32,32,32
BEGIN DESCRIPTION:
Mapping XS f1c064b3
END DESCRIPTION:
XS GIS Cut Line= 6
      3701434.27     10584397.50      3701262.37     10584189.14
      3701165.15     10584152.68      3701126.96     10584180.46
      3701083.55     10584176.99      3700907.49     10584054.44
#Sta/Elev= 30
  4648.6  266.73  4707.2  263.38  4714.6  262.76  4720.8  260.60  4729.3  260.08
  4735.5  260.45  4744.0  259.53  4750.2  260.55  4771.0  258.00  4779.5  258.09
  4800.4  256.05  4829.7  255.83  4843.3  254.45  4859.3  254.22  4878.9  250.67
  4885.4  248.57  4893.2  247.78  4997.0  247.59  4999.8  247.09  5003.0  247.59
  5042.6  248.77  5048.7  247.98  5063.4  249.30  5090.0  249.63  5110.1  253.04
  5115.7  253.00  5123.2  254.32  5173.8  255.19  5245.4  258.39  5330.7  260.87
#Mann=3,-1,0
  4648.6    0.15       0  4997.0    0.05       0  5003.0    0.15       0
Bank Sta=4997,5003
Exp/Cntr=0.3,0.1

Type RM Length L Ch R = 1,2704,126,126,126
BEGIN DESCRIPTION:
Mapping XS 33de3bd3
END DESCRIPTION:
XS GIS Cut Line= 6
      3701460.29     10584399.21      3701345.71     10584211.71
      3701286.68     10584161.36      3701158.21     10584114.49
      3701087.03     10584154.42      3700915.15     10584029.42
#Sta/Elev= 30
  4601.3  267.93  4709.8  262.16  4740.7  259.47  4746.5  257.42  4762.0  256.36
  4821.0  255.02  4841.1  249.70  4847.6  246.41  4855.3  245.87  4868.5  247.93
  4876.2  252.43  4940.8  253.78  4958.1  252.70  4967.5  253.71  4982.8  253.50
  4990.9  251.18  4996.1  253.53  4997.0  245.87  4999.8  245.37  5003.0  245.87
  5003.5  253.20  5031.3  252.68  5034.6  253.46  5038.7  252.68  5054.7  253.61
  5060.4  252.96  5139.3  253.70  5147.8  255.08  5239.7  258.83  5330.1  261.26
#Mann=3,-1,0
  4601.3    0.15       0  4997.0    0.05       0  5003.0    0.15       0
Bank Sta=4997,5003
Exp/Cntr=0.3,0.1

Type RM Length L Ch R = 1,2578,166,166,166
BEGIN DESCRIPTION:
UNT 095 IN BOCR 5.0
END DESCRIPTION:
XS GIS Cut Line= 2
      3701485.47     10584403.28      3701100.07     10583781.78
#Sta/Elev= 30
  4537.9  268.58  4595.5  267.16  4718.0  256.96  4753.7  255.68  4763.2  252.61
  4769.1  255.26  4776.9  255.14  4784.5  249.82  4812.2  245.60  4827.0  247.38
  4835.7  245.44  4842.4  247.55  4848.2  245.34  4863.6  247.41  4884.9  245.26
  4894.4  247.68  4900.2  245.96  4915.6  248.72  4921.5  245.83  4929.8  247.29
  4942.7  243.84  4973.5  245.93  4997.0  243.62  4999.8  243.12  5003.0  243.62
  5031.4  247.12  5052.6  253.87  5104.6  258.55  5183.8  262.32  5269.2  261.35
#Mann=3,-1,0
  4537.9    0.15       0  4997.0    0.05       0  5003.0    0.15       0
Bank Sta=4997,5003
Exp/Cntr=0.3,0.1

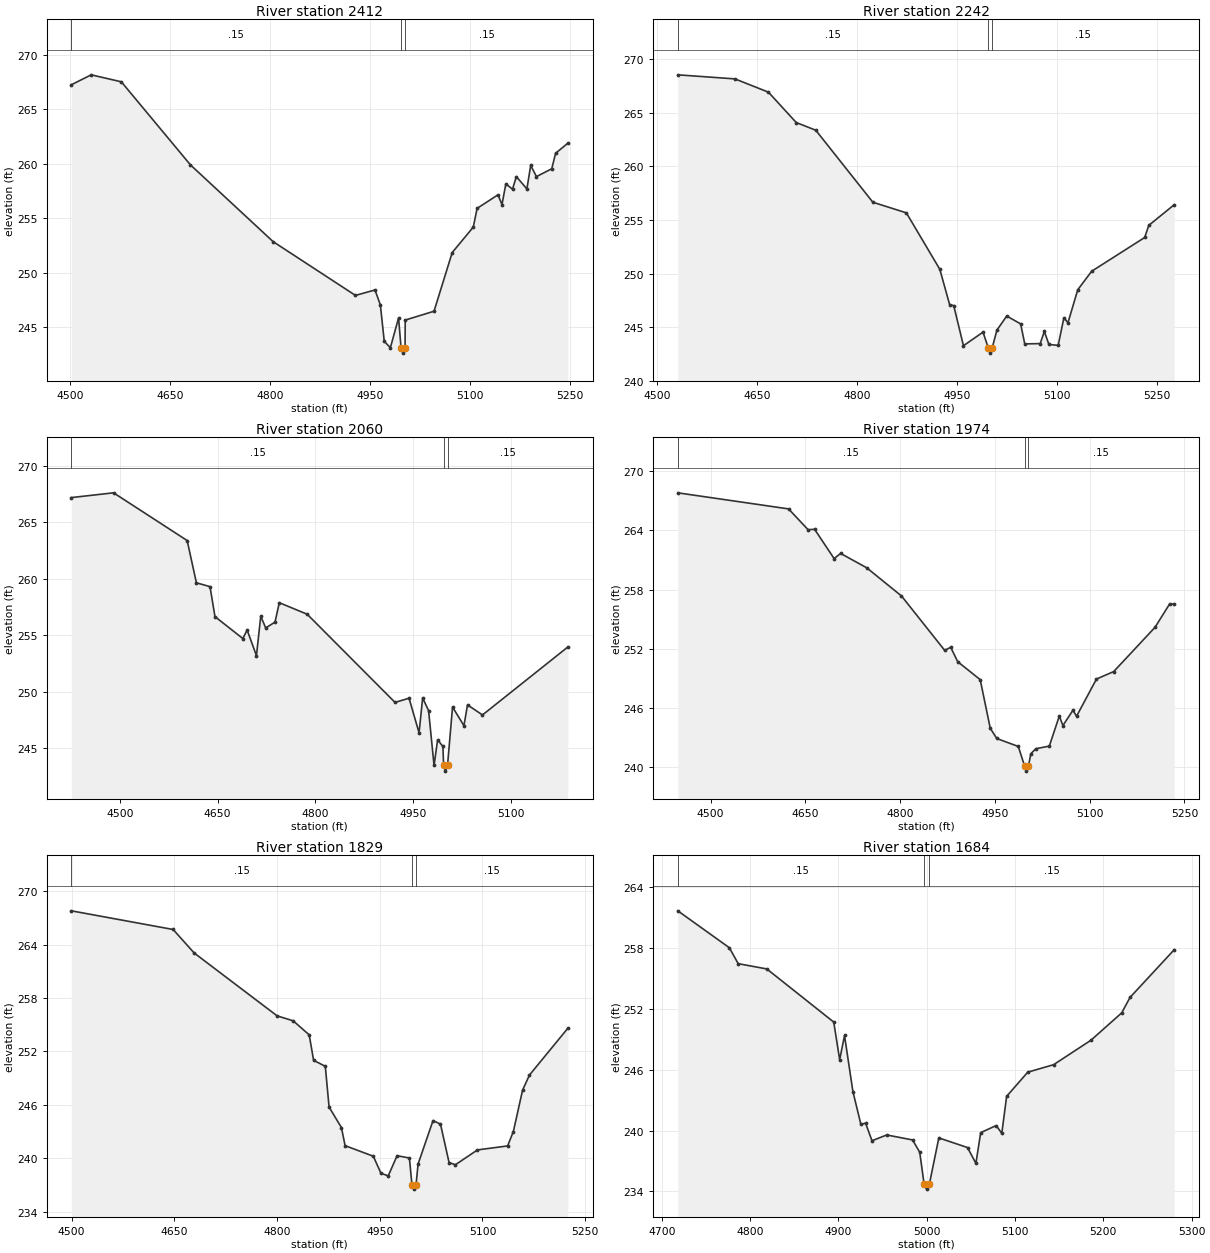
Type RM Length L Ch R = 1,2412,170,170,170
BEGIN DESCRIPTION:
UNT 095 IN BOCR 4.0
END DESCRIPTION:
XS GIS Cut Line= 2
      3701607.03     10584325.20      3701235.48     10583679.34
#Sta/Elev= 30
  4502.2  267.24  4532.0  268.15  4577.2  267.51  4681.0  259.89  4805.0  252.86
  4928.6  247.93  4957.9  248.43  4966.0  247.05  4971.8  243.72  4981.0  243.14
  4993.3  245.87  4997.0  243.14  4999.8  242.64  5003.0  243.14  5003.3  245.67
  5046.5  246.48  5073.8  251.86  5105.4  254.19  5111.2  255.91  5142.5  257.15
  5148.5  256.26  5154.3  258.15  5164.3  257.67  5170.1  258.82  5185.9  257.69
  5191.6  259.85  5200.2  258.82  5223.2  259.54  5229.0  260.96  5247.3  261.88
#Mann=3,-1,0
  4502.2    0.15       0  4997.0    0.05       0  5003.0    0.15       0
Bank Sta=4997,5003
Exp/Cntr=0.3,0.1

Type RM Length L Ch R = 1,2242,182,182,182
BEGIN DESCRIPTION:
Mapping XS e5a7eb80
END DESCRIPTION:
XS GIS Cut Line= 2
      3701777.13     10584241.81      3701339.65     10583637.67
#Sta/Elev= 30
  4530.6  268.55  4616.5  268.17  4666.8  266.93  4708.5  264.10  4737.9  263.38
  4823.7  256.66  4874.0  255.67  4924.3  250.40  4939.0  247.11  4945.2  247.01
  4959.8  243.27  4989.2  244.54  4997.0  243.08  4999.8  242.58  5003.0  243.08
  5010.1  244.73  5024.8  246.04  5045.7  245.31  5051.9  243.44  5075.1  243.47
  5081.3  244.60  5088.2  243.39  5102.1  243.30  5110.7  245.88  5116.8  245.41
  5131.5  248.49  5152.4  250.22  5232.1  253.37  5238.2  254.50  5276.5  256.43
#Mann=3,-1,0
  4530.6    0.15       0  4997.0    0.05       0  5003.0    0.15       0
Bank Sta=4997,5003
Exp/Cntr=0.3,0.1

Type RM Length L Ch R = 1,2060,86,86,86
BEGIN DESCRIPTION:
Mapping XS 1218e801
END DESCRIPTION:
XS GIS Cut Line= 3
      3701979.60     10584070.96      3701586.82     10583732.44
      3701365.42     10583630.42
#Sta/Elev= 30
  4425.4  267.19  4490.2  267.61  4603.2  263.39  4617.4  259.65  4638.3  259.31
  4645.9  256.66  4688.7  254.72  4695.3  255.47  4709.6  253.21  4716.2  256.69
  4723.8  255.66  4738.1  256.17  4744.7  257.89  4787.5  256.87  4922.4  249.07
  4943.9  249.44  4959.3  246.38  4964.8  249.46  4973.9  248.35  4982.3  243.49
  4987.8  245.76  4995.9  245.17  4997.0  243.49  4999.8  242.99  5003.0  243.49
  5010.7  248.66  5028.2  247.01  5033.7  248.85  5056.7  247.96  5187.7  253.97
#Mann=3,-1,0
  4425.4    0.15       0  4997.0    0.05       0  5003.0    0.15       0
Bank Sta=4997,5003
Exp/Cntr=0.3,0.1

Type RM Length L Ch R = 1,1974,145,145,145
BEGIN DESCRIPTION:
Mapping XS 0ecc4db0
END DESCRIPTION:
XS GIS Cut Line= 3
      3702109.83     10583769.33      3701588.99     10583641.29
      3701373.29     10583516.19
#Sta/Elev= 30
  4448.1  267.82  4623.4  266.19  4654.3  264.08  4664.6  264.12  4695.5  261.15
  4705.8  261.67  4747.0  260.22  4802.1  257.36  4870.5  251.84  4880.0  252.15
  4891.1  250.69  4926.7  248.87  4942.6  243.94  4952.9  242.90  4987.0  242.09
  4997.0  240.09  4999.8  239.59  5003.0  240.09  5006.8  241.35  5014.6  241.86
  5036.1  242.13  5051.9  245.18  5057.6  244.21  5073.4  245.76  5079.2  245.16
  5110.7  248.93  5138.0  249.69  5203.4  254.18  5226.5  256.55  5233.8  256.52
#Mann=3,-1,0
  4448.1    0.15       0  4997.0    0.05       0  5003.0    0.15       0
Bank Sta=4997,5003
Exp/Cntr=0.3,0.1

Type RM Length L Ch R = 1,1829,145,145,145
BEGIN DESCRIPTION:
Mapping XS c4cfea6f
END DESCRIPTION:
XS GIS Cut Line= 2
      3702114.15     10583712.90      3701448.98     10583424.74
#Sta/Elev= 30
  4499.7  267.82  4648.3  265.72  4679.0  263.08  4800.1  256.01  4823.6  255.45
  4847.0  253.87  4853.4  251.01  4870.5  250.33  4876.0  245.75  4894.0  243.45
  4899.4  241.41  4940.6  240.22  4951.8  238.30  4962.4  238.01  4975.3  240.28
  4993.3  240.02  4997.0  237.02  4999.8  236.52  5003.0  237.02  5006.0  239.35
  5027.8  244.23  5038.7  243.83  5051.2  239.51  5060.4  239.26  5092.7  240.93
  5136.7  241.38  5145.1  243.00  5158.5  247.64  5168.6  249.35  5224.6  254.61
#Mann=3,-1,0
  4499.7    0.15       0  4997.0    0.05       0  5003.0    0.15       0
Bank Sta=4997,5003
Exp/Cntr=0.3,0.1

Type RM Length L Ch R = 1,1684,502,502,502
BEGIN DESCRIPTION:
UNT 095 IN BOCR 3.0
END DESCRIPTION:
XS GIS Cut Line= 2
      3702002.84     10583505.73      3701483.27     10583290.97
#Sta/Elev= 30
  4718.1  261.67  4776.5  258.03  4786.5  256.46  4818.9  255.94  4894.7  250.70
  4901.4  246.99  4906.9  249.38  4916.4  243.85  4925.4  240.63  4930.8  240.73
  4938.0  239.00  4954.7  239.57  4984.0  239.08  4992.1  237.86  4997.0  234.73
  4999.8  234.23  5003.0  234.73  5013.7  239.28  5046.2  238.33  5055.7  236.77
  5061.1  239.80  5078.7  240.50  5085.0  239.73  5090.5  243.38  5114.4  245.76
  5143.7  246.50  5186.1  248.92  5220.8  251.61  5230.2  253.13  5280.3  257.84
#Mann=3,-1,0
  4718.1    0.15       0  4997.0    0.05       0  5003.0    0.15       0
Bank Sta=4997,5003
Exp/Cntr=0.3,0.1

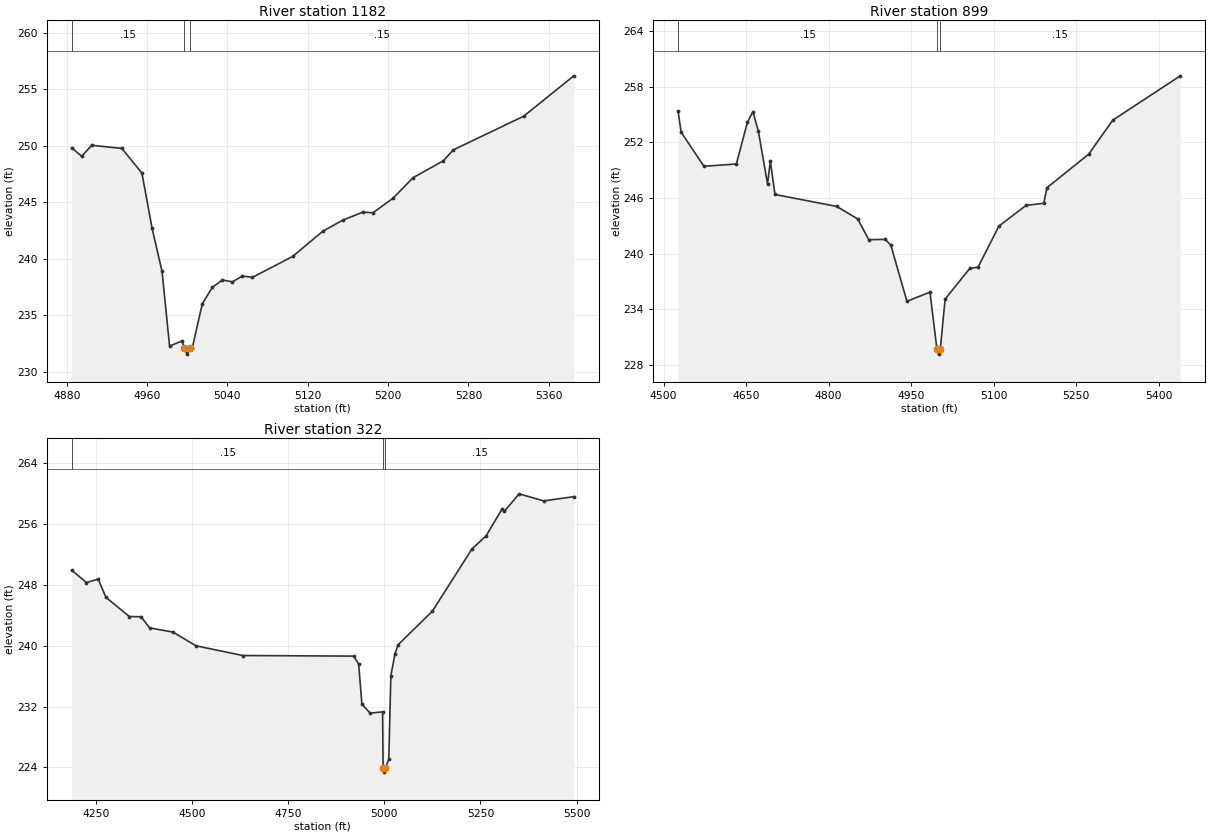
Type RM Length L Ch R = 1,1182,283,283,283
BEGIN DESCRIPTION:
UNT 095 IN BOCR 2.0
END DESCRIPTION:
XS GIS Cut Line= 3
      3702049.64     10583010.19      3701949.61     10583010.19
      3701549.64     10583010.19
#Sta/Elev= 30
  4884.9  249.83  4894.9  249.07  4904.9  250.05  4934.9  249.77  4954.9  247.58
  4964.9  242.73  4974.9  238.88  4982.4  232.26  4994.9  232.73  4997.0  232.05
  4999.8  231.55  5003.0  232.05  5004.9  232.05  5014.9  235.99  5024.9  237.46
  5034.9  238.12  5044.9  237.95  5054.9  238.47  5064.9  238.35  5104.9  240.20
  5134.9  242.43  5154.9  243.42  5174.9  244.13  5184.9  244.07  5204.9  245.36
  5224.9  247.18  5254.9  248.67  5264.9  249.64  5334.9  252.62  5384.9  256.20
#Mann=3,-1,0
  4884.9    0.15       0  4997.0    0.05       0  5003.0    0.15       0
Bank Sta=4997,5003
Exp/Cntr=0.3,0.1

Type RM Length L Ch R = 1,899,577,577,577
BEGIN DESCRIPTION:
Mapping XS 7a08d8ac
END DESCRIPTION:
XS GIS Cut Line= 3
      3702305.14     10582701.62      3701886.30     10582736.35
      3701453.48     10582972.23
#Sta/Elev= 30
  4526.3  255.32  4531.8  253.08  4573.2  249.41  4632.2  249.65  4652.3  254.15
  4662.3  255.29  4672.3  253.16  4688.9  247.51  4694.0  249.98  4702.4  246.37
  4814.7  245.08  4852.9  243.73  4873.0  241.50  4903.1  241.53  4913.1  240.91
  4942.4  234.86  4984.3  235.85  4997.0  229.67  4999.8  229.17  5003.0  229.67
  5011.8  235.10  5056.7  238.40  5071.7  238.54  5109.6  242.96  5159.2  245.20
  5191.3  245.42  5197.0  247.10  5272.9  250.71  5316.6  254.37  5439.5  259.15
#Mann=3,-1,0
  4526.3    0.15       0  4997.0    0.05       0  5003.0    0.15       0
Bank Sta=4997,5003
Exp/Cntr=0.3,0.1

Type RM Length L Ch R = 1,322,0,0,0
BEGIN DESCRIPTION:
UNT 095 IN BOCR 1.0
END DESCRIPTION:
XS GIS Cut Line= 3
      3702287.60     10582568.24      3701586.18     10582450.17
      3701367.44     10583002.23
#Sta/Elev= 30
  4187.5  249.91  4226.0  248.28  4256.4  248.74  4276.7  246.34  4337.6  243.82
  4368.0  243.79  4390.0  242.33  4450.5  241.78  4511.1  239.97  4632.2  238.70
  4920.3  238.62  4933.3  237.61  4941.8  232.33  4963.3  231.13  4995.6  231.30
  4997.0  223.88  4999.8  223.38  5003.0  223.88  5011.7  225.08  5017.1  236.05
  5027.9  238.96  5036.0  240.12  5125.1  244.53  5227.8  252.70  5264.5  254.41
  5306.2  257.96  5311.6  257.63  5350.6  259.94  5414.3  259.01  5492.6  259.57
#Mann=3,-1,0
  4187.5    0.15       0  4997.0    0.05       0  5003.0    0.15       0
Bank Sta=4997,5003
Exp/Cntr=0.3,0.1

Chan Stop Cuts=-1