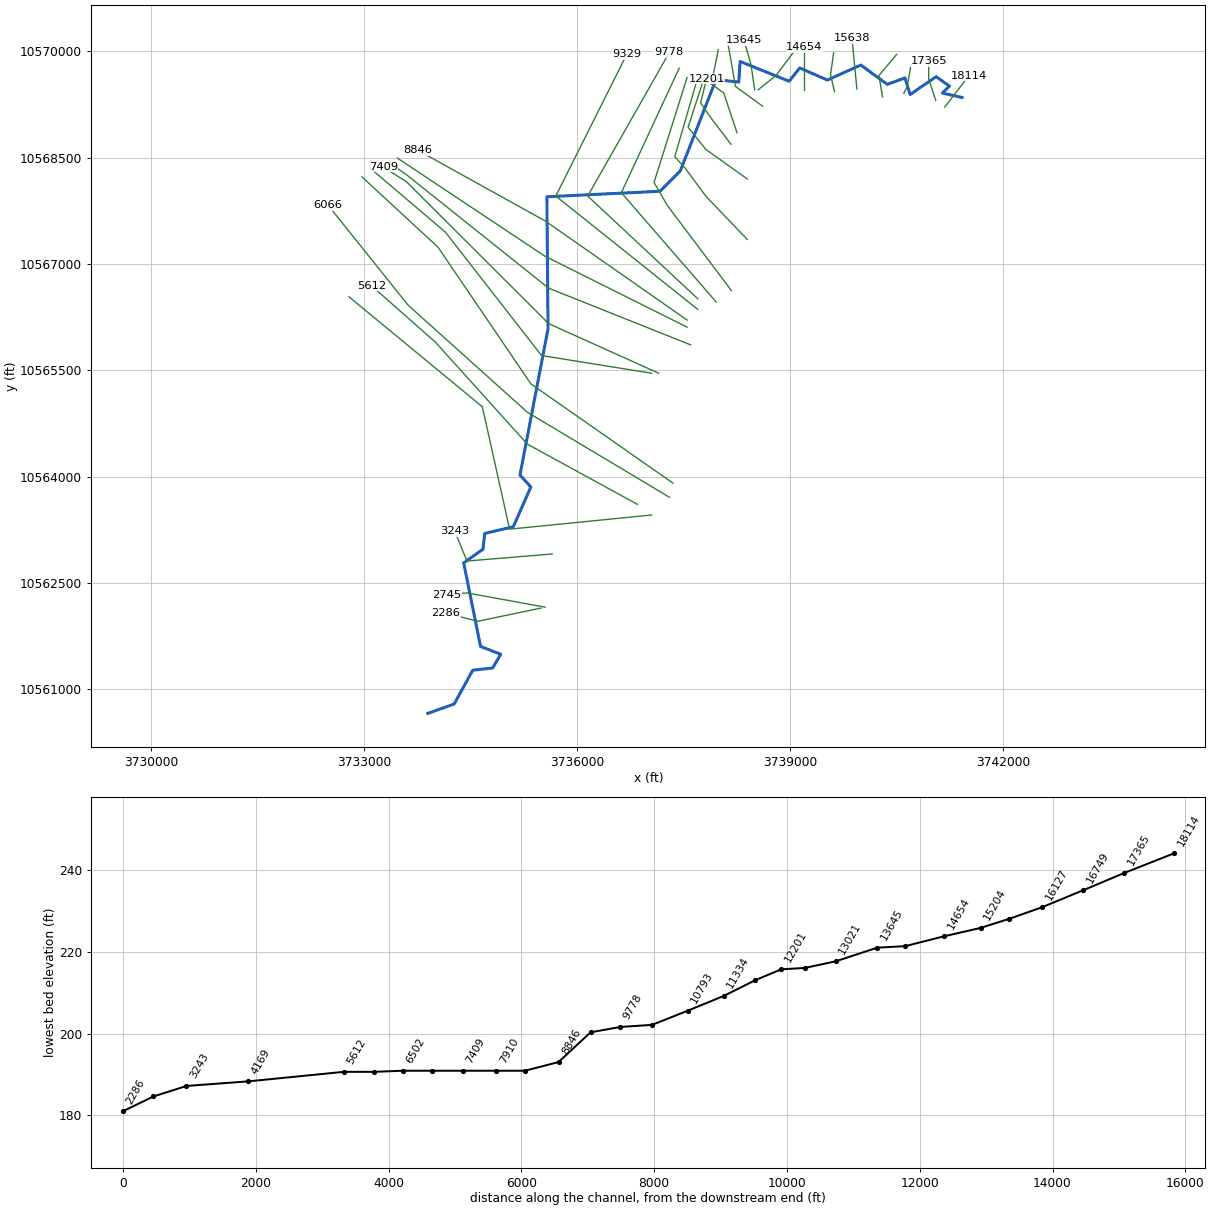
--- UNT 097 IN BOCR.prj (project) ---

Proj Title=UNT 097 IN BOCR Base Level Engineering
Current Plan=p01
Default Exp/Contr=0.3,0.1
English Units
Geom File=g01
Flow File=f01
Plan File=p01
BEGIN DESCRIPTION:
UNT 097 IN BOCR
END DESCRIPTION:

--- UNT 097 IN BOCR.p01 (plan) ---

Plan Title=Multiple Run
Short Identifier=Multiple
Geom File=g01
Flow File=f01
Subcritical Flow
K Sum by GR= 0
Std Step Tol= 0.01
Critical Tol= 0.01
Num of Std Step Trials= 20
Max Error Tol= 0.3
Flow Tol Ratio= 0.001
Split Flow NTrial= 30
Split Flow Tol= 0.02
Split Flow Ratio= 0.02
Log Output Level= 0
Friction Slope Method= 1
Unsteady Friction Slope Method= 2
Unsteady Bridges Friction Slope Method= 1
Parabolic Critical Depth
Global Vel Dist=  1 , 1 , 1
Global Log Level= 0
CheckData=True
Encroach Param= -1, 0, 0, 0
BEGIN DESCRIPTION:
Multiple Run
END DESCRIPTION:

--- UNT 097 IN BOCR.f01 (steady flow) ---

Flow Title=Multiple
Number of Profiles=7
Profile Names=10-year,25-year,50-year,1pct_min,100-year,1pct_plu,500-year
River Rch & RM= UNT 097 IN BOCR,Reach-1,18114
     661     913    1126    1022    1382    1869    2090
River Rch & RM= UNT 097 IN BOCR,Reach-1,14070
     817    1133    1401    1272    1720    2327    2606
River Rch & RM= UNT 097 IN BOCR,Reach-1,4169
    1325    1883    2366    2179    2947    3986    4595
Boundary for River Rch & Prof#=UNT 097 IN BOCR,Reach-1,1
Up Type=0
Dn Type=3
Dn Slope=0.005
Boundary for River Rch & Prof#=UNT 097 IN BOCR,Reach-1,2
Up Type=0
Dn Type=3
Dn Slope=0.005
Boundary for River Rch & Prof#=UNT 097 IN BOCR,Reach-1,3
Up Type=0
Dn Type=3
Dn Slope=0.005
Boundary for River Rch & Prof#=UNT 097 IN BOCR,Reach-1,4
Up Type=0
Dn Type=3
Dn Slope=0.005
Boundary for River Rch & Prof#=UNT 097 IN BOCR,Reach-1,5
Up Type=0
Dn Type=3
Dn Slope=0.005
Boundary for River Rch & Prof#=UNT 097 IN BOCR,Reach-1,6
Up Type=0
Dn Type=3
Dn Slope=0.005
Boundary for River Rch & Prof#=UNT 097 IN BOCR,Reach-1,7
Up Type=0
Dn Type=3
Dn Slope=0.005

--- UNT 097 IN BOCR.g01 (geometry) ---

Geom Title=Existing Conditions

River Reach=UNT 097 IN BOCR,Reach-1
Reach XY= 30
      3741420.25     10569351.00      3741141.00     10569414.00
      3741243.25     10569512.00      3741054.00     10569644.00
      3740687.75     10569392.00      3740617.25     10569627.00
      3740367.25     10569536.00      3739993.75     10569809.00
      3739522.75     10569597.00      3739134.75     10569768.00
      3738985.00     10569580.00      3738295.25     10569859.00
      3738276.25     10569569.00      3737955.00     10569603.00
      3737453.75     10568317.00      3737165.75     10568028.00
      3735574.50     10567950.00      3735591.00     10566088.00
      3735196.00     10564025.00      3735348.75     10563855.00
      3735101.75     10563294.00      3734699.25     10563200.00
      3734674.75     10562977.00      3734403.50     10562785.00
      3734640.75     10561605.00      3734924.75     10561495.00
      3734812.25     10561302.00      3734531.00     10561270.00
      3734269.25     10560793.00      3733899.50     10560661.00

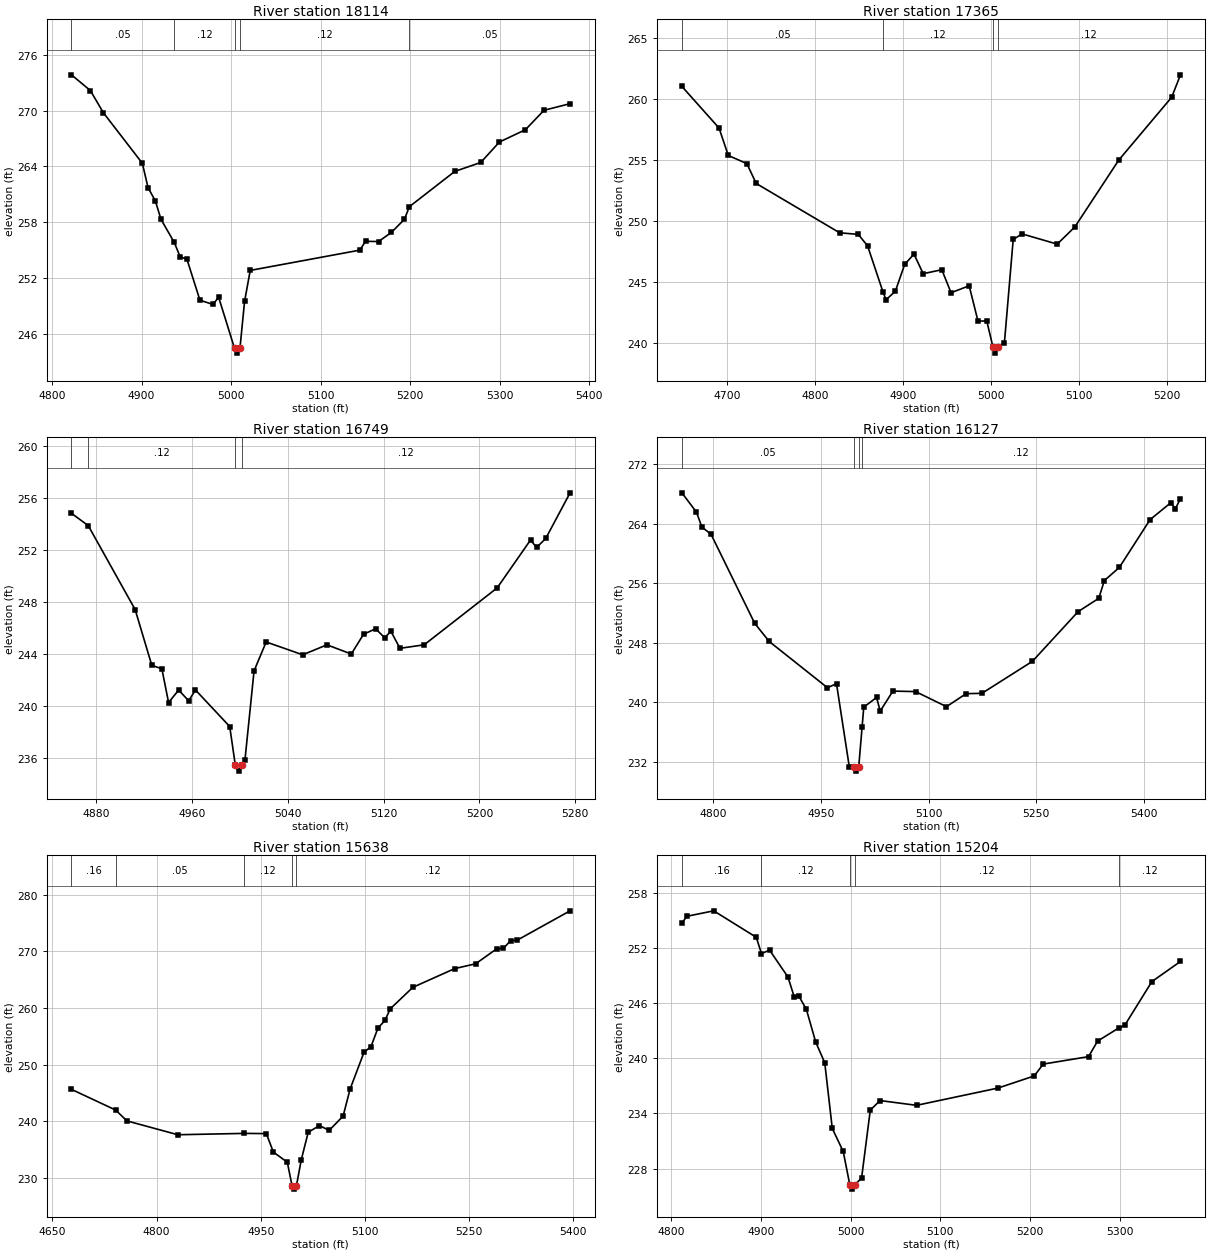
Type RM Length L Ch R = 1,18114,749,749,749
BEGIN DESCRIPTION:
UNT 097 IN BOCR 30.0
END DESCRIPTION:
XS GIS Cut Line= 2
      3741175.35     10569213.82      3741513.95     10569656.09
#Sta/Elev= 30
  4821.7  273.84  4842.8  272.15  4857.3  269.77  4900.9  264.33  4907.2  261.72
  4915.4  260.29  4921.7  258.31  4936.5  255.83  4943.1  254.29  4950.7  254.02
  4965.2  249.62  4979.8  249.16  4986.1  249.94  5003.9  244.43  5006.6  243.93
  5009.9  244.43  5015.1  249.51  5021.4  252.82  5143.9  255.00  5150.2  255.95
  5164.7  255.92  5179.2  256.91  5193.7  258.32  5199.2  259.67  5249.9  263.46
  5278.9  264.42  5299.8  266.62  5328.8  267.94  5349.6  270.03  5378.7  270.74
#Mann=5,-1,0
  4821.7    0.05       0  4936.5    0.12       0  5003.9    0.07       0
  5009.9    0.12       0  5199.2    0.05       0
Bank Sta=5003.9,5009.9
Exp/Cntr=0.3,0.1

Type RM Length L Ch R = 1,17365,616,616,616
BEGIN DESCRIPTION:
UNT 097 IN BOCR 29.0
END DESCRIPTION:
XS GIS Cut Line= 3
      3741049.62     10569310.15      3740949.61     10569610.19
      3740949.61     10569860.22
#Sta/Elev= 30
  4648.6  261.05  4690.8  257.63  4701.3  255.38  4722.4  254.71  4733.0  253.08
  4827.8  249.03  4848.9  248.90  4859.5  247.96  4877.1  244.15  4880.5  243.53
  4891.1  244.24  4901.6  246.43  4912.2  247.28  4922.7  245.67  4943.8  246.00
  4954.3  244.11  4974.9  244.68  4984.9  241.78  4994.9  241.79  5001.9  239.65
  5004.6  239.15  5007.9  239.65  5014.9  239.98  5024.9  248.48  5034.9  248.94
  5074.9  248.10  5094.9  249.51  5144.9  255.01  5204.9  260.16  5214.9  262.00
#Mann=4,-1,0
  4648.6    0.05       0  4877.1    0.12       0  5001.9    0.07       0
  5007.9    0.12       0
Bank Sta=5001.9,5007.9
Exp/Cntr=0.3,0.1

Type RM Length L Ch R = 1,16749,622,622,622
BEGIN DESCRIPTION:
UNT 097 IN BOCR 28.0
END DESCRIPTION:
XS GIS Cut Line= 3
      3740599.63     10569410.23      3740649.61     10569510.19
      3740699.61     10569810.19
#Sta/Elev= 30
  4859.7  254.83  4873.7  253.88  4912.8  247.41  4926.7  243.11  4935.1  242.84
  4940.7  240.24  4949.1  241.20  4957.5  240.37  4963.1  241.21  4991.7  238.39
  4996.3  235.45  4999.1  234.95  5002.3  235.45  5004.4  235.80  5012.0  242.68
  5022.1  244.91  5052.6  243.92  5072.8  244.69  5093.1  243.98  5103.3  245.50
  5113.4  245.93  5121.0  245.23  5126.1  245.74  5133.7  244.42  5153.9  244.69
  5214.8  249.08  5242.6  252.77  5247.7  252.20  5255.3  252.89  5275.6  256.41
#Mann=4,-1,0
  4859.7    0.05       0  4873.7    0.12       0  4996.3    0.07       0
  5002.3    0.12       0
Bank Sta=4996.3,5002.3
Exp/Cntr=0.3,0.1

Type RM Length L Ch R = 1,16127,489,489,489
BEGIN DESCRIPTION:
UNT 097 IN BOCR 27.0
END DESCRIPTION:
XS GIS Cut Line= 3
      3740299.61     10569360.20      3740249.61     10569660.19
      3740499.58     10569960.16
#Sta/Elev= 30
  4756.2  268.13  4776.5  265.54  4784.1  263.53  4796.7  262.59  4857.6  250.63
  4877.8  248.19  4959.0  241.98  4971.6  242.52  4989.4  231.38  4996.5  231.29
  4999.3  230.79  5002.5  231.29  5007.3  236.76  5009.6  239.38  5027.4  240.67
  5032.5  238.85  5050.2  241.53  5081.8  241.46  5124.8  239.44  5152.1  241.18
  5174.2  241.23  5244.5  245.52  5308.3  252.20  5336.9  253.97  5344.8  256.36
  5365.6  258.12  5408.5  264.54  5437.2  266.79  5443.7  266.01  5450.8  267.35
#Mann=4,-1,0
  4756.2    0.05       0  4996.5    0.03       0  5002.5    0.05       0
  5007.3    0.12       0
Bank Sta=4996.5,5002.5
Exp/Cntr=0.3,0.1

Type RM Length L Ch R = 1,15638,434,434,434
BEGIN DESCRIPTION:
UNT 097 IN BOCR 26.0
END DESCRIPTION:
XS GIS Cut Line= 2
      3739939.23     10569470.76      3739869.83     10570185.60
#Sta/Elev= 30
  4677.4  245.63  4741.1  241.97  4757.2  240.06  4830.6  237.61  4926.6  237.85
  4958.1  237.81  4968.2  234.55  4988.3  232.75  4995.3  228.50  4998.1  228.00
  5001.3  228.50  5008.4  233.17  5018.4  238.05  5034.6  239.23  5048.6  238.38
  5068.7  240.91  5078.7  245.68  5098.8  252.18  5108.8  253.18  5118.9  256.47
  5128.9  257.80  5136.6  259.86  5169.1  263.66  5229.4  266.97  5259.6  267.82
  5289.7  270.45  5299.7  270.56  5309.8  271.89  5319.8  272.02  5395.6  277.18
#Mann=5,-1,0
  4677.4    0.16       0  4741.1    0.05       0  4926.6    0.12       0
  4995.3    0.07       0  5001.3    0.12       0
Bank Sta=4995.3,5001.3
Exp/Cntr=0.3,0.1

Type RM Length L Ch R = 1,15204,550,550,550
BEGIN DESCRIPTION:
UNT 097 IN BOCR 25.0
END DESCRIPTION:
XS GIS Cut Line= 3
      3739623.78     10569434.99      3739568.23     10569671.10
      3739611.62     10569981.82
#Sta/Elev= 30
  4811.6  254.68  4816.9  255.45  4847.1  256.05  4894.6  253.17  4900.4  251.39
  4909.4  251.78  4929.9  248.85  4937.0  246.67  4942.2  246.75  4950.5  245.32
  4960.8  241.80  4971.0  239.51  4979.4  232.36  4991.6  229.86  4998.9  226.26
  5001.6  225.76  5004.9  226.26  5012.1  226.97  5021.8  234.36  5032.7  235.40
  5073.4  234.88  5164.3  236.76  5204.7  238.08  5214.8  239.37  5265.3  240.18
  5275.4  241.87  5299.2  243.31  5305.7  243.59  5336.0  248.35  5367.9  250.54
#Mann=5,-1,0
  4811.6    0.16       0  4900.4    0.12       0  4998.9    0.07       0
  5004.9    0.12       0  5299.2    0.12       0
Bank Sta=4998.9,5004.9
Exp/Cntr=0.3,0.1

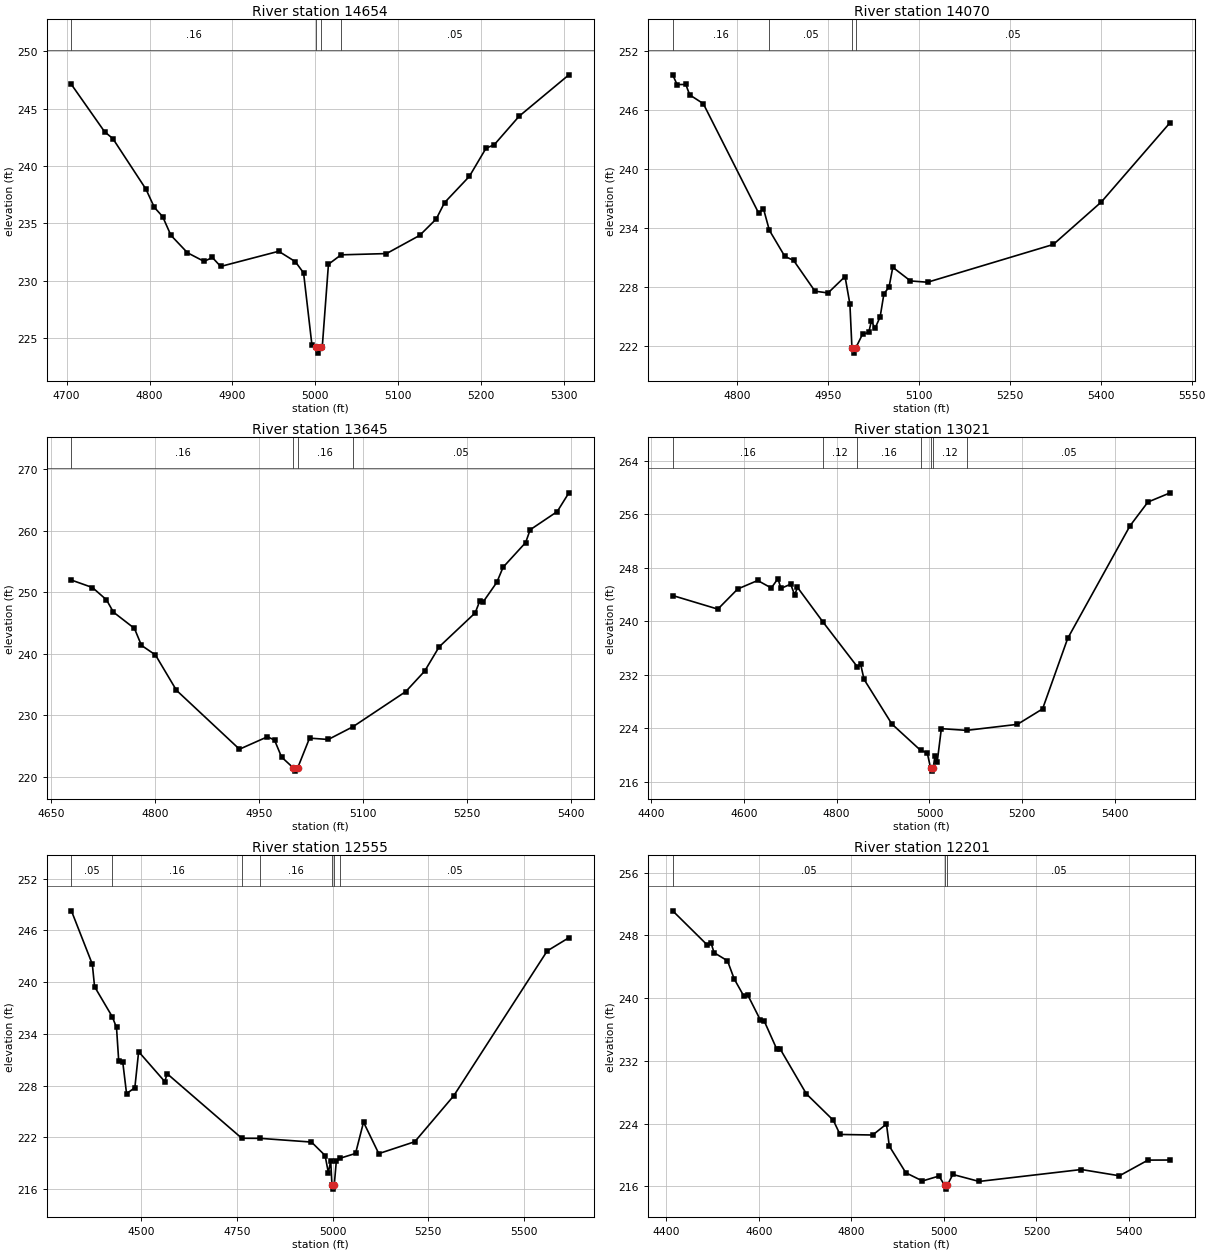
Type RM Length L Ch R = 1,14654,584,584,584
BEGIN DESCRIPTION:
UNT 097 IN BOCR 24.0
END DESCRIPTION:
XS GIS Cut Line= 3
      3739199.61     10569460.21      3739199.61     10569760.19
      3739199.61     10570060.21
#Sta/Elev= 30
  4705.8  247.09  4745.8  242.98  4755.8  242.38  4795.8  237.97  4805.8  236.40
  4815.8  235.60  4825.8  233.97  4845.8  232.45  4865.8  231.70  4875.8  232.04
  4885.8  231.26  4955.8  232.58  4975.8  231.68  4985.8  230.70  4995.8  224.47
  5000.3  224.22  5003.0  223.72  5006.3  224.22  5008.3  224.22  5015.8  231.45
  5031.0  232.27  5085.8  232.38  5125.8  233.96  5145.8  235.39  5155.8  236.81
  5185.8  239.10  5205.8  241.54  5215.8  241.85  5245.8  244.33  5305.8  247.93
#Mann=4,-1,0
  4705.8    0.16       0  5000.3    0.07       0  5006.3    0.16       0
  5031.0    0.05       0
Bank Sta=5000.3,5006.3
Exp/Cntr=0.3,0.1

Type RM Length L Ch R = 1,14070,425,425,425
BEGIN DESCRIPTION:
UNT 097 IN BOCR 23.0
END DESCRIPTION:
XS GIS Cut Line= 3
      3738549.64     10569460.22      3738799.61     10569660.19
      3739099.60     10570060.18
#Sta/Elev= 30
  4694.5  249.62  4701.7  248.63  4716.1  248.64  4722.5  247.58  4744.9  246.69
  4836.1  235.57  4844.1  236.01  4853.8  233.82  4879.3  231.16  4893.8  230.75
  4929.0  227.62  4950.6  227.44  4978.6  229.11  4986.6  226.31  4990.0  221.82
  4992.8  221.32  4996.0  221.82  5007.4  223.24  5017.7  223.42  5021.9  224.57
  5028.2  223.86  5036.5  225.02  5042.7  227.36  5051.1  228.03  5057.3  230.05
  5086.5  228.66  5114.6  228.53  5321.9  232.37  5401.1  236.69  5514.6  244.77
#Mann=4,-1,0
  4694.5    0.16       0  4853.8    0.05       0  4990.0    0.03       0
  4996.0    0.05       0
Bank Sta=4990,4996
Exp/Cntr=0.3,0.1

Type RM Length L Ch R = 1,13645,624,624,624
BEGIN DESCRIPTION:
UNT 097 IN BOCR 22.0
END DESCRIPTION:
XS GIS Cut Line= 3
      3738499.61     10569460.18      3738449.61     10569810.19
      3738349.60     10570160.22
#Sta/Elev= 30
  4679.1  251.96  4709.4  250.75  4729.6  248.76  4739.7  246.75  4770.0  244.11
  4780.1  241.36  4800.3  239.80  4830.6  234.06  4921.5  224.49  4961.9  226.51
  4972.1  225.97  4982.2  223.22  4999.4  221.43  5002.1  220.93  5005.4  221.43
  5022.6  226.29  5049.6  226.07  5085.2  228.14  5161.4  233.85  5188.7  237.18
  5209.5  241.11  5261.5  246.63  5268.0  248.52  5273.2  248.44  5292.7  251.59
  5301.8  254.05  5334.3  258.05  5340.8  260.13  5379.8  263.08  5396.7  266.13
#Mann=4,-1,0
  4679.1    0.16       0  4999.4    0.07       0  5005.4    0.16       0
  5085.2    0.05       0
Bank Sta=4999.4,5005.4
Exp/Cntr=0.3,0.1

Type RM Length L Ch R = 1,13021,466,466,466
BEGIN DESCRIPTION:
UNT 097 IN BOCR 21.0
END DESCRIPTION:
XS GIS Cut Line= 3
      3738612.80     10569227.73      3738230.90     10569505.48
      3738126.79     10570095.44
#Sta/Elev= 30
  4447.1  243.85  4544.3  241.82  4587.1  244.83  4630.1  246.10  4659.4  244.98
  4673.6  246.36  4680.3  244.92  4701.2  245.55  4709.7  243.93  4715.8  245.07
  4771.3  239.84  4844.5  233.22  4851.9  233.55  4859.1  231.33  4919.1  224.65
  4981.0  220.71  4995.2  220.35  5002.3  218.11  5005.1  217.61  5008.3  218.11
  5011.7  219.87  5016.8  219.03  5025.6  223.96  5079.9  223.70  5189.4  224.60
  5243.6  226.91  5297.7  237.45  5431.8  254.26  5470.4  257.82  5518.4  259.20
#Mann=7,-1,0
  4447.1    0.16       0  4771.3    0.12       0  4844.5    0.16       0
  4981.0    0.12       0  5002.3    0.07       0  5008.3    0.12       0
  5079.9    0.05       0
Bank Sta=5002.3,5008.3
Exp/Cntr=0.3,0.1

Type RM Length L Ch R = 1,12555,354,354,354
BEGIN DESCRIPTION:
UNT 097 IN BOCR 20.0
END DESCRIPTION:
XS GIS Cut Line= 4
      3738251.72     10568852.72      3738064.23     10569415.21
      3737890.62     10569540.21      3737987.73     10570025.75
#Sta/Elev= 30
  4316.6  248.28  4371.3  242.09  4377.2  239.48  4423.4  236.00  4434.6  234.75
  4440.4  230.86  4451.0  230.72  4460.9  227.08  4482.6  227.75  4492.5  231.94
  4561.1  228.46  4566.9  229.39  4762.6  221.89  4811.1  221.88  4944.9  221.45
  4980.5  219.89  4989.0  217.91  4995.2  219.24  4998.5  216.49  5001.2  215.99
  5004.5  216.49  5009.9  219.23  5019.6  219.57  5060.2  220.13  5081.1  223.76
  5121.0  220.11  5215.2  221.49  5317.2  226.82  5561.9  243.63  5618.6  245.16
#Mann=7,-1,0
  4316.6    0.05       0  4423.4    0.16       0  4762.6    0.12       0
  4811.1    0.16       0  4998.5    0.07       0  5004.5    0.16       0
  5019.6    0.05       0
Bank Sta=4998.5,5004.5
Exp/Cntr=0.3,0.1

Type RM Length L Ch R = 1,12201,391,391,391
BEGIN DESCRIPTION:
Mapping XS 8fdd16dd
END DESCRIPTION:
XS GIS Cut Line= 4
      3738166.60     10568691.36      3737900.98     10569040.31
      3737739.52     10569274.68      3737822.46     10569616.82
#Sta/Elev= 30
  4413.8  251.14  4488.6  246.78  4496.8  247.03  4503.1  245.81  4532.2  244.77
  4546.7  242.46  4567.6  240.26  4575.7  240.44  4602.9  237.26  4611.2  237.14
  4638.5  233.54  4646.5  233.48  4702.7  227.80  4760.9  224.44  4775.4  222.63
  4846.1  222.56  4875.8  223.96  4881.9  221.15  4917.7  217.74  4953.6  216.70
  4989.4  217.33  5001.3  216.16  5004.0  215.66  5007.3  216.16  5019.2  217.53
  5076.0  216.64  5297.0  218.16  5379.3  217.36  5441.0  219.36  5489.0  219.37
#Mann=3,-1,0
  4413.8    0.05       0  5001.3    0.03       0  5007.3    0.05       0
Bank Sta=5001.3,5007.3
Exp/Cntr=0.3,0.1

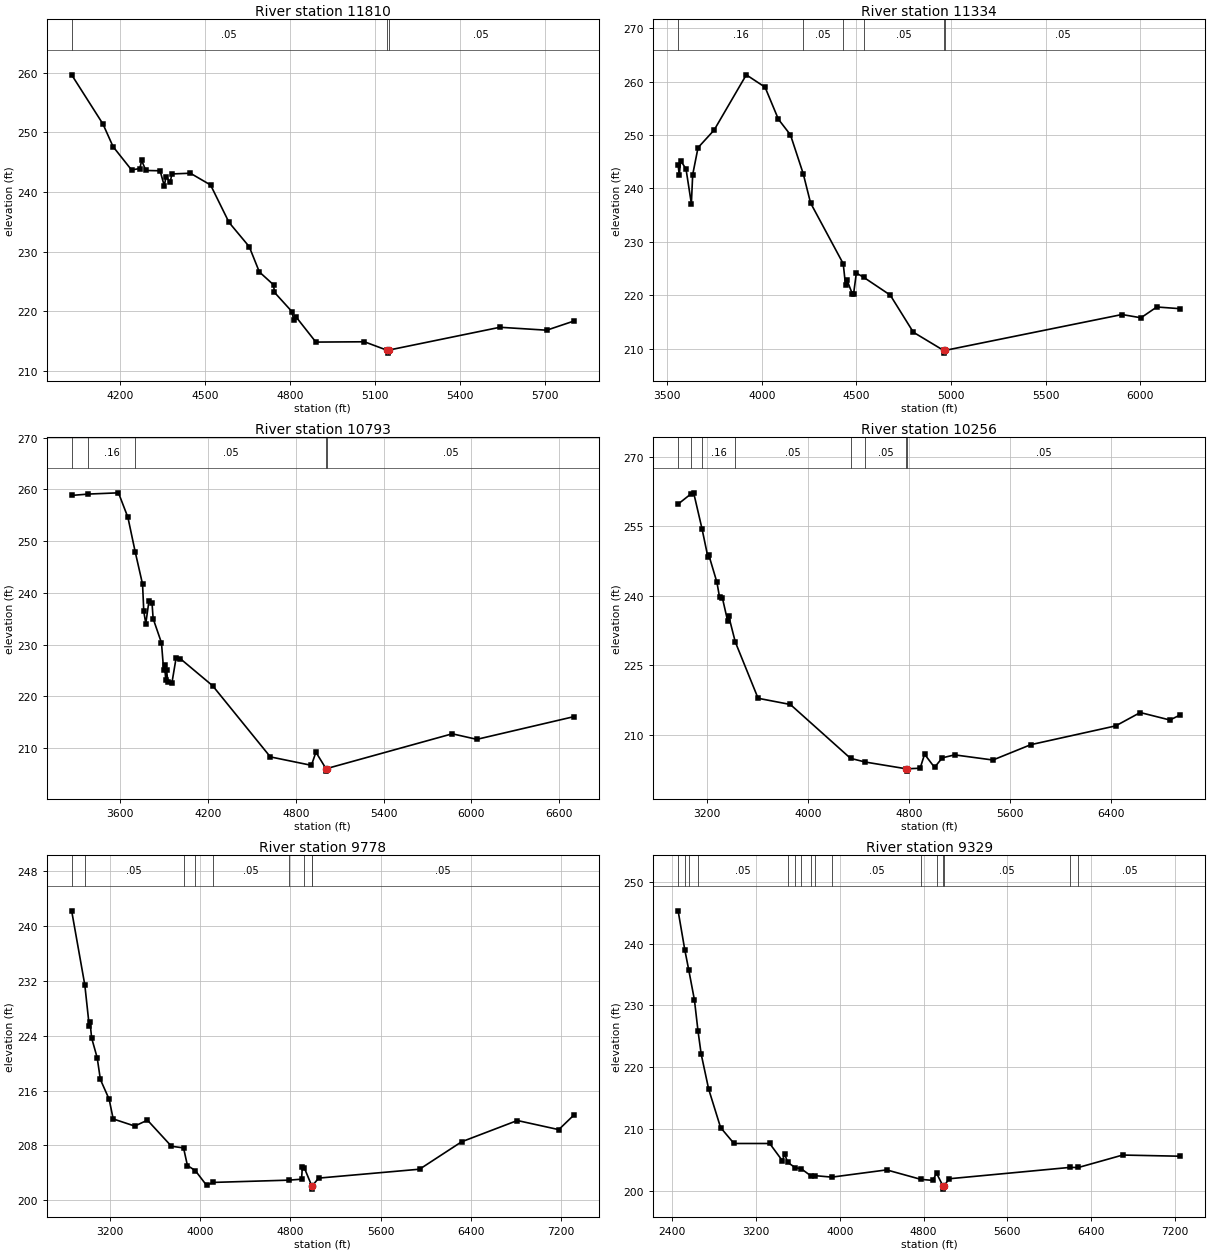
Type RM Length L Ch R = 1,11810,476,476,476
BEGIN DESCRIPTION:
Mapping XS 7302f816
END DESCRIPTION:
XS GIS Cut Line= 4
      3738395.78     10568201.76      3737812.44     10568618.43
      3737562.44     10568930.93      3737764.96     10569554.08
#Sta/Elev= 30
  4029.5  259.62  4140.1  251.37  4175.7  247.59  4240.9  243.69  4270.3  243.93
  4276.5  245.29  4291.2  243.60  4341.6  243.55  4356.4  241.03  4362.5  242.54
  4377.3  241.67  4383.4  243.02  4448.5  243.14  4519.8  241.17  4584.9  234.90
  4656.2  230.84  4691.9  226.61  4742.2  224.44  4745.0  223.20  4806.6  219.98
  4813.0  218.59  4821.0  219.10  4891.4  214.86  5062.7  214.91  5141.8  213.51
  5144.6  213.01  5147.8  213.51  5541.0  217.34  5706.0  216.85  5801.8  218.38
#Mann=3,-1,0
  4029.5    0.05       0  5141.8    0.03       0  5147.8    0.05       0
Bank Sta=5141.8,5147.8
Exp/Cntr=0.3,0.1

Type RM Length L Ch R = 1,11334,541,541,541
BEGIN DESCRIPTION:
Mapping XS e97ecd68
END DESCRIPTION:
XS GIS Cut Line= 5
      3738395.80     10567347.57      3737812.44     10567958.71
      3737520.77     10568354.55      3737374.94     10568514.27
      3737680.49     10569569.80
#Sta/Elev= 30
  3558.5  244.46  3564.6  242.43  3571.9  245.22  3600.2  243.64  3628.5  237.15
  3635.4  242.58  3663.7  247.64  3748.6  250.93  3918.5  261.28  4017.5  258.97
  4088.0  252.96  4151.8  250.03  4219.1  242.76  4257.8  237.29  4430.4  225.90
  4442.5  221.88  4449.5  222.90  4478.8  220.22  4485.0  220.26  4499.6  224.16
  4537.9  223.37  4678.5  220.03  4800.4  213.08  4960.6  209.66  4963.3  209.16
  4966.6  209.66  5902.4  216.39  6002.4  215.78  6086.0  217.80  6210.2  217.48
#Mann=6,-1,0
  3558.5    0.16       0  4219.1    0.05       0  4430.4    0.08       0
  4537.9    0.05       0  4960.6    0.03       0  4966.6    0.05       0
Bank Sta=4960.6,4966.6
Exp/Cntr=0.3,0.1

Type RM Length L Ch R = 1,10793,537,537,537
BEGIN DESCRIPTION:
Mapping XS 4a169a6a
END DESCRIPTION:
XS GIS Cut Line= 4
      3738173.56     10566625.37      3737270.77     10567826.77
      3737083.27     10568153.16      3737548.54     10569632.30
#Sta/Elev= 30
  3269.4  258.83  3384.2  259.09  3589.2  259.33  3653.7  254.58  3703.0  247.98
  3753.7  241.67  3762.0  236.43  3775.8  234.06  3797.4  238.46  3818.3  238.10
  3825.8  235.04  3882.8  230.36  3897.4  225.20  3903.7  226.16  3912.0  223.22
  3918.2  225.02  3925.9  222.85  3953.6  222.51  3982.8  227.44  4012.0  227.28
  4232.7  222.05  4626.4  208.32  4906.9  206.69  4937.6  209.23  5006.0  206.07
  5008.7  205.57  5012.0  206.07  5868.8  212.78  6036.6  211.71  6699.2  216.09
#Mann=5,-1,0
  3269.4    0.05       0  3384.2    0.16       0  3703.0    0.05       0
  5006.0    0.04       0  5012.0    0.05       0
Bank Sta=5006,5012
Exp/Cntr=0.3,0.1

Type RM Length L Ch R = 1,10256,478,478,478
BEGIN DESCRIPTION:
UNT 097 IN BOCR 19.0
END DESCRIPTION:
XS GIS Cut Line= 3
      3737958.26     10566465.67      3736622.89     10568007.50
      3737437.42     10569764.23
#Sta/Elev= 30
  2970.2  259.77  3074.3  262.02  3093.3  262.20  3159.3  254.45  3206.3  248.30
  3213.9  248.71  3277.6  242.86  3298.4  239.63  3320.1  239.58  3362.0  234.57
  3369.7  235.69  3422.8  230.00  3603.3  217.84  3858.8  216.50  4335.3  204.87
  4452.2  204.07  4777.1  202.61  4779.8  202.11  4783.1  202.61  4886.5  202.74
  4921.6  205.76  5000.2  202.92  5062.0  204.98  5159.2  205.62  5462.5  204.51
  5762.4  207.82  6434.8  211.88  6629.1  214.76  6863.7  213.15  6946.3  214.25
#Mann=8,-1,0
  2970.2    0.05       0  3074.3     0.1       0  3159.3    0.16       0
  3422.8    0.05       0  4335.3    0.12       0  4452.2    0.05       0
  4777.1    0.04       0  4783.1    0.05       0
Bank Sta=4777.1,4783.1
Exp/Cntr=0.3,0.1

Type RM Length L Ch R = 1,9778,449,449,449
BEGIN DESCRIPTION:
UNT 097 IN BOCR 18.0
END DESCRIPTION:
XS GIS Cut Line= 3
      3737699.60     10566510.20      3736149.61     10567960.19
      3737298.18     10569985.83
#Sta/Elev= 30
  2860.7  242.24  2977.4  231.41  3016.3  225.47  3023.6  225.97  3037.8  223.68
  3087.1  220.78  3115.4  217.61  3193.1  214.72  3228.8  211.85  3419.8  210.81
  3532.6  211.67  3745.1  207.86  3852.5  207.62  3886.8  205.05  3957.1  204.30
  4056.3  202.16  4113.7  202.58  4784.5  202.91  4898.4  203.05  4905.3  204.77
  4922.4  204.73  4988.1  202.10  4990.9  201.60  4994.1  202.10  5050.3  203.21
  5944.6  204.51  6316.8  208.51  6811.0  211.62  7178.0  210.29  7311.8  212.41
#Mann=9,-1,0
  2860.7    0.16       0  2977.4    0.05       0  3852.5    0.16       0
  3957.1    0.12       0  4113.7    0.05       0  4784.5     0.1       0
  4922.4    0.05       0  4988.1    0.04       0  4994.1    0.05       0
Bank Sta=4988.1,4994.1
Exp/Cntr=0.3,0.1

Type RM Length L Ch R = 1,9329,483,483,483
BEGIN DESCRIPTION:
UNT 097 IN BOCR 17.0
END DESCRIPTION:
XS GIS Cut Line= 3
      3737699.58     10566360.21      3735699.61     10567960.19
      3736699.62     10569960.21
#Sta/Elev= 30
  2455.1  245.29  2519.3  238.94  2556.5  235.75  2611.1  230.86  2645.1  225.86
  2675.2  222.14  2747.2  216.44  2860.9  210.24  2988.9  207.67  3329.9  207.67
  3451.5  204.87  3472.4  206.04  3500.7  204.62  3575.6  203.75  3631.3  203.58
  3725.4  202.41  3762.0  202.47  3924.0  202.23  4447.2  203.40  4774.0  201.87
  4888.2  201.70  4923.8  202.87  4985.3  200.79  4988.0  200.29  4991.3  200.79
  5047.1  201.97  6196.5  203.80  6278.7  203.79  6701.7  205.80  7252.4  205.61
#Mann=16,-1,0
  2455.1    0.16       0  2519.3    0.05       0  2556.5    0.16       0
  2645.1    0.05       0  3500.7    0.12       0  3575.6    0.16       0
  3631.3    0.07       0  3725.4    0.05       0  3762.0    0.07       0
  3924.0    0.05       0  4774.0     0.1       0  4923.8    0.05       0
  4985.3    0.04       0  4991.3    0.05       0  6196.5    0.07       0
  6278.7    0.05       0
Bank Sta=4985.3,4991.3
Exp/Cntr=0.3,0.1

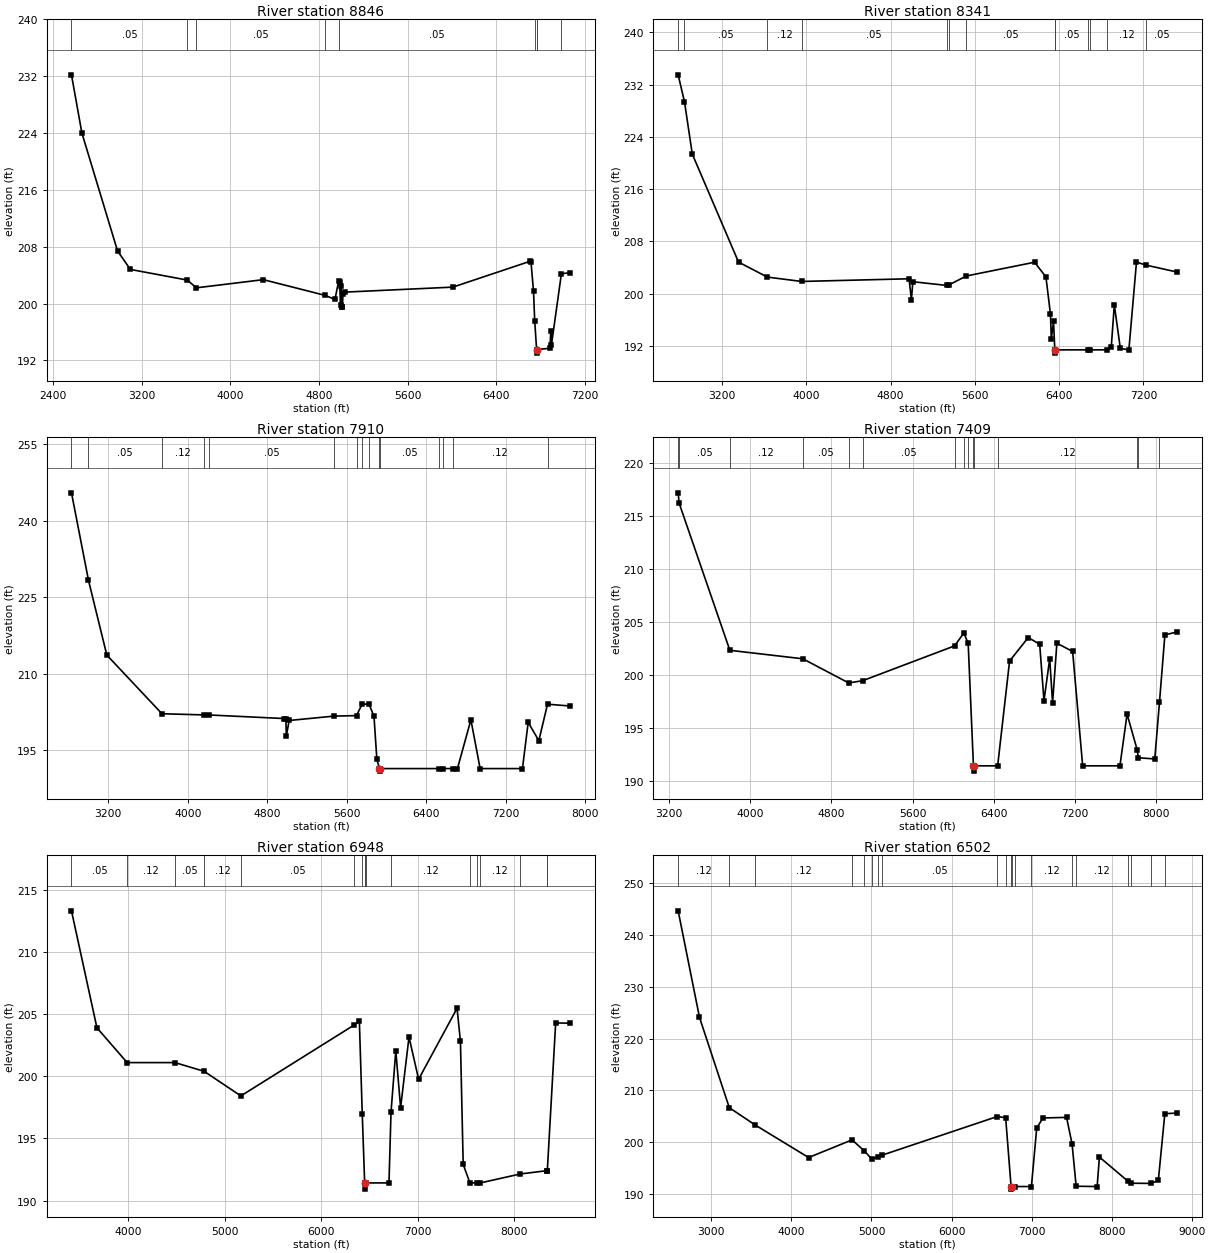
Type RM Length L Ch R = 1,8846,505,505,505
BEGIN DESCRIPTION:
UNT 097 IN BOCR 16.0
END DESCRIPTION:
XS GIS Cut Line= 3
      3737549.59     10566210.20      3735549.61     10567610.19
      3733749.62     10568610.18
#Sta/Elev= 30
  2566.2  232.20  2659.9  224.02  2981.6  207.42  3097.6  204.81  3611.6  203.31
  3692.9  202.22  4297.3  203.37  4852.2  201.17  4943.4  200.59  4976.2  203.12
  4985.3  203.03  4994.0  199.76  5000.1  202.45  5004.4  199.55  5010.4  199.55
  5015.5  201.30  5037.2  201.62  6007.3  202.32  6700.5  205.94  6712.0  205.89
  6734.9  201.74  6745.4  197.62  6762.8  193.53  6765.5  193.03  6768.8  193.53
  6883.6  193.72  6890.4  196.08  6896.2  194.12  6986.5  204.22  7066.6  204.34
#Mann=9,-1,0
  2566.2    0.05       0  3611.6    0.07       0  3692.9    0.05       0
  4852.2    0.08       0  4976.2    0.05       0  6745.4    0.12       0
  6762.8    0.03       0  6768.8    0.12       0  6986.5    0.05       0
Bank Sta=6762.8,6768.8
Exp/Cntr=0.3,0.1

Type RM Length L Ch R = 1,8341,431,431,431
BEGIN DESCRIPTION:
UNT 097 IN BOCR 15.0
END DESCRIPTION:
XS GIS Cut Line= 3
      3737549.62     10566110.18      3735549.61     10567110.19
      3733470.78     10568495.49
#Sta/Elev= 30
  2784.3  233.48  2844.4  229.35  2918.5  221.36  3357.3  204.84  3630.6  202.55
  3955.4  201.88  4975.7  202.29  4998.0  199.09  5012.0  201.84  5335.1  201.27
  5352.9  201.34  5520.2  202.72  6166.7  204.82  6274.9  202.58  6318.2  196.83
  6326.0  193.11  6347.0  195.79  6359.1  191.42  6361.8  190.92  6365.1  191.42
  6673.5  191.42  6690.6  191.42  6856.7  191.42  6895.0  191.87  6924.0  198.29
  6981.1  191.64  7062.2  191.42  7134.3  204.84  7227.7  204.37  7518.5  203.32
#Mann=13,-1,0
  2784.3    0.16       0  2844.4    0.05       0  3630.6    0.12       0
  3955.4    0.05       0  5335.1     0.1       0  5352.9    0.08       0
  5520.2    0.05       0  6359.1    0.03       0  6365.1    0.05       0
  6673.5    0.16       0  6690.6    0.05       0  6856.7    0.12       0
  7227.7    0.05       0
Bank Sta=6359.1,6365.1
Exp/Cntr=0.3,0.1

Type RM Length L Ch R = 1,7910,501,501,501
BEGIN DESCRIPTION:
UNT 097 IN BOCR 14.0
END DESCRIPTION:
XS GIS Cut Line= 4
      3737599.62     10565860.18      3735599.61     10566660.19
      3733599.61     10568260.19      3733351.00     10568432.83
#Sta/Elev= 30
  2830.2  245.43  3001.2  228.30  3185.6  213.65  3740.6  202.16  4164.3  201.93
  4214.4  201.92  4969.5  201.22  4987.5  201.05  4991.5  197.80  5020.3  200.84
  5472.9  201.70  5697.6  201.79  5753.1  204.01  5822.6  204.08  5873.5  201.66
  5902.3  193.24  5928.1  191.42  5930.9  190.92  5934.1  191.42  6527.2  191.42
  6571.6  191.42  6667.8  191.42  6713.1  191.42  6848.4  200.97  6941.2  191.42
  7367.0  191.42  7424.7  200.46  7531.9  196.89  7619.3  204.03  7848.2  203.67
#Mann=15,-1,0
  2830.2    0.16       0  3001.2    0.05       0  3740.6    0.12       0
  4164.3    0.07       0  4214.4    0.05       0  5472.9     0.1       0
  5697.6    0.08       0  5753.1    0.12       0  5822.6    0.05       0
  5928.1    0.03       0  5934.1    0.05       0  6527.2    0.12       0
  6571.6    0.07       0  6667.8    0.12       0  7619.3    0.05       0
Bank Sta=5928.1,5934.1
Exp/Cntr=0.3,0.1

Type RM Length L Ch R = 1,7409,461,461,461
BEGIN DESCRIPTION:
UNT 097 IN BOCR 13.0
END DESCRIPTION:
XS GIS Cut Line= 4
      3737149.59     10565460.20      3735599.61     10566160.19
      3733599.61     10568160.19      3733268.54     10568372.06
#Sta/Elev= 30
  3287.0  217.18  3296.9  216.20  3797.1  202.32  4517.1  201.52  4970.3  199.24
  5106.6  199.45  6015.3  202.74  6106.1  203.96  6148.9  202.97  6200.9  191.42
  6203.7  190.92  6206.9  191.42  6439.8  191.42  6557.5  201.31  6741.3  203.52
  6854.5  202.90  6896.9  197.56  6953.5  201.53  6981.8  197.36  7024.2  202.99
  7179.7  202.21  7278.7  191.42  7646.4  191.42  7717.1  196.30  7816.5  192.93
  7828.6  192.18  7990.3  192.07  8036.9  197.44  8090.1  203.78  8209.2  204.05
#Mann=15,-1,0
  3287.0    0.12       0  3296.9    0.05       0  3797.1    0.12       0
  4517.1    0.05       0  4970.3    0.12       0  5106.6    0.05       0
  6015.3    0.08       0  6106.1    0.12       0  6148.9    0.05       0
  6200.9    0.07       0  6206.9    0.05       0  6439.8    0.12       0
  7816.5    0.05       0  7828.6    0.12       0  8036.9    0.05       0
Bank Sta=6200.9,6206.9
Exp/Cntr=0.3,0.1

Type RM Length L Ch R = 1,6948,446,446,446
BEGIN DESCRIPTION:
UNT 097 IN BOCR 12.0
END DESCRIPTION:
XS GIS Cut Line= 4
      3737049.61     10565460.19      3735499.61     10565710.19
      3734145.29     10567451.45      3733088.44     10568352.51
#Sta/Elev= 30
  3415.3  213.31  3678.7  203.90  3991.8  201.10  4486.2  201.10  4788.5  200.40
  5169.1  198.42  6341.6  204.12  6396.1  204.43  6426.3  196.93  6451.0  191.42
  6453.7  190.92  6457.0  191.42  6462.3  191.42  6702.8  191.42  6723.9  197.11
  6773.4  202.05  6823.2  197.48  6910.1  203.16  7009.6  199.76  7407.6  205.47
  7442.7  202.81  7471.3  192.91  7540.9  191.42  7619.1  191.42  7648.9  191.42
  8062.8  192.14  8334.9  192.40  8342.3  192.40  8428.8  204.29  8580.1  204.27
#Mann=17,-1,0
  3415.3    0.05       0  3991.8    0.12       0  4486.2    0.05       0
  4788.5    0.12       0  5169.1    0.05       0  6341.6    0.08       0
  6426.3    0.12       0  6451.0    0.07       0  6457.0    0.12       0
  6462.3    0.05       0  6723.9    0.12       0  7540.9    0.07       0
  7619.1    0.05       0  7648.9    0.12       0  8062.8    0.05       0
  8334.9    0.12       0  8342.3    0.05       0
Bank Sta=6451,6457
Exp/Cntr=0.3,0.1

Type RM Length L Ch R = 1,6502,436,436,436
BEGIN DESCRIPTION:
UNT 097 IN BOCR 11.0
END DESCRIPTION:
XS GIS Cut Line= 4
      3737349.62     10563910.18      3735349.61     10565310.19
      3734043.28     10567237.08      3732971.23     10568231.01
#Sta/Elev= 30
  2584.8  244.65  2851.2  224.08  3223.5  206.65  3544.0  203.33  4214.8  197.02
  4756.9  200.43  4906.2  198.36  5005.0  196.71  5075.9  197.14  5137.2  197.50
  6571.7  204.94  6676.0  204.71  6743.8  191.42  6746.5  190.92  6749.8  191.42
  6788.6  191.42  6997.7  191.42  7064.2  202.73  7142.1  204.66  7436.8  204.77
  7505.8  199.64  7556.7  191.48  7818.9  191.42  7847.3  197.11  8199.5  192.51
  8245.1  192.06  8493.1  192.02  8583.2  192.60  8664.6  205.49  8816.0  205.60
#Mann=20,-1,0
  2584.8    0.12       0  3223.5    0.05       0  3544.0    0.12       0
  4756.9    0.05       0  4906.2    0.12       0  5005.0    0.05       0
  5075.9    0.07       0  5137.2    0.05       0  6571.7    0.12       0
  6676.0    0.07       0  6743.8    0.07       0  6749.8    0.07       0
  6788.6    0.05       0  6997.7    0.12       0  7505.8    0.07       0
  7556.7    0.12       0  8199.5    0.07       0  8245.1    0.05       0
  8493.1    0.12       0  8664.6    0.05       0
Bank Sta=6743.8,6749.8
Exp/Cntr=0.3,0.1

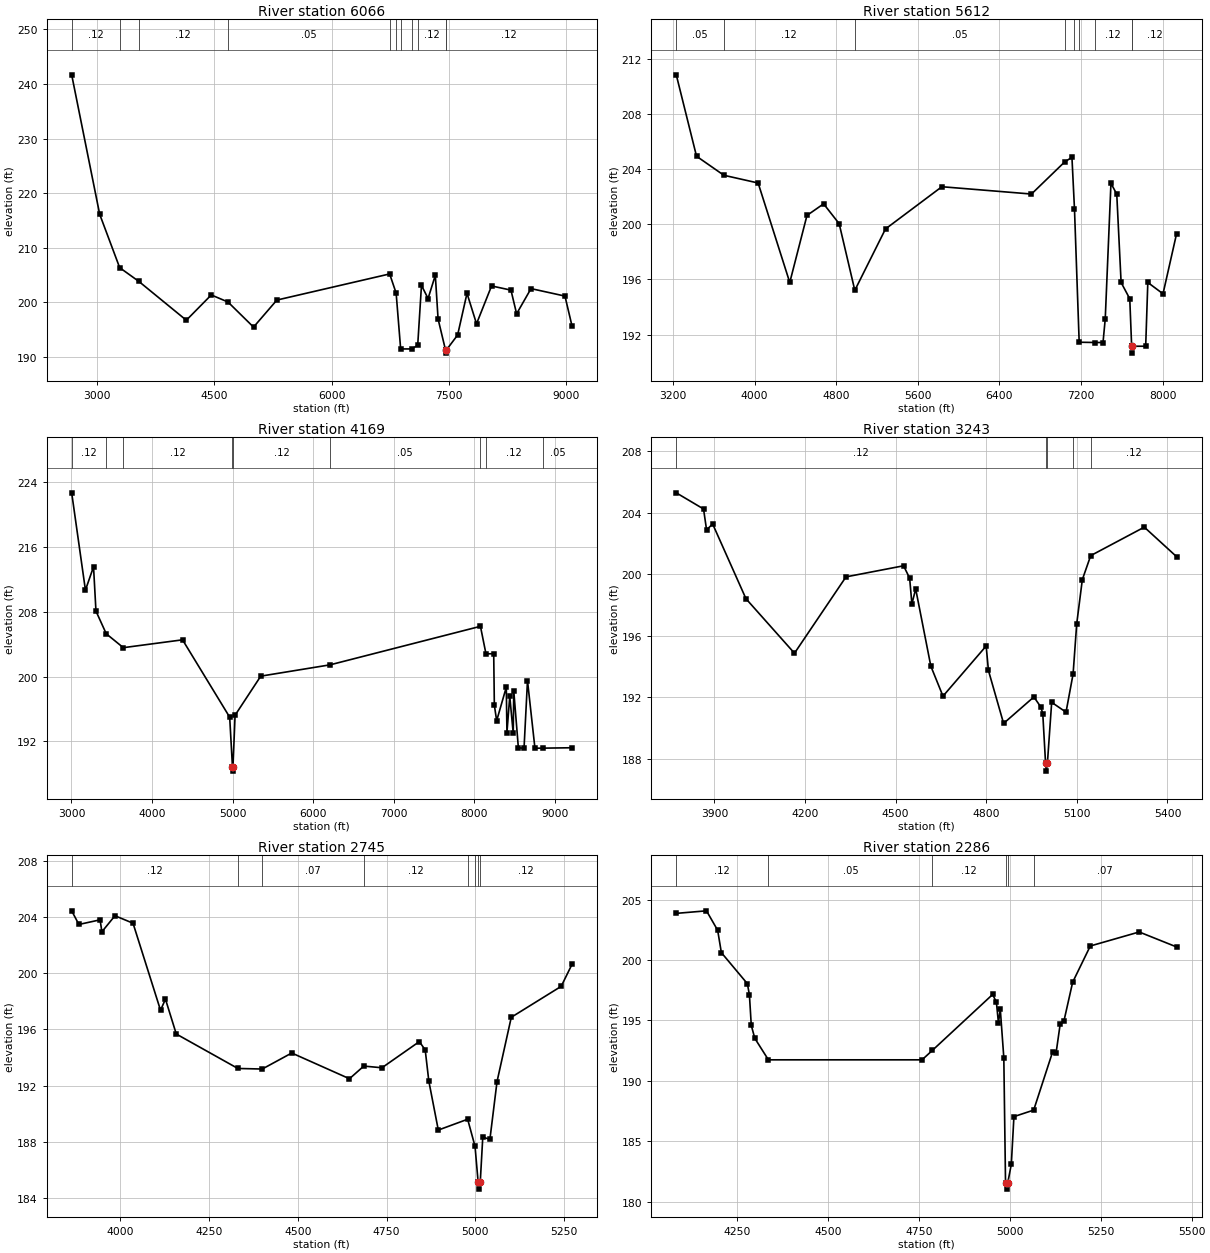
Type RM Length L Ch R = 1,6066,454,454,454
BEGIN DESCRIPTION:
UNT 097 IN BOCR 10.0
END DESCRIPTION:
XS GIS Cut Line= 4
      3737299.64     10563710.17      3735299.61     10564910.19
      3733619.22     10566422.54      3732494.22     10567831.18
#Sta/Elev= 30
  2678.3  241.68  3036.0  216.12  3291.7  206.32  3535.1  203.82  4143.8  196.68
  4462.6  201.32  4676.5  200.02  5002.9  195.42  5301.1  200.38  6742.8  205.17
  6825.7  201.65  6883.4  191.42  7024.0  191.42  7101.3  192.08  7149.5  203.08
  7233.9  200.66  7326.5  204.93  7361.7  196.92  7458.0  191.15  7460.7  190.65
  7464.0  191.15  7611.5  193.97  7731.5  201.62  7853.2  196.03  8045.4  202.97
  8293.5  202.20  8365.6  197.86  8549.7  202.48  8983.6  201.11  9074.2  195.61
#Mann=11,-1,0
  2678.3    0.12       0  3291.7    0.05       0  3535.1    0.12       0
  4676.5    0.05       0  6742.8    0.08       0  6825.7    0.12       0
  6883.4    0.05       0  7024.0    0.07       0  7101.3    0.12       0
  7458.0    0.03       0  7464.0    0.12       0
Bank Sta=7458,7464
Exp/Cntr=0.3,0.1

Type RM Length L Ch R = 1,5612,1443,1443,1443
BEGIN DESCRIPTION:
UNT 097 IN BOCR 9.0
END DESCRIPTION:
XS GIS Cut Line= 4
      3736849.65     10563610.17      3735299.61     10564460.19
      3734005.57     10565898.01      3733105.78     10566694.55
#Sta/Elev= 30
  3232.3  210.82  3430.9  204.92  3699.0  203.54  4034.7  202.98  4344.7  195.77
  4513.4  200.63  4676.4  201.47  4829.0  200.03  4982.2  195.20  5283.0  199.65
  5835.4  202.71  6713.6  202.18  7039.4  204.51  7110.3  204.84  7135.2  201.09
  7181.2  191.44  7334.5  191.42  7414.8  191.42  7436.6  193.13  7492.6  202.96
  7549.5  202.17  7592.1  195.77  7677.0  194.59  7695.4  191.15  7698.1  190.65
  7701.4  191.15  7833.0  191.15  7853.9  195.77  8002.8  194.95  8136.2  199.32
#Mann=9,-1,0
  3232.3    0.05       0  3699.0    0.12       0  4982.2    0.05       0
  7039.4    0.08       0  7135.2    0.12       0  7181.2    0.05       0
  7334.5    0.12       0  7695.4    0.03       0  7701.4    0.12       0
Bank Sta=7695.4,7701.4
Exp/Cntr=0.3,0.1

Type RM Length L Ch R = 1,4169,926,926,926
BEGIN DESCRIPTION:
UNT 097 IN BOCR 8.0
END DESCRIPTION:
XS GIS Cut Line= 4
      3737049.60     10563460.19      3735049.61     10563260.19
      3734665.81     10564987.30      3732788.94     10566538.30
#Sta/Elev= 30
  3002.6  222.72  3173.4  210.69  3273.9  213.58  3304.1  208.10  3431.8  205.30
  3644.1  203.58  4379.4  204.55  4964.8  194.99  4999.5  188.82  5002.3  188.32
  5005.5  188.82  5031.8  195.23  5350.6  200.06  6212.3  201.46  8079.0  206.22
  8147.6  202.82  8243.8  202.83  8251.7  196.47  8280.4  194.55  8400.2  198.70
  8408.0  193.09  8443.2  197.55  8486.2  192.99  8492.7  198.25  8550.0  191.20
  8620.3  191.15  8663.3  199.50  8755.8  191.15  8852.3  191.16  9216.6  191.21
#Mann=9,-1,0
  3002.6    0.12       0  3431.8    0.05       0  3644.1    0.12       0
  4999.5    0.07       0  5005.5    0.12       0  6212.3    0.05       0
  8079.0    0.07       0  8147.6    0.12       0  8852.3    0.05       0
Bank Sta=4999.5,5005.5
Exp/Cntr=0.3,0.1

Type RM Length L Ch R = 1,3243,498,498,498
BEGIN DESCRIPTION:
UNT 097 IN BOCR 7.0
END DESCRIPTION:
XS GIS Cut Line= 3
      3735649.62     10562910.19      3734449.61     10562810.19
      3734278.95     10563229.30
#Sta/Elev= 30
  3773.6  205.29  3863.9  204.24  3874.0  202.88  3894.0  203.27  4004.4  198.41
  4165.0  194.87  4335.6  199.83  4526.2  200.55  4546.3  199.75  4553.8  198.07
  4566.3  199.05  4616.5  194.03  4656.7  192.08  4799.7  195.34  4807.2  193.75
  4857.4  190.31  4957.7  192.03  4980.5  191.38  4987.1  190.95  4996.4  187.71
  4999.1  187.21  5002.4  187.71  5016.6  191.68  5064.1  191.04  5087.5  193.52
  5099.5  196.78  5118.1  199.65  5145.8  201.21  5323.3  203.06  5430.3  201.14
#Mann=5,-1,0
  3773.6    0.12       0  4996.4    0.07       0  5002.4    0.12       0
  5087.5    0.07       0  5145.8    0.12       0
Bank Sta=4996.4,5002.4
Exp/Cntr=0.3,0.1

Type RM Length L Ch R = 1,2745,459,459,459
BEGIN DESCRIPTION:
UNT 097 IN BOCR 6.0
END DESCRIPTION:
XS GIS Cut Line= 3
      3735549.59     10562160.19      3734449.61     10562360.19
      3734159.12     10562333.78
#Sta/Elev= 30
  3862.8  204.43  3883.1  203.46  3942.8  203.79  3947.9  202.94  3984.7  204.08
  4035.6  203.55  4113.1  197.36  4127.0  198.15  4157.5  195.67  4331.0  193.22
  4399.7  193.18  4482.8  194.32  4645.4  192.49  4685.8  193.39  4736.9  193.27
  4842.3  195.13  4858.8  194.54  4869.0  192.32  4895.7  188.84  4978.4  189.61
  4999.2  187.68  5007.9  185.14  5010.7  184.64  5013.9  185.14  5021.0  188.34
  5041.1  188.18  5061.1  192.28  5101.3  196.86  5241.9  199.06  5272.5  200.63
#Mann=8,-1,0
  3862.8    0.12       0  4331.0    0.05       0  4399.7    0.07       0
  4685.8    0.12       0  4978.4    0.07       0  4999.2    0.12       0
  5007.9    0.07       0  5013.9    0.12       0
Bank Sta=5007.9,5013.9
Exp/Cntr=0.3,0.1

Type RM Length L Ch R = 1,2286,76,76,76
BEGIN DESCRIPTION:
UNT 097 IN BOCR 5.0
END DESCRIPTION:
XS GIS Cut Line= 3
      3735490.98     10562146.39      3734599.61     10561960.19
      3734150.07     10562078.27
#Sta/Elev= 30
  4083.3  203.86  4166.4  204.07  4197.1  202.46  4207.3  200.61  4278.8  198.04
  4284.4  197.11  4289.5  194.59  4299.2  193.52  4336.6  191.74  4758.9  191.74
  4787.6  192.53  4953.0  197.15  4963.3  196.51  4968.9  194.80  4974.0  195.93
  4983.7  191.91  4988.4  181.54  4991.1  181.04  4994.4  181.54  5004.3  183.10
  5011.5  187.04  5065.8  187.58  5118.0  192.41  5127.4  192.32  5138.7  194.71
  5149.0  194.96  5172.9  198.16  5221.4  201.16  5355.8  202.32  5458.7  201.08
#Mann=6,-1,0
  4083.3    0.12       0  4336.6    0.05       0  4787.6    0.12       0
  4988.4    0.07       0  4994.4    0.12       0  5065.8    0.07       0
Bank Sta=4988.4,4994.4
Exp/Cntr=0.3,0.1