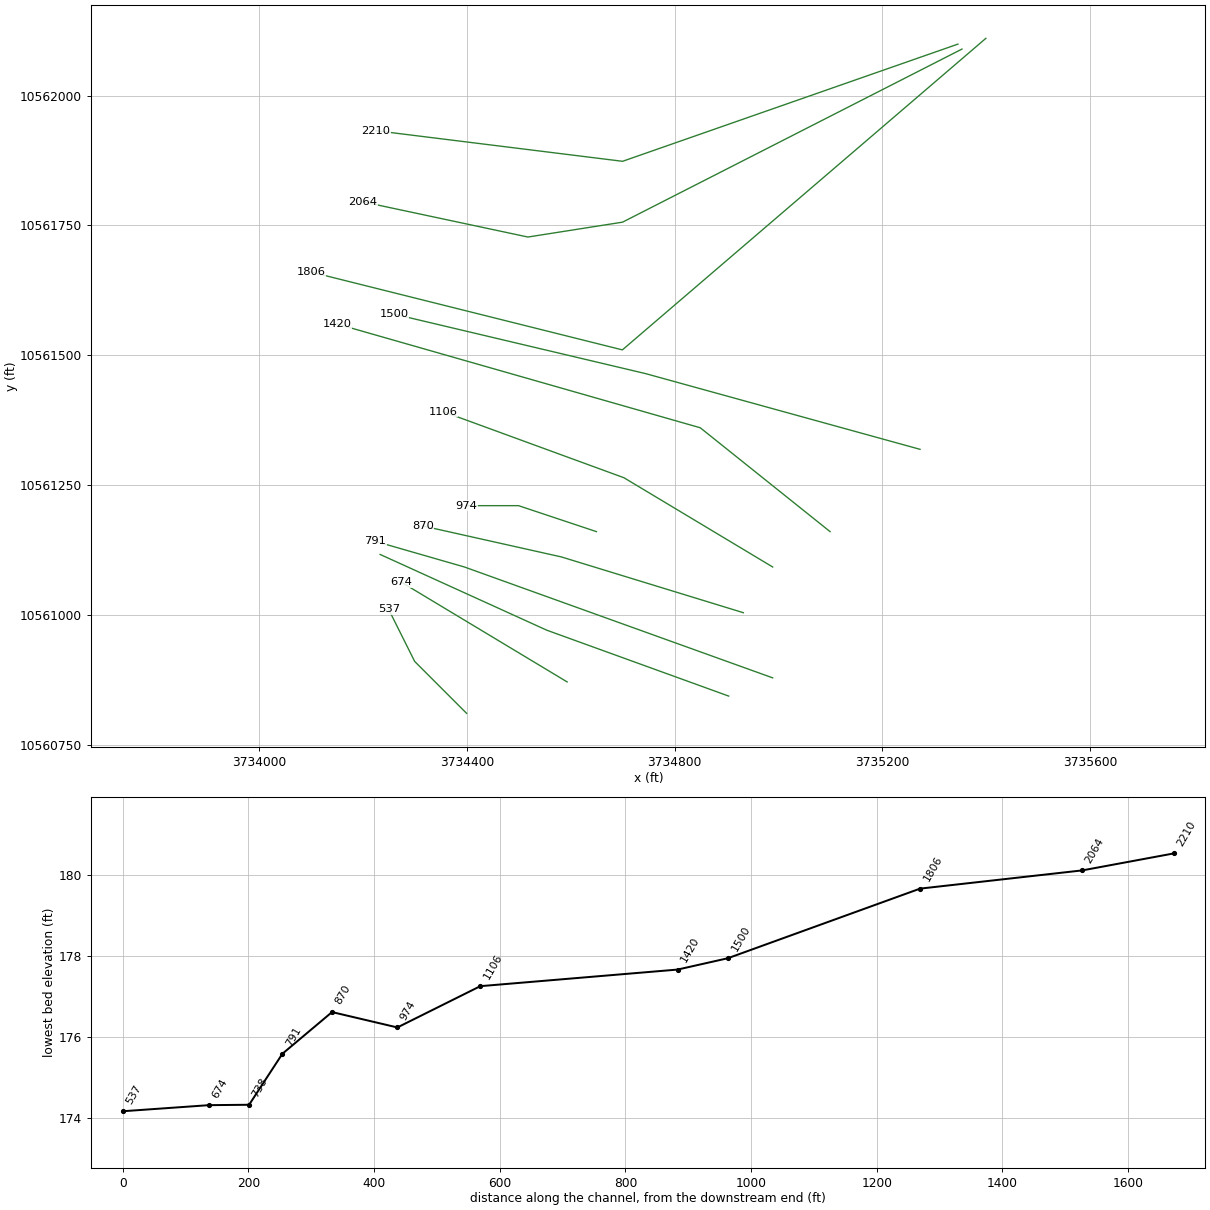
HEC-RAS study UNT 097 IN BOCR.prj: UNT 097 IN BOCR Base Level Engineering

--- UNT 097 IN BOCR.g01 (geometry) --- (continued)

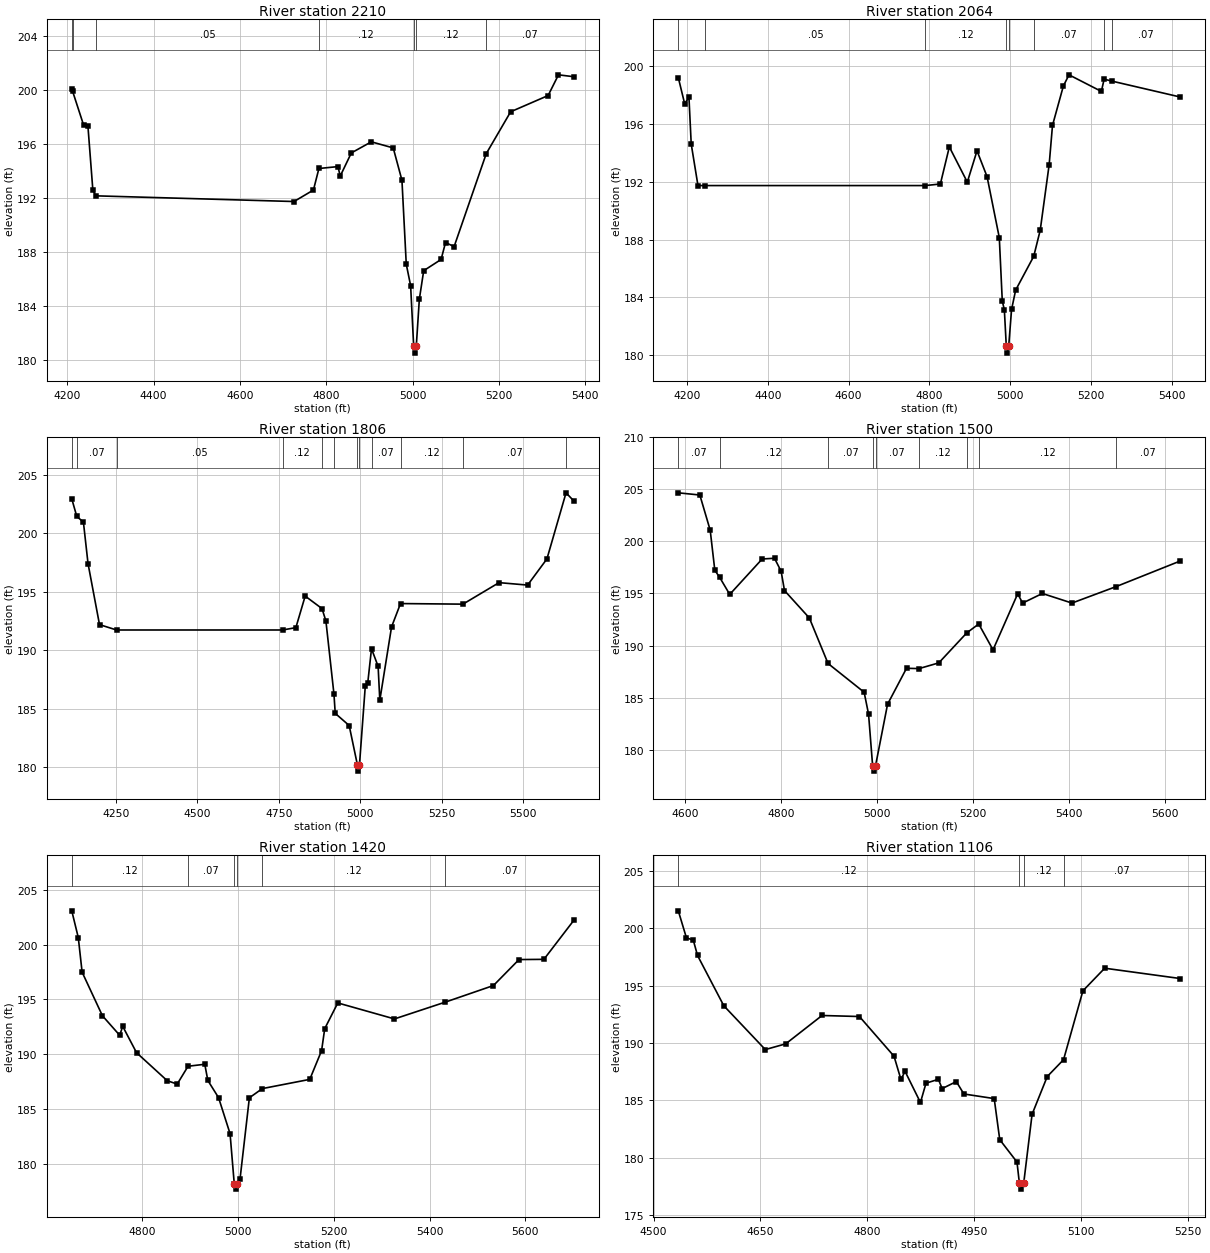
Type RM Length L Ch R = 1,2210,146,146,146
BEGIN DESCRIPTION:
Mapping XS 4f42c369
END DESCRIPTION:
XS GIS Cut Line= 3
      3735345.78     10562099.05      3734699.97     10561873.37
      3734224.43     10561932.37
#Sta/Elev= 30
  4210.2  200.06  4211.9  199.91  4237.9  197.36  4247.7  197.29  4259.1  192.57
  4266.1  192.16  4725.2  191.74  4770.2  192.59  4782.9  194.18  4827.0  194.32
  4832.3  193.62  4858.0  195.33  4904.4  196.15  4955.1  195.70  4975.3  193.31
  4985.3  187.11  4995.4  185.53  5002.5  181.04  5005.3  180.54  5008.5  181.04
  5015.6  184.52  5025.7  186.63  5066.0  187.46  5076.3  188.71  5096.2  188.41
  5170.7  195.28  5227.2  198.37  5314.0  199.57  5338.0  201.10  5373.5  200.96
#Mann=7,-1,0
  4210.2    0.12       0  4211.9    0.07       0  4266.1    0.05       0
  4782.9    0.12       0  5002.5    0.07       0  5008.5    0.12       0
  5170.7    0.07       0
Bank Sta=5002.5,5008.5
Exp/Cntr=0.3,0.1

Type RM Length L Ch R = 1,2064,258,258,258
BEGIN DESCRIPTION:
Mapping XS 9875b44d
END DESCRIPTION:
XS GIS Cut Line= 4
      3735353.61     10562089.51      3734699.97     10561756.18
      3734517.68     10561727.53      3734200.07     10561795.22
#Sta/Elev= 30
  4178.2  199.23  4193.9  197.42  4204.6  197.85  4210.2  194.62  4226.9  191.74
  4245.3  191.74  4789.7  191.74  4827.1  191.85  4849.3  194.42  4893.8  191.98
  4917.8  194.15  4942.7  192.36  4973.0  188.13  4980.4  183.73  4985.5  183.13
  4990.3  180.62  4993.0  180.12  4996.3  180.62  5003.4  183.15  5013.5  184.49
  5058.2  186.83  5074.3  188.64  5096.5  193.20  5104.7  195.91  5131.7  198.65
  5145.6  199.42  5225.7  198.27  5232.6  199.12  5250.9  198.99  5421.2  197.88
#Mann=8,-1,0
  4178.2    0.07       0  4245.3    0.05       0  4789.7    0.12       0
  4990.3    0.07       0  4996.3    0.12       0  5058.2    0.07       0
  5232.6    0.12       0  5250.9    0.07       0
Bank Sta=4990.3,4996.3
Exp/Cntr=0.3,0.1

Type RM Length L Ch R = 1,1806,306,306,306
BEGIN DESCRIPTION:
UNT 097 IN BOCR 4.0
END DESCRIPTION:
XS GIS Cut Line= 3
      3735399.62     10562110.19      3734699.61     10561510.19
      3734099.64     10561660.18
#Sta/Elev= 30
  4114.3  202.96  4129.7  201.45  4150.0  200.97  4164.2  197.42  4199.4  192.20
  4251.7  191.74  4761.0  191.74  4801.9  191.94  4830.5  194.64  4882.1  193.57
  4894.1  192.51  4918.8  186.26  4922.7  184.61  4965.5  183.57  4991.0  180.17
  4993.8  179.67  4997.0  180.17  5014.9  186.93  5022.5  187.21  5034.0  190.14
  5054.3  188.63  5059.5  185.73  5095.5  192.00  5123.0  194.00  5314.6  193.95
  5425.4  195.79  5513.0  195.58  5572.3  197.82  5630.9  203.47  5654.7  202.78
#Mann=12,-1,0
  4114.3    0.12       0  4129.7    0.07       0  4251.7    0.05       0
  4761.0    0.12       0  4882.1    0.07       0  4918.8    0.12       0
  4991.0    0.07       0  4997.0    0.12       0  5034.0    0.07       0
  5123.0    0.12       0  5314.6    0.07       0  5630.9    0.12       0
Bank Sta=4991,4997
Exp/Cntr=0.3,0.1

Type RM Length L Ch R = 1,1500,80,80,80
BEGIN DESCRIPTION:
Mapping XS 7e9a5fa7
END DESCRIPTION:
XS GIS Cut Line= 3
      3735272.92     10561318.67      3734744.24     10561464.51
      3734259.84     10561579.10
#Sta/Elev= 30
  4585.6  204.66  4630.5  204.45  4652.1  201.07  4661.7  197.23  4671.9  196.54
  4692.8  194.91  4760.4  198.31  4786.1  198.38  4799.9  197.13  4806.9  195.28
  4858.7  192.65  4897.7  188.28  4972.9  185.52  4982.1  183.42  4990.6  178.45
  4993.4  177.95  4996.6  178.45  5021.7  184.37  5061.2  187.82  5087.2  187.79
  5128.5  188.34  5186.8  191.22  5211.7  192.07  5241.5  189.59  5292.9  194.97
  5303.2  194.08  5344.3  195.00  5406.0  194.08  5498.0  195.66  5631.8  198.12
#Mann=9,-1,0
  4585.6    0.07       0  4671.9    0.12       0  4897.7    0.07       0
  4990.6    0.07       0  4996.6    0.07       0  5087.2    0.12       0
  5186.8    0.07       0  5211.7    0.12       0  5498.0    0.07       0
Bank Sta=4990.6,4996.6
Exp/Cntr=0.3,0.1

Type RM Length L Ch R = 1,1420,314,314,314
BEGIN DESCRIPTION:
UNT 097 IN BOCR 3.0
END DESCRIPTION:
XS GIS Cut Line= 3
      3735099.58     10561160.21      3734849.61     10561360.19
      3734149.64     10561560.18
#Sta/Elev= 30
  4653.1  203.08  4666.7  200.64  4674.7  197.48  4717.1  193.50  4753.1  191.72
  4759.5  192.53  4788.3  190.13  4852.4  187.57  4873.2  187.26  4895.9  188.89
  4930.8  189.07  4937.2  187.59  4959.6  186.02  4983.6  182.73  4992.3  178.17
  4995.1  177.67  4998.3  178.17  5004.4  178.59  5023.9  186.01  5051.0  186.85
  5150.0  187.69  5174.7  190.32  5181.2  192.32  5208.5  194.67  5326.8  193.21
  5433.3  194.75  5533.5  196.26  5586.8  198.63  5638.8  198.65  5701.2  202.21
#Mann=6,-1,0
  4653.1    0.12       0  4895.9    0.07       0  4992.3    0.07       0
  4998.3    0.07       0  5051.0    0.12       0  5433.3    0.07       0
Bank Sta=4992.3,4998.3
Exp/Cntr=0.3,0.1

Type RM Length L Ch R = 1,1106,132,132,132
BEGIN DESCRIPTION:
Mapping XS e2dcc406
END DESCRIPTION:
XS GIS Cut Line= 3
      3734989.04     10561092.11      3734702.57     10561263.99
      3734354.12     10561391.41
#Sta/Elev= 30
  4534.7  201.51  4546.1  199.16  4555.8  198.95  4561.7  197.62  4598.6  193.24
  4656.9  189.42  4685.6  189.92  4736.6  192.39  4789.1  192.30  4837.7  188.84
  4847.4  186.82  4853.2  187.52  4874.8  184.81  4882.6  186.49  4900.0  186.83
  4905.3  186.02  4925.2  186.63  4935.8  185.55  4978.4  185.15  4986.2  181.57
  5010.4  179.62  5013.8  177.76  5016.5  177.26  5019.8  177.76  5031.6  183.78
  5052.9  187.07  5075.8  188.54  5103.0  194.54  5133.6  196.51  5239.8  195.61
#Mann=4,-1,0
  4534.7    0.12       0  5013.8    0.07       0  5019.8    0.12       0
  5075.8    0.07       0
Bank Sta=5013.8,5019.8
Exp/Cntr=0.3,0.1

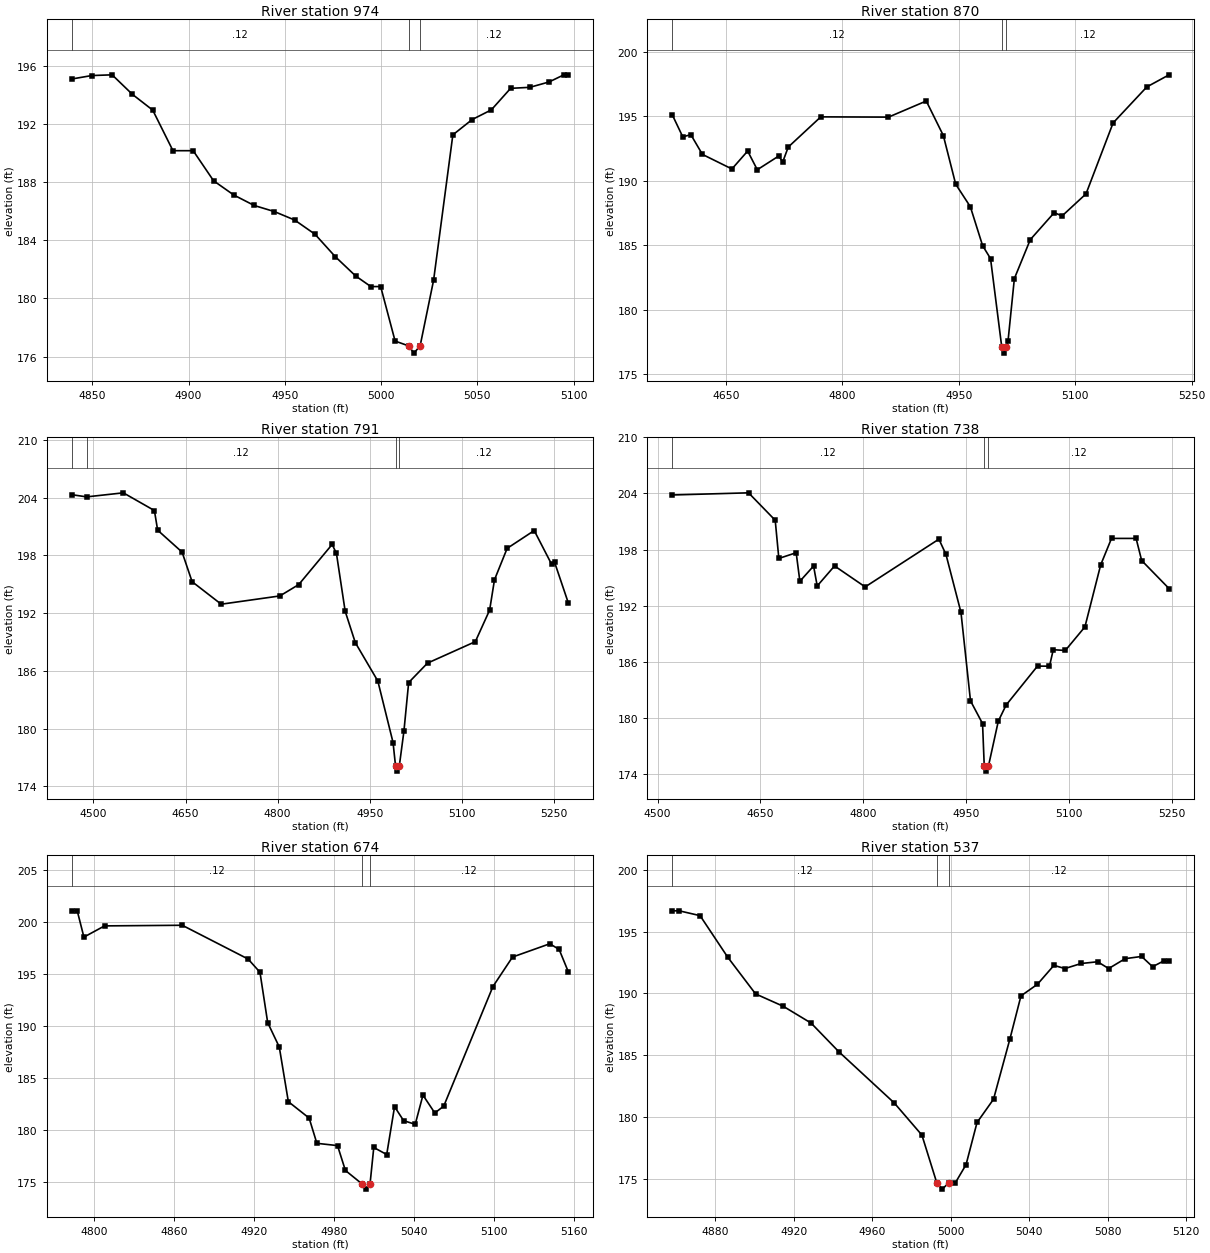
Type RM Length L Ch R = 1,974,104,104,104
BEGIN DESCRIPTION:
UNT 097 IN BOCR 2.0
END DESCRIPTION:
XS GIS Cut Line= 3
      3734649.60     10561160.19      3734499.61     10561210.19
      3734399.62     10561210.19
#Sta/Elev= 30
  4839.2  195.10  4849.7  195.34  4860.3  195.39  4870.8  194.05  4881.4  192.96
  4891.9  190.17  4902.4  190.17  4913.0  188.10  4923.5  187.12  4934.1  186.40
  4944.6  185.98  4955.1  185.40  4965.7  184.42  4976.2  182.88  4986.8  181.55
  4994.7  180.82  4999.8  180.82  5007.3  177.07  5014.3  176.74  5017.1  176.24
  5020.3  176.74  5027.3  181.26  5037.3  191.26  5047.3  192.31  5057.3  192.98
  5067.3  194.46  5077.3  194.53  5087.3  194.90  5094.8  195.38  5097.3  195.38
#Mann=3,-1,0
  4839.2    0.12       0  5014.3    0.07       0  5020.3    0.12       0
Bank Sta=5014.3,5020.3
Exp/Cntr=0.3,0.1

Type RM Length L Ch R = 1,870,79,79,79
BEGIN DESCRIPTION:
Mapping XS a860cddf
END DESCRIPTION:
XS GIS Cut Line= 3
      3734932.57     10561004.04      3734582.13     10561111.45
      3734315.16     10561171.14
#Sta/Elev= 30
  4580.7  195.11  4594.3  193.39  4604.7  193.56  4619.6  192.03  4657.6  190.90
  4677.9  192.29  4690.3  190.84  4717.8  191.90  4723.1  191.45  4730.2  192.60
  4772.1  194.94  4859.3  194.92  4908.0  196.17  4930.0  193.49  4945.9  189.72
  4964.8  187.97  4980.6  184.95  4990.8  183.95  5005.2  177.12  5007.9  176.62
  5011.2  177.12  5013.3  177.54  5021.5  182.40  5042.0  185.42  5072.8  187.51
  5083.0  187.26  5113.8  188.97  5148.7  194.47  5192.1  197.26  5220.8  198.20
#Mann=3,-1,0
  4580.7    0.12       0  5005.2    0.07       0  5011.2    0.12       0
Bank Sta=5005.2,5011.2
Exp/Cntr=0.3,0.1

Type RM Length L Ch R = 1,791,53,53,53
BEGIN DESCRIPTION:
Mapping XS 531e7b1d
END DESCRIPTION:
XS GIS Cut Line= 3
      3734989.04     10560878.57      3734395.28     10561092.12
      3734224.03     10561141.41
#Sta/Elev= 30
  4464.3  204.31  4489.0  204.08  4548.7  204.50  4599.3  202.66  4604.6  200.62
  4644.4  198.34  4660.7  195.27  4708.1  192.93  4803.7  193.79  4834.4  194.97
  4888.8  199.14  4895.8  198.20  4910.0  192.20  4926.5  188.94  4963.2  184.95
  4988.0  178.56  4992.1  176.09  4994.8  175.59  4998.1  176.09  5005.7  179.74
  5013.4  184.79  5044.1  186.81  5122.0  189.04  5145.3  192.32  5153.2  195.47
  5173.8  198.73  5217.9  200.58  5246.3  197.07  5251.0  197.30  5273.5  193.05
#Mann=4,-1,0
  4464.3    0.07       0  4489.0    0.12       0  4992.1    0.07       0
  4998.1    0.12       0
Bank Sta=4992.1,4998.1
Exp/Cntr=0.3,0.1

Type RM Length L Ch R = 1,738,64,64,64
BEGIN DESCRIPTION:
Mapping XS 944ee30c
END DESCRIPTION:
XS GIS Cut Line= 3
      3734904.39     10560843.44      3734553.92     10560970.39
      3734233.16     10561116.19
#Sta/Elev= 30
  4521.3  203.83  4632.7  204.06  4671.6  201.13  4676.9  197.05  4702.2  197.66
  4707.6  194.61  4727.6  196.24  4732.9  194.11  4758.2  196.25  4802.9  194.01
  4910.5  199.11  4920.8  197.48  4942.7  191.29  4956.6  181.84  4974.2  179.41
  4976.7  174.83  4979.4  174.33  4982.7  174.83  4997.2  179.67  5008.6  181.39
  5054.4  185.55  5071.9  185.54  5077.4  187.30  5095.0  187.22  5123.6  189.74
  5146.6  196.36  5162.4  199.19  5198.3  199.19  5206.4  196.83  5246.4  193.83
#Mann=3,-1,0
  4521.3    0.12       0  4976.7    0.07       0  4982.7    0.12       0
Bank Sta=4976.7,4982.7
Exp/Cntr=0.3,0.1

Type RM Length L Ch R = 1,674,137,137,137
BEGIN DESCRIPTION:
Mapping XS b7d426a2
END DESCRIPTION:
XS GIS Cut Line= 2
      3734593.18     10560870.77      3734273.73     10561062.96
#Sta/Elev= 30
  4783.2  201.11  4787.5  201.11  4792.5  198.58  4808.0  199.66  4866.3  199.72
  4915.7  196.47  4924.6  195.20  4930.4  190.35  4939.1  188.00  4945.9  182.74
  4961.5  181.16  4967.3  178.73  4982.8  178.51  4988.7  176.12  5001.2  174.82
  5004.0  174.32  5007.2  174.82  5010.0  178.33  5019.7  177.65  5025.6  182.26
  5032.4  180.91  5041.1  180.56  5046.9  183.37  5055.8  181.65  5062.5  182.31
  5099.4  193.82  5114.1  196.66  5142.1  197.94  5149.1  197.39  5156.0  195.23
#Mann=3,-1,0
  4783.2    0.12       0  5001.2    0.07       0  5007.2    0.12       0
Bank Sta=5001.2,5007.2
Exp/Cntr=0.3,0.1

Type RM Length L Ch R = 1,537,0,0,0
BEGIN DESCRIPTION:
UNT 097 IN BOCR 1.0
END DESCRIPTION:
XS GIS Cut Line= 3
      3734399.64     10560810.16      3734299.61     10560910.19
      3734249.59     10561010.22
#Sta/Elev= 30
  4858.0  196.68  4861.6  196.68  4872.2  196.29  4886.3  192.93  4900.5  189.96
  4914.6  188.96  4928.8  187.60  4942.9  185.29  4971.2  181.14  4985.3  178.54
  4992.9  174.67  4995.7  174.17  4998.9  174.67  5002.3  174.67  5007.8  176.15
  5013.4  179.56  5021.8  181.44  5030.2  186.34  5035.8  189.80  5044.2  190.74
  5052.6  192.27  5058.2  192.01  5066.5  192.42  5074.9  192.56  5080.5  192.01
  5088.9  192.81  5097.3  192.99  5102.9  192.16  5108.5  192.62  5111.3  192.62
#Mann=3,-1,0
  4858.0    0.12       0  4992.9    0.07       0  4998.9    0.12       0
Bank Sta=4992.9,4998.9
Exp/Cntr=0.3,0.1

Chan Stop Cuts=-1