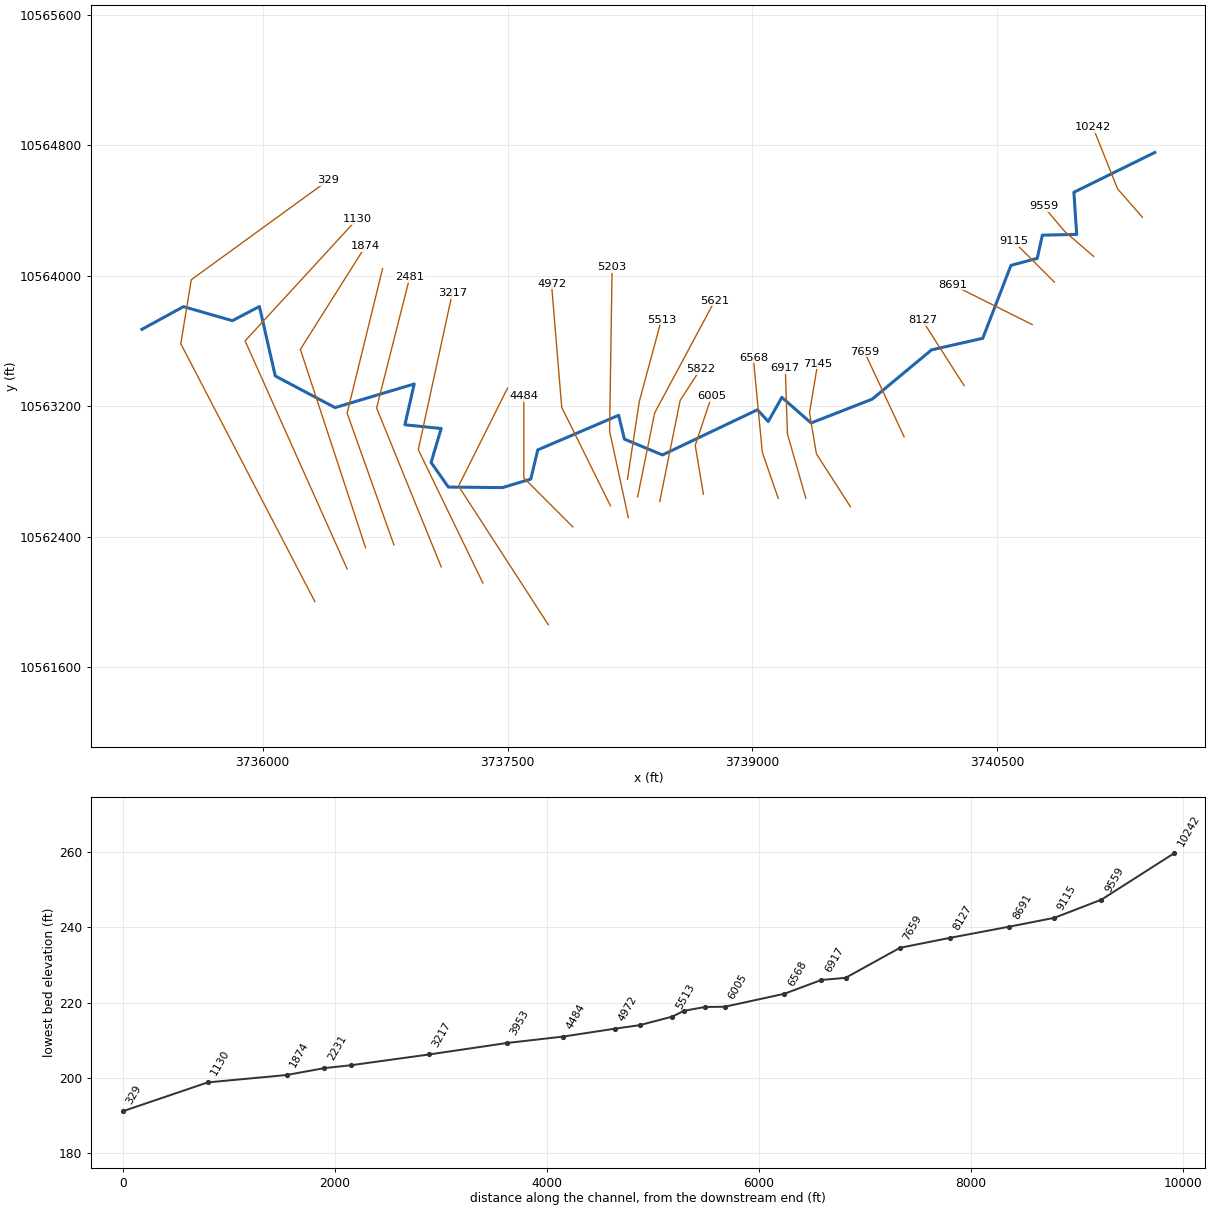
--- UNT 098 IN BOCR.prj (project) ---

Proj Title=UNT 098 IN BOCR Base Level Engineering
Current Plan=p01
Default Exp/Contr=0.3,0.1
English Units
Geom File=g01
Flow File=f01
Plan File=p01
BEGIN DESCRIPTION:
UNT 098 IN BOCR
END DESCRIPTION:

--- UNT 098 IN BOCR.p01 (plan) ---

Plan Title=Multiple Run
Short Identifier=Multiple
Geom File=g01
Flow File=f01
Subcritical Flow
K Sum by GR= 0
Std Step Tol= 0.01
Critical Tol= 0.01
Num of Std Step Trials= 20
Max Error Tol= 0.3
Flow Tol Ratio= 0.001
Split Flow NTrial= 30
Split Flow Tol= 0.02
Split Flow Ratio= 0.02
Log Output Level= 0
Friction Slope Method= 1
Unsteady Friction Slope Method= 2
Unsteady Bridges Friction Slope Method= 1
Parabolic Critical Depth
Global Vel Dist=  1 , 1 , 1
Global Log Level= 0
CheckData=True
Encroach Param= -1, 0, 0, 0
BEGIN DESCRIPTION:
Multiple Run
END DESCRIPTION:

--- UNT 098 IN BOCR.f01 (steady flow) ---

Flow Title=Multiple
Number of Profiles=7
Profile Names=10-year,25-year,50-year,1pct_min,100-year,1pct_plu,500-year
River Rch & RM= UNT 098 IN BOCR,Reach-1,10242
     734    1012    1246    1128    1525    2063    2294
Boundary for River Rch & Prof#=UNT 098 IN BOCR,Reach-1,1
Up Type=0
Dn Type=3
Dn Slope=0.005
Boundary for River Rch & Prof#=UNT 098 IN BOCR,Reach-1,2
Up Type=0
Dn Type=3
Dn Slope=0.005
Boundary for River Rch & Prof#=UNT 098 IN BOCR,Reach-1,3
Up Type=0
Dn Type=3
Dn Slope=0.005
Boundary for River Rch & Prof#=UNT 098 IN BOCR,Reach-1,4
Up Type=0
Dn Type=3
Dn Slope=0.005
Boundary for River Rch & Prof#=UNT 098 IN BOCR,Reach-1,5
Up Type=0
Dn Type=3
Dn Slope=0.005
Boundary for River Rch & Prof#=UNT 098 IN BOCR,Reach-1,6
Up Type=0
Dn Type=3
Dn Slope=0.005
Boundary for River Rch & Prof#=UNT 098 IN BOCR,Reach-1,7
Up Type=0
Dn Type=3
Dn Slope=0.005

--- UNT 098 IN BOCR.g01 (geometry) ---

Geom Title=Existing Conditions

River Reach=UNT 098 IN BOCR,Reach-1
Reach XY= 30
      3741464.50     10564755.00      3740969.00     10564511.00
      3740986.25     10564253.00      3740775.75     10564248.00
      3740744.50     10564106.00      3740583.50     10564063.00
      3740410.75     10563616.00      3740097.25     10563545.00
      3739733.50     10563243.00      3739359.50     10563097.00
      3739180.00     10563254.00      3739096.75     10563106.00
      3739030.75     10563178.00      3738448.75     10562901.00
      3738215.75     10562998.00      3738180.50     10563144.00
      3737685.00     10562932.00      3737642.25     10562753.00
      3737469.50     10562701.00      3737137.50     10562704.00
      3737031.50     10562855.00      3737093.50     10563063.00
      3736871.25     10563086.00      3736928.00     10563336.00
      3736443.13     10563191.11      3736077.00     10563385.00
      3735980.00     10563811.00      3735814.50     10563724.00
      3735514.75     10563810.00      3735260.25     10563671.00

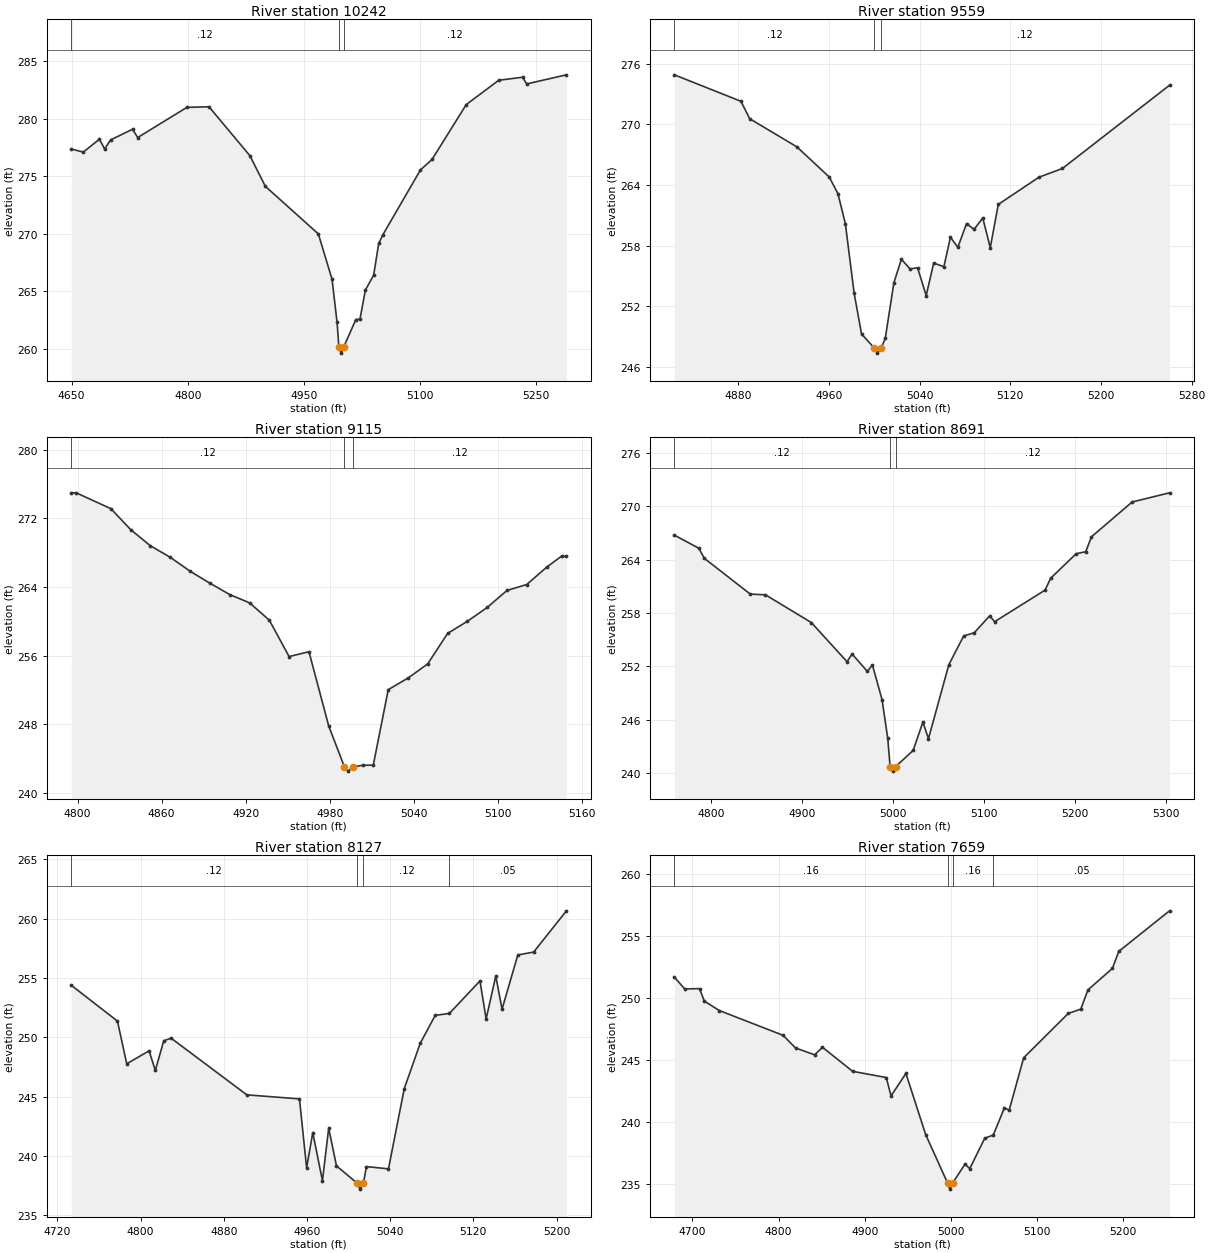
Type RM Length L Ch R = 1,10242,683,683,683
BEGIN DESCRIPTION:
UNT 098 IN BOCR 14.0
END DESCRIPTION:
XS GIS Cut Line= 3
      3741388.78     10564357.97      3741236.89     10564531.56
      3741084.98     10564911.34
#Sta/Elev= 30
  4649.6  277.35  4665.2  277.09  4686.0  278.21  4692.7  277.35  4700.3  278.14
  4728.7  279.07  4735.4  278.35  4799.0  280.97  4827.5  281.02  4880.3  276.78
  4900.3  274.12  4968.8  269.99  4986.5  266.06  4993.0  262.31  4995.4  260.15
  4998.1  259.65  5001.4  260.15  5017.2  262.56  5022.6  262.60  5029.6  265.12
  5040.3  266.42  5046.8  269.16  5052.2  269.92  5100.7  275.54  5115.7  276.45
  5159.9  281.21  5201.9  283.32  5232.6  283.58  5238.0  283.00  5289.3  283.79
#Mann=3,-1,0
  4649.6    0.12       0  4995.4    0.07       0  5001.4    0.12       0
Bank Sta=4995.4,5001.4
Exp/Cntr=0.3,0.1

Type RM Length L Ch R = 1,9559,444,444,444
BEGIN DESCRIPTION:
UNT 098 IN BOCR 13.0
END DESCRIPTION:
XS GIS Cut Line= 3
      3741090.07     10564117.67      3740912.08     10564271.79
      3740782.17     10564425.51
#Sta/Elev= 30
  4823.7  274.90  4882.4  272.28  4890.1  270.56  4931.8  267.77  4960.3  264.79
  4967.9  263.16  4974.5  260.18  4982.2  253.32  4988.8  249.25  5000.1  247.87
  5002.8  247.37  5006.1  247.87  5009.7  248.83  5017.3  254.33  5023.9  256.65
  5031.6  255.70  5038.2  255.81  5045.8  253.07  5052.4  256.28  5061.4  255.92
  5067.2  258.84  5073.7  257.83  5081.4  260.19  5088.0  259.61  5095.7  260.74
  5102.3  257.80  5109.4  262.08  5145.2  264.77  5166.0  265.64  5260.4  273.87
#Mann=3,-1,0
  4823.7    0.12       0  5000.1    0.07       0  5006.1    0.12       0
Bank Sta=5000.1,5006.1
Exp/Cntr=0.3,0.1

Type RM Length L Ch R = 1,9115,424,424,424
BEGIN DESCRIPTION:
UNT 098 IN BOCR 12.0
END DESCRIPTION:
XS GIS Cut Line= 3
      3740849.60     10563960.20      3740699.61     10564110.19
      3740599.63     10564210.16
#Sta/Elev= 30
  4795.5  274.99  4799.0  274.99  4823.8  273.14  4837.9  270.70  4852.0  268.81
  4866.2  267.47  4880.3  265.85  4894.5  264.45  4908.6  263.13  4922.8  262.16
  4936.9  260.14  4951.0  255.90  4965.2  256.46  4979.3  247.80  4990.5  243.04
  4993.2  242.54  4996.5  243.04  5004.1  243.23  5011.1  243.23  5021.8  252.04
  5035.9  253.39  5050.0  255.05  5064.2  258.60  5078.3  260.01  5092.5  261.63
  5106.6  263.61  5120.7  264.30  5134.9  266.32  5145.5  267.60  5149.0  267.60
#Mann=3,-1,0
  4795.5    0.12       0  4990.5    0.07       0  4996.5    0.12       0
Bank Sta=4990.5,4996.5
Exp/Cntr=0.3,0.1

Type RM Length L Ch R = 1,8691,564,564,564
BEGIN DESCRIPTION:
UNT 098 IN BOCR 11.0
END DESCRIPTION:
XS GIS Cut Line= 2
      3740713.56     10563700.20      3740227.44     10563943.26
#Sta/Elev= 30
  4760.1  266.74  4786.9  265.27  4793.0  264.13  4843.4  260.11  4860.1  260.03
  4910.4  256.91  4949.6  252.51  4955.2  253.37  4971.9  251.42  4977.5  252.14
  4988.1  248.22  4994.3  243.89  4996.9  240.70  4999.6  240.20  5002.9  240.70
  5022.2  242.53  5032.9  245.72  5039.0  243.85  5061.4  252.18  5077.6  255.39
  5089.3  255.77  5106.1  257.65  5111.7  257.01  5167.0  260.56  5173.2  261.90
  5201.1  264.65  5211.7  264.88  5217.9  266.55  5262.6  270.47  5303.6  271.50
#Mann=3,-1,0
  4760.1    0.12       0  4996.9    0.07       0  5002.9    0.12       0
Bank Sta=4996.9,5002.9
Exp/Cntr=0.3,0.1

Type RM Length L Ch R = 1,8127,468,468,468
BEGIN DESCRIPTION:
UNT 098 IN BOCR 10.0
END DESCRIPTION:
XS GIS Cut Line= 2
      3740296.85     10563325.24      3740040.80     10563726.62
#Sta/Elev= 30
  4733.4  254.39  4777.8  251.37  4786.7  247.77  4808.2  248.86  4814.2  247.21
  4822.3  249.71  4829.4  249.93  4902.2  245.15  4952.8  244.81  4959.7  238.99
  4965.6  241.97  4974.9  237.91  4980.9  242.34  4988.4  239.16  5008.3  237.70
  5011.1  237.20  5014.3  237.70  5017.2  239.10  5038.4  238.91  5053.6  245.68
  5068.9  249.49  5083.3  251.85  5097.0  252.02  5126.4  254.76  5132.3  251.55
  5141.6  255.18  5147.6  252.37  5162.8  256.95  5178.0  257.19  5209.5  260.67
#Mann=4,-1,0
  4733.4    0.12       0  5008.3    0.07       0  5014.3    0.12       0
  5097.0    0.05       0
Bank Sta=5008.3,5014.3
Exp/Cntr=0.3,0.1

Type RM Length L Ch R = 1,7659,514,514,514
BEGIN DESCRIPTION:
UNT 098 IN BOCR 9.0
END DESCRIPTION:
XS GIS Cut Line= 2
      3739928.82     10563012.69      3739685.75     10563533.57
#Sta/Elev= 30
  4679.0  251.66  4690.9  250.71  4708.2  250.73  4713.7  249.73  4731.1  248.97
  4805.2  246.97  4819.7  245.95  4841.8  245.40  4850.9  246.01  4885.9  244.07
  4925.0  243.57  4930.5  242.09  4947.8  243.90  4970.7  238.98  4996.1  235.08
  4998.8  234.58  5002.1  235.08  5016.4  236.59  5021.9  236.23  5039.3  238.68
  5049.2  238.94  5062.1  241.12  5067.7  240.95  5084.5  245.16  5136.2  248.73
  5150.8  249.08  5159.1  250.63  5187.5  252.36  5194.9  253.73  5253.8  257.00
#Mann=4,-1,0
  4679.0    0.16       0  4996.1    0.07       0  5002.1    0.16       0
  5049.2    0.05       0
Bank Sta=4996.1,5002.1
Exp/Cntr=0.3,0.1

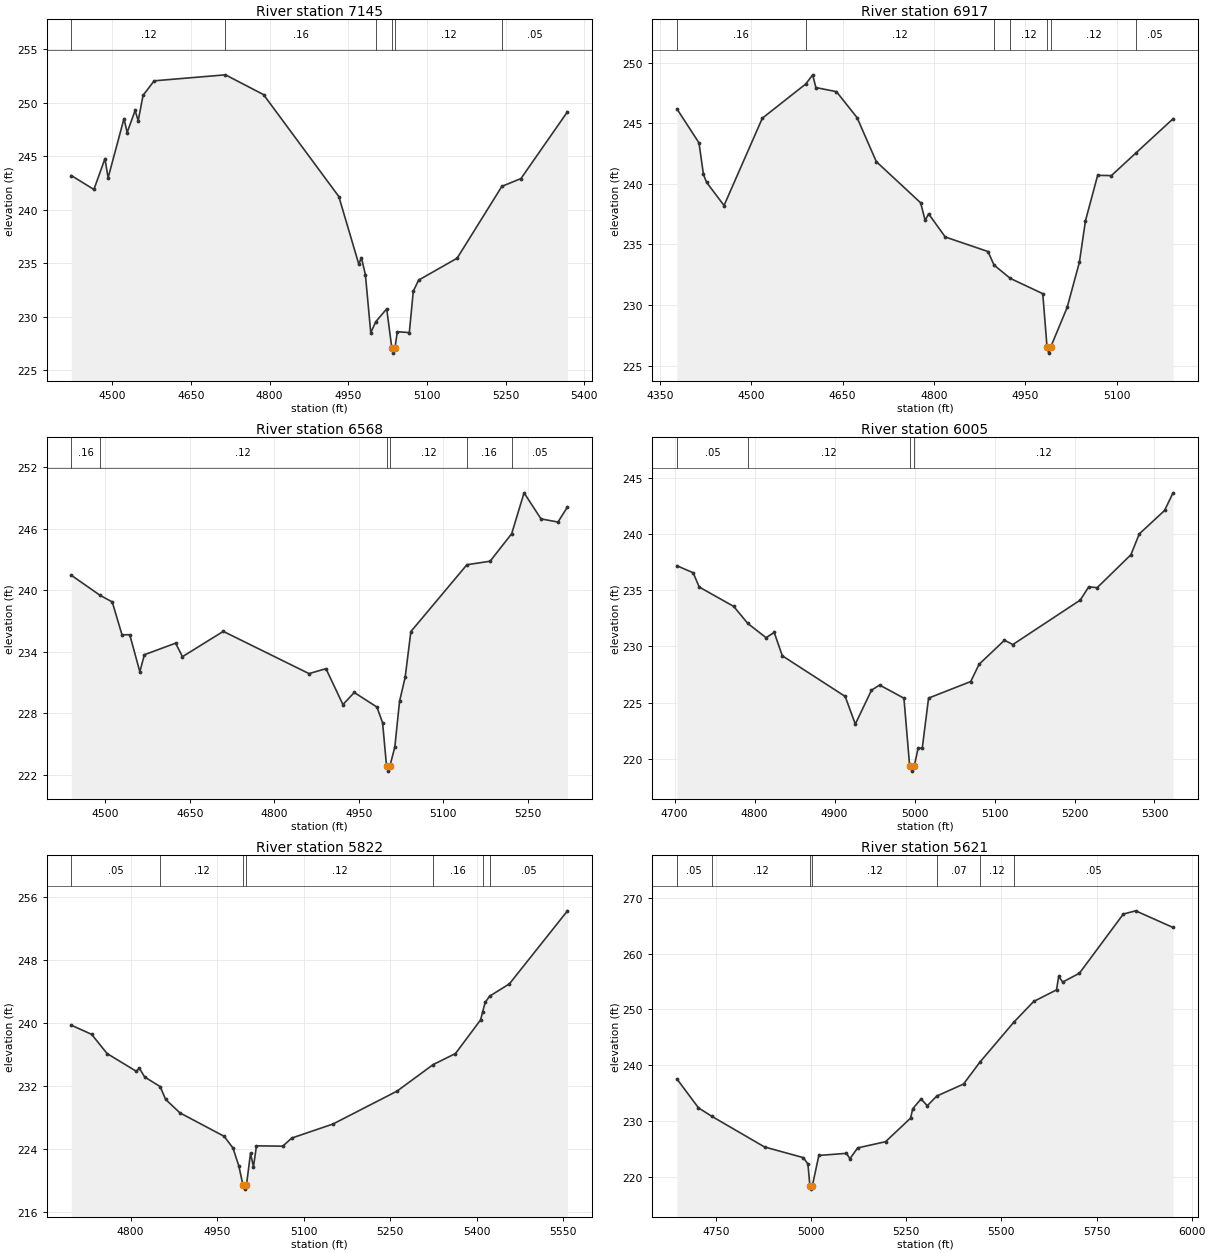
Type RM Length L Ch R = 1,7145,228,228,228
BEGIN DESCRIPTION:
UNT 098 IN BOCR 8.0
END DESCRIPTION:
XS GIS Cut Line= 4
      3739600.56     10562583.24      3739391.65     10562907.92
      3739349.61     10563160.19      3739399.61     10563460.22
#Sta/Elev= 30
  4422.0  243.18  4465.0  241.88  4486.1  244.76  4492.1  242.97  4522.4  248.50
  4528.4  247.20  4543.6  249.26  4549.5  248.30  4558.7  250.67  4579.9  252.03
  4715.9  252.59  4788.5  250.74  4932.0  241.22  4970.1  234.90  4975.1  235.51
  4982.7  233.91  4992.9  228.49  5002.4  229.52  5023.3  230.73  5033.0  227.09
  5035.7  226.59  5039.0  227.09  5043.6  228.59  5066.4  228.51  5074.0  232.37
  5084.1  233.41  5157.6  235.46  5242.9  242.17  5279.3  242.90  5368.0  249.14
#Mann=6,-1,0
  4422.0    0.12       0  4715.9    0.16       0  5002.4    0.12       0
  5033.0    0.07       0  5039.0    0.12       0  5242.9    0.05       0
Bank Sta=5033,5039
Exp/Cntr=0.3,0.1

Type RM Length L Ch R = 1,6917,349,349,349
BEGIN DESCRIPTION:
Mapping XS 67d41b0f
END DESCRIPTION:
XS GIS Cut Line= 3
      3739327.15     10562635.27      3739214.29     10563030.27
      3739201.27     10563433.96
#Sta/Elev= 30
  4378.0  246.20  4414.3  243.39  4421.6  240.78  4426.8  240.13  4455.4  238.22
  4518.3  245.43  4589.7  248.26  4601.0  249.01  4606.2  247.96  4640.0  247.62
  4673.8  245.48  4705.5  241.84  4778.3  238.44  4785.6  236.99  4791.3  237.53
  4818.7  235.62  4888.8  234.42  4898.8  233.30  4925.5  232.20  4978.8  230.94
  4985.8  226.53  4988.6  226.03  4991.8  226.53  5018.8  229.80  5038.9  233.53
  5048.9  236.96  5068.9  240.71  5091.5  240.69  5132.2  242.58  5192.7  245.38
#Mann=7,-1,0
  4378.0    0.16       0  4589.7    0.12       0  4898.8    0.16       0
  4925.5    0.12       0  4985.8    0.07       0  4991.8    0.12       0
  5132.2    0.05       0
Bank Sta=4985.8,4991.8
Exp/Cntr=0.3,0.1

Type RM Length L Ch R = 1,6568,563,563,563
BEGIN DESCRIPTION:
UNT 098 IN BOCR 7.0
END DESCRIPTION:
XS GIS Cut Line= 3
      3739157.88     10562635.27      3739060.30     10562917.22
      3739005.38     10563496.97
#Sta/Elev= 30
  4439.7  241.46  4490.8  239.50  4512.3  238.86  4529.6  235.66  4543.4  235.66
  4561.3  232.05  4569.3  233.71  4624.8  234.84  4636.9  233.52  4709.4  235.99
  4861.6  231.87  4891.7  232.35  4921.8  228.85  4941.9  230.03  4982.1  228.61
  4992.2  227.08  4999.2  222.86  5001.9  222.36  5005.2  222.86  5013.9  224.71
  5022.3  229.17  5032.3  231.52  5042.4  235.97  5141.9  242.49  5183.0  242.83
  5221.3  245.51  5243.3  249.50  5273.4  246.96  5303.5  246.65  5320.4  248.13
#Mann=6,-1,0
  4439.7    0.16       0  4490.8    0.12       0  4999.2    0.07       0
  5005.2    0.12       0  5141.9    0.16       0  5221.3    0.05       0
Bank Sta=4999.2,5005.2
Exp/Cntr=0.3,0.1

Type RM Length L Ch R = 1,6005,183,183,183
BEGIN DESCRIPTION:
UNT 098 IN BOCR 6.0
END DESCRIPTION:
XS GIS Cut Line= 3
      3738699.61     10562660.17      3738649.61     10562960.19
      3738749.61     10563260.20
#Sta/Elev= 30
  4702.8  237.16  4723.1  236.54  4730.7  235.27  4773.8  233.55  4791.5  232.03
  4814.3  230.77  4824.5  231.23  4834.6  229.16  4913.2  225.55  4925.9  223.09
  4946.1  226.10  4956.3  226.56  4986.7  225.39  4993.8  219.41  4996.6  218.91
  4999.8  219.41  5004.4  220.95  5009.6  220.95  5017.5  225.40  5070.2  226.87
  5080.7  228.41  5112.4  230.54  5122.9  230.16  5207.2  234.11  5217.8  235.29
  5228.3  235.21  5270.5  238.14  5281.0  239.99  5312.6  242.07  5323.2  243.64
#Mann=4,-1,0
  4702.8    0.05       0  4791.5    0.12       0  4993.8    0.07       0
  4999.8    0.12       0
Bank Sta=4993.8,4999.8
Exp/Cntr=0.3,0.1

Type RM Length L Ch R = 1,5822,201,201,201
BEGIN DESCRIPTION:
Mapping XS d33b47ad
END DESCRIPTION:
XS GIS Cut Line= 3
      3738432.17     10562615.56      3738557.17     10563235.34
      3738681.27     10563426.66
#Sta/Elev= 30
  4697.2  239.69  4732.5  238.52  4759.1  236.09  4809.9  233.83  4815.0  234.24
  4824.3  233.11  4851.2  231.89  4860.7  230.26  4885.5  228.55  4962.2  225.57
  4977.4  224.09  4987.6  221.81  4994.8  219.36  4997.5  218.86  5000.8  219.36
  5007.9  223.43  5013.0  221.69  5018.2  224.36  5063.8  224.32  5079.4  225.35
  5150.8  227.13  5261.9  231.31  5324.5  234.68  5363.3  236.09  5406.8  240.36
  5410.2  241.32  5414.7  242.58  5422.6  243.38  5456.9  244.95  5557.5  254.22
#Mann=7,-1,0
  4697.2    0.05       0  4851.2    0.12       0  4994.8    0.07       0
  5000.8    0.12       0  5324.5    0.16       0  5410.2    0.07       0
  5422.6    0.05       0
Bank Sta=4994.8,5000.8
Exp/Cntr=0.3,0.1

Type RM Length L Ch R = 1,5621,108,108,108
BEGIN DESCRIPTION:
UNT 098 IN BOCR 5.0
END DESCRIPTION:
XS GIS Cut Line= 3
      3738296.86     10562644.62      3738401.03     10563158.55
      3738768.85     10563845.61
#Sta/Elev= 30
  4647.4  237.57  4704.1  232.39  4738.8  230.89  4877.6  225.39  4979.6  223.48
  4991.7  222.34  4997.0  218.34  4999.7  217.84  5003.0  218.34  5020.4  223.87
  5093.0  224.25  5102.0  223.28  5122.4  225.22  5195.6  226.33  5261.4  230.55
  5267.1  232.23  5289.0  233.99  5305.3  232.77  5330.2  234.50  5400.5  236.65
  5443.8  240.59  5533.2  247.76  5584.8  251.43  5644.9  253.51  5650.6  255.91
  5661.2  254.91  5705.1  256.49  5820.4  267.08  5852.9  267.66  5951.1  264.68
#Mann=7,-1,0
  4647.4    0.05       0  4738.8    0.12       0  4997.0    0.07       0
  5003.0    0.12       0  5330.2    0.07       0  5443.8    0.12       0
  5533.2    0.05       0
Bank Sta=4997,5003
Exp/Cntr=0.3,0.1

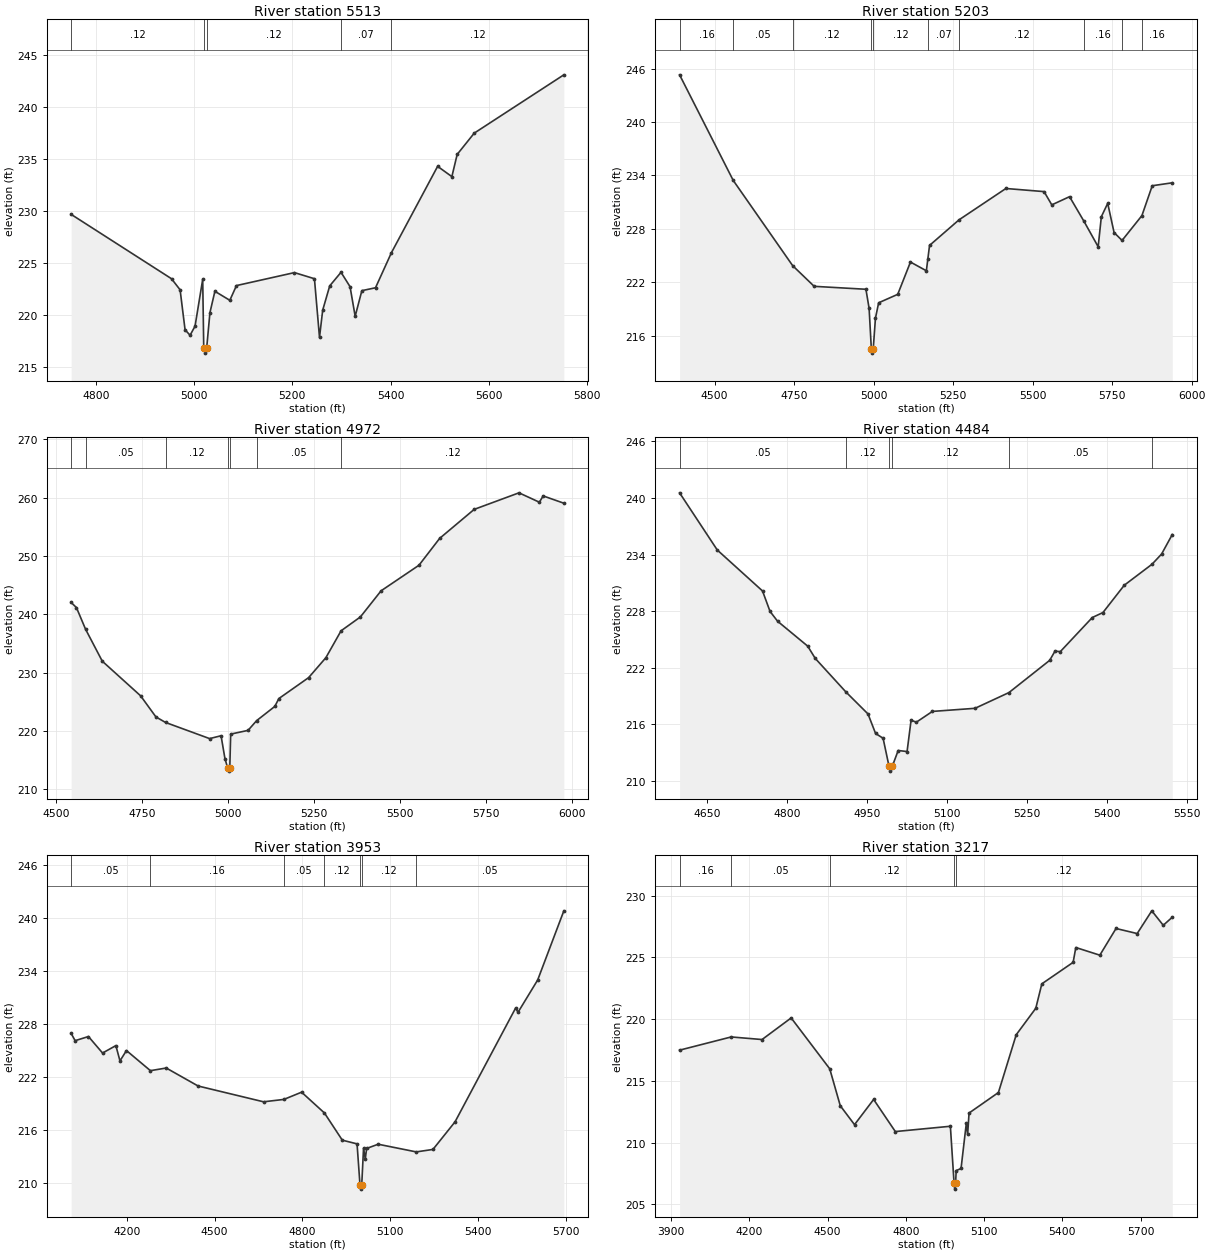
Type RM Length L Ch R = 1,5513,310,310,310
BEGIN DESCRIPTION:
Mapping XS 870132b6
END DESCRIPTION:
XS GIS Cut Line= 3
      3738234.26     10562750.98      3738307.17     10563230.14
      3738442.59     10563730.15
#Sta/Elev= 30
  4749.9  229.68  4954.1  223.48  4971.6  222.41  4981.7  218.56  4991.9  218.03
  5002.0  218.91  5017.6  223.42  5019.7  216.81  5022.4  216.31  5025.7  216.81
  5032.3  220.21  5042.4  222.27  5072.8  221.40  5086.3  222.82  5204.3  224.07
  5245.0  223.48  5255.3  217.83  5261.8  220.45  5276.1  222.79  5299.1  224.10
  5317.5  222.71  5327.9  219.86  5341.5  222.33  5369.3  222.61  5401.8  226.00
  5495.7  234.31  5524.7  233.32  5535.5  235.46  5570.2  237.51  5752.6  243.13
#Mann=5,-1,0
  4749.9    0.12       0  5019.7    0.07       0  5025.7    0.12       0
  5299.1    0.07       0  5401.8    0.12       0
Bank Sta=5019.7,5025.7
Exp/Cntr=0.3,0.1

Type RM Length L Ch R = 1,5203,231,231,231
BEGIN DESCRIPTION:
Mapping XS 57a6e150
END DESCRIPTION:
XS GIS Cut Line= 3
      3738239.46     10562516.63      3738124.88     10563047.84
      3738140.51     10564053.09
#Sta/Elev= 30
  4390.2  245.31  4558.8  233.44  4745.8  223.85  4813.3  221.53  4976.0  221.20
  4986.0  219.06  4993.0  214.52  4995.7  214.02  4999.0  214.52  5006.0  217.96
  5016.0  219.68  5076.0  220.63  5116.0  224.26  5166.0  223.28  5170.7  224.62
  5176.0  226.13  5268.8  229.01  5416.0  232.53  5536.0  232.18  5560.3  230.69
  5616.1  231.61  5661.5  228.84  5706.1  225.98  5716.1  229.36  5736.1  230.86
  5756.1  227.58  5781.2  226.69  5843.6  229.48  5876.1  232.84  5939.0  233.17
#Mann=10,-1,0
  4390.2    0.16       0  4558.8    0.05       0  4745.8    0.12       0
  4993.0    0.07       0  4999.0    0.12       0  5170.7    0.07       0
  5268.8    0.12       0  5661.5    0.16       0  5781.2    0.12       0
  5843.6    0.16       0
Bank Sta=4993,4999
Exp/Cntr=0.3,0.1

Type RM Length L Ch R = 1,4972,488,488,488
BEGIN DESCRIPTION:
UNT 098 IN BOCR 4.0
END DESCRIPTION:
XS GIS Cut Line= 3
      3738130.22     10562589.07      3737831.59     10563193.27
      3737769.09     10563950.22
#Sta/Elev= 30
  4542.9  242.03  4558.2  241.16  4584.7  237.45  4633.4  231.96  4744.9  226.02
  4789.6  222.39  4817.5  221.45  4945.7  218.68  4979.0  219.17  4990.3  215.26
  4998.4  213.60  5001.2  213.10  5004.4  213.60  5007.0  219.45  5057.5  220.09
  5082.5  221.76  5135.4  224.20  5147.2  225.55  5233.8  229.14  5284.0  232.56
  5328.2  237.17  5384.4  239.55  5444.6  244.03  5554.9  248.42  5615.1  253.03
  5715.5  258.00  5845.9  260.84  5905.2  259.23  5916.2  260.31  5976.4  259.06
#Mann=7,-1,0
  4542.9    0.16       0  4584.7    0.05       0  4817.5    0.12       0
  4998.4    0.07       0  5004.4    0.12       0  5082.5    0.05       0
  5328.2    0.12       0
Bank Sta=4998.4,5004.4
Exp/Cntr=0.3,0.1

Type RM Length L Ch R = 1,4484,531,531,531
BEGIN DESCRIPTION:
UNT 098 IN BOCR 3.0
END DESCRIPTION:
XS GIS Cut Line= 3
      3737899.60     10562460.19      3737599.61     10562760.19
      3737599.61     10563260.23
#Sta/Elev= 30
  4598.4  240.55  4669.1  234.48  4754.0  230.13  4768.1  227.96  4782.2  226.92
  4838.8  224.27  4852.9  222.97  4910.2  219.42  4951.9  217.07  4966.1  215.00
  4980.2  214.49  4991.4  211.50  4994.1  211.00  4997.4  211.50  5008.5  213.19
  5025.2  213.08  5032.7  216.40  5042.7  216.20  5072.7  217.34  5152.7  217.67
  5216.3  219.34  5292.7  222.76  5302.7  223.74  5312.7  223.69  5372.7  227.31
  5392.7  227.84  5432.7  230.74  5484.8  232.97  5502.7  234.05  5522.7  236.12
#Mann=6,-1,0
  4598.4    0.05       0  4910.2    0.12       0  4991.4    0.07       0
  4997.4    0.12       0  5216.3    0.05       0  5484.8    0.12       0
Bank Sta=4991.4,4997.4
Exp/Cntr=0.3,0.1

Type RM Length L Ch R = 1,3953,736,736,736
BEGIN DESCRIPTION:
UNT 098 IN BOCR 2.0
END DESCRIPTION:
XS GIS Cut Line= 3
      3737749.61     10561860.19      3737199.61     10562710.19
      3737499.59     10563310.15
#Sta/Elev= 30
  4009.7  226.94  4023.2  226.12  4068.7  226.59  4116.9  224.72  4162.4  225.56
  4176.4  223.83  4198.6  225.00  4280.4  222.72  4334.5  223.02  4443.4  220.98
  4667.0  219.19  4736.4  219.46  4796.9  220.28  4875.0  217.92  4936.0  214.84
  4986.4  214.42  4996.4  209.79  4999.1  209.29  5002.4  209.79  5008.6  213.94
  5014.5  212.70  5019.1  213.90  5058.5  214.38  5188.7  213.51  5245.7  213.79
  5321.2  216.92  5528.0  229.81  5536.4  229.34  5603.5  233.00  5692.9  240.84
#Mann=7,-1,0
  4009.7    0.05       0  4280.4    0.16       0  4736.4    0.05       0
  4875.0    0.12       0  4996.4    0.07       0  5002.4    0.12       0
  5188.7    0.05       0
Bank Sta=4996.4,5002.4
Exp/Cntr=0.3,0.1

Type RM Length L Ch R = 1,3217,736,736,736
BEGIN DESCRIPTION:
Mapping XS ae3582d1
END DESCRIPTION:
XS GIS Cut Line= 3
      3737348.84     10562115.54      3736953.01     10562933.26
      3737161.34     10563891.59
#Sta/Elev= 30
  3932.4  217.49  4130.3  218.56  4248.6  218.35  4360.3  220.10  4508.2  215.98
  4548.6  212.99  4603.2  211.46  4676.5  213.50  4759.7  210.90  4970.8  211.33
  4984.9  206.74  4987.6  206.24  4990.9  206.74  4993.0  207.74  5011.7  207.91
  5031.9  211.57  5037.0  210.67  5042.4  212.40  5155.0  214.06  5223.3  218.74
  5298.3  220.88  5321.5  222.86  5441.5  224.60  5451.8  225.80  5543.9  225.18
  5606.0  227.34  5687.1  226.93  5743.1  228.77  5787.1  227.60  5821.6  228.25
#Mann=5,-1,0
  3932.4    0.16       0  4130.3    0.05       0  4508.2    0.12       0
  4984.9    0.07       0  4990.9    0.12       0
Bank Sta=4984.9,4990.9
Exp/Cntr=0.3,0.1

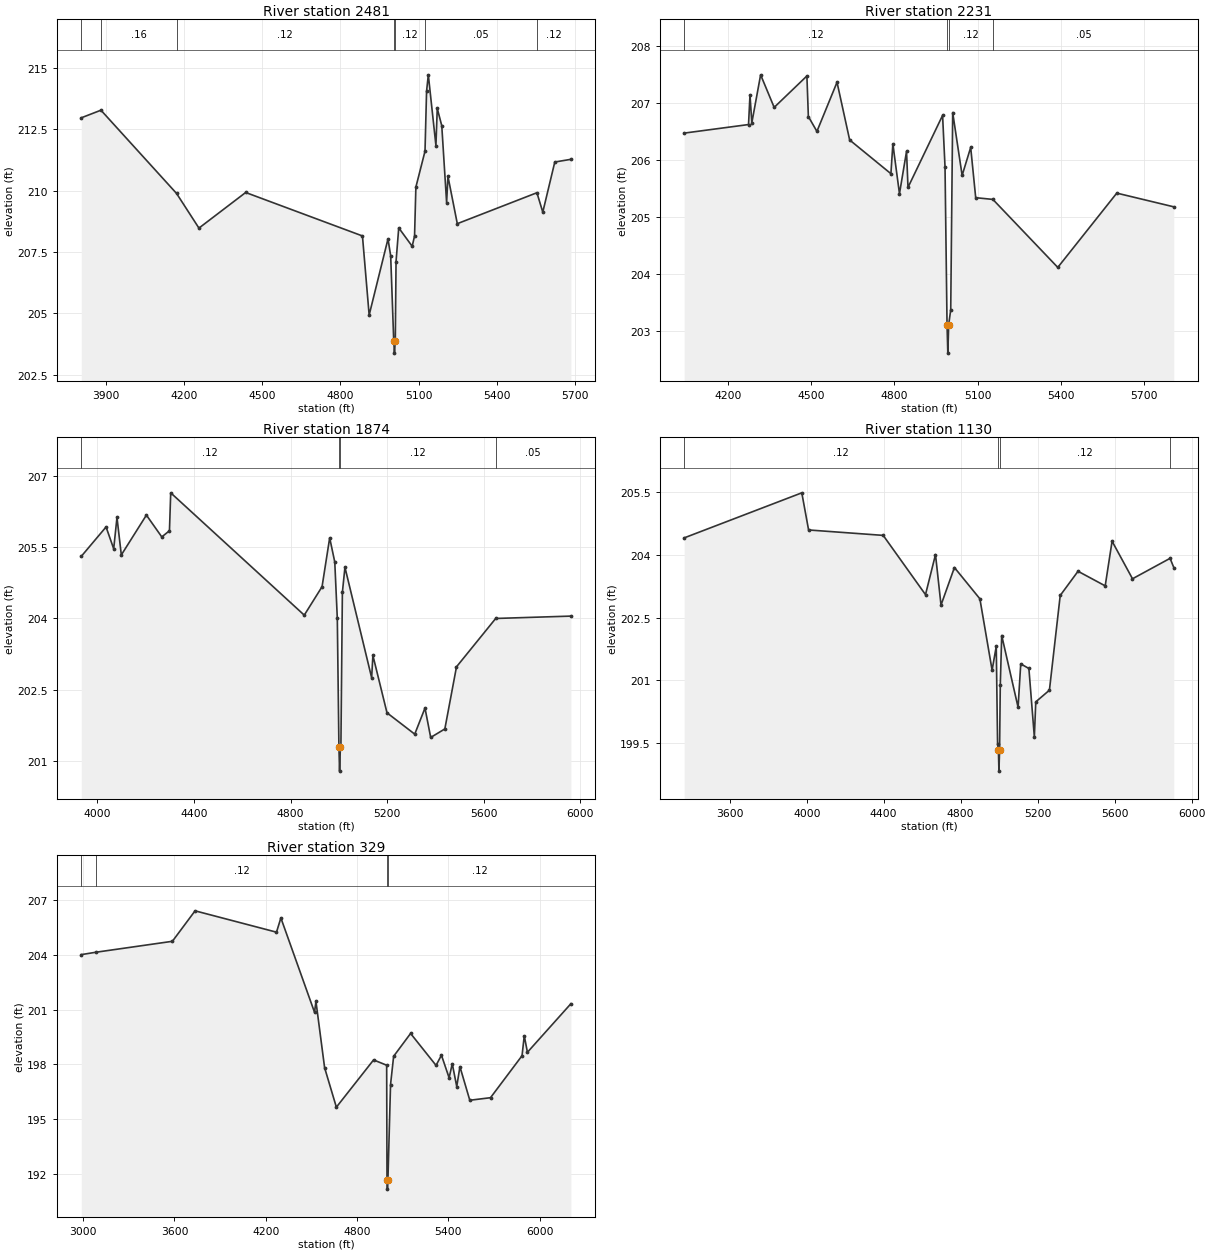
Type RM Length L Ch R = 1,2481,250,250,250
BEGIN DESCRIPTION:
Mapping XS d6d943d2
END DESCRIPTION:
XS GIS Cut Line= 3
      3737093.62     10562214.54      3736697.80     10563188.47
      3736900.92     10563990.55
#Sta/Elev= 30
  3805.6  212.96  3881.1  213.27  4171.3  209.88  4257.1  208.47  4436.4  209.92
  4884.5  208.15  4910.2  204.93  4982.5  208.03  4992.8  207.34  5004.5  203.88
  5007.3  203.38  5010.5  203.88  5013.4  207.11  5023.7  208.48  5075.3  207.73
  5084.4  208.15  5089.5  210.14  5124.5  211.60  5130.5  214.04  5137.2  214.71
  5166.4  211.83  5171.5  213.34  5188.8  212.64  5207.4  209.51  5212.5  210.58
  5248.4  208.65  5553.9  209.91  5576.4  209.12  5622.5  211.16  5684.3  211.27
#Mann=7,-1,0
  3805.6    0.05       0  3881.1    0.16       0  4171.3    0.12       0
  5004.5    0.07       0  5010.5    0.12       0  5124.5    0.05       0
  5553.9    0.12       0
Bank Sta=5004.5,5010.5
Exp/Cntr=0.3,0.1

Type RM Length L Ch R = 1,2231,357,357,357
BEGIN DESCRIPTION:
Mapping XS e75b5c6c
END DESCRIPTION:
XS GIS Cut Line= 3
      3736803.69     10562349.94      3736517.24     10563157.22
      3736734.25     10564042.62
#Sta/Elev= 30
  4040.6  206.47  4273.0  206.62  4278.3  207.14  4284.9  206.65  4316.7  207.49
  4365.6  206.92  4483.8  207.47  4489.1  206.76  4520.0  206.50  4592.6  207.36
  4638.2  206.35  4787.2  205.76  4794.2  206.28  4818.1  205.41  4843.6  206.15
  4848.9  205.52  4973.8  206.78  4982.6  205.88  4989.9  203.12  4992.7  202.62
  4995.9  203.12  5003.2  203.38  5010.3  206.83  5044.4  205.73  5075.3  206.22
  5093.4  205.34  5155.4  205.31  5389.8  204.12  5602.9  205.42  5808.8  205.18
#Mann=4,-1,0
  4040.6    0.12       0  4989.9    0.07       0  4995.9    0.12       0
  5155.4    0.05       0
Bank Sta=4989.9,4995.9
Exp/Cntr=0.3,0.1

Type RM Length L Ch R = 1,1874,744,744,744
BEGIN DESCRIPTION:
Mapping XS cc67ec18
END DESCRIPTION:
XS GIS Cut Line= 3
      3736630.08     10562332.60      3736230.78     10563547.84
      3736630.11     10564181.56
#Sta/Elev= 30
  3933.1  205.31  4035.8  205.93  4067.4  205.47  4081.0  206.13  4099.0  205.34
  4202.9  206.18  4266.6  205.72  4298.4  205.85  4303.6  206.65  4856.8  204.07
  4930.5  204.67  4962.1  205.70  4983.2  205.19  4993.7  204.00  5000.4  201.28
  5003.1  200.78  5006.4  201.28  5008.6  201.32  5014.7  204.55  5025.3  205.08
  5135.9  202.75  5141.1  203.22  5199.5  202.01  5314.4  201.56  5356.9  202.11
  5380.5  201.49  5439.1  201.67  5487.4  202.98  5649.8  204.00  5961.3  204.05
#Mann=4,-1,0
  3933.1    0.12       0  5000.4    0.07       0  5006.4    0.12       0
  5649.8    0.05       0
Bank Sta=5000.4,5006.4
Exp/Cntr=0.3,0.1

Type RM Length L Ch R = 1,1130,801,801,801
BEGIN DESCRIPTION:
Mapping XS f240a8fb
END DESCRIPTION:
XS GIS Cut Line= 3
      3736517.25     10562202.35      3735892.24     10563599.93
      3736577.42     10564345.82
#Sta/Elev= 30
  3363.5  204.41  3974.6  205.49  4009.9  204.60  4397.5  204.47  4617.3  203.05
  4669.2  204.01  4697.9  202.80  4767.5  203.70  4899.8  202.95  4963.3  201.24
  4984.9  201.81  4991.7  199.48  4996.1  199.32  4998.8  198.82  5002.1  199.32
  5005.8  200.88  5013.2  202.07  5098.3  200.35  5112.1  201.39  5154.4  201.28
  5182.8  199.64  5190.2  200.48  5261.1  200.76  5317.2  203.03  5409.7  203.61
  5550.9  203.26  5586.6  204.33  5692.7  203.43  5887.9  203.92  5907.3  203.70
#Mann=4,-1,0
  3363.5    0.12       0  4996.1    0.07       0  5002.1    0.12       0
  5887.9    0.05       0
Bank Sta=4996.1,5002.1
Exp/Cntr=0.3,0.1

Type RM Length L Ch R = 1,329,0,0,0
BEGIN DESCRIPTION:
UNT 098 IN BOCR 1.0
END DESCRIPTION:
XS GIS Cut Line= 4
      3736319.56     10562001.88      3735498.32     10563582.60
      3735562.38     10563974.93      3736402.45     10564585.40
#Sta/Elev= 30
  2987.7  204.01  3083.3  204.14  3586.4  204.74  3735.5  206.41  4270.5  205.24
  4299.3  206.02  4520.4  200.85  4529.7  201.45  4586.7  197.81  4663.9  195.65
  4908.4  198.24  4994.4  197.95  4996.6  191.66  4999.4  191.16  5002.6  191.66
  5019.9  196.89  5040.2  198.44  5151.6  199.69  5318.9  197.94  5354.4  198.50
  5404.7  197.26  5425.5  198.03  5454.9  196.78  5475.8  197.87  5540.7  196.03
  5676.7  196.17  5883.9  198.47  5898.5  199.56  5919.4  198.66  6205.0  201.32
#Mann=4,-1,0
  2987.7    0.05       0  3083.3    0.12       0  4996.6    0.07       0
  5002.6    0.12       0
Bank Sta=4996.6,5002.6
Exp/Cntr=0.3,0.1

Chan Stop Cuts=-1