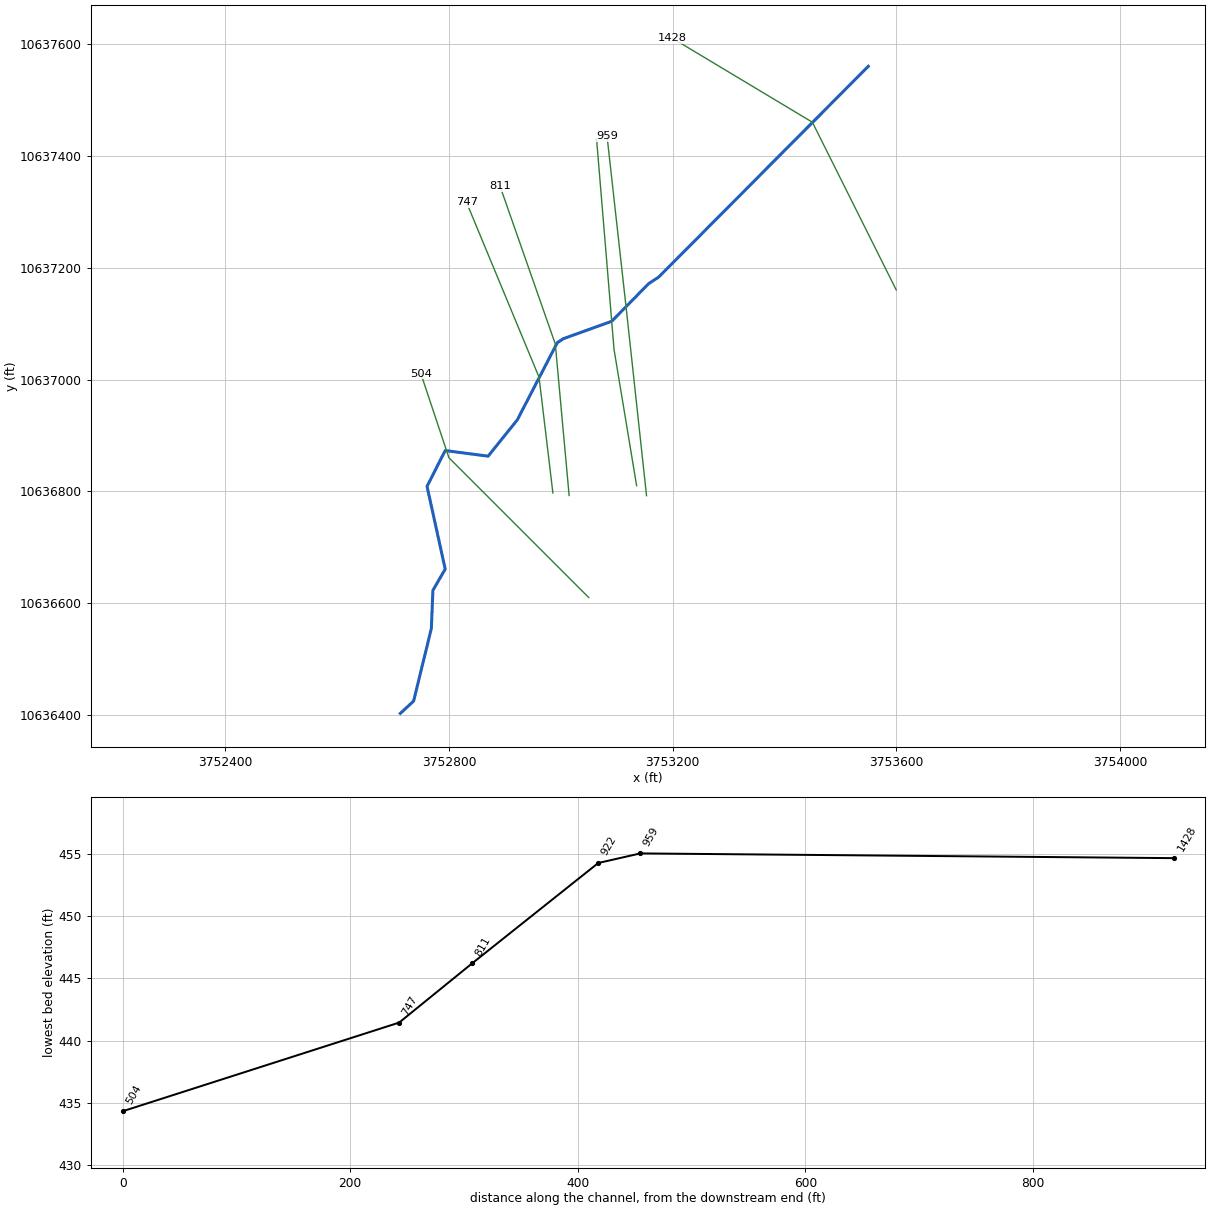
--- UNT 101 IN BOCR.prj (project) ---

Proj Title=UNT 101 IN BOCR Base Level Engineering
Current Plan=p01
Default Exp/Contr=0.3,0.1
English Units
Geom File=g01
Flow File=f01
Plan File=p01
BEGIN DESCRIPTION:
UNT 101 IN BOCR
END DESCRIPTION:

--- UNT 101 IN BOCR.p01 (plan) ---

Plan Title=Multiple Run
Short Identifier=Multiple
Geom File=g01
Flow File=f01
Subcritical Flow
K Sum by GR= 0
Std Step Tol= 0.01
Critical Tol= 0.01
Num of Std Step Trials= 20
Max Error Tol= 0.3
Flow Tol Ratio= 0.001
Split Flow NTrial= 30
Split Flow Tol= 0.02
Split Flow Ratio= 0.02
Log Output Level= 0
Friction Slope Method= 1
Unsteady Friction Slope Method= 2
Unsteady Bridges Friction Slope Method= 1
Parabolic Critical Depth
Global Vel Dist=  1 , 1 , 1
Global Log Level= 0
CheckData=True
Encroach Param= -1, 0, 0, 0
BEGIN DESCRIPTION:
Multiple Run
END DESCRIPTION:

--- UNT 101 IN BOCR.f01 (steady flow) ---

Flow Title=Multiple
Number of Profiles=7
Profile Names=10-year,25-year,50-year,1pct_min,100-year,1pct_plu,500-year
River Rch & RM= UNT 101 IN BOCR,Reach-1,1428
     227     292     343     298     404     546     558
Boundary for River Rch & Prof#=UNT 101 IN BOCR,Reach-1,1
Up Type=0
Dn Type=3
Dn Slope=0.005
Boundary for River Rch & Prof#=UNT 101 IN BOCR,Reach-1,2
Up Type=0
Dn Type=3
Dn Slope=0.005
Boundary for River Rch & Prof#=UNT 101 IN BOCR,Reach-1,3
Up Type=0
Dn Type=3
Dn Slope=0.005
Boundary for River Rch & Prof#=UNT 101 IN BOCR,Reach-1,4
Up Type=0
Dn Type=3
Dn Slope=0.005
Boundary for River Rch & Prof#=UNT 101 IN BOCR,Reach-1,5
Up Type=0
Dn Type=3
Dn Slope=0.005
Boundary for River Rch & Prof#=UNT 101 IN BOCR,Reach-1,6
Up Type=0
Dn Type=3
Dn Slope=0.005
Boundary for River Rch & Prof#=UNT 101 IN BOCR,Reach-1,7
Up Type=0
Dn Type=3
Dn Slope=0.005

--- UNT 101 IN BOCR.g01 (geometry) ---

Geom Title=Existing Conditions

River Reach=UNT 101 IN BOCR,Reach-1
Reach XY= 15
      3753549.61     10637560.19      3753174.50     10637183.00
      3753156.99     10637171.68      3753090.74     10637104.19
      3753004.61     10637073.18      3752993.50     10637066.00
      3752922.00     10636928.00      3752869.75     10636863.00
      3752793.00     10636873.00      3752760.50     10636809.00
      3752793.00     10636661.00      3752771.00     10636623.00
      3752768.25     10636555.00      3752736.50     10636425.00
      3752712.75     10636403.00

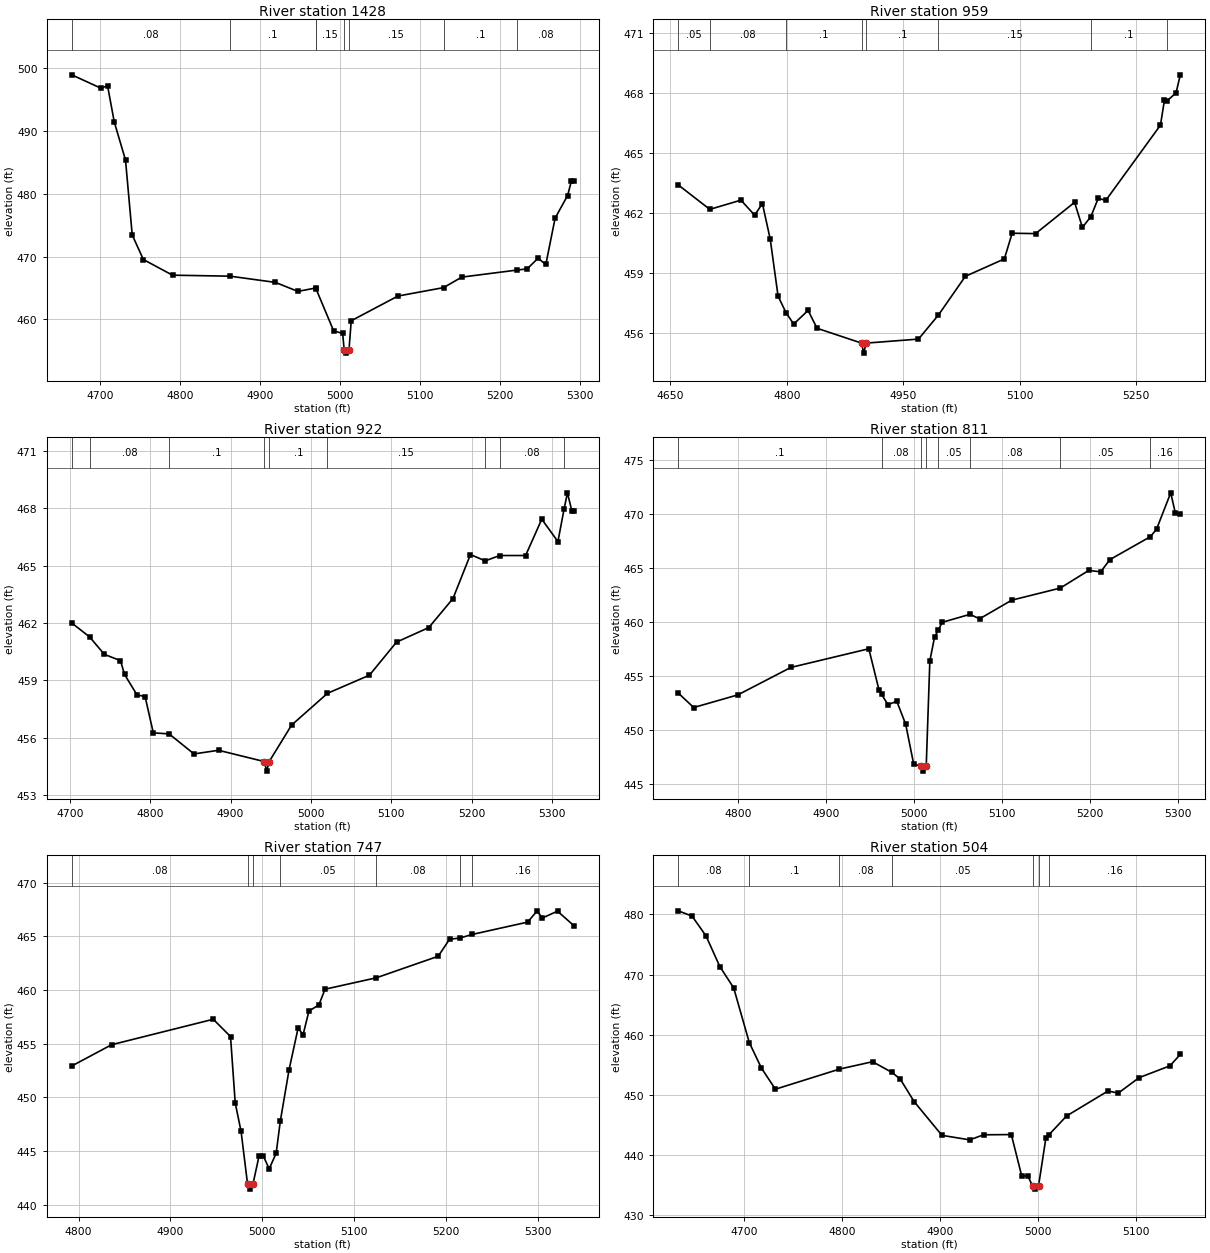
Type RM Length L Ch R = 1,1428,469,469,469
BEGIN DESCRIPTION:
UNT 101 IN BOCR 3.0
END DESCRIPTION:
XS GIS Cut Line= 3
      3753599.61     10637160.19      3753449.61     10637460.19
      3753199.57     10637610.21
#Sta/Elev= 30
  4665.0  498.91  4701.3  496.79  4709.7  497.17  4718.1  491.39  4732.1  485.36
  4740.5  473.43  4754.4  469.53  4790.8  467.04  4862.7  466.88  4919.4  465.89
  4947.3  464.46  4969.6  465.00  4970.1  464.85  4992.0  458.19  5003.3  457.77
  5005.2  455.14  5007.9  454.64  5011.2  455.14  5014.0  459.79  5072.3  463.72
  5129.3  465.06  5152.0  466.73  5221.4  467.86  5233.7  468.04  5247.3  469.74
  5257.0  468.74  5268.6  476.11  5284.2  479.71  5289.0  482.05  5292.0  482.05
#Mann=8,-1,0
  4665.0    0.08       0  4862.7     0.1       0  4969.6    0.08       0
  4970.1    0.15       0  5005.2    0.07       0  5011.2    0.15       0
  5129.3     0.1       0  5221.4    0.08       0
Bank Sta=5005.2,5011.2
Exp/Cntr=0.3,0.1

Type RM Length L Ch R = 1,959,37,37,37
BEGIN DESCRIPTION:
UNT 101 IN BOCR 2.0
END DESCRIPTION:
XS GIS Cut Line= 3
      3753153.03     10636792.28      3753117.68     10637118.56
      3753082.36     10637435.61
#Sta/Elev= 30
  4660.0  463.41  4700.7  462.19  4740.8  462.65  4758.5  461.90  4768.5  462.48
  4778.6  460.70  4788.7  457.86  4798.9  457.04  4808.8  456.47  4827.4  457.15
  4838.9  456.26  4896.3  455.52  4899.0  455.02  4902.3  455.52  4969.7  455.72
  4995.4  456.92  5030.1  458.85  5080.4  459.72  5090.4  461.00  5120.6  460.98
  5170.9  462.54  5181.0  461.29  5191.9  461.83  5201.4  462.74  5211.2  462.64
  5281.6  466.39  5286.8  467.65  5290.1  467.60  5301.7  468.00  5307.2  468.90
#Mann=8,-1,0
  4660.0    0.05       0  4700.7    0.08       0  4798.9     0.1       0
  4896.3    0.07       0  4902.3     0.1       0  4995.4    0.15       0
  5191.9     0.1       0  5290.1    0.05       0
Bank Sta=4896.3,4902.3
Exp/Cntr=0.3,0.1

Type RM Length L Ch R = 1,922,111,111,111
BEGIN DESCRIPTION:
Mapping XS daa56492
END DESCRIPTION:
XS GIS Cut Line= 3
      3753135.30     10636810.19      3753094.94     10637053.69
      3753063.69     10637429.97
#Sta/Elev= 30
  4702.5  462.00  4724.7  461.27  4743.0  460.36  4763.1  460.03  4768.1  459.31
  4783.6  458.24  4793.7  458.15  4803.9  456.25  4823.5  456.20  4854.5  455.15
  4885.0  455.34  4942.0  454.75  4944.8  454.25  4948.0  454.75  4975.9  456.66
  5020.5  458.32  5072.7  459.27  5106.4  461.00  5146.5  461.76  5176.6  463.28
  5198.3  465.58  5216.7  465.25  5234.7  465.53  5266.9  465.53  5287.0  467.43
  5307.1  466.26  5314.8  467.97  5318.9  468.81  5324.5  467.85  5326.9  467.85
#Mann=9,-1,0
  4702.5    0.05       0  4724.7    0.08       0  4823.5     0.1       0
  4942.0    0.07       0  4948.0     0.1       0  5020.5    0.15       0
  5216.7     0.1       0  5234.7    0.08       0  5314.8    0.05       0
Bank Sta=4942,4948
Exp/Cntr=0.3,0.1

Type RM Length L Ch R = 1,811,64,64,64
BEGIN DESCRIPTION:
Mapping XS f8fac51f
END DESCRIPTION:
XS GIS Cut Line= 3
      3753014.62     10636792.70      3752989.87     10637063.58
      3752891.08     10637345.67
#Sta/Elev= 30
  4731.9  453.42  4749.5  452.08  4799.7  453.25  4859.9  455.79  4948.6  457.52
  4960.3  453.67  4963.1  453.30  4970.4  452.34  4980.4  452.66  4990.5  450.54
  4999.7  446.81  5007.9  446.69  5010.7  446.19  5013.9  446.69  5018.0  456.40
  5023.3  458.58  5027.5  459.24  5032.1  459.97  5063.7  460.71  5074.5  460.29
  5111.1  462.02  5166.3  463.14  5198.8  464.78  5212.2  464.64  5222.8  465.78
  5268.8  467.90  5275.8  468.60  5291.9  471.96  5297.2  470.07  5302.8  469.97
#Mann=8,-1,0
  4731.9     0.1       0  4963.1    0.08       0  5007.9    0.07       0
  5013.9    0.08       0  5027.5    0.05       0  5063.7    0.08       0
  5166.3    0.05       0  5268.8    0.16       0
Bank Sta=5007.9,5013.9
Exp/Cntr=0.3,0.1

Type RM Length L Ch R = 1,747,243,243,243
BEGIN DESCRIPTION:
Mapping XS db8a0b56
END DESCRIPTION:
XS GIS Cut Line= 3
      3752985.57     10636797.13      3752960.82     10637004.21
      3752831.19     10637316.63
#Sta/Elev= 30
  4792.5  452.92  4835.9  454.90  4946.6  457.27  4965.4  455.66  4970.5  449.48
  4976.9  446.82  4983.9  441.95  4986.7  441.45  4989.9  441.95  4996.5  444.55
  5001.0  444.55  5007.5  443.34  5015.1  444.79  5019.6  447.78  5029.2  452.59
  5039.0  456.45  5044.4  455.83  5050.8  458.03  5061.7  458.62  5068.3  460.07
  5124.1  461.13  5191.6  463.14  5203.9  464.72  5215.4  464.84  5228.6  465.17
  5289.0  466.32  5299.4  467.37  5304.8  466.69  5321.5  467.34  5339.3  465.99
#Mann=7,-1,0
  4792.5    0.08       0  4983.9    0.07       0  4989.9    0.08       0
  5019.6    0.05       0  5124.1    0.08       0  5215.4    0.05       0
  5228.6    0.16       0
Bank Sta=4983.9,4989.9
Exp/Cntr=0.3,0.1

Type RM Length L Ch R = 1,504,0,0,0
BEGIN DESCRIPTION:
UNT 101 IN BOCR 1.0
END DESCRIPTION:
XS GIS Cut Line= 3
      3753049.59     10636610.20      3752799.61     10636860.19
      3752749.62     10637010.15
#Sta/Elev= 30
  4633.3  480.60  4647.4  479.72  4661.6  476.43  4675.7  471.33  4689.8  467.79
  4705.7  458.70  4718.1  454.45  4732.3  450.95  4797.6  454.29  4831.3  455.52
  4851.2  453.73  4859.6  452.61  4873.7  448.88  4902.0  443.28  4930.3  442.53
  4944.4  443.37  4972.7  443.41  4983.3  436.54  4989.5  436.54  4994.4  434.84
  4997.1  434.34  5000.4  434.84  5007.9  442.81  5010.9  443.35  5029.0  446.50
  5071.2  450.65  5081.7  450.30  5102.8  452.86  5134.4  454.84  5144.9  456.74
#Mann=7,-1,0
  4633.3    0.08       0  4705.7     0.1       0  4797.6    0.08       0
  4851.2    0.05       0  4994.4    0.04       0  5000.4    0.05       0
  5010.9    0.16       0
Bank Sta=4994.4,5000.4
Exp/Cntr=0.3,0.1

Chan Stop Cuts=-1