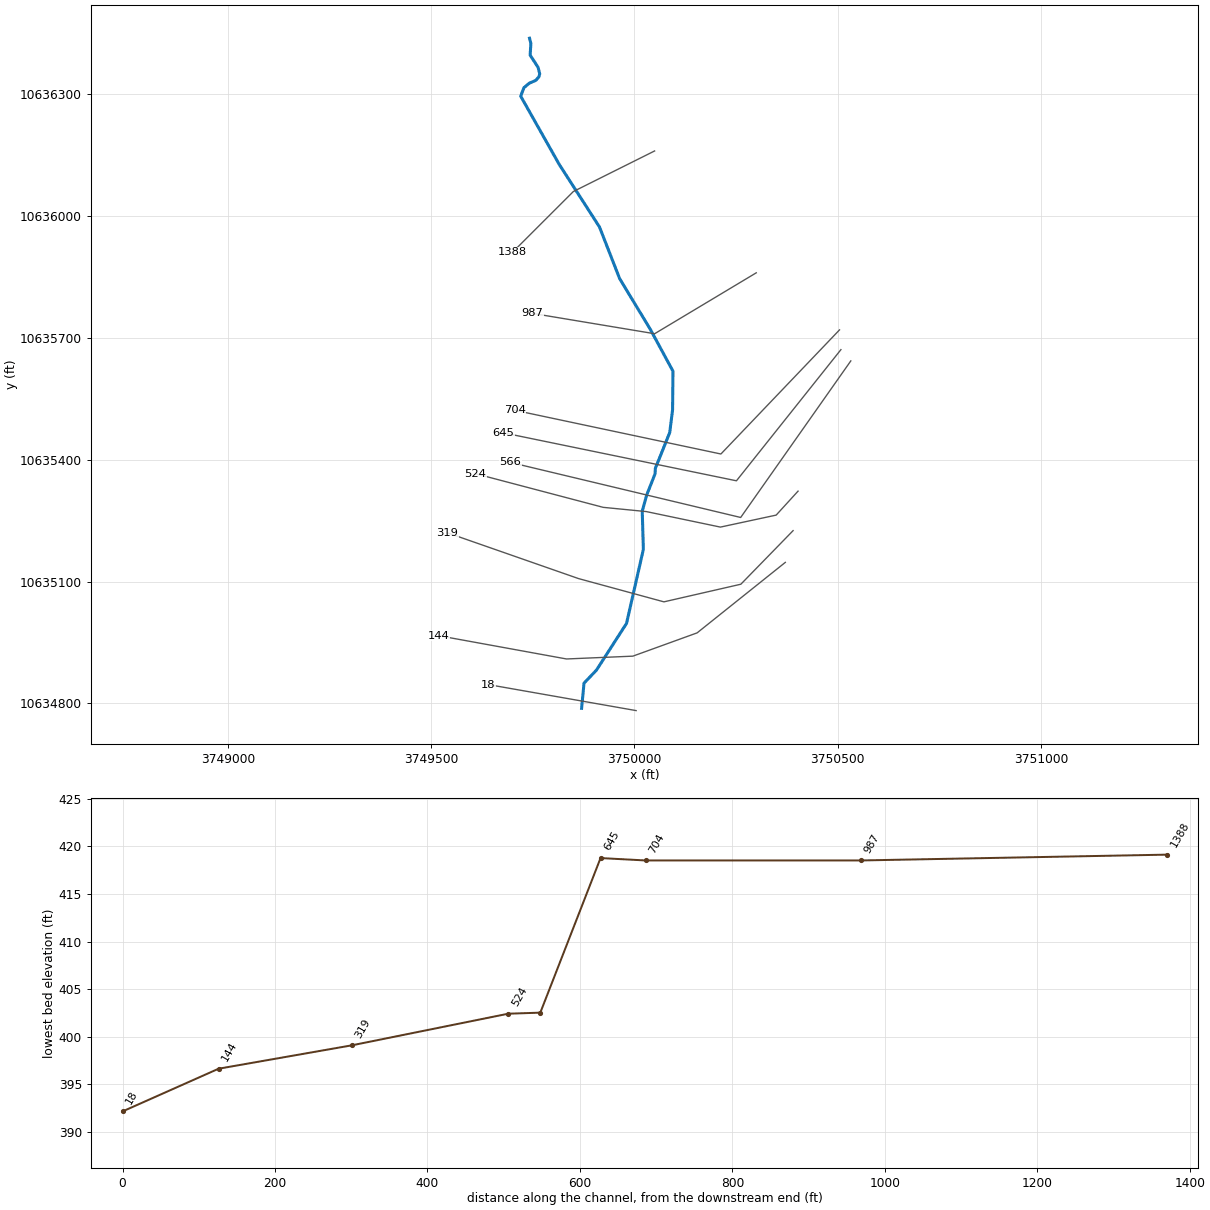
--- UNT 102 IN BOCR.prj (project) ---

Proj Title=UNT 102 IN BOCR Base Level Engineering
Current Plan=p01
Default Exp/Contr=0.3,0.1
English Units
Geom File=g01
Flow File=f01
Plan File=p01
Y Axis Title=Elevation
X Axis Title(PF)=Main Channel Distance
X Axis Title(XS)=Station
BEGIN DESCRIPTION:
UNT 102 IN BOCR
END DESCRIPTION:
DSS Export Rating Curves= 0
DSS Export Rating Curve Sorted= 0
DSS Export Volume Flow Curves= 0
DXF OffsetX= 0
DXF OffsetY= 0
DXF ScaleX= 1
DXF ScaleY= 10

--- UNT 102 IN BOCR.p01 (plan) ---

Plan Title=Multiple Run
Short Identifier=Multiple
Geom File=g01
Flow File=f01
Subcritical Flow
K Sum by GR= 0
Std Step Tol= 0.01
Critical Tol= 0.01
Num of Std Step Trials= 20
Max Error Tol= 0.3
Flow Tol Ratio= 0.001
Split Flow NTrial= 30
Split Flow Tol= 0.02
Split Flow Ratio= 0.02
Log Output Level= 0
Friction Slope Method= 1
Unsteady Friction Slope Method= 2
Unsteady Bridges Friction Slope Method= 1
Parabolic Critical Depth
Global Vel Dist=  1 , 1 , 1
Global Log Level= 0
CheckData=True
Encroach Param= -1, 0, 0, 0
BEGIN DESCRIPTION:
Multiple Run
END DESCRIPTION:

--- UNT 102 IN BOCR.f01 (steady flow) ---

Flow Title=Multiple
Program Version=4.10
Number of Profiles= 7
Profile Names=10-year,25-year,50-year,1pct_min,100-year,1pct_plu,500-year
River Rch & RM=UNT 102 IN BOCR,Reach-1         ,1388
     300     392     467     410     555     751     785
Boundary for River Rch & Prof#=UNT 102 IN BOCR,Reach-1         , 1
Up Type= 0
Dn Type= 3
Dn Slope=0.005
Boundary for River Rch & Prof#=UNT 102 IN BOCR,Reach-1         , 2
Up Type= 0
Dn Type= 3
Dn Slope=0.005
Boundary for River Rch & Prof#=UNT 102 IN BOCR,Reach-1         , 3
Up Type= 0
Dn Type= 3
Dn Slope=0.005
Boundary for River Rch & Prof#=UNT 102 IN BOCR,Reach-1         , 4
Up Type= 0
Dn Type= 3
Dn Slope=0.005
Boundary for River Rch & Prof#=UNT 102 IN BOCR,Reach-1         , 5
Up Type= 0
Dn Type= 3
Dn Slope=0.005
Boundary for River Rch & Prof#=UNT 102 IN BOCR,Reach-1         , 6
Up Type= 0
Dn Type= 3
Dn Slope=0.005
Boundary for River Rch & Prof#=UNT 102 IN BOCR,Reach-1         , 7
Up Type= 0
Dn Type= 3
Dn Slope=0.005
DSS Import GetInterval= 0
DSS Import GetPeak= 0
DSS Import FillOption= 0

--- UNT 102 IN BOCR.g01 (geometry) ---

Geom Title=Existing Conditions
Program Version=4.10

River Reach=UNT 102 IN BOCR ,Reach-1
Reach XY= 26
      3749741.96     10636437.73      3749745.25       10636425.
       3749743.5       10636396.        3749763.       10636366.
        3749767.       10636350.      3749765.25       10636343.
       3749757.5       10636334.       3749741.5       10636327.
      3749728.25       10636316.      3749720.25       10636295.
        3749815.       10636127.        3749914.       10635973.
       3749963.5       10635846.        3750039.       10635721.
      3750094.75       10635618.      3750093.75       10635523.
      3750086.75       10635467.       3750051.5       10635379.
      3750050.61     10635365.19      3750030.15     10635313.14
      3750019.15     10635273.33      3750021.91     10635179.29
       3749980.5       10634997.       3749906.5       10634882.
        3749876.       10634850.        3749870.       10634788.

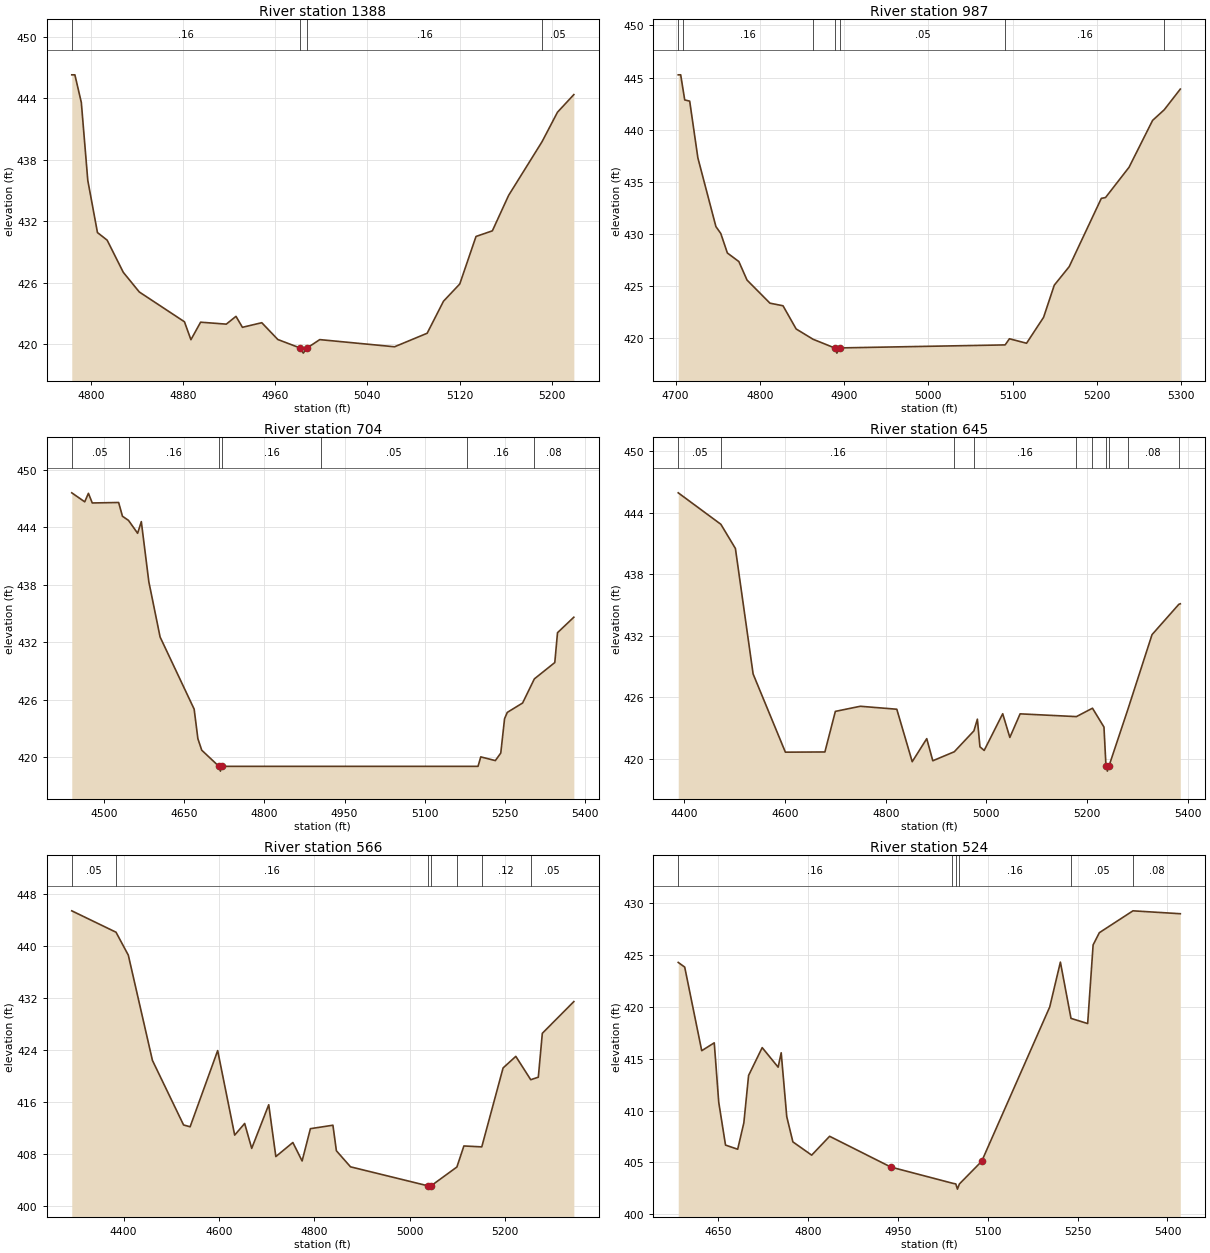
Type RM Length L Ch R = 1 ,1388    ,401,401,401
BEGIN DESCRIPTION:
UNT 102 IN BOCR 3.0
END DESCRIPTION:
XS GIS Cut Line= 3
      3750049.56     10636160.17      3749849.61     10636060.19
       3749699.6     10635910.18
#Sta/Elev= 30
  4783.5   446.3  4786.2   446.3  4791.8   443.6  4797.4     436  4805.8   430.9
  4814.2  430.16  4828.2  427.02  4842.1   425.1  4881.3  422.19  4886.9  420.44
  4895.3  422.15  4917.6  421.96    4926  422.72  4931.6  421.65  4948.4   422.1
  4962.3  420.46  4981.7  419.63  4984.4  419.13  4987.7  419.63  4998.7  420.45
  5063.6  419.75  5091.9  421.07  5106.1   424.2  5120.2  425.88  5134.3  430.52
  5148.5  431.07  5162.6  434.53  5191.6  439.77    5205  442.65  5219.2  444.37
#Mann= 4 ,-1 , 0
  4783.5     .16       0  4981.7     .07       0  4987.7     .16       0
  5191.6     .05       0
Bank Sta=4981.7,4987.7
XS Rating Curve= 0 ,0
Exp/Cntr=0.3,0.1

Type RM Length L Ch R = 1 ,987     ,283,283,283
BEGIN DESCRIPTION:
UNT 102 IN BOCR 2.0
END DESCRIPTION:
XS GIS Cut Line= 3
      3750299.57     10635860.16      3750049.61     10635710.19
      3749749.65     10635760.18
#Sta/Elev= 30
  4703.2  445.26  4706.1  445.26  4708.7  443.95  4710.9  442.85  4716.8  442.73
  4726.5  437.28  4747.9  430.68  4753.7  430.01  4761.5  428.14  4775.1  427.32
  4784.8  425.54    4812  423.32  4827.5  423.07  4843.1  420.84  4863.2  419.85
  4888.7  419.02  4891.4  418.52  4894.7  419.02    5091  419.31  5096.1   419.9
  5116.4  419.47  5136.6  421.96  5149.3  425.05    5167  426.83  5205.1  433.39
  5210.1  433.47    5238  436.38  5265.9  440.88  5279.7   441.9  5298.8  443.89
#Mann= 7 ,-1 , 0
  4703.2     .05       0  4708.7     .16       0  4863.2     .05       0
  4888.7    .033       0  4894.7     .05       0    5091     .16       0
  5279.7     .05       0
Bank Sta=4888.7,4894.7
XS Rating Curve= 0 ,0
Exp/Cntr=0.3,0.1

Type RM Length L Ch R = 1 ,704     ,59,59,59
BEGIN DESCRIPTION:
Mapping XS bf5131c5
END DESCRIPTION:
XS GIS Cut Line= 3
      3750504.31     10635719.67      3750212.63      10635414.1
      3749705.67     10635521.74
#Sta/Elev= 30
    4439  447.61  4463.3  446.67  4470.2  447.56  4477.4  446.55  4526.8   446.6
    4534  445.16  4545.3  444.73  4562.4  443.38  4569.3   444.6  4583.4  438.31
  4604.5  432.54  4668.3     425  4675.3  421.91  4682.5  420.71  4714.7  419.02
  4717.5  418.52  4720.7  419.02  4905.6  419.02  5179.3  419.02  5200.2  419.02
  5205.3  420.01  5232.6  419.62  5242.8  420.41  5249.9     424    5255  424.66
  5283.7  425.64  5305.7  428.16    5344  429.87  5349.1  432.99  5379.7  434.61
#Mann= 7 ,-1 , 0
    4439     .05       0  4545.3     .16       0  4714.7    .033       0
  4720.7     .16       0  4905.6     .05       0  5179.3     .16       0
  5305.7     .08       0
Bank Sta=4714.7,4720.7
XS Rating Curve= 0 ,0
Exp/Cntr=0.3,0.1

Type RM Length L Ch R = 1 ,645     ,79,79,79
BEGIN DESCRIPTION:
Mapping XS 1ed89056
END DESCRIPTION:
XS GIS Cut Line= 3
      3750507.75     10635671.02      3750250.83     10635348.13
       3749677.9     10635466.19
#Sta/Elev= 30
  4387.7  445.93  4472.4  442.86  4501.3   440.5  4536.5  428.25  4600.6  420.62
  4679.1  420.64  4699.9   424.6  4749.5   425.1    4822  424.81  4852.6  419.69
  4881.5  421.94  4893.5  419.78  4936.2  420.66  4975.2   422.7  4982.1  423.84
  4987.2  421.14  4995.6  420.79  5032.4  424.37  5046.6  422.06    5067  424.36
  5178.8  424.09  5210.8  424.91  5233.6  423.07  5237.6  419.27  5240.4  418.77
  5243.6  419.27  5280.6  424.72  5329.1  432.09  5382.4  435.05  5385.3   435.1
#Mann= 10 ,-1 , 0
  4387.7     .05       0  4472.4     .16       0  4936.2     .05       0
  4975.2     .16       0  5178.8     .12       0  5210.8     .16       0
  5237.6     .07       0  5243.6     .16       0  5280.6     .08       0
  5382.4     .05       0
Bank Sta=5237.6,5243.6
XS Rating Curve= 0 ,0
Exp/Cntr=0.3,0.1

Type RM Length L Ch R = 1 ,566     ,42,42,42
BEGIN DESCRIPTION:
UNT 102 IN BOCR 1.0
END DESCRIPTION:
XS GIS Cut Line= 3
      3750532.09     10635643.29      3750261.24     10635257.85
      3749695.31     10635393.26
#Sta/Elev= 30
  4291.3  445.34  4384.1  442.05  4409.9  438.52  4460.5  422.33  4525.8   412.4
  4539.5  412.12  4597.3  423.84    4633  410.84  4653.9  412.63  4668.7   408.8
  4704.4  415.51  4719.3  407.54    4755   409.7  4774.4  406.86  4791.8  411.83
    4839  412.36  4846.3  408.43  4875.9  405.96  5038.7  403.03  5041.4  402.53
  5044.7  403.03    5099  405.93  5113.7  409.17  5151.2  409.03  5195.9  421.17
  5222.6  422.95  5253.9  419.36  5269.8  419.75  5278.2   426.5  5344.3  431.38
#Mann= 7 ,-1 , 0
  4291.3     .05       0  4384.1     .16       0  5038.7     .07       0
  5044.7     .16       0    5099     .16       0  5151.2     .12       0
  5253.9     .05       0
Bank Sta=5038.7,5044.7
XS Rating Curve= 0 ,0
Exp/Cntr=0.3,0.1

Type RM Length L Ch R = 1 ,524     ,205,205,205
BEGIN DESCRIPTION:
Mapping XS 5cb73942
END DESCRIPTION:
XS GIS Cut Line= 6
      3750402.34      10635322.7      3750348.52     10635263.67
      3750211.37     10635234.16      3750029.07     10635272.36
      3749923.17     10635282.77      3749608.95     10635365.64
#Sta/Elev= 30
  4583.6   424.3  4594.4  423.85  4622.8  415.78  4643.7  416.54  4651.2   410.8
  4662.5  406.67  4682.8  406.27  4693.1  408.82    4701  413.39  4723.7  416.08
  4750.3  414.19  4755.4  415.58  4764.7  409.41  4774.9  406.98  4806.3   405.7
  4836.2  407.52  4938.4  404.55  5041.2  402.99  5046.8  402.92  5049.5  402.42
  5052.8  402.92    5090  405.11  5203.5     420  5221.3  424.33    5239   418.9
  5266.8   418.4  5275.9  425.99  5286.3  427.17  5342.4  429.28  5421.4     429
#Mann= 6 ,-1 , 0
  4583.6     .16       0  5041.2     .12       0  5046.8     .07       0
  5052.8     .16       0    5239     .05       0  5342.4     .08       0
Bank Sta=4938.4,5090
XS Rating Curve= 0 ,0
Exp/Cntr=0.3,0.1

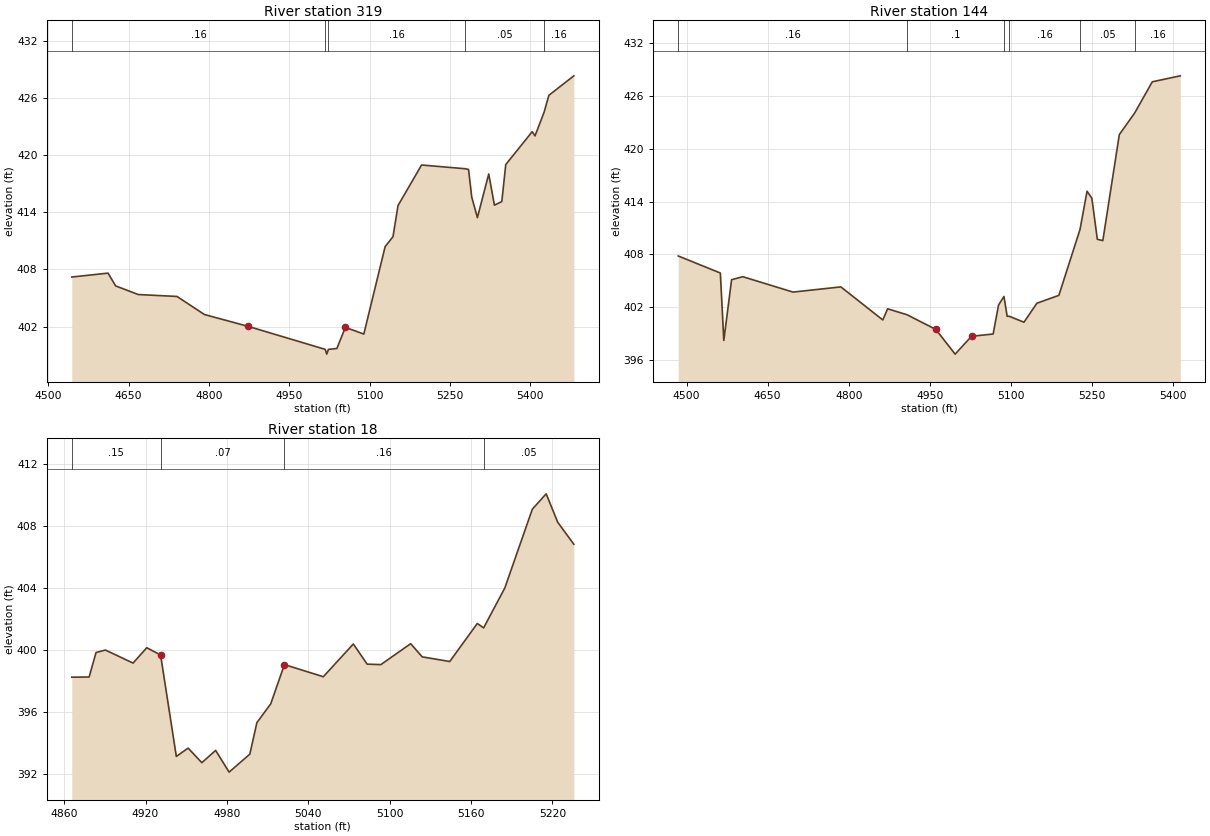
Type RM Length L Ch R = 1 ,319     ,175,175,175
BEGIN DESCRIPTION:
Mapping XS 938bddfe
END DESCRIPTION:
XS GIS Cut Line= 5
      3750390.19     10635225.48      3750261.71     10635093.54
      3750072.48     10635050.13      3749862.41     10635107.42
      3749539.51     10635220.27
#Sta/Elev= 30
  4543.7   407.2  4611.5  407.61  4625.6  406.27    4668  405.36  4740.3  405.16
  4791.6  403.26  4873.7  402.01  5017.3   399.6  5020.1   399.1  5023.3   399.6
    5039  399.69  5054.9  401.91  5089.4  401.21  5129.2  410.39  5143.9  411.44
  5153.3  414.71  5197.3  418.97  5278.5  418.58  5285.1   418.5    5291  415.61
  5301.6  413.44  5322.8  418.03  5333.4  414.75  5347.2  415.13  5354.6  419.02
    5404  422.47  5409.3  422.03  5426.3  424.53  5435.1  426.29  5481.8  428.34
#Mann= 5 ,-1 , 0
  4543.7     .16       0  5017.3     .07       0  5023.3     .16       0
  5278.5     .05       0  5426.3     .16       0
Bank Sta=4873.7,5054.9
XS Rating Curve= 0 ,0
Exp/Cntr=0.3,0.1

Type RM Length L Ch R = 1 ,144     ,126,126,126
BEGIN DESCRIPTION:
Mapping XS 84ede811
END DESCRIPTION:
XS GIS Cut Line= 5
      3750371.05     10635147.33      3750154.07     10634973.74
      3749996.09     10634916.45      3749832.89     10634909.51
      3749518.64      10634966.8
#Sta/Elev= 30
  4484.7  407.81  4562.6  405.87    4569   398.2  4583.4  405.11  4604.2  405.45
    4697   403.7  4785.5  404.29  4863.1  400.53    4872   401.8    4908  401.12
  4961.2  399.45  4996.9  396.64  5027.2  398.67  5067.2  398.93  5077.2  402.23
  5087.2   403.2  5093.1  400.95  5096.9  400.95  5124.2  400.27  5148.1  402.43
  5188.8  403.33  5227.9  410.83  5240.9  415.18  5249.8  414.38  5259.9  409.71
  5270.1  409.56  5300.6  421.62  5329.1  424.09  5361.6  427.63  5413.4  428.31
#Mann= 6 ,-1 , 0
  4484.7     .16       0    4908      .1       0  5087.2     .12       0
  5096.9     .16       0  5227.9     .05       0  5329.1     .16       0
Bank Sta=4961.2,5027.2
XS Rating Curve= 0 ,0
Exp/Cntr=0.3,0.1

Type RM Length L Ch R = 1 ,18      ,0,0,0
BEGIN DESCRIPTION:
Mapping XS 8fad6a16
END DESCRIPTION:
XS GIS Cut Line= 2
      3750004.08     10634782.42      3749639.49     10634846.65
#Sta/Elev= 30
  4865.6  398.27  4878.4  398.28  4883.5  399.86  4890.4  400.02  4910.8  399.18
  4920.9  400.17  4931.1   399.7  4942.7  393.16  4951.4   393.7  4961.5  392.76
  4971.7  393.55  4981.6  392.15  4996.9  393.31  5002.1  395.34  5012.3  396.55
  5022.4  399.08  5051.1   398.3  5073.2  400.41  5083.4  399.11  5093.5  399.08
  5115.5  400.43    5124  399.58  5144.3  399.28  5164.6  401.73  5169.3  401.45
  5184.9  404.02  5205.2   409.1  5215.4  410.09  5223.9  408.26  5235.8  406.84
#Mann= 4 ,-1 , 0
  4865.6     .15       0  4931.1     .07       0  5022.4     .16       0
  5169.3     .05       0
Bank Sta=4931.1,5022.4
XS Rating Curve= 0 ,0
Exp/Cntr=0.3,0.1

Chan Stop Cuts=-1
Use User Specified Reach Order=0
Composite Channel Slope=5