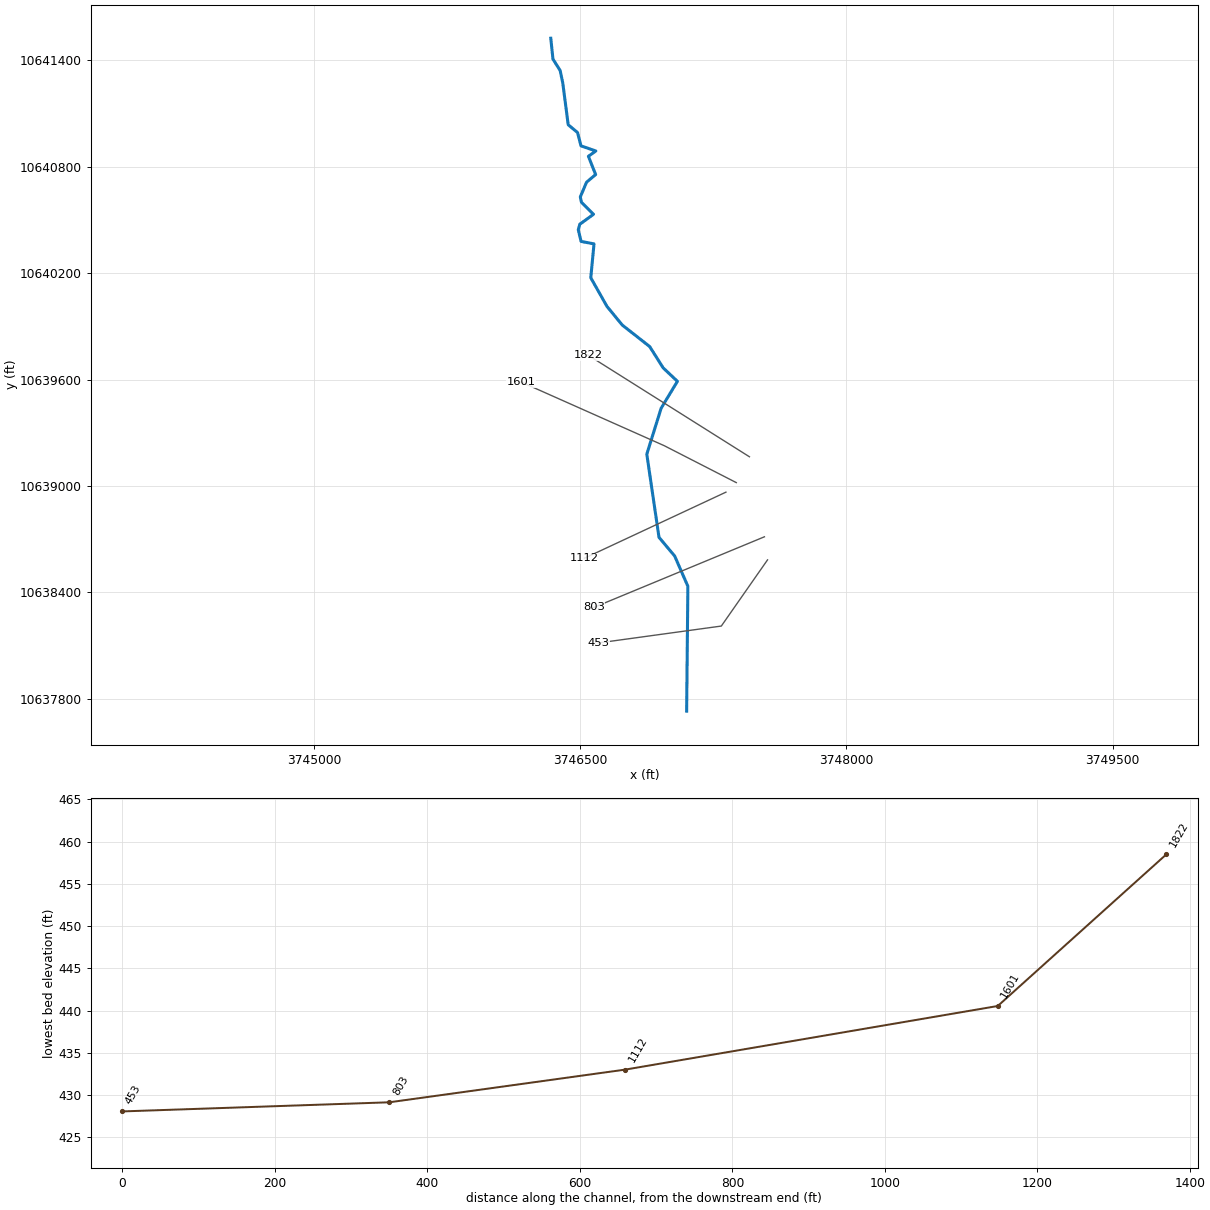
--- UNT 104 IN BOCR.prj (project) ---

Proj Title=UNT 104 IN BOCR Base Level Engineering
Current Plan=p01
Default Exp/Contr=0.3,0.1
English Units
Geom File=g01
Flow File=f01
Plan File=p01
BEGIN DESCRIPTION:
UNT 104 IN BOCR
END DESCRIPTION:

--- UNT 104 IN BOCR.p01 (plan) ---

Plan Title=Multiple Run
Short Identifier=Multiple
Geom File=g01
Flow File=f01
Subcritical Flow
K Sum by GR= 0
Std Step Tol= 0.01
Critical Tol= 0.01
Num of Std Step Trials= 20
Max Error Tol= 0.3
Flow Tol Ratio= 0.001
Split Flow NTrial= 30
Split Flow Tol= 0.02
Split Flow Ratio= 0.02
Log Output Level= 0
Friction Slope Method= 1
Unsteady Friction Slope Method= 2
Unsteady Bridges Friction Slope Method= 1
Parabolic Critical Depth
Global Vel Dist=  1 , 1 , 1
Global Log Level= 0
CheckData=True
Encroach Param= -1, 0, 0, 0
BEGIN DESCRIPTION:
Multiple Run
END DESCRIPTION:

--- UNT 104 IN BOCR.f01 (steady flow) ---

Flow Title=Multiple
Number of Profiles=7
Profile Names=10-year,25-year,50-year,1pct_min,100-year,1pct_plu,500-year
River Rch & RM= UNT 104 IN BOCR,Reach-1,1822
     436     586     710     635     859    1162    1258
Boundary for River Rch & Prof#=UNT 104 IN BOCR,Reach-1,1
Up Type=0
Dn Type=3
Dn Slope=0.005
Boundary for River Rch & Prof#=UNT 104 IN BOCR,Reach-1,2
Up Type=0
Dn Type=3
Dn Slope=0.005
Boundary for River Rch & Prof#=UNT 104 IN BOCR,Reach-1,3
Up Type=0
Dn Type=3
Dn Slope=0.005
Boundary for River Rch & Prof#=UNT 104 IN BOCR,Reach-1,4
Up Type=0
Dn Type=3
Dn Slope=0.005
Boundary for River Rch & Prof#=UNT 104 IN BOCR,Reach-1,5
Up Type=0
Dn Type=3
Dn Slope=0.005
Boundary for River Rch & Prof#=UNT 104 IN BOCR,Reach-1,6
Up Type=0
Dn Type=3
Dn Slope=0.005
Boundary for River Rch & Prof#=UNT 104 IN BOCR,Reach-1,7
Up Type=0
Dn Type=3
Dn Slope=0.005

--- UNT 104 IN BOCR.g01 (geometry) ---

Geom Title=Existing Conditions

River Reach=UNT 104 IN BOCR,Reach-1
Reach XY= 30
      3746333.75     10641525.00      3746346.25     10641407.00
      3746386.50     10641343.00      3746401.25     10641274.00
      3746432.00     10641037.00      3746484.75     10640993.00
      3746504.00     10640918.00      3746587.75     10640889.00
      3746545.75     10640859.00      3746586.75     10640756.00
      3746535.50     10640713.00      3746500.25     10640630.00
      3746506.50     10640600.00      3746574.75     10640532.00
      3746497.50     10640476.00      3746488.75     10640445.00
      3746504.75     10640379.00      3746577.50     10640365.00
      3746559.25     10640174.00      3746650.25     10640013.00
      3746737.00     10639907.00      3746891.25     10639786.00
      3746967.00     10639666.00      3747047.50     10639590.00
      3746955.75     10639438.00      3746875.00     10639179.00
      3746943.75     10638710.00      3747032.05     10638604.75
      3747106.50     10638434.00      3747099.50     10637730.00

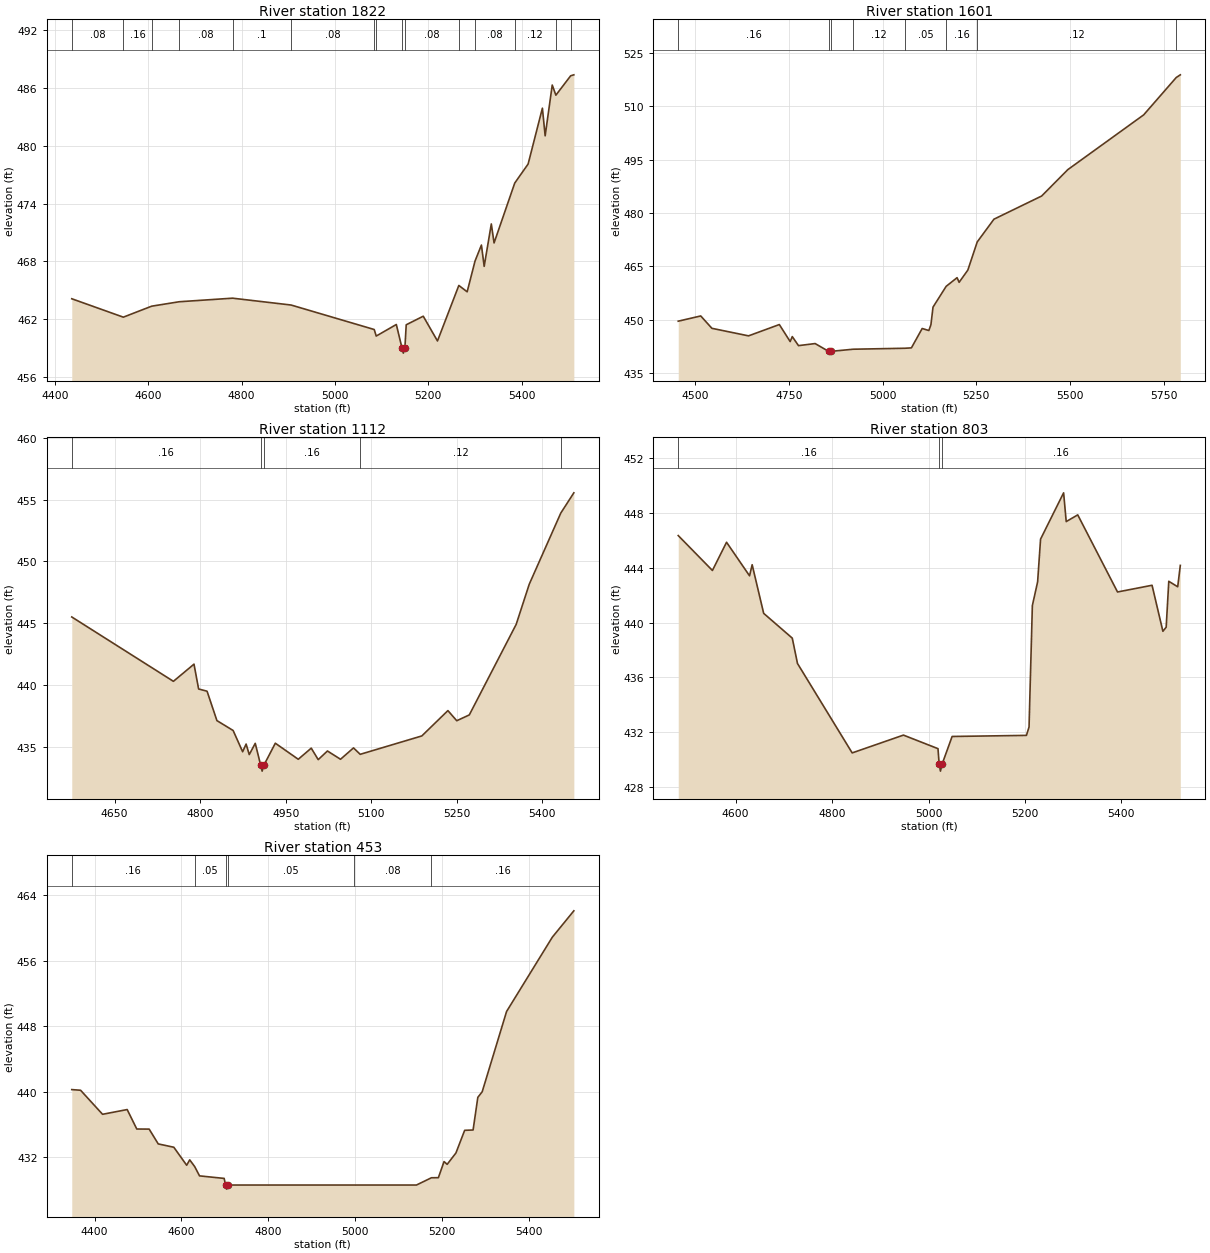
Type RM Length L Ch R = 1,1822,221,221,221
BEGIN DESCRIPTION:
Mapping XS f2845b59
END DESCRIPTION:
XS GIS Cut Line= 2
      3747453.44     10639164.38      3746543.05     10639738.32
#Sta/Elev= 30
  4436.0  464.12  4546.5  462.21  4607.3  463.35  4666.4  463.81  4780.6  464.18
  4906.1  463.47  5084.3  460.93  5088.6  460.25  5131.7  461.45  5144.0  458.98
  5146.7  458.48  5150.0  458.98  5152.9  461.42  5189.4  462.31  5219.9  459.74
  5265.7  465.50  5283.5  464.84  5300.4  468.03  5314.1  469.69  5320.0  467.48
  5335.3  471.88  5341.2  469.91  5385.5  476.12  5414.2  478.10  5444.8  483.89
  5450.7  481.02  5465.9  486.29  5473.7  485.24  5505.4  487.25  5512.2  487.35
#Mann=15,-1,0
  4436.0    0.08       0  4546.5    0.16       0  4607.3     0.1       0
  4666.4    0.08       0  4780.6     0.1       0  4906.1    0.08       0
  5084.3     0.1       0  5088.6    0.08       0  5144.0    0.07       0
  5150.0    0.08       0  5265.7    0.12       0  5300.4    0.08       0
  5385.5    0.12       0  5473.7    0.08       0  5505.4    0.12       0
Bank Sta=5144,5150
Exp/Cntr=0.3,0.1

Type RM Length L Ch R = 1,1601,489,489,489
BEGIN DESCRIPTION:
Mapping XS fc722322
END DESCRIPTION:
XS GIS Cut Line= 3
      3747379.49     10639018.60      3746973.24     10639226.93
      3746167.25     10639585.73
#Sta/Elev= 30
  4455.3  449.54  4515.3  451.01  4545.1  447.53  4642.8  445.41  4724.9  448.59
  4753.8  443.80  4759.4  445.20  4776.0  442.66  4820.4  443.24  4856.2  441.05
  4858.9  440.55  4862.2  441.05  4922.1  441.65  5059.5  441.92  5077.1  442.03
  5105.8  447.48  5123.6  446.91  5129.1  448.55  5134.7  453.50  5169.7  459.34
  5198.8  461.78  5204.3  460.48  5227.5  463.91  5252.6  471.84  5297.2  478.24
  5424.4  484.76  5494.1  492.18  5696.4  507.59  5783.2  518.10  5794.1  518.86
#Mann=8,-1,0
  4455.3    0.16       0  4856.2    0.07       0  4862.2    0.16       0
  4922.1    0.12       0  5059.5    0.05       0  5169.7    0.16       0
  5252.6    0.12       0  5783.2    0.16       0
Bank Sta=4856.2,4862.2
Exp/Cntr=0.3,0.1

Type RM Length L Ch R = 1,1112,309,309,309
BEGIN DESCRIPTION:
UNT 104 IN BOCR 9.0
END DESCRIPTION:
XS GIS Cut Line= 2
      3747321.07     10638964.87      3746523.58     10638592.13
#Sta/Elev= 30
  4574.9  445.50  4753.1  440.29  4789.2  441.68  4797.3  439.67  4812.1  439.49
  4829.4  437.11  4857.8  436.31  4874.5  434.59  4880.6  435.21  4886.1  434.36
  4896.6  435.27  4906.0  433.52  4908.7  433.02  4912.0  433.52  4931.8  435.28
  4972.0  433.98  4994.8  434.88  5007.0  433.95  5023.2  434.65  5046.1  433.98
  5068.9  434.90  5080.6  434.38  5188.7  435.87  5234.4  437.92  5249.9  437.10
  5271.9  437.57  5354.1  444.90  5377.0  448.15  5432.3  453.91  5455.2  455.55
#Mann=5,-1,0
  4574.9    0.16       0  4906.0    0.07       0  4912.0    0.16       0
  5080.6    0.12       0  5432.3    0.16       0
Bank Sta=4906,4912
Exp/Cntr=0.3,0.1

Type RM Length L Ch R = 1,803,350,350,350
BEGIN DESCRIPTION:
UNT 104 IN BOCR 2.0
END DESCRIPTION:
XS GIS Cut Line= 2
      3747538.09     10638713.14      3746576.22     10638314.52
#Sta/Elev= 30
  4480.9  446.36  4551.8  443.81  4581.1  445.87  4628.8  443.42  4634.2  444.23
  4658.1  440.68  4717.4  438.87  4728.2  437.02  4841.6  430.49  4947.9  431.79
  5019.6  430.80  5022.0  429.66  5024.7  429.16  5028.0  429.66  5048.9  431.69
  5203.0  431.77  5208.4  432.38  5215.3  441.25  5226.2  442.98  5232.3  446.10
  5280.1  449.48  5285.5  447.38  5309.4  447.87  5391.9  442.24  5463.5  442.73
  5486.0  439.37  5492.8  439.67  5498.2  443.02  5516.7  442.62  5522.1  444.18
#Mann=3,-1,0
  4480.9    0.16       0  5022.0    0.07       0  5028.0    0.16       0
Bank Sta=5022,5028
Exp/Cntr=0.3,0.1

Type RM Length L Ch R = 1,453,0,0,0
BEGIN DESCRIPTION:
UNT 104 IN BOCR 1.0
END DESCRIPTION:
XS GIS Cut Line= 3
      3747555.44     10638582.93      3747295.02     10638209.66
      3746600.59     10638114.17
#Sta/Elev= 30
  4347.5  440.25  4367.8  440.17  4418.4  437.23  4475.1  437.81  4497.2  435.43
  4525.7  435.42  4546.6  433.61  4582.5  433.20  4612.1  431.00  4619.1  431.66
  4630.6  430.83  4641.7  429.70  4698.4  429.39  4701.5  428.58  4704.3  428.08
  4707.5  428.58  4996.4  428.58  5141.2  428.58  5175.7  429.47  5191.7  429.48
  5204.7  431.45  5211.9  431.11  5232.1  432.50  5252.2  435.27  5271.6  435.31
  5282.5  439.30  5292.6  439.99  5348.7  449.80  5454.1  458.89  5503.6  462.11
#Mann=6,-1,0
  4347.5    0.16       0  4630.6    0.05       0  4701.5    0.07       0
  4707.5    0.05       0  4996.4    0.08       0  5175.7    0.16       0
Bank Sta=4701.5,4707.5
Exp/Cntr=0.3,0.1

Chan Stop Cuts=-1