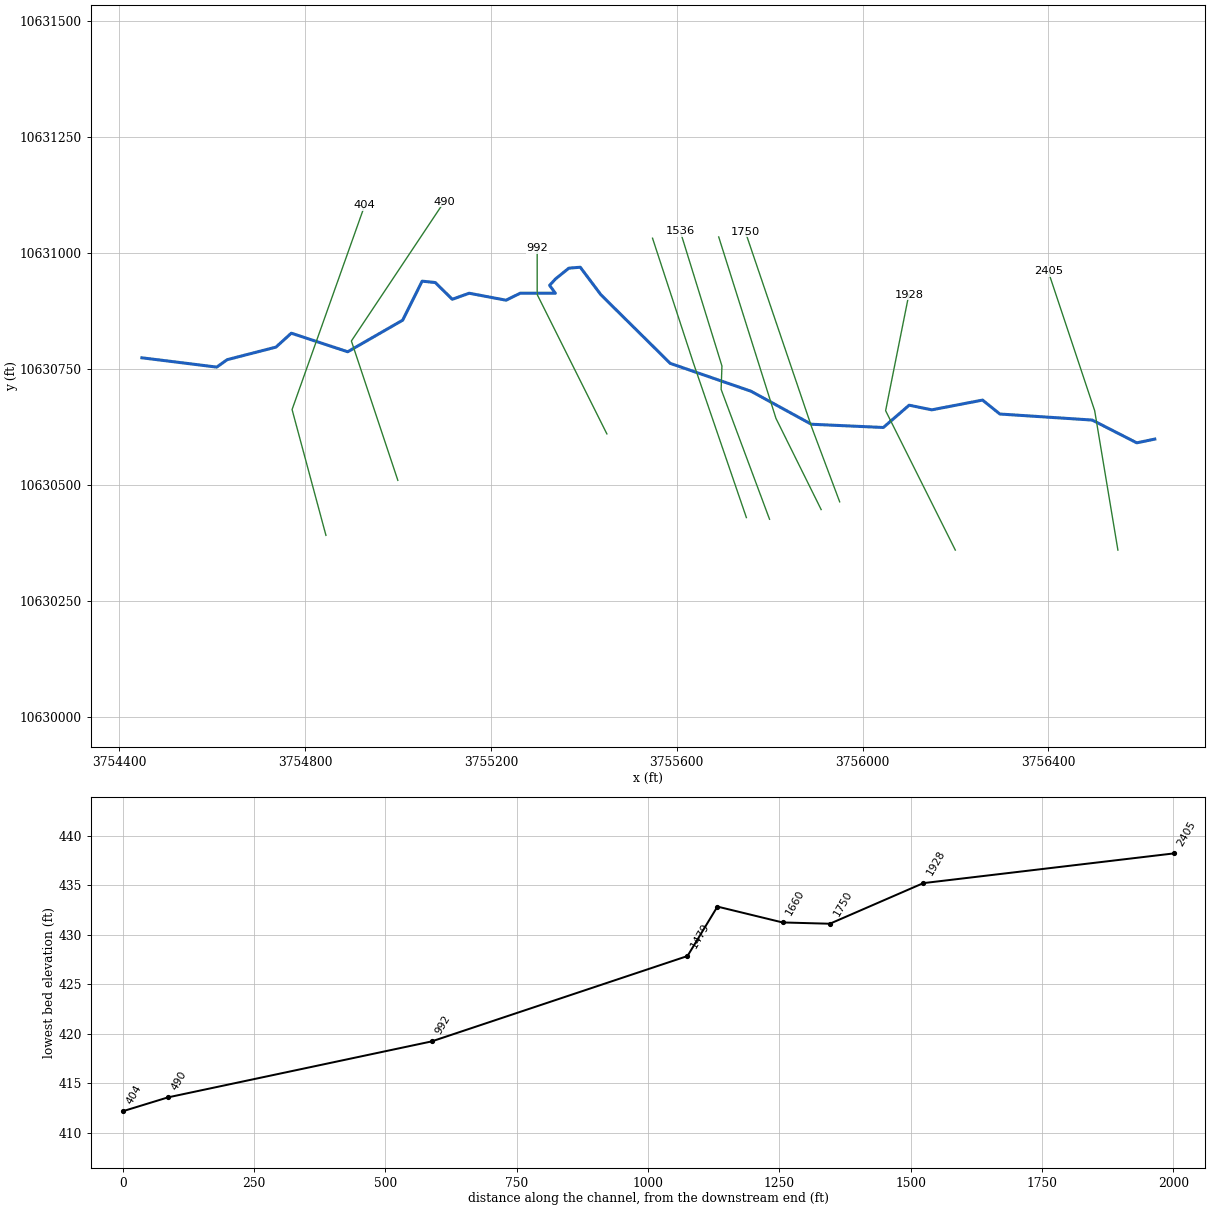
--- UNT 106 IN BOCR.prj (project) ---

Proj Title=UNT 106 IN BOCR Base Level Engineering
Current Plan=p01
Default Exp/Contr=0.3,0.1
English Units
Geom File=g01
Flow File=f01
Plan File=p01
Y Axis Title=Elevation
X Axis Title(PF)=Main Channel Distance
X Axis Title(XS)=Station
BEGIN DESCRIPTION:
UNT 106 IN BOCR
END DESCRIPTION:
DSS Export Rating Curves= 0
DSS Export Rating Curve Sorted= 0
DSS Export Volume Flow Curves= 0
DXF OffsetX= 0
DXF OffsetY= 0
DXF ScaleX= 1
DXF ScaleY= 10

--- UNT 106 IN BOCR.p01 (plan) ---

Plan Title=Multiple Run
Short Identifier=Multiple
Geom File=g01
Flow File=f01
Subcritical Flow
K Sum by GR= 0
Std Step Tol= 0.01
Critical Tol= 0.01
Num of Std Step Trials= 20
Max Error Tol= 0.3
Flow Tol Ratio= 0.001
Split Flow NTrial= 30
Split Flow Tol= 0.02
Split Flow Ratio= 0.02
Log Output Level= 0
Friction Slope Method= 1
Unsteady Friction Slope Method= 2
Unsteady Bridges Friction Slope Method= 1
Parabolic Critical Depth
Global Vel Dist=  1 , 1 , 1
Global Log Level= 0
CheckData=True
Encroach Param= -1, 0, 0, 0
BEGIN DESCRIPTION:
Multiple Run
END DESCRIPTION:

--- UNT 106 IN BOCR.f01 (steady flow) ---

Flow Title=Multiple
Number of Profiles=7
Profile Names=10-year,25-year,50-year,1pct_min,100-year,1pct_plu,500-year
River Rch & RM= UNT 106 IN BOCR,Reach-1,2405
     449     603     731     653     883    1195    1292
Boundary for River Rch & Prof#=UNT 106 IN BOCR,Reach-1,1
Up Type=0
Dn Type=3
Dn Slope=0.005
Boundary for River Rch & Prof#=UNT 106 IN BOCR,Reach-1,2
Up Type=0
Dn Type=3
Dn Slope=0.005
Boundary for River Rch & Prof#=UNT 106 IN BOCR,Reach-1,3
Up Type=0
Dn Type=3
Dn Slope=0.005
Boundary for River Rch & Prof#=UNT 106 IN BOCR,Reach-1,4
Up Type=0
Dn Type=3
Dn Slope=0.005
Boundary for River Rch & Prof#=UNT 106 IN BOCR,Reach-1,5
Up Type=0
Dn Type=3
Dn Slope=0.005
Boundary for River Rch & Prof#=UNT 106 IN BOCR,Reach-1,6
Up Type=0
Dn Type=3
Dn Slope=0.005
Boundary for River Rch & Prof#=UNT 106 IN BOCR,Reach-1,7
Up Type=0
Dn Type=3
Dn Slope=0.005

--- UNT 106 IN BOCR.g01 (geometry) ---

Geom Title=Existing Conditions
Program Version=4.10

River Reach=UNT 106 IN BOCR ,Reach-1
Reach XY= 30
        3756629.       10630599.      3756590.25       10630591.
      3756494.25       10630640.       3756295.5       10630653.
      3756258.25       10630683.        3756149.       10630662.
      3756100.25       10630672.      3756044.75       10630624.
      3755889.75       10630631.        3755760.       10630702.
      3755585.99     10630761.99       3755436.5       10630910.
      3755392.25       10630969.      3755367.75       10630967.
      3755339.25       10630944.      3755326.25       10630930.
      3755338.75       10630913.        3755263.       10630913.
       3755232.5       10630898.      3755153.25       10630913.
      3755116.75       10630900.      3755080.25       10630936.
      3755051.88       10630939.        3755010.       10630855.
      3754891.75       10630787.      3754770.25       10630827.
      3754737.25       10630797.      3754632.25       10630770.
      3754609.75       10630754.      3754448.75       10630774.

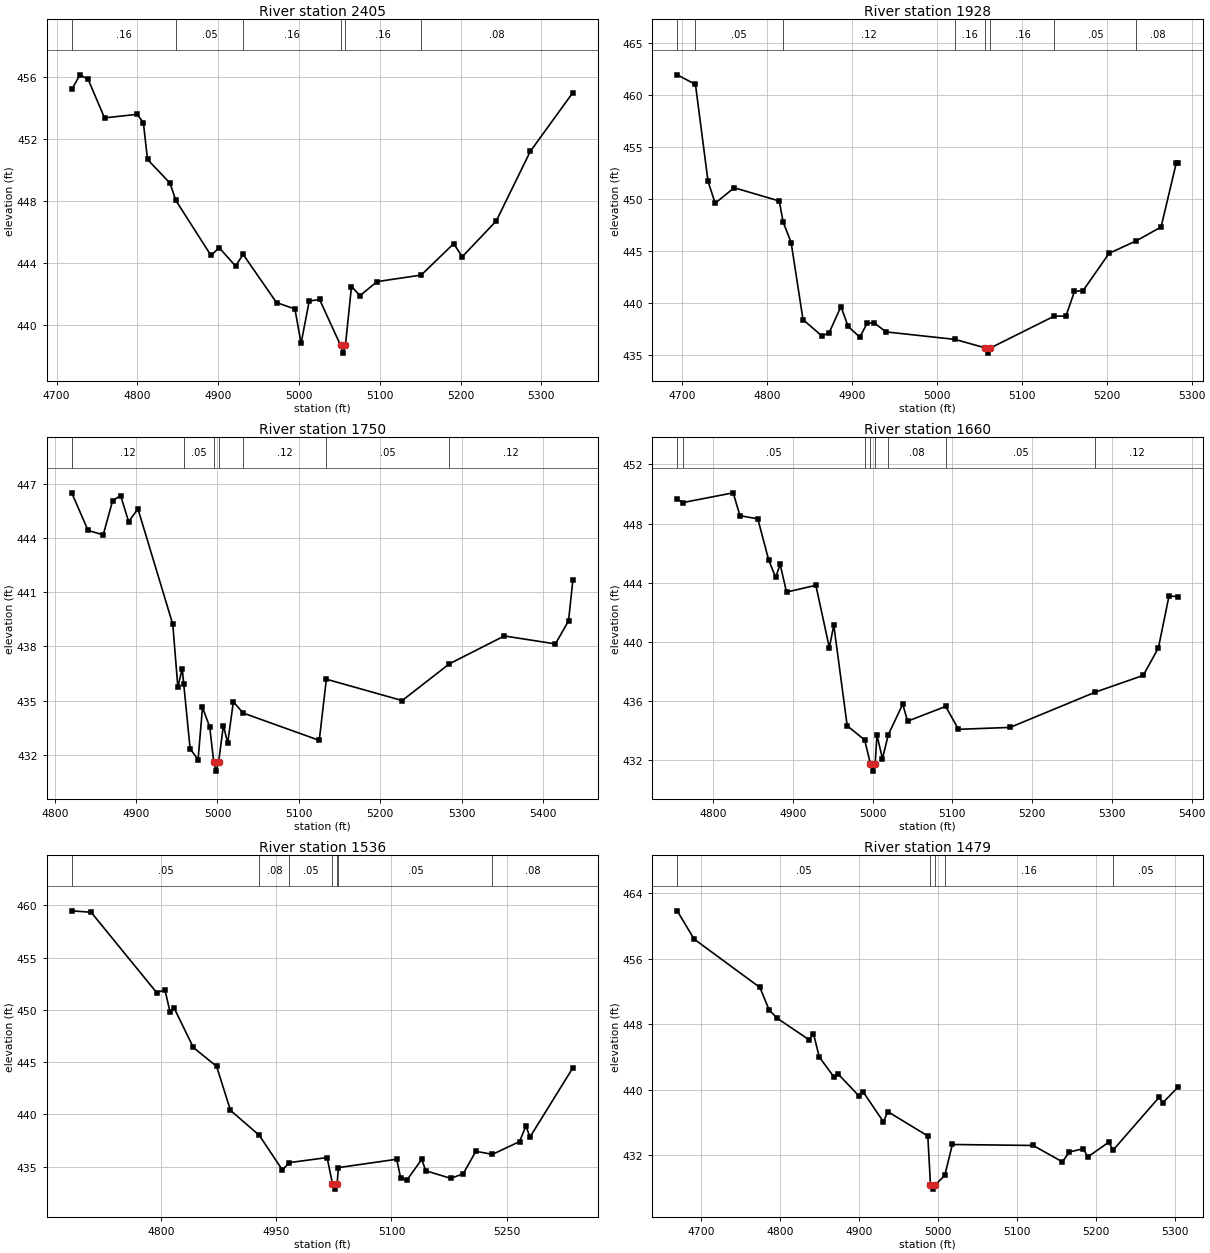
Type RM Length L Ch R = 1 ,2405    ,477,477,477
BEGIN DESCRIPTION:
UNT 106 IN BOCR 5.0
END DESCRIPTION:
XS GIS Cut Line= 3
      3756549.62     10630360.15      3756499.61     10630660.19
      3756399.61     10630960.18
#Sta/Elev= 30
  4718.7  455.17  4728.9  456.11    4739  455.82  4759.3  453.34  4799.8  453.57
  4807.4  453.03  4812.5  450.67  4840.4  449.14  4847.5  448.04  4891.1  444.49
  4901.2  444.99  4921.5  443.81  4930.9  444.56  4972.2  441.46    4995  441.05
  5002.6  438.84  5012.7  441.56  5025.5  441.66  5051.5  438.71  5054.3  438.21
  5057.5  438.71    5065  442.49  5075.6  441.91  5096.7  442.81  5151.3  443.23
  5191.5  445.25  5202.1  444.41  5244.2  446.71  5286.4  451.19  5339.1  454.97
#Mann= 6 ,-1 , 0
  4718.7     .16       0  4847.5     .05       0  4930.9     .16       0
  5051.5     .07       0  5057.5     .16       0  5151.3     .08       0
Bank Sta=5051.5,5057.5
XS Rating Curve= 0 ,0
Exp/Cntr=0.3,0.1

Type RM Length L Ch R = 1 ,1928    ,178,178,178
BEGIN DESCRIPTION:
UNT 106 IN BOCR 4.0
END DESCRIPTION:
XS GIS Cut Line= 3
      3756199.61     10630360.18      3756049.61     10630660.19
      3756099.61     10630910.21
#Sta/Elev= 30
    4694  461.97  4715.5  461.05  4730.3  451.73  4738.7  449.62  4761.1  451.11
  4814.2  449.84  4818.8  447.82  4828.2  445.84  4842.2  438.43  4864.5  436.86
  4872.9  437.15  4886.9  439.69  4895.3  437.78  4909.2  436.74  4917.6  438.08
    4926  438.12    4940  437.25  5021.3  436.53    5057  435.71  5059.8  435.21
    5063  435.71  5138.4  438.78  5151.8  438.76    5162  441.14  5172.2  441.23
  5202.8  444.81  5234.9  446.01    5264  447.34  5281.8  453.46  5284.4  453.46
#Mann= 8 ,-1 , 0
    4694     .16       0  4715.5     .05       0  4818.8     .12       0
  5021.3     .16       0    5057     .07       0    5063     .16       0
  5138.4     .05       0  5234.9     .08       0
Bank Sta=5057,5063
XS Rating Curve= 0 ,0
Exp/Cntr=0.3,0.1

Type RM Length L Ch R = 1 ,1750    ,90,90,90
BEGIN DESCRIPTION:
Mapping XS d9bdf4e2
END DESCRIPTION:
XS GIS Cut Line= 3
      3755950.73     10630463.93      3755891.17     10630622.74
      3755747.59     10631045.31
#Sta/Elev= 30
  4820.9  446.49    4841  444.41  4859.6  444.17  4871.2  446.06    4881  446.34
  4890.8   444.9  4902.3   445.6  4945.1  439.22  4951.3  435.76  4956.7  436.77
  4958.6   435.9  4966.4  432.34  4976.2  431.75  4981.6  434.63  4990.5  433.55
  4995.4  431.61  4998.1  431.11  5001.4  431.61  5007.3  433.63  5012.6  432.66
  5019.5  434.94  5031.6  434.32  5125.1  432.81  5133.8  436.19    5227  435.01
    5285  437.04  5352.5  438.58  5415.3  438.14  5431.4  439.41  5436.8  441.68
#Mann= 7 ,-1 , 0
  4820.9     .12       0  4958.6     .05       0  4995.4     .04       0
  5001.4     .05       0  5031.6     .12       0  5133.8     .05       0
    5285     .12       0
Bank Sta=4995.4,5001.4
XS Rating Curve= 0 ,0
Exp/Cntr=0.3,0.1

Type RM Length L Ch R = 1 ,1660    ,124,124,124
BEGIN DESCRIPTION:
Mapping XS 86318a46
END DESCRIPTION:
XS GIS Cut Line= 3
      3755910.84     10630447.33       3755813.6     10630643.55
      3755690.34     10631034.17
#Sta/Elev= 30
  4754.9  449.67  4761.9  449.42  4825.1  450.08  4833.6  448.53    4856  448.32
  4869.7  445.52  4878.4  444.35    4884  445.24    4892  443.36  4928.8  443.82
  4945.7   439.6  4951.3  441.12  4968.1  434.31    4990  433.35  4997.2  431.74
  4999.9  431.24  5003.2  431.74  5005.4  433.69  5012.3  432.08  5019.7  433.71
  5037.8  435.78  5043.8  434.62  5091.6  435.62  5107.7  434.07  5172.4   434.2
  5279.4  436.59  5339.4  437.72  5358.4  439.58  5371.7  443.09  5383.5  443.06
#Mann= 8 ,-1 , 0
  4754.9     .12       0  4761.9     .05       0    4990     .12       0
  4997.2     .07       0  5003.2     .12       0  5019.7     .08       0
  5091.6     .05       0  5279.4     .12       0
Bank Sta=4997.2,5003.2
XS Rating Curve= 0 ,0
Exp/Cntr=0.3,0.1

Type RM Length L Ch R = 1 ,1536    ,57,57,57
BEGIN DESCRIPTION:
Mapping XS 7396c3e3
END DESCRIPTION:
XS GIS Cut Line= 4
      3755799.73      10630426.5      3755695.55     10630706.05
      3755697.28     10630756.39      3755607.46      10631046.6
#Sta/Elev= 30
  4683.7  459.48    4709  459.34  4794.4  451.64    4805  451.93  4811.6  449.83
    4817  450.18    4842   446.4  4872.3  444.59  4890.4  440.38  4927.9  437.99
  4957.9  434.68  4967.2  435.38  5016.2  435.86  5023.2  433.34  5025.9  432.84
  5029.2  433.34  5030.9   434.9  5106.8   435.7    5112  433.89  5120.1  433.71
  5139.4  435.69  5144.6   434.6  5177.2  433.87  5193.4  434.31  5209.8  436.46
  5231.5  436.17  5266.7  437.39  5275.1  438.89  5280.3  437.82  5336.2  444.46
#Mann= 7 ,-1 , 0
  4683.7     .05       0  4927.9     .08       0  4967.2     .05       0
  5023.2     .04       0  5029.2     .05       0  5030.9     .05       0
  5231.5     .08       0
Bank Sta=5023.2,5029.2
XS Rating Curve= 0 ,0
Exp/Cntr=0.3,0.1

Type RM Length L Ch R = 1 ,1479    ,487,487,487
BEGIN DESCRIPTION:
Mapping XS d62f37e1
END DESCRIPTION:
XS GIS Cut Line= 3
      3755749.88      10630430.1      3755635.46     10630764.03
      3755547.87     10631031.46
#Sta/Elev= 30
  4669.9  461.83  4691.3  458.38  4774.6  452.47  4786.3  449.72  4796.8  448.69
  4837.1  446.07  4842.4  446.84  4849.7  443.98  4868.4  441.54  4873.7   441.9
  4899.7  439.25    4905  439.76    4931  436.06  4936.3  437.32  4987.1  434.34
  4990.5  428.35  4993.3  427.85  4996.5  428.35  5008.6  429.53  5018.2   433.3
  5120.4  433.18  5157.5  431.18  5166.2  432.38  5184.1  432.79  5189.4  431.77
    5216  433.57  5221.8  432.63  5279.7  439.04  5284.9  438.42  5304.3  440.36
#Mann= 5 ,-1 , 0
  4669.9     .05       0  4990.5     .04       0  4996.5     .05       0
  5008.6     .16       0  5221.8     .05       0
Bank Sta=4990.5,4996.5
XS Rating Curve= 0 ,0
Exp/Cntr=0.3,0.1

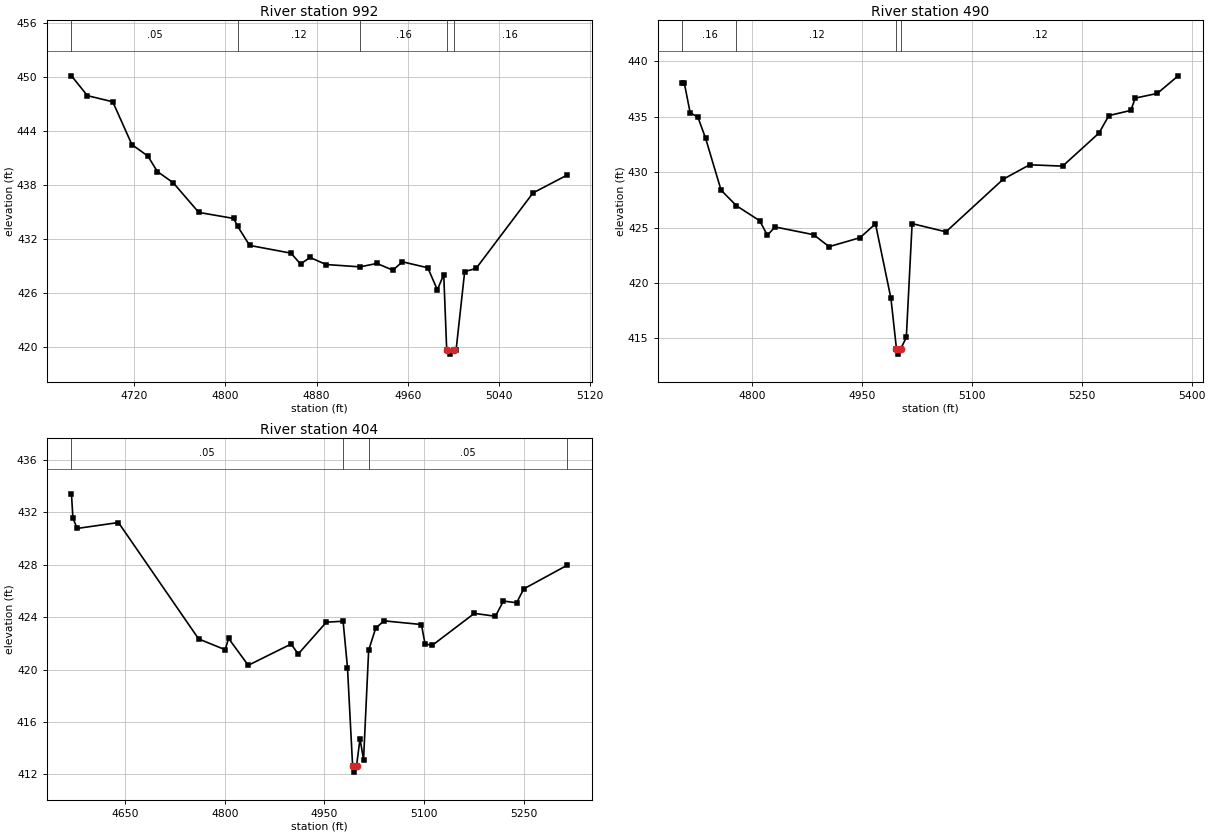
Type RM Length L Ch R = 1 ,992     ,502,502,502
BEGIN DESCRIPTION:
UNT 106 IN BOCR 2.0
END DESCRIPTION:
XS GIS Cut Line= 3
       3755449.6      10630610.2      3755299.61     10630910.19
      3755299.61     10631010.19
#Sta/Elev= 30
  4664.7   450.1  4678.7   447.9    4701  447.22  4717.8  442.47  4731.8   441.2
  4740.2  439.48  4754.1  438.24  4776.5  434.95  4807.2  434.28  4810.6  433.42
  4821.2  431.29  4857.5  430.43  4865.9  429.23  4874.3  429.95  4888.3  429.17
  4918.2  428.91    4933  429.29    4947  428.54  4955.4  429.47  4977.7  428.81
  4986.1  426.36  4991.7  428.06  4994.3  419.73  4997.1  419.23  5000.3  419.73
  5002.6  419.73  5010.1  428.39  5020.1  428.73  5070.1  437.11  5100.1  439.09
#Mann= 5 ,-1 , 0
  4664.7     .05       0  4810.6     .12       0  4918.2     .16       0
  4994.3     .07       0  5000.3     .16       0
Bank Sta=4994.3,5000.3
XS Rating Curve= 0 ,0
Exp/Cntr=0.3,0.1

Type RM Length L Ch R = 1 ,490     ,86,86,86
BEGIN DESCRIPTION:
UNT 106 IN BOCR 1.0
END DESCRIPTION:
XS GIS Cut Line= 3
      3754999.59     10630510.24      3754899.61     10630810.19
      3755099.59     10631110.16
#Sta/Elev= 30
  4704.9  438.02  4707.5  438.02  4715.4  435.37  4725.9  434.98  4736.5  433.06
  4757.6  428.38  4778.5  426.98  4810.3  425.62  4820.8  424.31  4831.3  425.06
    4884  424.36  4905.1  423.28  4947.3  424.09  4968.4  425.34  4989.5  418.61
    4997  414.08  4999.7  413.58    5003  414.08  5010.5  415.09  5018.4  425.36
  5064.6  424.62  5142.8  429.37  5178.8  430.67  5223.9  430.55  5273.5  433.53
    5287  435.11    5317  435.58    5323  436.69  5353.1  437.11  5381.6   438.7
#Mann= 4 ,-1 , 0
  4704.9     .16       0  4778.5     .12       0    4997     .07       0
    5003     .12       0
Bank Sta=4997,5003
XS Rating Curve= 0 ,0
Exp/Cntr=0.3,0.1

Type RM Length L Ch R = 1 ,404     ,0,0,0
BEGIN DESCRIPTION:
Mapping XS 7225d80f
END DESCRIPTION:
XS GIS Cut Line= 3
      3754844.85     10630391.82      3754771.94     10630662.64
       3754928.2     10631101.91
#Sta/Elev= 30
  4568.9  433.41  4571.1  431.55  4577.6  430.77  4639.7  431.22  4760.5  422.34
  4800.4  421.52  4805.6  422.38  4835.2  420.33  4899.8  421.95  4910.5  421.19
  4952.9  423.62  4978.1  423.69  4984.7  420.16  4992.4  412.68  4995.1  412.18
  4998.4  412.68  5003.6  414.73  5008.9  413.13  5016.6  421.48  5027.2  423.16
  5039.7  423.72  5096.1  423.44  5101.5  421.97  5112.1  421.84  5175.8  424.29
  5207.6  424.07  5219.5  425.23  5239.5   425.1  5250.3  426.16  5315.6  427.96
#Mann= 4 ,-1 , 0
  4568.9     .05       0  4978.1     .03       0  5016.6     .05       0
  5315.6     .12       0
Bank Sta=4992.4,4998.4
XS Rating Curve= 0 ,0
Exp/Cntr=0.3,0.1

Chan Stop Cuts=-1
Use User Specified Reach Order=0
Composite Channel Slope=5