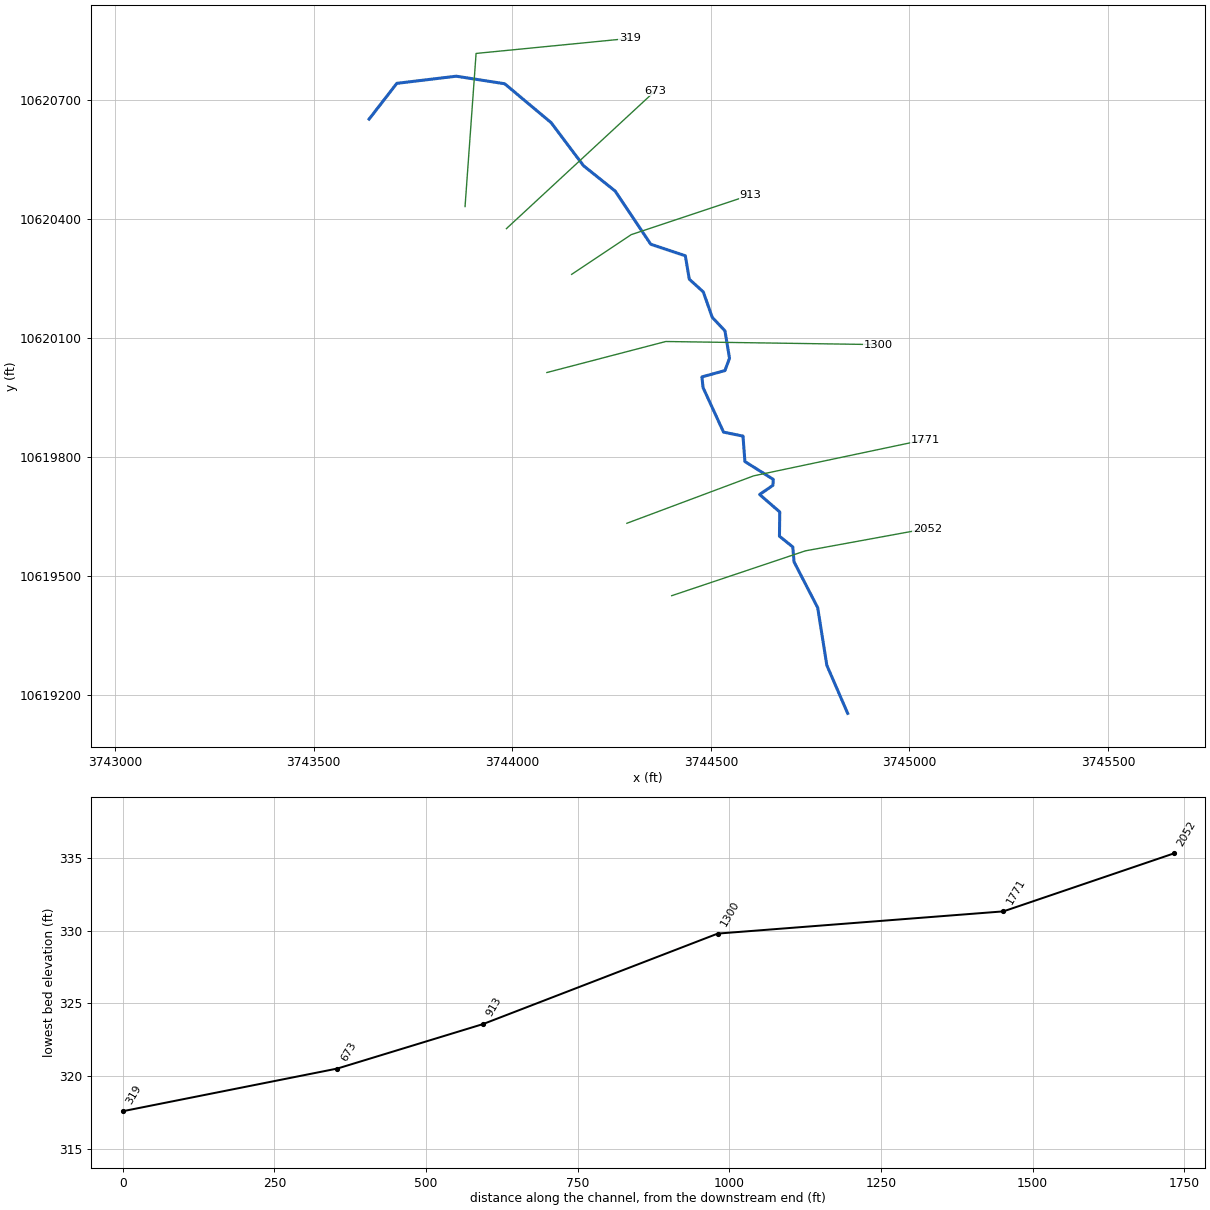
--- UNT 108 IN BOCR.prj (project) ---

Proj Title=UNT 108 IN BOCR Base Level Engineering
Current Plan=p01
Default Exp/Contr=0.3,0.1
English Units
Geom File=g01
Flow File=f01
Plan File=p01
Y Axis Title=Elevation
X Axis Title(PF)=Main Channel Distance
X Axis Title(XS)=Station
BEGIN DESCRIPTION:
UNT 108 IN BOCR
END DESCRIPTION:
DSS Export Rating Curves= 0
DSS Export Rating Curve Sorted= 0
DSS Export Volume Flow Curves= 0
DXF OffsetX= 0
DXF OffsetY= 0
DXF ScaleX= 1
DXF ScaleY= 10

--- UNT 108 IN BOCR.p01 (plan) ---

Plan Title=Multiple Run
Short Identifier=Multiple
Geom File=g01
Flow File=f01
Subcritical Flow
K Sum by GR= 0
Std Step Tol= 0.01
Critical Tol= 0.01
Num of Std Step Trials= 20
Max Error Tol= 0.3
Flow Tol Ratio= 0.001
Split Flow NTrial= 30
Split Flow Tol= 0.02
Split Flow Ratio= 0.02
Log Output Level= 0
Friction Slope Method= 1
Unsteady Friction Slope Method= 2
Unsteady Bridges Friction Slope Method= 1
Parabolic Critical Depth
Global Vel Dist=  1 , 1 , 1
Global Log Level= 0
CheckData=True
Encroach Param= -1, 0, 0, 0
BEGIN DESCRIPTION:
Multiple Run
END DESCRIPTION:

--- UNT 108 IN BOCR.f01 (steady flow) ---

Flow Title=Multiple
Program Version=4.10
Number of Profiles= 7
Profile Names=10-year,25-year,50-year,1pct_min,100-year,1pct_plu,500-year
River Rch & RM=UNT 108 IN BOCR,Reach-1         ,2052
     292     379     448     392     530     716     740
Boundary for River Rch & Prof#=UNT 108 IN BOCR,Reach-1         , 1
Up Type= 0
Dn Type= 3
Dn Slope=0.005
Boundary for River Rch & Prof#=UNT 108 IN BOCR,Reach-1         , 2
Up Type= 0
Dn Type= 3
Dn Slope=0.005
Boundary for River Rch & Prof#=UNT 108 IN BOCR,Reach-1         , 3
Up Type= 0
Dn Type= 3
Dn Slope=0.005
Boundary for River Rch & Prof#=UNT 108 IN BOCR,Reach-1         , 4
Up Type= 0
Dn Type= 3
Dn Slope=0.005
Boundary for River Rch & Prof#=UNT 108 IN BOCR,Reach-1         , 5
Up Type= 0
Dn Type= 3
Dn Slope=0.005
Boundary for River Rch & Prof#=UNT 108 IN BOCR,Reach-1         , 6
Up Type= 0
Dn Type= 3
Dn Slope=0.005
Boundary for River Rch & Prof#=UNT 108 IN BOCR,Reach-1         , 7
Up Type= 0
Dn Type= 3
Dn Slope=0.005
DSS Import GetInterval= 0
DSS Import GetPeak= 0
DSS Import FillOption= 0

--- UNT 108 IN BOCR.g01 (geometry) ---

Geom Title=Existing Conditions
Program Version=4.10

River Reach=UNT 108 IN BOCR ,Reach-1
Reach XY= 30
       3744844.5       10619155.        3744792.       10619276.
        3744769.       10619421.      3744709.53     10619536.29
      3744706.25       10619574.      3744672.75       10619601.
       3744673.5       10619662.      3744622.75       10619706.
      3744656.25       10619729.      3744657.25       10619744.
      3744585.75       10619789.        3744581.       10619853.
        3744532.       10619863.       3744480.5       10619975.
       3744477.5       10620002.       3744535.5       10620018.
        3744547.       10620049.       3744535.5       10620118.
       3744503.5       10620152.        3744481.       10620216.
      3744445.75       10620248.      3744435.75       10620307.
      3744348.75       10620336.        3744259.       10620470.
      3744179.68     10620533.43        3744098.       10620642.
        3743981.       10620740.        3743859.       10620759.
       3743709.5       10620741.      3743639.75       10620651.

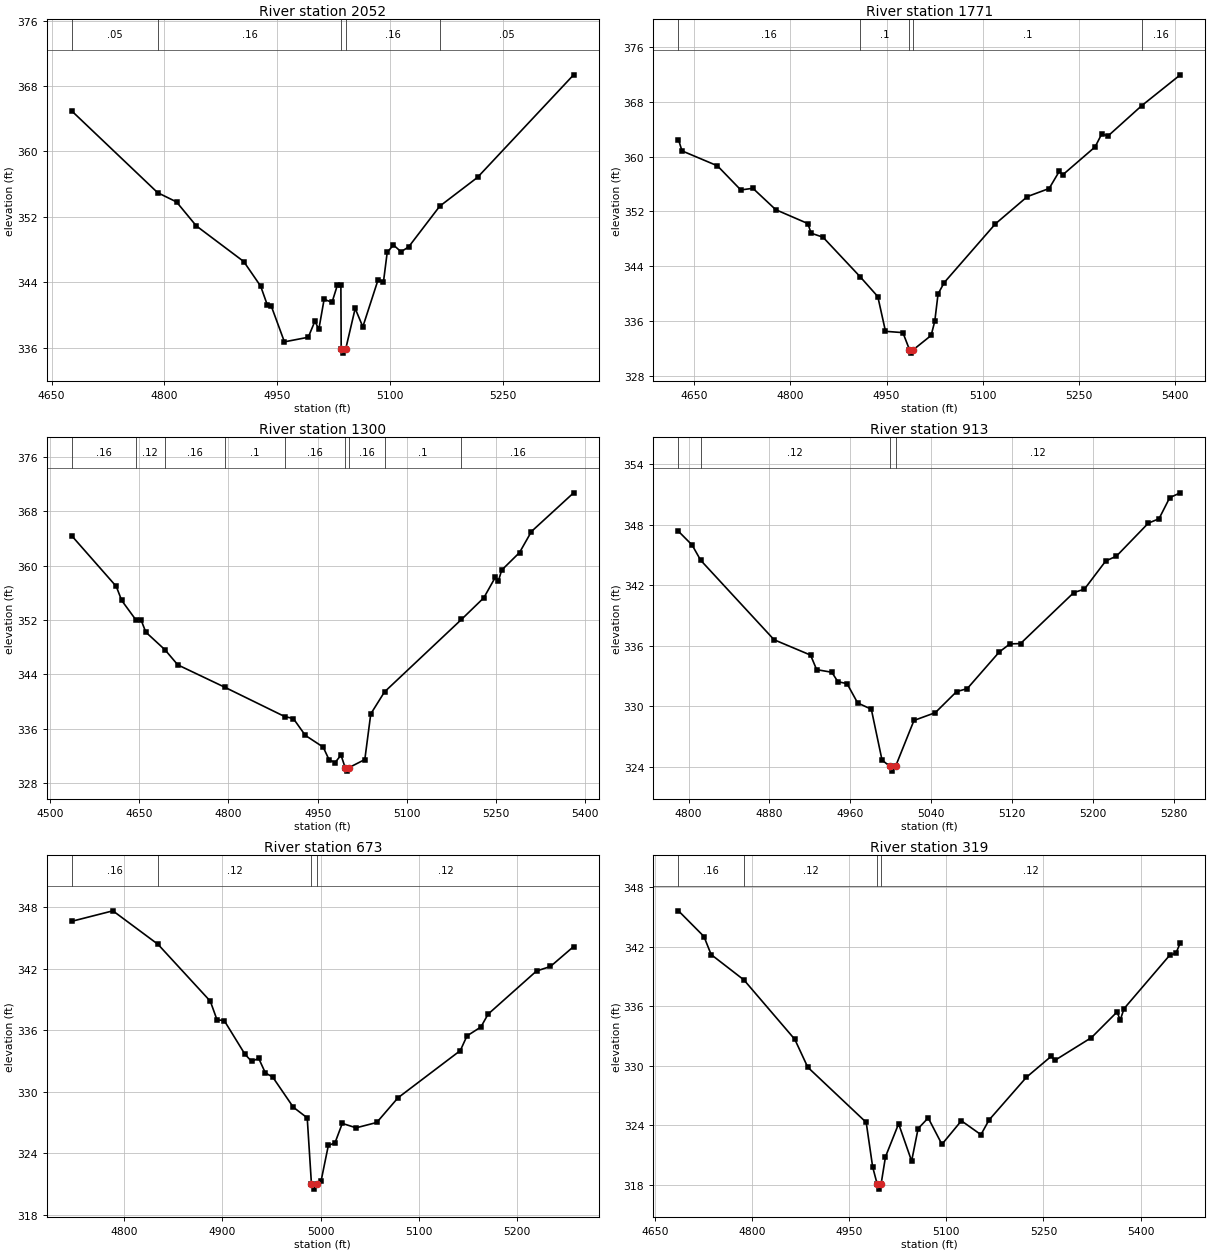
Type RM Length L Ch R = 1 ,2052    ,281,281,281
BEGIN DESCRIPTION:
Mapping XS f9813c60
END DESCRIPTION:
XS GIS Cut Line= 3
      3744401.47     10619451.24      3744737.88      10619564.1
      3745045.34     10619620.39
#Sta/Elev= 30
  4676.7  364.94  4790.9  354.95    4816  353.82  4842.3  350.89  4905.4  346.53
  4927.9  343.52  4936.9  341.18  4942.2  341.04  4959.5  336.71  4991.2  337.27
    5000  339.22  5005.3  338.26  5012.3  341.91  5022.8  341.54  5029.8   343.6
  5034.6   343.6    5035  335.83  5037.7  335.33    5041  335.83  5053.6  340.79
  5063.8  338.55  5084.1  344.31  5091.2  344.03  5096.2  347.65  5104.5  348.56
  5114.6  347.72  5124.8  348.33  5166.1   353.3  5216.3  356.82  5344.1  369.36
#Mann= 5 ,-1 , 0
  4676.7     .05       0  4790.9     .16       0    5035     .07       0
    5041     .16       0  5166.1     .05       0
Bank Sta=5035,5041
XS Rating Curve= 0 ,0
Exp/Cntr=0.3,0.1

Type RM Length L Ch R = 1 ,1771    ,471,471,471
BEGIN DESCRIPTION:
UNT 108 IN BOCR 4.0
END DESCRIPTION:
XS GIS Cut Line= 3
      3744288.68     10619633.55      3744607.67      10619752.9
      3745039.57     10619844.06
#Sta/Elev= 30
  4625.8  362.48  4631.3  360.84  4686.5  358.66  4722.9  355.14  4741.8  355.38
  4777.4  352.26  4827.3  350.24  4832.6  348.83    4851  348.25  4908.6  342.51
  4936.4  339.59  4948.4  334.52  4975.5  334.33  4985.8  331.84  4988.6  331.34
  4991.8  331.84  5019.5  333.92  5025.2     336  5030.3  339.97  5039.9  341.63
  5119.6  350.19  5169.4  354.17  5203.4  355.35  5219.2  357.86  5224.3  357.32
    5275  361.42  5285.2  363.28  5295.4  363.03  5347.5  367.42  5407.8  371.93
#Mann= 5 ,-1 , 0
  4625.8     .16       0  4908.6      .1       0  4985.8     .07       0
  4991.8      .1       0  5347.5     .16       0
Bank Sta=4985.8,4991.8
XS Rating Curve= 0 ,0
Exp/Cntr=0.3,0.1

Type RM Length L Ch R = 1 ,1300    ,387,387,387
BEGIN DESCRIPTION:
UNT 108 IN BOCR 3.0
END DESCRIPTION:
XS GIS Cut Line= 3
      3744087.19     10620013.02      3744386.65     10620091.14
      3744920.51     10620083.33
#Sta/Elev= 30
  4536.8  364.36  4611.6  356.93  4620.7  354.87  4644.1  352.07    4653  352.07
  4661.2  350.22  4693.4  347.63    4715  345.41  4794.6   342.1  4894.7  337.82
  4909.2  337.53  4929.3  335.06  4959.3  333.34  4969.3  331.47  4979.3  331.07
  4989.3  332.16  4996.3  330.31    4999  329.81  5002.3  330.31  5029.3  331.51
  5039.3  338.21  5062.4  341.44  5191.7  352.08  5229.3  355.26  5248.8   358.3
  5253.8  357.72  5259.3  359.32  5289.3   361.9  5309.3  364.99  5380.2  370.67
#Mann= 9 ,-1 , 0
  4536.8     .16       0  4644.1     .12       0  4693.4     .16       0
  4794.6      .1       0  4894.7     .16       0  4996.3     .07       0
  5002.3     .16       0  5062.4      .1       0  5191.7     .16       0
Bank Sta=4996.3,5002.3
XS Rating Curve= 0 ,0
Exp/Cntr=0.3,0.1

Type RM Length L Ch R = 1 ,913     ,240,240,240
BEGIN DESCRIPTION:
UNT 108 IN BOCR 2.0
END DESCRIPTION:
XS GIS Cut Line= 3
      3744149.61     10620260.19      3744299.61     10620360.19
       3744599.6     10620460.19
#Sta/Elev= 30
    4790  347.33  4803.5  345.97    4812  344.46  4884.6  336.59  4920.7  335.07
  4926.7  333.63  4941.7  333.37  4947.7  332.44  4956.8  332.24  4967.3  330.33
  4980.8  329.71  4991.4  324.67  4998.9  324.08  5001.7  323.58  5004.9  324.08
    5023   328.6  5044.1  329.37  5065.1  331.45  5075.7  331.75  5107.3  335.37
  5117.9  336.18  5128.4  336.21  5181.1  341.26  5191.6   341.6  5212.7  344.39
  5223.3  344.87  5254.9  348.14  5265.4  348.57    5276  350.66  5286.5  351.14
#Mann= 4 ,-1 , 0
    4790     .16       0    4812     .12       0  4998.9     .07       0
  5004.9     .12       0
Bank Sta=4998.9,5004.9
XS Rating Curve= 0 ,0
Exp/Cntr=0.3,0.1

Type RM Length L Ch R = 1 ,673     ,354,354,354
BEGIN DESCRIPTION:
Mapping XS d08b8a6c
END DESCRIPTION:
XS GIS Cut Line= 2
      3743985.42     10620375.32      3744360.45     10620722.56
#Sta/Elev= 30
  4746.5   346.6  4788.4  347.62  4834.3  344.36  4887.6  338.82  4894.4  337.01
  4901.8  336.93  4922.7  333.68  4929.6  332.96  4936.9  333.25  4943.7  331.83
  4951.1  331.44  4972.1   328.5  4986.3  327.46  4990.6  321.02  4993.4  320.52
  4996.6  321.02  5000.4  321.31  5007.8  324.77  5014.6  325.03    5022  326.92
  5036.1  326.49  5057.1  327.01  5078.7  329.41  5142.2  334.01    5149  335.44
  5163.2  336.31  5170.5  337.56  5219.8  341.76    5234   342.2  5257.6  344.14
#Mann= 4 ,-1 , 0
  4746.5     .16       0  4834.3     .12       0  4990.6     .07       0
  4996.6     .12       0
Bank Sta=4990.6,4996.6
XS Rating Curve= 0 ,0
Exp/Cntr=0.3,0.1

Type RM Length L Ch R = 1 ,319     ,0,0,0
BEGIN DESCRIPTION:
UNT 108 IN BOCR 1.0
END DESCRIPTION:
XS GIS Cut Line= 3
      3743881.26     10620430.87      3743909.04      10620816.3
      3744296.25     10620854.33
#Sta/Elev= 30
    4686  345.64  4725.4  343.05  4736.5  341.23  4787.2  338.67  4865.8  332.68
  4885.8  329.87  4976.1  324.31  4986.1  319.81  4993.1  318.08  4995.9  317.58
  4999.1  318.08  5005.9  320.84  5026.2  324.17  5046.3  320.41  5056.3  323.68
  5071.9  324.76  5093.1   322.1  5123.2  324.47  5153.4  323.07  5165.9  324.55
  5223.7  328.86  5262.3  330.99  5267.3  330.55  5324.2  332.86  5363.7  335.44
  5368.7  334.62  5374.4  335.77  5444.8  341.14  5454.8  341.38  5461.5  342.42
#Mann= 4 ,-1 , 0
    4686     .16       0  4787.2     .12       0  4993.1     .07       0
  4999.1     .12       0
Bank Sta=4993.1,4999.1
XS Rating Curve= 0 ,0
Exp/Cntr=0.3,0.1

Chan Stop Cuts=-1
Use User Specified Reach Order=0
Composite Channel Slope=5