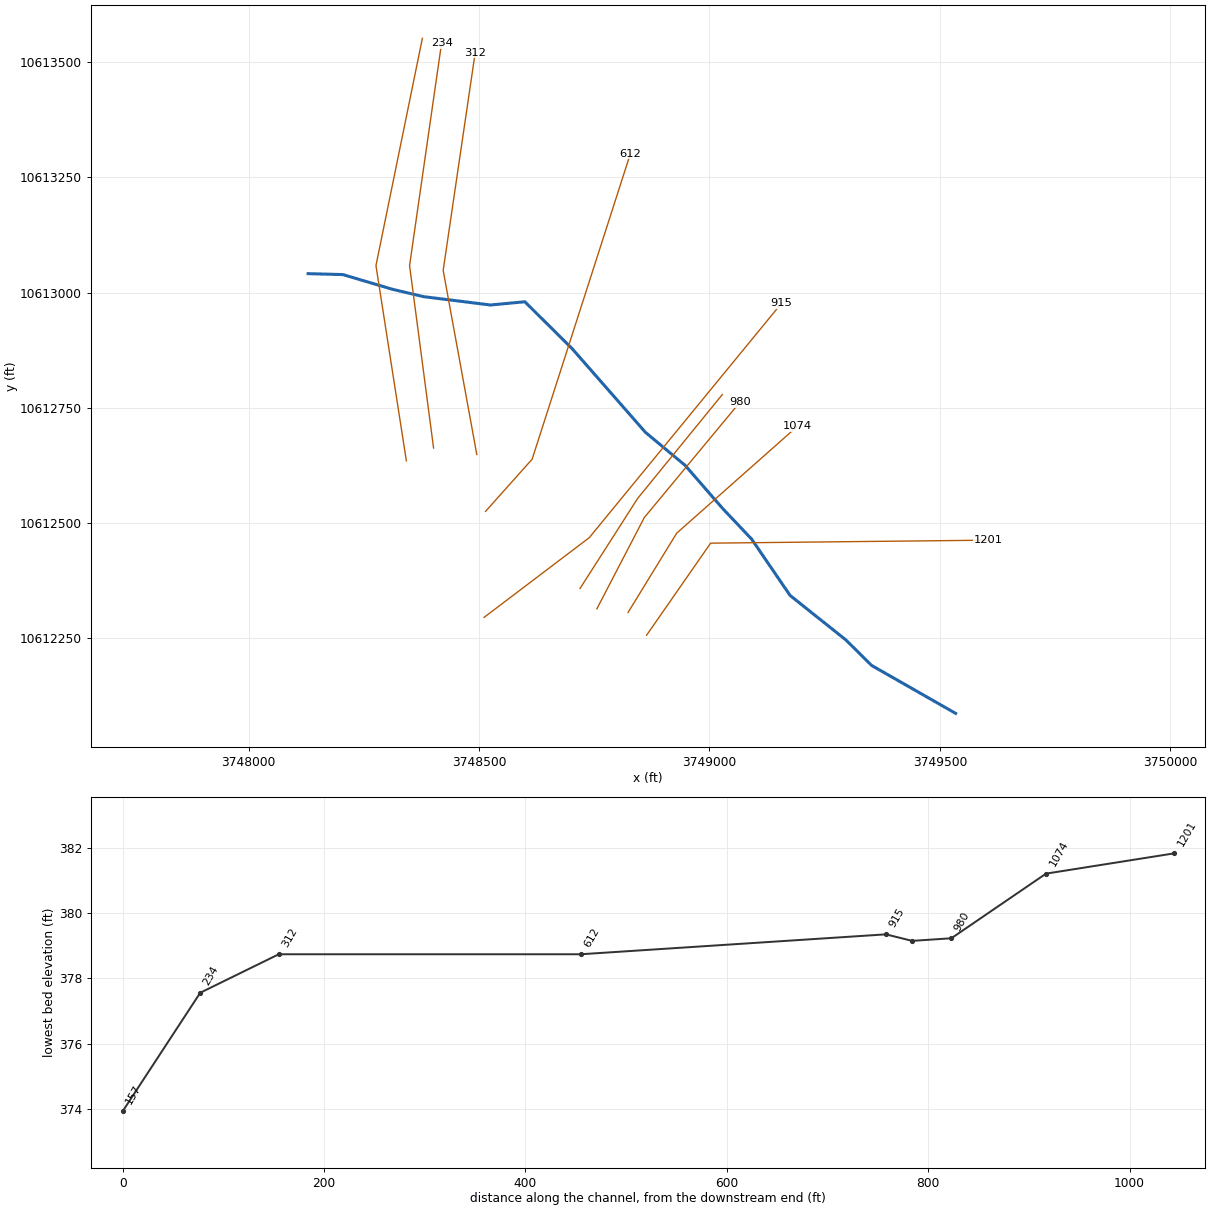
--- UNT 110 IN BOCR.prj (project) ---

Proj Title=UNT 110 IN BOCR Base Level Engineering
Current Plan=p01
Default Exp/Contr=0.3,0.1
English Units
Geom File=g01
Flow File=f01
Plan File=p01
Y Axis Title=Elevation
X Axis Title(PF)=Main Channel Distance
X Axis Title(XS)=Station
BEGIN DESCRIPTION:
UNT 110 IN BOCR
END DESCRIPTION:
DSS Export Rating Curves= 0
DSS Export Rating Curve Sorted= 0
DSS Export Volume Flow Curves= 0
DXF OffsetX= 0
DXF OffsetY= 0
DXF ScaleX= 1
DXF ScaleY= 10

--- UNT 110 IN BOCR.p01 (plan) ---

Plan Title=Multiple Run
Short Identifier=Multiple
Geom File=g01
Flow File=f01
Subcritical Flow
K Sum by GR= 0
Std Step Tol= 0.01
Critical Tol= 0.01
Num of Std Step Trials= 20
Max Error Tol= 0.3
Flow Tol Ratio= 0.001
Split Flow NTrial= 30
Split Flow Tol= 0.02
Split Flow Ratio= 0.02
Log Output Level= 0
Friction Slope Method= 1
Unsteady Friction Slope Method= 2
Unsteady Bridges Friction Slope Method= 1
Parabolic Critical Depth
Global Vel Dist=  1 , 1 , 1
Global Log Level= 0
CheckData=True
Encroach Param= -1, 0, 0, 0
BEGIN DESCRIPTION:
Multiple Run
END DESCRIPTION:

--- UNT 110 IN BOCR.f01 (steady flow) ---

Flow Title=Multiple
Program Version=4.10
Number of Profiles= 7
Profile Names=10-year,25-year,50-year,1pct_min,100-year,1pct_plu,500-year
River Rch & RM=UNT 110 IN BOCR,Reach-1         ,1201
     308     405     484     427     578     781     823
Boundary for River Rch & Prof#=UNT 110 IN BOCR,Reach-1         , 1
Up Type= 0
Dn Type= 3
Dn Slope=0.005
Boundary for River Rch & Prof#=UNT 110 IN BOCR,Reach-1         , 2
Up Type= 0
Dn Type= 3
Dn Slope=0.005
Boundary for River Rch & Prof#=UNT 110 IN BOCR,Reach-1         , 3
Up Type= 0
Dn Type= 3
Dn Slope=0.005
Boundary for River Rch & Prof#=UNT 110 IN BOCR,Reach-1         , 4
Up Type= 0
Dn Type= 3
Dn Slope=0.005
Boundary for River Rch & Prof#=UNT 110 IN BOCR,Reach-1         , 5
Up Type= 0
Dn Type= 3
Dn Slope=0.005
Boundary for River Rch & Prof#=UNT 110 IN BOCR,Reach-1         , 6
Up Type= 0
Dn Type= 3
Dn Slope=0.005
Boundary for River Rch & Prof#=UNT 110 IN BOCR,Reach-1         , 7
Up Type= 0
Dn Type= 3
Dn Slope=0.005
DSS Import GetInterval= 0
DSS Import GetPeak= 0
DSS Import FillOption= 0

--- UNT 110 IN BOCR.g01 (geometry) ---

Geom Title=Existing Conditions

River Reach=UNT 110 IN BOCR,Reach-1
Reach XY= 15
      3749534.00     10612087.00      3749351.75     10612191.00
      3749296.25     10612246.00      3749174.75     10612343.00
      3749091.50     10612465.00      3749029.00     10612531.00
      3748947.25     10612625.00      3748860.75     10612697.00
      3748702.25     10612878.00      3748599.50     10612980.00
      3748524.75     10612973.00      3748380.25     10612991.00
      3748312.50     10613007.00      3748204.50     10613039.00
      3748129.25     10613041.00

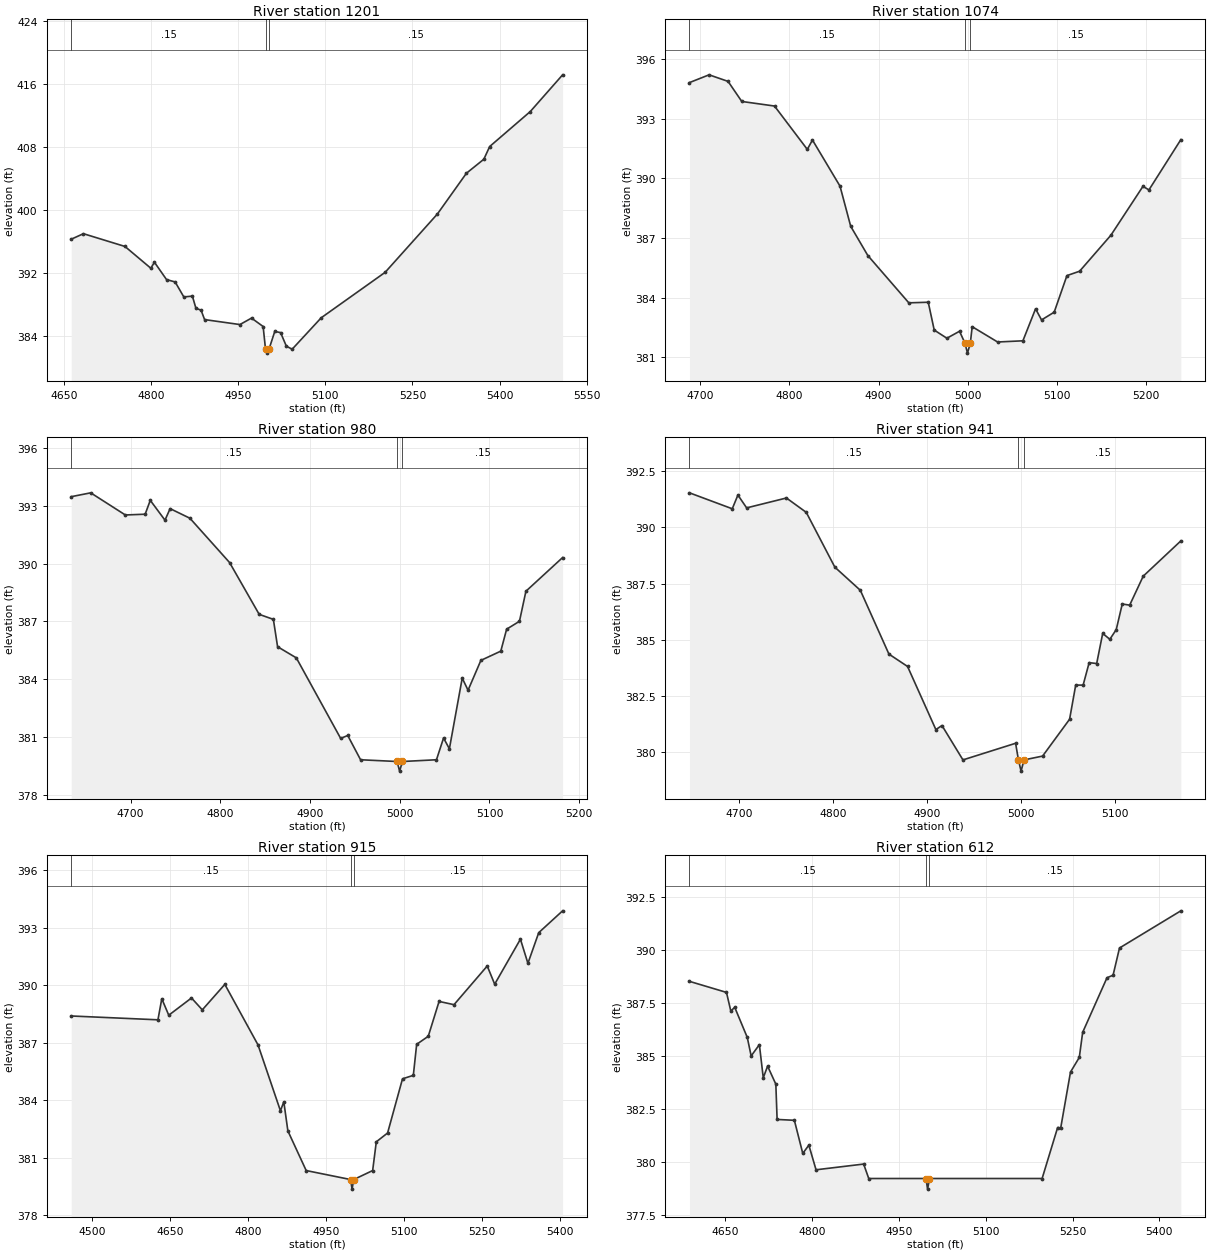
Type RM Length L Ch R = 1,1201,127,127,127
BEGIN DESCRIPTION:
UNT 110 IN BOCR 3.0
END DESCRIPTION:
XS GIS Cut Line= 3
      3748863.58     10612256.63      3749002.48     10612456.30
      3749605.21     10612462.80
#Sta/Elev= 30
  4662.5  396.30  4683.5  397.00  4755.0  395.38  4799.6  392.61  4805.7  393.38
  4826.6  391.17  4841.4  390.87  4856.3  388.97  4871.1  389.07  4877.2  387.52
  4886.0  387.29  4892.1  386.09  4952.9  385.46  4972.9  386.28  4992.9  385.21
  4997.0  382.33  4999.8  381.83  5003.0  382.33  5012.9  384.58  5022.9  384.44
  5032.9  382.71  5042.9  382.33  5092.9  386.32  5202.9  392.09  5292.9  399.50
  5342.9  404.68  5372.9  406.46  5382.9  408.07  5452.9  412.52  5508.5  417.18
#Mann=3,-1,0
  4662.5    0.15       0  4997.0    0.05       0  5003.0    0.15       0
Bank Sta=4997,5003
Exp/Cntr=0.3,0.1

Type RM Length L Ch R = 1,1074,94,94,94
BEGIN DESCRIPTION:
Mapping XS fae3663f
END DESCRIPTION:
XS GIS Cut Line= 3
      3748823.36     10612306.01      3748928.85     10612477.92
      3749190.58     10612709.70
#Sta/Elev= 30
  4687.9  394.82  4709.9  395.21  4731.2  394.88  4746.6  393.87  4783.3  393.64
  4820.1  391.46  4825.9  391.93  4856.8  389.61  4868.8  387.59  4888.0  386.12
  4934.0  383.74  4955.8  383.77  4962.5  382.37  4976.7  381.96  4990.9  382.31
  4997.0  381.71  4999.8  381.21  5003.0  381.71  5005.1  382.54  5033.6  381.77
  5062.0  381.83  5076.2  383.44  5082.9  382.88  5097.1  383.27  5111.4  385.11
  5125.6  385.33  5160.7  387.14  5196.7  389.60  5203.4  389.42  5239.2  391.95
#Mann=3,-1,0
  4687.9    0.15       0  4997.0    0.05       0  5003.0    0.15       0
Bank Sta=4997,5003
Exp/Cntr=0.3,0.1

Type RM Length L Ch R = 1,980,39,39,39
BEGIN DESCRIPTION:
Mapping XS 47b725de
END DESCRIPTION:
XS GIS Cut Line= 3
      3748755.67     10612313.85      3748858.54     10612511.78
      3749065.72     10612761.70
#Sta/Elev= 30
  4633.8  393.48  4655.5  393.68  4694.1  392.53  4716.2  392.57  4721.9  393.29
  4738.3  392.26  4744.0  392.86  4766.1  392.36  4810.3  390.06  4843.3  387.37
  4859.1  387.11  4863.8  385.69  4884.7  385.11  4934.1  380.93  4942.0  381.08
  4956.3  379.82  4997.0  379.73  4999.8  379.23  5003.0  379.73  5040.9  379.82
  5048.8  380.95  5055.3  380.39  5069.6  384.06  5076.1  383.43  5090.4  384.98
  5112.6  385.46  5119.1  386.60  5133.4  387.01  5140.6  388.57  5181.5  390.32
#Mann=3,-1,0
  4633.8    0.15       0  4997.0    0.05       0  5003.0    0.15       0
Bank Sta=4997,5003
Exp/Cntr=0.3,0.1

Type RM Length L Ch R = 1,941,26,26,26
BEGIN DESCRIPTION:
Mapping XS d2367117
END DESCRIPTION:
XS GIS Cut Line= 3
      3748719.22     10612358.14      3748844.21     10612553.44
      3749027.82     10612778.72
#Sta/Elev= 30
  4647.2  391.54  4692.7  390.83  4698.7  391.44  4708.0  390.87  4750.3  391.31
  4771.4  390.67  4801.8  388.23  4828.9  387.20  4859.3  384.36  4879.1  383.81
  4909.2  381.00  4915.7  381.18  4938.0  379.65  4994.0  380.39  4997.0  379.65
  4999.8  379.15  5003.0  379.65  5022.7  379.82  5051.4  381.46  5057.9  382.98
  5065.8  382.98  5072.2  383.98  5080.2  383.94  5086.6  385.28  5094.2  385.02
  5101.0  385.45  5107.4  386.59  5115.3  386.54  5129.7  387.83  5169.7  389.40
#Mann=3,-1,0
  4647.2    0.15       0  4997.0    0.05       0  5003.0    0.15       0
Bank Sta=4997,5003
Exp/Cntr=0.3,0.1

Type RM Length L Ch R = 1,915,303,303,303
BEGIN DESCRIPTION:
Mapping XS 17c44a95
END DESCRIPTION:
XS GIS Cut Line= 3
      3748510.86     10612295.18      3748739.10     10612468.13
      3749156.59     10612977.16
#Sta/Elev= 30
  4459.9  388.39  4626.6  388.19  4634.0  389.29  4647.4  388.43  4691.1  389.33
  4711.9  388.71  4755.2  390.04  4819.0  386.88  4862.1  383.44  4868.6  383.91
  4876.4  382.39  4911.6  380.32  4997.0  379.85  4999.8  379.35  5003.0  379.85
  5039.4  380.32  5046.4  381.82  5068.1  382.28  5096.8  385.11  5117.6  385.29
  5124.0  386.91  5146.3  387.33  5167.1  389.15  5195.8  388.98  5259.7  391.00
  5274.0  390.05  5323.5  392.40  5337.9  391.14  5358.7  392.74  5404.6  393.88
#Mann=3,-1,0
  4459.9    0.15       0  4997.0    0.05       0  5003.0    0.15       0
Bank Sta=4997,5003
Exp/Cntr=0.3,0.1

Type RM Length L Ch R = 1,612,300,300,300
BEGIN DESCRIPTION:
UNT 110 IN BOCR 2.0
END DESCRIPTION:
XS GIS Cut Line= 3
      3748514.14     10612525.24      3748615.20     10612638.38
      3748828.47     10613301.53
#Sta/Elev= 30
  4588.7  388.52  4652.6  388.00  4660.1  387.12  4666.8  387.30  4688.5  385.88
  4695.2  385.01  4709.4  385.54  4716.1  383.98  4723.6  384.53  4737.8  383.68
  4740.0  382.02  4769.8  381.98  4784.3  380.42  4794.8  380.81  4807.2  379.65
  4889.4  379.92  4898.2  379.24  4997.0  379.24  4999.8  378.74  5003.0  379.24
  5197.5  379.24  5224.3  381.64  5229.6  381.62  5246.5  384.25  5261.7  384.94
  5267.5  386.12  5309.5  388.69  5320.0  388.81  5331.1  390.09  5437.0  391.84
#Mann=3,-1,0
  4588.7    0.15       0  4997.0    0.05       0  5003.0    0.15       0
Bank Sta=4997,5003
Exp/Cntr=0.3,0.1

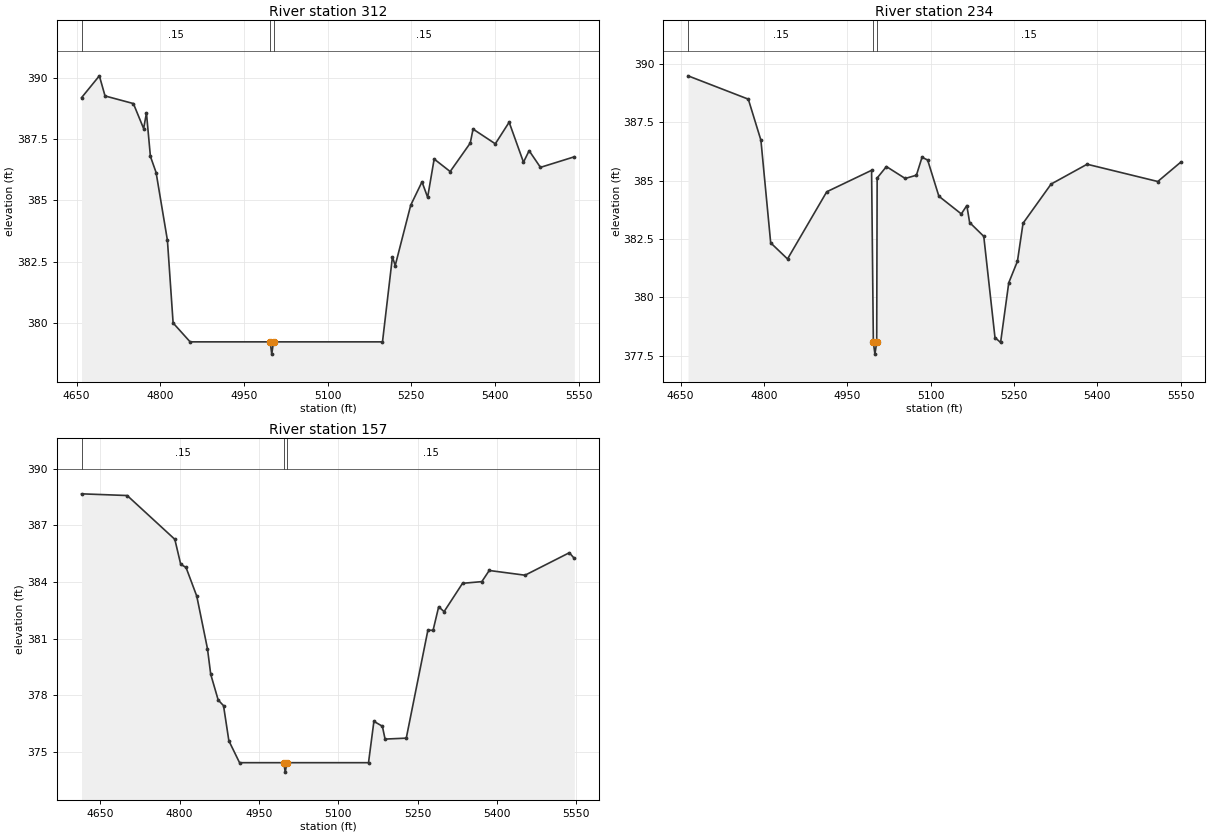
Type RM Length L Ch R = 1,312,78,78,78
BEGIN DESCRIPTION:
Mapping XS fb810b94
END DESCRIPTION:
XS GIS Cut Line= 3
      3748495.15     10612648.77      3748422.23     10613048.08
      3748491.67     10613520.29
#Sta/Elev= 30
  4658.9  389.19  4690.8  390.08  4701.0  389.26  4751.8  388.95  4770.2  387.93
  4775.2  388.57  4782.3  386.80  4792.5  386.14  4812.8  383.38  4823.0  380.01
  4853.5  379.24  4997.0  379.24  4999.8  378.74  5003.0  379.24  5198.3  379.24
  5216.1  382.70  5221.1  382.35  5248.9  384.81  5269.1  385.76  5279.2  385.13
  5290.9  386.69  5319.6  386.18  5355.6  387.34  5360.6  387.91  5400.5  387.31
  5425.3  388.19  5451.0  386.56  5461.1  387.03  5481.4  386.35  5542.1  386.78
#Mann=3,-1,0
  4658.9    0.15       0  4997.0    0.05       0  5003.0    0.15       0
Bank Sta=4997,5003
Exp/Cntr=0.3,0.1

Type RM Length L Ch R = 1,234,77,77,77
BEGIN DESCRIPTION:
Mapping XS 8405c0f6
END DESCRIPTION:
XS GIS Cut Line= 3
      3748401.40     10612662.65      3748349.31     10613058.50
      3748418.76     10613541.17
#Sta/Elev= 30
  4663.4  389.49  4771.9  388.49  4794.6  386.73  4812.2  382.33  4842.5  381.64
  4913.1  384.52  4993.8  385.44  4997.0  378.06  4999.8  377.56  5003.0  378.06
  5003.8  385.11  5020.5  385.60  5054.3  385.09  5074.5  385.23  5084.6  386.00
  5094.7  385.88  5114.9  384.33  5155.3  383.57  5165.2  383.93  5170.3  383.20
  5195.7  382.61  5215.9  378.27  5226.0  378.06  5240.7  380.62  5256.3  381.54
  5266.4  383.17  5316.9  384.85  5381.7  385.70  5508.9  384.96  5550.3  385.79
#Mann=3,-1,0
  4663.4    0.15       0  4997.0    0.05       0  5003.0    0.15       0
Bank Sta=4997,5003
Exp/Cntr=0.3,0.1

Type RM Length L Ch R = 1,157,0,0,0
BEGIN DESCRIPTION:
UNT 110 IN BOCR 1.0
END DESCRIPTION:
XS GIS Cut Line= 3
      3748342.37     10612634.91      3748276.40     10613058.50
      3748377.09     10613551.53
#Sta/Elev= 30
  4614.6  388.67  4700.9  388.58  4791.0  386.26  4802.1  384.94  4812.2  384.77
  4832.5  383.25  4852.7  380.47  4858.9  379.11  4873.0  377.75  4883.1  377.45
  4893.2  375.59  4913.4  374.43  4997.0  374.43  4999.8  373.93  5003.0  374.43
  5157.3  374.43  5167.5  376.62  5183.5  376.36  5188.6  375.68  5228.7  375.73
  5269.6  381.45  5279.4  381.44  5290.0  382.69  5300.2  382.43  5335.1  383.93
  5371.6  384.02  5385.6  384.61  5453.3  384.36  5537.1  385.55  5546.5  385.25
#Mann=3,-1,0
  4614.6    0.15       0  4997.0    0.05       0  5003.0    0.15       0
Bank Sta=4997,5003
Exp/Cntr=0.3,0.1

Chan Stop Cuts=-1