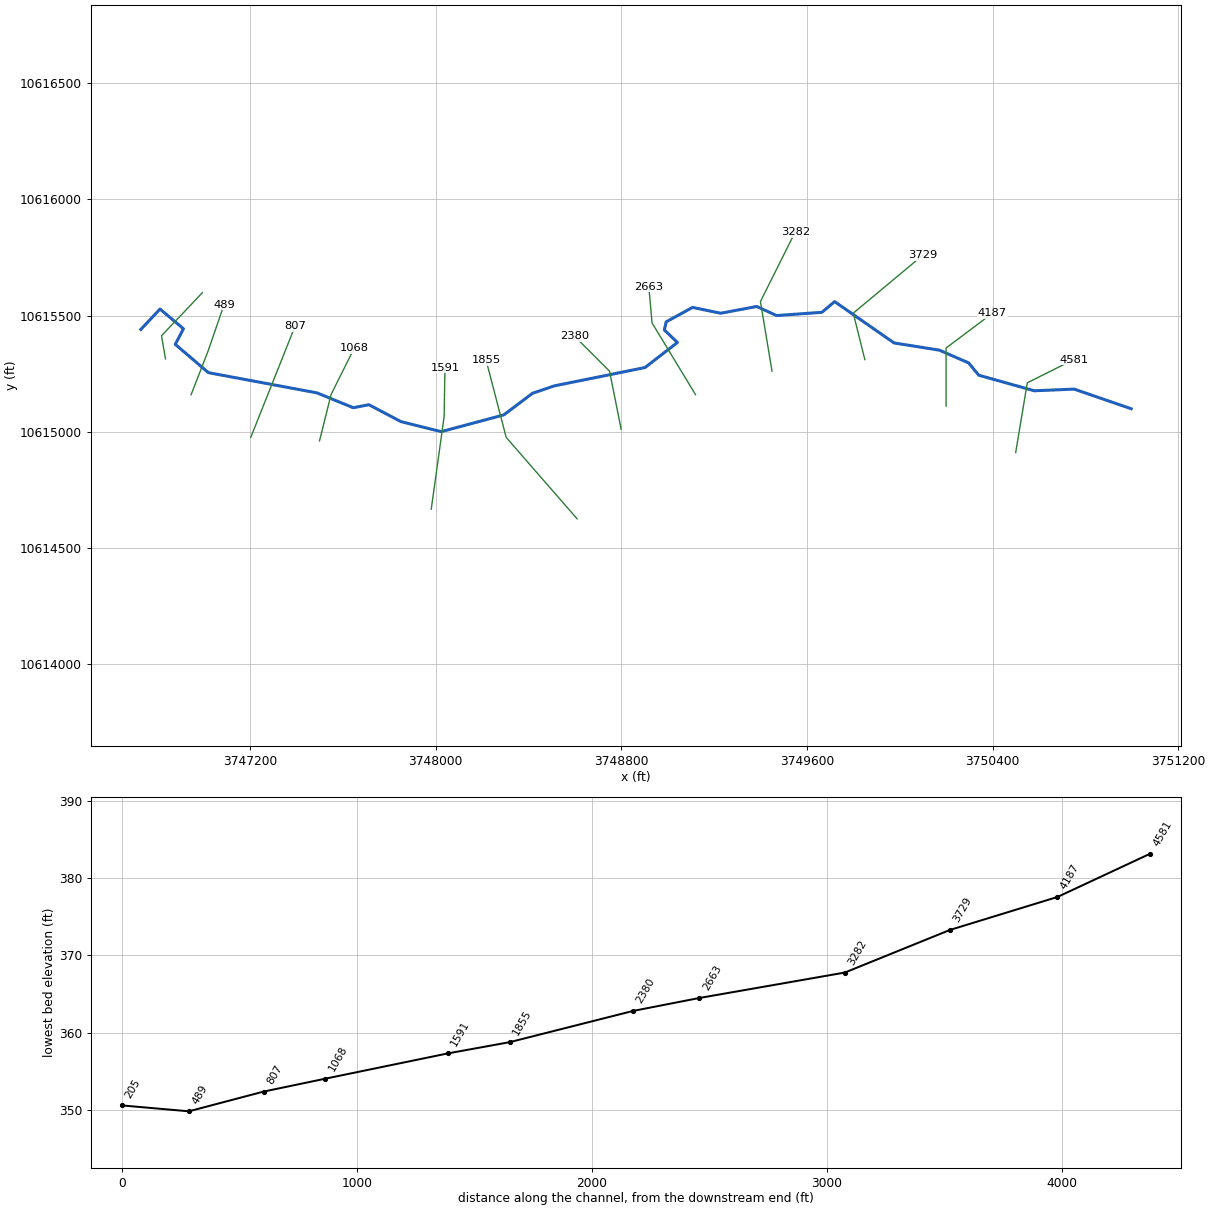
--- UNT 111 IN BOCR.prj (project) ---

Proj Title=UNT 111 IN BOCR Base Level Engineering
Current Plan=p01
Default Exp/Contr=0.3,0.1
English Units
Geom File=g01
Flow File=f01
Plan File=p01
Y Axis Title=Elevation
X Axis Title(PF)=Main Channel Distance
X Axis Title(XS)=Station
BEGIN DESCRIPTION:
UNT 111 IN BOCR
END DESCRIPTION:
DSS Export Rating Curves= 0
DSS Export Rating Curve Sorted= 0
DSS Export Volume Flow Curves= 0
DXF OffsetX= 0
DXF OffsetY= 0
DXF ScaleX= 1
DXF ScaleY= 10

--- UNT 111 IN BOCR.p01 (plan) ---

Plan Title=Multiple Run
Short Identifier=Multiple
Geom File=g01
Flow File=f01
Subcritical Flow
K Sum by GR= 0
Std Step Tol= 0.01
Critical Tol= 0.01
Num of Std Step Trials= 20
Max Error Tol= 0.3
Flow Tol Ratio= 0.001
Split Flow NTrial= 30
Split Flow Tol= 0.02
Split Flow Ratio= 0.02
Log Output Level= 0
Friction Slope Method= 1
Unsteady Friction Slope Method= 2
Unsteady Bridges Friction Slope Method= 1
Parabolic Critical Depth
Global Vel Dist=  1 , 1 , 1
Global Log Level= 0
CheckData=True
Encroach Param= -1, 0, 0, 0
BEGIN DESCRIPTION:
Multiple Run
END DESCRIPTION:

--- UNT 111 IN BOCR.f01 (steady flow) ---

Flow Title=Multiple
Number of Profiles=7
Profile Names=10-year,25-year,50-year,1pct_min,100-year,1pct_plu,500-year
River Rch & RM= UNT 111 IN BOCR,Reach-1,4581
     623     856    1052     952    1288    1742    1935
Boundary for River Rch & Prof#=UNT 111 IN BOCR,Reach-1,1
Up Type=0
Dn Type=3
Dn Slope=0.005
Boundary for River Rch & Prof#=UNT 111 IN BOCR,Reach-1,2
Up Type=0
Dn Type=3
Dn Slope=0.005
Boundary for River Rch & Prof#=UNT 111 IN BOCR,Reach-1,3
Up Type=0
Dn Type=3
Dn Slope=0.005
Boundary for River Rch & Prof#=UNT 111 IN BOCR,Reach-1,4
Up Type=0
Dn Type=3
Dn Slope=0.005
Boundary for River Rch & Prof#=UNT 111 IN BOCR,Reach-1,5
Up Type=0
Dn Type=3
Dn Slope=0.005
Boundary for River Rch & Prof#=UNT 111 IN BOCR,Reach-1,6
Up Type=0
Dn Type=3
Dn Slope=0.005
Boundary for River Rch & Prof#=UNT 111 IN BOCR,Reach-1,7
Up Type=0
Dn Type=3
Dn Slope=0.005

--- UNT 111 IN BOCR.g01 (geometry) ---

Geom Title=Existing Conditions
Program Version=4.10

River Reach=UNT 111 IN BOCR ,Reach-1
Reach XY= 30
      3750997.54     10615098.52      3750751.45     10615183.16
      3750579.75       10615176.       3750340.5       10615243.
      3750296.75       10615296.       3750170.5       10615351.
       3749975.5       10615382.       3749719.5       10615560.
      3749664.75       10615514.      3749469.25       10615500.
      3749383.75       10615539.       3749228.5       10615510.
      3749107.25       10615535.      3748993.75       10615473.
      3748985.75       10615438.        3749042.       10615384.
      3748902.25       10615276.        3748511.       10615197.
      3748417.25       10615165.      3748293.75       10615072.
      3748024.25       10615000.        3747851.       10615043.
      3747712.25       10615116.      3747645.25       10615103.
       3747488.5       10615167.        3747021.       10615254.
      3746878.25       10615376.       3746913.5       10615443.
       3746812.5       10615528.      3746729.75       10615440.

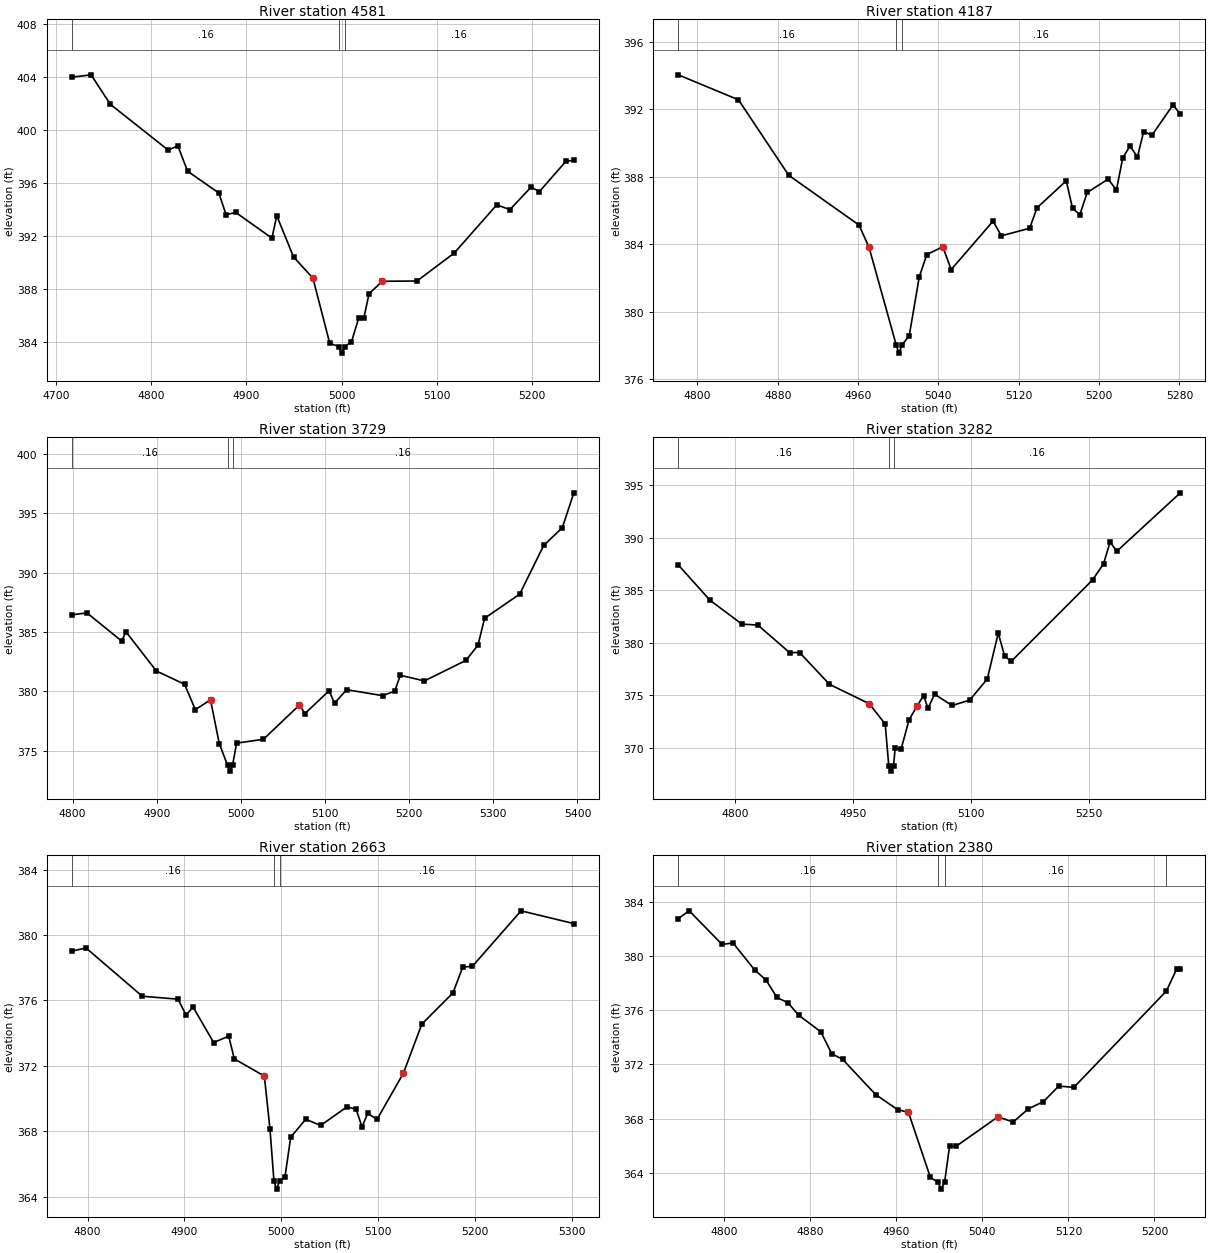
Type RM Length L Ch R = 1 ,4581    ,394,394,394
BEGIN DESCRIPTION:
UNT 111 IN BOCR 10.0
END DESCRIPTION:
XS GIS Cut Line= 3
       3750499.6     10614910.16      3750549.61     10615210.19
      3750749.64      10615310.2
#Sta/Elev= 30
  4716.4  403.98  4736.7  404.16    4757  401.93  4817.8  398.47  4827.9   398.8
  4838.1  396.88    4871  395.23  4878.6  393.59  4888.8  393.76  4926.8  391.82
  4931.9  393.51  4949.6  390.39  4969.9   388.8  4987.6  383.87  4997.3  383.63
    5000  383.13  5003.3  383.63  5010.4  383.97    5018  385.77  5023.4  385.77
  5028.9  387.62  5042.9  388.56  5079.3  388.58  5118.4  390.69  5163.1  394.33
  5177.1  393.98  5199.4  395.69  5207.8  395.32  5235.8  397.62  5244.2  397.71
#Mann= 3 ,-1 , 0
  4716.4     .16       0  4997.3     .07       0  5003.3     .16       0
Bank Sta=4969.9,5042.9
XS Rating Curve= 0 ,0
Exp/Cntr=0.3,0.1

Type RM Length L Ch R = 1 ,4187    ,458,458,458
BEGIN DESCRIPTION:
UNT 111 IN BOCR 9.0
END DESCRIPTION:
XS GIS Cut Line= 3
      3750199.61     10615110.22      3750199.61     10615360.19
      3750399.63     10615510.21
#Sta/Elev= 30
  4780.9  394.03  4840.9  392.55  4890.9  388.08  4960.9  385.13  4970.9  383.81
  4997.9  378.04  5000.6  377.54  5003.9  378.04  5010.9  378.56  5020.9  382.05
  5028.4  383.38  5044.4  383.84  5052.7  382.49  5094.4  385.36  5102.7  384.49
  5130.9  384.94  5138.2  386.15  5167.3  387.75  5173.6  386.11  5180.9  385.75
  5188.2  387.06    5209  387.85  5217.3  387.21  5223.6  389.12  5230.9  389.81
  5238.2  389.16  5244.4  390.67  5252.7  390.45  5273.6  392.25  5280.9   391.7
#Mann= 3 ,-1 , 0
  4780.9     .16       0  4997.9     .07       0  5003.9     .16       0
Bank Sta=4970.9,5044.4
XS Rating Curve= 0 ,0
Exp/Cntr=0.3,0.1

Type RM Length L Ch R = 1 ,3729    ,447,447,447
BEGIN DESCRIPTION:
UNT 111 IN BOCR 8.0
END DESCRIPTION:
XS GIS Cut Line= 3
      3749849.61     10615310.17      3749799.61     10615510.19
      3750099.62      10615760.2
#Sta/Elev= 30
    4799  386.44  4817.1   386.6  4858.3  384.23  4863.4  385.01  4899.5  381.71
    4933  380.59  4945.9  378.45  4963.9  379.28  4974.3  375.59  4984.1  373.77
  4986.9  373.27  4990.1  373.77  4994.9  375.63  5026.7  375.95  5069.6  378.84
  5076.1  378.12  5104.8  380.04  5111.3  378.99  5125.6  380.13  5168.5  379.63
  5182.9  380.01  5189.4  381.35    5218  380.87  5267.5   382.6  5281.8  383.89
  5289.6  386.15  5331.3  388.18  5359.9  392.29    5382  393.78  5395.7  396.72
#Mann= 3 ,-1 , 0
    4799     .16       0  4984.1     .07       0  4990.1     .16       0
Bank Sta=4963.9,5069.6
XS Rating Curve= 0 ,0
Exp/Cntr=0.3,0.1

Type RM Length L Ch R = 1 ,3282    ,619,619,619
BEGIN DESCRIPTION:
UNT 111 IN BOCR 7.0
END DESCRIPTION:
XS GIS Cut Line= 3
      3749449.61     10615260.19      3749399.61     10615560.19
      3749549.59     10615860.15
#Sta/Elev= 30
  4727.1  387.43  4767.6  384.05  4808.2  381.78  4828.5  381.69    4869  379.06
  4881.7  379.07  4919.7  376.04  4970.4  374.19  4990.7  372.25  4995.3  368.26
    4998  367.76  5001.3  368.26  5003.4  369.94    5011  369.86  5021.1  372.66
  5031.2  373.95  5039.6  374.97  5045.2  373.75  5053.6  375.09    5076  374.02
  5098.3  374.53  5120.7  376.54  5134.7  380.92    5143   378.7  5151.4  378.24
  5254.8  385.99  5268.8  387.53  5277.2  389.62  5285.6  388.72  5366.6   394.3
#Mann= 3 ,-1 , 0
  4727.1     .16       0  4995.3     .07       0  5001.3     .16       0
Bank Sta=4970.4,5031.2
XS Rating Curve= 0 ,0
Exp/Cntr=0.3,0.1

Type RM Length L Ch R = 1 ,2663    ,283,283,283
BEGIN DESCRIPTION:
UNT 111 IN BOCR 6.0
END DESCRIPTION:
XS GIS Cut Line= 3
      3749120.14     10615159.21      3748932.65     10615468.22
      3748918.76     10615624.47
#Sta/Elev= 30
  4783.7  379.02  4798.4  379.21  4856.5  376.26  4893.4  376.08  4901.8   375.1
  4908.8  375.61  4930.2  373.43  4945.7  373.82  4951.5  372.43  4982.5  371.38
  4988.3  368.15  4992.4  364.97  4995.1  364.47  4998.4  364.97  5003.8  365.22
  5009.7  367.64  5025.2  368.74  5040.6  368.36  5067.8   369.5  5077.3  369.35
  5083.3  368.27  5089.2   369.1  5098.8  368.73    5126  371.55  5145.1  374.56
  5177.2  376.46  5187.3  378.04  5197.3  378.09  5247.5  381.48    5302   380.7
#Mann= 3 ,-1 , 0
  4783.7     .16       0  4992.4     .07       0  4998.4     .16       0
Bank Sta=4982.5,5126
XS Rating Curve= 0 ,0
Exp/Cntr=0.3,0.1

Type RM Length L Ch R = 1 ,2380    ,525,525,525
BEGIN DESCRIPTION:
UNT 111 IN BOCR 5.0
END DESCRIPTION:
XS GIS Cut Line= 3
      3748799.62     10615010.15      3748749.61     10615260.19
      3748599.62     10615410.17
#Sta/Elev= 30
    4757  382.75  4767.2  383.32  4797.8  380.84    4808  380.95  4828.4  378.93
  4838.6  378.23  4848.8  376.93    4859  376.54  4869.2  375.61  4889.6   374.4
  4899.8  372.78    4910  372.36  4940.6  369.77    4961  368.66  4971.2  368.45
  4991.6  363.65  4998.8  363.29  5001.5  362.79  5004.8  363.29  5009.4  365.95
  5015.5  365.95  5054.4  368.12  5068.6  367.74  5082.7  368.71  5096.8  369.25
    5111  370.39  5125.1   370.3    5211  377.39  5220.6     379  5224.1     379
#Mann= 4 ,-1 , 0
    4757     .16       0  4998.8     .07       0  5004.8     .16       0
    5211     .12       0
Bank Sta=4971.2,5054.4
XS Rating Curve= 0 ,0
Exp/Cntr=0.3,0.1

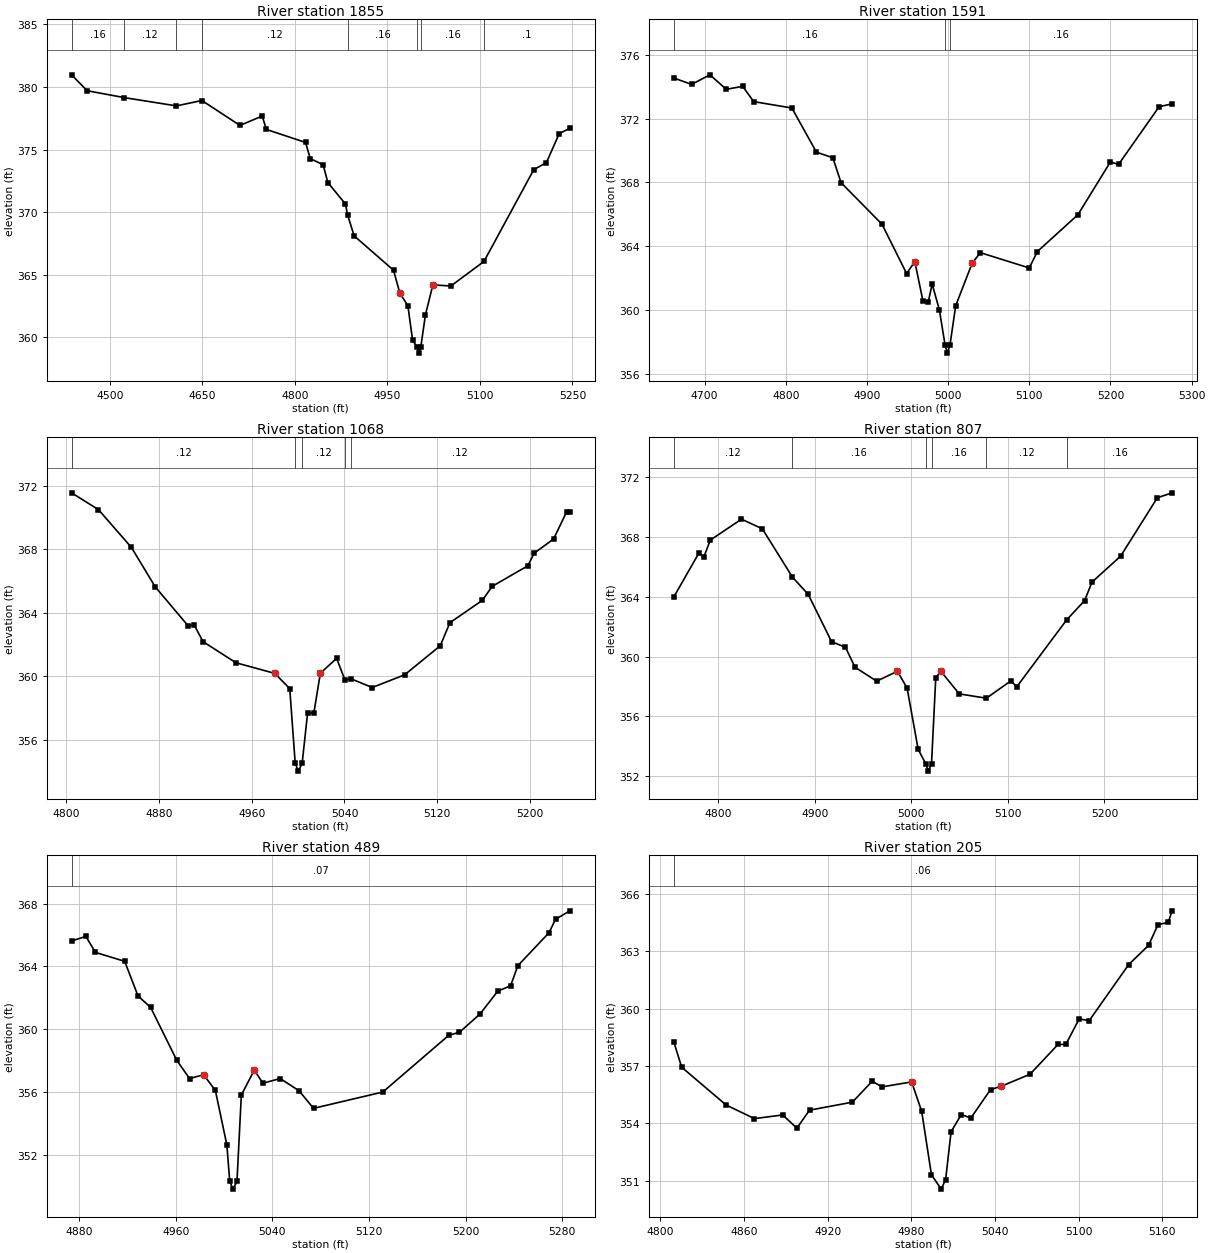
Type RM Length L Ch R = 1 ,1855    ,264,264,264
BEGIN DESCRIPTION:
Mapping XS 28508c19
END DESCRIPTION:
XS GIS Cut Line= 3
      3748609.74     10614624.46      3748304.17     10614975.17
       3748217.8     10615306.85
#Sta/Elev= 30
  4437.9  380.97  4463.2   379.7  4523.4  379.15  4607.9  378.49  4649.2  378.92
  4710.9  376.93    4747  377.68  4753.7  376.61  4817.3  375.57  4824.9  374.28
  4845.8  373.79  4853.4  372.37  4881.9  370.66  4885.6  369.76  4896.1  368.11
  4959.9  365.37  4970.2  363.54  4983.2  362.53  4990.9  359.77  4998.2  359.25
    5001  358.75  5004.2  359.25  5011.6  361.79  5023.7   364.2  5052.9  364.11
  5106.6  366.07  5187.2  373.39  5207.9  373.97  5228.6  376.28  5245.8   376.7
#Mann= 8 ,-1 , 0
  4437.9     .16       0  4523.4     .12       0  4607.9      .1       0
  4649.2     .12       0  4885.6     .16       0  4998.2     .07       0
  5004.2     .16       0  5106.6      .1       0
Bank Sta=4970.2,5023.7
XS Rating Curve= 0 ,0
Exp/Cntr=0.3,0.1

Type RM Length L Ch R = 1 ,1591    ,523,523,523
BEGIN DESCRIPTION:
Mapping XS b36d9fa7
END DESCRIPTION:
XS GIS Cut Line= 3
      3747981.26     10614666.16      3748036.81     10615065.45
      3748040.27     10615276.18
#Sta/Elev= 30
    4662  374.54  4683.8  374.14  4706.5  374.74  4726.6  373.83  4746.8  374.02
  4760.4  373.06  4807.4  372.66  4837.7  369.89  4857.9  369.54    4868  367.98
  4918.5  365.37  4948.8  362.28  4958.9  363.03    4969  360.54  4975.3  360.47
  4980.3  361.62  4989.2  359.99  4996.2  357.79    4999  357.29  5002.2  357.79
  5009.3  360.27  5029.5  362.92  5039.6  363.59  5099.9  362.63  5109.9  363.66
  5159.9  365.97  5199.9  369.28  5209.9  369.12  5259.9  372.74  5275.9  372.92
#Mann= 3 ,-1 , 0
    4662     .16       0  4996.2     .07       0  5002.2     .16       0
Bank Sta=4958.9,5029.5
XS Rating Curve= 0 ,0
Exp/Cntr=0.3,0.1

Type RM Length L Ch R = 1 ,1068    ,261,261,261
BEGIN DESCRIPTION:
UNT 111 IN BOCR 2.0
END DESCRIPTION:
XS GIS Cut Line= 3
       3747499.6     10614960.14      3747549.61     10615160.19
      3747649.61     10615360.18
#Sta/Elev= 30
  4804.6  371.55  4827.8  370.49  4856.2  368.11  4876.8  365.62  4905.1  363.17
  4910.3  363.23    4918  362.17  4946.4  360.84  4979.9  360.17  4992.8  359.21
  4997.5  354.51  5000.2  354.01  5003.5  354.51  5008.2  357.68  5013.6  357.68
  5019.2  360.18  5033.2  361.12  5040.5  359.74  5045.3  359.84  5063.9  359.28
  5091.9  360.08  5122.6  361.91    5131  363.37  5158.9  364.77  5167.3  365.65
  5198.1  366.95  5203.7  367.75  5220.4  368.64  5231.6  370.35  5234.4  370.35
#Mann= 5 ,-1 , 0
  4804.6     .12       0  4997.5     .07       0  5003.5     .12       0
  5040.5     .16       0  5045.3     .12       0
Bank Sta=4979.9,5019.2
XS Rating Curve= 0 ,0
Exp/Cntr=0.3,0.1

Type RM Length L Ch R = 1 ,807     ,318,318,318
BEGIN DESCRIPTION:
Mapping XS 4c6c150a
END DESCRIPTION:
XS GIS Cut Line= 2
      3747203.47     10614975.13      3747394.47     10615454.37
#Sta/Elev= 30
  4754.2  363.99    4780   366.9  4785.4  366.67  4791.9  367.78  4824.2  369.18
  4845.8  368.54    4877  365.31  4893.3  364.16  4917.5     361  4931.9  360.62
  4941.8  359.29  4964.2  358.36  4985.7  359.02  4995.7   357.9  5007.2   353.8
    5015  352.85  5017.7  352.35    5021  352.85  5025.4   358.6  5030.8  359.01
  5049.7  357.51  5077.8  357.22  5103.6   358.4    5109  357.96    5161  362.46
  5179.5  363.74  5187.2  364.98  5216.8  366.71  5254.8  370.61  5270.1  370.94
#Mann= 6 ,-1 , 0
  4754.2     .12       0    4877     .16       0    5015     .07       0
    5021     .16       0  5077.8     .12       0    5161     .16       0
Bank Sta=4985.7,5030.8
XS Rating Curve= 0 ,0
Exp/Cntr=0.3,0.1

Type RM Length L Ch R = 1 ,489     ,284,284,284
BEGIN DESCRIPTION:
UNT 111 IN BOCR 1.0
END DESCRIPTION:
XS GIS Cut Line= 3
      3746946.52     10615159.15      3747019.45      10615346.7
      3747088.39     10615546.61
#Sta/Elev= 30
  4873.7  365.62  4885.5  365.91  4893.5  364.89  4917.7  364.32  4928.7  362.12
  4939.2  361.38  4960.7  358.03  4971.4  356.85  4983.1  357.09  4992.8  356.09
  5002.3  352.62  5004.7   350.3  5007.4   349.8  5010.7   350.3  5014.3  355.79
    5025  357.39  5032.2  356.55  5046.5  356.85  5062.1  356.07  5074.1  354.95
  5131.5  355.99  5186.2  359.61    5195   359.8  5212.1  360.97  5226.7  362.42
  5237.3  362.76  5243.4  364.05    5269  366.13  5274.6     367  5286.4  367.54
#Mann= 1 ,-1 , 0
  4873.7     .07       0
Bank Sta=4983.1,5025
XS Rating Curve= 0 ,0
Exp/Cntr=0.3,0.1

Type RM Length L Ch R = 1 ,205     ,0,0,0
BEGIN DESCRIPTION:
Mapping XS 5ef5be21
END DESCRIPTION:
XS GIS Cut Line= 4
      3746836.19     10615313.24      3746818.83     10615413.06
      3746942.83     10615543.24      3746995.08     10615598.71
#Sta/Elev= 30
  4809.7  358.26  4815.3  356.94  4847.2  354.96  4867.5  354.25  4887.8  354.44
  4897.9  353.75    4907  354.69  4937.7  355.11  4951.9   356.2  4959.1  355.91
  4980.2  356.17  4987.4  354.64  4994.4  351.32  5001.4  350.56  5004.6  351.06
  5008.5  353.56  5015.8  354.46  5022.7  354.28  5036.8  355.77  5044.1  355.93
  5065.1  356.57  5085.2  358.13  5090.8  358.13  5100.3  359.46  5107.6  359.38
  5135.9  362.31  5150.1  363.31  5156.9   364.4  5164.2  364.51    5167  365.12
#Mann= 1 ,-1 , 0
  4809.7     .06       0
Bank Sta=4980.2,5044.1
XS Rating Curve= 0 ,0
Exp/Cntr=0.3,0.1

Chan Stop Cuts=-1
Use User Specified Reach Order=0
Composite Channel Slope=5