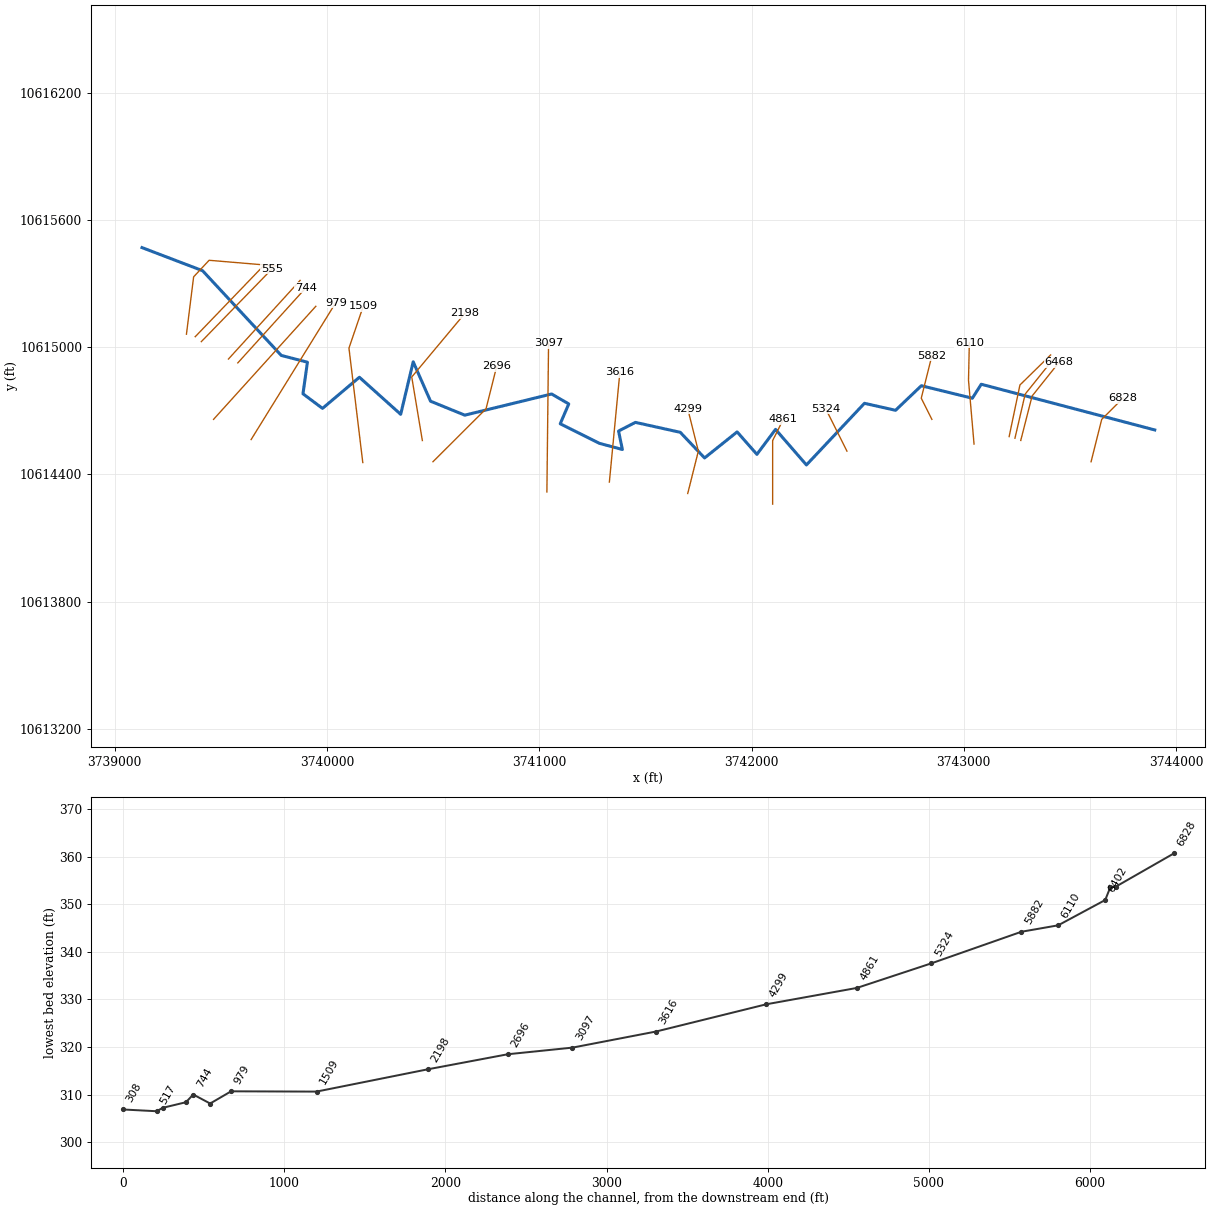
--- UNT 112 IN BOCR.prj (project) ---

Proj Title=UNT 112 IN BOCR Base Level Engineering
Current Plan=p01
Default Exp/Contr=0.3,0.1
English Units
Geom File=g01
Flow File=f01
Plan File=p01
Y Axis Title=Elevation
X Axis Title(PF)=Main Channel Distance
X Axis Title(XS)=Station
BEGIN DESCRIPTION:
UNT 112 IN BOCR
END DESCRIPTION:
DSS Export Rating Curves= 0
DSS Export Rating Curve Sorted= 0
DSS Export Volume Flow Curves= 0
DXF OffsetX= 0
DXF OffsetY= 0
DXF ScaleX= 1
DXF ScaleY= 10

--- UNT 112 IN BOCR.p01 (plan) ---

Plan Title=Multiple Run
Short Identifier=Multiple
Geom File=g01
Flow File=f01
Subcritical Flow
K Sum by GR= 0
Std Step Tol= 0.01
Critical Tol= 0.01
Num of Std Step Trials= 20
Max Error Tol= 0.3
Flow Tol Ratio= 0.001
Split Flow NTrial= 30
Split Flow Tol= 0.02
Split Flow Ratio= 0.02
Log Output Level= 0
Friction Slope Method= 1
Unsteady Friction Slope Method= 2
Unsteady Bridges Friction Slope Method= 1
Parabolic Critical Depth
Global Vel Dist=  1 , 1 , 1
Global Log Level= 0
CheckData=True
Encroach Param= -1, 0, 0, 0
BEGIN DESCRIPTION:
Multiple Run
END DESCRIPTION:

--- UNT 112 IN BOCR.f01 (steady flow) ---

Flow Title=Multiple
Program Version=4.10
Number of Profiles= 7
Profile Names=10-year,25-year,50-year,1pct_min,100-year,1pct_plu,500-year
River Rch & RM=UNT 112 IN BOCR,Reach-1         ,6828
     320     419     499     439     593     802     839
River Rch & RM=UNT 112 IN BOCR,Reach-1         ,2696
     476     640     775     691     935    1265    1364
River Rch & RM=UNT 112 IN BOCR,Reach-1         ,2198
     476     640     775     691     935    1265    1364
Boundary for River Rch & Prof#=UNT 112 IN BOCR,Reach-1         , 1
Up Type= 0
Dn Type= 3
Dn Slope=0.005
Boundary for River Rch & Prof#=UNT 112 IN BOCR,Reach-1         , 2
Up Type= 0
Dn Type= 3
Dn Slope=0.005
Boundary for River Rch & Prof#=UNT 112 IN BOCR,Reach-1         , 3
Up Type= 0
Dn Type= 3
Dn Slope=0.005
Boundary for River Rch & Prof#=UNT 112 IN BOCR,Reach-1         , 4
Up Type= 0
Dn Type= 3
Dn Slope=0.005
Boundary for River Rch & Prof#=UNT 112 IN BOCR,Reach-1         , 5
Up Type= 0
Dn Type= 3
Dn Slope=0.005
Boundary for River Rch & Prof#=UNT 112 IN BOCR,Reach-1         , 6
Up Type= 0
Dn Type= 3
Dn Slope=0.005
Boundary for River Rch & Prof#=UNT 112 IN BOCR,Reach-1         , 7
Up Type= 0
Dn Type= 3
Dn Slope=0.005
DSS Import GetInterval= 0
DSS Import GetPeak= 0
DSS Import FillOption= 0

--- UNT 112 IN BOCR.g01 (geometry) ---

Geom Title=Existing Conditions

River Reach=UNT 112 IN BOCR,Reach-1
Reach XY= 30
      3743899.61     10614610.19      3743082.25     10614826.00
      3743040.25     10614760.00      3742800.00     10614819.00
      3742678.50     10614703.00      3742532.00     10614736.00
      3742258.75     10614445.00      3742113.25     10614613.00
      3742025.50     10614495.00      3741932.25     10614601.00
      3741779.00     10614478.00      3741664.50     10614599.00
      3741453.00     10614646.00      3741373.75     10614605.00
      3741391.75     10614518.00      3741283.75     10614547.00
      3741098.97     10614639.37      3741139.25     10614733.00
      3741058.50     10614780.00      3740649.50     10614680.00
      3740488.00     10614746.00      3740406.50     10614932.00
      3740347.50     10614684.00      3740153.00     10614859.00
      3739979.25     10614712.00      3739887.25     10614781.00
      3739908.25     10614930.00      3739785.00     10614962.00
      3739414.25     10615362.00      3739129.25     10615471.00

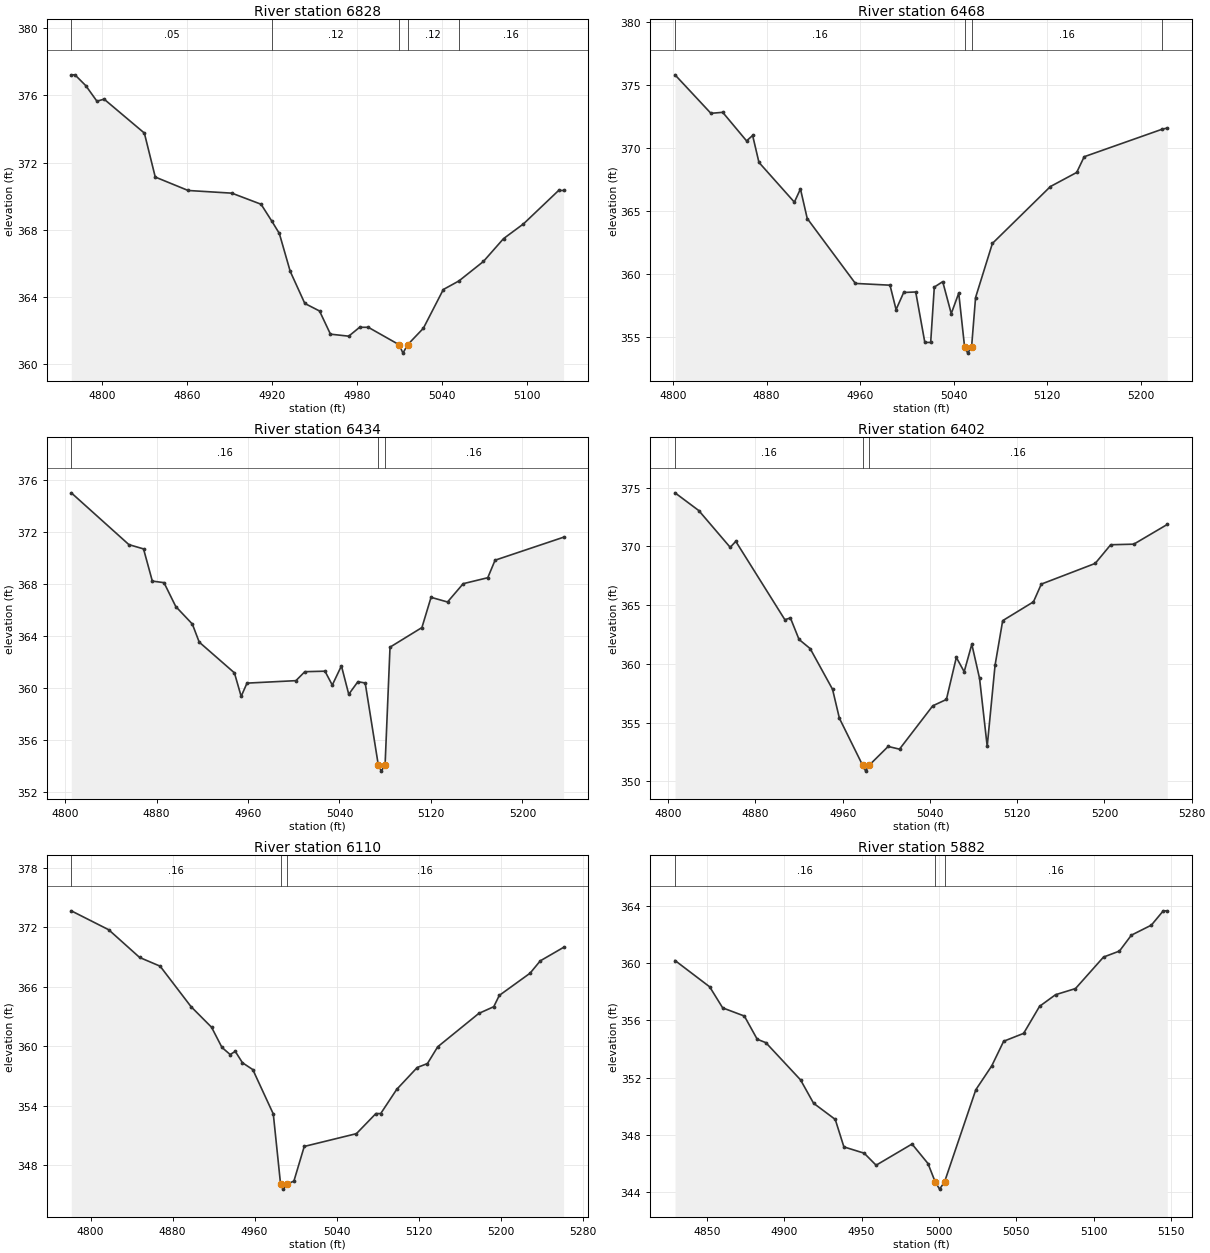
Type RM Length L Ch R = 1,6828,360,360,360
BEGIN DESCRIPTION:
UNT 112 IN BOCR 12.0
END DESCRIPTION:
XS GIS Cut Line= 3
      3743599.60     10614460.17      3743649.61     10614660.19
      3743749.61     10614760.19
#Sta/Elev= 30
  4778.5  377.23  4781.1  377.23  4788.8  376.58  4796.6  375.66  4801.7  375.78
  4830.1  373.76  4837.8  371.14  4861.0  370.34  4891.9  370.18  4912.5  369.52
  4920.2  368.50  4925.4  367.78  4933.1  365.52  4943.4  363.61  4953.8  363.16
  4961.5  361.78  4974.4  361.66  4982.1  362.19  4988.2  362.19  5010.0  361.15
  5012.7  360.65  5016.0  361.15  5027.1  362.13  5041.2  364.44  5052.2  364.95
  5069.5  366.11  5083.7  367.47  5097.8  368.35  5122.6  370.34  5126.1  370.34
#Mann=5,-1,0
  4778.5    0.05       0  4920.2    0.12       0  5010.0    0.07       0
  5016.0    0.12       0  5052.2    0.16       0
Bank Sta=5010,5016
Exp/Cntr=0.3,0.1

Type RM Length L Ch R = 1,6468,34,34,34
BEGIN DESCRIPTION:
Mapping XS dd0977ae
END DESCRIPTION:
XS GIS Cut Line= 3
      3743268.28     10614560.62      3743321.68     10614770.30
      3743449.25     10614930.42
#Sta/Elev= 30
  4801.7  375.80  4832.4  372.74  4842.5  372.82  4862.9  370.55  4868.1  370.98
  4873.5  368.84  4903.8  365.68  4909.0  366.73  4914.8  364.38  4956.0  359.22
  4985.6  359.08  4990.8  357.14  4997.3  358.50  5007.6  358.54  5015.4  354.53
  5020.4  354.53  5023.5  358.93  5030.7  359.36  5038.0  356.82  5044.4  358.45
  5049.4  354.18  5052.1  353.68  5055.4  354.18  5058.8  358.10  5073.2  362.40
  5122.8  366.92  5145.3  368.04  5151.7  369.29  5218.5  371.48  5222.8  371.57
#Mann=4,-1,0
  4801.7    0.16       0  5049.4    0.07       0  5055.4    0.16       0
  5218.5    0.05       0
Bank Sta=5049.4,5055.4
Exp/Cntr=0.3,0.1

Type RM Length L Ch R = 1,6434,32,32,32
BEGIN DESCRIPTION:
UNT 112 IN BOCR 11.0
END DESCRIPTION:
XS GIS Cut Line= 3
      3743240.96     10614571.13      3743289.13     10614779.42
      3743424.57     10614948.72
#Sta/Elev= 30
  4805.4  375.02  4855.8  371.03  4868.6  370.70  4876.3  368.22  4886.5  368.10
  4896.8  366.26  4911.3  364.91  4917.3  363.52  4948.1  361.15  4954.0  359.34
  4959.1  360.36  5001.9  360.55  5009.7  361.24  5027.3  361.28  5033.7  360.21
  5041.7  361.69  5048.1  359.50  5056.1  360.47  5062.5  360.37  5073.9  354.08
  5076.6  353.58  5079.9  354.08  5084.2  363.13  5112.1  364.64  5120.1  366.97
  5134.5  366.61  5148.2  368.02  5169.7  368.48  5176.1  369.83  5236.0  371.60
#Mann=3,-1,0
  4805.4    0.16       0  5073.9    0.07       0  5079.9    0.16       0
Bank Sta=5073.9,5079.9
Exp/Cntr=0.3,0.1

Type RM Length L Ch R = 1,6402,292,292,292
BEGIN DESCRIPTION:
Mapping XS 44242fbd
END DESCRIPTION:
XS GIS Cut Line= 3
      3743213.60     10614578.86      3743264.39     10614822.39
      3743408.90     10614964.29
#Sta/Elev= 30
  4806.3  374.56  4828.1  373.05  4856.9  369.92  4862.0  370.43  4907.0  363.76
  4912.1  363.91  4920.0  362.08  4930.2  361.30  4950.7  357.84  4957.0  355.37
  4978.3  351.37  4981.1  350.87  4984.3  351.37  5001.7  352.97  5012.1  352.74
  5042.6  356.43  5055.1  356.97  5064.2  360.55  5071.4  359.33  5078.4  361.67
  5085.5  358.76  5092.5  352.98  5099.7  359.88  5106.7  363.68  5134.9  365.28
  5142.1  366.79  5191.5  368.55  5205.7  370.14  5226.9  370.19  5257.6  371.87
#Mann=3,-1,0
  4806.3    0.16       0  4978.3    0.07       0  4984.3    0.16       0
Bank Sta=4978.3,4984.3
Exp/Cntr=0.3,0.1

Type RM Length L Ch R = 1,6110,228,228,228
BEGIN DESCRIPTION:
Mapping XS 69979d80
END DESCRIPTION:
XS GIS Cut Line= 3
      3743048.24     10614543.78      3743022.20     10614844.52
      3743026.11     10615022.91
#Sta/Elev= 30
  4781.2  373.66  4817.7  371.75  4847.9  368.95  4867.9  368.07  4898.0  363.99
  4918.1  361.90  4928.2  359.87  4936.2  359.15  4941.2  359.47  4948.2  358.32
  4958.3  357.63  4978.3  353.15  4985.4  346.06  4988.1  345.56  4991.4  346.06
  4998.4  346.37  5008.5  349.87  5059.4  351.16  5078.4  353.19  5083.1  353.19
  5098.7  355.63  5118.7  357.84  5128.7  358.24  5138.7  359.93  5178.8  363.30
  5193.4  363.98  5198.8  365.12  5228.8  367.36  5238.8  368.61  5261.5  369.97
#Mann=3,-1,0
  4781.2    0.16       0  4985.4    0.07       0  4991.4    0.16       0
Bank Sta=4985.4,4991.4
Exp/Cntr=0.3,0.1

Type RM Length L Ch R = 1,5882,558,558,558
BEGIN DESCRIPTION:
UNT 112 IN BOCR 10.0
END DESCRIPTION:
XS GIS Cut Line= 3
      3742849.63     10614660.15      3742799.61     10614760.19
      3742849.61     10614960.19
#Sta/Elev= 30
  4829.5  360.18  4851.9  358.34  4860.3  356.87  4874.3  356.30  4882.6  354.68
  4888.2  354.44  4910.6  351.84  4919.0  350.21  4933.0  349.08  4938.6  347.16
  4951.7  346.72  4959.4  345.88  4982.6  347.36  4992.9  346.00  4997.6  344.71
  5000.4  344.21  5003.6  344.71  5023.8  351.15  5034.1  352.82  5041.8  354.54
  5054.7  355.09  5065.0  356.98  5075.3  357.79  5088.2  358.22  5106.3  360.42
  5116.6  360.84  5124.3  361.95  5137.2  362.65  5144.9  363.65  5147.5  363.65
#Mann=3,-1,0
  4829.5    0.16       0  4997.6    0.07       0  5003.6    0.16       0
Bank Sta=4997.6,5003.6
Exp/Cntr=0.3,0.1

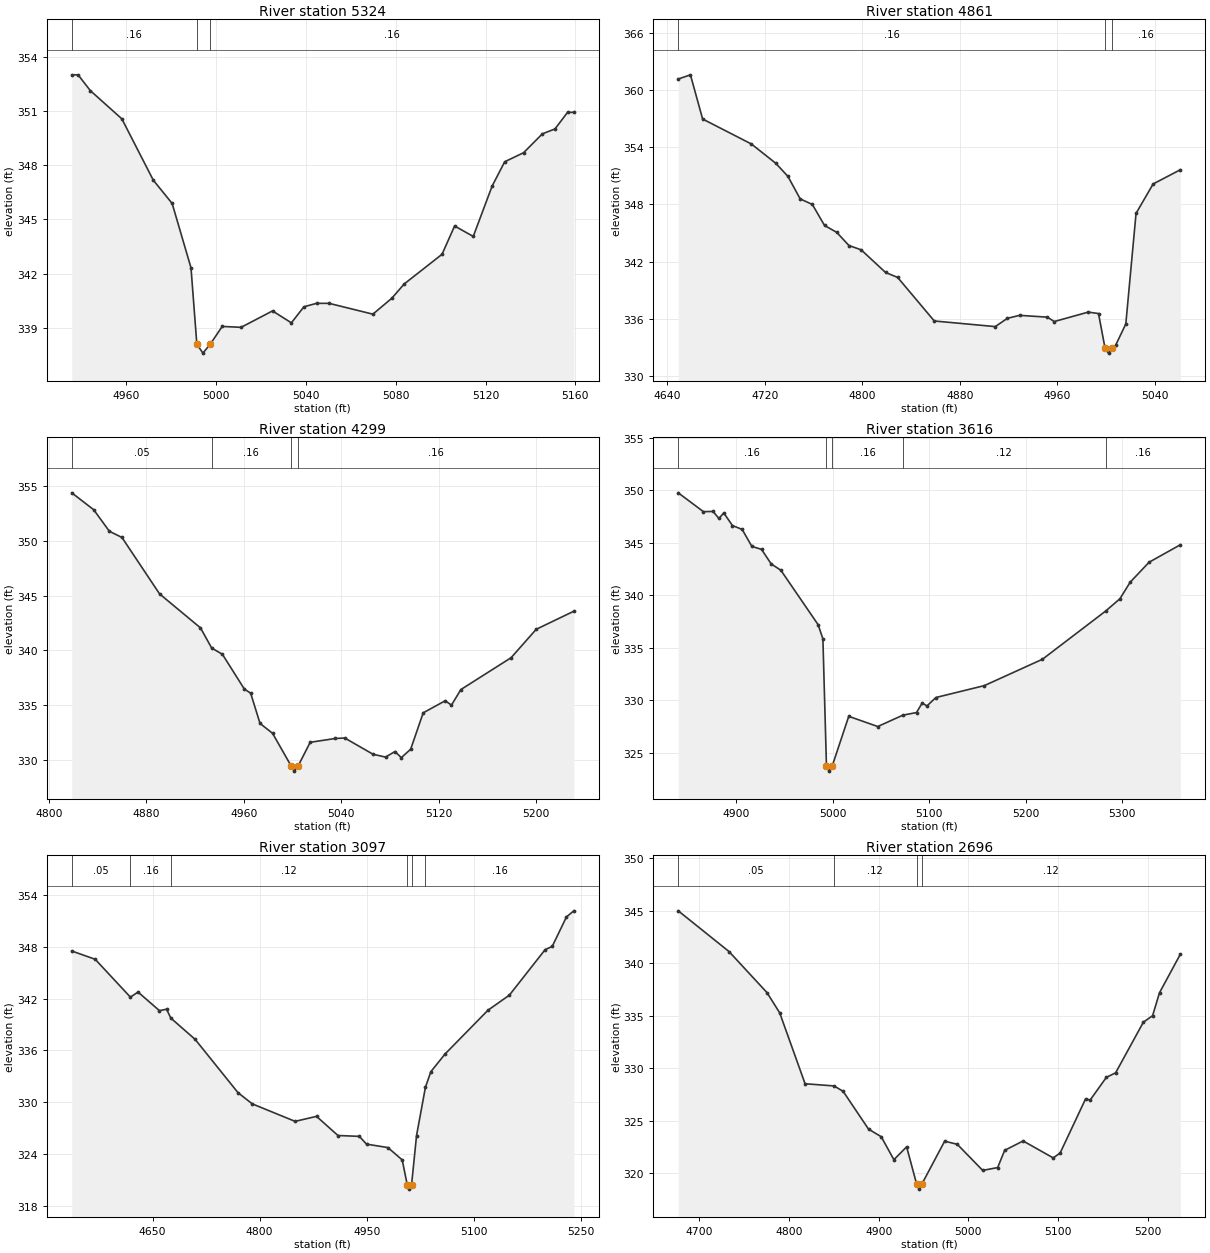
Type RM Length L Ch R = 1,5324,463,463,463
BEGIN DESCRIPTION:
UNT 112 IN BOCR 9.0
END DESCRIPTION:
XS GIS Cut Line= 3
      3742449.59     10614510.22      3742399.61     10614610.19
      3742349.59     10614710.22
#Sta/Elev= 30
  4935.7  353.02  4938.5  353.02  4944.0  352.14  4958.0  350.58  4972.0  347.18
  4980.4  345.89  4988.8  342.32  4991.4  338.09  4994.1  337.59  4997.4  338.09
  5002.7  339.07  5011.1  339.02  5025.1  339.93  5033.5  339.27  5039.1  340.16
  5044.7  340.35  5050.3  340.35  5069.8  339.75  5078.2  340.63  5083.8  341.43
  5100.6  343.07  5106.2  344.64  5114.5  344.06  5122.9  346.85  5128.5  348.20
  5136.9  348.70  5145.3  349.75  5150.9  350.02  5156.5  350.94  5159.3  350.94
#Mann=3,-1,0
  4935.7    0.16       0  4991.4    0.07       0  4997.4    0.16       0
Bank Sta=4991.4,4997.4
Exp/Cntr=0.3,0.1

Type RM Length L Ch R = 1,4861,562,562,562
BEGIN DESCRIPTION:
UNT 112 IN BOCR 8.0
END DESCRIPTION:
XS GIS Cut Line= 3
      3742099.61     10614260.18      3742099.61     10614560.19
      3742149.60     10614660.18
#Sta/Elev= 30
  4649.1  361.15  4659.1  361.59  4669.1  356.96  4709.1  354.34  4729.1  352.32
  4739.1  350.94  4749.1  348.59  4759.1  348.00  4769.1  345.80  4779.1  345.08
  4789.1  343.70  4799.1  343.25  4819.1  340.88  4829.1  340.35  4859.1  335.79
  4909.1  335.20  4919.1  336.07  4929.1  336.38  4951.9  336.19  4957.5  335.73
  4985.4  336.72  4993.8  336.57  4999.2  332.92  5002.0  332.42  5005.2  332.92
  5007.8  333.23  5016.2  335.48  5024.6  347.07  5038.6  350.15  5060.9  351.64
#Mann=3,-1,0
  4649.1    0.16       0  4999.2    0.07       0  5005.2    0.16       0
Bank Sta=4999.2,5005.2
Exp/Cntr=0.3,0.1

Type RM Length L Ch R = 1,4299,683,683,683
BEGIN DESCRIPTION:
UNT 112 IN BOCR 7.0
END DESCRIPTION:
XS GIS Cut Line= 3
      3741699.61     10614310.19      3741749.61     10614510.19
      3741699.61     10614710.18
#Sta/Elev= 30
  4818.8  354.38  4836.8  352.84  4849.7  350.87  4860.0  350.31  4890.9  345.16
  4924.5  342.06  4933.7  340.22  4942.5  339.65  4960.5  336.48  4965.7  336.10
  4973.4  333.34  4983.7  332.44  4998.8  329.49  5001.5  328.99  5004.8  329.49
  5014.6  331.62  5035.3  331.97  5043.0  332.01  5066.2  330.53  5076.5  330.27
  5084.2  330.78  5089.4  330.22  5097.1  330.99  5107.4  334.31  5125.5  335.41
  5130.6  335.01  5138.3  336.43  5179.6  339.34  5200.2  341.93  5231.1  343.58
#Mann=4,-1,0
  4818.8    0.05       0  4933.7    0.16       0  4998.8    0.07       0
  5004.8    0.16       0
Bank Sta=4998.8,5004.8
Exp/Cntr=0.3,0.1

Type RM Length L Ch R = 1,3616,519,519,519
BEGIN DESCRIPTION:
UNT 112 IN BOCR 6.0
END DESCRIPTION:
XS GIS Cut Line= 2
      3741330.50     10614364.23      3741379.98     10614882.47
#Sta/Elev= 30
  4839.8  349.74  4865.9  347.95  4875.9  347.97  4882.0  347.30  4887.0  347.83
  4896.0  346.63  4906.1  346.26  4916.1  344.65  4926.2  344.36  4936.2  342.98
  4946.2  342.38  4984.8  337.21  4989.8  335.86  4993.5  323.78  4996.2  323.28
  4999.5  323.78  5016.6  328.49  5046.7  327.52  5072.7  328.60  5086.9  328.85
  5092.7  329.75  5097.7  329.48  5107.0  330.28  5157.2  331.41  5217.5  333.92
  5283.0  338.50  5297.8  339.67  5308.4  341.24  5328.0  343.14  5360.4  344.80
#Mann=5,-1,0
  4839.8    0.16       0  4993.5    0.07       0  4999.5    0.16       0
  5072.7    0.12       0  5283.0    0.16       0
Bank Sta=4993.5,4999.5
Exp/Cntr=0.3,0.1

Type RM Length L Ch R = 1,3097,401,401,401
BEGIN DESCRIPTION:
UNT 112 IN BOCR 5.0
END DESCRIPTION:
XS GIS Cut Line= 2
      3741036.23     10614317.37      3741044.05     10615020.52
#Sta/Elev= 30
  4536.9  347.52  4569.7  346.56  4619.0  342.17  4629.7  342.76  4659.7  340.60
  4669.7  340.77  4675.6  339.74  4709.7  337.27  4769.7  331.09  4789.7  329.79
  4849.7  327.76  4879.7  328.34  4909.7  326.12  4939.7  326.02  4949.7  325.12
  4979.7  324.72  4999.7  323.29  5006.8  320.40  5009.5  319.90  5012.8  320.40
  5019.8  326.12  5032.2  331.70  5039.8  333.52  5059.8  335.58  5119.8  340.65
  5149.8  342.40  5199.8  347.67  5209.8  348.05  5229.8  351.48  5240.1  352.18
#Mann=6,-1,0
  4536.9    0.05       0  4619.0    0.16       0  4675.6    0.12       0
  5006.8    0.07       0  5012.8    0.12       0  5032.2    0.16       0
Bank Sta=5006.8,5012.8
Exp/Cntr=0.3,0.1

Type RM Length L Ch R = 1,2696,498,498,498
BEGIN DESCRIPTION:
UNT 112 IN BOCR 4.0
END DESCRIPTION:
XS GIS Cut Line= 3
      3740499.60     10614460.18      3740749.61     10614710.19
      3740799.60     10614910.17
#Sta/Elev= 30
  4676.5  344.97  4733.1  341.10  4775.5  337.19  4789.6  335.27  4817.9  328.53
  4850.3  328.32  4860.4  327.80  4888.6  324.22  4902.8  323.49  4916.9  321.31
  4931.1  322.53  4942.2  319.01  4945.0  318.51  4948.2  319.01  4973.5  323.07
  4987.6  322.77  5015.9  320.29  5032.6  320.56  5040.4  322.20  5061.0  323.09
  5094.5  321.48  5102.2  321.94  5130.6  327.09  5135.7  326.98  5153.8  329.14
  5164.1  329.57  5195.0  334.38  5205.3  335.00  5213.0  337.18  5236.2  340.84
#Mann=4,-1,0
  4676.5    0.05       0  4850.3    0.12       0  4942.2    0.07       0
  4948.2    0.12       0
Bank Sta=4942.2,4948.2
Exp/Cntr=0.3,0.1

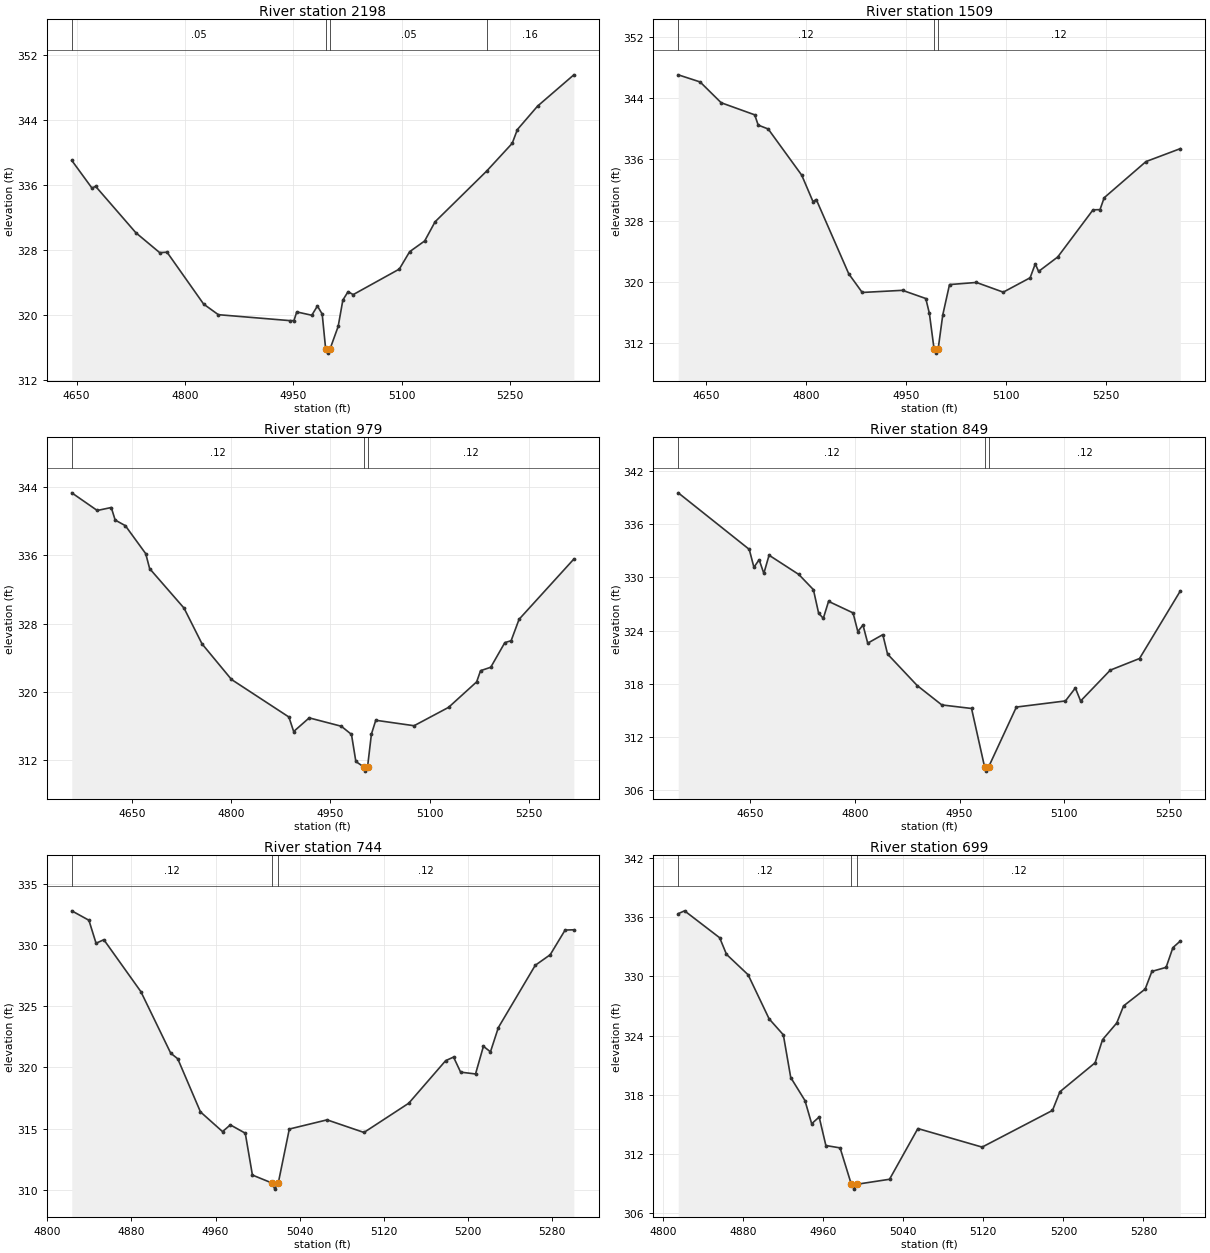
Type RM Length L Ch R = 1,2198,689,689,689
BEGIN DESCRIPTION:
UNT 112 IN BOCR 3.0
END DESCRIPTION:
XS GIS Cut Line= 3
      3740449.61     10614560.18      3740399.61     10614860.19
      3740649.63     10615160.22
#Sta/Elev= 30
  4643.3  339.05  4671.2  335.65  4676.3  335.86  4732.0  330.15  4765.0  327.70
  4775.1  327.76  4825.8  321.37  4846.1  320.07  4944.9  319.34  4950.7  319.34
  4954.6  320.41  4975.4  320.00  4983.2  321.14  4989.8  320.15  4994.6  315.84
  4997.3  315.34  5000.6  315.84  5011.9  318.62  5018.4  321.87  5025.6  322.90
  5032.7  322.54  5096.5  325.68  5110.8  327.82  5131.6  329.14  5146.0  331.50
  5217.6  337.76  5252.7  341.15  5259.9  342.85  5287.8  345.73  5338.0  349.58
#Mann=4,-1,0
  4643.3    0.05       0  4994.6    0.03       0  5000.6    0.05       0
  5217.6    0.16       0
Bank Sta=4994.6,5000.6
Exp/Cntr=0.3,0.1

Type RM Length L Ch R = 1,1509,530,530,530
BEGIN DESCRIPTION:
UNT 112 IN BOCR 2.0
END DESCRIPTION:
XS GIS Cut Line= 3
      3740168.97     10614456.29      3740103.87     10614996.63
      3740171.15     10615194.14
#Sta/Elev= 30
  4608.3  347.05  4641.1  346.12  4672.7  343.40  4723.0  341.82  4728.2  340.48
  4743.2  339.97  4793.5  333.93  4810.3  330.49  4815.3  330.75  4864.0  321.04
  4884.2  318.60  4944.6  318.88  4979.5  317.81  4984.9  315.87  4992.0  311.17
  4994.7  310.67  4998.0  311.17  5005.0  315.67  5015.1  319.63  5055.4  319.91
  5095.7  318.64  5136.0  320.52  5143.7  322.34  5148.7  321.35  5177.4  323.24
  5230.3  329.40  5240.8  329.43  5247.0  330.98  5309.7  335.71  5361.2  337.40
#Mann=3,-1,0
  4608.3    0.12       0  4992.0    0.07       0  4998.0    0.12       0
Bank Sta=4992,4998
Exp/Cntr=0.3,0.1

Type RM Length L Ch R = 1,979,130,130,130
BEGIN DESCRIPTION:
Mapping XS 491e3a50
END DESCRIPTION:
XS GIS Cut Line= 2
      3739642.99     10614564.76      3740041.45     10615210.64
#Sta/Elev= 30
  4559.2  343.34  4597.7  341.27  4618.9  341.62  4624.8  340.15  4640.2  339.49
  4671.0  336.21  4676.9  334.46  4728.9  329.83  4756.1  325.64  4800.6  321.47
  4887.4  317.07  4894.6  315.37  4918.1  316.97  4966.6  315.99  4982.0  315.03
  4988.6  311.86  5000.3  311.23  5003.0  310.73  5006.3  311.23  5012.1  315.06
  5018.7  316.69  5076.6  316.05  5128.7  318.20  5171.2  321.19  5177.1  322.50
  5192.5  322.90  5213.8  325.79  5223.3  326.01  5235.3  328.52  5318.1  335.58
#Mann=3,-1,0
  4559.2    0.12       0  5000.3    0.07       0  5006.3    0.12       0
Bank Sta=5000.3,5006.3
Exp/Cntr=0.3,0.1

Type RM Length L Ch R = 1,849,105,105,105
BEGIN DESCRIPTION:
Mapping XS ab95e51b
END DESCRIPTION:
XS GIS Cut Line= 2
      3739466.02     10614660.17      3739947.79     10615194.03
#Sta/Elev= 30
  4547.0  339.53  4648.7  333.16  4655.4  331.14  4662.9  331.99  4669.6  330.45
  4677.1  332.50  4719.7  330.33  4740.6  328.62  4748.1  325.96  4754.8  325.39
  4762.3  327.30  4797.4  326.00  4804.2  323.90  4811.6  324.64  4818.4  322.59
  4840.0  323.55  4846.8  321.36  4889.3  317.81  4924.5  315.63  4967.1  315.23
  4985.7  308.67  4988.5  308.17  4991.7  308.67  5031.3  315.39  5101.6  316.08
  5115.8  317.54  5123.3  316.07  5165.8  319.55  5207.7  320.86  5266.1  328.47
#Mann=3,-1,0
  4547.0    0.12       0  4985.7    0.07       0  4991.7    0.12       0
Bank Sta=4985.7,4991.7
Exp/Cntr=0.3,0.1

Type RM Length L Ch R = 1,744,45,45,45
BEGIN DESCRIPTION:
Mapping XS b078a796
END DESCRIPTION:
XS GIS Cut Line= 2
      3739580.30     10614926.77      3739900.60     10615280.92
#Sta/Elev= 30
  4823.3  332.80  4839.6  332.03  4846.4  330.15  4853.8  330.44  4889.0  326.20
  4917.4  321.17  4924.1  320.71  4945.7  316.37  4966.7  314.76  4974.1  315.31
  4988.3  314.63  4995.1  311.21  5013.7  310.56  5016.4  310.06  5019.7  310.56
  5030.2  314.97  5066.1  315.72  5101.2  314.69  5143.8  317.08  5178.9  320.56
  5186.4  320.85  5193.1  319.62  5207.3  319.47  5214.8  321.73  5221.5  321.28
  5229.0  323.26  5264.1  328.35  5278.3  329.21  5292.5  331.23  5300.8  331.25
#Mann=3,-1,0
  4823.3    0.12       0  5013.7    0.07       0  5019.7    0.12       0
Bank Sta=5013.7,5019.7
Exp/Cntr=0.3,0.1

Type RM Length L Ch R = 1,699,144,144,144
BEGIN DESCRIPTION:
Mapping XS 1b00561b
END DESCRIPTION:
XS GIS Cut Line= 2
      3739536.27     10614945.04      3739873.68     10615316.19
#Sta/Elev= 30
  4815.2  336.36  4821.5  336.65  4856.6  333.92  4863.4  332.24  4885.0  330.17
  4906.0  325.70  4920.2  324.08  4927.6  319.75  4941.8  317.42  4948.5  315.07
  4956.0  315.75  4962.7  312.86  4976.9  312.62  4988.1  308.94  4990.9  308.44
  4994.1  308.94  5026.3  309.44  5054.6  314.58  5118.8  312.70  5189.1  316.42
  5196.5  318.31  5231.7  321.25  5239.1  323.59  5253.3  325.28  5260.1  327.01
  5281.7  328.72  5288.4  330.51  5302.6  330.92  5309.4  332.92  5316.8  333.59
#Mann=3,-1,0
  4815.2    0.12       0  4988.1    0.07       0  4994.1    0.12       0
Bank Sta=4988.1,4994.1
Exp/Cntr=0.3,0.1

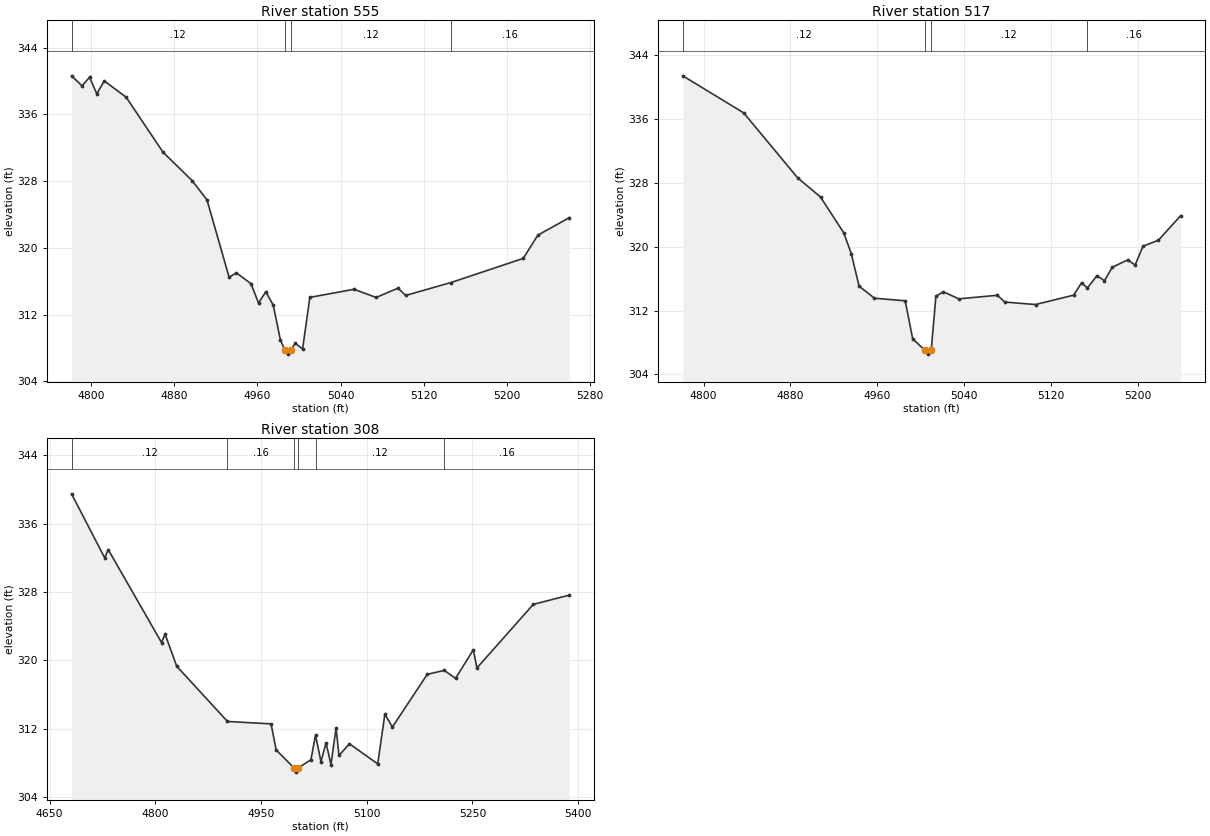
Type RM Length L Ch R = 1,555,38,38,38
BEGIN DESCRIPTION:
Mapping XS f34a17b7
END DESCRIPTION:
XS GIS Cut Line= 2
      3739408.41     10615027.02      3739741.80     10615370.82
#Sta/Elev= 30
  4781.1  340.62  4791.2  339.42  4798.4  340.45  4805.4  338.46  4812.6  340.01
  4833.7  338.05  4869.1  331.47  4897.2  328.05  4911.4  325.76  4932.7  316.48
  4939.7  317.01  4953.8  315.71  4961.0  313.39  4968.0  314.75  4975.2  313.13
  4982.1  308.94  4986.3  307.77  4989.1  307.27  4992.3  307.77  4996.3  308.57
  5003.4  307.89  5010.4  314.07  5052.9  315.04  5074.2  314.06  5095.3  315.18
  5102.5  314.30  5146.2  315.85  5215.7  318.74  5229.8  321.53  5260.0  323.62
#Mann=4,-1,0
  4781.1    0.12       0  4986.3    0.07       0  4992.3    0.12       0
  5146.2    0.16       0
Bank Sta=4986.3,4992.3
Exp/Cntr=0.3,0.1

Type RM Length L Ch R = 1,517,209,209,209
BEGIN DESCRIPTION:
Mapping XS deeff6f1
END DESCRIPTION:
XS GIS Cut Line= 2
      3739379.79     10615050.48      3739697.49     10615381.20
#Sta/Elev= 30
  4780.9  341.40  4837.0  336.76  4886.7  328.63  4907.8  326.22  4929.2  321.74
  4936.1  319.15  4943.3  315.07  4957.5  313.55  4985.8  313.23  4992.7  308.47
  5003.8  307.05  5006.6  306.55  5009.8  307.05  5014.1  313.80  5021.0  314.36
  5035.1  313.47  5070.7  313.92  5077.6  313.07  5105.9  312.76  5141.1  313.94
  5148.3  315.49  5153.7  314.83  5162.5  316.38  5169.4  315.74  5176.6  317.43
  5190.8  318.35  5197.7  317.71  5204.9  320.07  5219.1  320.81  5239.5  323.87
#Mann=4,-1,0
  4780.9    0.12       0  5003.8    0.07       0  5009.8    0.12       0
  5153.7    0.16       0
Bank Sta=5003.8,5009.8
Exp/Cntr=0.3,0.1

Type RM Length L Ch R = 1,308,0,0,0
BEGIN DESCRIPTION:
UNT 112 IN BOCR 1.0
END DESCRIPTION:
XS GIS Cut Line= 4
      3739338.32     10615062.18      3739372.17     10615333.02
      3739445.09     10615411.15      3739770.43     10615383.82
#Sta/Elev= 30
  4681.2  339.50  4728.2  332.01  4733.3  332.96  4808.9  322.09  4813.9  323.07
  4830.4  319.32  4902.5  312.85  4964.3  312.57  4971.6  309.51  4996.9  307.42
  4999.7  306.92  5002.9  307.42  5020.9  308.37  5027.4  311.25  5035.1  308.16
  5042.4  310.35  5049.3  307.81  5056.6  312.10  5060.7  308.87  5075.6  310.24
  5115.7  307.88  5125.8  313.71  5136.5  312.20  5186.0  318.37  5210.2  318.83
  5226.1  317.89  5251.4  321.25  5256.4  319.11  5336.5  326.56  5387.5  327.64
#Mann=6,-1,0
  4681.2    0.12       0  4902.5    0.16       0  4996.9    0.07       0
  5002.9    0.16       0  5027.4    0.12       0  5210.2    0.16       0
Bank Sta=4996.9,5002.9
Exp/Cntr=0.3,0.1

Chan Stop Cuts=-1