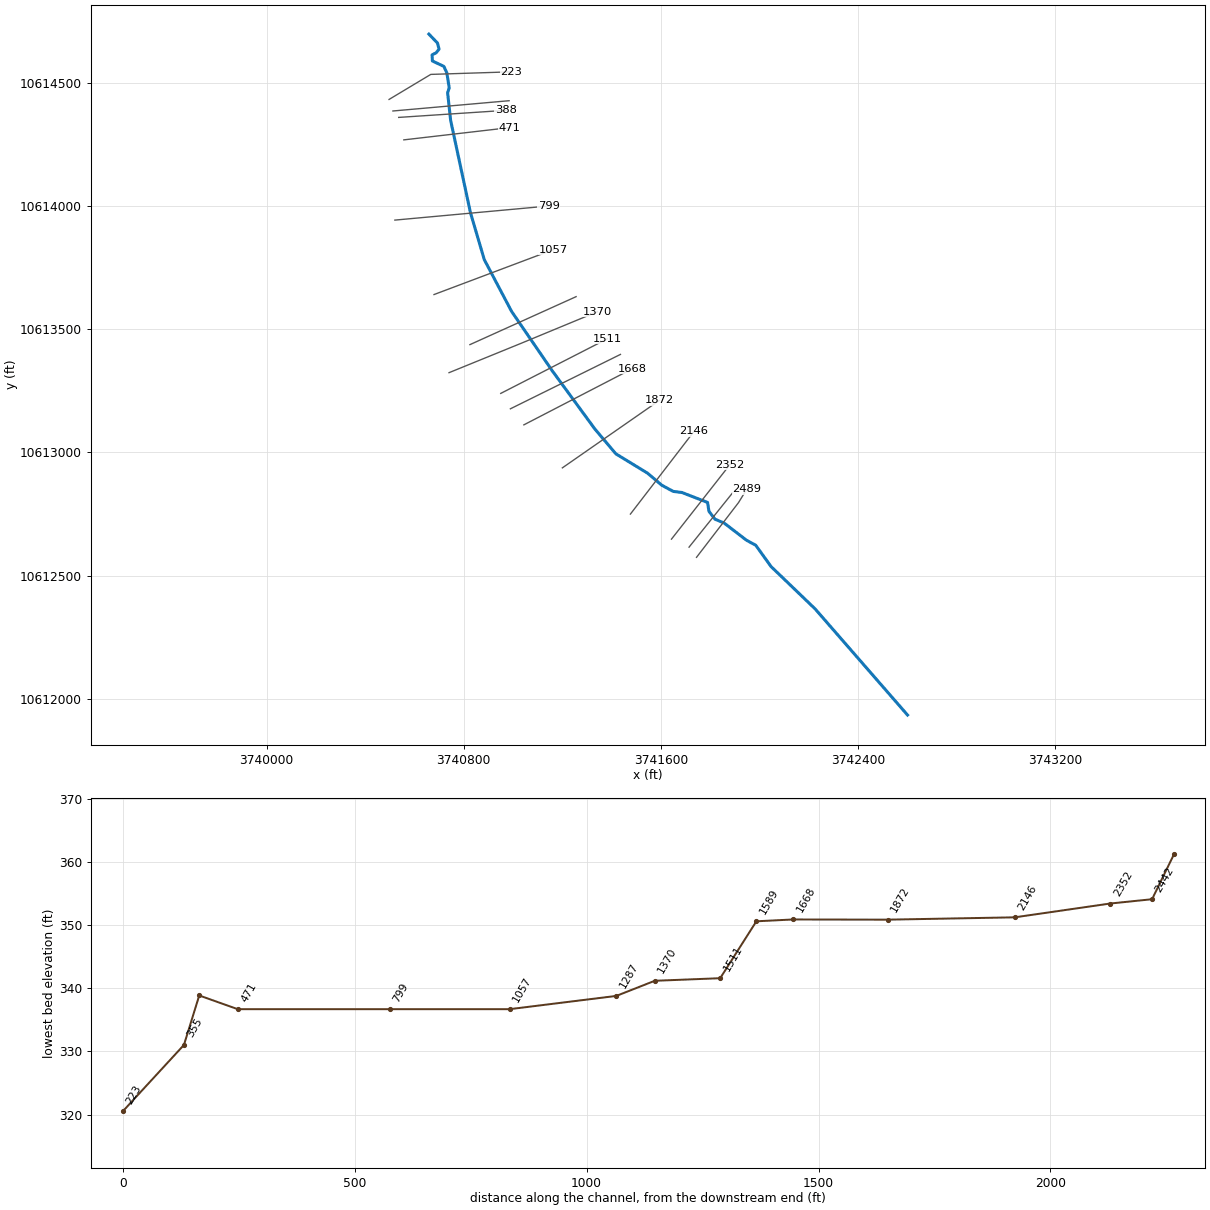
--- UNT 113 IN BOCR.prj (project) ---

Proj Title=UNT 113 IN BOCR Base Level Engineering
Current Plan=p01
Default Exp/Contr=0.3,0.1
English Units
Geom File=g01
Flow File=f01
Plan File=p01
Y Axis Title=Elevation
X Axis Title(PF)=Main Channel Distance
X Axis Title(XS)=Station
BEGIN DESCRIPTION:
UNT 113 IN BOCR
END DESCRIPTION:
DSS Export Rating Curves= 0
DSS Export Rating Curve Sorted= 0
DSS Export Volume Flow Curves= 0
DXF OffsetX= 0
DXF OffsetY= 0
DXF ScaleX= 1
DXF ScaleY= 10

--- UNT 113 IN BOCR.p01 (plan) ---

Plan Title=Multiple Run
Short Identifier=Multiple
Geom File=g01
Flow File=f01
Subcritical Flow
K Sum by GR= 0
Std Step Tol= 0.01
Critical Tol= 0.01
Num of Std Step Trials= 20
Max Error Tol= 0.3
Flow Tol Ratio= 0.001
Split Flow NTrial= 30
Split Flow Tol= 0.02
Split Flow Ratio= 0.02
Log Output Level= 0
Friction Slope Method= 1
Unsteady Friction Slope Method= 2
Unsteady Bridges Friction Slope Method= 1
Parabolic Critical Depth
Global Vel Dist=  1 , 1 , 1
Global Log Level= 0
CheckData=True
Encroach Param= -1, 0, 0, 0
BEGIN DESCRIPTION:
Multiple Run
END DESCRIPTION:

--- UNT 113 IN BOCR.f01 (steady flow) ---

Flow Title=Multiple
Program Version=4.10
Number of Profiles= 7
Profile Names=10-year,25-year,50-year,1pct_min,100-year,1pct_plu,500-year
River Rch & RM=UNT 113 IN BOCR,Reach-1         ,2489
     116     140     158     132     179     242     228
Boundary for River Rch & Prof#=UNT 113 IN BOCR,Reach-1         , 1
Up Type= 0
Dn Type= 3
Dn Slope=0.005
Boundary for River Rch & Prof#=UNT 113 IN BOCR,Reach-1         , 2
Up Type= 0
Dn Type= 3
Dn Slope=0.005
Boundary for River Rch & Prof#=UNT 113 IN BOCR,Reach-1         , 3
Up Type= 0
Dn Type= 3
Dn Slope=0.005
Boundary for River Rch & Prof#=UNT 113 IN BOCR,Reach-1         , 4
Up Type= 0
Dn Type= 3
Dn Slope=0.005
Boundary for River Rch & Prof#=UNT 113 IN BOCR,Reach-1         , 5
Up Type= 0
Dn Type= 3
Dn Slope=0.005
Boundary for River Rch & Prof#=UNT 113 IN BOCR,Reach-1         , 6
Up Type= 0
Dn Type= 3
Dn Slope=0.005
Boundary for River Rch & Prof#=UNT 113 IN BOCR,Reach-1         , 7
Up Type= 0
Dn Type= 3
Dn Slope=0.005
DSS Import GetInterval= 0
DSS Import GetPeak= 0
DSS Import FillOption= 0

--- UNT 113 IN BOCR.g01 (geometry) ---

Geom Title=Existing Conditions
Program Version=4.10

River Reach=UNT 113 IN BOCR ,Reach-1
Reach XY= 30
      3742600.63     10611934.41      3742225.75       10612365.
      3742046.75       10612537.        3741985.       10612623.
      3741946.75       10612644.        3741857.       10612713.
       3741819.5       10612729.        3741795.       10612761.
      3741789.25       10612797.      3741685.19      10612837.3
      3741649.95     10612841.74      3741603.76     10612866.74
      3741545.56     10612915.81       3741417.5       10612994.
      3741332.75       10613094.      3741159.25       10613331.
      3740994.25       10613572.       3740883.5       10613782.
      3740827.25       10613973.        3740747.       10614347.
      3740734.75       10614459.      3740741.25       10614479.
       3740731.5       10614540.       3740719.5       10614566.
        3740673.       10614588.      3740671.75       10614613.
        3740688.       10614621.        3740700.       10614636.
       3740693.5       10614661.      3740658.75       10614697.

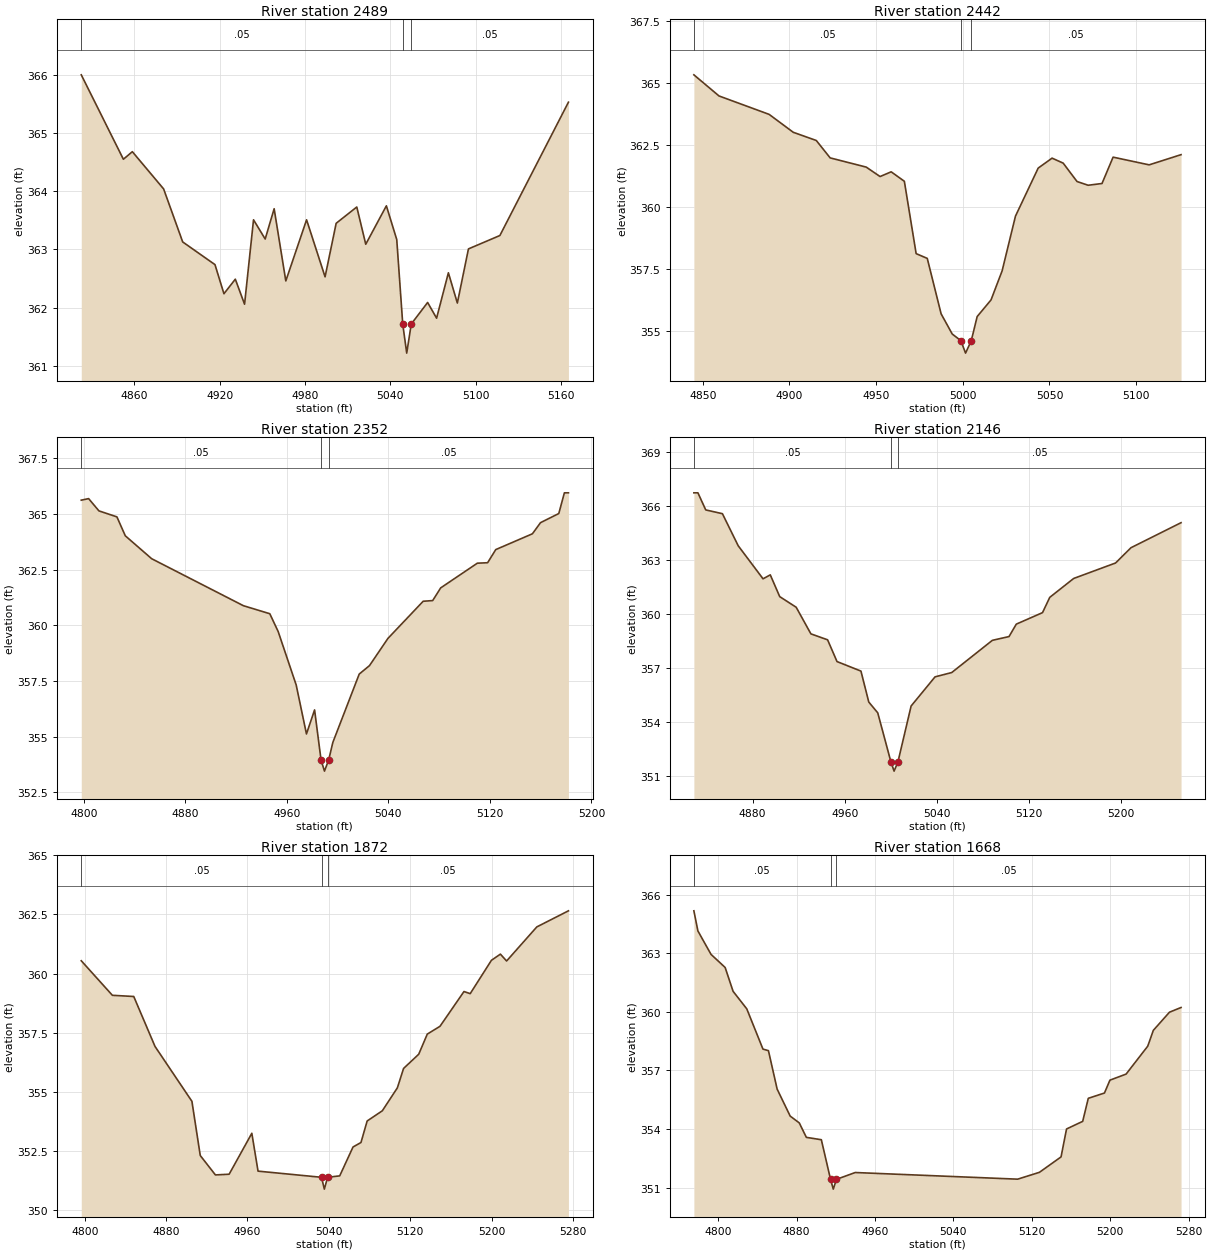
Type RM Length L Ch R = 1 ,2489    ,47,47,47
BEGIN DESCRIPTION:
Mapping XS a164194e
END DESCRIPTION:
XS GIS Cut Line= 3
      3741744.59     10612574.25      3741915.09     10612796.41
      3741947.79     10612849.62
#Sta/Elev= 30
  4822.7     366  4852.3  364.55  4858.6  364.68  4880.6  364.04    4894  363.13
  4916.7  362.74    4923  362.24    4931  362.49  4937.5  362.06  4943.8  363.51
    4952  363.18  4958.3   363.7  4966.5  362.46  4981.1  363.51  4994.1  362.53
  5001.9  363.45  5016.4  363.73  5022.7  363.09  5037.2  363.75  5044.5  363.17
  5048.7  361.72  5051.5  361.22  5054.7  361.72  5066.2  362.09  5072.5  361.82
  5080.8   362.6  5087.1  362.08  5094.9  363.01    5117  363.24  5165.2  365.53
#Mann= 3 ,-1 , 0
  4822.7     .05       0  5048.7     .03       0  5054.7     .05       0
Bank Sta=5048.7,5054.7
XS Rating Curve= 0 ,0
Exp/Cntr=0.3,0.1

Type RM Length L Ch R = 1 ,2442    ,90,90,90
BEGIN DESCRIPTION:
Mapping XS 0d6eba45
END DESCRIPTION:
XS GIS Cut Line= 2
       3741714.2     10612615.47        3741890.     10612834.68
#Sta/Elev= 30
  4844.9  365.32  4859.4  364.47  4888.3  363.73  4902.2  363.01  4915.5  362.68
  4923.5  361.98  4944.3  361.61  4952.3  361.23  4958.7  361.42  4966.3  361.04
  4973.1  358.13  4979.5  357.94  4987.5  355.71  4993.9   354.9  4998.9  354.63
  5001.6  354.13  5004.9  354.63  5008.3   355.6  5016.3  356.27  5022.7  357.44
  5030.4  359.64  5043.5  361.57  5051.5  361.97  5057.9  361.77  5065.9  361.03
  5072.3  360.88  5080.3  360.95  5086.7  362.01  5107.5   361.7  5125.9  362.11
#Mann= 3 ,-1 , 0
  4844.9     .05       0  4998.9     .03       0  5004.9     .05       0
Bank Sta=4998.9,5004.9
XS Rating Curve= 0 ,0
Exp/Cntr=0.3,0.1

Type RM Length L Ch R = 1 ,2352    ,206,206,206
BEGIN DESCRIPTION:
Mapping XS dd0a9664
END DESCRIPTION:
XS GIS Cut Line= 2
        3741643.     10612648.11      3741880.01     10612950.24
#Sta/Elev= 30
  4797.9  365.62  4803.7  365.69  4811.8  365.14    4826  364.87  4832.6  364.02
  4853.4  362.99  4925.7  360.88  4946.5  360.52  4953.1  359.72  4967.3  357.32
  4975.4  355.12  4981.8   356.2  4986.9  353.95  4989.6  353.45  4992.9  353.95
  4996.2  354.74    5017  357.81  5025.1  358.19  5039.6  359.41  5067.4  361.08
  5074.9  361.11  5081.2  361.68  5110.1  362.79  5118.2  362.81  5124.6   363.4
  5153.5  364.11  5159.9  364.61  5174.3  365.02  5178.7  365.95  5181.9  365.95
#Mann= 3 ,-1 , 0
  4797.9     .05       0  4986.9     .03       0  4992.9     .05       0
Bank Sta=4986.9,4992.9
XS Rating Curve= 0 ,0
Exp/Cntr=0.3,0.1

Type RM Length L Ch R = 1 ,2146    ,274,274,274
BEGIN DESCRIPTION:
Mapping XS 8ea809dd
END DESCRIPTION:
XS GIS Cut Line= 2
      3741476.34     10612749.69      3741734.49     10613085.29
#Sta/Elev= 30
  4828.9  366.73  4832.4  366.73  4839.2  365.78  4853.7  365.57  4867.4  363.79
    4889  361.95  4895.3  362.17  4903.5  360.96  4917.8  360.37  4930.6  358.89
  4945.1  358.56  4953.3  357.35  4974.1  356.82  4980.9   355.1  4988.7   354.5
  5000.2  351.76  5002.9  351.26  5006.2  351.76  5017.7  354.88  5038.5   356.5
    5053  356.74  5088.3  358.53  5102.8  358.74  5109.1  359.43  5131.9  360.07
  5138.2  360.92    5159  361.97  5195.4  362.83  5208.8  363.68  5252.3  365.07
#Mann= 3 ,-1 , 0
  4828.9     .05       0  5000.2     .03       0  5006.2     .05       0
Bank Sta=5000.2,5006.2
XS Rating Curve= 0 ,0
Exp/Cntr=0.3,0.1

Type RM Length L Ch R = 1 ,1872    ,204,204,204
BEGIN DESCRIPTION:
Mapping XS 4c604836
END DESCRIPTION:
XS GIS Cut Line= 2
      3741200.26     10612937.16      3741593.53     10613210.63
#Sta/Elev= 30
  4796.6  360.54  4827.2  359.08  4848.2  359.03  4869.1  356.92  4905.4   354.6
  4913.6  352.31  4928.5  351.49    4942  351.52  4964.3  353.25  4970.4  351.65
  5032.8  351.39  5035.6  350.89  5038.8  351.39  5050.7  351.45  5063.8  352.67
  5071.6  352.86  5077.7  353.77  5092.6   354.2  5107.4  355.17  5113.5  355.99
  5128.4  356.59  5136.8  357.44  5149.3  357.77  5172.9  359.24    5179  359.15
  5199.9  360.56  5208.7  360.82  5214.8  360.53  5244.5  361.97  5275.6  362.65
#Mann= 3 ,-1 , 0
  4796.6     .05       0  5032.8     .03       0  5038.8     .05       0
Bank Sta=5032.8,5038.8
XS Rating Curve= 0 ,0
Exp/Cntr=0.3,0.1

Type RM Length L Ch R = 1 ,1668    ,79,79,79
BEGIN DESCRIPTION:
Mapping XS 9e367180
END DESCRIPTION:
XS GIS Cut Line= 2
      3741044.09     10613111.69      3741485.73      10613340.3
#Sta/Elev= 30
  4775.1  365.17  4779.2  364.14  4792.6  362.94    4807  362.27  4815.1  361.05
  4829.1  360.15  4845.6  358.09  4851.2  358.01  4860.1  356.04  4873.4  354.66
  4882.7  354.31  4889.9  353.57  4905.2  353.45  4914.6  351.42  4917.4  350.92
  4920.6  351.42  4939.8  351.77  5105.6  351.43  5127.8  351.78  5149.9  352.57
  5155.5     354    5172  354.39  5177.7  355.57  5194.2  355.84  5199.8   356.5
  5216.3  356.81  5238.4  358.24  5244.1  359.05  5260.6  359.98  5272.4  360.22
#Mann= 3 ,-1 , 0
  4775.1     .05       0  4914.6     .03       0  4920.6     .05       0
Bank Sta=4914.6,4920.6
XS Rating Curve= 0 ,0
Exp/Cntr=0.3,0.1

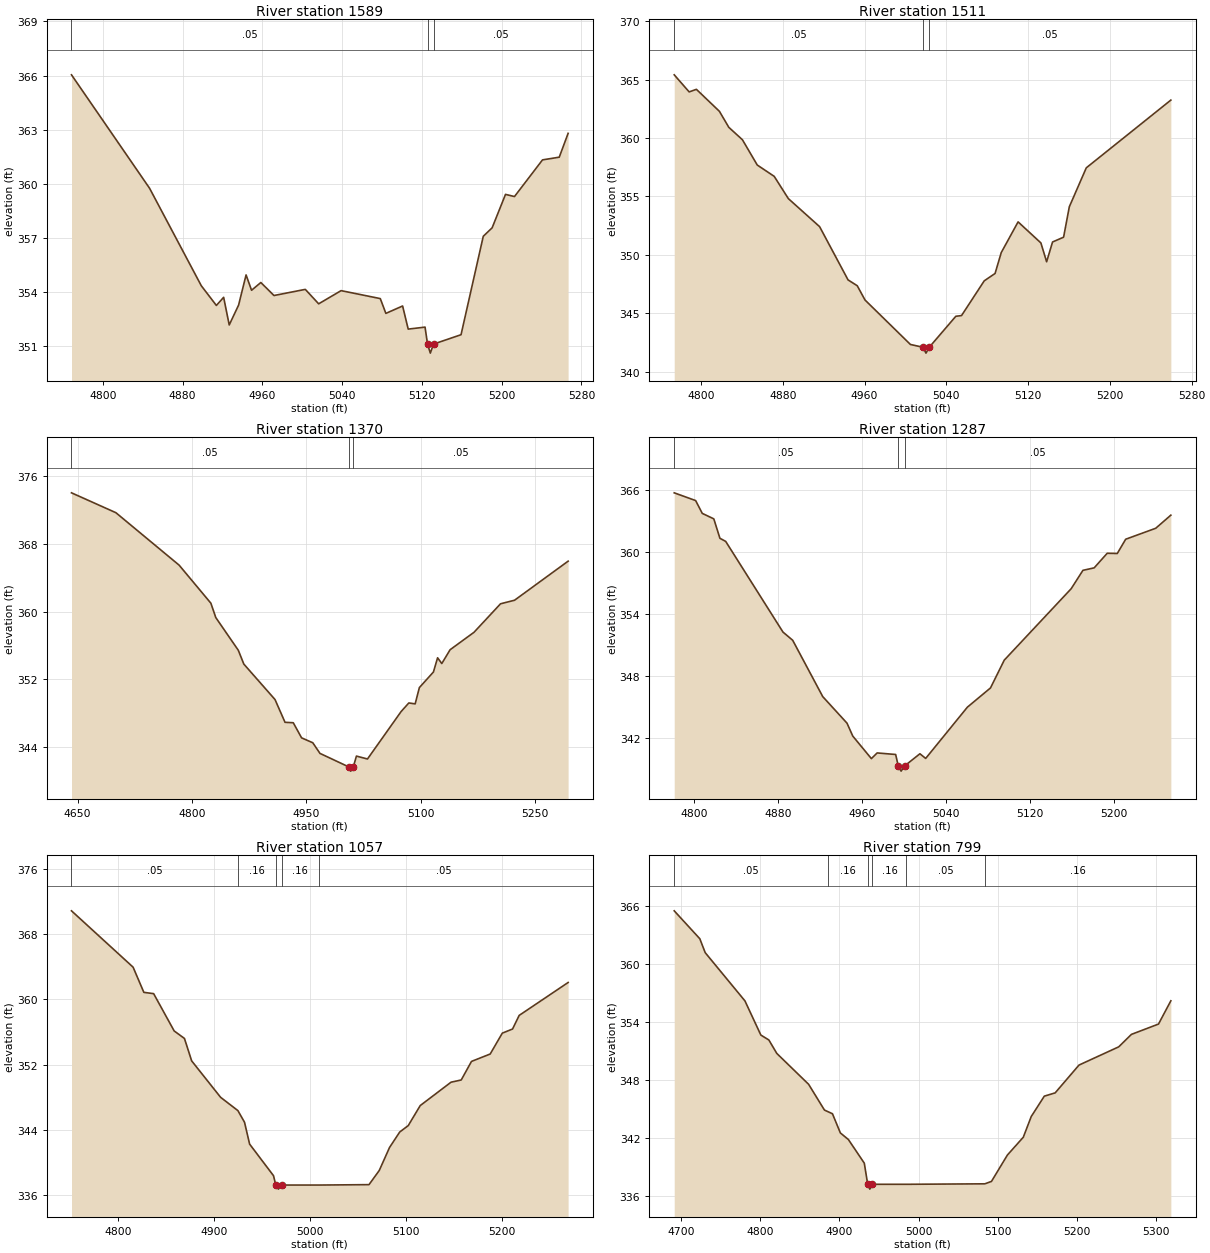
Type RM Length L Ch R = 1 ,1589    ,78,78,78
BEGIN DESCRIPTION:
Mapping XS 1e7ac10c
END DESCRIPTION:
XS GIS Cut Line= 2
      3740989.39     10613176.79      3741435.94     10613397.46
#Sta/Elev= 30
  4768.5  366.04  4846.8  359.76  4898.7  354.36  4913.8  353.27  4921.1  353.72
  4926.7  352.19  4936.1  353.29  4943.6  354.96  4949.1  354.11  4958.4  354.54
  4971.6  353.82    5003  354.16  5016.4  353.36  5038.9  354.09  5078.2  353.65
  5083.8  352.83  5100.6  353.24  5106.2  351.96  5123.1  352.07  5125.6  351.13
  5128.4  350.63  5131.6  351.13  5159.2  351.65  5181.5   357.1  5190.4  357.57
  5203.8  359.42  5212.8   359.3  5240.9  361.33  5257.7  361.48  5266.6   362.8
#Mann= 3 ,-1 , 0
  4768.5     .05       0  5125.6     .03       0  5131.6     .05       0
Bank Sta=5125.6,5131.6
XS Rating Curve= 0 ,0
Exp/Cntr=0.3,0.1

Type RM Length L Ch R = 1 ,1511    ,141,141,141
BEGIN DESCRIPTION:
Mapping XS a34c7fb2
END DESCRIPTION:
XS GIS Cut Line= 2
      3740950.26     10613239.25      3741382.58     10613460.62
#Sta/Elev= 30
  4773.9   365.4  4788.5  363.94  4795.6  364.16  4818.1  362.28  4827.3  360.91
  4840.6  359.85  4855.1  357.69  4871.7  356.72  4885.5  354.82  4916.1  352.42
  4943.9  347.87  4952.9  347.37  4960.5  346.15  5004.9  342.35  5017.3  342.11
  5020.1  341.61  5023.3  342.11  5049.3  344.76  5054.9  344.82  5077.1  347.79
  5087.7  348.42  5093.7   350.2  5110.2  352.83  5132.5  351.03  5138.1  349.42
  5143.9  351.11  5154.7  351.52  5160.3  354.12  5176.9  357.45  5259.6  363.24
#Mann= 3 ,-1 , 0
  4773.9     .05       0  5017.3     .03       0  5023.3     .05       0
Bank Sta=5017.3,5023.3
XS Rating Curve= 0 ,0
Exp/Cntr=0.3,0.1

Type RM Length L Ch R = 1 ,1370    ,83,83,83
BEGIN DESCRIPTION:
Mapping XS 240a8b11
END DESCRIPTION:
XS GIS Cut Line= 3
      3740740.41     10613323.36      3741033.37     10613442.71
      3741342.57     10613570.73
#Sta/Elev= 30
    4642  373.98  4700.2  371.64  4783.1  365.46  4824.7  360.98  4831.2  359.28
  4860.7  355.43  4867.9  353.81  4908.8  349.63  4921.9  346.95  4932.7   346.9
  4943.6  345.12  4958.3  344.54  4967.7  343.29  5005.4   341.7  5008.1   341.2
  5011.4   341.7  5015.5  342.97    5030  342.63  5074.1  348.22  5084.2  349.23
  5092.5  349.12    5098  351.04  5116.4  352.87  5121.9  354.55  5127.4  353.87
  5138.3   355.5  5169.6  357.55  5204.4  360.91  5222.8  361.33    5293  365.93
#Mann= 3 ,-1 , 0
    4642     .05       0  5005.4     .03       0  5011.4     .05       0
Bank Sta=5005.4,5011.4
XS Rating Curve= 0 ,0
Exp/Cntr=0.3,0.1

Type RM Length L Ch R = 1 ,1287    ,230,230,230
BEGIN DESCRIPTION:
Mapping XS a9be8d82
END DESCRIPTION:
XS GIS Cut Line= 2
      3740825.25     10613437.17      3741256.12     10613631.84
#Sta/Elev= 30
    4781  365.73  4801.4  364.98  4807.7  363.74  4818.7  363.21  4824.5  361.33
    4830  361.03  4884.5  352.26  4893.8  351.46  4922.4  346.01  4945.5  343.44
    4951  342.19  4968.7  340.01  4974.2  340.56  4991.8  340.41  4994.3   339.3
    4997   338.8  5000.3   339.3  5014.9  340.48  5020.4  340.03  5060.1  344.99
  5082.1  346.85  5095.2  349.54  5158.9  356.45  5170.1  358.23  5180.8  358.47
  5193.2  359.88  5202.8  359.86  5210.8  361.24  5239.4   362.3  5253.8  363.57
#Mann= 3 ,-1 , 0
    4781     .05       0  4994.3     .03       0  5000.3     .05       0
Bank Sta=4994.3,5000.3
XS Rating Curve= 0 ,0
Exp/Cntr=0.3,0.1

Type RM Length L Ch R = 1 ,1057    ,258,258,258
BEGIN DESCRIPTION:
Mapping XS 2e5aa084
END DESCRIPTION:
XS GIS Cut Line= 2
      3740679.48     10613640.32      3741163.82      10613822.6
#Sta/Elev= 30
  4751.5  370.87  4815.7  363.95  4826.9  360.86  4837.1   360.7  4858.5  356.12
  4869.2   355.2  4876.7  352.45  4906.9  347.97  4924.9  346.34  4931.8  344.91
  4937.1  342.23    4962  338.35  4964.4   337.2  4967.1   336.7  4970.4   337.2
  5009.3   337.2  5061.5  337.25  5072.2  338.99  5082.9  341.81  5093.5  343.71
  5102.4   344.5  5114.9  346.96    5147  349.83  5157.6   350.1  5168.3  352.38
  5187.8  353.29  5200.4  355.85  5211.1  356.36    5218  358.03    5269  362.07
#Mann= 5 ,-1 , 0
  4751.5     .05       0  4924.9     .16       0  4964.4     .07       0
  4970.4     .16       0  5009.3     .05       0
Bank Sta=4964.4,4970.4
XS Rating Curve= 0 ,0
Exp/Cntr=0.3,0.1

Type RM Length L Ch R = 1 ,799     ,328,328,328
BEGIN DESCRIPTION:
UNT 113 IN BOCR 2.0
END DESCRIPTION:
XS GIS Cut Line= 2
      3740520.65      10613942.4      3741145.14     10613999.65
#Sta/Elev= 30
  4691.4  365.53  4723.7  362.64  4730.5   361.2  4780.7   356.2  4800.8  352.66
  4810.9  352.15  4820.9  350.76  4861.1  347.56  4881.1  344.89  4885.6  344.72
  4891.2  344.51  4901.2  342.52  4911.3  341.84  4931.4  339.39  4935.7   337.2
  4938.4   336.7  4941.7   337.2  4984.6   337.2  5083.6  337.25    5092   337.5
  5112.1  340.23  5132.2  342.08  5142.2  344.22  5158.7  346.33  5172.4  346.67
  5202.5  349.55  5252.7  351.44  5268.7  352.73  5302.9   353.8  5318.5  356.21
#Mann= 6 ,-1 , 0
  4691.4     .05       0  4885.6     .16       0  4935.7    .033       0
  4941.7     .16       0  4984.6     .05       0  5083.6     .16       0
Bank Sta=4935.7,4941.7
XS Rating Curve= 0 ,0
Exp/Cntr=0.3,0.1

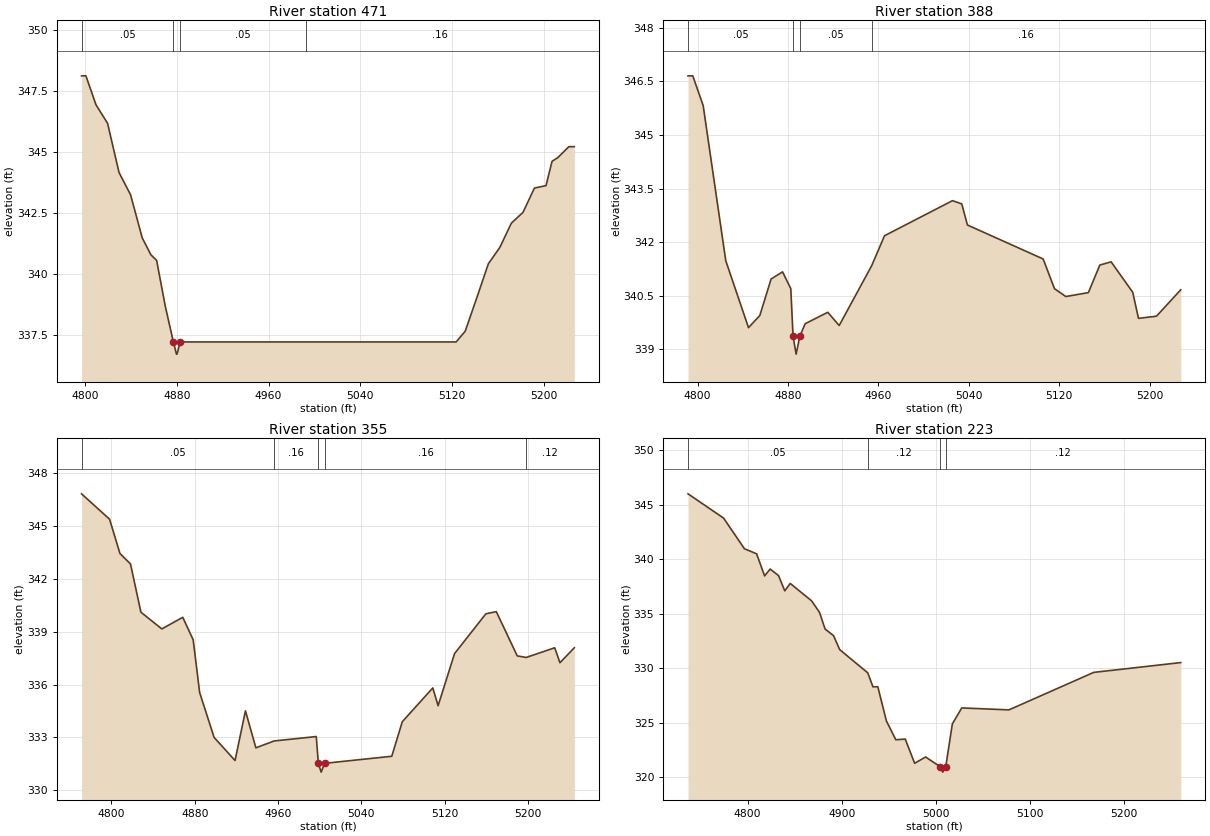
Type RM Length L Ch R = 1 ,471     ,83,83,83
BEGIN DESCRIPTION:
Mapping XS 7d248768
END DESCRIPTION:
XS GIS Cut Line= 2
       3740557.1     10614267.92      3740984.14      10614317.4
#Sta/Elev= 30
  4796.8  348.13  4800.6  348.13  4809.4  346.94  4819.5  346.18  4829.5  344.16
  4839.6  343.24  4849.7  341.48  4857.3  340.78  4862.3  340.55  4869.8  338.68
  4876.9   337.2  4879.6   336.7  4880.1   336.7  4882.9   337.2  4990.6   337.2
  4992.2   337.2  5000.7   337.2  5123.6   337.2  5131.5  337.64  5141.6  339.01
  5151.7  340.41  5161.7  341.08  5171.8  342.08  5181.9  342.52  5191.9  343.52
    5202  343.62  5207.3  344.62  5212.3  344.77  5221.9  345.22  5226.7  345.22
#Mann= 4 ,-1 , 0
  4796.8     .05       0  4876.9     .07       0  4882.9     .05       0
  4992.2     .16       0
Bank Sta=4876.9,4882.9
XS Rating Curve= 0 ,0
Exp/Cntr=0.3,0.1

Type RM Length L Ch R = 1 ,388     ,33,33,33
BEGIN DESCRIPTION:
Mapping XS 51b5ab1e
END DESCRIPTION:
XS GIS Cut Line= 2
      3740536.23     10614359.06      3740971.09     10614387.71
#Sta/Elev= 30
  4791.6  346.65  4795.8  346.65    4805  345.82    4825  341.48  4845.1  339.61
  4855.1  339.95  4865.1  340.97  4875.2  341.17  4882.5   340.7  4884.5  339.37
  4887.2  338.87  4890.5  339.37  4895.2  339.72  4915.2  340.04  4925.3  339.67
    4954  341.34  4965.4  342.18  5025.5  343.16  5033.7  343.07  5038.7  342.48
  5105.7  341.53  5115.7   340.7  5125.7  340.48  5145.7  340.59  5155.8  341.36
  5165.8  341.45  5184.9   340.6    5190  339.87  5205.9  339.93  5227.4  340.67
#Mann= 4 ,-1 , 0
  4791.6     .05       0  4884.5     .07       0  4890.5     .05       0
    4954     .16       0
Bank Sta=4884.5,4890.5
XS Rating Curve= 0 ,0
Exp/Cntr=0.3,0.1

Type RM Length L Ch R = 1 ,355     ,132,132,132
BEGIN DESCRIPTION:
Mapping XS e921dad7
END DESCRIPTION:
XS GIS Cut Line= 2
      3740512.82     10614385.11      3740984.18     10614426.78
#Sta/Elev= 30
  4771.3  346.83  4798.2  345.39  4808.2  343.44  4818.3  342.85  4828.3  340.11
  4848.4  339.16  4868.5  339.82  4878.5  338.54  4884.7  335.55  4898.6     333
  4918.7  331.69  4928.7  334.51  4938.7  332.41  4956.3   332.8  4996.7  333.05
  4998.7  331.53  5001.4  331.03  5004.7  331.53  5069.2  331.93  5079.3  333.89
  5108.6  335.81  5113.7   334.8  5129.5  337.76  5159.6  340.02  5169.6  340.14
  5189.7  337.63  5198.3  337.54  5225.7  338.09  5230.7  337.24  5244.5  338.09
#Mann= 5 ,-1 , 0
  4771.3     .05       0  4956.3     .16       0  4998.7     .07       0
  5004.7     .16       0  5198.3     .12       0
Bank Sta=4998.7,5004.7
XS Rating Curve= 0 ,0
Exp/Cntr=0.3,0.1

Type RM Length L Ch R = 1 ,223     ,0,0,0
BEGIN DESCRIPTION:
UNT 113 IN BOCR 1.0
END DESCRIPTION:
XS GIS Cut Line= 3
      3740497.16     10614431.98      3740666.44     10614533.54
      3740991.96     10614543.96
#Sta/Elev= 30
  4736.8  346.02  4774.6  343.79  4796.7  340.98  4809.6  340.52  4818.1  338.49
    4824  339.12  4832.9  338.52  4839.5  337.12  4845.3   337.8  4867.9  336.21
  4876.4  335.15  4882.3  333.62  4891.3  333.01  4897.8  331.73  4927.6   329.6
  4933.1  328.32  4938.3  328.32  4947.4  325.18  4957.4  323.46  4967.4  323.52
  4977.4   321.3    4989  321.88  5004.4  320.99  5007.2  320.49  5010.4  320.99
  5017.4  324.91  5027.4  326.38  5077.5   326.2  5167.5  329.64  5259.9  330.54
#Mann= 4 ,-1 , 0
  4736.8     .05       0  4927.6     .12       0  5004.4     .07       0
  5010.4     .12       0
Bank Sta=5004.4,5010.4
XS Rating Curve= 0 ,0
Exp/Cntr=0.3,0.1

Chan Stop Cuts=-1
Use User Specified Reach Order=0
Composite Channel Slope=5