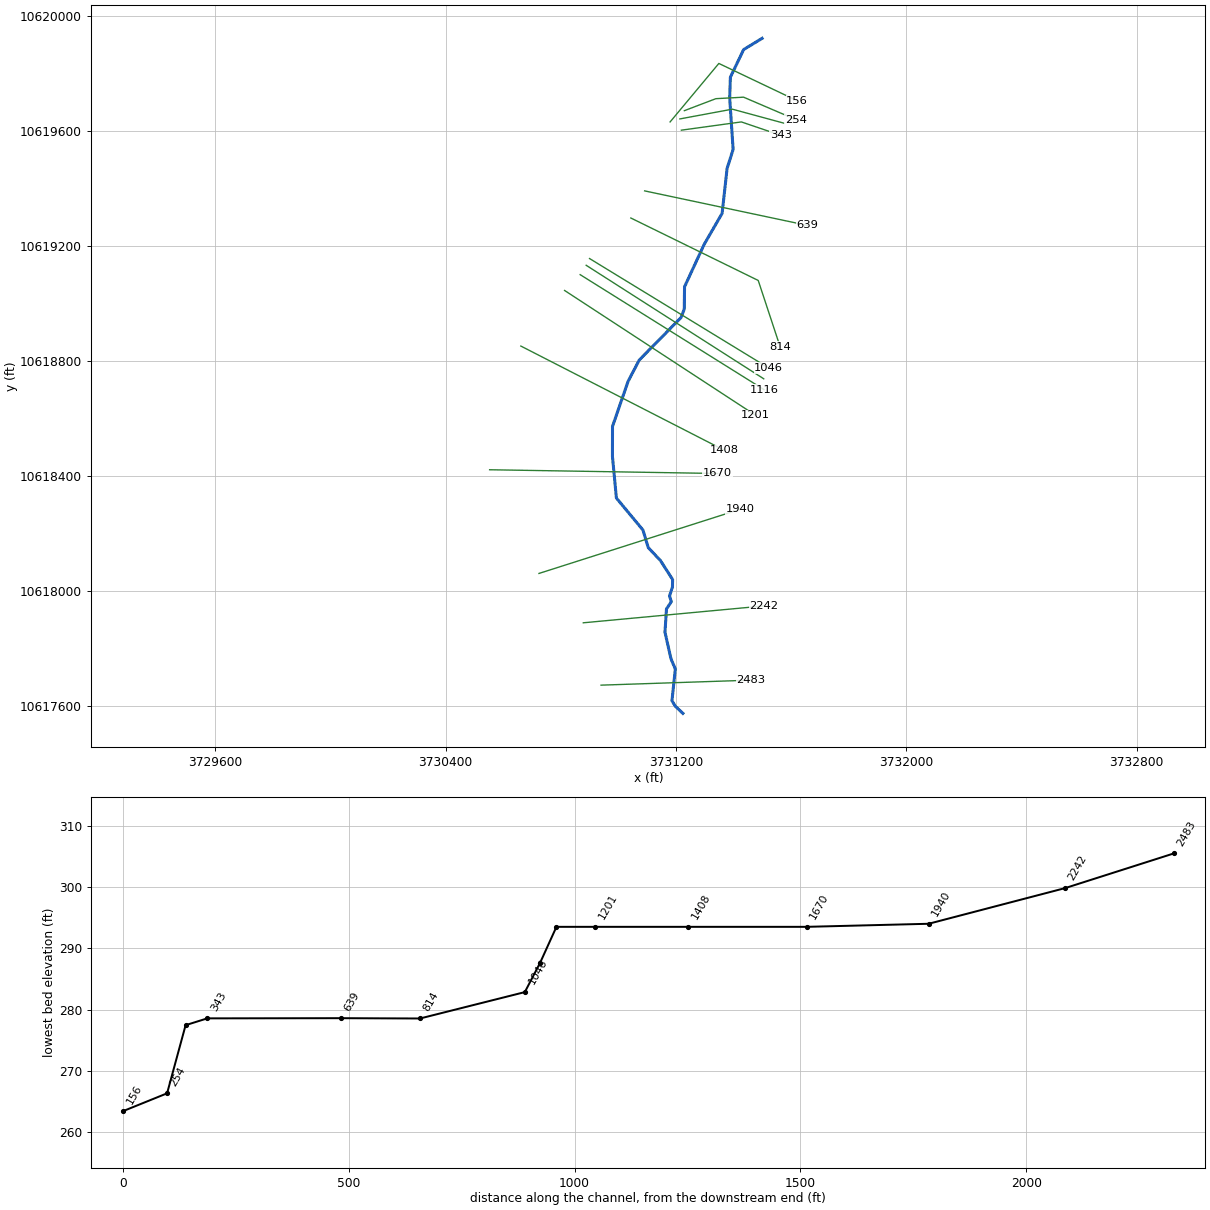
--- UNT 114 IN BOCR.prj (project) ---

Proj Title=UNT 114 IN BOCR Base Level Engineering
Current Plan=p01
Default Exp/Contr=0.3,0.1
English Units
Geom File=g01
Flow File=f01
Plan File=p01
Y Axis Title=Elevation
X Axis Title(PF)=Main Channel Distance
X Axis Title(XS)=Station
BEGIN DESCRIPTION:
UNT 114 IN BOCR
END DESCRIPTION:
DSS Export Rating Curves= 0
DSS Export Rating Curve Sorted= 0
DSS Export Volume Flow Curves= 0
DXF OffsetX= 0
DXF OffsetY= 0
DXF ScaleX= 1
DXF ScaleY= 10

--- UNT 114 IN BOCR.p01 (plan) ---

Plan Title=Multiple Run
Short Identifier=Multiple
Geom File=g01
Flow File=f01
Subcritical Flow
K Sum by GR= 0
Std Step Tol= 0.01
Critical Tol= 0.01
Num of Std Step Trials= 20
Max Error Tol= 0.3
Flow Tol Ratio= 0.001
Split Flow NTrial= 30
Split Flow Tol= 0.02
Split Flow Ratio= 0.02
Log Output Level= 0
Friction Slope Method= 1
Unsteady Friction Slope Method= 2
Unsteady Bridges Friction Slope Method= 1
Parabolic Critical Depth
Global Vel Dist=  1 , 1 , 1
Global Log Level= 0
CheckData=True
Encroach Param= -1, 0, 0, 0
BEGIN DESCRIPTION:
Multiple Run
END DESCRIPTION:

--- UNT 114 IN BOCR.f01 (steady flow) ---

Flow Title=Multiple
Program Version=4.10
Number of Profiles= 7
Profile Names=10-year,25-year,50-year,1pct_min,100-year,1pct_plu,500-year
River Rch & RM=UNT 114 IN BOCR,Reach-1         ,2483
     198     250     291     250     338     457     456
Boundary for River Rch & Prof#=UNT 114 IN BOCR,Reach-1         , 1
Up Type= 0
Dn Type= 3
Dn Slope=0.03
Boundary for River Rch & Prof#=UNT 114 IN BOCR,Reach-1         , 2
Up Type= 0
Dn Type= 3
Dn Slope=0.03
Boundary for River Rch & Prof#=UNT 114 IN BOCR,Reach-1         , 3
Up Type= 0
Dn Type= 3
Dn Slope=0.03
Boundary for River Rch & Prof#=UNT 114 IN BOCR,Reach-1         , 4
Up Type= 0
Dn Type= 3
Dn Slope=0.03
Boundary for River Rch & Prof#=UNT 114 IN BOCR,Reach-1         , 5
Up Type= 0
Dn Type= 3
Dn Slope=0.03
Boundary for River Rch & Prof#=UNT 114 IN BOCR,Reach-1         , 6
Up Type= 0
Dn Type= 3
Dn Slope=0.03
Boundary for River Rch & Prof#=UNT 114 IN BOCR,Reach-1         , 7
Up Type= 0
Dn Type= 3
Dn Slope=0.03
DSS Import GetInterval= 0
DSS Import GetPeak= 0
DSS Import FillOption= 0

--- UNT 114 IN BOCR.g01 (geometry) ---

Geom Title=Existing Conditions
Program Version=4.10

River Reach=UNT 114 IN BOCR ,Reach-1
Reach XY= 30
        3731224.       10617576.       3731197.5       10617601.
        3731186.       10617620.      3731197.75       10617730.
       3731182.5       10617766.      3731161.75       10617858.
        3731167.       10617939.      3731183.75       10617964.
       3731177.5       10617984.      3731187.75       10618015.
      3731188.25       10618041.        3731146.       10618107.
       3731103.5       10618152.      3731085.25       10618213.
        3730993.       10618324.      3730979.25       10618469.
       3730979.5       10618573.       3731033.5       10618729.
        3731072.       10618803.       3731217.5       10618951.
      3731228.75       10618980.      3731229.75       10619058.
      3731297.75       10619205.      3731360.25       10619313.
       3731377.5       10619469.       3731398.5       10619535.
       3731386.5       10619714.        3731389.       10619786.
        3731435.       10619882.      3731499.25       10619921.

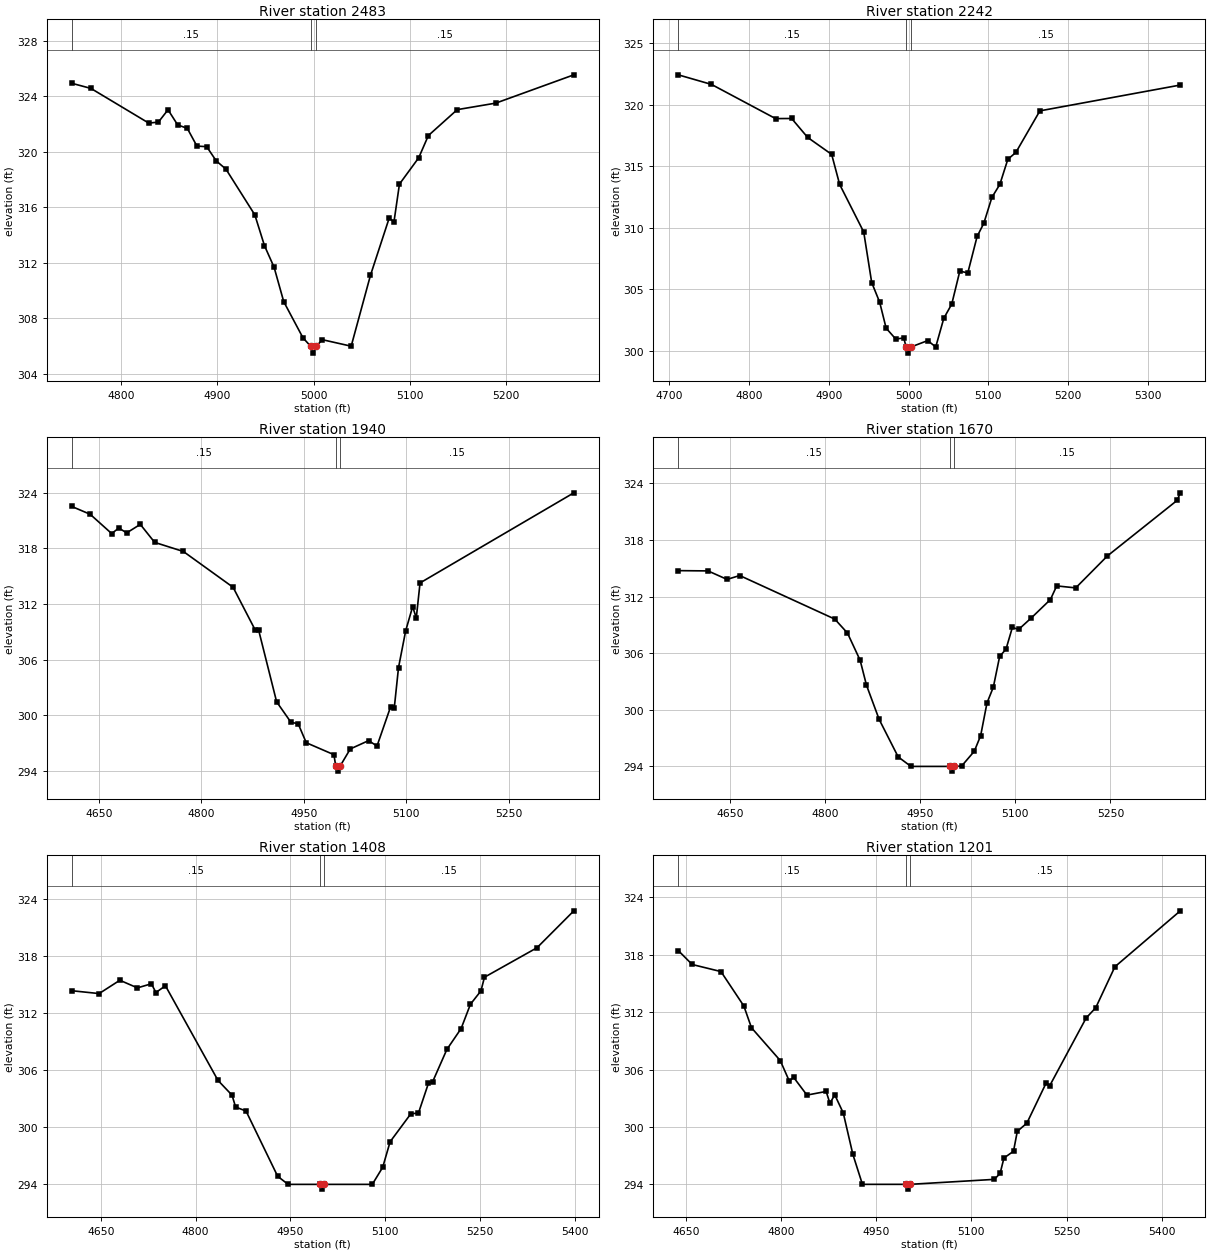
Type RM Length L Ch R = 1 ,2483    ,241,241,241
BEGIN DESCRIPTION:
UNT 114 IN BOCR 5.0
END DESCRIPTION:
XS GIS Cut Line= 2
      3730939.73     10617674.07      3731460.54     10617691.43
#Sta/Elev= 30
  4749.1  324.93    4769  324.56    4829  322.06    4839  322.13    4849  323.02
    4859  321.93    4869  321.68    4879   320.4  4889.1  320.36  4899.1  319.33
  4909.1  318.74  4939.1  315.44  4949.1  313.22  4959.1  311.66  4969.1  309.18
  4989.1  306.57    4997  305.97  4999.8  305.47    5003  305.97  5009.1  306.44
  5039.1  305.97  5059.1  311.08  5078.5   315.2  5083.5  314.93  5089.2  317.66
  5109.2  319.56  5119.2  321.16  5149.2  323.03  5189.2   323.5  5270.2  325.54
#Mann= 3 ,-1 , 0
  4749.1     .15       0    4997     .05       0    5003     .15       0
Bank Sta=4997,5003
XS Rating Curve= 0 ,0
Exp/Cntr=0.3,0.1

Type RM Length L Ch R = 1 ,2242    ,302,302,302
BEGIN DESCRIPTION:
Mapping XS 95a40d75
END DESCRIPTION:
XS GIS Cut Line= 2
      3730878.06     10617890.65      3731504.93     10617949.21
#Sta/Elev= 30
  4711.2  322.44  4752.9  321.66  4833.3  318.88  4853.4  318.89  4873.5  317.35
  4903.6  315.97  4913.6  313.53  4943.8  309.66  4953.8  305.55  4963.8  303.95
  4971.9  301.84  4983.9  300.96    4994  301.04    4997  300.31  4999.8  299.81
    5003  300.31  5024.1  300.83  5034.1  300.31  5044.2  302.64  5054.2   303.8
  5064.3  306.48  5074.3  306.33    5086   309.3  5094.4  310.37  5104.5  312.47
  5114.5  313.53  5124.5  315.57  5134.6  316.13  5164.7  319.51  5340.8  321.61
#Mann= 3 ,-1 , 0
  4711.2     .15       0    4997     .05       0    5003     .15       0
Bank Sta=4997,5003
XS Rating Curve= 0 ,0
Exp/Cntr=0.3,0.1

Type RM Length L Ch R = 1 ,1940    ,270,270,270
BEGIN DESCRIPTION:
Mapping XS a4432528
END DESCRIPTION:
XS GIS Cut Line= 2
      3730724.01     10618062.09      3731424.08     10618285.33
#Sta/Elev= 30
  4610.6  322.52  4637.5  321.68    4669   319.6  4679.5   320.2  4690.9  319.67
  4710.9  320.59  4731.9  318.65  4773.9  317.67  4846.7  313.81  4878.9  309.23
  4884.1  309.19  4910.4  301.47  4931.4  299.26  4941.9  299.11  4953.8  297.06
  4994.3  295.77    4997   294.5  4999.8     294    5003   294.5  5018.2  296.39
  5045.1  297.29  5057.3   296.7  5077.3  300.95  5082.6  300.82  5088.8  305.16
  5099.3  309.13  5109.5  311.73  5114.8   310.5  5120.3  314.28  5345.4  323.99
#Mann= 3 ,-1 , 0
  4610.6     .15       0    4997     .05       0    5003     .15       0
Bank Sta=4997,5003
XS Rating Curve= 0 ,0
Exp/Cntr=0.3,0.1

Type RM Length L Ch R = 1 ,1670    ,262,262,262
BEGIN DESCRIPTION:
Mapping XS b60e955b
END DESCRIPTION:
XS GIS Cut Line= 2
      3730552.61     10618422.33       3731344.6     10618409.31
#Sta/Elev= 30
  4568.2  314.76  4615.2  314.73  4645.2  313.83  4665.2  314.24  4815.2  309.62
  4835.2  308.14  4855.2  305.25  4865.2  302.61  4885.2  298.98  4915.2  295.01
  4935.3     294    4997     294  4999.8   293.5    5003     294  5015.3  294.04
  5035.3  295.61  5045.3  297.26  5055.3  300.73  5065.3   302.4  5075.3  305.67
  5085.3  306.43  5095.3  308.73  5105.3  308.53  5125.3  309.75  5155.3  311.69
  5165.3  313.14  5195.3  312.93  5245.3  316.32  5355.3  322.21  5360.3  323.01
#Mann= 3 ,-1 , 0
  4568.2     .15       0    4997     .05       0    5003     .15       0
Bank Sta=4997,5003
XS Rating Curve= 0 ,0
Exp/Cntr=0.3,0.1

Type RM Length L Ch R = 1 ,1408    ,207,207,207
BEGIN DESCRIPTION:
Mapping XS c0ec0ed5
END DESCRIPTION:
XS GIS Cut Line= 2
      3730661.04     10618852.04      3731368.51     10618489.62
#Sta/Elev= 30
  4603.9  314.36  4647.2  314.06    4680  315.46  4707.8  314.66    4730  315.09
  4737.1  314.17  4752.2  314.88  4835.4  304.93  4857.6  303.38  4863.3  302.13
  4879.8  301.71  4929.9  294.85  4946.4     294    4997     294  4999.8   293.5
    5003     294  5079.7     294  5096.2   295.8  5107.9  298.48  5140.7  301.42
  5152.8   301.5  5168.5  304.61  5175.3   304.8  5197.8  308.19  5220.3  310.38
  5235.1  312.94  5251.7  314.34  5257.3  315.78  5340.5  318.88  5398.8  322.76
#Mann= 3 ,-1 , 0
  4603.9     .15       0    4997     .05       0    5003     .15       0
Bank Sta=4997,5003
XS Rating Curve= 0 ,0
Exp/Cntr=0.3,0.1

Type RM Length L Ch R = 1 ,1201    ,85,85,85
BEGIN DESCRIPTION:
Mapping XS cd50091d
END DESCRIPTION:
XS GIS Cut Line= 2
      3730812.97     10619045.17      3731475.84     10618611.92
#Sta/Elev= 30
  4637.6  318.44  4659.6  316.98    4705  316.24  4741.1  312.64  4753.1  310.37
  4798.5  306.94  4812.8  304.79  4819.5  305.19  4840.6  303.33  4870.9  303.71
  4876.8  302.48  4884.5  303.35  4897.9  301.46    4913  297.14  4928.1     294
    4997     294  4999.8   293.5    5003     294  5136.2  294.52  5145.3  295.15
  5151.3  296.75  5166.4  297.46  5172.4  299.54  5187.5   300.4  5217.7  304.57
  5223.7  304.33    5281  311.39  5296.1  312.46  5326.3  316.74  5429.5  322.59
#Mann= 3 ,-1 , 0
  4637.6     .15       0    4997     .05       0    5003     .15       0
Bank Sta=4997,5003
XS Rating Curve= 0 ,0
Exp/Cntr=0.3,0.1

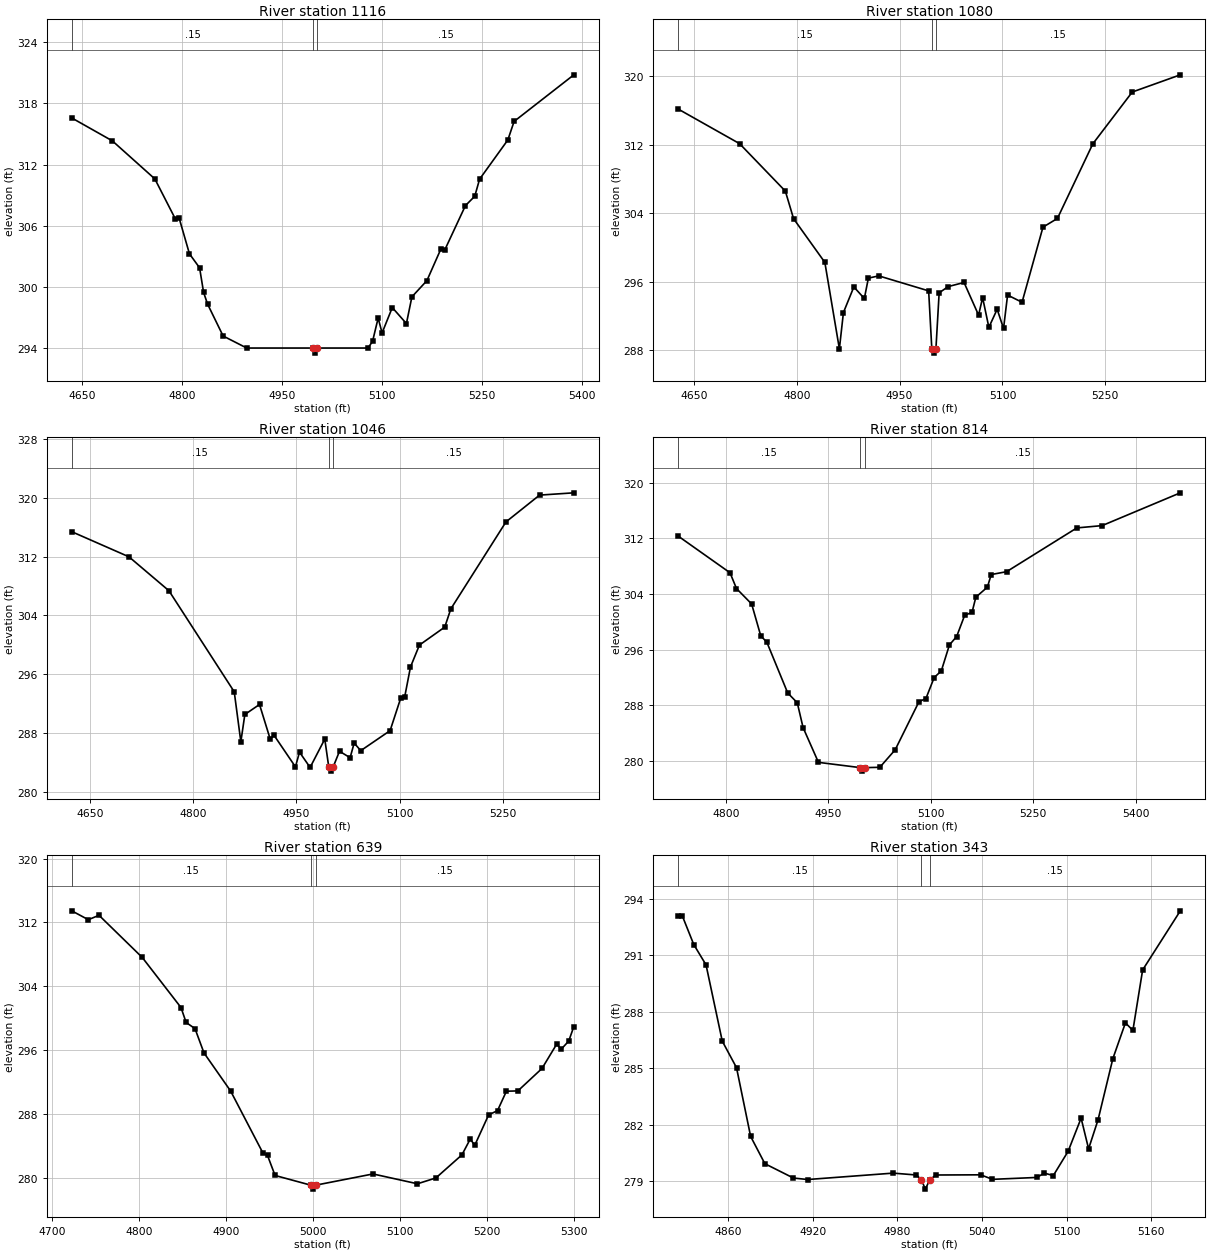
Type RM Length L Ch R = 1 ,1116    ,36,36,36
BEGIN DESCRIPTION:
Mapping XS 6d80dd84
END DESCRIPTION:
XS GIS Cut Line= 2
       3730867.1     10619100.08      3731505.57     10618700.88
#Sta/Elev= 30
    4635  316.57  4695.9  314.32  4759.6  310.59  4790.3  306.67  4796.2  306.71
  4811.5  303.24  4826.7  301.87  4832.7  299.46  4838.6  298.32    4862  295.18
  4897.4     294    4997     294  4999.8   293.5    5003     294  5079.2     294
  5086.1  294.65  5094.5  296.94  5100.4  295.48  5115.7  297.97  5136.9   296.4
  5145.1  299.02  5167.6  300.61  5188.8  303.75  5194.7  303.66  5225.4  307.97
  5239.4  308.89  5246.6  310.56    5289  314.41  5298.4  316.23    5388   320.8
#Mann= 3 ,-1 , 0
    4635     .15       0    4997     .05       0    5003     .15       0
Bank Sta=4997,5003
XS Rating Curve= 0 ,0
Exp/Cntr=0.3,0.1

Type RM Length L Ch R = 1 ,1080    ,34,34,34
BEGIN DESCRIPTION:
Mapping XS 913538e0
END DESCRIPTION:
XS GIS Cut Line= 2
      3730887.97     10619132.61      3731504.89     10618738.25
#Sta/Elev= 30
  4627.2  316.16  4716.7  312.12  4783.4  306.58  4795.4  303.36    4841  298.26
  4862.2  288.16  4868.1   292.4  4883.3  295.39  4898.6  294.04  4904.5  296.42
  4919.7  296.68  4992.4  294.93    4997  288.16  4999.8  287.66    5003  288.16
  5007.7   294.7  5020.8  295.43    5044  295.91  5065.2   292.1  5071.1  294.14
  5080.2  290.67  5092.3  292.78  5101.6  290.54  5107.5  294.44  5128.6   293.6
  5159.1  302.37  5180.2  303.39  5231.8   312.1  5289.3  318.15  5359.4  320.16
#Mann= 3 ,-1 , 0
  4627.2     .15       0    4997     .05       0    5003     .15       0
Bank Sta=4997,5003
XS Rating Curve= 0 ,0
Exp/Cntr=0.3,0.1

Type RM Length L Ch R = 1 ,1046    ,232,232,232
BEGIN DESCRIPTION:
Mapping XS 191743e8
END DESCRIPTION:
XS GIS Cut Line= 2
      3730899.71     10619156.04      3731522.07     10618775.85
#Sta/Elev= 30
  4623.6  315.37  4706.7  311.96  4764.7  307.36  4859.6  293.63  4869.2  286.84
    4875  290.55  4896.3  291.91  4911.8  287.22  4917.6   287.7  4948.5  283.44
  4954.4  285.44  4969.8  283.36  4991.1  287.21    4997  283.36  4999.8  282.86
    5003  283.36  5012.5  285.56  5027.9  284.68  5033.8  286.67  5043.4  285.64
    5086  288.36  5101.4  292.77  5107.3  292.99  5115.6     297  5128.6  299.98
  5165.4  302.42  5174.2  304.89  5254.3   316.7  5303.1  320.34  5352.9  320.65
#Mann= 3 ,-1 , 0
  4623.6     .15       0    4997     .05       0    5003     .15       0
Bank Sta=4997,5003
XS Rating Curve= 0 ,0
Exp/Cntr=0.3,0.1

Type RM Length L Ch R = 1 ,814     ,175,175,175
BEGIN DESCRIPTION:
Mapping XS 07ad14c7
END DESCRIPTION:
XS GIS Cut Line= 3
      3731043.06     10619296.88      3731485.72     10619079.89
      3731561.66     10618849.89
#Sta/Elev= 30
  4730.2  312.32    4806  307.06  4815.5  304.79  4837.7  302.57    4851  298.01
    4860  297.07  4890.5  289.79  4904.5  288.38    4913  284.82  4935.5  279.82
    4997  279.06  4999.8  278.56    5003  279.06  5025.4  279.11  5047.9  281.63
  5082.7  288.53  5092.9  288.99    5105  292.01  5115.4  292.95  5127.3  296.69
  5137.9   297.9  5149.6  300.94  5160.4  301.37    5166  303.55  5182.9  304.99
  5188.5   306.8    5211  307.21  5313.9   313.5  5350.9  313.83  5465.4  318.54
#Mann= 3 ,-1 , 0
  4730.2     .15       0    4997     .05       0    5003     .15       0
Bank Sta=4997,5003
XS Rating Curve= 0 ,0
Exp/Cntr=0.3,0.1

Type RM Length L Ch R = 1 ,639     ,296,296,296
BEGIN DESCRIPTION:
Mapping XS 4830f4fc
END DESCRIPTION:
XS GIS Cut Line= 2
      3731091.05     10619391.06      3731655.41     10619271.43
#Sta/Elev= 30
  4722.5  313.46  4741.5  312.35  4753.8   312.9  4803.5  307.62    4848  301.35
  4853.9  299.48  4864.1  298.71  4874.4  295.67    4905   290.9  4942.3   283.1
  4947.4  282.83  4956.1  280.32    4997  279.11  4999.8  278.61    5003  279.11
  5068.6  280.51  5119.7  279.28  5140.9  280.01  5170.8   282.9  5180.4  284.89
  5185.5  284.09  5201.5  287.91  5211.7  288.44  5221.9  290.87  5235.1  290.91
  5262.8  293.72  5279.7  296.77  5284.8  296.12  5293.5  297.15  5299.4  298.97
#Mann= 3 ,-1 , 0
  4722.5     .15       0    4997     .05       0    5003     .15       0
Bank Sta=4997,5003
XS Rating Curve= 0 ,0
Exp/Cntr=0.3,0.1

Type RM Length L Ch R = 1 ,343     ,48,48,48
BEGIN DESCRIPTION:
Mapping XS eb6cb45c
END DESCRIPTION:
XS GIS Cut Line= 3
      3731218.74       10619602.      3731427.03     10619630.64
      3731564.85     10619583.83
#Sta/Elev= 30
  4824.7  293.09  4827.6  293.09  4835.7  291.57  4844.4  290.49  4855.9  286.44
    4866  285.03    4876  281.38  4886.1  279.93  4906.3  279.17  4916.4  279.09
    4977  279.43  4993.5  279.33    4997  279.08  4999.8  278.58    5003  279.08
  5007.3  279.33    5039  279.34  5047.4   279.1  5078.8   279.2  5084.1  279.43
  5090.5   279.3    5101  280.59  5110.2  282.35  5115.5  280.72  5122.2  282.26
  5132.7  285.51  5141.6  287.41  5146.9  287.01  5153.8  290.22  5180.5  293.36
#Mann= 3 ,-1 , 0
  4824.7     .15       0    4997     .05       0    5003     .15       0
Bank Sta=4997,5003
XS Rating Curve= 0 ,0
Exp/Cntr=0.3,0.1

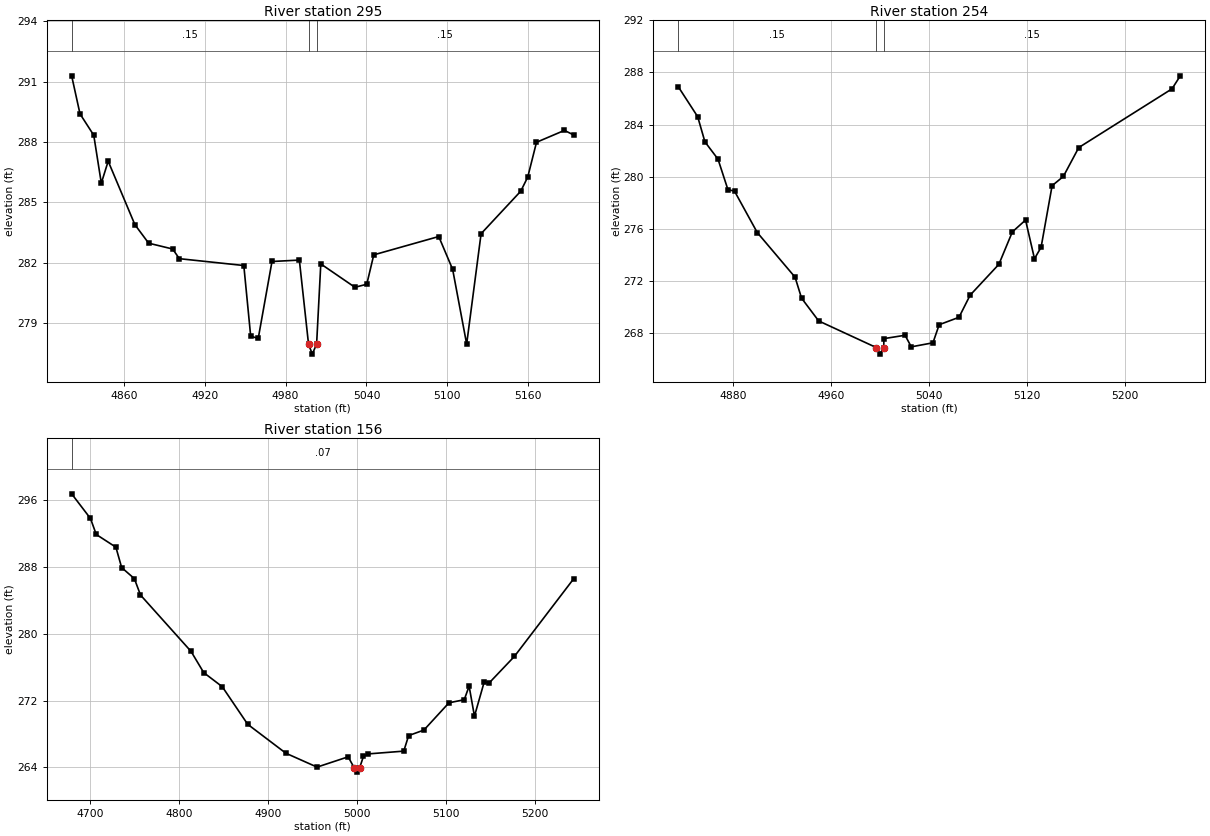
Type RM Length L Ch R = 1 ,295     ,41,41,41
BEGIN DESCRIPTION:
Mapping XS 96221fc0
END DESCRIPTION:
XS GIS Cut Line= 3
      3731213.51     10619641.06      3731395.78     10619674.91
      3731576.36     10619625.89
#Sta/Elev= 30
  4821.3  291.29  4827.5   289.4  4837.7  288.34  4843.3  285.96  4848.4  287.05
  4868.2   283.9  4878.4  282.98  4896.2  282.69  4901.2  282.21    4949  281.87
  4954.1  278.36  4959.7  278.25  4969.9  282.07  4990.2  282.14    4997  277.97
  4999.8  277.47    5003  277.97  5006.1  281.95  5031.4  280.79  5040.2  280.94
  5045.4   282.4  5093.6  283.31  5103.9  281.68  5114.3  277.97    5125  283.45
  5154.4  285.56  5159.6  286.26  5166.1  287.99  5186.8  288.58  5193.8  288.35
#Mann= 3 ,-1 , 0
  4821.3     .15       0    4997     .05       0    5003     .15       0
Bank Sta=4997,5003
XS Rating Curve= 0 ,0
Exp/Cntr=0.3,0.1

Type RM Length L Ch R = 1 ,254     ,98,98,98
BEGIN DESCRIPTION:
Mapping XS c8784165
END DESCRIPTION:
XS GIS Cut Line= 4
      3731229.14     10619669.71      3731338.49     10619711.37
      3731434.85     10619716.57       3731615.9     10619638.98
#Sta/Elev= 30
  4834.9  286.92  4850.9   284.6  4856.8  282.67  4867.5  281.34  4875.6     279
    4881  278.88  4899.6   275.7  4930.5  272.27  4935.8  270.66  4949.8  268.91
    4997  266.86  4999.8  266.36    5003  266.86  5003.1  267.55  5020.4  267.81
  5025.5  266.92  5043.2  267.23  5048.3  268.62  5064.5  269.19  5073.6  270.89
  5097.1  273.26  5108.1  275.75  5118.9  276.66  5126.2  273.69  5131.6  274.57
  5140.6   279.3  5149.8  280.01  5162.4  282.23  5238.6  286.74  5245.4  287.74
#Mann= 3 ,-1 , 0
  4834.9     .15       0    4997     .05       0    5003     .15       0
Bank Sta=4997,5003
XS Rating Curve= 0 ,0
Exp/Cntr=0.3,0.1

Type RM Length L Ch R = 1 ,156     ,0,0,0
BEGIN DESCRIPTION:
UNT 114 IN BOCR 1.0
END DESCRIPTION:
XS GIS Cut Line= 3
      3731179.64     10619630.64      3731348.91     10619833.76
      3731620.66     10619704.35
#Sta/Elev= 30
  4678.8  296.72    4700  293.77  4706.5  291.86  4728.6  290.34  4735.1   287.9
  4749.4  286.58  4756.3  284.62  4813.2  277.88  4827.5  275.34  4848.4  273.65
    4877  269.16    4920   265.7  4955.1  264.04  4990.1  265.27    4997  263.94
  4999.8  263.44    5003  263.94  5007.3  265.32  5012.8  265.62  5052.7  265.95
  5058.2  267.81  5075.4  268.47  5103.6  271.73  5120.8   272.1  5126.3  273.72
  5132.3  270.13  5143.3  274.23  5149.1  274.13  5177.3  277.28  5244.2  286.59
#Mann= 1 ,-1 , 0
  4678.8     .07       0
Bank Sta=4997,5003
XS Rating Curve= 0 ,0
Exp/Cntr=0.3,0.1

Chan Stop Cuts=-1
Use User Specified Reach Order=0
Composite Channel Slope=5