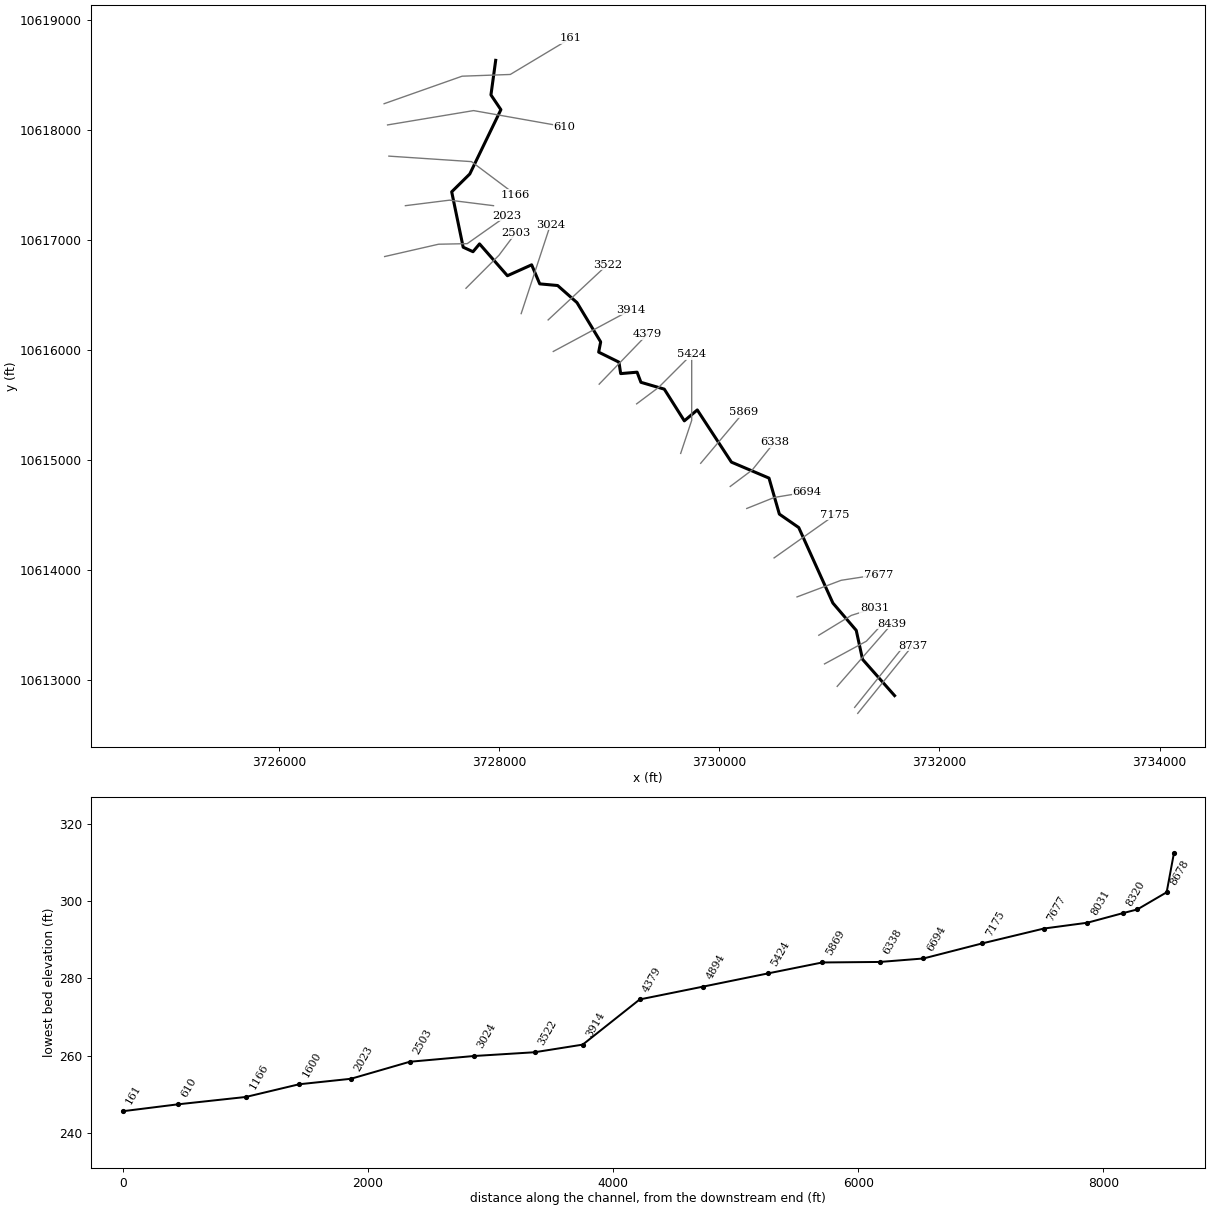
--- UNT 115 IN BOCR.prj (project) ---

Proj Title=UNT 115 IN BOCR Base Level Engineering
Current Plan=p01
Default Exp/Contr=0.3,0.1
English Units
Geom File=g01
Flow File=f01
Plan File=p01
Y Axis Title=Elevation
X Axis Title(PF)=Main Channel Distance
X Axis Title(XS)=Station
BEGIN DESCRIPTION:
UNT 115 IN BOCR
END DESCRIPTION:
DSS Export Rating Curves= 0
DSS Export Rating Curve Sorted= 0
DSS Export Volume Flow Curves= 0
DXF OffsetX= 0
DXF OffsetY= 0
DXF ScaleX= 1
DXF ScaleY= 10

--- UNT 115 IN BOCR.p01 (plan) ---

Plan Title=Multiple Run
Short Identifier=Multiple
Geom File=g01
Flow File=f01
Subcritical Flow
K Sum by GR= 0
Std Step Tol= 0.01
Critical Tol= 0.01
Num of Std Step Trials= 20
Max Error Tol= 0.3
Flow Tol Ratio= 0.001
Split Flow NTrial= 30
Split Flow Tol= 0.02
Split Flow Ratio= 0.02
Log Output Level= 0
Friction Slope Method= 1
Unsteady Friction Slope Method= 2
Unsteady Bridges Friction Slope Method= 1
Parabolic Critical Depth
Global Vel Dist=  1 , 1 , 1
Global Log Level= 0
CheckData=True
Encroach Param= -1, 0, 0, 0
BEGIN DESCRIPTION:
Multiple Run
END DESCRIPTION:

--- UNT 115 IN BOCR.f01 (steady flow) ---

Flow Title=Multiple
Number of Profiles=7
Profile Names=10-year,25-year,50-year,1pct_min,100-year,1pct_plu,500-year
River Rch & RM= UNT 115 IN BOCR,Reach-1,8737
     445     592     712     630     851    1151    1221
River Rch & RM= UNT 115 IN BOCR,Reach-1,2023
     714     976    1195    1074    1453    1965    2158
Boundary for River Rch & Prof#=UNT 115 IN BOCR,Reach-1,1
Up Type=0
Dn Type=3
Dn Slope=0.005
Boundary for River Rch & Prof#=UNT 115 IN BOCR,Reach-1,2
Up Type=0
Dn Type=3
Dn Slope=0.005
Boundary for River Rch & Prof#=UNT 115 IN BOCR,Reach-1,3
Up Type=0
Dn Type=3
Dn Slope=0.005
Boundary for River Rch & Prof#=UNT 115 IN BOCR,Reach-1,4
Up Type=0
Dn Type=3
Dn Slope=0.005
Boundary for River Rch & Prof#=UNT 115 IN BOCR,Reach-1,5
Up Type=0
Dn Type=3
Dn Slope=0.005
Boundary for River Rch & Prof#=UNT 115 IN BOCR,Reach-1,6
Up Type=0
Dn Type=3
Dn Slope=0.005
Boundary for River Rch & Prof#=UNT 115 IN BOCR,Reach-1,7
Up Type=0
Dn Type=3
Dn Slope=0.005

--- UNT 115 IN BOCR.g01 (geometry) ---

Geom Title=Existing Conditions
Program Version=4.10

River Reach=UNT 115 IN BOCR ,Reach-1
Reach XY= 30
      3731592.14     10612860.54      3731301.25       10613190.
        3731244.       10613453.        3731032.       10613701.
      3730721.75       10614387.      3730545.75       10614509.
      3730451.75       10614836.       3730110.5       10614981.
      3729800.25       10615455.      3729682.75       10615356.
      3729500.75       10615644.       3729288.5       10615706.
      3729253.75       10615798.      3729104.75       10615785.
        3729089.       10615889.      3728904.75       10615980.
        3728923.       10616073.      3728707.75       10616430.
      3728532.25       10616585.       3728369.5       10616600.
        3728296.       10616773.        3728076.       10616674.
      3727822.75       10616963.       3727763.5       10616892.
      3727674.25       10616933.        3727570.       10617436.
      3727734.25       10617598.      3728016.75       10618182.
       3727926.5       10618316.       3727969.5       10618630.

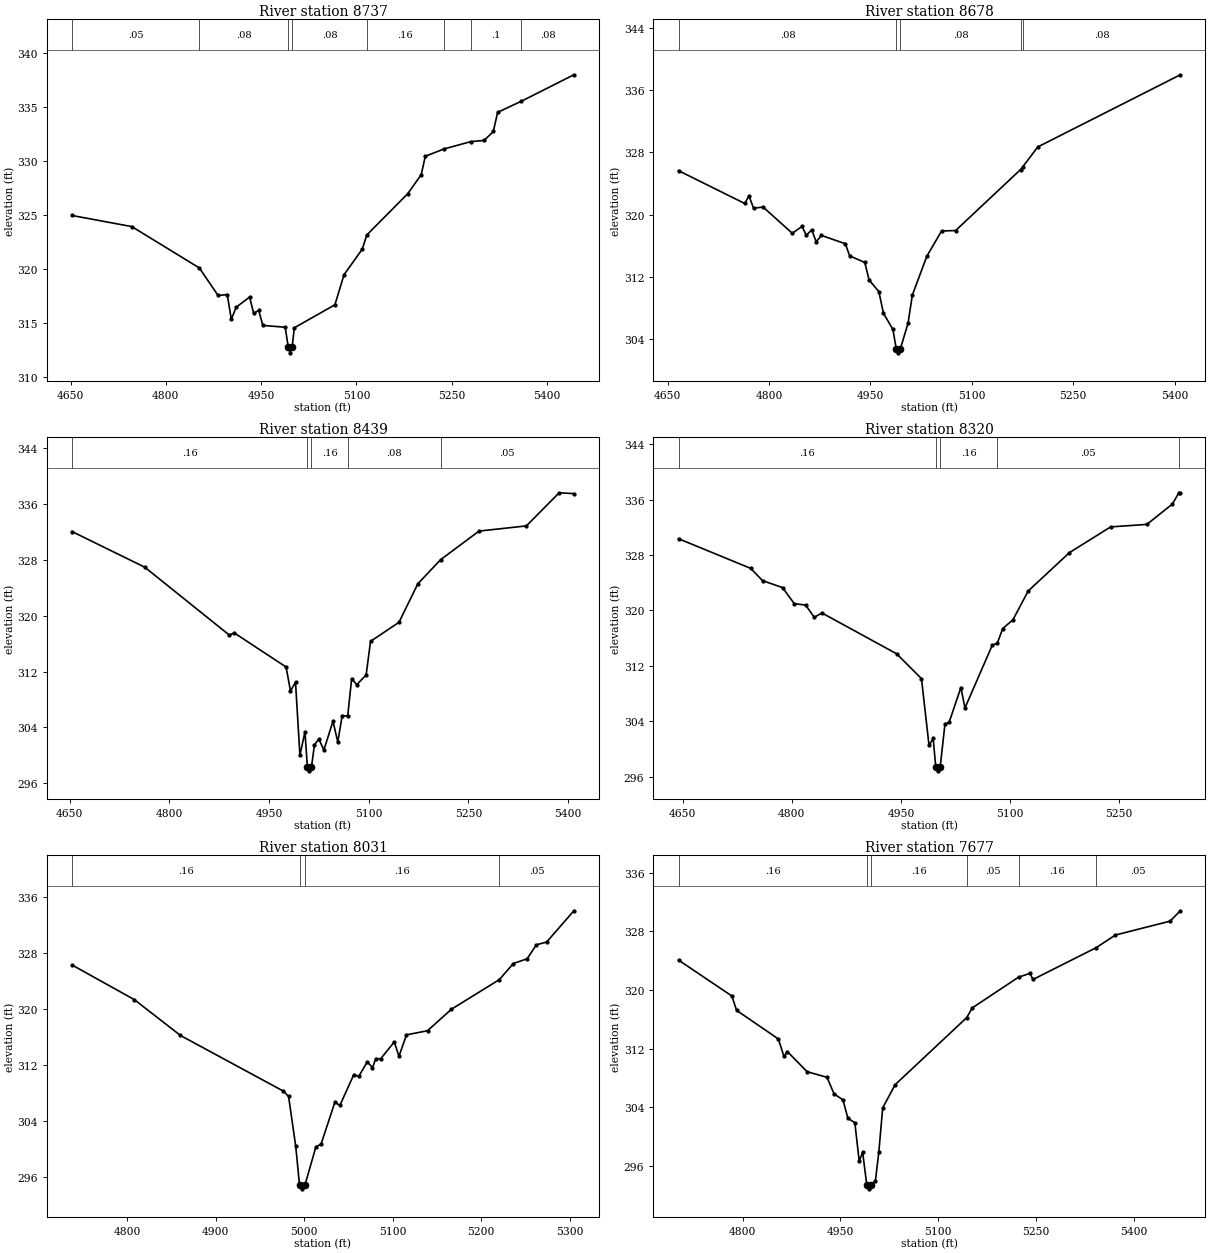
Type RM Length L Ch R = 1 ,8737    ,59,59,59
BEGIN DESCRIPTION:
UNT 115 IN BOCR 18.0
END DESCRIPTION:
XS GIS Cut Line= 2
      3731257.68     10612699.31      3731754.62     10613313.44
#Sta/Elev= 30
  4652.4  324.99  4746.5  323.96  4852.8  320.13  4882.3  317.58  4896.7  317.67
  4903.1  315.37  4910.8  316.49  4931.9  317.44  4938.3  315.93  4946.3   316.2
  4952.7  314.81    4988  314.64  4992.8  312.77  4995.6  312.27  4998.8  312.77
  5002.3  314.59  5066.2  316.72  5080.6  319.51  5109.4  321.88  5116.2  323.17
  5180.9  327.01  5202.1  328.77  5208.5  330.47  5237.4  331.14  5280.1  331.83
  5301.2  331.94  5315.6  332.77  5322.4  334.54  5359.7  335.57  5442.4  338.02
#Mann= 8 ,-1 , 0
  4652.4     .05       0  4852.8     .08       0  4992.8     .07       0
  4998.8     .08       0  5116.2     .16       0  5237.4     .08       0
  5280.1      .1       0  5359.7     .08       0
Bank Sta=4992.8,4998.8
XS Rating Curve= 0 ,0
Exp/Cntr=0.3,0.1

Type RM Length L Ch R = 1 ,8678    ,239,239,239
BEGIN DESCRIPTION:
Mapping XS a99c62df
END DESCRIPTION:
XS GIS Cut Line= 2
      3731229.51     10612753.61      3731693.87     10613332.99
#Sta/Elev= 30
  4666.1  325.65    4764  321.43  4770.4   322.4  4777.1  320.82  4791.2  320.97
  4834.4   317.6  4848.8  318.47  4855.2  317.34  4863.2  318.04  4869.7  316.51
  4877.6  317.32  4912.9  316.25  4919.3   314.7  4941.7  313.84  4948.1  311.58
  4962.5   310.1  4969.3  307.31  4983.3  305.23  4988.3  302.72    4991  302.22
  4994.3  302.72  5005.7  306.03  5012.1  309.65  5033.4  314.62  5055.3  317.89
  5076.1  317.95  5172.2  325.79  5175.5  326.15  5197.7   328.7  5408.6  337.98
#Mann= 5 ,-1 , 0
  4666.1     .08       0  4988.3     .07       0  4994.3     .08       0
  5172.2     .16       0  5175.5     .08       0
Bank Sta=4988.3,4994.3
XS Rating Curve= 0 ,0
Exp/Cntr=0.3,0.1

Type RM Length L Ch R = 1 ,8439    ,119,119,119
BEGIN DESCRIPTION:
Mapping XS 46cedb2b
END DESCRIPTION:
XS GIS Cut Line= 2
      3731071.05     10612944.54      3731568.05     10613513.16
#Sta/Elev= 30
  4653.4  332.03  4762.8  326.93    4890  317.22  4897.6  317.52  4975.5  312.65
  4982.1  309.23  4989.7  310.45  4996.3  300.02  5003.9  303.36  5007.6  298.29
  5010.3  297.79  5013.6  298.29  5018.2  301.51  5024.8  302.32  5032.4  300.78
  5046.1  304.89  5053.3  301.91  5059.9  305.69  5068.2  305.63  5074.2  310.99
  5081.8  310.11    5096  311.52  5102.6  316.32  5145.4  319.04  5173.8  324.56
  5208.1  328.01  5265.9   332.1  5337.1  332.84  5386.5  337.58  5408.6  337.46
#Mann= 5 ,-1 , 0
  4653.4     .16       0  5007.6     .07       0  5013.6     .16       0
  5068.2     .08       0  5208.1     .05       0
Bank Sta=5007.6,5013.6
XS Rating Curve= 0 ,0
Exp/Cntr=0.3,0.1

Type RM Length L Ch R = 1 ,8320    ,289,289,289
BEGIN DESCRIPTION:
Mapping XS 798b6c3c
END DESCRIPTION:
XS GIS Cut Line= 3
      3730956.02     10613148.53      3731335.82     10613354.71
      3731511.59      10613543.5
#Sta/Elev= 30
  4644.2  330.37  4743.5  326.08  4759.7  324.31  4787.2  323.31  4803.4  320.98
    4819  320.78  4830.9  319.01  4841.4  319.64  4944.1  313.74  4978.3  310.15
  4988.7  300.49  4994.4   301.5    4998  297.32  5000.8  296.82    5004  297.32
  5010.6  303.59  5016.3  303.82  5032.5  308.86  5038.1   305.9  5075.7  314.99
  5082.6  315.25    5090  317.38  5104.1  318.65  5125.1  322.82  5181.8  328.36
  5238.5  332.08  5288.3  332.44  5323.5  335.39  5332.2  337.01  5334.3  337.01
#Mann= 5 ,-1 , 0
  4644.2     .16       0    4998     .07       0    5004     .16       0
  5082.6     .05       0  5332.2      .1       0
Bank Sta=4998,5004
XS Rating Curve= 0 ,0
Exp/Cntr=0.3,0.1

Type RM Length L Ch R = 1 ,8031    ,354,354,354
BEGIN DESCRIPTION:
UNT 115 IN BOCR 17.0
END DESCRIPTION:
XS GIS Cut Line= 3
      3730903.95     10613408.96       3731199.1     10613589.08
      3731409.93     10613655.78
#Sta/Elev= 30
  4737.8   326.3  4808.1  321.36  4860.3  316.24  4976.5   308.3  4982.4  307.54
  4990.5  300.41  4994.8  294.85  4997.6  294.35  5000.8  294.85  5013.3  300.36
  5019.1  300.73  5034.6  306.68  5040.4  306.27  5055.9   310.6  5061.8  310.43
  5071.3  312.48  5077.2  311.65  5080.9  312.92  5086.5  312.92  5101.8  315.32
  5107.1  313.27  5115.6  316.33  5139.4  316.92  5166.4  319.99  5220.5  324.21
  5236.3  326.51  5251.9  327.19  5262.4  329.19  5273.9  329.57  5304.7  334.04
#Mann= 4 ,-1 , 0
  4737.8     .16       0  4994.8     .07       0  5000.8     .16       0
  5220.5     .05       0
Bank Sta=4994.8,5000.8
XS Rating Curve= 0 ,0
Exp/Cntr=0.3,0.1

Type RM Length L Ch R = 1 ,7677    ,502,502,502
BEGIN DESCRIPTION:
Mapping XS be2c7573
END DESCRIPTION:
XS GIS Cut Line= 3
      3730706.24     10613756.97       3731107.3     10613908.02
      3731445.26     10613960.02
#Sta/Elev= 30
  4701.4  324.07  4783.3  319.17  4790.5  317.21  4854.6  313.31  4863.3  310.92
  4868.6  311.58  4898.8  308.84  4929.4  308.07  4940.1  305.83  4953.9  304.98
  4961.5  302.47  4972.1  301.89  4978.8  296.65  4984.1  297.83  4990.5  293.35
  4993.3  292.85  4996.5  293.35  5003.6  293.88    5009  297.91  5014.9   303.9
  5033.9  307.06  5143.8  316.21  5152.5  317.55  5223.5  321.74  5240.7  322.25
  5245.8  321.43  5342.8  325.77  5372.2  327.49  5456.1  329.38  5471.9   330.8
#Mann= 6 ,-1 , 0
  4701.4     .16       0  4990.5     .07       0  4996.5     .16       0
  5143.8     .05       0  5223.5     .16       0  5342.8     .05       0
Bank Sta=4990.5,4996.5
XS Rating Curve= 0 ,0
Exp/Cntr=0.3,0.1

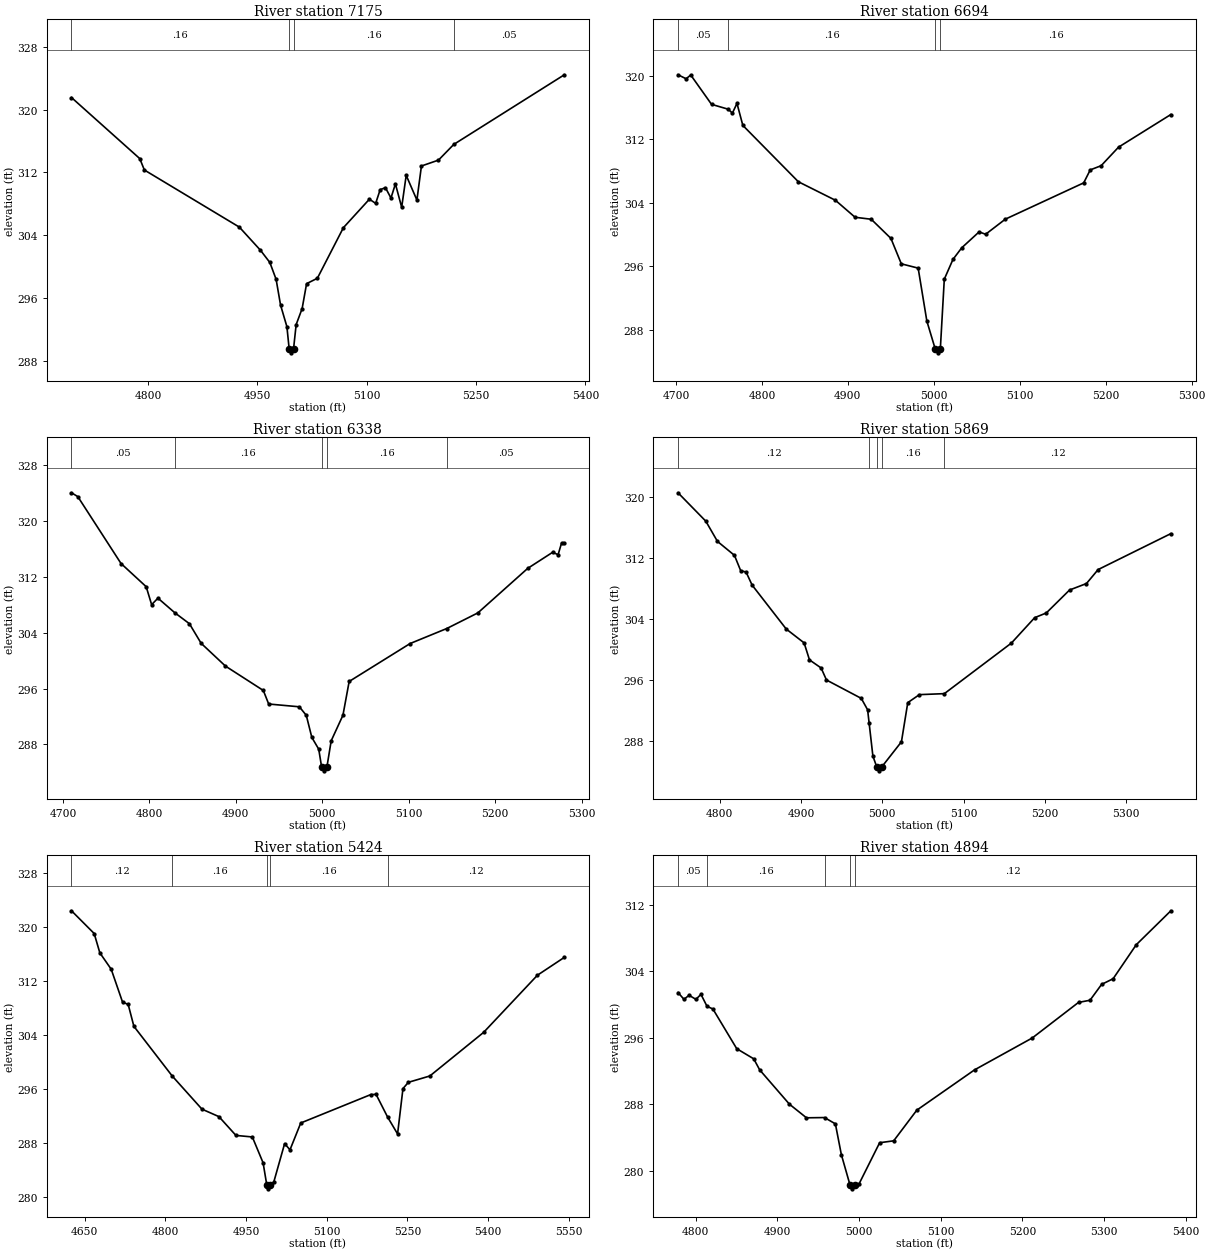
Type RM Length L Ch R = 1 ,7175    ,481,481,481
BEGIN DESCRIPTION:
Mapping XS 52ea147f
END DESCRIPTION:
XS GIS Cut Line= 2
      3730497.95     10614111.16      3731050.03     10614501.79
#Sta/Elev= 30
  4694.9  321.54  4788.6  313.76  4794.9  312.31  4925.3  305.03  4954.2  302.09
  4967.1  300.53  4975.7  298.38  4981.8   295.1  4990.5  292.35  4993.6  289.52
  4996.4  289.02  4999.6  289.52  5003.2  292.62  5011.4  294.66  5017.5  297.83
  5032.3  298.52    5068  304.96  5103.7  308.59  5112.3  308.06  5118.5  309.81
  5125.7  310.06  5133.3  308.74  5139.4  310.54    5148  307.56  5154.2  311.63
  5168.9  308.48  5175.1  312.82  5198.5  313.57  5219.5  315.57  5371.2  324.44
#Mann= 4 ,-1 , 0
  4694.9     .16       0  4993.6     .07       0  4999.6     .16       0
  5219.5     .05       0
Bank Sta=4993.6,4999.6
XS Rating Curve= 0 ,0
Exp/Cntr=0.3,0.1

Type RM Length L Ch R = 1 ,6694    ,356,356,356
BEGIN DESCRIPTION:
UNT 115 IN BOCR 14.0
END DESCRIPTION:
XS GIS Cut Line= 3
      3730249.63      10614560.2      3730499.61     10614660.19
      3730799.63     10614710.19
#Sta/Elev= 30
  4702.4   320.1  4711.8   319.6  4717.2  320.07  4741.4  316.38  4760.7  315.77
  4765.7  315.28    4771   316.5  4777.8  313.73  4842.4  306.64  4885.5  304.31
  4908.4  302.17  4927.2  301.92  4950.1  299.51  4962.2  296.31  4981.8  295.77
  4991.9  289.11  5001.6  285.61  5004.3  285.11  5007.6  285.61  5012.2  294.38
  5022.3  296.87  5032.5  298.33  5052.7  300.33  5060.3  300.03  5083.2  301.93
  5174.4   306.5    5182  308.13  5194.7  308.66  5214.9  310.99  5275.8   315.1
#Mann= 4 ,-1 , 0
  4702.4     .05       0  4760.7     .16       0  5001.6     .07       0
  5007.6     .16       0
Bank Sta=5001.6,5007.6
XS Rating Curve= 0 ,0
Exp/Cntr=0.3,0.1

Type RM Length L Ch R = 1 ,6338    ,469,469,469
BEGIN DESCRIPTION:
UNT 115 IN BOCR 13.0
END DESCRIPTION:
XS GIS Cut Line= 3
      3730099.62      10614760.2      3730299.61     10614910.19
      3730499.58     10615160.16
#Sta/Elev= 30
  4709.9  324.03  4717.2  323.48  4767.2   313.9  4796.3  310.58  4802.6  308.01
  4809.9  308.94  4829.4  306.85  4846.3  305.28  4859.9  302.47    4888  299.21
  4931.8  295.72    4938  293.78  4973.5  293.38  4981.5  292.16  4987.9     289
  4995.9  287.31  4999.3  284.71  5002.1  284.21  5005.3  284.71  5010.3  288.51
  5023.9  292.17  5031.1  297.01  5101.6  302.44    5144  304.59    5180  306.83
  5237.6   313.2  5266.4   315.5  5272.8  315.17  5276.8  316.83    5280  316.83
#Mann= 5 ,-1 , 0
  4709.9     .05       0  4829.4     .16       0  4999.3     .07       0
  5005.3     .16       0    5144     .05       0
Bank Sta=4999.3,5005.3
XS Rating Curve= 0 ,0
Exp/Cntr=0.3,0.1

Type RM Length L Ch R = 1 ,5869    ,445,445,445
BEGIN DESCRIPTION:
Mapping XS 8941dab6
END DESCRIPTION:
XS GIS Cut Line= 2
      3729831.27     10614970.54      3730221.91     10615434.09
#Sta/Elev= 30
  4748.8  320.57    4783  316.84  4797.3  314.19  4818.2  312.36  4825.9  310.34
  4832.5  310.17  4839.9  308.46  4881.9  302.69  4903.9  300.87  4910.5  298.64
  4924.8  297.58  4931.4     296  4974.2  293.59    4982  292.09  4983.8  290.41
  4988.5  286.01  4993.3  284.58    4996  284.08  4999.3  284.58  5023.6  287.89
  5031.4  293.03  5045.7  294.08  5076.4  294.21  5158.9  300.85  5187.5  304.18
  5201.8   304.8  5230.4  307.81  5251.2  308.66  5265.5  310.49    5355  315.21
#Mann= 5 ,-1 , 0
  4748.8     .12       0  4983.8     .16       0  4993.3     .07       0
  4999.3     .16       0  5076.4     .12       0
Bank Sta=4993.3,4999.3
XS Rating Curve= 0 ,0
Exp/Cntr=0.3,0.1

Type RM Length L Ch R = 1 ,5424    ,530,530,530
BEGIN DESCRIPTION:
UNT 115 IN BOCR 11.0
END DESCRIPTION:
XS GIS Cut Line= 3
       3729649.6     10615060.17      3729749.61     10615360.19
      3729749.61     10615960.14
#Sta/Elev= 30
  4625.7  322.41  4667.9  319.04  4678.4  316.18  4699.5  313.76  4720.6  308.89
  4731.1  308.54  4741.7   305.3  4812.9  297.95  4868.2  293.04  4899.8  291.93
  4931.4  289.15  4961.9  288.92  4981.9  285.09  4988.9  281.74  4991.7  281.24
  4994.9  281.74  5001.9  282.29  5021.9  287.93  5031.9  287.02  5051.9  290.99
  5181.9  295.19  5191.9  295.23  5213.4  291.86  5231.9  289.37  5241.9  296.08
  5251.9  297.01  5291.9  297.95  5391.9  304.41  5491.9  312.87  5541.9  315.51
#Mann= 5 ,-1 , 0
  4625.7     .12       0  4812.9     .16       0  4988.9     .07       0
  4994.9     .16       0  5213.4     .12       0
Bank Sta=4988.9,4994.9
XS Rating Curve= 0 ,0
Exp/Cntr=0.3,0.1

Type RM Length L Ch R = 1 ,4894    ,515,515,515
BEGIN DESCRIPTION:
UNT 115 IN BOCR 10.0
END DESCRIPTION:
XS GIS Cut Line= 3
      3729249.62     10615510.19      3729449.61     10615660.19
      3729699.58     10615910.16
#Sta/Elev= 30
  4778.2  301.45  4785.5  300.63  4791.7  301.12  4800.1  300.63  4806.3  301.23
  4813.7  299.79  4820.9  299.47  4850.1  294.69  4870.9  293.47  4878.2  292.14
  4914.6  288.01  4935.5  286.37  4957.6   286.4  4970.9  285.64  4978.2  281.94
  4988.7  278.32  4991.5  277.82  4994.7  278.32  5000.1  278.46  5025.1  283.37
  5042.3   283.6  5070.6  287.29  5141.3  292.14    5212  295.98  5268.6  300.26
  5282.7  300.52  5296.9  302.43    5311  303.11  5339.3   307.2  5381.7  311.29
#Mann= 5 ,-1 , 0
  4778.2     .05       0  4813.7     .16       0  4957.6     .12       0
  4988.7     .07       0  4994.7     .12       0
Bank Sta=4988.7,4994.7
XS Rating Curve= 0 ,0
Exp/Cntr=0.3,0.1

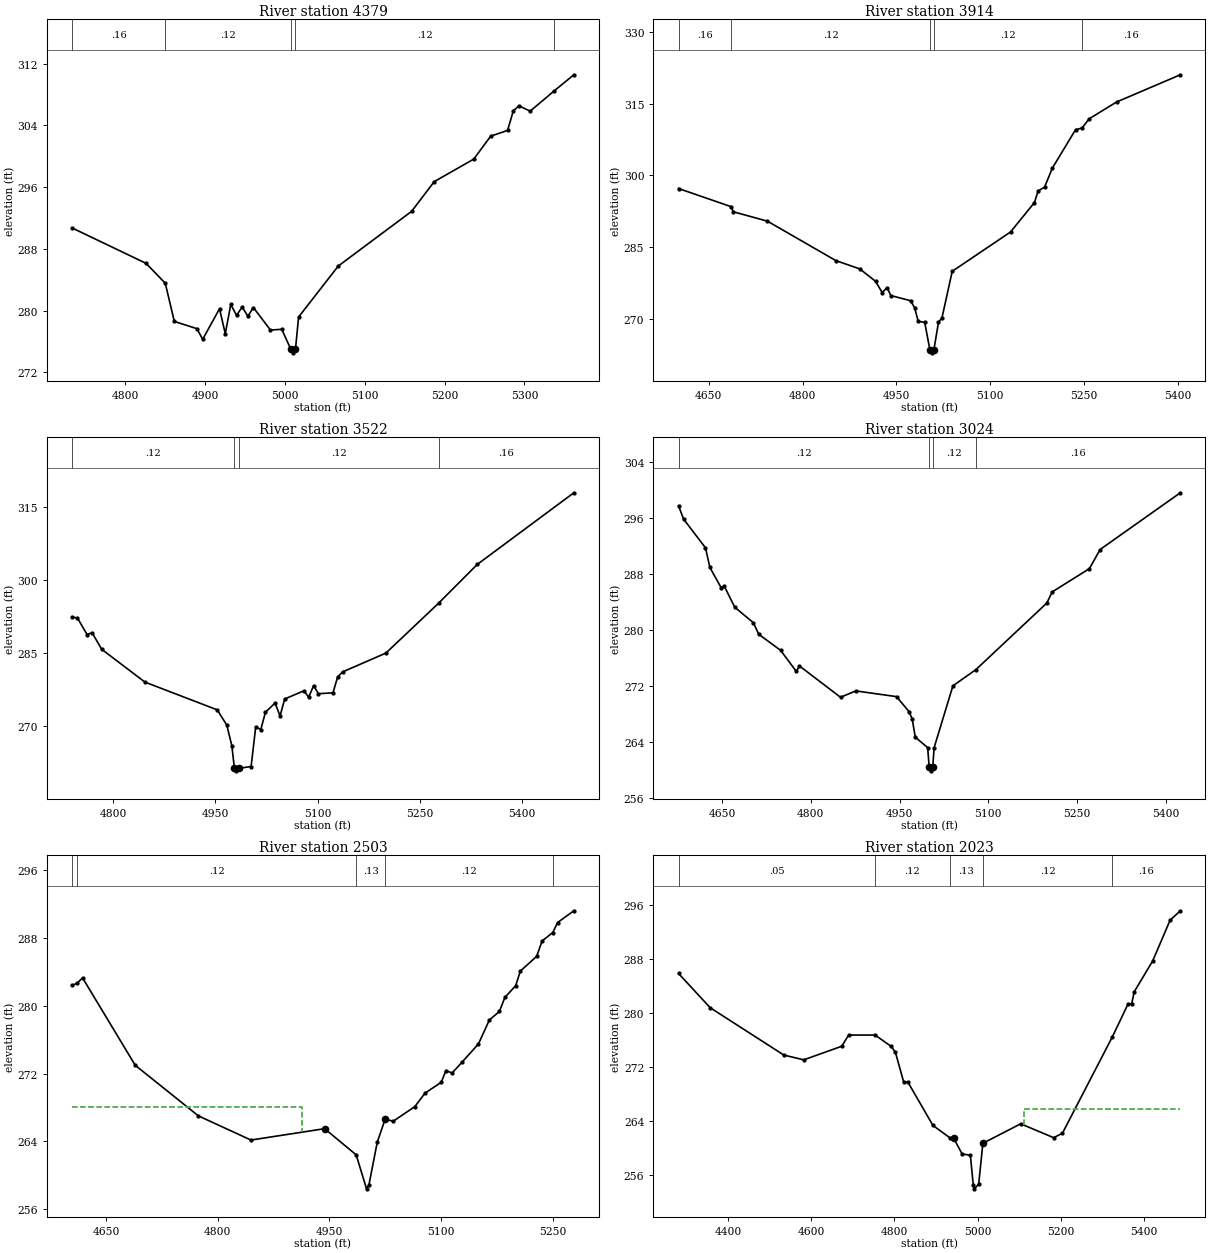
Type RM Length L Ch R = 1 ,4379    ,465,465,465
BEGIN DESCRIPTION:
Mapping XS 2af08f8c
END DESCRIPTION:
XS GIS Cut Line= 2
       3728909.4     10615689.29      3729345.75     10616141.22
#Sta/Elev= 30
  4733.7   290.7  4826.4  286.11  4850.4  283.53  4861.7  278.59    4890  277.65
  4897.2  276.27  4918.3  280.23  4925.5     277  4932.4  280.79  4939.6  279.37
  4946.6  280.45  4953.8  279.26  4960.7  280.39  4982.1  277.47  4996.2  277.57
  5007.4  275.02  5010.1  274.52  5013.4  275.02  5017.3  279.16    5067  285.77
  5158.8  292.85  5187.1   296.7  5236.5  299.61  5257.8  302.59  5278.9  303.33
  5286.1  305.86  5293.1  306.52  5307.2  305.83    5337  308.43  5361.9  310.54
#Mann= 5 ,-1 , 0
  4733.7     .16       0  4850.4     .12       0  5007.4     .07       0
  5013.4     .12       0    5337     .16       0
Bank Sta=5007.4,5013.4
XS Rating Curve= 0 ,0
Exp/Cntr=0.3,0.1

Type RM Length L Ch R = 1 ,3914    ,392,392,392
BEGIN DESCRIPTION:
Mapping XS dce965e4
END DESCRIPTION:
XS GIS Cut Line= 2
      3728492.67     10615986.12      3729199.93     10616365.75
#Sta/Elev= 30
  4601.6  297.22  4685.4  293.44  4689.4  292.35  4743.8  290.39  4853.4  282.13
  4891.6   280.4  4916.8   277.8  4927.3  275.46  4935.4  276.48  4941.1  274.83
  4972.7  273.75  4979.3  272.27  4984.9  269.45  4995.4   269.2  5003.9  263.34
  5006.6  262.84  5009.9  263.34  5017.4  269.19  5023.1   270.2  5039.4   279.9
  5132.7  288.13  5170.9  294.28  5176.9  296.73  5187.1   297.5  5199.6   301.5
  5236.7  309.53    5247  309.88  5258.6  311.82  5302.4  315.33  5404.3  321.02
#Mann= 5 ,-1 , 0
  4601.6     .16       0  4685.4     .12       0  5003.9     .07       0
  5009.9     .12       0    5247     .16       0
Bank Sta=5003.9,5009.9
XS Rating Curve= 0 ,0
Exp/Cntr=0.3,0.1

Type RM Length L Ch R = 1 ,3522    ,498,498,498
BEGIN DESCRIPTION:
Mapping XS 15fba1bc
END DESCRIPTION:
XS GIS Cut Line= 2
      3728445.85     10616272.61      3728984.66     10616775.16
#Sta/Elev= 30
  4739.6  292.47  4747.5  292.29  4761.6  288.89    4769  289.26  4783.1  285.85
  4846.7   279.1  4952.7  273.41  4966.8  270.27  4974.2  266.02    4978  261.37
  4980.7  260.87    4984  261.37  5002.5  261.76  5009.3  269.96  5016.7  269.33
  5023.5  272.91  5037.7  274.81    5045  272.15  5051.8  275.64  5080.2  277.33
    5087  275.98  5094.3   278.4  5101.2  276.73  5122.7   276.9  5129.5  280.15
  5136.8   281.2  5200.4  285.07  5278.1  295.37  5334.7  303.31  5476.4  318.02
#Mann= 4 ,-1 , 0
  4739.6     .12       0    4978     .07       0    4984     .12       0
  5278.1     .16       0
Bank Sta=4978,4984
XS Rating Curve= 0 ,0
Exp/Cntr=0.3,0.1

Type RM Length L Ch R = 1 ,3024    ,521,521,521
BEGIN DESCRIPTION:
Mapping XS a24ff0f9
END DESCRIPTION:
XS GIS Cut Line= 2
      3728201.04     10616329.87      3728466.33     10617136.15
#Sta/Elev= 30
  4576.2  297.68  4584.7  295.79  4621.8  291.69  4629.2  288.89  4648.3     286
  4653.5  286.24  4671.3  283.22  4702.9     281  4711.9  279.36  4748.9  277.07
  4775.4  274.07  4780.7  274.85  4850.2  270.38  4876.1  271.29    4945  270.47
    4966  268.34  4971.4   267.3  4976.7  264.69  4997.6   263.2  5000.2  260.39
    5003  259.89  5006.2  260.39  5008.5  263.18  5040.3  272.01  5079.3  274.33
  5199.2  283.82  5208.2   285.4  5271.3  288.73  5289.3  291.45    5425  299.54
#Mann= 4 ,-1 , 0
  4576.2     .12       0  5000.2     .07       0  5006.2     .12       0
  5079.3     .16       0
Bank Sta=5000.2,5006.2
XS Rating Curve= 0 ,0
Exp/Cntr=0.3,0.1

Type RM Length L Ch R = 1 ,2503    ,480,480,480
BEGIN DESCRIPTION:
UNT 115 IN BOCR 5.0
END DESCRIPTION:
XS GIS Cut Line= 3
      3727699.61     10616560.19      3727999.61     10616860.19
      3728149.63     10617060.21
#Sta/Elev= 30
  4604.3  282.38  4610.9  282.64  4618.4  283.27  4689.2  272.97    4774  267.01
  4844.7  264.16  4943.7   265.5  4986.1  262.41    5000  258.41  5003.3  258.91
  5014.4  263.91    5025  266.62  5035.9  266.38    5065  268.11  5078.6  269.69
  5100.4  270.97  5106.7  272.35    5115  272.06  5128.6  273.36  5150.4  275.49
    5165   278.3  5178.6  279.32  5185.9  280.97  5200.4  282.35  5206.7  284.07
  5228.6  285.81  5235.9  287.62  5250.3  288.62  5256.7  289.79  5278.6  291.18
#Mann= 5 ,-1 , 0
  4604.3     .16       0  4610.9     .12       0  4986.1     .13       0
    5025     .12       0  5250.3     .16       0
#XS Ineff= 2 , 0
         4912.61  268.02
Permanent Ineff=
       F       F
Bank Sta=4943.7,5025
XS Rating Curve= 0 ,0
Exp/Cntr=0.3,0.1

Type RM Length L Ch R = 1 ,2023    ,423,423,423
BEGIN DESCRIPTION:
UNT 115 IN BOCR 4.0
END DESCRIPTION:
XS GIS Cut Line= 4
      3726961.12     10616848.12      3727450.69      10616960.1
      3727711.11      10616965.3       3728073.1     10617220.52
#Sta/Elev= 30
  4281.6   285.9  4357.6  280.83  4534.5  273.82  4582.5  273.11  4673.6  275.12
  4690.4  276.78  4753.8  276.78  4792.7  275.09  4802.7  274.22  4822.7  269.78
  4832.7  269.81  4892.8   263.4  4932.8   261.6  4942.8  261.49  4962.8  259.18
  4982.8  258.98  4989.8  254.51  4992.5  254.01  5002.8  254.73  5012.8  260.75
  5103.6  263.64    5183  261.58    5204  262.25  5324.2  276.55  5361.6  281.38
  5370.3   281.4  5376.4  283.18  5420.8  287.76  5462.6  293.78  5487.2  295.18
#Mann= 5 ,-1 , 0
  4281.6     .05       0  4753.8     .12       0  4932.8     .13       0
  5012.8     .12       0  5324.2     .16       0
#XS Ineff= 2 , 0
                         5112.39          265.89
Permanent Ineff=
       F       F
Bank Sta=4942.8,5012.8
XS Rating Curve= 0 ,0
Exp/Cntr=0.3,0.1

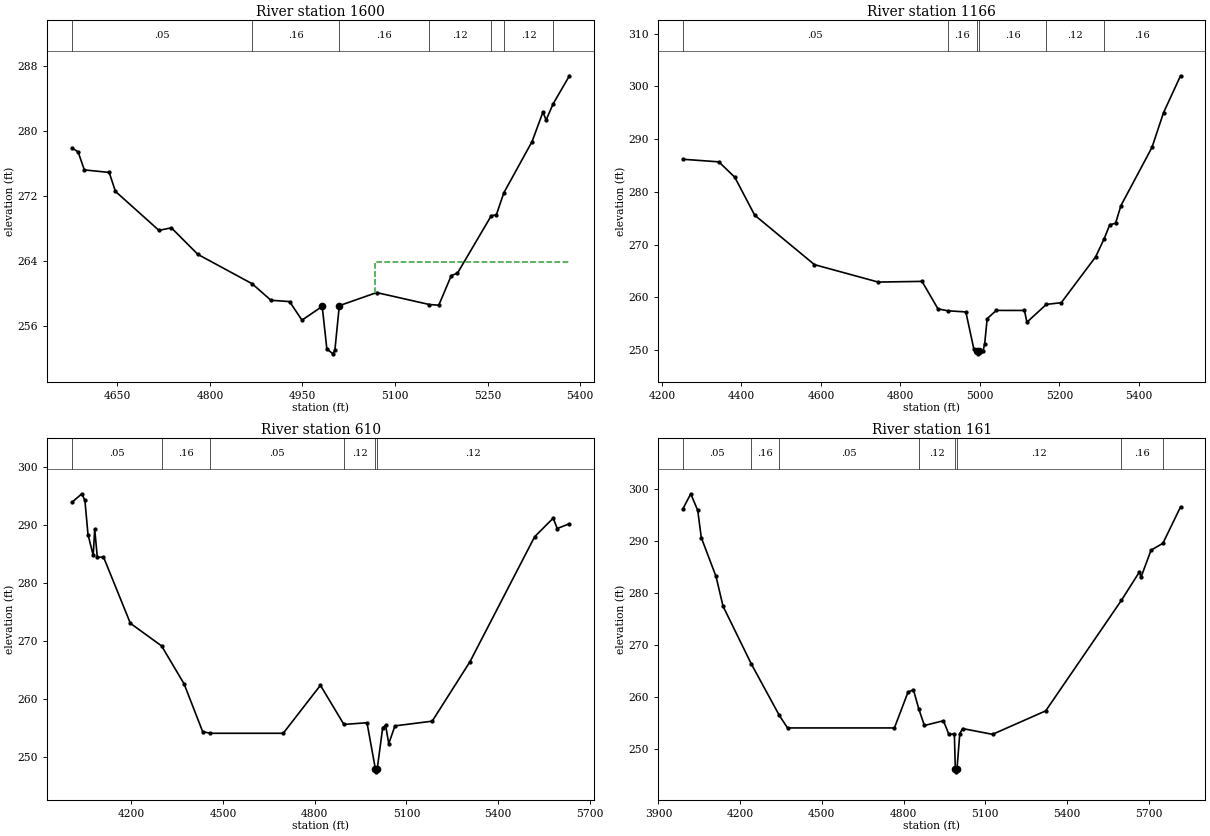
Type RM Length L Ch R = 1 ,1600    ,434,434,434
BEGIN DESCRIPTION:
UNT 115 IN BOCR 3.0
END DESCRIPTION:
XS GIS Cut Line= 3
      3727149.57     10617310.18      3727549.61     10617360.19
      3727949.65     10617310.18
#Sta/Elev= 30
  4576.3  277.91  4586.4  277.42  4596.5   275.2  4636.8  274.89  4646.9  272.56
  4717.4  267.77  4737.6  268.08  4780.4  264.82  4868.6   261.2  4898.8  259.18
  4929.1  259.01  4949.2  256.73    4982  258.42  4989.5  253.19  4999.4  252.59
  5002.6  253.09  5009.7  258.51  5070.2  260.12  5155.8  258.65  5170.9  258.57
  5191.1   262.2  5201.2  262.51    5256  269.57  5264.2  269.68  5276.3  272.38
  5322.1  278.69  5339.7  282.31  5344.8  281.33  5356.2  283.32  5382.6  286.77
#Mann= 7 ,-1 , 0
  4576.3     .05       0  4868.6     .16       0  5009.7     .16       0
  5155.8     .12       0    5256     .16       0  5276.3     .12       0
  5356.2     .16       0
#XS Ineff= 2 , 0
                         5067.61          263.87
Permanent Ineff=
       F       F
Bank Sta=4982,5009.7
XS Rating Curve= 0 ,0
Exp/Cntr=0.3,0.1

Type RM Length L Ch R = 1 ,1166    ,556,556,556
BEGIN DESCRIPTION:
UNT 115 IN BOCR 2.0
END DESCRIPTION:
XS GIS Cut Line= 3
      3726999.56     10617760.19      3727749.61     10617710.19
       3728149.6      10617410.2
#Sta/Elev= 30
  4252.8  286.18    4343  285.69  4383.1  282.78  4433.2  275.59  4583.6  266.21
  4743.9  262.91  4854.2  263.04  4894.3  257.83  4918.9  257.47  4964.4  257.25
  4984.5  250.24  4991.5  249.81  4994.2  249.31  4997.5  249.81  5007.6  249.85
  5011.8  251.22  5018.1  255.98    5041  257.54  5111.8  257.53  5118.1   255.3
  5166.8  258.68  5204.5     259    5291   267.7  5312.6  271.16  5326.4  273.78
    5341  274.04  5354.5  277.39  5432.6  288.42  5461.8  295.03  5504.5     302
#Mann= 6 ,-1 , 0
  4252.8     .05       0  4918.9     .16       0  4991.5     .07       0
  4997.5     .16       0  5166.8     .12       0  5312.6     .16       0
Bank Sta=4991.5,4997.5
XS Rating Curve= 0 ,0
Exp/Cntr=0.3,0.1

Type RM Length L Ch R = 1 ,610     ,449,449,449
BEGIN DESCRIPTION:
Mapping XS 55a68c79
END DESCRIPTION:
XS GIS Cut Line= 3
      3726987.48     10618043.44      3727768.76     10618173.65
      3728591.68     10618027.81
#Sta/Elev= 30
  4005.4  293.94    4038  295.43  4048.1  294.29  4058.2  288.39  4075.2  284.81
  4080.2  289.29  4088.7  284.43  4108.9  284.52  4196.8  273.06  4298.9  269.15
  4372.5   262.6  4433.4  254.33  4458.8  254.06  4696.9  254.06  4818.6  262.35
  4895.4  255.59    4971  255.88  4998.4   247.9  5001.2   247.4  5004.4   247.9
  5022.3  255.04  5031.9  255.44  5042.1  252.26  5062.4  255.34  5184.2  256.15
  5307.8  266.42  5519.4  288.01  5580.3  291.23  5593.2  289.43  5633.2  290.25
#Mann= 6 ,-1 , 0
  4005.4     .05       0  4298.9     .16       0  4458.8     .05       0
  4895.4     .12       0  4998.4     .07       0  5004.4     .12       0
Bank Sta=4998.4,5004.4
XS Rating Curve= 0 ,0
Exp/Cntr=0.3,0.1

Type RM Length L Ch R = 1 ,161     ,0,0,0
BEGIN DESCRIPTION:
UNT 115 IN BOCR 1.0
END DESCRIPTION:
XS GIS Cut Line= 4
      3726956.26     10618236.15      3727664.59     10618486.15
      3728102.09     10618501.77      3728648.97      10618829.9
#Sta/Elev= 30
  3990.1   296.2  4018.7  299.07  4044.3  295.87  4057.3  290.65  4111.5  283.17
  4137.1  277.47  4240.3  266.43  4343.8  256.47    4374  254.06  4766.3  254.06
  4816.3  260.94  4836.3  261.38  4855.9   257.7  4876.4  254.53  4946.4  255.44
  4966.4   252.8  4986.4  252.94    4990  246.12  4992.7  245.62    4996  246.12
  5006.4  252.97  5016.4  253.94  5126.5  252.83  5321.8  257.34  5599.7  278.59
  5665.8  284.04  5671.7  283.04  5708.6  288.23    5752  289.55  5816.8  296.54
#Mann= 8 ,-1 , 0
  3990.1     .05       0  4240.3     .16       0  4343.8     .05       0
  4855.9     .12       0    4990     .07       0    4996     .12       0
  5599.7     .16       0    5752     .12       0
Bank Sta=4990,4996
XS Rating Curve= 0 ,0
Exp/Cntr=0.3,0.1

Chan Stop Cuts=-1
Use User Specified Reach Order=0
Composite Channel Slope=5