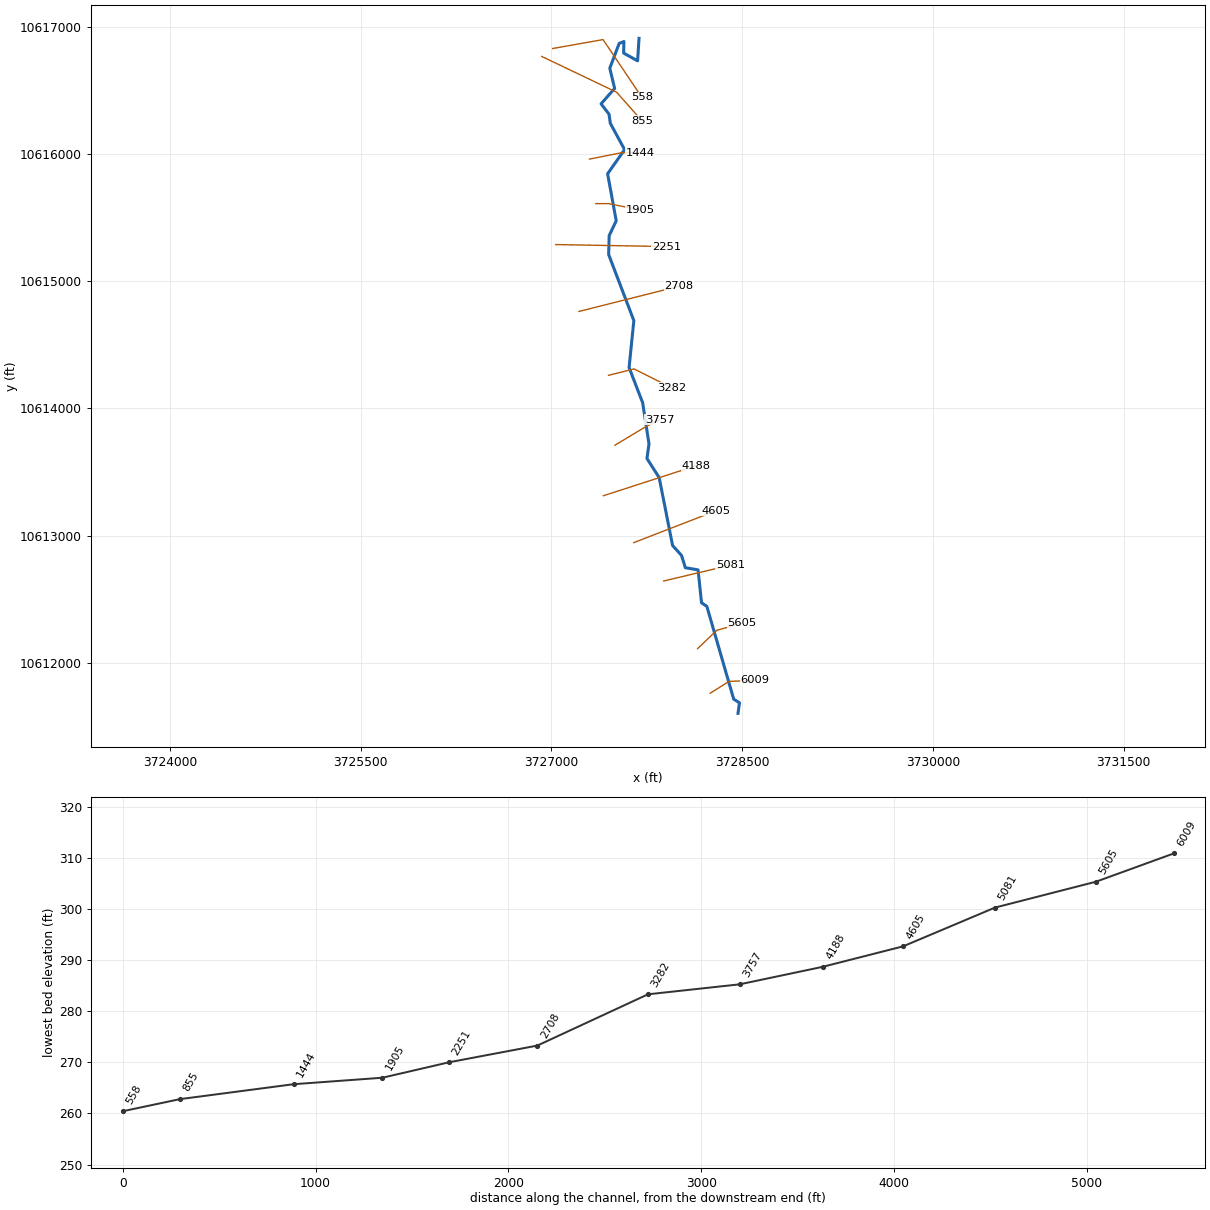
--- UNT 116 IN BOCR.prj (project) ---

Proj Title=UNT 116 IN BOCR Base Level Engineering
Current Plan=p01
Default Exp/Contr=0.3,0.1
English Units
Geom File=g01
Flow File=f01
Plan File=p01
Y Axis Title=Elevation
X Axis Title(PF)=Main Channel Distance
X Axis Title(XS)=Station
BEGIN DESCRIPTION:
UNT 116 IN BOCR
END DESCRIPTION:
DSS Export Rating Curves= 0
DSS Export Rating Curve Sorted= 0
DSS Export Volume Flow Curves= 0
DXF OffsetX= 0
DXF OffsetY= 0
DXF ScaleX= 1
DXF ScaleY= 10

--- UNT 116 IN BOCR.p01 (plan) ---

Plan Title=Multiple Run
Short Identifier=Multiple
Geom File=g01
Flow File=f01
Subcritical Flow
K Sum by GR= 0
Std Step Tol= 0.01
Critical Tol= 0.01
Num of Std Step Trials= 20
Max Error Tol= 0.3
Flow Tol Ratio= 0.001
Split Flow NTrial= 30
Split Flow Tol= 0.02
Split Flow Ratio= 0.02
Log Output Level= 0
Friction Slope Method= 1
Unsteady Friction Slope Method= 2
Unsteady Bridges Friction Slope Method= 1
Parabolic Critical Depth
Global Vel Dist=  1 , 1 , 1
Global Log Level= 0
CheckData=True
Encroach Param= -1, 0, 0, 0
BEGIN DESCRIPTION:
Multiple Run
END DESCRIPTION:

--- UNT 116 IN BOCR.f01 (steady flow) ---

Flow Title=Multiple
Number of Profiles=7
Profile Names=10-year,25-year,50-year,1pct_min,100-year,1pct_plu,500-year
River Rch & RM= UNT 116 IN BOCR,Reach-1,6009
     321     416     491     427     578     782     801
Boundary for River Rch & Prof#=UNT 116 IN BOCR,Reach-1,1
Up Type=0
Dn Type=3
Dn Slope=0.005
Boundary for River Rch & Prof#=UNT 116 IN BOCR,Reach-1,2
Up Type=0
Dn Type=3
Dn Slope=0.005
Boundary for River Rch & Prof#=UNT 116 IN BOCR,Reach-1,3
Up Type=0
Dn Type=3
Dn Slope=0.005
Boundary for River Rch & Prof#=UNT 116 IN BOCR,Reach-1,4
Up Type=0
Dn Type=3
Dn Slope=0.005
Boundary for River Rch & Prof#=UNT 116 IN BOCR,Reach-1,5
Up Type=0
Dn Type=3
Dn Slope=0.005
Boundary for River Rch & Prof#=UNT 116 IN BOCR,Reach-1,6
Up Type=0
Dn Type=3
Dn Slope=0.005
Boundary for River Rch & Prof#=UNT 116 IN BOCR,Reach-1,7
Up Type=0
Dn Type=3
Dn Slope=0.005

--- UNT 116 IN BOCR.g01 (geometry) ---

Geom Title=Existing Conditions
Program Version=4.10

River Reach=UNT 116 IN BOCR ,Reach-1
Reach XY= 30
      3728467.85     10611601.46      3728479.32     10611684.97
      3728434.25      10611712.5      3728222.75       10612443.
        3728181.       10612471.      3728153.75       10612730.
       3728053.5       10612747.        3728024.       10612843.
      3727953.25       10612922.        3727848.       10613455.
      3727751.75       10613606.        3727768.       10613720.
      3727717.75       10614045.      3727611.25       10614321.
      3727648.75       10614690.       3727450.5       10615210.
      3727454.75       10615359.        3727510.       10615475.
       3727442.5       10615845.        3727576.       10616035.
       3727463.5       10616242.      3727453.75       10616313.
        3727391.       10616395.      3727497.75       10616516.
      3727459.51      10616674.8      3727533.25       10616870.
      3727570.75       10616885.      3727568.25       10616794.
      3727678.25       10616733.       3727689.5       10616910.

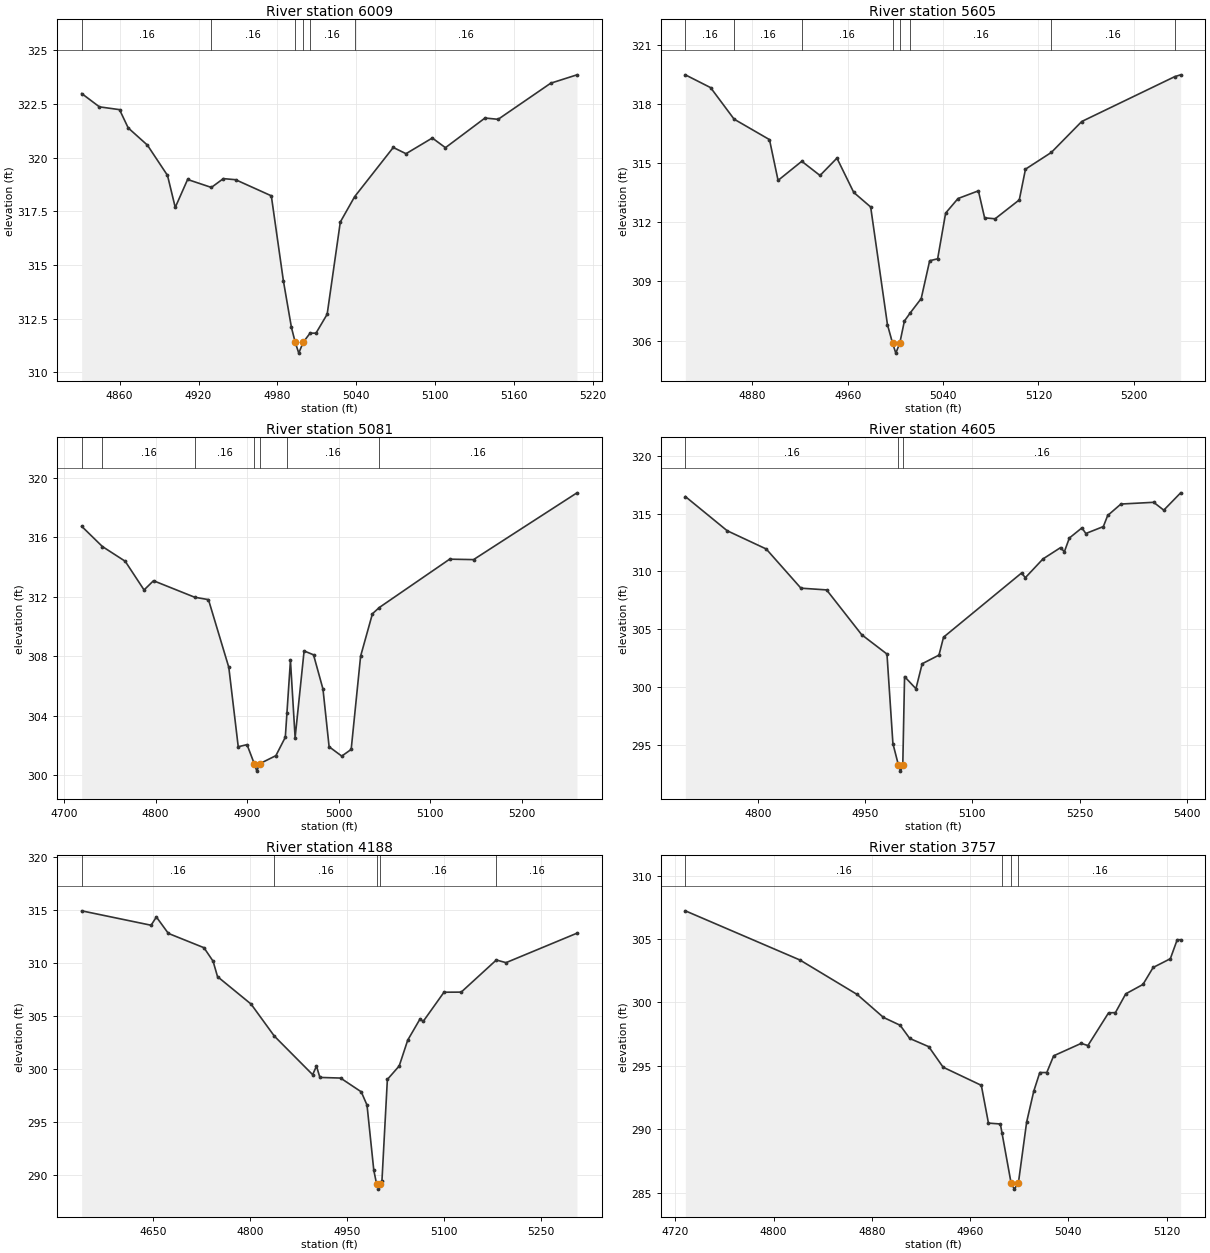
Type RM Length L Ch R = 1 ,6009    ,404,404,404
BEGIN DESCRIPTION:
UNT 116 IN BOCR 13.0
END DESCRIPTION:
XS GIS Cut Line= 3
      3728249.63      10611760.2      3728397.55     10611853.19
       3728599.6     10611860.19
#Sta/Elev= 30
  4831.1  322.98  4844.6  322.36  4859.9  322.23  4866.5  321.38  4881.1  320.58
  4896.4  319.17  4902.3  317.68  4911.7  318.98  4929.8  318.61  4938.9  319.02
  4948.2  318.97  4975.4  318.22  4984.6  314.26  4990.7   312.1  4993.6   311.4
  4996.3   310.9  4999.6   311.4  5004.9  311.83  5009.4  311.83  5017.9  312.71
  5027.9     317  5038.8  318.18  5068.2  320.47  5077.9  320.18  5097.9  320.91
  5107.9  320.46    5138  321.84    5148  321.78    5188  323.46    5208  323.85
#Mann= 6 ,-1 , 0
  4831.1     .16       0  4929.8     .16       0  4993.6     .16       0
  4999.6     .16       0  5004.9     .16       0  5038.8     .16       0
Bank Sta=4993.6,4999.6
XS Rating Curve= 0 ,0
Exp/Cntr=0.3,0.1

Type RM Length L Ch R = 1 ,5605    ,524,524,524
BEGIN DESCRIPTION:
UNT 116 IN BOCR 12.0
END DESCRIPTION:
XS GIS Cut Line= 3
      3728149.64     10612110.21      3728301.01     10612254.99
      3728499.62     10612310.19
#Sta/Elev= 30
  4823.7  319.49  4844.9  318.84  4864.6  317.24  4894.3   316.2  4901.5  314.13
  4921.4   315.1  4936.7  314.38  4950.9  315.26    4965  313.52  4979.2  312.78
  4993.3   306.8  4997.6  305.86  5000.3  305.36  5003.6  305.86  5007.5  306.99
  5012.5  307.41  5021.6  308.13  5028.7  310.05  5035.4  310.15  5042.1  312.47
  5052.5  313.21  5069.6   313.6  5074.8  312.23  5083.6  312.18  5103.9  313.14
  5109.1   314.7  5130.8  315.55  5156.3  317.12  5234.4   319.4  5239.3  319.49
#Mann= 8 ,-1 , 0
  4823.7     .16       0  4864.6     .16       0  4921.4     .16       0
  4997.6     .16       0  5003.6     .16       0  5012.5     .16       0
  5130.8     .16       0  5234.4     .16       0
Bank Sta=4997.6,5003.6
XS Rating Curve= 0 ,0
Exp/Cntr=0.3,0.1

Type RM Length L Ch R = 1 ,5081    ,476,476,476
BEGIN DESCRIPTION:
Mapping XS 69bc2e37
END DESCRIPTION:
XS GIS Cut Line= 2
      3727883.36      10612642.4      3728409.41      10612767.4
#Sta/Elev= 30
  4719.4  316.75    4742  315.39  4766.9   314.4  4787.5  312.47  4797.8  313.09
  4842.8  311.98  4857.8  311.82    4880  307.27  4890.3  301.93  4899.9  302.07
  4907.8  300.79  4910.6  300.29  4913.8  300.79  4931.4  301.33  4941.7  302.57
  4943.5  304.23  4947.3  307.73  4952.4  302.54  4962.2  308.37  4972.5  308.11
  4982.8  305.81  4989.5  301.93  5003.3   301.3  5013.6  301.75  5023.9  308.02
  5036.8  310.87  5044.3  311.29  5121.1  314.54  5147.2  314.51  5260.1     319
#Mann= 7 ,-1 , 0
  4719.4     .16       0    4742     .16       0  4842.8     .16       0
  4907.8     .16       0  4913.8     .16       0  4943.5     .16       0
  5044.3     .16       0
Bank Sta=4907.8,4913.8
XS Rating Curve= 0 ,0
Exp/Cntr=0.3,0.1

Type RM Length L Ch R = 1 ,4605    ,417,417,417
BEGIN DESCRIPTION:
Mapping XS 55aa14e7
END DESCRIPTION:
XS GIS Cut Line= 2
      3727648.93     10612944.47      3728294.74     10613194.46
#Sta/Elev= 30
  4698.8  316.47  4757.3  313.51  4811.9  311.93  4860.4  308.54  4896.3  308.39
  4945.4  304.51  4980.7  302.84    4989   295.1  4996.8  293.21  4999.5  292.71
  5002.8  293.21  5005.3  300.89  5021.2  299.84  5029.9     302  5053.4  302.75
  5059.8   304.3  5168.8  309.85  5174.2  309.45  5198.8  311.07  5223.4  312.05
  5228.7  311.69  5235.7  312.88  5253.3  313.76  5258.7  313.27  5283.2  313.87
  5289.3  314.83  5307.8  315.82  5353.6  315.97  5367.7  315.29  5391.3  316.79
#Mann= 3 ,-1 , 0
  4698.8     .16       0  4996.8     .16       0  5002.8     .16       0
Bank Sta=4996.8,5002.8
XS Rating Curve= 0 ,0
Exp/Cntr=0.3,0.1

Type RM Length L Ch R = 1 ,4188    ,431,431,431
BEGIN DESCRIPTION:
UNT 116 IN BOCR 9.0
END DESCRIPTION:
XS GIS Cut Line= 2
      3727409.61     10613313.05      3728138.74     10613549.14
#Sta/Elev= 30
  4539.2  314.96  4646.6   313.6  4654.8  314.38  4673.3  312.83  4728.4  311.48
  4742.5  310.21  4749.4  308.75  4801.3  306.16  4837.3  303.14  4896.6   299.5
  4902.5  300.31  4907.8  299.24  4939.8  299.18  4971.8  297.88  4980.7  296.63
  4991.2  290.48  4995.5   289.2  4998.3   288.7  5001.5   289.2  5003.8  289.47
  5012.2  299.05  5030.5  300.32  5043.7  302.76  5062.5  304.73  5067.8  304.54
  5099.8  307.28  5126.5  307.29  5180.8  310.32  5195.8  310.07  5305.6  312.85
#Mann= 5 ,-1 , 0
  4539.2     .16       0  4837.3     .16       0  4995.5     .16       0
  5001.5     .16       0  5180.8     .16       0
Bank Sta=4995.5,5001.5
XS Rating Curve= 0 ,0
Exp/Cntr=0.3,0.1

Type RM Length L Ch R = 1 ,3757    ,475,475,475
BEGIN DESCRIPTION:
UNT 116 IN BOCR 8.0
END DESCRIPTION:
XS GIS Cut Line= 3
      3727499.65     10613710.21      3727749.61     10613860.19
       3727849.6     10613910.18
#Sta/Elev= 30
  4728.2  307.23  4821.5  303.35  4868.1  300.63  4889.5  298.82  4903.1   298.2
  4910.9  297.16  4926.4  296.51  4938.1  294.89  4969.2  293.46    4975  290.48
  4984.7  290.41    4986  289.72  4993.4  285.77  4996.1  285.27  4999.4  285.77
  5006.1  290.56  5011.9     293  5016.8  294.47  5022.5  294.47  5028.1  295.79
  5050.5  296.77    5056   296.6  5072.8  299.18  5078.4   299.2  5086.8  300.68
  5100.8  301.42  5109.1  302.76  5123.1  303.45  5128.7  304.95  5131.5  304.95
#Mann= 4 ,-1 , 0
  4728.2     .16       0    4986     .16       0  4993.4     .16       0
  4999.4     .16       0
Bank Sta=4993.4,4999.4
XS Rating Curve= 0 ,0
Exp/Cntr=0.3,0.1

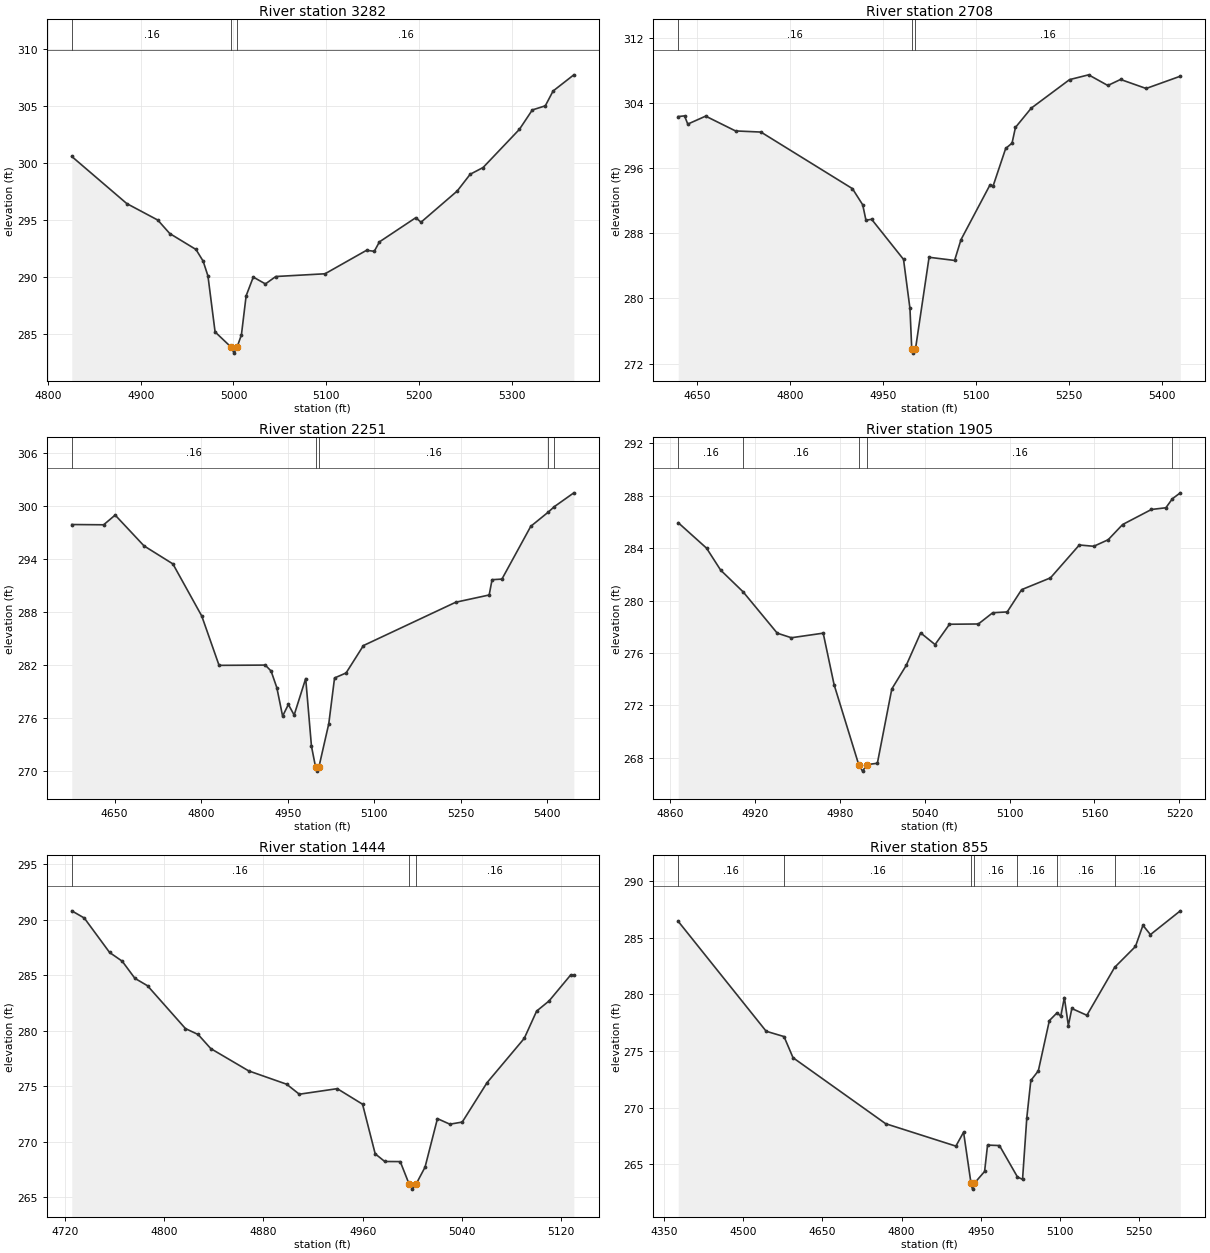
Type RM Length L Ch R = 1 ,3282    ,574,574,574
BEGIN DESCRIPTION:
UNT 116 IN BOCR 7.0
END DESCRIPTION:
XS GIS Cut Line= 3
      3727449.61     10614260.19      3727649.61     10614310.19
      3727949.64     10614160.17
#Sta/Elev= 30
  4825.6  300.57  4884.9  296.44  4918.4  294.99  4931.3  293.81  4959.6  292.41
  4967.3  291.39  4972.5  290.09  4980.2  285.18  4997.8  283.82  5000.6  283.32
  5003.8  283.82  5008.6  284.92  5013.7  288.35  5021.4  289.99  5034.5  289.39
  5045.7  290.04  5098.8  290.28  5143.6  292.34  5151.9  292.25  5157.5  293.08
  5196.7   295.2  5202.3   294.8  5241.4  297.54  5255.4  299.01  5269.3   299.6
  5308.5  302.95  5322.4  304.65  5336.4  305.01  5344.8  306.31  5367.2  307.73
#Mann= 3 ,-1 , 0
  4825.6     .16       0  4997.8     .16       0  5003.8     .16       0
Bank Sta=4997.8,5003.8
XS Rating Curve= 0 ,0
Exp/Cntr=0.3,0.1

Type RM Length L Ch R = 1 ,2708    ,457,457,457
BEGIN DESCRIPTION:
Mapping XS 9e0d4657
END DESCRIPTION:
XS GIS Cut Line= 2
      3727216.67     10614762.19      3728003.15     10614960.11
#Sta/Elev= 30
  4618.9  302.38  4629.1  302.46  4634.3  301.45  4663.2  302.43  4711.4  300.61
  4752.5  300.47  4900.3  293.51  4916.9  291.52  4922.1  289.63  4931.3  289.74
  4982.8  284.81  4993.2  278.77  4996.1  273.78  4998.9  273.28  5002.1  273.78
  5024.1  285.07  5065.3  284.68  5075.6  287.23  5122.5  293.97  5127.6  293.86
  5147.8  298.45  5158.1  299.11  5163.6  301.04  5189.1  303.41    5251  306.92
  5281.8  307.51  5312.8   306.2  5333.4  306.94  5374.7  305.83  5429.9  307.34
#Mann= 3 ,-1 , 0
  4618.9     .16       0  4996.1     .16       0  5002.1     .16       0
Bank Sta=4996.1,5002.1
XS Rating Curve= 0 ,0
Exp/Cntr=0.3,0.1

Type RM Length L Ch R = 1 ,2251    ,346,346,346
BEGIN DESCRIPTION:
Mapping XS ff9d5d80
END DESCRIPTION:
XS GIS Cut Line= 2
      3727034.41     10615288.23      3727904.17     10615272.61
#Sta/Elev= 30
  4575.9  297.95  4631.1  297.92  4651.1  299.02  4701.1  295.53  4751.1  293.49
  4801.1  287.59  4831.1     282  4911.2  282.03  4921.2  281.36  4931.2  279.47
  4941.2  276.25  4951.2  277.57  4961.2  276.37  4981.2  280.51  4991.2  272.84
  4998.2  270.52  5000.9  270.02  5004.2  270.52  5021.2  275.39  5031.2  280.57
  5051.2  281.14  5081.2  284.24  5241.2  289.15  5299.1  289.97  5304.1   291.7
  5321.2  291.77  5371.2  297.75  5401.2  299.34  5411.9  299.97  5445.8  301.54
#Mann= 5 ,-1 , 0
  4575.9     .16       0  4998.2     .16       0  5004.2     .16       0
  5401.2     .16       0  5411.9     .16       0
Bank Sta=4998.2,5004.2
XS Rating Curve= 0 ,0
Exp/Cntr=0.3,0.1

Type RM Length L Ch R = 1 ,1905    ,461,461,461
BEGIN DESCRIPTION:
UNT 116 IN BOCR 4.0
END DESCRIPTION:
XS GIS Cut Line= 3
      3727349.61     10615610.19      3727449.61     10615610.19
      3727699.66     10615560.18
#Sta/Elev= 30
  4865.7  285.95  4885.7  284.01  4895.7  282.33  4911.6  280.67  4935.7  277.52
  4945.7  277.17  4968.2  277.52  4975.9  273.59  4993.3  267.49    4996  266.99
  4999.3  267.49  5006.5  267.59  5016.7  273.26  5026.9  275.06  5037.1  277.54
  5047.3  276.65  5057.5   278.2  5077.9  278.22  5088.1  279.08  5098.3  279.14
  5108.5  280.84  5128.9  281.74  5149.3  284.25  5159.5  284.15  5169.7  284.65
  5179.9  285.81  5200.3  286.96  5210.5  287.09  5215.1  287.78  5220.7  288.23
#Mann= 5 ,-1 , 0
  4865.7     .16       0  4911.6     .16       0  4993.3     .16       0
  4999.3     .16       0  5215.1     .16       0
Bank Sta=4993.3,4999.3
XS Rating Curve= 0 ,0
Exp/Cntr=0.3,0.1

Type RM Length L Ch R = 1 ,1444    ,589,589,589
BEGIN DESCRIPTION:
UNT 116 IN BOCR 3.0
END DESCRIPTION:
XS GIS Cut Line= 3
      3727299.66      10615960.2      3727549.61     10616010.19
      3727699.61     10616010.19
#Sta/Elev= 30
  4725.4  290.79  4735.5  290.14  4755.9  287.04  4766.1  286.25  4776.3  284.71
  4786.5  284.04  4817.1  280.18  4827.3  279.65  4837.5  278.38  4868.1  276.37
  4898.7  275.17  4908.9  274.27  4939.5  274.77  4959.9  273.37  4970.1   268.9
  4977.8  268.21  4990.3   268.2  4997.3  266.22  5000.1  265.72  5003.3  266.22
  5010.3   267.7  5020.3  272.07  5030.3  271.57  5040.3  271.76  5060.3  275.31
  5090.3   279.3  5100.3  281.76  5110.3  282.67  5127.8  285.02  5130.3  285.02
#Mann= 3 ,-1 , 0
  4725.4     .16       0  4997.3     .16       0  5003.3     .16       0
Bank Sta=4997.3,5003.3
XS Rating Curve= 0 ,0
Exp/Cntr=0.3,0.1

Type RM Length L Ch R = 1 ,855     ,297,297,297
BEGIN DESCRIPTION:
UNT 116 IN BOCR 2.0
END DESCRIPTION:
XS GIS Cut Line= 3
      3726925.01      10616767.4      3727513.55     10616486.15
      3727711.49     10616262.17
#Sta/Elev= 30
    4377  286.46  4543.6  276.75  4577.4  276.28  4594.5  274.41    4770  268.58
    4903   266.6  4917.6  267.83  4931.7   263.3  4934.5   262.8  4937.7   263.3
  4957.4  264.36    4963  266.69  4985.6  266.65  5019.6  263.88  5029.3  263.66
  5037.4  269.12    5045   272.4  5059.2  273.25  5080.1  277.69  5094.5  278.37
  5101.8  278.09  5108.5  279.73  5116.1  277.25  5122.7  278.76  5151.2  278.16
  5203.7  282.39  5243.2  284.24  5257.4  286.11  5271.6  285.29  5328.2  287.39
#Mann= 7 ,-1 , 0
    4377     .16       0  4577.4     .16       0  4931.7     .16       0
  4937.7     .16       0  5019.6     .16       0  5094.5     .16       0
  5203.7     .16       0
Bank Sta=4931.7,4937.7
XS Rating Curve= 0 ,0
Exp/Cntr=0.3,0.1

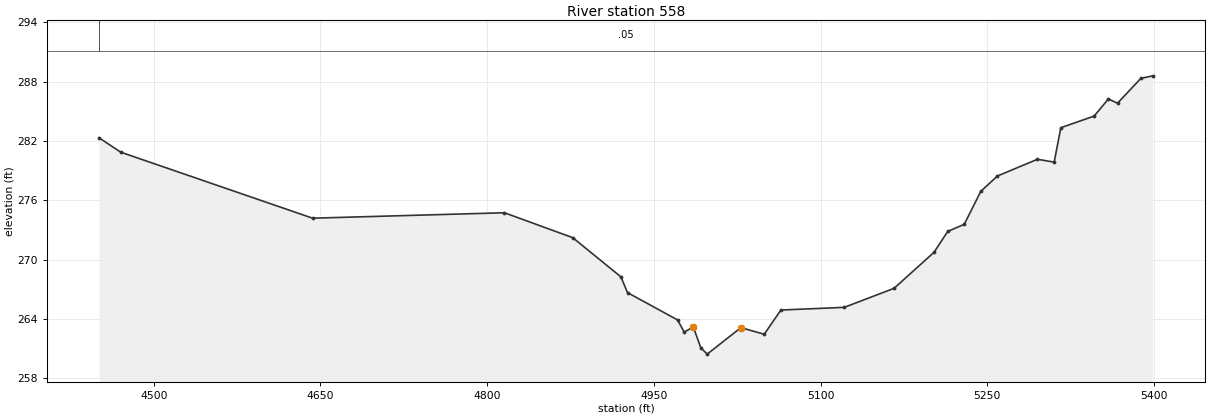
Type RM Length L Ch R = 1 ,558     ,0,0,0
BEGIN DESCRIPTION:
UNT 116 IN BOCR 1.0
END DESCRIPTION:
XS GIS Cut Line= 3
      3727010.61     10616829.89      3727406.42      10616900.2
      3727711.08     10616447.11
#Sta/Elev= 30
  4450.9   282.3  4470.2  280.86  4642.9  274.18  4815.5  274.73    4877  272.21
  4920.3  268.25  4926.3  266.65  4971.3  263.89  4977.3  262.66  4985.5  263.17
  4992.3  261.06    4998  260.43  5028.3  263.11  5049.3  262.44  5064.3  264.89
  5121.3  265.16  5166.2  267.09  5202.2  270.74  5214.4  272.84  5229.3  273.56
  5244.2   276.9  5259.2  278.45  5295.2  280.14  5310.2  279.85  5316.2  283.33
  5346.2  284.51    5359  286.24  5367.2  285.81  5388.2  288.32  5398.9  288.58
#Mann= 1 ,-1 , 0
  4450.9     .05       0
Bank Sta=4985.5,5028.3
XS Rating Curve= 0 ,0
Exp/Cntr=0.3,0.1

Chan Stop Cuts=-1
Use User Specified Reach Order=0
Composite Channel Slope=5