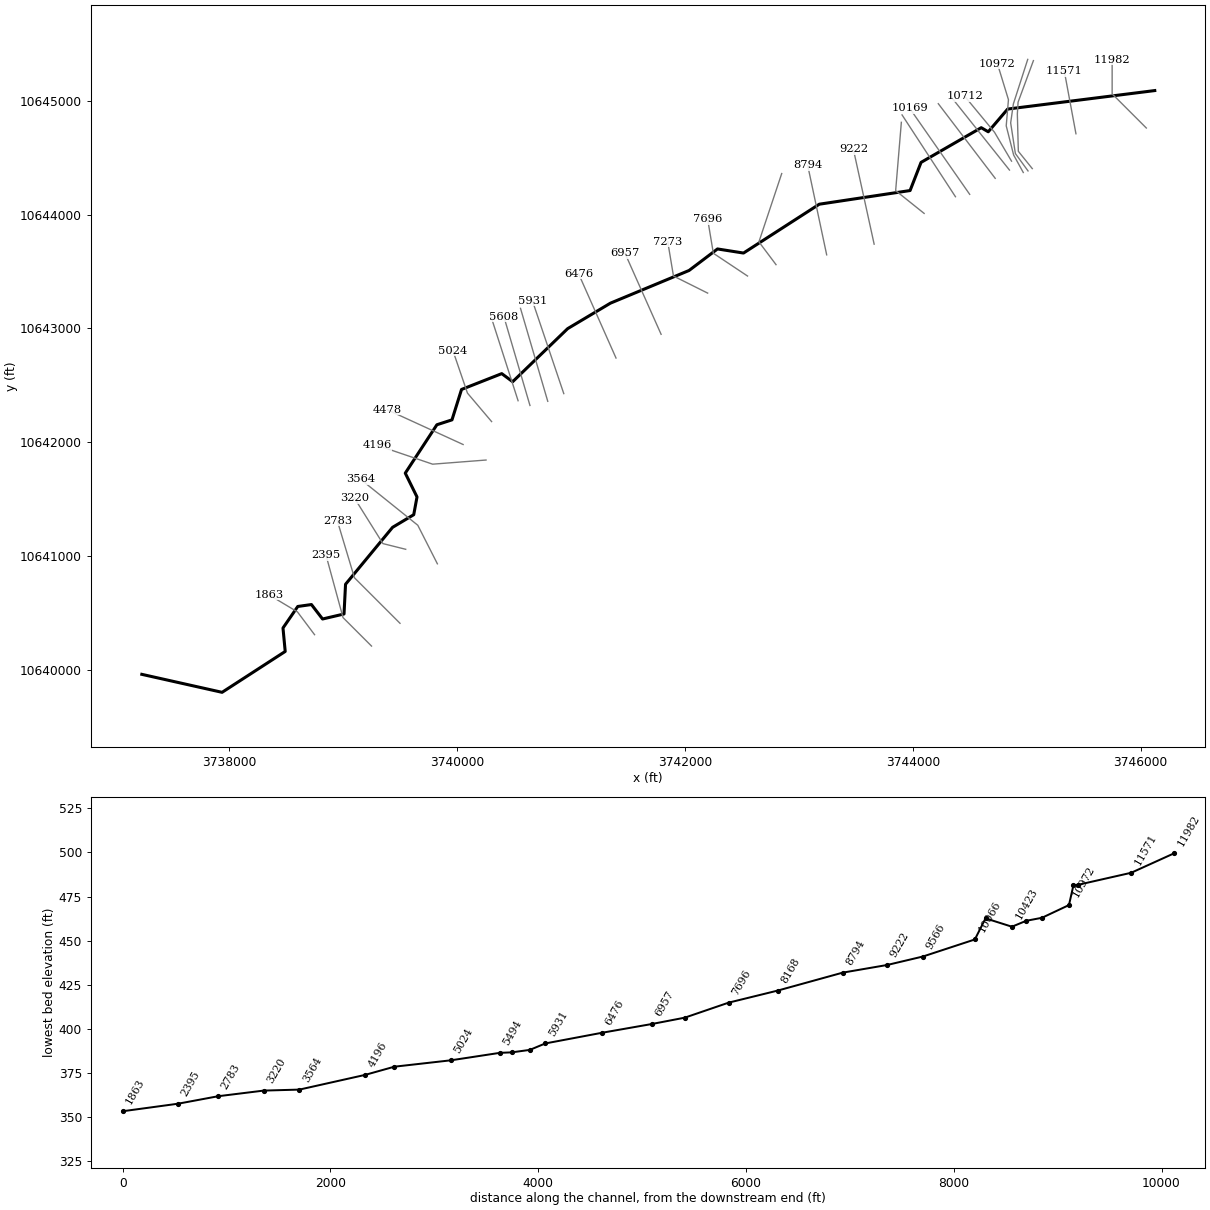
--- UNT 117 IN BOCR.prj (project) ---

Proj Title=UNT 117 IN BOCR Base Level Engineering
Current Plan=p01
Default Exp/Contr=0.3,0.1
English Units
Geom File=g01
Flow File=f01
Plan File=p01
Y Axis Title=Elevation
X Axis Title(PF)=Main Channel Distance
X Axis Title(XS)=Station
BEGIN DESCRIPTION:
UNT 117 IN BOCR
END DESCRIPTION:
DSS Export Rating Curves= 0
DSS Export Rating Curve Sorted= 0
DSS Export Volume Flow Curves= 0
DXF OffsetX= 0
DXF OffsetY= 0
DXF ScaleX= 1
DXF ScaleY= 10

--- UNT 117 IN BOCR.p01 (plan) ---

Plan Title=Multiple Run
Short Identifier=Multiple
Geom File=g01
Flow File=f01
Subcritical Flow
K Sum by GR= 0
Std Step Tol= 0.01
Critical Tol= 0.01
Num of Std Step Trials= 20
Max Error Tol= 0.3
Flow Tol Ratio= 0.001
Split Flow NTrial= 30
Split Flow Tol= 0.02
Split Flow Ratio= 0.02
Log Output Level= 0
Friction Slope Method= 1
Unsteady Friction Slope Method= 2
Unsteady Bridges Friction Slope Method= 1
Parabolic Critical Depth
Global Vel Dist=  1 , 1 , 1
Global Log Level= 0
CheckData=True
Encroach Param= -1, 0, 0, 0
BEGIN DESCRIPTION:
Multiple Run
END DESCRIPTION:

--- UNT 117 IN BOCR.f01 (steady flow) ---

Flow Title=Multiple
Number of Profiles=7
Profile Names=10-year,25-year,50-year,1pct_min,100-year,1pct_plu,500-year
River Rch & RM= UNT 117 IN BOCR,Reach-1,11982
     565     770     942     849    1148    1553    1710
River Rch & RM= UNT 117 IN BOCR,Reach-1,3564
     886    1238    1538    1406    1901    2571    2912
Boundary for River Rch & Prof#=UNT 117 IN BOCR,Reach-1,1
Up Type=0
Dn Type=3
Dn Slope=0.005
Boundary for River Rch & Prof#=UNT 117 IN BOCR,Reach-1,2
Up Type=0
Dn Type=3
Dn Slope=0.005
Boundary for River Rch & Prof#=UNT 117 IN BOCR,Reach-1,3
Up Type=0
Dn Type=3
Dn Slope=0.005
Boundary for River Rch & Prof#=UNT 117 IN BOCR,Reach-1,4
Up Type=0
Dn Type=3
Dn Slope=0.005
Boundary for River Rch & Prof#=UNT 117 IN BOCR,Reach-1,5
Up Type=0
Dn Type=3
Dn Slope=0.005
Boundary for River Rch & Prof#=UNT 117 IN BOCR,Reach-1,6
Up Type=0
Dn Type=3
Dn Slope=0.005
Boundary for River Rch & Prof#=UNT 117 IN BOCR,Reach-1,7
Up Type=0
Dn Type=3
Dn Slope=0.005

--- UNT 117 IN BOCR.g01 (geometry) ---

Geom Title=Existing Conditions
Program Version=4.10

River Reach=UNT 117 IN BOCR ,Reach-1
Reach XY= 30
      3746123.75       10645089.      3744832.54     10644926.61
      3744662.25       10644727.      3744600.75       10644763.
      3744072.57     10644458.27      3743976.25       10644211.
       3743179.5       10644091.      3742514.25       10643662.
        3742286.       10643698.       3742036.5       10643509.
       3741346.5       10643222.      3740970.75       10642998.
      3740488.25       10642532.       3740392.5       10642603.
       3740039.5       10642464.      3739955.75       10642197.
      3739823.25       10642154.      3739545.75       10641729.
      3739648.75       10641520.        3739620.       10641364.
      3739434.25       10641253.       3739021.5       10640753.
      3739008.25       10640492.      3738819.75       10640448.
      3738722.25       10640575.      3738602.25       10640558.
       3738472.5       10640369.        3738492.       10640163.
        3737938.       10639804.       3737233.5       10639962.

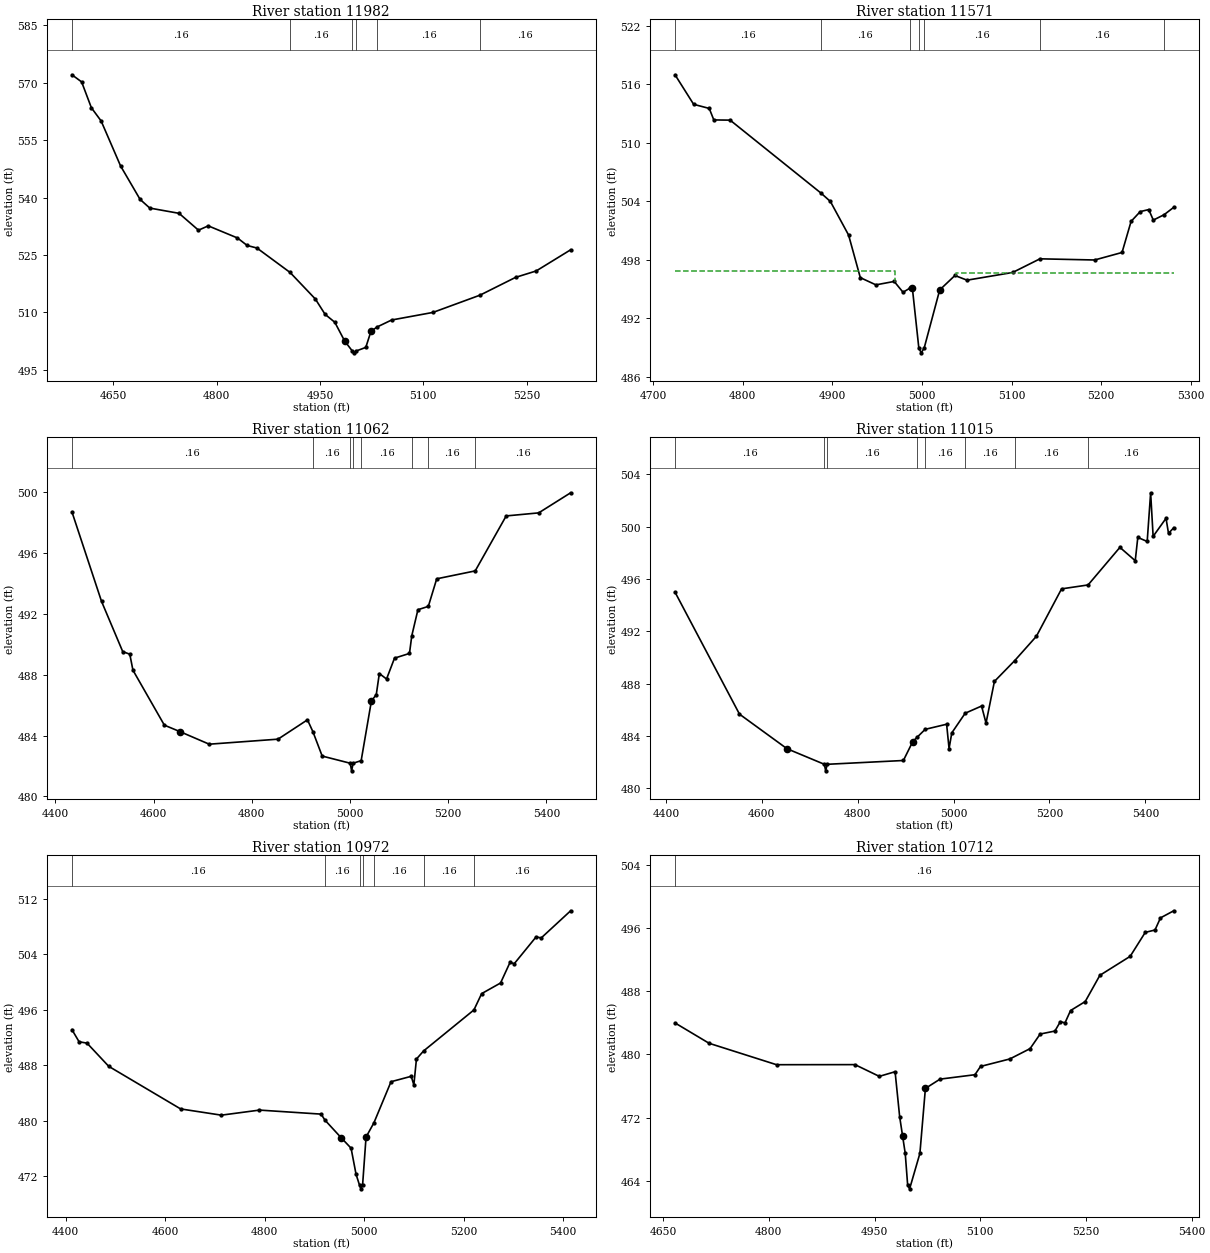
Type RM Length L Ch R = 1 ,11982   ,411,411,411
BEGIN DESCRIPTION:
UNT 117 IN BOCR 26.0
END DESCRIPTION:
XS GIS Cut Line= 3
       3746049.6     10644760.19      3745749.61     10645060.19
      3745749.61     10645360.23
#Sta/Elev= 30
  4589.7  572.04  4603.8  570.18    4618  563.42  4632.1  559.99  4660.4  548.23
  4688.7  539.51  4702.8  537.24  4745.3  535.87  4773.5  531.47  4787.7   532.6
  4830.1  529.44  4844.2  527.48  4858.4  526.81  4906.5  520.44  4943.2  513.51
  4957.4   509.5  4971.5  507.43  4985.7  502.57  4996.8  499.95  4999.6  499.45
  5002.8  499.95  5016.5  500.87    5024  505.07  5033.1  506.22    5054  508.02
    5114     510  5182.4  514.51    5234  519.15    5264  520.83    5314  526.35
#Mann= 6 ,-1 , 0
  4589.7     .16       0  4906.5     .16       0  4996.8     .16       0
  5002.8     .16       0  5033.1     .16       0  5182.4     .16       0
Bank Sta=4985.7,5024
XS Rating Curve= 0 ,0
Exp/Cntr=0.3,0.1

Type RM Length L Ch R = 1 ,11571   ,509,509,509
BEGIN DESCRIPTION:
UNT 117 IN BOCR 25.0
END DESCRIPTION:
XS GIS Cut Line= 2
      3745431.99     10644709.73      3745330.33     10645256.96
#Sta/Elev= 30
  4724.3  516.98  4745.1  513.95  4762.5  513.53  4767.6  512.35  4785.8  512.33
  4887.2  504.85  4897.7  503.99    4918  500.55  4931.1  496.18  4948.5  495.44
  4968.9  495.79  4978.8  494.68  4986.2  495.09  4989.2   495.1  4996.4  488.97
  4999.1  488.47  5002.4  488.97  5019.7  494.92  5036.7   496.4  5050.2  495.92
  5101.1  496.71  5131.6  498.11  5192.6  497.99  5223.2  498.76  5233.3  501.95
  5243.5  502.95    5253  503.16  5258.1  502.08  5270.1  502.63  5280.9  503.39
#Mann= 7 ,-1 , 0
  4724.3     .16       0  4887.2     .16       0  4986.2     .16       0
  4996.4     .16       0  5002.4     .16       0  5131.6     .16       0
  5270.1     .16       0
#XS Ineff= 2 , 0
         4969.66  496.87 5037.84           496.7
Permanent Ineff=
       F       F
Bank Sta=4989.2,5019.7
XS Rating Curve= 0 ,0
Exp/Cntr=0.3,0.1

Type RM Length L Ch R = 1 ,11062   ,47,47,47
BEGIN DESCRIPTION:
Mapping XS 57aa48e5
END DESCRIPTION:
XS GIS Cut Line= 5
      3745048.75     10644403.63      3744926.35     10644555.61
      3744917.67      10644883.3      3744924.18     10644987.46
      3745058.72     10645352.02
#Sta/Elev= 30
  4433.5  498.69  4493.8  492.81    4537  489.51  4551.4  489.34  4557.8  488.29
  4621.8  484.68  4653.2  484.26  4713.2  483.43  4853.3  483.76  4913.3  485.03
  4924.4  484.25  4943.3  482.65  5000.4  482.18  5003.2  481.68  5006.4  482.18
  5022.7  482.35  5043.5  486.26  5053.5  486.69  5059.7  488.07  5074.4  487.71
  5090.6  489.08  5121.1  489.39  5125.8  490.55  5138.3  492.26  5159.5  492.48
  5176.6  494.29    5255  494.81  5318.1  498.42  5384.3  498.62  5449.4  499.94
#Mann= 8 ,-1 , 0
  4433.5     .16       0  4924.4     .16       0  5000.4     .16       0
  5006.4     .16       0  5022.7     .16       0  5125.8     .16       0
  5159.5     .16       0    5255     .16       0
Bank Sta=4653.2,5043.5
XS Rating Curve= 0 ,0
Exp/Cntr=0.3,0.1

Type RM Length L Ch R = 1 ,11015   ,43,43,43
BEGIN DESCRIPTION:
Mapping XS e8bbd326
END DESCRIPTION:
XS GIS Cut Line= 5
      3745011.43     10644383.22      3744900.31     10644536.08
      3744859.08     10644805.17      3744882.95     10644972.27
      3745008.81     10645362.88
#Sta/Elev= 30
  4418.8  494.99  4553.3  485.67  4652.4  483.03  4730.3  481.84  4733.1  481.34
  4736.3  481.84  4895.2  482.13  4914.7  483.57  4924.5  483.93  4940.7  484.51
  4985.4   484.9  4990.5  483.04  4996.2  484.24  5024.1  485.74  5058.3  486.29
  5067.6  484.99  5085.1  488.17  5127.2  489.75  5172.7  491.62  5225.2  495.24
  5280.5  495.54  5346.9  498.41  5378.9  497.39  5384.2  499.17  5403.8  498.86
    5411  502.58  5416.2  499.25  5443.1  500.63  5448.3  499.48  5459.2  499.91
#Mann= 8 ,-1 , 0
  4418.8     .16       0  4730.3     .16       0  4736.3     .16       0
  4924.5     .16       0  4940.7     .16       0  5024.1     .16       0
  5127.2     .16       0  5280.5     .16       0
Bank Sta=4652.4,4914.7
XS Rating Curve= 0 ,0
Exp/Cntr=0.3,0.1

Type RM Length L Ch R = 1 ,10972   ,260,260,260
BEGIN DESCRIPTION:
Mapping XS d5705fdb
END DESCRIPTION:
XS GIS Cut Line= 5
      3744969.76     10644369.35      3744885.12     10644523.05
      3744820.02     10644779.13      3744839.55     10645009.17
      3744742.35     10645326.67
#Sta/Elev= 30
  4412.3  493.11  4426.7  491.36  4442.7  491.16  4486.3  487.82  4630.8  481.68
  4712.7  480.78  4789.4  481.51  4913.3  480.93  4920.8  480.08  4953.4  477.54
  4973.5  476.02  4983.5  472.26  4990.6  470.66  4993.3  470.16  4996.6  470.66
  5003.6  477.62  5019.5  479.69  5053.8   485.6  5094.4  486.38  5099.7  485.14
  5104.9  488.87  5119.2  490.03  5220.5  495.95    5236   498.3    5274  499.83
  5293.1  502.81  5301.5  502.61  5345.4  506.47  5355.8  506.33  5414.9  510.24
#Mann= 7 ,-1 , 0
  4412.3     .16       0  4920.8     .16       0  4990.6     .16       0
  4996.6     .16       0  5019.5     .16       0  5119.2     .16       0
  5220.5     .16       0
Bank Sta=4953.4,5003.6
XS Rating Curve= 0 ,0
Exp/Cntr=0.3,0.1

Type RM Length L Ch R = 1 ,10712   ,152,152,152
BEGIN DESCRIPTION:
Mapping XS 06aff65a
END DESCRIPTION:
XS GIS Cut Line= 3
      3744866.57     10644469.21      3744717.27     10644722.66
      3744454.02     10645041.33
#Sta/Elev= 30
    4667     484  4715.3  481.42    4811   478.7  4922.3  478.71  4956.8  477.22
  4979.2  477.81  4985.7  472.09  4989.8  469.68  4993.6  467.44    4997  463.45
  4999.8  462.95  5014.4  467.45  5022.2  475.69    5043  476.87  5092.5  477.43
  5100.4  478.48    5142  479.43  5170.7  480.74    5185  482.59  5205.9  482.97
  5213.7  484.17  5220.2     484  5228.1  485.57  5248.9  486.71  5269.7  490.04
  5312.7  492.45  5334.1  495.49  5347.9  495.79  5355.7  497.33  5374.5  498.23
#Mann= 1 ,-1 , 0
    4667     .16       0
Bank Sta=4989.8,5022.2
XS Rating Curve= 0 ,0
Exp/Cntr=0.3,0.1

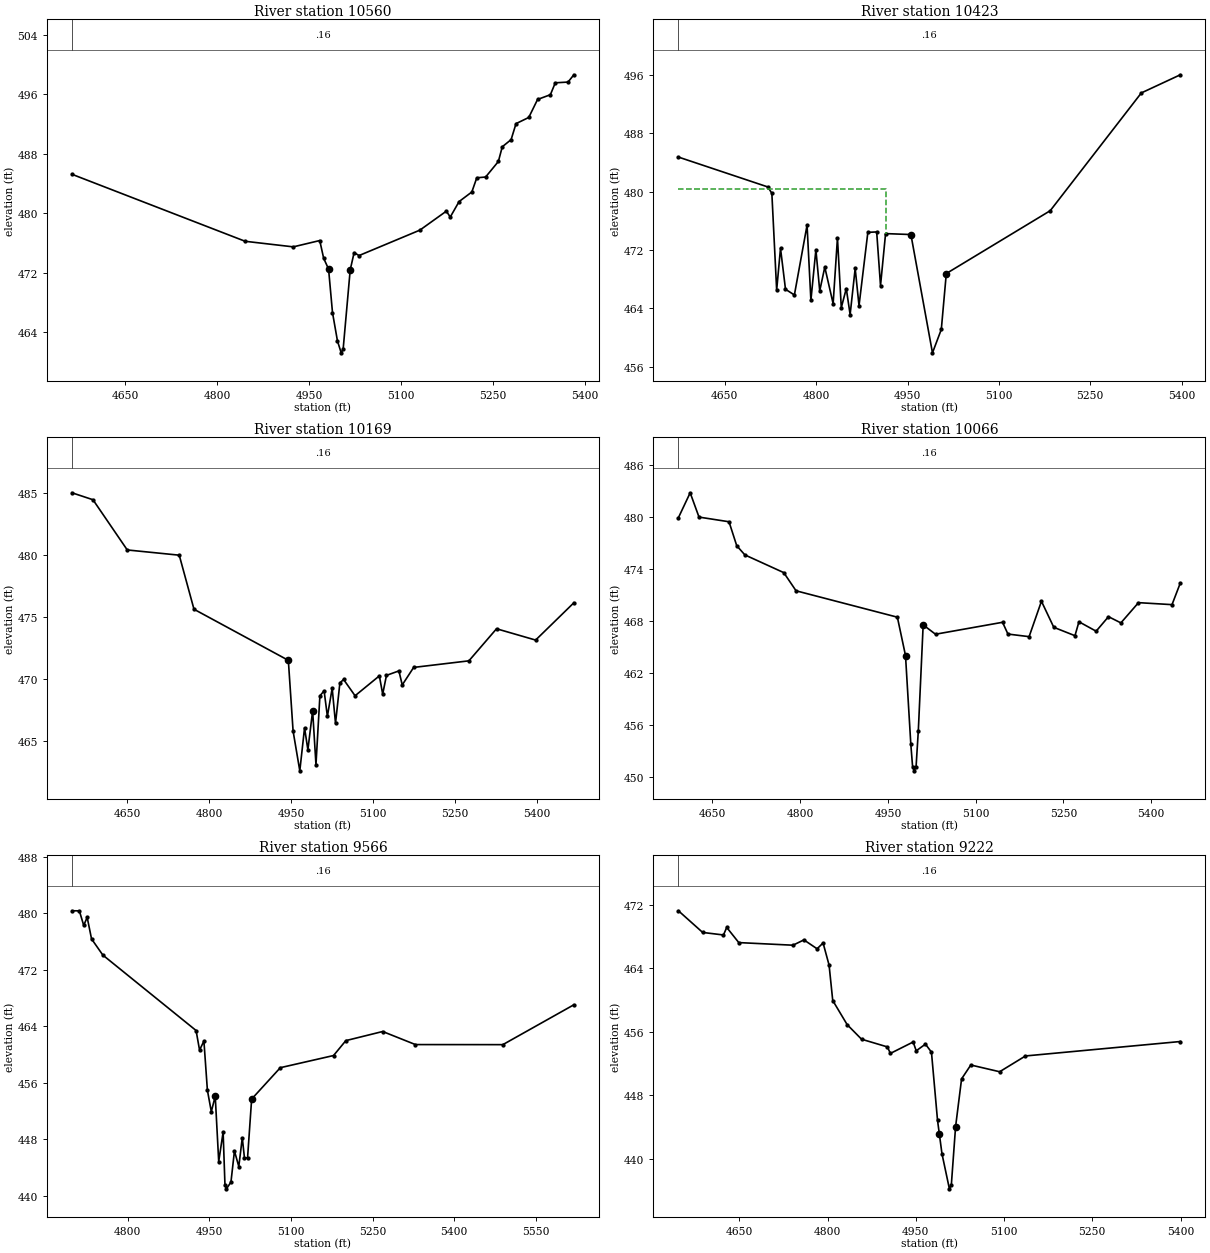
Type RM Length L Ch R = 1 ,10560   ,137,137,137
BEGIN DESCRIPTION:
Mapping XS 2abd3416
END DESCRIPTION:
XS GIS Cut Line= 2
      3744848.37     10644391.08      3744337.95     10645031.71
#Sta/Elev= 30
  4562.9  485.24  4845.6  476.23  4924.1  475.48  4967.3  476.33  4973.7  473.94
  4981.7   472.5  4988.1  466.65  4996.2  462.83  5002.3  461.23  5005.5  461.73
    5017  472.38  5023.4  474.71  5031.4  474.31  5130.7  477.73  5173.9  480.28
  5180.3  479.49  5194.7  481.57  5215.5  482.86  5223.6  484.77    5238  484.87
  5258.8  486.96  5265.2  488.94  5279.6   489.9  5287.6  492.05  5308.4  492.88
  5322.8   495.3  5343.7  495.94  5351.7  497.54  5372.5  497.64    5382  498.62
#Mann= 1 ,-1 , 0
  4562.9     .16       0
Bank Sta=4981.7,5017
XS Rating Curve= 0 ,0
Exp/Cntr=0.3,0.1

Type RM Length L Ch R = 1 ,10423   ,254,254,254
BEGIN DESCRIPTION:
Mapping XS a2a943d2
END DESCRIPTION:
XS GIS Cut Line= 2
      3744723.36     10644318.18      3744223.98     10644973.62
#Sta/Elev= 30
  4573.8  484.75  4720.6  480.65  4727.2  479.78  4735.1   466.5  4741.4  472.24
  4749.6  466.61  4764.2  465.83    4785  475.41  4791.3   465.1  4799.5  472.04
  4805.8   466.4  4814.1  469.65  4827.8  464.64  4834.9  473.66  4841.2  464.09
  4849.4  466.71  4855.7  463.14    4864  469.47  4870.3  464.36  4884.8  474.42
  4899.3  474.48  4905.6  467.12  4913.9  474.25  4955.5  474.12  4990.9  457.89
  5005.4   461.1  5013.6  468.77  5184.2  477.39  5333.8  493.55  5397.8  496.04
#Mann= 1 ,-1 , 0
  4573.8     .16       0
#XS Ineff= 2 , 0
         4914.99  480.37
Permanent Ineff=
       F       F
Bank Sta=4955.5,5013.6
XS Rating Curve= 0 ,0
Exp/Cntr=0.3,0.1

Type RM Length L Ch R = 1 ,10169   ,103,103,103
BEGIN DESCRIPTION:
Mapping XS d0833e7b
END DESCRIPTION:
XS GIS Cut Line= 2
       3744499.4     10644177.55      3743974.02     10644931.81
#Sta/Elev= 30
  4548.4     485  4586.9  484.44  4649.7   480.4  4744.9  479.98  4771.9  475.63
  4944.7  471.52  4953.4  465.83  4965.7  462.63  4974.4  466.09  4980.5  464.32
  4989.2  467.46  4995.3  463.13  5002.5  468.66  5010.2  469.07  5016.2  467.02
    5025  469.27  5031.1  466.45  5039.1   469.7  5045.9  469.98  5066.9  468.67
  5111.4  470.27  5117.5   468.8  5124.4  470.31  5147.2  470.67  5153.3  469.54
  5174.2  470.95  5275.4  471.48    5326  474.06  5397.6  473.15  5467.6  476.15
#Mann= 1 ,-1 , 0
  4548.4     .16       0
Bank Sta=4944.7,4989.2
XS Rating Curve= 0 ,0
Exp/Cntr=0.3,0.1

Type RM Length L Ch R = 1 ,10066   ,500,500,500
BEGIN DESCRIPTION:
Mapping XS 9162c2f7
END DESCRIPTION:
XS GIS Cut Line= 2
      3744374.45     10644156.65      3743905.75     10644875.32
#Sta/Elev= 30
  4591.8  479.92  4611.9   482.8    4627  479.99  4678.3  479.45  4691.5  476.68
  4705.4  475.62  4771.9  473.57  4792.9  471.47  4966.1  468.42    4980  463.99
  4989.1  453.72  4992.1  451.16  4994.9  450.66  4998.1  451.16  5001.9  455.28
  5010.2  467.53  5031.3  466.45  5145.9  467.83  5155.1  466.47  5191.3  466.17
  5212.4  470.26  5233.5  467.25  5269.7  466.28  5276.5  467.89  5305.9   466.8
    5327  468.48  5348.2  467.76  5378.3   470.1  5435.6  469.87  5449.8  472.37
#Mann= 1 ,-1 , 0
  4591.8     .16       0
Bank Sta=4980,5010.2
XS Rating Curve= 0 ,0
Exp/Cntr=0.3,0.1

Type RM Length L Ch R = 1 ,9566    ,344,344,344
BEGIN DESCRIPTION:
UNT 117 IN BOCR 21.0
END DESCRIPTION:
XS GIS Cut Line= 3
      3744099.62     10644010.18      3743849.61     10644210.19
      3743899.61     10644810.23
#Sta/Elev= 30
  4697.4  480.33    4711  480.32    4719  478.27  4725.4  479.39  4733.4  476.35
  4754.2  474.06  4925.5  463.39  4931.9  460.62  4939.9   461.9  4946.3  454.94
  4953.5  451.91  4960.7   454.1  4967.1  444.85  4975.2  449.02  4978.6  441.49
  4981.3  440.99  4989.6  441.95    4996  446.35    5004  444.15  5010.4  448.21
  5014.4  445.37  5020.1  445.37  5027.6  453.69  5080.3  458.13  5178.1  459.85
  5200.7  461.96  5268.4  463.25  5328.6   461.4  5489.2  461.39  5619.7  467.03
#Mann= 1 ,-1 , 0
  4697.4     .16       0
Bank Sta=4960.7,5027.6
XS Rating Curve= 0 ,0
Exp/Cntr=0.3,0.1

Type RM Length L Ch R = 1 ,9222    ,428,428,428
BEGIN DESCRIPTION:
Mapping XS 5e96d73e
END DESCRIPTION:
XS GIS Cut Line= 2
      3743660.89     10643739.98      3743478.59     10644573.37
#Sta/Elev= 30
  4546.5  471.24  4587.7  468.51  4623.1  468.19  4628.6  469.14  4649.1  467.23
  4741.2   466.9  4759.8  467.57  4782.2  466.45  4792.4  467.18  4802.6  464.39
  4808.8  459.93  4833.3  456.89  4857.8  455.05  4901.7  454.08  4906.8  453.26
  4945.5   454.7  4950.7  453.59  4966.4  454.43  4976.6  453.42  4986.9  444.84
  4990.1  443.05  4994.5   440.6  5007.1  436.19  5010.4  436.69  5017.6  444.02
  5027.8  450.05  5043.5   451.8  5092.5  450.95  5136.4  452.94  5399.6  454.76
#Mann= 1 ,-1 , 0
  4546.5     .16       0
Bank Sta=4990.1,5017.6
XS Rating Curve= 0 ,0
Exp/Cntr=0.3,0.1

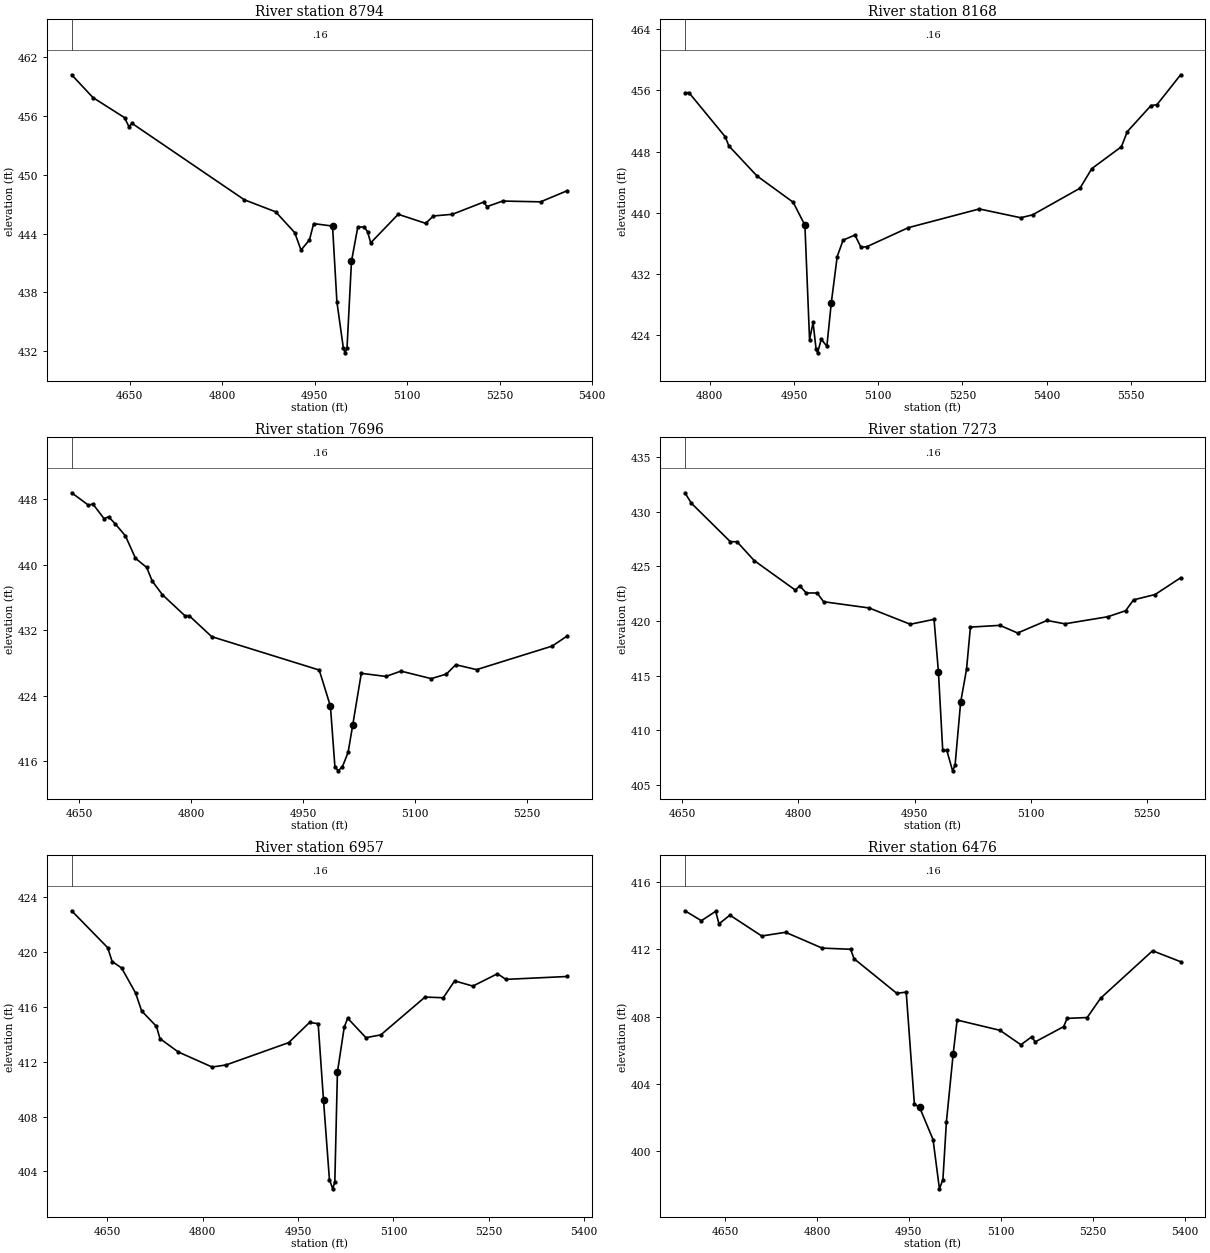
Type RM Length L Ch R = 1 ,8794    ,626,626,626
BEGIN DESCRIPTION:
Mapping XS ea30d01c
END DESCRIPTION:
XS GIS Cut Line= 2
      3743244.22     10643646.25      3743077.56     10644432.68
#Sta/Elev= 30
    4556  460.19  4590.7  457.86  4641.8  455.82  4648.8  454.91  4653.9  455.24
    4836  447.45  4886.9  446.22  4917.8   444.1    4928  442.32  4941.7  443.37
  4948.5  445.02  4979.1  444.77  4986.2  437.03  4996.6  432.35  4999.3  431.85
  5002.6  432.35  5009.8  441.16    5020  444.66  5030.2  444.69  5035.9   444.2
    5041  443.06  5085.6  445.97  5130.1  445.05  5142.7   445.8  5173.4  445.97
  5224.4  447.22  5229.5  446.75  5255.1  447.32  5316.5  447.24  5359.9  448.38
#Mann= 1 ,-1 , 0
    4556     .16       0
Bank Sta=4979.1,5009.8
XS Rating Curve= 0 ,0
Exp/Cntr=0.3,0.1

Type RM Length L Ch R = 1 ,8168    ,472,472,472
BEGIN DESCRIPTION:
UNT 117 IN BOCR 18.0
END DESCRIPTION:
XS GIS Cut Line= 3
      3742799.62     10643560.17      3742649.61     10643760.19
      3742849.62     10644360.21
#Sta/Elev= 30
    4756   455.7  4763.3  455.69  4827.9  449.92  4834.1  448.75  4884.1  444.82
  4948.7  441.37  4969.6  438.37  4977.9  423.39  4984.1  425.64  4989.5  422.17
  4992.2  421.67  4998.7  423.45  5008.7  422.53  5016.6  428.22  5027.1  434.26
  5037.6  436.41  5058.7  437.08  5069.3  435.49  5079.8  435.55  5153.6  438.04
  5280.1  440.49  5353.9  439.34    5375  439.72  5459.3   443.2  5480.4  445.77
  5533.1  448.63  5543.6  450.61  5585.8  454.02  5596.3  454.12  5638.5  458.04
#Mann= 1 ,-1 , 0
    4756     .16       0
Bank Sta=4969.6,5016.6
XS Rating Curve= 0 ,0
Exp/Cntr=0.3,0.1

Type RM Length L Ch R = 1 ,7696    ,423,423,423
BEGIN DESCRIPTION:
UNT 117 IN BOCR 17.0
END DESCRIPTION:
XS GIS Cut Line= 3
      3742549.59      10643460.2      3742249.61     10643660.19
       3742199.6     10643960.22
#Sta/Elev= 30
  4639.6   448.8  4662.1  447.29  4668.1  447.43  4683.1  445.64  4689.2  445.87
  4698.2  444.99  4711.7  443.54  4725.2   440.8  4740.2  439.68  4747.7  438.01
  4761.3  436.35  4791.3   433.8  4797.3  433.78  4827.4  431.23  4971.6  427.15
  4986.6  422.74  4992.6  415.35  4996.9  414.84  5002.7  415.34  5010.3  417.09
  5016.6  420.48    5028  426.75    5061  426.37  5081.2  427.02  5121.8   426.1
  5142.1  426.66  5154.7   427.8  5182.6   427.2    5284  430.08  5304.3  431.32
#Mann= 1 ,-1 , 0
  4639.6     .16       0
Bank Sta=4986.6,5016.6
XS Rating Curve= 0 ,0
Exp/Cntr=0.3,0.1

Type RM Length L Ch R = 1 ,7273    ,316,316,316
BEGIN DESCRIPTION:
UNT 117 IN BOCR 16.0
END DESCRIPTION:
XS GIS Cut Line= 3
      3742199.59      10643310.2      3741899.61     10643460.19
      3741849.61     10643760.17
#Sta/Elev= 30
  4653.5  431.73  4661.9  430.77  4712.2  427.25  4720.6  427.26  4742.9  425.53
    4796  422.83  4801.6  423.23    4810  422.57    4824  422.57  4832.4  421.77
  4891.1   421.2  4944.2  419.71  4974.9  420.16  4980.5  415.39  4986.1  408.17
  4991.4  408.17  4998.8  406.31    5002  406.81  5009.2  412.58  5016.8  415.59
  5021.8  419.45  5059.9  419.61  5082.7  418.91  5120.7  420.06  5143.5  419.75
  5199.2   420.4  5222.1  420.95  5232.2  421.94  5260.1  422.43    5293  423.96
#Mann= 1 ,-1 , 0
  4653.5     .16       0
Bank Sta=4980.5,5009.2
XS Rating Curve= 0 ,0
Exp/Cntr=0.3,0.1

Type RM Length L Ch R = 1 ,6957    ,481,481,481
BEGIN DESCRIPTION:
Mapping XS 4f1dfb30
END DESCRIPTION:
XS GIS Cut Line= 2
      3741791.09     10642948.35      3741473.98     10643660.54
#Sta/Elev= 30
    4594     423  4650.7  420.31  4657.7   419.3  4672.6  418.83  4694.5  417.01
  4704.1   415.7  4727.4  414.57  4732.9  413.68  4761.6  412.71  4814.9  411.61
  4836.8  411.76  4935.4  413.39  4968.2  414.86  4981.7  414.77  4990.1   409.2
  4999.4  403.41  5004.6  402.73  5007.9  403.23    5012  411.24  5022.7  414.51
  5028.1  415.17  5056.8  413.75  5080.1  413.95  5149.8  416.71  5178.5  416.66
  5196.3  417.89    5225  417.51  5263.7  418.41  5276.9     418  5373.6  418.21
#Mann= 1 ,-1 , 0
    4594     .16       0
Bank Sta=4990.1,5012
XS Rating Curve= 0 ,0
Exp/Cntr=0.3,0.1

Type RM Length L Ch R = 1 ,6476    ,545,545,545
BEGIN DESCRIPTION:
Mapping XS 05ad82a5
END DESCRIPTION:
XS GIS Cut Line= 2
      3741395.26     10642740.02      3741067.13      10643479.6
#Sta/Elev= 30
  4584.5  414.29  4611.4   413.7  4634.7  414.26  4640.1  413.51  4657.9  414.03
  4709.9  412.79  4748.8  413.01  4808.5  412.07    4855     412  4860.5  411.44
  4930.3  409.38  4945.7  409.45    4959   402.8  4967.6  402.59  4989.5  400.68
  4999.9  397.75  5005.6   398.3  5011.3  401.73  5022.3  405.76  5028.8  407.79
  5098.7  407.18  5132.9  406.32  5150.7   406.8  5156.1  406.49  5202.7   407.4
  5208.3  407.89  5241.1  407.94    5263  409.09  5347.8  411.91  5393.6  411.26
#Mann= 1 ,-1 , 0
  4584.5     .16       0
Bank Sta=4967.6,5022.3
XS Rating Curve= 0 ,0
Exp/Cntr=0.3,0.1

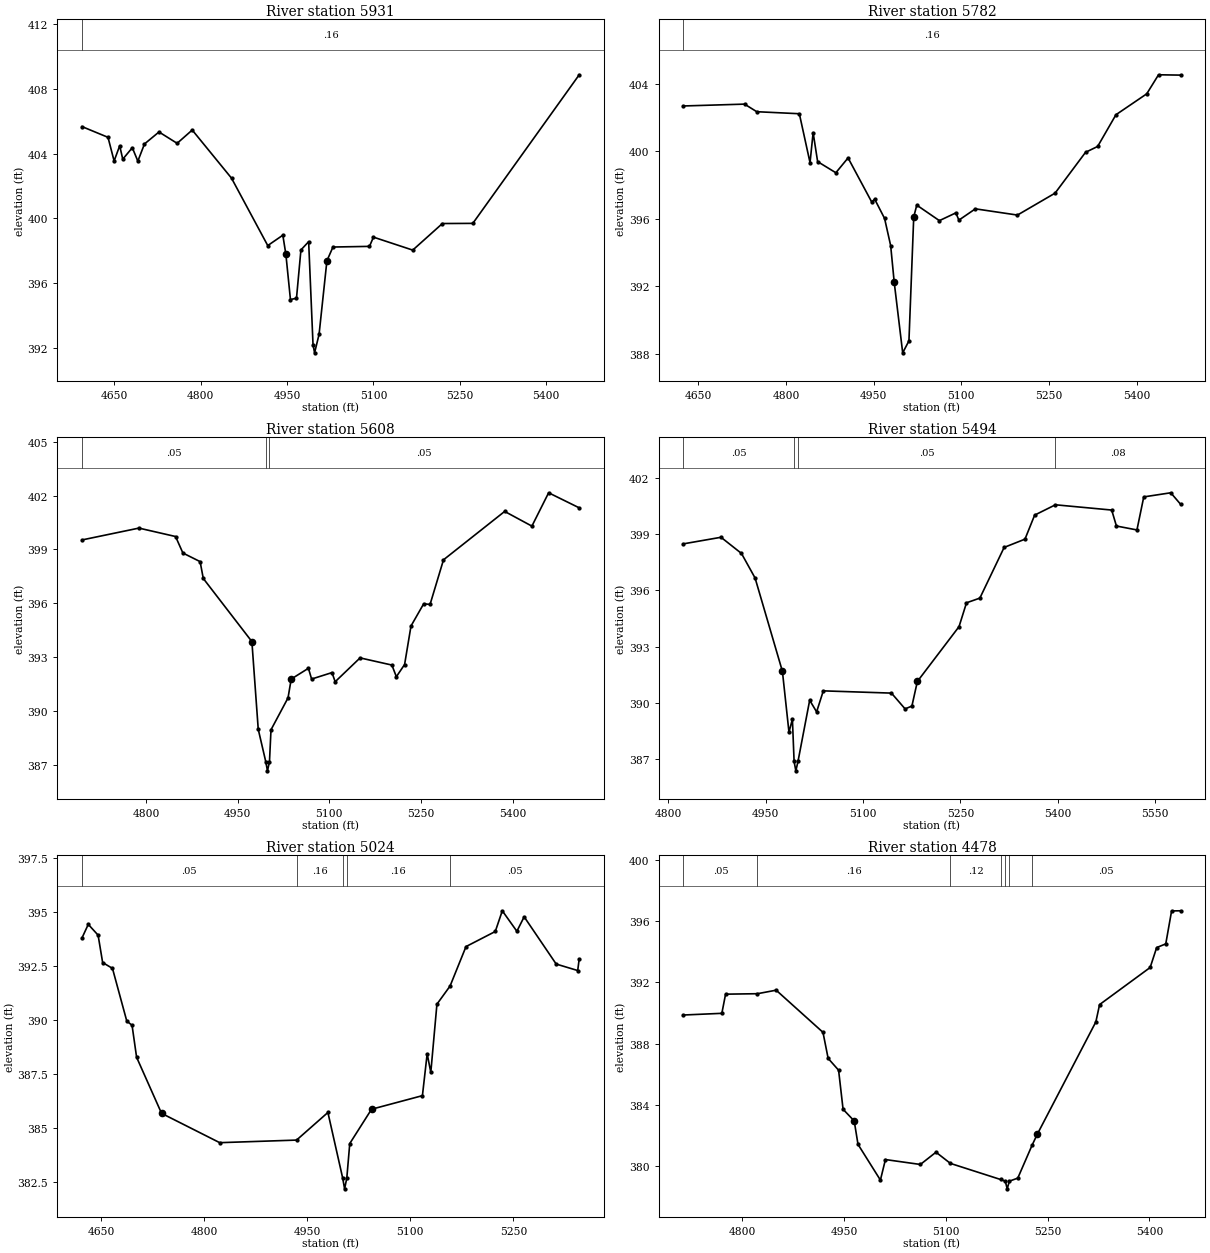
Type RM Length L Ch R = 1 ,5931    ,149,149,149
BEGIN DESCRIPTION:
Mapping XS ac689acc
END DESCRIPTION:
XS GIS Cut Line= 2
      3740936.92     10642427.53      3740660.89      10643245.2
#Sta/Elev= 30
  4594.3  405.66  4639.3     405  4649.9  403.54  4659.6  404.48  4664.9  403.65
  4681.5  404.36  4691.1  403.53  4702.6  404.59  4727.8  405.33  4759.3  404.63
  4785.5  405.45  4853.7  402.48  4916.6  398.32  4942.8  398.96  4948.1  397.77
    4956  394.99  4966.5  395.07  4974.2  398.05  4987.6  398.56  4995.2   392.2
  4997.9   391.7  5005.7  392.84  5019.3  397.38  5029.8  398.23  5093.2  398.27
  5100.1  398.84  5168.3  398.04  5219.8  399.68  5272.6  399.69  5457.3  408.86
#Mann= 1 ,-1 , 0
  4594.3     .16       0
Bank Sta=4948.1,5019.3
XS Rating Curve= 0 ,0
Exp/Cntr=0.3,0.1

Type RM Length L Ch R = 1 ,5782    ,174,174,174
BEGIN DESCRIPTION:
UNT 117 IN BOCR 13.0
END DESCRIPTION:
XS GIS Cut Line= 2
      3740796.31     10642359.78      3740557.06     10643176.35
#Sta/Elev= 30
  4624.5  402.69  4729.1   402.8    4750  402.35  4822.9  402.23  4841.2  399.33
  4846.5  401.11  4854.2  399.39  4885.4  398.73  4906.3  399.61  4946.7     397
  4951.9  397.16  4968.8  396.02  4979.2  394.41  4985.3  392.23  4999.8  388.05
  5010.5  388.76  5018.7  396.11  5023.9  396.81  5062.6  395.89  5090.8  396.35
    5096  395.92  5124.2  396.59  5196.2  396.22  5260.6  397.52  5312.7  399.94
  5333.5  400.29  5364.8  402.17  5417.5  403.41  5437.7  404.54  5475.4  404.52
#Mann= 1 ,-1 , 0
  4624.5     .16       0
Bank Sta=4985.3,5018.7
XS Rating Curve= 0 ,0
Exp/Cntr=0.3,0.1

Type RM Length L Ch R = 1 ,5608    ,114,114,114
BEGIN DESCRIPTION:
UNT 117 IN BOCR 12.0
END DESCRIPTION:
XS GIS Cut Line= 2
      3740640.06     10642323.31      3740410.88      10643104.6
#Sta/Elev= 30
    4695  399.53  4788.1  400.19  4848.1  399.72  4860.1   398.8  4888.3  398.32
  4893.5  397.38  4973.1  393.86  4983.5  388.97  4995.9  387.15  4998.6  386.65
  5001.9  387.15  5004.4  388.94  5032.3  390.72  5037.5  391.77  5065.7  392.37
  5070.9  391.77  5104.3  392.13  5109.5  391.62  5150.3  392.95  5202.4  392.55
  5209.7   391.9  5223.2  392.58  5233.7  394.73  5254.5  395.97  5264.9  395.93
  5286.9  398.42  5387.1  401.12  5431.7   400.3  5459.1  402.16  5509.2  401.32
#Mann= 3 ,-1 , 0
    4695     .05       0  4995.9     .03       0  5001.9     .05       0
Bank Sta=4973.1,5037.5
XS Rating Curve= 0 ,0
Exp/Cntr=0.3,0.1

Type RM Length L Ch R = 1 ,5494    ,470,470,470
BEGIN DESCRIPTION:
Mapping XS 8f2a8855
END DESCRIPTION:
XS GIS Cut Line= 2
      3740535.87     10642365.05       3740301.5      10643094.2
#Sta/Elev= 30
  4823.4  398.47  4881.3  398.82  4912.8  397.96  4933.8  396.65  4975.9  391.68
    4986  388.44  4991.3  389.13  4993.9  386.88  4996.6  386.38  4999.9  386.88
  5017.9  390.14  5028.6  389.52  5038.9  390.64  5143.9  390.52  5164.9  389.68
  5175.4  389.83  5183.8  391.14    5248  394.06  5259.5  395.33  5280.1  395.58
  5317.5  398.28  5349.6  398.72  5364.5     400  5396.5  400.55  5483.2  400.27
  5490.5  399.42  5522.1  399.21  5532.6  400.97  5574.2  401.19  5589.3  400.58
#Mann= 4 ,-1 , 0
  4823.4     .05       0  4993.9     .03       0  4999.9     .05       0
  5396.5     .08       0
Bank Sta=4975.9,5183.8
XS Rating Curve= 0 ,0
Exp/Cntr=0.3,0.1

Type RM Length L Ch R = 1 ,5024    ,546,546,546
BEGIN DESCRIPTION:
UNT 117 IN BOCR 11.0
END DESCRIPTION:
XS GIS Cut Line= 3
      3740303.44     10642181.82      3740091.65      10642431.8
      3739963.44     10642806.01
#Sta/Elev= 30
  4622.6   393.8  4631.6  394.42  4645.9  393.92  4652.5  392.65  4666.8  392.38
  4687.6  389.94  4695.3  389.74  4701.9  388.26  4738.2  385.66  4822.8   384.3
  4934.6  384.42  4980.2   385.7  5001.7  382.66  5004.5  382.16  5007.7  382.66
    5012  384.26  5043.7  385.85  5117.7  386.48  5124.6  388.42  5129.9  387.56
  5138.8  390.72  5157.9  391.56  5181.1  393.39  5223.7  394.09  5233.9  395.05
  5255.1   394.1  5265.7  394.77  5312.3  392.58  5343.6  392.28  5345.8  392.82
#Mann= 5 ,-1 , 0
  4622.6     .05       0  4934.6     .16       0  5001.7     .07       0
  5007.7     .16       0  5157.9     .05       0
Bank Sta=4738.2,5043.7
XS Rating Curve= 0 ,0
Exp/Cntr=0.3,0.1

Type RM Length L Ch R = 1 ,4478    ,282,282,282
BEGIN DESCRIPTION:
UNT 117 IN BOCR 10.0
END DESCRIPTION:
XS GIS Cut Line= 2
      3740053.43     10641980.42      3739387.63     10642285.58
#Sta/Elev= 30
  4713.6  389.86  4770.2  389.97  4775.7  391.22  4822.7  391.25  4850.2  391.48
  4919.2  388.73  4926.8  387.03  4942.2  386.26  4948.8  383.71  4965.2  382.95
  4970.8  381.42  5003.8  379.09  5011.2  380.43  5062.7  380.11  5085.7  380.91
  5106.9  380.18  5180.8  379.13  5187.8  379.02  5190.6  378.52  5193.8  379.02
  5206.2  379.22  5227.1  381.35  5234.8  382.07  5321.2  389.41  5326.7  390.54
  5401.2  392.96  5410.8  394.26  5424.2   394.5  5432.8  396.65    5446  396.66
#Mann= 7 ,-1 , 0
  4713.6     .05       0  4822.7     .16       0  5106.9     .12       0
  5180.8     .16       0  5187.8     .07       0  5193.8     .16       0
  5227.1     .05       0
Bank Sta=4965.2,5234.8
XS Rating Curve= 0 ,0
Exp/Cntr=0.3,0.1

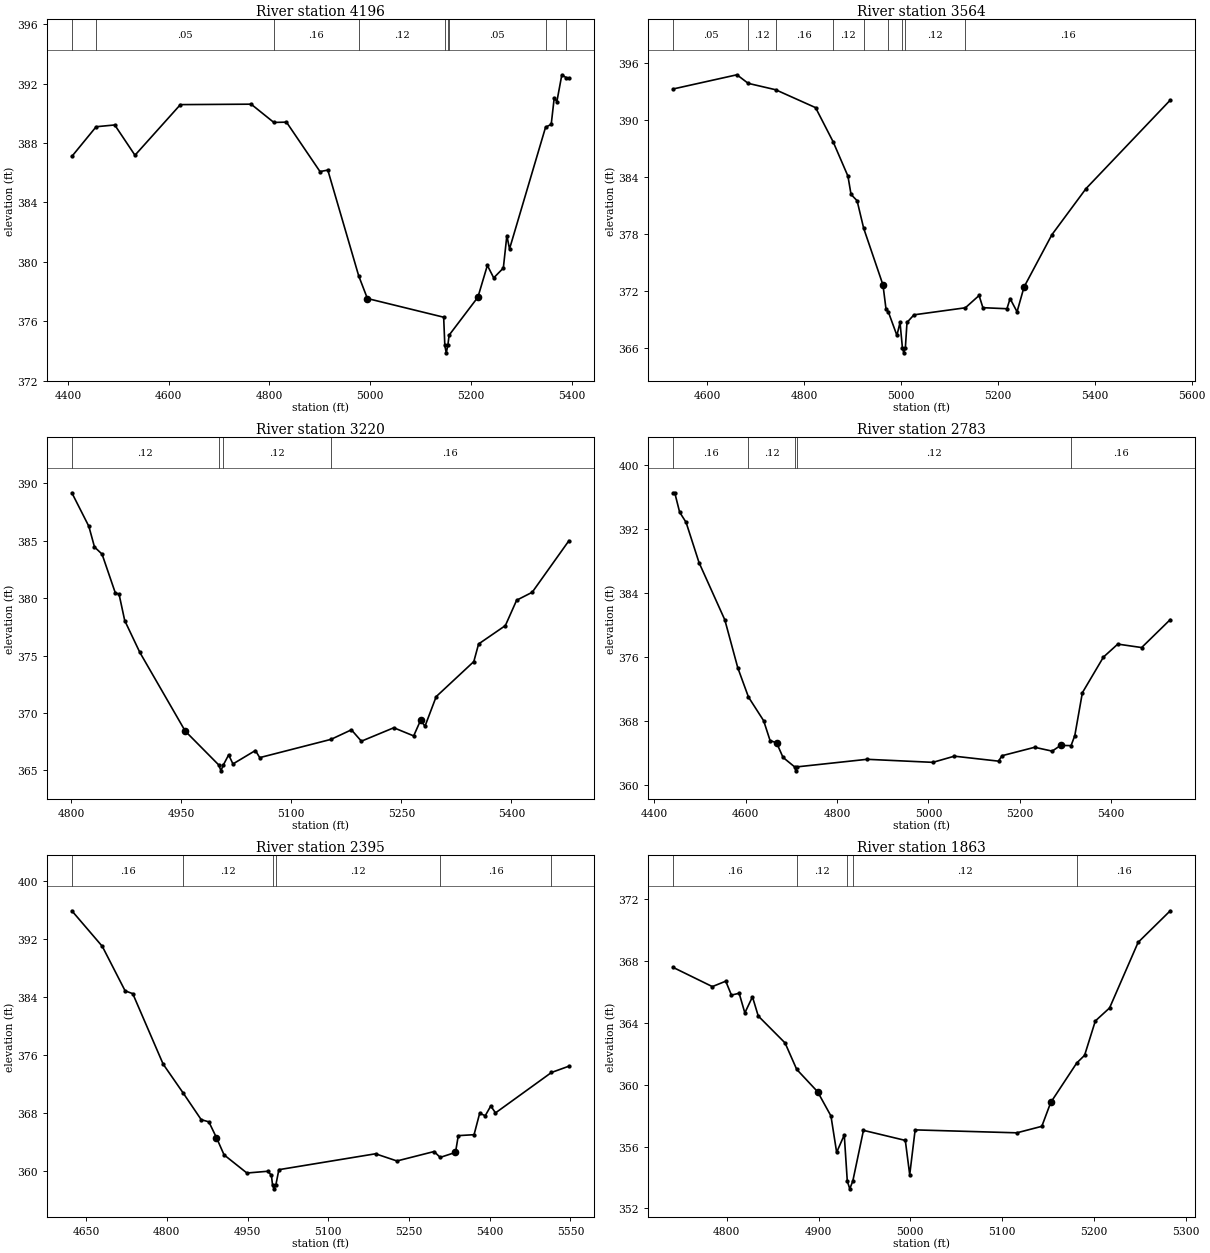
Type RM Length L Ch R = 1 ,4196    ,632,632,632
BEGIN DESCRIPTION:
UNT 117 IN BOCR 9.0
END DESCRIPTION:
XS GIS Cut Line= 3
      3740254.59     10641844.18      3739785.88     10641807.73
       3739296.3      10641974.4
#Sta/Elev= 30
  4407.6   387.1  4455.9   389.1  4492.8  389.22    4533  387.18  4623.2  390.59
  4763.7  390.62  4808.8  389.39  4833.9  389.41  4900.5  386.08    4916  386.18
  4977.3  379.06  4994.6  377.53  5146.1  376.27  5148.4  374.37  5151.2  373.87
  5154.4  374.37  5156.9  375.06  5214.1  377.62  5232.9  379.76  5245.5  378.92
  5264.6  379.58  5271.6  381.77  5276.9  380.87  5348.5  389.07  5359.7  389.26
  5365.7  391.05  5370.9  390.79  5380.8   392.6  5389.2  392.41  5394.9  392.38
#Mann= 9 ,-1 , 0
  4407.6     .16       0  4455.9     .05       0  4808.8     .16       0
  4977.3     .12       0  5148.4     .07       0  5154.4     .12       0
  5156.9     .05       0  5348.5     .12       0  5389.2     .16       0
Bank Sta=4994.6,5214.1
XS Rating Curve= 0 ,0
Exp/Cntr=0.3,0.1

Type RM Length L Ch R = 1 ,3564    ,344,344,344
BEGIN DESCRIPTION:
UNT 117 IN BOCR 8.0
END DESCRIPTION:
XS GIS Cut Line= 3
      3739827.54     10640932.74      3739655.67     10641271.27
       3739151.9     10641676.37
#Sta/Elev= 30
  4529.7  393.24  4661.4  394.73  4684.6  393.83  4741.2  393.16  4823.7  391.28
  4859.9   387.7  4890.5  384.09  4896.9  382.17  4909.4  381.51  4922.9  378.63
  4962.8  372.67  4969.2  370.09  4973.8  369.85  4991.6  367.37    4998  368.73
    5003  366.04  5005.7  365.54    5009  366.04  5012.4  368.73  5026.8  369.53
  5132.9  370.27  5161.2  371.56  5169.1  370.28  5218.7  370.17  5225.2  371.23
  5239.6  369.85    5254  372.45  5311.5  377.94  5381.9  382.78  5555.8  392.07
#Mann= 9 ,-1 , 0
  4529.7     .05       0  4684.6     .12       0  4741.2     .16       0
  4859.9     .12       0  4922.9     .16       0  4973.8     .12       0
    5003     .07       0    5009     .12       0  5132.9     .16       0
Bank Sta=4962.8,5254
XS Rating Curve= 0 ,0
Exp/Cntr=0.3,0.1

Type RM Length L Ch R = 1 ,3220    ,437,437,437
BEGIN DESCRIPTION:
UNT 117 IN BOCR 7.0
END DESCRIPTION:
XS GIS Cut Line= 3
      3739549.58      10641060.2      3739349.61     10641110.19
      3739099.62     10641510.17
#Sta/Elev= 30
  4800.7  389.17  4823.9  386.25  4831.6  384.45  4841.9  383.83  4859.9  380.47
  4865.1  380.34  4872.8  378.05  4893.4  375.28  4955.3  368.43  5001.2  365.47
    5004  364.97  5007.2  365.47  5014.5  366.36  5020.4  365.57    5051  366.74
  5056.9  366.12  5154.1  367.71  5181.9  368.54  5195.5  367.55  5239.7  368.72
  5266.8  368.01  5276.3  369.38  5282.2  368.85  5297.5  371.43  5348.8  374.48
  5355.3  376.01  5391.8  377.61  5407.2  379.82  5428.4  380.51  5478.5     385
#Mann= 4 ,-1 , 0
  4800.7     .12       0  5001.2     .07       0  5007.2     .12       0
  5154.1     .16       0
Bank Sta=4955.3,5276.3
XS Rating Curve= 0 ,0
Exp/Cntr=0.3,0.1

Type RM Length L Ch R = 1 ,2783    ,388,388,388
BEGIN DESCRIPTION:
UNT 117 IN BOCR 6.0
END DESCRIPTION:
XS GIS Cut Line= 3
      3739499.62     10640410.18      3739099.61     10640810.19
      3738949.61     10641310.18
#Sta/Elev= 30
  4441.4   396.5  4444.9   396.5  4455.6  394.08  4469.7  392.81    4498  387.79
  4554.5  380.63  4582.8  374.66  4606.2     371  4639.4  368.05  4653.5  365.57
  4667.7  365.29  4681.8  363.47  4707.1  362.29  4709.9  361.79  4713.1  362.29
  4865.7  363.23  5009.7  362.85  5056.7  363.62  5153.3     363  5161.1  363.68
  5232.4  364.73  5270.7  364.25    5289  364.96  5312.1  364.94  5320.3   366.2
  5336.8  371.54  5382.9  375.99  5414.3  377.61  5466.5  377.18  5529.1  380.67
#Mann= 5 ,-1 , 0
  4441.4     .16       0  4606.2     .12       0  4707.1     .07       0
  4713.1     .12       0  5312.1     .16       0
Bank Sta=4667.7,5289
XS Rating Curve= 0 ,0
Exp/Cntr=0.3,0.1

Type RM Length L Ch R = 1 ,2395    ,532,532,532
BEGIN DESCRIPTION:
UNT 117 IN BOCR 5.0
END DESCRIPTION:
XS GIS Cut Line= 3
      3739249.62     10640210.18      3738999.61     10640460.19
       3738849.6     10641010.23
#Sta/Elev= 30
  4623.5  395.84  4680.1  390.94  4722.5  384.81  4736.7  384.42  4793.2  374.71
  4830.6  370.71  4863.9  367.06  4878.1  366.76  4892.2  364.59  4906.4  362.21
  4948.8  359.71  4987.4  359.95  4994.3  359.41  4996.5  358.03  4999.3  357.53
  5002.5  358.03  5008.2  360.17  5187.8  362.36  5227.6  361.37  5296.7  362.67
  5307.9  361.86  5336.4  362.55  5341.6  364.86  5370.9  364.99  5381.3  367.93
  5391.7  367.61    5402  368.95  5410.7  367.99  5514.7  373.56  5547.2  374.43
#Mann= 6 ,-1 , 0
  4623.5     .16       0  4830.6     .12       0  4996.5     .07       0
  5002.5     .12       0  5307.9     .16       0  5514.7     .12       0
Bank Sta=4892.2,5336.4
XS Rating Curve= 0 ,0
Exp/Cntr=0.3,0.1

Type RM Length L Ch R = 1 ,1863    ,488,488,488
BEGIN DESCRIPTION:
UNT 117 IN BOCR 4.0
END DESCRIPTION:
XS GIS Cut Line= 3
      3738749.59     10640310.21      3738599.61     10640510.19
      3738349.63     10640660.18
#Sta/Elev= 30
  4741.6  367.58  4784.3  366.34  4798.9  366.69  4805.1  365.79  4813.5  365.91
  4819.7  364.64    4828  365.68  4834.3  364.44  4863.5   362.7  4876.2  360.99
  4898.9  359.55  4913.5  357.98  4919.7  355.63    4928  356.75  4931.3  353.77
    4934  353.27  4937.3  353.77  4948.9  357.05  4994.5   356.4  4999.3  354.18
  5005.2  357.08    5116  356.89  5143.2  357.31  5152.9  358.85  5181.2   361.4
  5189.8   361.9  5201.5  364.12    5217  364.96  5248.1   369.2  5283.1  371.24
#Mann= 5 ,-1 , 0
  4741.6     .16       0  4876.2     .12       0  4931.3     .07       0
  4937.3     .12       0  5181.2     .16       0
Bank Sta=4898.9,5152.9
XS Rating Curve= 0 ,0
Exp/Cntr=0.3,0.1