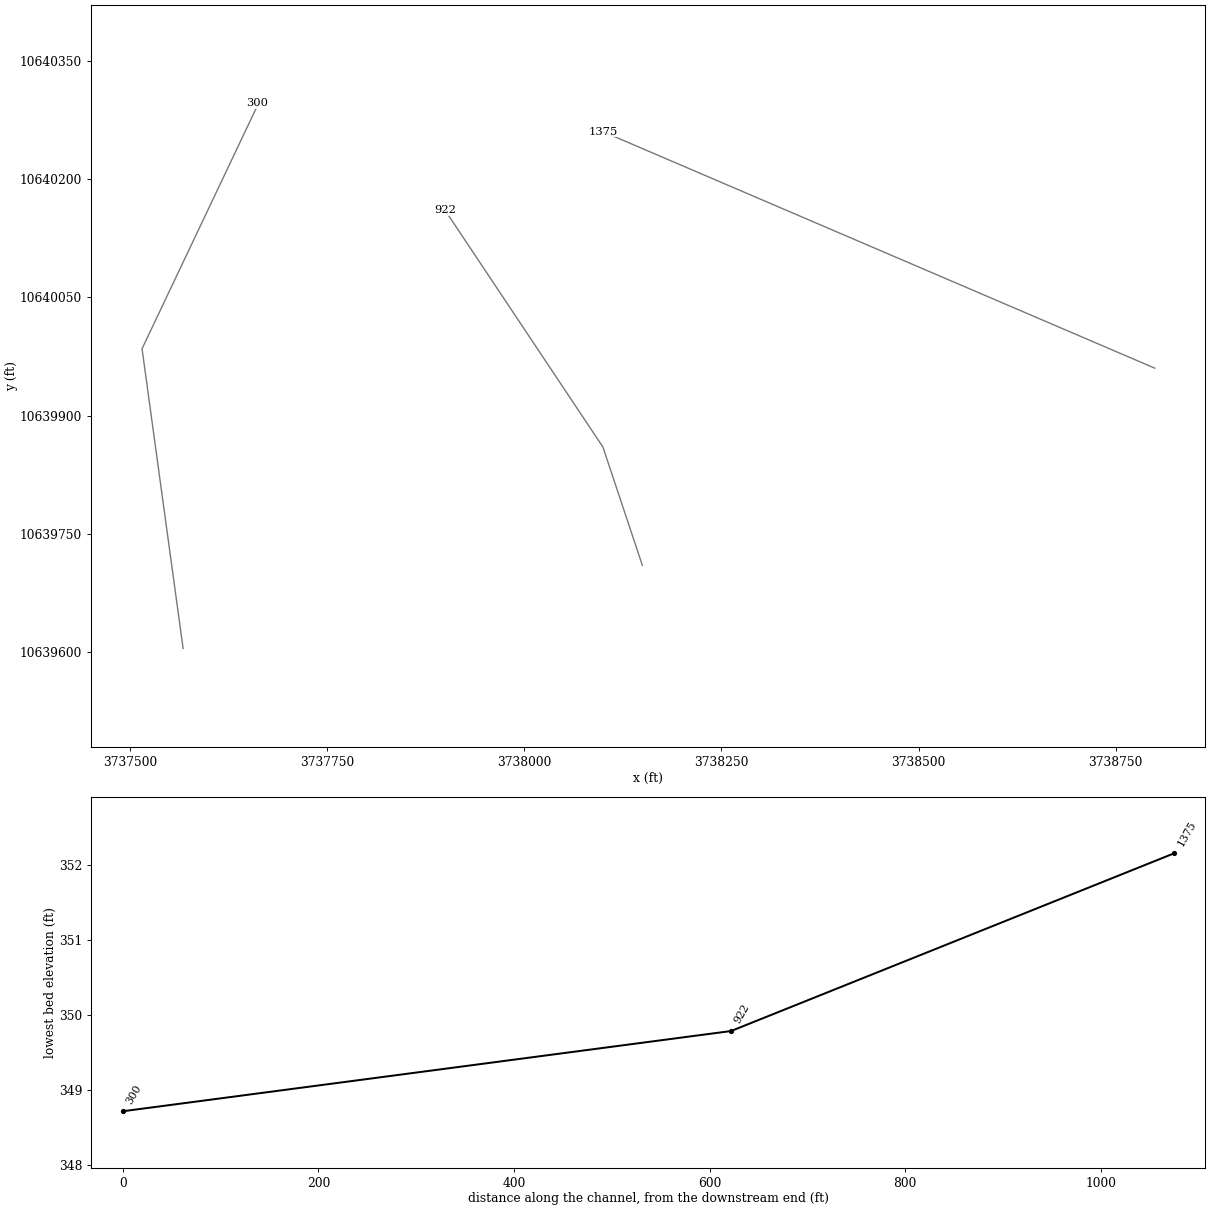
HEC-RAS study UNT 117 IN BOCR.prj: UNT 117 IN BOCR Base Level Engineering

--- UNT 117 IN BOCR.g01 (geometry) --- (continued)

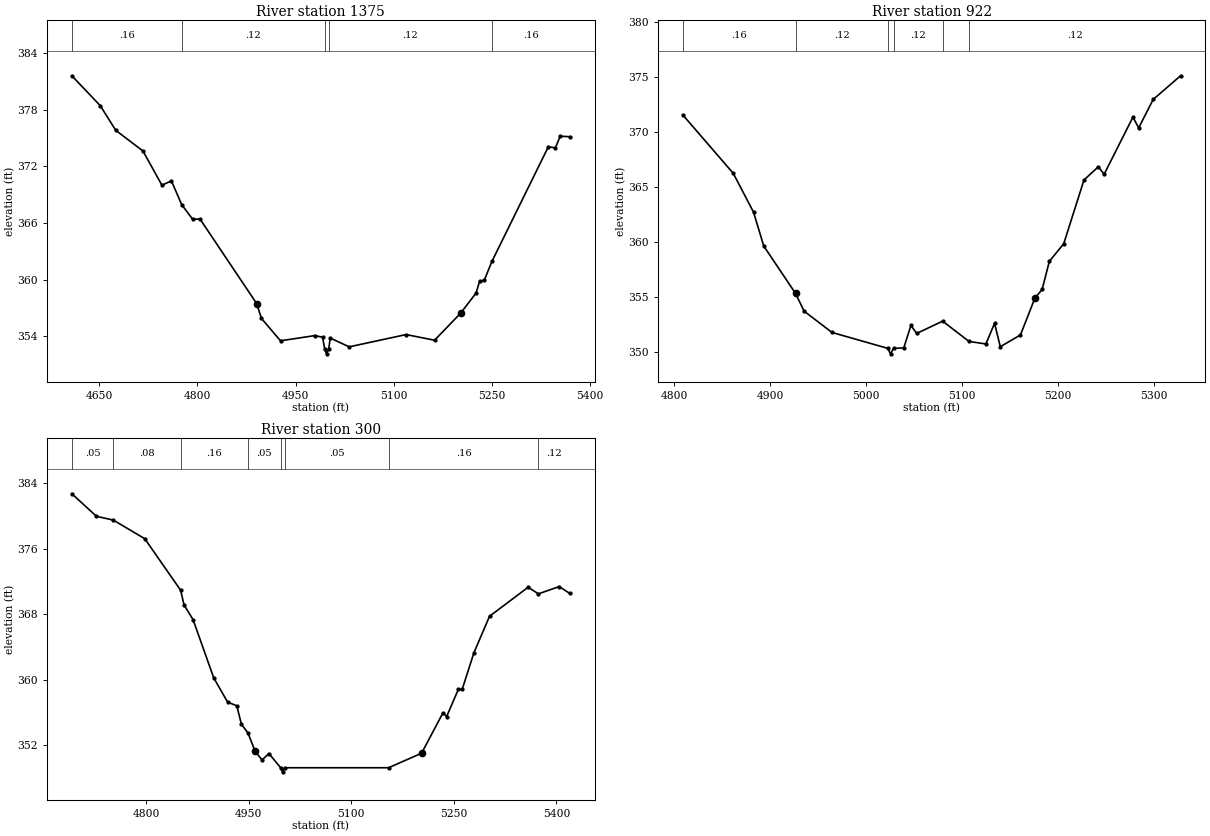
Type RM Length L Ch R = 1 ,1375    ,453,453,453
BEGIN DESCRIPTION:
UNT 117 IN BOCR 3.0
END DESCRIPTION:
XS GIS Cut Line= 3
      3738799.63     10639960.18      3738449.61     10640110.19
      3738099.61     10640260.19
#Sta/Elev= 30
  4607.8  381.58  4651.3  378.41  4674.9  375.81  4716.6  373.62  4745.6     370
  4760.1  370.46  4775.9  367.94  4792.8  366.38  4803.7  366.44  4890.7  357.46
  4897.9   355.9    4927  353.54  4979.5  354.09  4991.3  353.92  4994.7  352.66
  4997.4  352.16  5000.7  352.66  5003.1  353.83  5032.1   352.9  5119.2   354.2
  5162.7   353.6  5202.6  356.46  5226.2  358.59  5231.6  359.83  5238.8  359.95
  5250.4  361.93  5336.8  374.07  5347.6  373.95  5354.9  375.19  5369.4  375.13
#Mann= 5 ,-1 , 0
  4607.8     .16       0  4775.9     .12       0  4994.7     .07       0
  5000.7     .12       0  5250.4     .16       0
Bank Sta=4890.7,5202.6
XS Rating Curve= 0 ,0
Exp/Cntr=0.3,0.1

Type RM Length L Ch R = 1 ,922     ,622,622,622
BEGIN DESCRIPTION:
UNT 117 IN BOCR 2.0
END DESCRIPTION:
XS GIS Cut Line= 3
      3738149.62     10639710.15      3738099.61     10639860.19
      3737899.61     10640160.18
#Sta/Elev= 30
  4809.1  371.58  4861.8  366.24  4882.9   362.7  4893.5  359.62  4926.6   355.3
  4935.6  353.68  4964.6  351.74  5022.8  350.29  5025.6  349.79  5028.8  350.29
  5039.4  350.33  5046.9  352.38  5052.9  351.65  5079.9  352.77  5107.4  350.92
    5125  350.69    5134  352.57    5140  350.44    5161  351.51  5176.1  354.88
  5183.6  355.66  5191.1  358.22  5206.1  359.83  5227.2  365.64  5242.2  366.85
  5248.2  366.16  5278.2  371.37  5284.2  370.39  5299.3  372.98  5327.8  375.14
#Mann= 6 ,-1 , 0
  4809.1     .16       0  4926.6     .12       0  5022.8     .07       0
  5028.8     .12       0  5079.9     .16       0  5107.4     .12       0
Bank Sta=4926.6,5176.1
XS Rating Curve= 0 ,0
Exp/Cntr=0.3,0.1

Type RM Length L Ch R = 1 ,300     ,0,0,0
BEGIN DESCRIPTION:
UNT 117 IN BOCR 1.0
END DESCRIPTION:
XS GIS Cut Line= 4
      3737567.13     10639604.62      3737515.05     10639984.81
      3737660.88      10640292.1      3737660.88     10640296.22
#Sta/Elev= 30
  4691.4   382.7  4727.3  379.95  4752.1  379.48    4798  377.21  4850.5  370.91
  4855.4  369.12  4868.6  367.33  4898.9   360.2  4919.1  357.25  4932.6  356.79
  4939.3  354.55    4949  353.46  4959.5  351.21  4969.5  350.17  4979.6  350.96
  4996.7  349.22  4999.5  348.72  5002.7  349.22  5154.6  349.22  5202.9     351
    5234  355.91  5239.5  355.48  5256.7  358.82  5262.2   358.8  5279.4  363.27
  5302.2  367.73  5358.7  371.28  5373.7  370.47  5404.1  371.36  5419.4  370.53
#Mann= 8 ,-1 , 0
  4691.4     .05       0  4752.1     .08       0  4850.5     .16       0
    4949     .05       0  4996.7    .033       0  5002.7     .05       0
  5154.6     .16       0  5373.7     .12       0
Bank Sta=4959.5,5202.9
XS Rating Curve= 0 ,0
Exp/Cntr=0.3,0.1

Chan Stop Cuts=-1
Use User Specified Reach Order=0
Composite Channel Slope=5