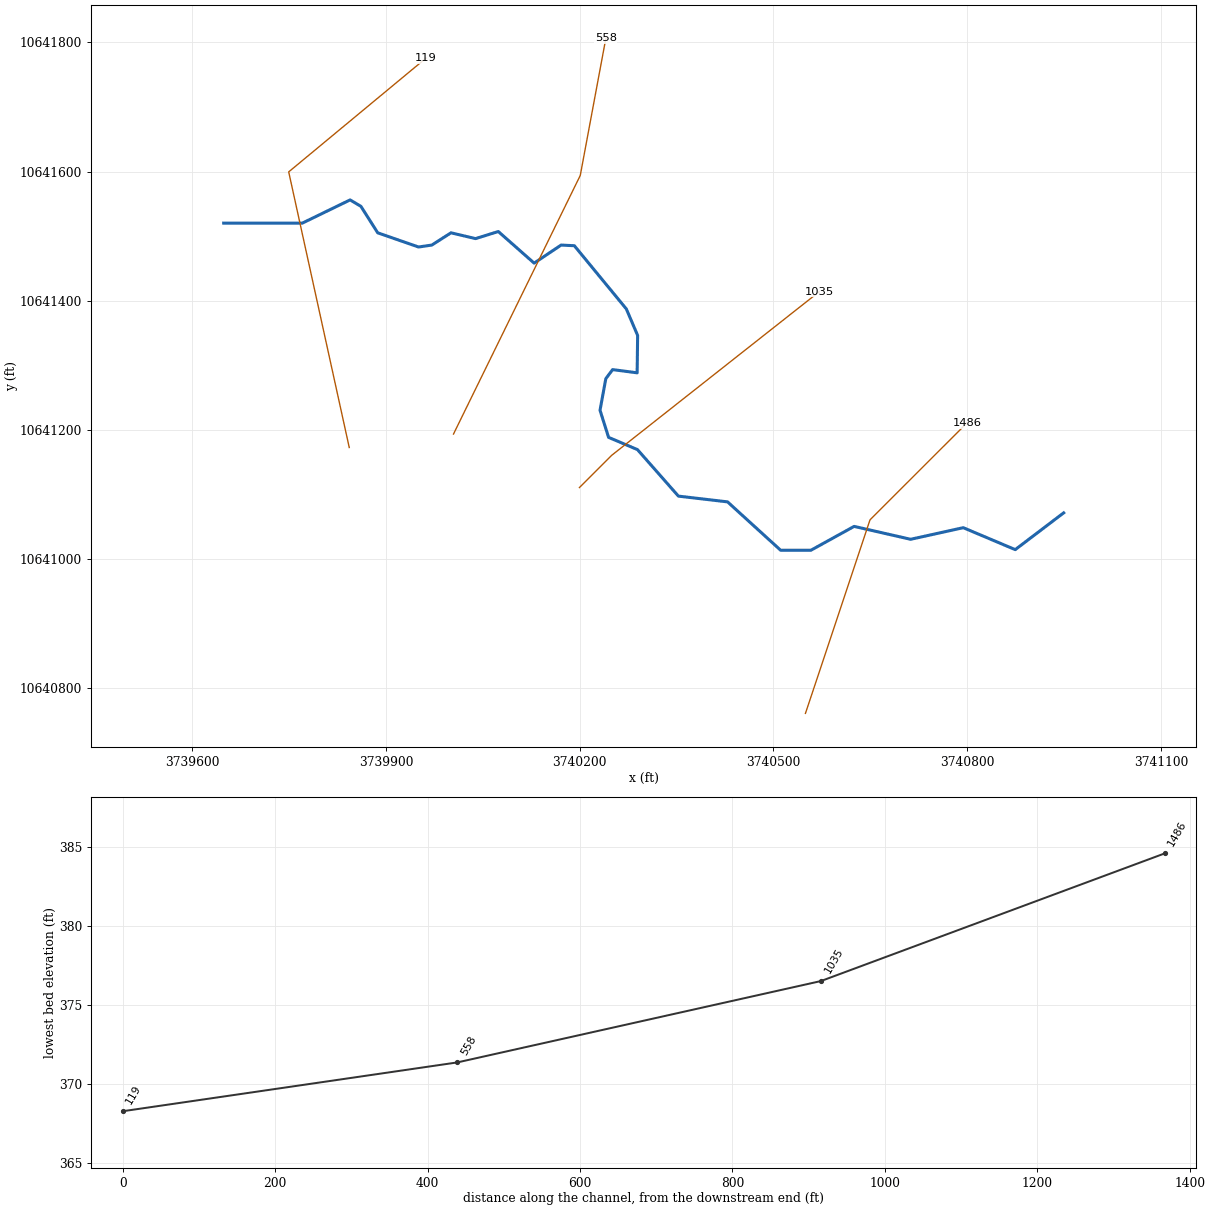
--- UNT 118 IN BOCR.prj (project) ---

Proj Title=UNT 118 IN BOCR Base Level Engineering
Current Plan=p01
Default Exp/Contr=0.3,0.1
English Units
Geom File=g01
Flow File=f01
Plan File=p01
BEGIN DESCRIPTION:
UNT 118 IN BOCR
END DESCRIPTION:

--- UNT 118 IN BOCR.p01 (plan) ---

Plan Title=Multiple Run
Short Identifier=Multiple
Geom File=g01
Flow File=f01
Subcritical Flow
K Sum by GR= 0
Std Step Tol= 0.01
Critical Tol= 0.01
Num of Std Step Trials= 20
Max Error Tol= 0.3
Flow Tol Ratio= 0.001
Split Flow NTrial= 30
Split Flow Tol= 0.02
Split Flow Ratio= 0.02
Log Output Level= 0
Friction Slope Method= 1
Unsteady Friction Slope Method= 2
Unsteady Bridges Friction Slope Method= 1
Parabolic Critical Depth
Global Vel Dist=  1 , 1 , 1
Global Log Level= 0
CheckData=True
Encroach Param= -1, 0, 0, 0
BEGIN DESCRIPTION:
Multiple Run
END DESCRIPTION:

--- UNT 118 IN BOCR.f01 (steady flow) ---

Flow Title=Multiple
Number of Profiles=7
Profile Names=10-year,25-year,50-year,1pct_min,100-year,1pct_plu,500-year
River Rch & RM= UNT 118 IN BOCR,Reach-1,1486
     479     648     789     709     959    1297    1417
Boundary for River Rch & Prof#=UNT 118 IN BOCR,Reach-1,1
Up Type=0
Dn Type=3
Dn Slope=0.005
Boundary for River Rch & Prof#=UNT 118 IN BOCR,Reach-1,2
Up Type=0
Dn Type=3
Dn Slope=0.005
Boundary for River Rch & Prof#=UNT 118 IN BOCR,Reach-1,3
Up Type=0
Dn Type=3
Dn Slope=0.005
Boundary for River Rch & Prof#=UNT 118 IN BOCR,Reach-1,4
Up Type=0
Dn Type=3
Dn Slope=0.005
Boundary for River Rch & Prof#=UNT 118 IN BOCR,Reach-1,5
Up Type=0
Dn Type=3
Dn Slope=0.005
Boundary for River Rch & Prof#=UNT 118 IN BOCR,Reach-1,6
Up Type=0
Dn Type=3
Dn Slope=0.005
Boundary for River Rch & Prof#=UNT 118 IN BOCR,Reach-1,7
Up Type=0
Dn Type=3
Dn Slope=0.005

--- UNT 118 IN BOCR.g01 (geometry) ---

Geom Title=Existing Conditions

River Reach=UNT 118 IN BOCR,Reach-1
Reach XY= 30
      3740949.50     10641071.00      3740874.50     10641014.00
      3740794.00     10641048.00      3740712.50     10641030.00
      3740625.00     10641050.00      3740558.00     10641013.00
      3740511.25     10641013.00      3740429.00     10641088.00
      3740352.88     10641096.92      3740289.50     10641169.00
      3740244.75     10641188.00      3740231.50     10641230.00
      3740240.50     10641279.00      3740251.00     10641293.00
      3740289.00     10641288.00      3740289.75     10641346.00
      3740272.25     10641387.00      3740191.75     10641485.00
      3740171.25     10641486.00      3740129.50     10641458.00
      3740074.00     10641507.00      3740038.75     10641496.00
      3740000.75     10641505.00      3739971.00     10641486.00
      3739950.50     10641483.00      3739887.25     10641505.00
      3739861.25     10641546.00      3739844.50     10641556.00
      3739770.50     10641520.00      3739648.75     10641520.00

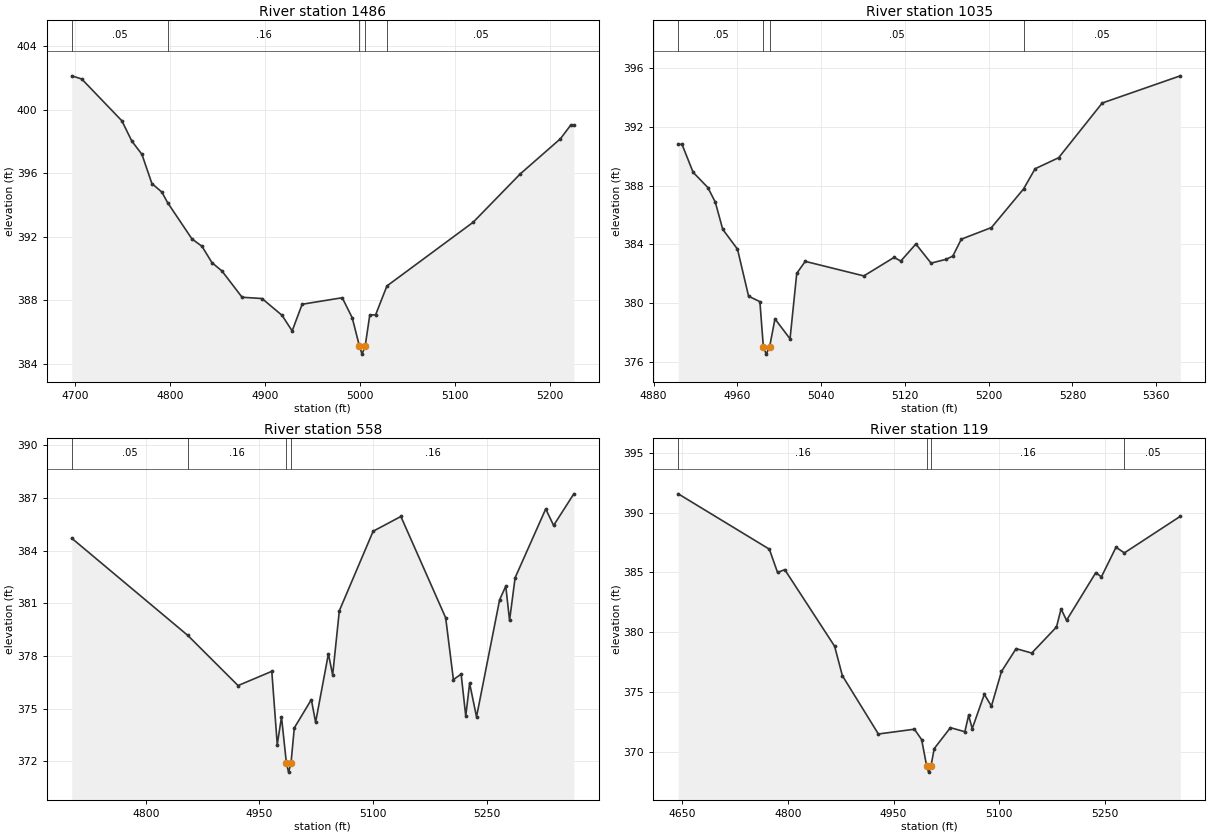
Type RM Length L Ch R = 1,1486,451,451,451
BEGIN DESCRIPTION:
UNT 118 IN BOCR 3.0
END DESCRIPTION:
XS GIS Cut Line= 3
      3740549.62     10640760.22      3740649.61     10641060.19
      3740799.59     10641210.17
#Sta/Elev= 30
  4696.5  402.13  4707.0  401.93  4749.2  399.30  4759.7  398.02  4770.3  397.19
  4780.8  395.35  4791.3  394.81  4797.4  394.14  4823.0  391.86  4833.5  391.40
  4844.0  390.37  4854.6  389.84  4875.7  388.19  4896.7  388.11  4917.8  387.05
  4928.4  386.07  4938.9  387.75  4981.1  388.16  4991.6  386.90  4999.2  385.11
  5001.9  384.61  5005.2  385.11  5010.1  387.08  5016.2  387.08  5028.1  388.90
  5118.8  392.91  5168.3  395.95  5210.7  398.17  5221.3  399.01  5224.8  399.01
#Mann=5,-1,0
  4696.5    0.05       0  4797.4    0.16       0  4999.2    0.07       0
  5005.2    0.16       0  5028.1    0.05       0
Bank Sta=4999.2,5005.2
Exp/Cntr=0.3,0.1

Type RM Length L Ch R = 1,1035,477,477,477
BEGIN DESCRIPTION:
UNT 118 IN BOCR 2.0
END DESCRIPTION:
XS GIS Cut Line= 3
      3740199.59     10641110.17      3740249.61     10641160.19
      3740570.59     10641413.45
#Sta/Elev= 30
  4903.5  390.80  4907.1  390.80  4917.7  388.90  4931.8  387.86  4938.9  386.87
  4946.0  385.02  4960.1  383.67  4970.7  380.47  4981.5  380.10  4984.8  377.03
  4987.6  376.53  4990.8  377.03  4995.9  378.93  5010.3  377.57  5016.7  382.02
  5024.8  382.84  5080.8  381.85  5109.7  383.11  5116.1  382.86  5130.5  384.02
  5145.0  382.72  5159.4  382.98  5165.8  383.20  5173.9  384.35  5202.7  385.14
  5233.4  387.77  5244.4  389.14  5266.9  389.89  5308.5  393.61  5383.1  395.46
#Mann=4,-1,0
  4903.5    0.05       0  4984.8    0.07       0  4990.8    0.05       0
  5233.4    0.05       0
Bank Sta=4984.8,4990.8
Exp/Cntr=0.3,0.1

Type RM Length L Ch R = 1,558,439,439,439
BEGIN DESCRIPTION:
Mapping XS 752b8f34
END DESCRIPTION:
XS GIS Cut Line= 3
      3740004.63     10641193.15      3740200.93     10641593.93
      3740240.53     10641806.40
#Sta/Elev= 30
  4702.4  384.70  4855.4  379.17  4921.8  376.31  4966.3  377.12  4973.5  372.95
  4979.1  374.52  4985.6  371.88  4988.4  371.38  4991.6  371.88  4996.0  373.90
  5018.5  375.51  5024.1  374.22  5041.0  378.12  5046.6  376.91  5055.4  380.57
  5100.0  385.10  5136.6  385.94  5195.7  380.17  5205.9  376.65  5216.1  376.96
  5222.2  374.57  5227.3  376.44  5236.4  374.53  5266.9  381.20  5275.0  381.97
  5280.0  380.02  5287.3  382.45  5327.7  386.37  5338.1  385.43  5364.8  387.23
#Mann=4,-1,0
  4702.4    0.05       0  4855.4    0.16       0  4985.6    0.07       0
  4991.6    0.16       0
Bank Sta=4985.6,4991.6
Exp/Cntr=0.3,0.1

Type RM Length L Ch R = 1,119,0,0,0
BEGIN DESCRIPTION:
UNT 118 IN BOCR 1.0
END DESCRIPTION:
XS GIS Cut Line= 3
      3739843.18     10641172.28      3739749.42     10641599.40
      3739962.19     10641775.84
#Sta/Elev= 30
  4644.0  391.57  4773.5  386.94  4785.2  384.99  4795.4  385.23  4866.3  378.82
  4877.3  376.36  4928.5  371.48  4979.7  371.88  4990.0  371.01  4997.2  368.79
  4999.9  368.29  5003.2  368.79  5007.9  370.26  5030.9  372.01  5051.4  371.67
  5056.8  373.04  5061.9  371.93  5079.1  374.80  5089.2  373.81  5103.5  376.71
  5124.3  378.62  5146.5  378.25  5181.7  380.43  5188.2  381.94  5196.0  380.99
  5237.6  384.98  5245.5  384.62  5266.3  387.10  5278.2  386.63  5357.7  389.69
#Mann=4,-1,0
  4644.0    0.16       0  4997.2    0.07       0  5003.2    0.16       0
  5278.2    0.05       0
Bank Sta=4997.2,5003.2
Exp/Cntr=0.3,0.1

Chan Stop Cuts=-1