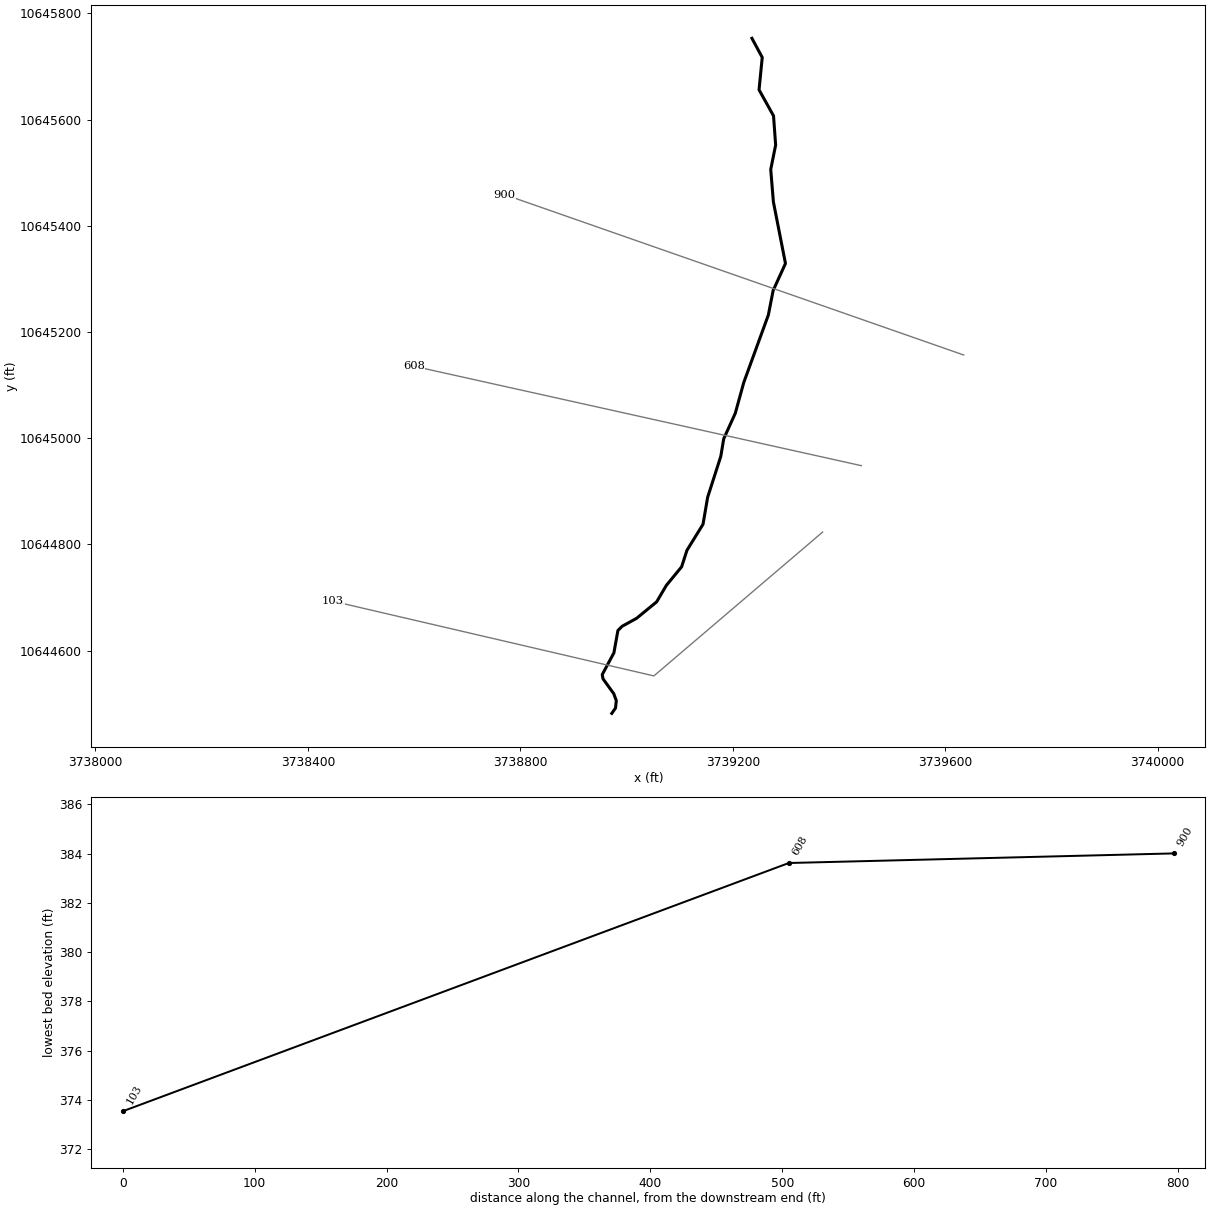
--- UNT 120 IN BOCR.prj (project) ---

Proj Title=UNT 120 IN BOCR Base Level Engineering
Current Plan=p01
Default Exp/Contr=0.3,0.1
English Units
Geom File=g01
Flow File=f01
Plan File=p01
Y Axis Title=Elevation
X Axis Title(PF)=Main Channel Distance
X Axis Title(XS)=Station
BEGIN DESCRIPTION:
UNT 120 IN BOCR
END DESCRIPTION:
DSS Export Rating Curves= 0
DSS Export Rating Curve Sorted= 0
DSS Export Volume Flow Curves= 0
DXF OffsetX= 0
DXF OffsetY= 0
DXF ScaleX= 1
DXF ScaleY= 10

--- UNT 120 IN BOCR.p01 (plan) ---

Plan Title=Multiple Run
Short Identifier=Multiple
Geom File=g01
Flow File=f01
Subcritical Flow
K Sum by GR= 0
Std Step Tol= 0.01
Critical Tol= 0.01
Num of Std Step Trials= 20
Max Error Tol= 0.3
Flow Tol Ratio= 0.001
Split Flow NTrial= 30
Split Flow Tol= 0.02
Split Flow Ratio= 0.02
Log Output Level= 0
Friction Slope Method= 1
Unsteady Friction Slope Method= 2
Unsteady Bridges Friction Slope Method= 1
Parabolic Critical Depth
Global Vel Dist=  1 , 1 , 1
Global Log Level= 0
CheckData=True
Encroach Param= -1, 0, 0, 0
BEGIN DESCRIPTION:
Multiple Run
END DESCRIPTION:

--- UNT 120 IN BOCR.f01 (steady flow) ---

Flow Title=Multiple
Program Version=4.10
Number of Profiles= 7
Profile Names=10-year,25-year,50-year,1pct_min,100-year,1pct_plu,500-year
River Rch & RM=UNT 120 IN BOCR,Reach-1         ,900
     208     263     306     264     357     482     483
Boundary for River Rch & Prof#=UNT 120 IN BOCR,Reach-1         , 1
Up Type= 0
Dn Type= 3
Dn Slope=0.005
Boundary for River Rch & Prof#=UNT 120 IN BOCR,Reach-1         , 2
Up Type= 0
Dn Type= 3
Dn Slope=0.005
Boundary for River Rch & Prof#=UNT 120 IN BOCR,Reach-1         , 3
Up Type= 0
Dn Type= 3
Dn Slope=0.005
Boundary for River Rch & Prof#=UNT 120 IN BOCR,Reach-1         , 4
Up Type= 0
Dn Type= 3
Dn Slope=0.005
Boundary for River Rch & Prof#=UNT 120 IN BOCR,Reach-1         , 5
Up Type= 0
Dn Type= 3
Dn Slope=0.005
Boundary for River Rch & Prof#=UNT 120 IN BOCR,Reach-1         , 6
Up Type= 0
Dn Type= 3
Dn Slope=0.005
Boundary for River Rch & Prof#=UNT 120 IN BOCR,Reach-1         , 7
Up Type= 0
Dn Type= 3
Dn Slope=0.005
DSS Import GetInterval= 0
DSS Import GetPeak= 0
DSS Import FillOption= 0

--- UNT 120 IN BOCR.g01 (geometry) ---

Geom Title=Existing Conditions

River Reach=UNT 120 IN BOCR,Reach-1
Reach XY= 30
      3739236.12     10645752.90      3739255.50     10645717.00
      3739249.50     10645656.00      3739276.75     10645607.00
      3739280.75     10645552.00      3739271.50     10645506.00
      3739276.50     10645445.00      3739299.25     10645329.00
      3739276.00     10645278.00      3739267.00     10645232.00
      3739220.75     10645105.00      3739204.75     10645047.00
      3739183.00     10644999.00      3739177.50     10644966.00
      3739152.75     10644889.00      3739144.00     10644838.00
      3739113.75     10644789.00      3739103.75     10644758.00
      3739075.00     10644723.00      3739056.75     10644692.00
      3739019.00     10644661.00      3738991.75     10644646.00
      3738983.75     10644638.00      3738976.25     10644596.00
      3738954.25     10644555.00      3738955.75     10644547.00
      3738976.00     10644519.00      3738980.75     10644506.00
      3738979.25     10644492.00      3738972.25     10644482.00

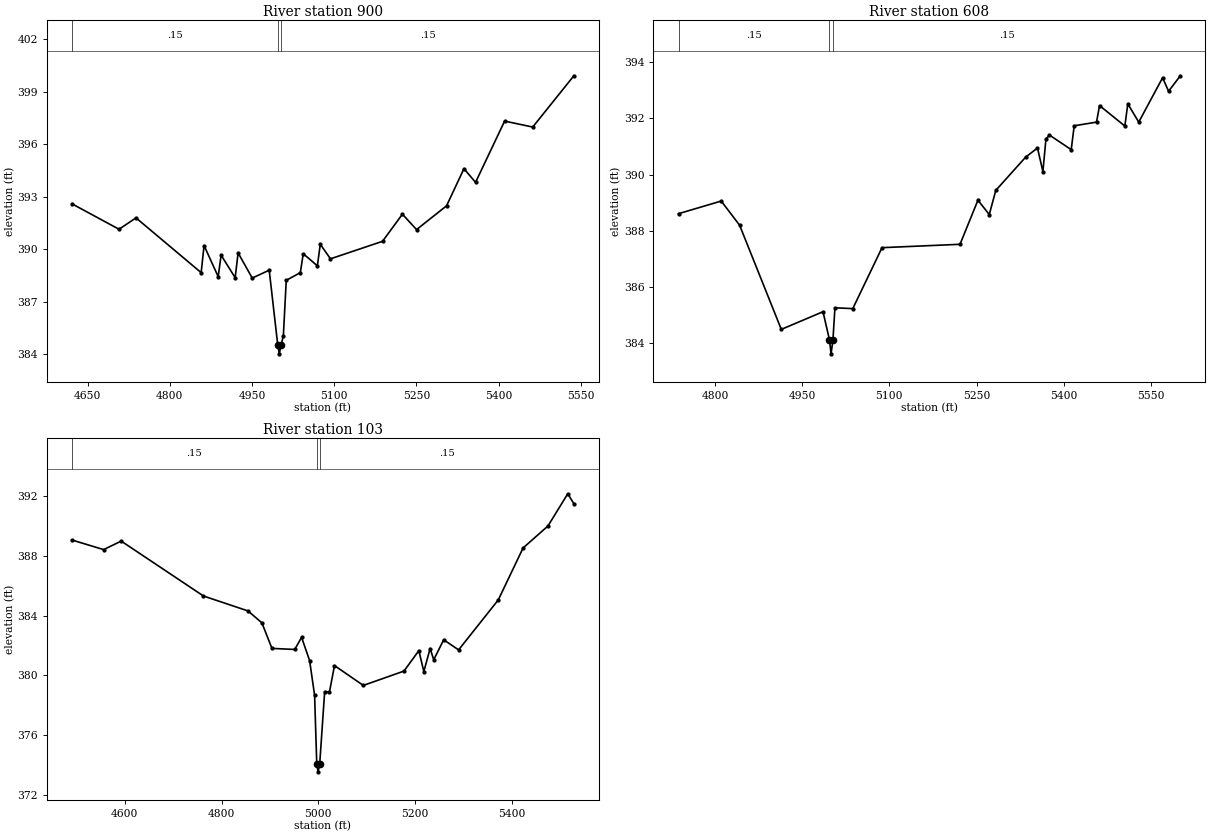
Type RM Length L Ch R = 1,900,292,292,292
BEGIN DESCRIPTION:
UNT 120 IN BOCR 3.0
END DESCRIPTION:
XS GIS Cut Line= 2
      3739634.82     10645156.69      3738770.27     10645458.76
#Sta/Elev= 30
  4621.6  392.58  4707.3  391.13  4738.3  391.78  4857.2  388.65  4862.5  390.20
  4888.3  388.42  4893.6  389.65  4919.3  388.36  4924.6  389.78  4950.4  388.34
  4981.4  388.79  4997.0  384.51  4999.8  384.01  5003.0  384.51  5007.2  385.03
  5012.5  388.21  5038.2  388.65  5043.5  389.73  5069.3  389.04  5074.6  390.27
  5093.2  389.44  5188.2  390.44  5224.5  391.99  5250.3  391.11  5305.1  392.47
  5336.8  394.59  5358.0  393.81  5411.0  397.31  5462.3  396.97  5537.4  399.90
#Mann=3,-1,0
  4621.6    0.15       0  4997.0    0.05       0  5003.0    0.15       0
Bank Sta=4997,5003
Exp/Cntr=0.3,0.1

Type RM Length L Ch R = 1,608,505,505,505
BEGIN DESCRIPTION:
UNT 120 IN BOCR 2.0
END DESCRIPTION:
XS GIS Cut Line= 2
      3739442.11     10644948.36      3738599.85     10645135.53
#Sta/Elev= 30
  4737.5  388.61  4810.9  389.06  4842.5  388.20  4914.2  384.49  4985.9  385.12
  4997.0  384.12  4999.8  383.62  5003.0  384.12  5006.4  385.26  5037.1  385.23
  5087.4  387.40  5221.5  387.52  5252.3  389.09  5271.8  388.58  5283.0  389.44
  5334.2  390.62  5354.7  390.95  5364.0  390.11  5369.2  391.26  5375.2  391.41
  5412.7  390.89  5417.8  391.74  5456.2  391.87  5461.4  392.46  5504.9  391.73
  5510.0  392.52  5528.8  391.87  5569.8  393.45  5580.1  392.97  5600.3  393.52
#Mann=3,-1,0
  4737.5    0.15       0  4997.0    0.05       0  5003.0    0.15       0
Bank Sta=4997,5003
Exp/Cntr=0.3,0.1

Type RM Length L Ch R = 1,103,0,0,0
BEGIN DESCRIPTION:
UNT 120 IN BOCR 1.0
END DESCRIPTION:
XS GIS Cut Line= 3
      3739369.24     10644823.38      3739051.51     10644552.52
      3738447.37     10644693.14
#Sta/Elev= 30
  4490.9  389.07  4556.2  388.43  4592.5  389.00  4762.7  385.32  4854.9  384.32
  4883.5  383.52  4904.3  381.81  4951.4  381.74  4965.6  382.55  4982.2  380.99
  4992.5  378.67  4997.0  374.04  4999.8  373.54  5003.0  374.04  5013.3  378.91
  5023.3  378.90  5033.6  380.66  5093.3  379.33  5177.3  380.29  5208.1  381.66
  5218.4  380.26  5231.4  381.80  5238.9  381.05  5259.5  382.39  5290.3  381.71
  5372.4  385.06  5423.7  388.54  5475.1  390.01  5516.1  392.17  5528.7  391.51
#Mann=3,-1,0
  4490.9    0.15       0  4997.0    0.05       0  5003.0    0.15       0
Bank Sta=4997,5003
Exp/Cntr=0.3,0.1

Chan Stop Cuts=-1