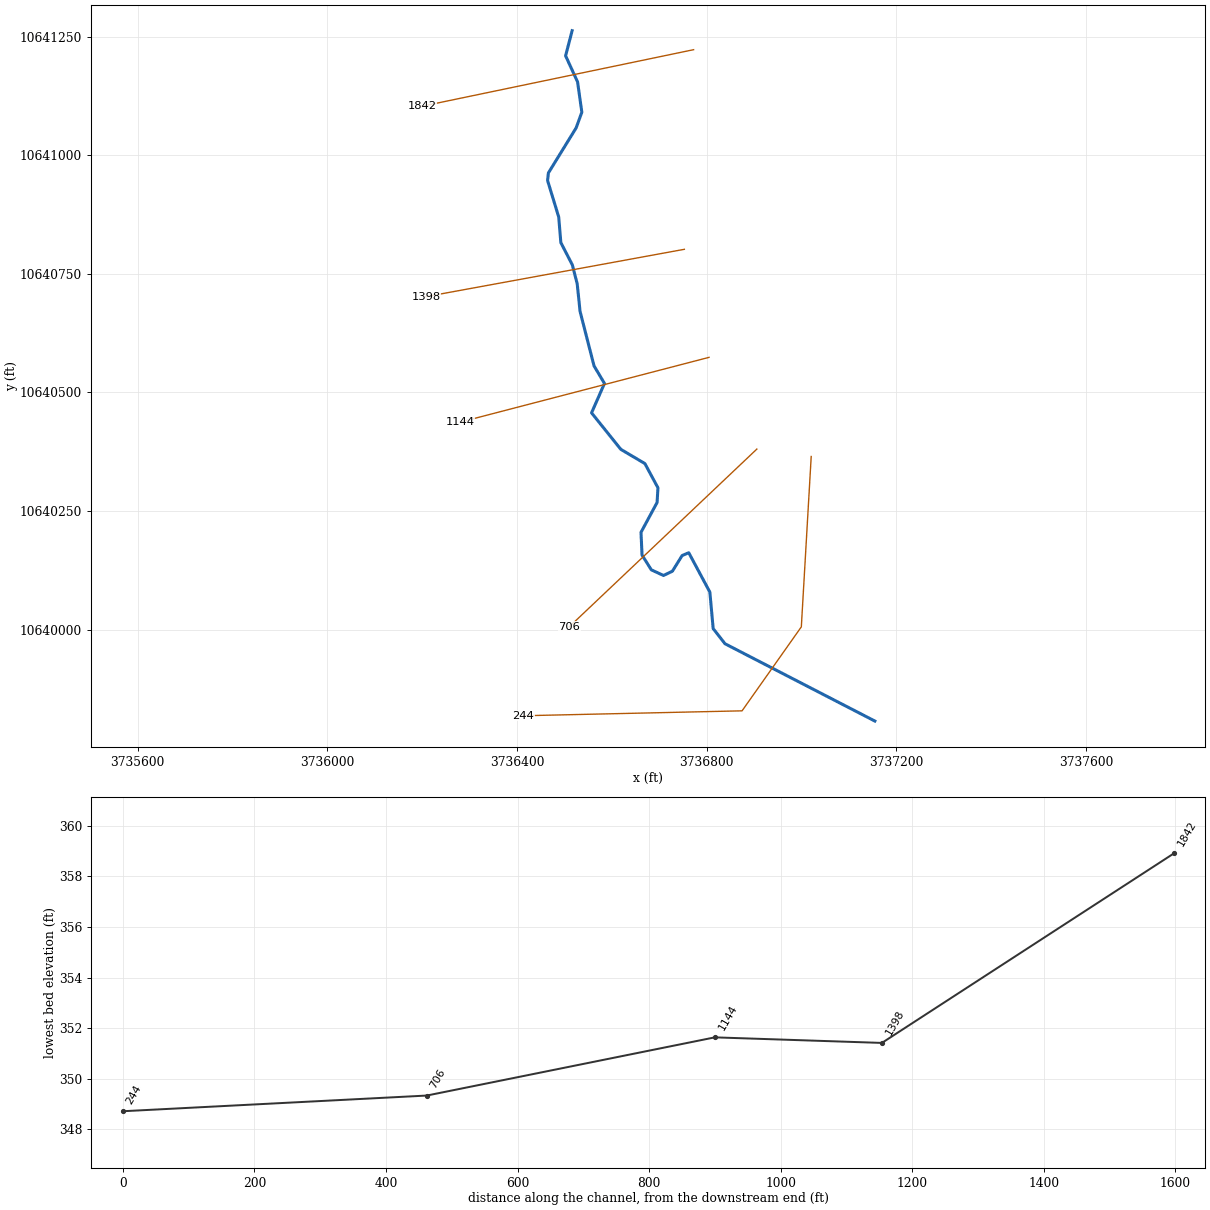
--- UNT 121 IN BOCR.prj (project) ---

Proj Title=UNT 121 IN BOCR Base Level Engineering
Current Plan=p01
Default Exp/Contr=0.3,0.1
English Units
Geom File=g01
Flow File=f01
Plan File=p01
Y Axis Title=Elevation
X Axis Title(PF)=Main Channel Distance
X Axis Title(XS)=Station
BEGIN DESCRIPTION:
UNT 121 IN BOCR
END DESCRIPTION:
DSS Export Rating Curves= 0
DSS Export Rating Curve Sorted= 0
DSS Export Volume Flow Curves= 0
DXF OffsetX= 0
DXF OffsetY= 0
DXF ScaleX= 1
DXF ScaleY= 10

--- UNT 121 IN BOCR.p01 (plan) ---

Plan Title=Multiple Run
Short Identifier=Multiple
Geom File=g01
Flow File=f01
Subcritical Flow
K Sum by GR= 0
Std Step Tol= 0.01
Critical Tol= 0.01
Num of Std Step Trials= 20
Max Error Tol= 0.3
Flow Tol Ratio= 0.001
Split Flow NTrial= 30
Split Flow Tol= 0.02
Split Flow Ratio= 0.02
Log Output Level= 0
Friction Slope Method= 1
Unsteady Friction Slope Method= 2
Unsteady Bridges Friction Slope Method= 1
Parabolic Critical Depth
Global Vel Dist=  1 , 1 , 1
Global Log Level= 0
CheckData=True
Encroach Param= -1, 0, 0, 0
BEGIN DESCRIPTION:
Multiple Run
END DESCRIPTION:

--- UNT 121 IN BOCR.f01 (steady flow) ---

Flow Title=Multiple
Program Version=4.10
Number of Profiles= 7
Profile Names=10-year,25-year,50-year,1pct_min,100-year,1pct_plu,500-year
River Rch & RM=UNT 121 IN BOCR,Reach-1         ,1842
     325     422     499     435     588     795     819
Boundary for River Rch & Prof#=UNT 121 IN BOCR,Reach-1         , 1
Up Type= 0
Dn Type= 3
Dn Slope=0.005
Boundary for River Rch & Prof#=UNT 121 IN BOCR,Reach-1         , 2
Up Type= 0
Dn Type= 3
Dn Slope=0.005
Boundary for River Rch & Prof#=UNT 121 IN BOCR,Reach-1         , 3
Up Type= 0
Dn Type= 3
Dn Slope=0.005
Boundary for River Rch & Prof#=UNT 121 IN BOCR,Reach-1         , 4
Up Type= 0
Dn Type= 3
Dn Slope=0.005
Boundary for River Rch & Prof#=UNT 121 IN BOCR,Reach-1         , 5
Up Type= 0
Dn Type= 3
Dn Slope=0.005
Boundary for River Rch & Prof#=UNT 121 IN BOCR,Reach-1         , 6
Up Type= 0
Dn Type= 3
Dn Slope=0.005
Boundary for River Rch & Prof#=UNT 121 IN BOCR,Reach-1         , 7
Up Type= 0
Dn Type= 3
Dn Slope=0.005
DSS Import GetInterval= 0
DSS Import GetPeak= 0
DSS Import FillOption= 0

--- UNT 121 IN BOCR.g01 (geometry) ---

Geom Title=Existing Conditions

River Reach=UNT 121 IN BOCR,Reach-1
Reach XY= 30
      3736516.06     10641263.04      3736502.25     10641210.00
      3736527.50     10641155.00      3736536.50     10641091.00
      3736524.50     10641058.00      3736466.00     10640963.00
      3736464.25     10640947.00      3736487.75     10640870.00
      3736492.25     10640816.00      3736516.50     10640769.00
      3736526.75     10640729.00      3736532.75     10640671.00
      3736562.25     10640556.00      3736584.25     10640519.00
      3736557.00     10640457.00      3736618.75     10640380.00
      3736669.50     10640350.00      3736697.00     10640299.00
      3736695.25     10640268.00      3736661.25     10640205.00
      3736663.50     10640157.00      3736683.00     10640126.00
      3736708.75     10640114.00      3736727.50     10640123.00
      3736748.00     10640156.00      3736762.00     10640162.00
      3736806.50     10640079.00      3736813.50     10640002.00
      3736838.50     10639970.00      3737154.50     10639807.00

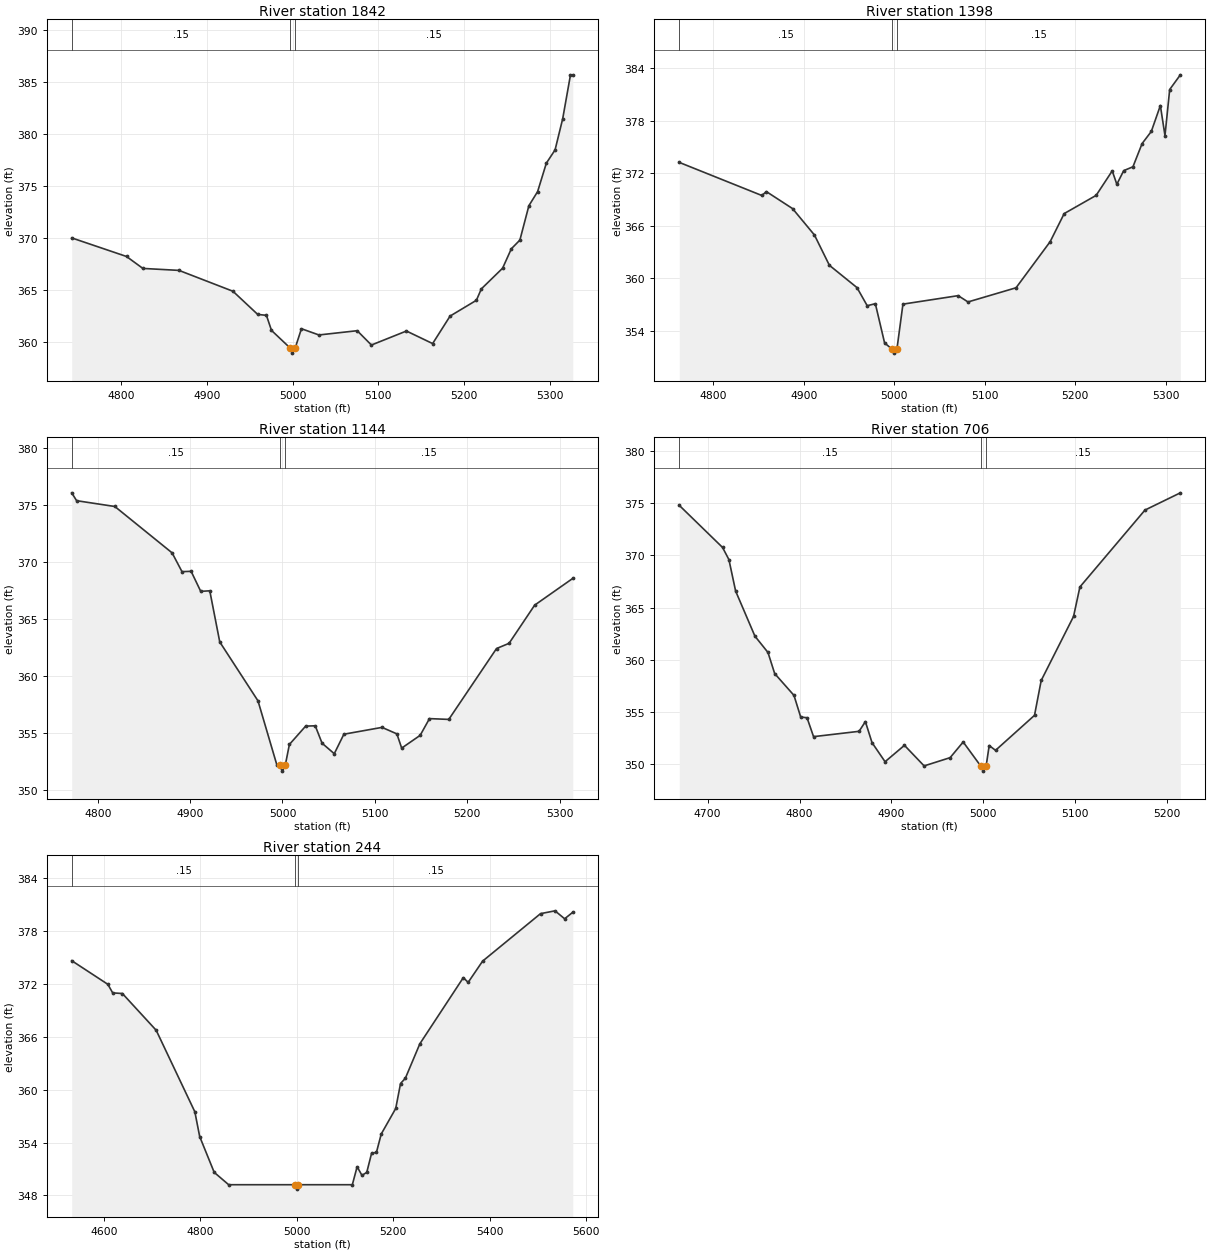
Type RM Length L Ch R = 1,1842,444,444,444
BEGIN DESCRIPTION:
UNT 121 IN BOCR 4.0
END DESCRIPTION:
XS GIS Cut Line= 2
      3736772.25     10641222.92      3736199.35     10641103.57
#Sta/Elev= 30
  4742.0  370.01  4806.0  368.22  4825.1  367.07  4867.3  366.88  4930.3  364.87
  4959.2  362.64  4969.4  362.55  4975.3  361.10  4997.0  359.41  4999.8  358.91
  5003.0  359.41  5010.3  361.26  5030.7  360.66  5075.4  361.07  5092.0  359.69
  5132.9  361.04  5163.5  359.83  5183.9  362.48  5214.6  364.00  5220.4  365.10
  5245.2  367.09  5255.4  368.96  5265.4  369.80  5275.9  373.11  5286.1  374.47
  5296.3  377.21  5306.5  378.49  5315.4  381.49  5324.5  385.72  5327.2  385.72
#Mann=3,-1,0
  4742.0    0.15       0  4997.0    0.05       0  5003.0    0.15       0
Bank Sta=4997,5003
Exp/Cntr=0.3,0.1

Type RM Length L Ch R = 1,1398,254,254,254
BEGIN DESCRIPTION:
UNT 121 IN BOCR 3.0
END DESCRIPTION:
XS GIS Cut Line= 2
      3736752.75     10640801.92      3736208.02     10640702.09
#Sta/Elev= 30
  4762.4  373.22  4853.6  369.44  4858.7  369.88  4887.6  367.94  4911.8  364.92
  4928.3  361.46  4958.8  358.91  4970.1  356.84  4979.1  357.07  4989.3  352.59
  4997.0  351.92  4999.8  351.42  5003.0  351.92  5009.6  357.02  5070.6  357.99
  5081.5  357.27  5134.6  358.89  5172.3  364.16  5187.8  367.37  5223.1  369.45
  5240.9  372.25  5246.0  370.72  5253.6  372.28  5263.8  372.72  5273.9  375.37
  5284.1  376.76  5294.1  379.72  5299.2  376.28  5304.4  381.55  5316.2  383.23
#Mann=3,-1,0
  4762.4    0.15       0  4997.0    0.05       0  5003.0    0.15       0
Bank Sta=4997,5003
Exp/Cntr=0.3,0.1

Type RM Length L Ch R = 1,1144,438,438,438
BEGIN DESCRIPTION:
UNT 121 IN BOCR 2.0
END DESCRIPTION:
XS GIS Cut Line= 2
      3736804.78     10640574.04      3736279.68     10640437.34
#Sta/Elev= 30
  4771.8  376.07  4777.1  375.38  4818.5  374.87  4880.5  370.80  4891.2  369.15
  4901.1  369.18  4911.5  367.42  4921.3  367.47  4932.1  362.98  4973.5  357.81
  4994.1  352.14  4997.0  352.14  4999.8  351.64  5003.0  352.14  5007.5  353.98
  5025.1  355.59  5035.5  355.62  5042.9  354.09  5056.1  353.17  5066.5  354.88
  5107.8  355.48  5123.9  354.91  5129.1  353.66  5149.1  354.78  5159.2  356.25
  5180.1  356.18  5231.8  362.40  5245.4  362.86  5273.1  366.21  5314.4  368.56
#Mann=3,-1,0
  4771.8    0.15       0  4997.0    0.05       0  5003.0    0.15       0
Bank Sta=4997,5003
Exp/Cntr=0.3,0.1

Type RM Length L Ch R = 1,706,462,462,462
BEGIN DESCRIPTION:
Mapping XS 263d25d8
END DESCRIPTION:
XS GIS Cut Line= 2
      3736905.64     10640380.61      3736509.85     10640005.66
#Sta/Elev= 30
  4669.1  374.78  4716.2  370.75  4723.1  369.59  4730.4  366.58  4751.4  362.26
  4765.6  360.70  4772.9  358.68  4793.9  356.59  4801.2  354.52  4808.1  354.45
  4815.2  352.64  4864.7  353.15  4871.6  354.08  4878.8  352.07  4893.0  350.24
  4914.1  351.81  4935.5  349.84  4963.8  350.63  4978.0  352.13  4997.0  349.84
  4999.8  349.34  5003.0  349.84  5006.3  351.79  5013.2  351.33  5055.6  354.68
  5062.9  358.02  5098.1  364.15  5105.0  366.97  5175.8  374.33  5214.3  375.98
#Mann=3,-1,0
  4669.1    0.15       0  4997.0    0.05       0  5003.0    0.15       0
Bank Sta=4997,5003
Exp/Cntr=0.3,0.1

Type RM Length L Ch R = 1,244,0,0,0
BEGIN DESCRIPTION:
UNT 121 IN BOCR 1.0
END DESCRIPTION:
XS GIS Cut Line= 4
      3737020.25     10640364.97      3736999.42     10640005.65
      3736874.42     10639828.56      3736412.73     10639818.19
#Sta/Elev= 30
  4533.6  374.61  4608.5  371.93  4618.5  370.96  4638.6  370.89  4708.7  366.72
  4788.8  357.48  4798.8  354.68  4828.9  350.62  4858.9  349.22  4997.0  349.22
  4999.8  348.72  5003.0  349.22  5115.2  349.22  5125.1  351.26  5135.1  350.28
  5145.1  350.62  5155.1  352.79  5165.1  352.88  5175.1  354.97  5205.1  357.86
  5215.1  360.69  5225.1  361.29  5255.1  365.19  5345.2  372.69  5355.2  372.15
  5385.2  374.56  5505.2  379.94  5535.2  380.26  5555.2  379.36  5572.1  380.10
#Mann=3,-1,0
  4533.6    0.15       0  4997.0    0.05       0  5003.0    0.15       0
Bank Sta=4997,5003
Exp/Cntr=0.3,0.1

Chan Stop Cuts=-1