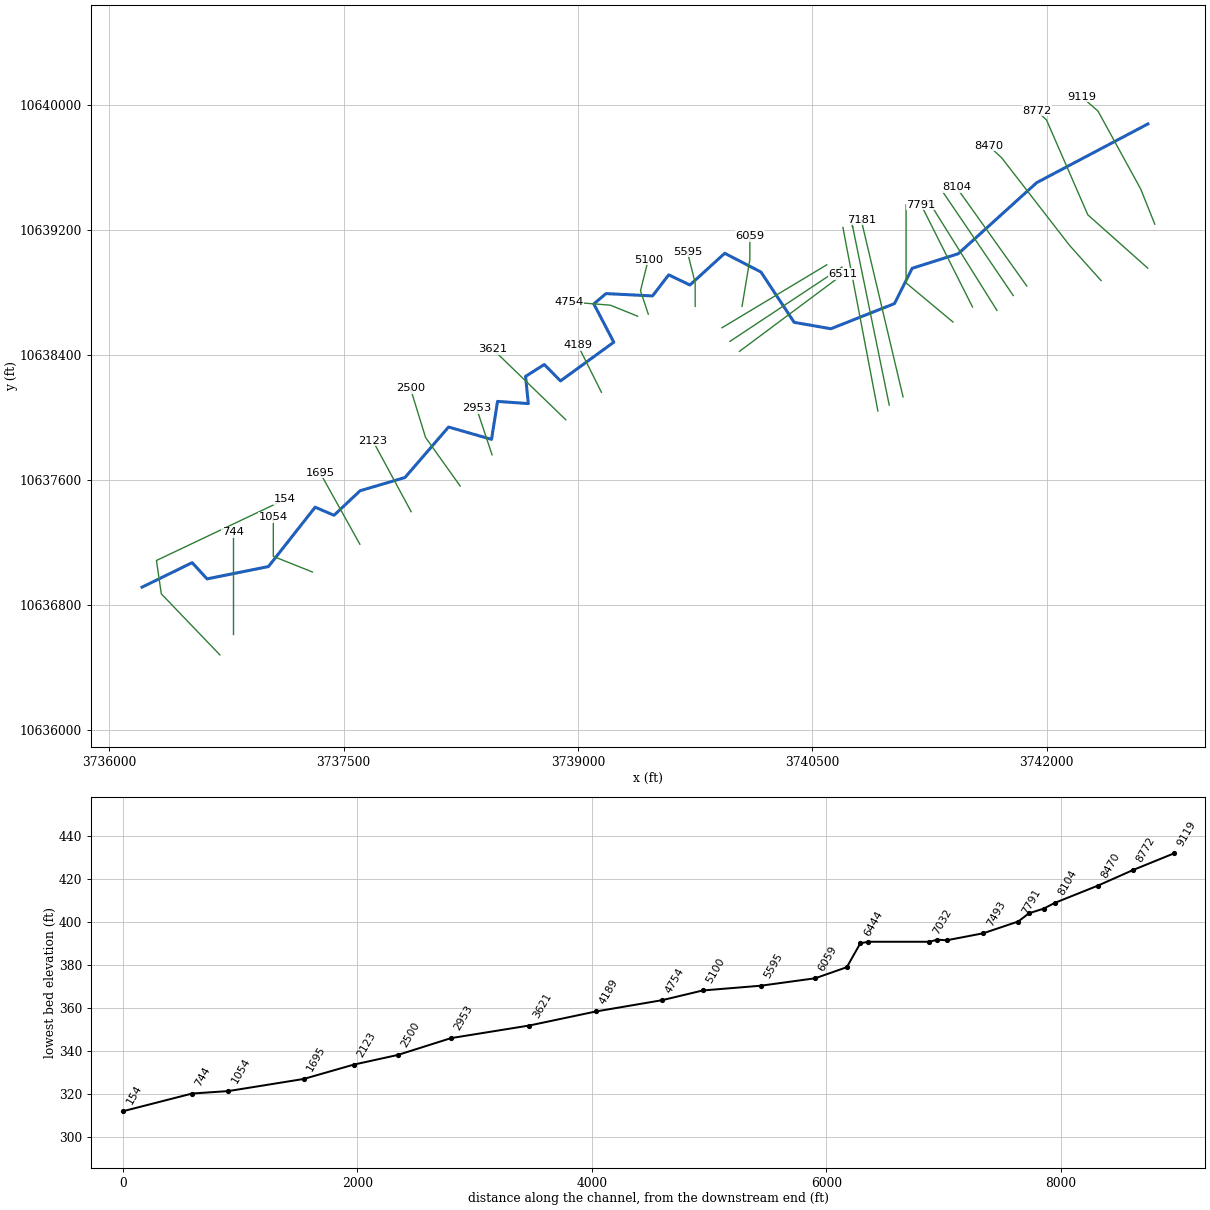
--- UNT 122 IN BOCR.prj (project) ---

Proj Title=UNT 122 IN BOCR Base Level Engineering
Current Plan=p01
Default Exp/Contr=0.3,0.1
English Units
Geom File=g01
Flow File=f01
Plan File=p01
BEGIN DESCRIPTION:
UNT 122 IN BOCR
END DESCRIPTION:

--- UNT 122 IN BOCR.p01 (plan) ---

Plan Title=Multiple Run
Short Identifier=Multiple
Geom File=g01
Flow File=f01
Subcritical Flow
K Sum by GR= 0
Std Step Tol= 0.01
Critical Tol= 0.01
Num of Std Step Trials= 20
Max Error Tol= 0.3
Flow Tol Ratio= 0.001
Split Flow NTrial= 30
Split Flow Tol= 0.02
Split Flow Ratio= 0.02
Log Output Level= 0
Friction Slope Method= 1
Unsteady Friction Slope Method= 2
Unsteady Bridges Friction Slope Method= 1
Parabolic Critical Depth
Global Vel Dist=  1 , 1 , 1
Global Log Level= 0
CheckData=True
Encroach Param= -1, 0, 0, 0
BEGIN DESCRIPTION:
Multiple Run
END DESCRIPTION:

--- UNT 122 IN BOCR.f01 (steady flow) ---

Flow Title=Multiple
Number of Profiles=7
Profile Names=10-year,25-year,50-year,1pct_min,100-year,1pct_plu,500-year
River Rch & RM= UNT 122 IN BOCR,Reach-1,9119
     495     670     815     732     990    1339    1462
Boundary for River Rch & Prof#=UNT 122 IN BOCR,Reach-1,1
Up Type=0
Dn Type=3
Dn Slope=0.005
Boundary for River Rch & Prof#=UNT 122 IN BOCR,Reach-1,2
Up Type=0
Dn Type=3
Dn Slope=0.005
Boundary for River Rch & Prof#=UNT 122 IN BOCR,Reach-1,3
Up Type=0
Dn Type=3
Dn Slope=0.005
Boundary for River Rch & Prof#=UNT 122 IN BOCR,Reach-1,4
Up Type=0
Dn Type=3
Dn Slope=0.005
Boundary for River Rch & Prof#=UNT 122 IN BOCR,Reach-1,5
Up Type=0
Dn Type=3
Dn Slope=0.005
Boundary for River Rch & Prof#=UNT 122 IN BOCR,Reach-1,6
Up Type=0
Dn Type=3
Dn Slope=0.005
Boundary for River Rch & Prof#=UNT 122 IN BOCR,Reach-1,7
Up Type=0
Dn Type=3
Dn Slope=0.005

--- UNT 122 IN BOCR.g01 (geometry) ---

Geom Title=Existing Conditions

River Reach=UNT 122 IN BOCR,Reach-1
Reach XY= 30
      3742647.50     10639878.00      3741935.50     10639502.00
      3741433.00     10639047.00      3741138.25     10638954.00
      3741025.25     10638728.00      3740618.00     10638567.00
      3740383.25     10638608.00      3740170.75     10638930.00
      3739938.75     10639050.00      3739716.00     10638847.00
      3739580.25     10638912.00      3739476.50     10638777.00
      3739178.75     10638792.00      3739101.00     10638726.00
      3739228.75     10638481.00      3738887.50     10638233.00
      3738783.75     10638338.00      3738664.00     10638262.00
      3738681.75     10638088.00      3738484.75     10638102.00
      3738446.25     10637859.00      3738171.25     10637938.00
      3737892.50     10637615.00      3737604.75     10637530.00
      3737438.25     10637373.00      3737317.50     10637425.00
      3737018.50     10637045.00      3736625.50     10636966.00
      3736530.25     10637070.00      3736209.50     10636913.00

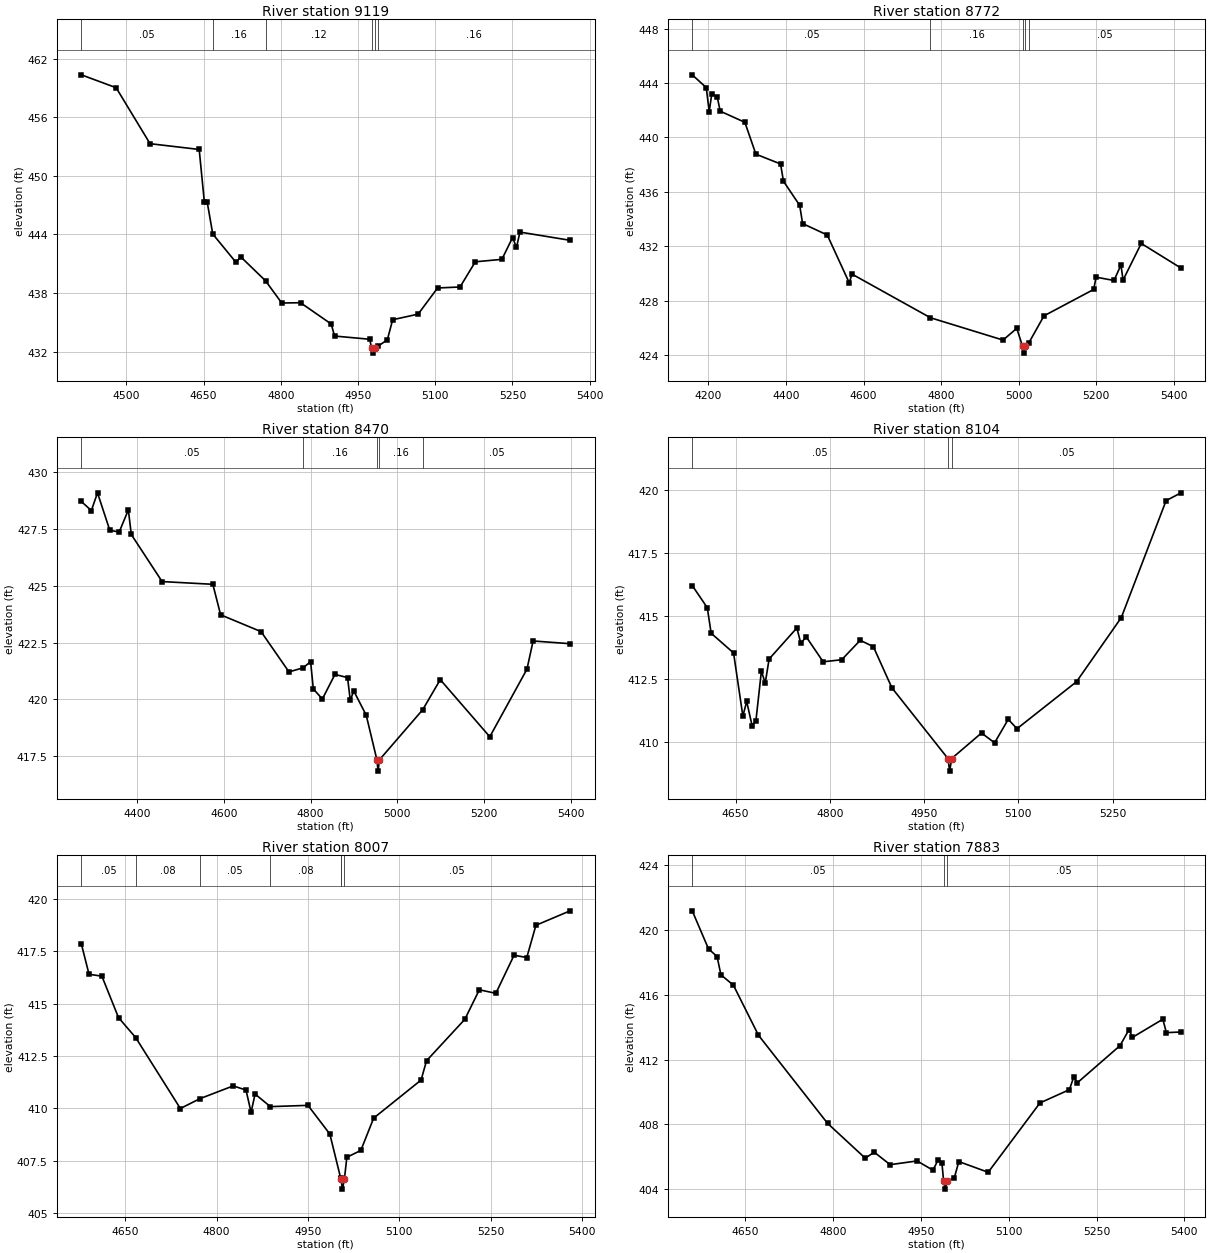
Type RM Length L Ch R = 1,9119,347,347,347
BEGIN DESCRIPTION:
UNT 122 IN BOCR 15.0
END DESCRIPTION:
XS GIS Cut Line= 4
      3742691.25     10639236.29      3742601.20     10639461.16
      3742327.76     10639960.29      3742223.52     10640051.40
#Sta/Elev= 30
  4412.3  460.34  4479.9  459.02  4545.8  453.29  4641.3  452.70  4651.3  447.33
  4656.8  447.33  4667.7  444.04  4713.0  441.13  4721.8  441.72  4770.3  439.25
  4801.7  436.98  4838.2  437.01  4897.9  434.83  4904.3  433.60  4972.7  433.27
  4976.4  432.35  4979.2  431.85  4982.4  432.35  4989.3  432.58  5006.9  433.21
  5017.3  435.27  5066.7  435.84  5104.6  438.52  5148.2  438.62  5177.9  441.20
  5229.5  441.45  5250.3  443.68  5257.9  442.67  5264.6  444.24  5362.1  443.40
#Mann=6,-1,0
  4412.3    0.05       0  4667.7    0.16       0  4770.3    0.12       0
  4976.4    0.07       0  4982.4    0.12       0  4989.3    0.16       0
Bank Sta=4976.4,4982.4
Exp/Cntr=0.3,0.1

Type RM Length L Ch R = 1,8772,302,302,302
BEGIN DESCRIPTION:
Mapping XS 9415e3c9
END DESCRIPTION:
XS GIS Cut Line= 4
      3742646.09     10638955.08      3742262.66     10639296.23
      3741997.90     10639903.87      3741936.94     10639961.45
#Sta/Elev= 30
  4158.4  444.60  4194.6  443.66  4202.1  441.90  4208.8  443.19  4223.0  442.96
  4230.5  441.93  4294.1  441.11  4322.5  438.77  4386.1  438.05  4393.6  436.78
  4435.4  435.01  4442.9  433.67  4506.5  432.83  4563.3  429.31  4570.0  429.96
  4772.5  426.75  4959.6  425.11  4995.0  425.97  5009.9  424.65  5012.7  424.15
  5015.9  424.65  5025.6  424.88  5065.2  426.89  5193.3  428.83  5199.5  429.73
  5245.6  429.49  5263.6  430.62  5269.0  429.52  5315.9  432.21  5418.3  430.40
#Mann=5,-1,0
  4158.4    0.05       0  4772.5    0.16       0  5009.9    0.07       0
  5015.9    0.16       0  5025.6    0.05       0
Bank Sta=5009.9,5015.9
Exp/Cntr=0.3,0.1

Type RM Length L Ch R = 1,8470,366,366,366
BEGIN DESCRIPTION:
Mapping XS 0f5afb87
END DESCRIPTION:
XS GIS Cut Line= 4
      3742347.46     10638875.25      3742145.47     10639100.91
      3741711.45     10639660.81      3741627.58     10639738.94
#Sta/Elev= 30
  4272.1  428.70  4295.1  428.30  4309.3  429.08  4337.7  427.43  4359.3  427.36
  4380.4  428.33  4387.1  427.25  4458.1  425.18  4575.0  425.06  4592.9  423.72
  4686.1  422.98  4750.4  421.21  4782.9  421.39  4800.2  421.66  4806.5  420.46
  4827.3  420.02  4856.3  421.10  4885.3  420.96  4891.6  419.97  4899.7  420.37
  4928.3  419.31  4952.9  417.35  4955.6  416.85  4958.9  417.35  5058.5  419.55
  5098.9  420.87  5213.0  418.36  5298.6  421.33  5312.8  422.57  5398.0  422.45
#Mann=5,-1,0
  4272.1    0.05       0  4782.9    0.16       0  4952.9    0.07       0
  4958.9    0.16       0  5058.5    0.05       0
Bank Sta=4952.9,4958.9
Exp/Cntr=0.3,0.1

Type RM Length L Ch R = 1,8104,97,97,97
BEGIN DESCRIPTION:
Mapping XS fbb48032
END DESCRIPTION:
XS GIS Cut Line= 2
      3741872.02     10638840.52      3741420.63     10639474.20
#Sta/Elev= 30
  4581.0  416.21  4605.0  415.33  4611.1  414.32  4646.8  413.54  4661.6  411.04
  4667.7  411.62  4676.3  410.66  4682.4  410.86  4691.1  412.82  4697.2  412.35
  4703.4  413.30  4747.6  414.53  4753.8  413.92  4762.4  414.18  4789.4  413.19
  4818.9  413.27  4848.4  414.04  4869.3  413.79  4898.8  412.16  4988.0  409.36
  4990.8  408.86  4994.0  409.36  5041.5  410.37  5062.3  409.98  5084.0  410.91
  5098.0  410.54  5192.7  412.40  5264.0  414.94  5335.3  419.57  5359.0  419.88
#Mann=3,-1,0
  4581.0    0.05       0  4988.0    0.03       0  4994.0    0.05       0
Bank Sta=4988,4994
Exp/Cntr=0.3,0.1

Type RM Length L Ch R = 1,8007,124,124,124
BEGIN DESCRIPTION:
Mapping XS 1ac266d2
END DESCRIPTION:
XS GIS Cut Line= 2
      3741785.22     10638779.75      3741334.20     10639443.27
#Sta/Elev= 30
  4578.1  417.85  4590.7  416.40  4611.8  416.31  4639.1  414.33  4667.2  413.38
  4740.6  409.99  4772.8  410.46  4827.4  411.07  4848.4  410.87  4856.7  409.81
  4863.3  410.68  4888.4  410.08  4950.1  410.14  4986.0  408.77  5003.9  406.65
  5004.0  406.64  5006.7  406.14  5010.0  406.64  5013.9  407.66  5036.9  407.99
  5057.9  409.53  5135.8  411.35  5144.7  412.27  5207.6  414.25  5231.4  415.66
  5258.5  415.49  5288.4  417.31  5309.3  417.20  5324.3  418.74  5380.4  419.43
#Mann=7,-1,0
  4578.1    0.05       0  4667.2    0.08       0  4772.8    0.05       0
  4888.4    0.08       0  5003.9    0.05       0  5004.0    0.07       0
  5010.0    0.05       0
Bank Sta=5004,5010
Exp/Cntr=0.3,0.1

Type RM Length L Ch R = 1,7883,92,92,92
BEGIN DESCRIPTION:
Mapping XS 2daec3b2
END DESCRIPTION:
XS GIS Cut Line= 2
      3741681.04     10638684.28      3741238.37     10639391.69
#Sta/Elev= 30
  4559.7  421.19  4587.5  418.84  4602.1  418.37  4608.7  417.24  4630.0  416.60
  4672.8  413.51  4790.8  408.07  4855.1  405.92  4870.5  406.29  4897.6  405.52
  4943.6  405.75  4970.7  405.18  4979.5  405.81  4986.0  405.64  4988.9  404.51
  4991.6  404.01  4994.9  404.51  5007.2  404.71  5014.9  405.71  5065.0  405.05
  5153.4  409.33  5203.7  410.15  5211.2  410.94  5217.1  410.57  5290.2  412.87
  5305.5  413.86  5311.4  413.38  5363.3  414.50  5369.2  413.67  5394.2  413.71
#Mann=3,-1,0
  4559.7    0.05       0  4988.9    0.03       0  4994.9    0.05       0
Bank Sta=4988.9,4994.9
Exp/Cntr=0.3,0.1

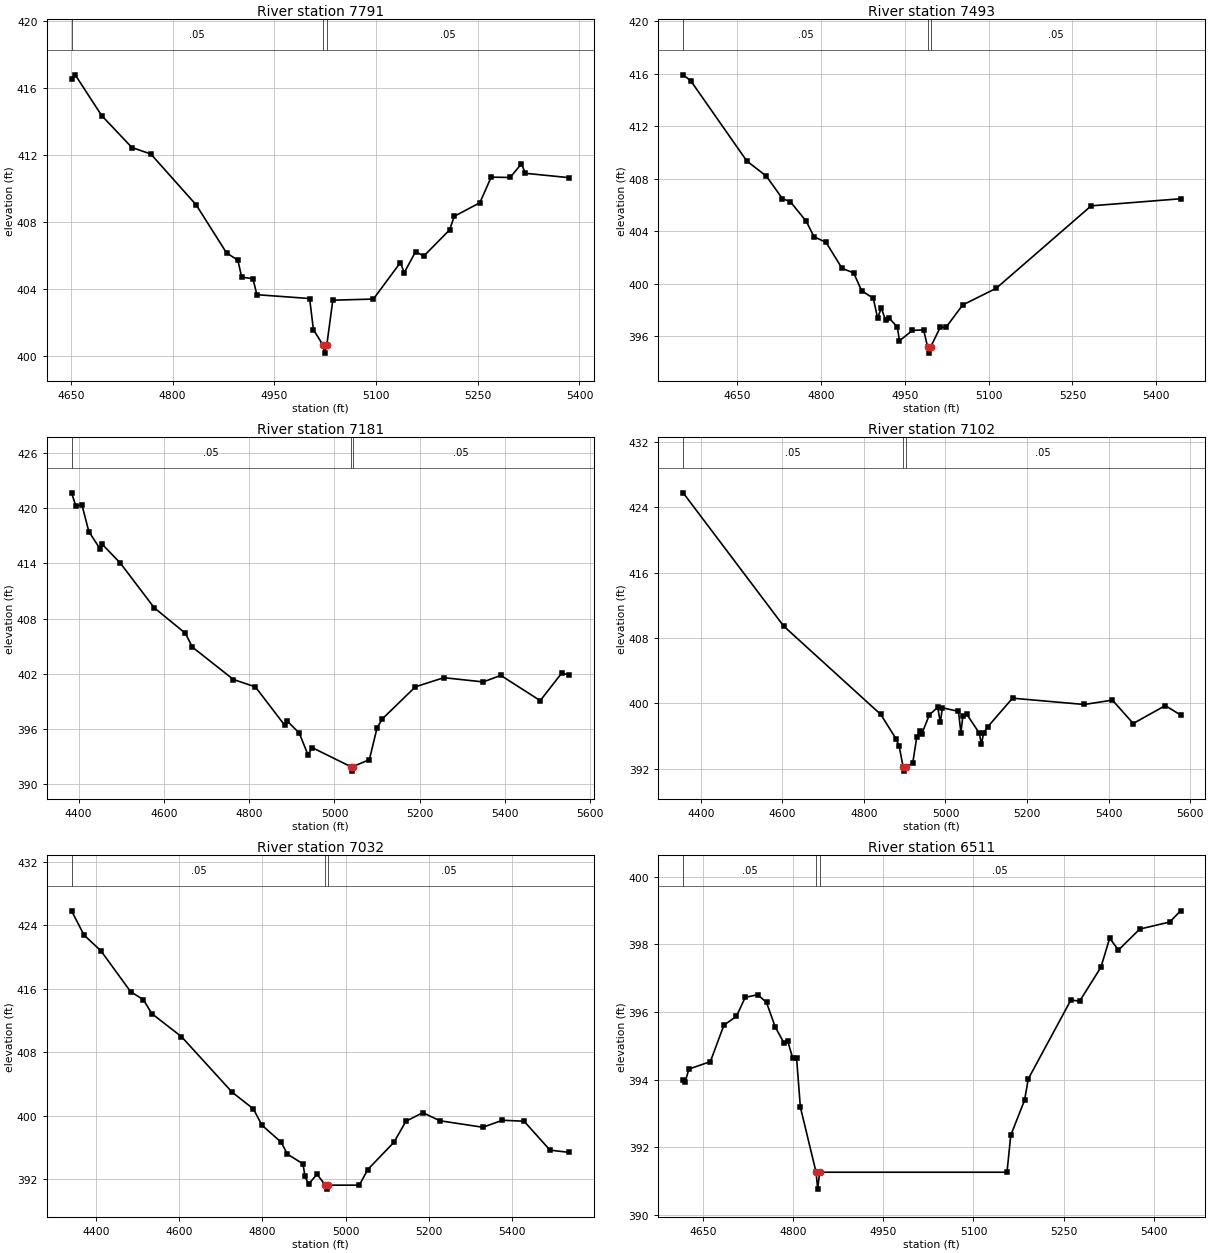
Type RM Length L Ch R = 1,7791,298,298,298
BEGIN DESCRIPTION:
Mapping XS 783bed13
END DESCRIPTION:
XS GIS Cut Line= 2
      3741524.80     10638705.97      3741194.95     10639361.34
#Sta/Elev= 30
  4650.8  416.54  4656.2  416.80  4695.2  414.37  4739.8  412.46  4767.8  412.07
  4834.7  409.03  4879.4  406.17  4896.1  405.73  4901.8  404.72  4918.4  404.62
  4924.2  403.67  5002.0  403.44  5007.6  401.58  5021.4  400.68  5024.1  400.18
  5027.4  400.68  5036.2  403.34  5096.1  403.41  5135.9  405.59  5141.5  404.98
  5158.3  406.24  5170.5  405.98  5208.5  407.54  5215.3  408.35  5253.1  409.16
  5269.8  410.69  5297.8  410.67  5314.5  411.49  5320.1  410.92  5384.5  410.66
#Mann=3,-1,0
  4650.8    0.05       0  5021.4    0.03       0  5027.4    0.05       0
Bank Sta=5021.4,5027.4
Exp/Cntr=0.3,0.1

Type RM Length L Ch R = 1,7493,312,312,312
BEGIN DESCRIPTION:
UNT 122 IN BOCR 14.0
END DESCRIPTION:
XS GIS Cut Line= 3
      3741399.61     10638610.19      3741099.61     10638860.19
      3741099.61     10639360.17
#Sta/Elev= 30
  4553.0  415.91  4566.7  415.45  4666.9  409.35  4702.0  408.19  4730.7  406.48
  4745.0  406.24  4773.6  404.74  4787.3  403.57  4808.8  403.15  4837.4  401.17
  4858.3  400.82  4872.6  399.46  4893.4  398.89  4901.2  397.37  4907.7  398.16
  4915.5  397.20  4922.0  397.37  4936.4  396.70  4940.3  395.65  4963.5  396.44
  4983.5  396.48  4990.5  395.21  4993.3  394.71  4996.5  395.21  5013.5  396.70
  5023.5  396.67  5053.5  398.38  5113.5  399.65  5283.5  405.93  5443.5  406.47
#Mann=3,-1,0
  4553.0    0.05       0  4990.5    0.03       0  4996.5    0.05       0
Bank Sta=4990.5,4996.5
Exp/Cntr=0.3,0.1

Type RM Length L Ch R = 1,7181,79,79,79
BEGIN DESCRIPTION:
Mapping XS bfda7358
END DESCRIPTION:
XS GIS Cut Line= 2
      3741080.15     10638130.66      3740811.79     10639265.66
#Sta/Elev= 30
  4383.5  421.65  4393.3  420.27  4408.1  420.30  4424.1  417.44  4450.4  415.57
  4455.6  416.06  4497.8  414.03  4577.3  409.18  4650.2  406.42  4667.0  404.90
  4763.2  401.39  4814.6  400.59  4883.5  396.42  4888.6  396.92  4917.4  395.58
  4937.9  393.23  4948.2  393.99  5037.7  391.95  5040.4  391.45  5043.7  391.95
  5081.8  392.69  5100.1  396.18  5112.6  397.13  5189.8  400.60  5256.5  401.59
  5348.9  401.13  5390.0  401.84  5482.5  399.10  5533.1  402.10  5549.8  401.87
#Mann=3,-1,0
  4383.5    0.05       0  5037.7    0.03       0  5043.7    0.05       0
Bank Sta=5037.7,5043.7
Exp/Cntr=0.3,0.1

Type RM Length L Ch R = 1,7102,70,70,70
BEGIN DESCRIPTION:
Mapping XS a0bf16fa
END DESCRIPTION:
XS GIS Cut Line= 4
      3740991.61     10638078.54      3740757.24     10639221.79
      3740757.24     10639216.58      3740746.83     10639263.41
#Sta/Elev= 30
  4356.5  425.79  4603.2  409.47  4841.3  398.66  4878.8  395.67  4886.6  394.74
  4896.2  392.22  4899.0  391.72  4902.2  392.22  4919.6  392.67  4929.8  395.94
  4937.0  396.66  4942.1  396.30  4960.5  398.61  4980.9  399.52  4987.4  397.71
  4992.5  399.47  5031.9  399.04  5037.8  396.43  5042.9  398.49  5052.3  398.68
  5082.9  396.38  5088.3  395.01  5093.4  396.38  5103.4  397.13  5164.6  400.65
  5340.3  399.88  5409.6  400.41  5460.6  397.55  5539.2  399.74  5576.7  398.60
#Mann=3,-1,0
  4356.5    0.05       0  4896.2    0.03       0  4902.2    0.05       0
Bank Sta=4896.2,4902.2
Exp/Cntr=0.3,0.1

Type RM Length L Ch R = 1,7032,521,521,521
BEGIN DESCRIPTION:
Mapping XS e395ef6d
END DESCRIPTION:
XS GIS Cut Line= 2
      3740919.15     10638040.69      3740695.20     10639215.13
#Sta/Elev= 30
  4341.2  425.80  4371.2  422.75  4411.9  420.76  4483.2  415.62  4513.8  414.62
  4534.1  412.86  4605.4  409.96  4727.5  402.95  4778.4  400.86  4798.8  398.81
  4845.3  396.66  4859.9  395.17  4897.4  393.95  4902.5  392.36  4910.8  391.37
  4931.1  392.63  4951.6  391.26  4954.4  390.76  4957.6  391.26  5032.9  391.26
  5053.3  393.23  5116.2  396.66  5144.9  399.30  5185.6  400.39  5226.4  399.37
  5329.8  398.55  5376.9  399.43  5429.0  399.31  5491.3  395.67  5536.8  395.39
#Mann=3,-1,0
  4341.2    0.05       0  4951.6    0.03       0  4957.6    0.05       0
Bank Sta=4951.6,4957.6
Exp/Cntr=0.3,0.1

Type RM Length L Ch R = 1,6511,67,67,67
BEGIN DESCRIPTION:
Mapping XS eab593d5
END DESCRIPTION:
XS GIS Cut Line= 2
      3740033.27     10638422.31      3740697.31     10638917.08
#Sta/Elev= 30
  4616.7  393.98  4619.9  393.92  4626.2  394.31  4662.0  394.53  4684.6  395.61
  4705.4  395.87  4720.0  396.43  4740.9  396.51  4755.5  396.28  4770.1  395.55
  4784.7  395.08  4790.9  395.13  4799.2  394.63  4805.5  394.65  4811.8  393.19
  4838.0  391.26  4840.7  390.76  4844.0  391.26  5155.9  391.26  5162.1  392.35
  5185.1  393.39  5191.3  394.02  5262.2  396.35  5276.8  396.32  5312.2  397.32
  5326.8  398.18  5341.4  397.83  5376.9  398.45  5426.9  398.66  5444.8  398.99
#Mann=3,-1,0
  4616.7    0.05       0  4838.0   0.033       0  4844.0    0.05       0
Bank Sta=4838,4844
Exp/Cntr=0.3,0.1

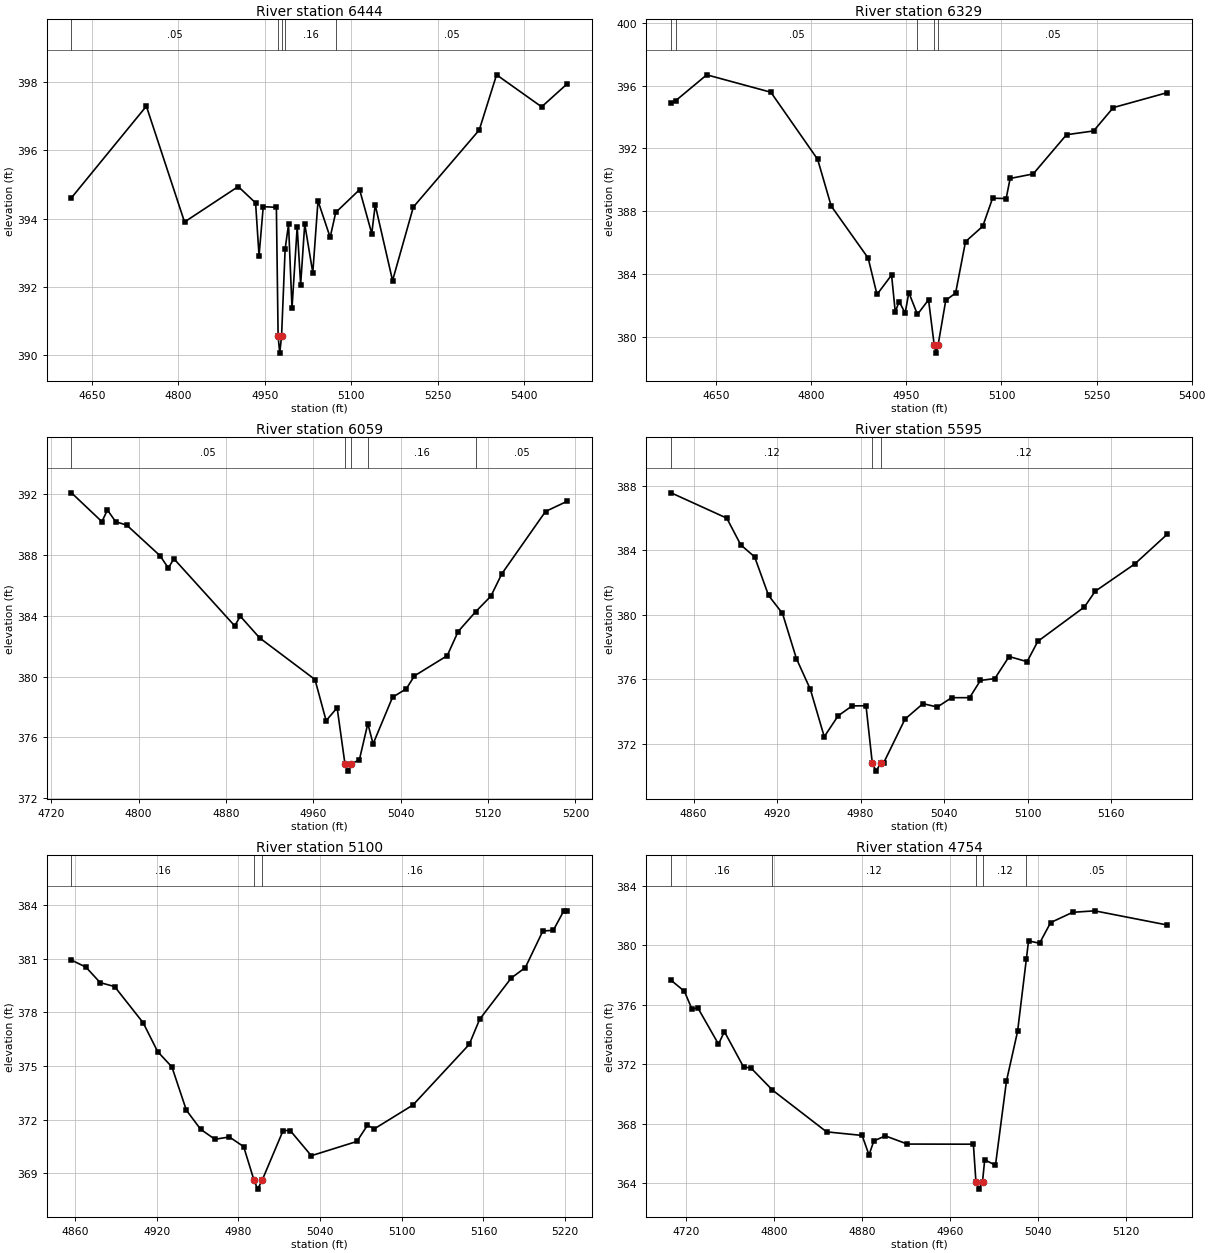
Type RM Length L Ch R = 1,6444,115,115,115
BEGIN DESCRIPTION:
UNT 122 IN BOCR 13.0
END DESCRIPTION:
XS GIS Cut Line= 2
      3739972.15     10638486.15      3740689.53     10638961.37
#Sta/Elev= 30
  4614.4  394.61  4744.4  397.30  4810.6  393.90  4903.8  394.94  4933.9  394.46
  4939.9  392.91  4947.2  394.35  4970.0  394.33  4973.0  390.55  4975.8  390.05
  4979.0  390.55  4985.2  393.11  4991.1  393.83  4997.1  391.37  5006.1  393.75
  5012.1  392.06  5019.2  393.84  5033.2  392.41  5042.2  394.52  5063.3  393.45
  5073.0  394.18  5114.4  394.85  5135.5  393.56  5141.5  394.40  5171.6  392.18
  5207.7  394.34  5322.0  396.60  5352.1  398.22  5430.3  397.28  5474.9  397.96
#Mann=5,-1,0
  4614.4    0.05       0  4973.0    0.07       0  4979.0    0.05       0
  4985.2    0.16       0  5073.0    0.05       0
Bank Sta=4973,4979
Exp/Cntr=0.3,0.1

Type RM Length L Ch R = 1,6329,270,270,270
BEGIN DESCRIPTION:
Mapping XS 5027baf8
END DESCRIPTION:
XS GIS Cut Line= 2
      3739921.26     10638573.33      3740591.67     10638976.10
#Sta/Elev= 30
  4579.0  394.88  4586.2  395.04  4635.2  396.69  4736.3  395.58  4810.1  391.30
  4831.5  388.32  4889.8  385.00  4903.7  382.68  4926.7  383.92  4932.5  381.57
  4938.7  382.23  4948.1  381.49  4953.9  382.80  4967.5  381.41  4985.0  382.34
  4994.0  379.44  4996.8  378.94  5000.0  379.44  5012.2  382.31  5027.7  382.77
  5043.3  386.05  5070.5  387.03  5086.0  388.82  5107.4  388.80  5113.7  390.08
  5150.1  390.37  5202.6  392.87  5245.3  393.11  5276.4  394.60  5361.1  395.55
#Mann=5,-1,0
  4579.0    0.12       0  4586.2    0.05       0  4967.5    0.16       0
  4994.0    0.03       0  5000.0    0.05       0
Bank Sta=4994,5000
Exp/Cntr=0.3,0.1

Type RM Length L Ch R = 1,6059,464,464,464
BEGIN DESCRIPTION:
UNT 122 IN BOCR 12.0
END DESCRIPTION:
XS GIS Cut Line= 3
      3740049.61     10638710.21      3740099.61     10639010.19
      3740099.61     10639160.17
#Sta/Elev= 30
  4738.5  392.10  4766.4  390.20  4771.4  390.97  4779.0  390.20  4789.2  389.97
  4819.6  387.96  4827.2  387.15  4832.3  387.76  4888.0  383.34  4893.1  383.98
  4910.8  382.55  4961.5  379.81  4971.7  377.10  4981.8  377.95  4988.9  374.28
  4991.7  373.78  4994.9  374.28  5002.1  374.51  5009.9  376.91  5014.7  375.57
  5032.5  378.64  5045.1  379.20  5052.6  380.05  5082.6  381.38  5092.6  382.97
  5108.6  384.27  5122.6  385.30  5132.6  386.77  5172.6  390.87  5192.6  391.55
#Mann=5,-1,0
  4738.5    0.05       0  4988.9    0.03       0  4994.9    0.05       0
  5009.9    0.16       0  5108.6    0.05       0
Bank Sta=4988.9,4994.9
Exp/Cntr=0.3,0.1

Type RM Length L Ch R = 1,5595,495,495,495
BEGIN DESCRIPTION:
UNT 122 IN BOCR 11.0
END DESCRIPTION:
XS GIS Cut Line= 3
      3739749.61     10638710.19      3739749.61     10638860.19
      3739699.60     10639060.23
#Sta/Elev= 30
  4843.9  387.56  4883.9  385.99  4893.9  384.34  4903.9  383.59  4913.9  381.20
  4923.9  380.09  4933.9  377.29  4943.9  375.39  4953.9  372.45  4963.9  373.75
  4973.9  374.36  4983.9  374.37  4988.4  370.82  4991.2  370.32  4994.4  370.82
  4996.5  370.82  5011.9  373.54  5024.8  374.50  5035.1  374.29  5045.4  374.87
  5058.3  374.87  5066.1  375.94  5076.4  376.05  5086.7  377.42  5099.6  377.10
  5107.3  378.36  5140.8  380.49  5148.5  381.46  5176.9  383.15  5200.1  384.98
#Mann=3,-1,0
  4843.9    0.12       0  4988.4    0.07       0  4994.4    0.12       0
Bank Sta=4988.4,4994.4
Exp/Cntr=0.3,0.1

Type RM Length L Ch R = 1,5100,346,346,346
BEGIN DESCRIPTION:
UNT 122 IN BOCR 10.0
END DESCRIPTION:
XS GIS Cut Line= 3
      3739449.62     10638660.15      3739399.61     10638810.19
      3739449.61     10639010.18
#Sta/Elev= 30
  4857.3  380.93  4867.9  380.54  4878.4  379.67  4889.0  379.45  4910.0  377.42
  4920.6  375.81  4931.1  374.95  4941.7  372.53  4952.2  371.46  4962.7  370.90
  4973.3  371.03  4983.8  370.49  4991.4  368.61  4994.1  368.11  4997.4  368.61
  5012.8  371.39  5018.0  371.39  5033.5  369.98  5067.0  370.78  5074.7  371.68
  5079.9  371.49  5108.2  372.82  5149.5  376.21  5157.2  377.62  5180.4  379.93
  5190.7  380.51  5203.6  382.56  5211.3  382.60  5219.0  383.69  5221.6  383.69
#Mann=3,-1,0
  4857.3    0.16       0  4991.4    0.07       0  4997.4    0.16       0
Bank Sta=4991.4,4997.4
Exp/Cntr=0.3,0.1

Type RM Length L Ch R = 1,4754,565,565,565
BEGIN DESCRIPTION:
UNT 122 IN BOCR 9.0
END DESCRIPTION:
XS GIS Cut Line= 3
      3739380.85     10638647.58      3739206.37     10638717.89
      3738944.00     10638738.67
#Sta/Elev= 30
  4706.2  377.64  4718.3  376.90  4725.1  375.71  4730.5  375.79  4749.3  373.35
  4754.7  374.19  4772.2  371.80  4778.8  371.75  4798.4  370.26  4847.7  367.45
  4880.0  367.21  4886.3  365.90  4890.7  366.84  4901.1  367.18  4921.2  366.63
  4981.3  366.62  4983.6  364.10  4986.3  363.60  4989.6  364.10  4991.6  365.57
  5001.4  365.21  5011.4  370.87  5021.5  374.20  5029.5  379.07  5031.5  380.29
  5041.5  380.13  5051.6  381.52  5071.6  382.21  5091.7  382.31  5157.5  381.36
#Mann=5,-1,0
  4706.2    0.16       0  4798.4    0.12       0  4983.6    0.07       0
  4989.6    0.12       0  5029.5    0.05       0
Bank Sta=4983.6,4989.6
Exp/Cntr=0.3,0.1

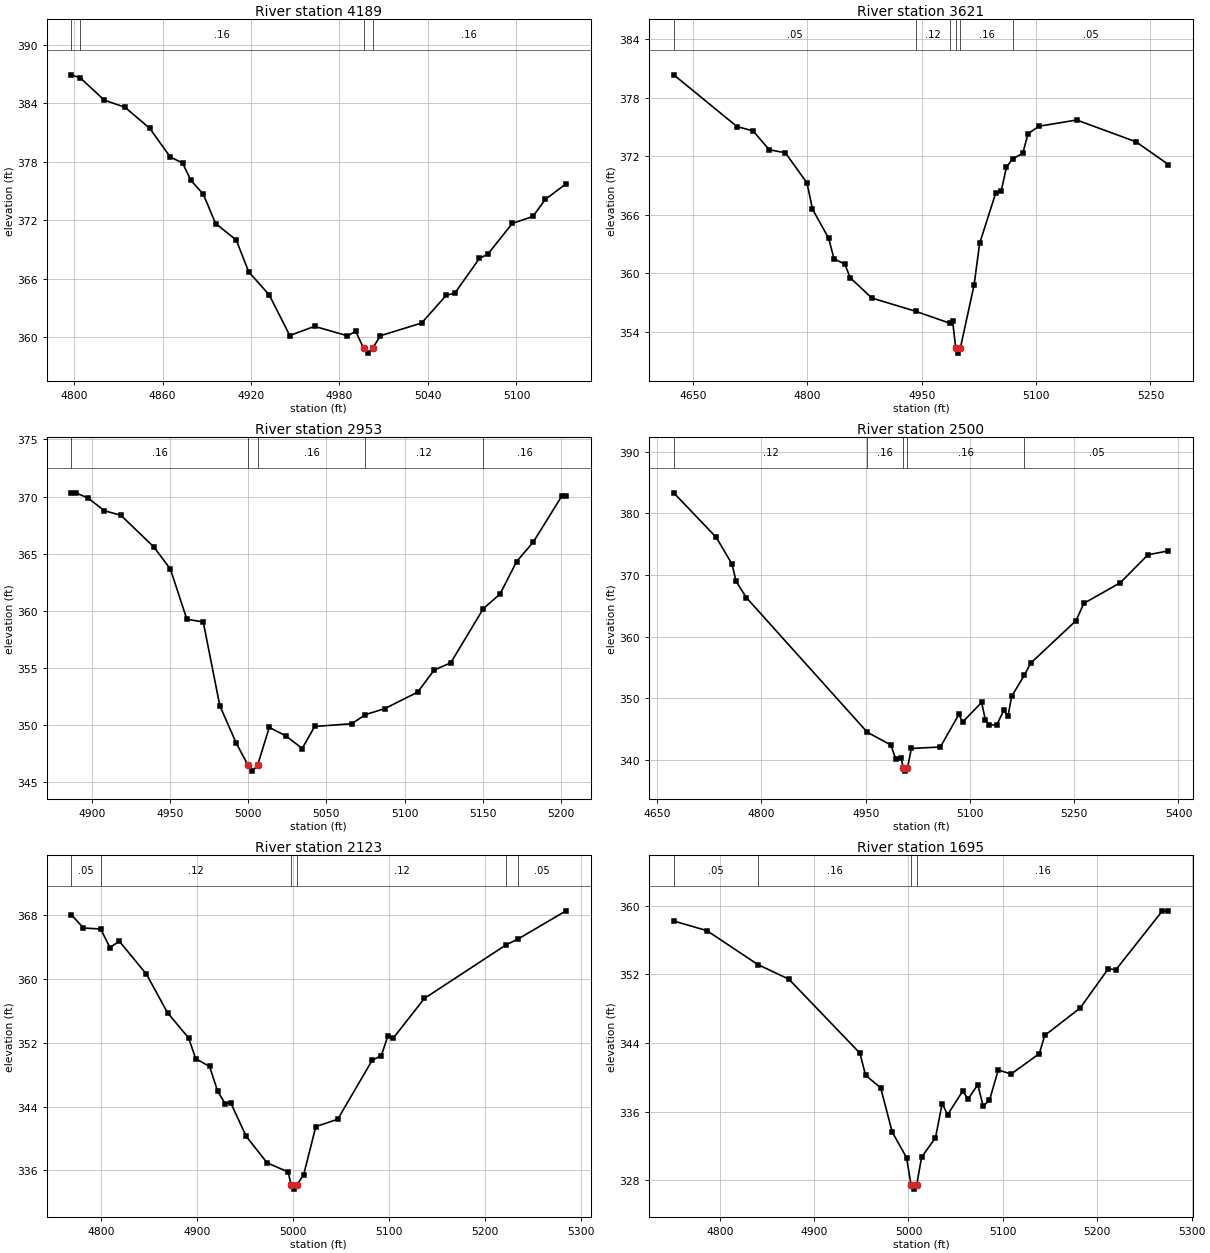
Type RM Length L Ch R = 1,4189,568,568,568
BEGIN DESCRIPTION:
UNT 122 IN BOCR 8.0
END DESCRIPTION:
XS GIS Cut Line= 3
      3739149.59     10638160.22      3739049.61     10638360.19
      3738999.60     10638460.21
#Sta/Elev= 30
  4798.2  386.93  4804.3  386.61  4820.5  384.33  4834.5  383.60  4851.3  381.44
  4865.2  378.50  4873.6  377.87  4879.2  376.10  4887.6  374.68  4896.0  371.66
  4910.0  369.96  4918.4  366.71  4932.3  364.34  4946.3  360.16  4963.1  361.10
  4985.4  360.13  4991.0  360.58  4996.4  358.85  4999.2  358.35  5002.4  358.85
  5007.8  360.14  5035.7  361.44  5052.5  364.31  5058.1  364.48  5074.9  368.08
  5080.5  368.50  5097.2  371.67  5111.2  372.39  5119.6  374.14  5133.6  375.73
#Mann=4,-1,0
  4798.2    0.05       0  4804.3    0.16       0  4996.4    0.07       0
  5002.4    0.16       0
Bank Sta=4996.4,5002.4
Exp/Cntr=0.3,0.1

Type RM Length L Ch R = 1,3621,668,668,668
BEGIN DESCRIPTION:
Mapping XS 6b5b24bd
END DESCRIPTION:
XS GIS Cut Line= 2
      3738921.32     10637984.79      3738454.98     10638435.59
#Sta/Elev= 30
  4624.9  380.34  4707.8  375.04  4728.9  374.59  4750.2  372.66  4771.3  372.35
  4799.6  369.26  4806.8  366.58  4827.9  363.61  4835.1  361.49  4849.3  360.93
  4856.2  359.56  4884.5  357.47  4942.1  356.11  4986.7  354.89  4990.5  355.15
  4994.7  352.32  4997.5  351.82  5000.7  352.32  5018.8  358.82  5026.0  363.06
  5047.1  368.22  5054.3  368.44  5061.2  370.88  5069.2  371.71  5082.6  372.31
  5089.5  374.30  5103.7  375.07  5153.3  375.71  5231.0  373.48  5273.5  371.15
#Mann=6,-1,0
  4624.9    0.05       0  4942.1    0.12       0  4986.7    0.16       0
  4994.7    0.07       0  5000.7    0.16       0  5069.2    0.05       0
Bank Sta=4994.7,5000.7
Exp/Cntr=0.3,0.1

Type RM Length L Ch R = 1,2953,453,453,453
BEGIN DESCRIPTION:
UNT 122 IN BOCR 6.0
END DESCRIPTION:
XS GIS Cut Line= 3
      3738449.61     10637760.17      3738399.61     10637910.19
      3738349.62     10638060.15
#Sta/Elev= 30
  4887.0  370.33  4889.7  370.33  4897.6  369.88  4908.1  368.76  4918.6  368.37
  4939.7  365.59  4950.3  363.65  4960.8  359.26  4971.3  359.02  4981.9  351.68
  4992.4  348.41  5000.0  346.46  5002.7  345.96  5006.0  346.46  5013.5  349.79
  5024.0  349.06  5034.6  347.94  5042.5  349.87  5066.2  350.11  5075.0  350.91
  5087.3  351.43  5108.4  352.88  5118.9  354.81  5129.5  355.44  5150.3  360.18
  5161.1  361.48  5171.6  364.31  5182.2  366.00  5200.6  370.06  5203.2  370.06
#Mann=5,-1,0
  4887.0    0.16       0  5000.0    0.07       0  5006.0    0.16       0
  5075.0    0.12       0  5150.3    0.16       0
Bank Sta=5000,5006
Exp/Cntr=0.3,0.1

Type RM Length L Ch R = 1,2500,377,377,377
BEGIN DESCRIPTION:
UNT 122 IN BOCR 5.0
END DESCRIPTION:
XS GIS Cut Line= 3
      3738245.53     10637560.37      3738024.19     10637870.68
      3737926.89     10638186.36
#Sta/Elev= 30
  4673.9  383.35  4735.1  376.10  4757.6  371.79  4763.7  368.95  4778.4  366.32
  4952.2  344.47  4986.2  342.38  4993.0  340.19  5000.9  340.27  5004.1  338.64
  5006.8  338.14  5010.1  338.64  5015.7  341.82  5057.4  342.06  5084.1  347.36
  5089.4  346.10  5116.8  349.31  5122.1  346.50  5127.8  345.71  5138.3  345.60
  5148.7  348.01  5154.7  347.03  5160.0  350.30  5178.2  353.71  5187.4  355.68
  5252.7  362.60  5263.8  365.39  5316.2  368.74  5356.0  373.28  5385.4  373.92
#Mann=5,-1,0
  4673.9    0.12       0  4952.2    0.16       0  5004.1    0.07       0
  5010.1    0.16       0  5178.2    0.05       0
Bank Sta=5004.1,5010.1
Exp/Cntr=0.3,0.1

Type RM Length L Ch R = 1,2123,428,428,428
BEGIN DESCRIPTION:
Mapping XS 89b020aa
END DESCRIPTION:
XS GIS Cut Line= 2
      3737931.72     10637396.25      3737686.94     10637849.36
#Sta/Elev= 30
  4769.3  368.06  4781.9  366.40  4799.8  366.28  4809.4  363.95  4819.2  364.74
  4847.5  360.60  4869.4  355.77  4891.3  352.61  4898.8  349.99  4913.2  349.03
  4921.5  345.94  4929.4  344.36  4935.1  344.50  4951.3  340.26  4973.1  336.93
  4995.0  335.78  4998.1  334.13  5000.8  333.63  5004.1  334.13  5011.2  335.46
  5023.8  341.48  5046.6  342.40  5082.6  349.82  5092.0  350.38  5098.8  352.85
  5104.5  352.59  5136.9  357.57  5222.1  364.30  5234.1  365.00  5284.3  368.56
#Mann=6,-1,0
  4769.3    0.05       0  4799.8    0.12       0  4998.1    0.07       0
  5004.1    0.12       0  5222.1    0.16       0  5234.1    0.05       0
Bank Sta=4998.1,5004.1
Exp/Cntr=0.3,0.1

Type RM Length L Ch R = 1,1695,641,641,641
BEGIN DESCRIPTION:
Mapping XS 56cf068e
END DESCRIPTION:
XS GIS Cut Line= 2
      3737603.60     10637187.92      3737348.68     10637645.73
#Sta/Elev= 30
  4751.3  358.24  4786.4  357.12  4840.4  353.16  4873.3  351.45  4948.5  342.82
  4954.5  340.24  4970.5  338.78  4982.8  333.60  4997.9  330.64  5002.7  327.45
  5005.5  326.95  5008.7  327.45  5013.9  330.69  5028.6  332.94  5035.7  336.94
  5041.4  335.63  5057.4  338.39  5063.1  337.47  5073.4  339.13  5079.1  336.65
  5085.8  337.32  5095.1  340.86  5108.7  340.38  5138.6  342.76  5144.3  344.88
  5182.0  348.10  5211.7  352.68  5219.7  352.55  5269.0  359.43  5275.3  359.39
#Mann=4,-1,0
  4751.3    0.05       0  4840.4    0.16       0  5002.7    0.07       0
  5008.7    0.16       0
Bank Sta=5002.7,5008.7
Exp/Cntr=0.3,0.1

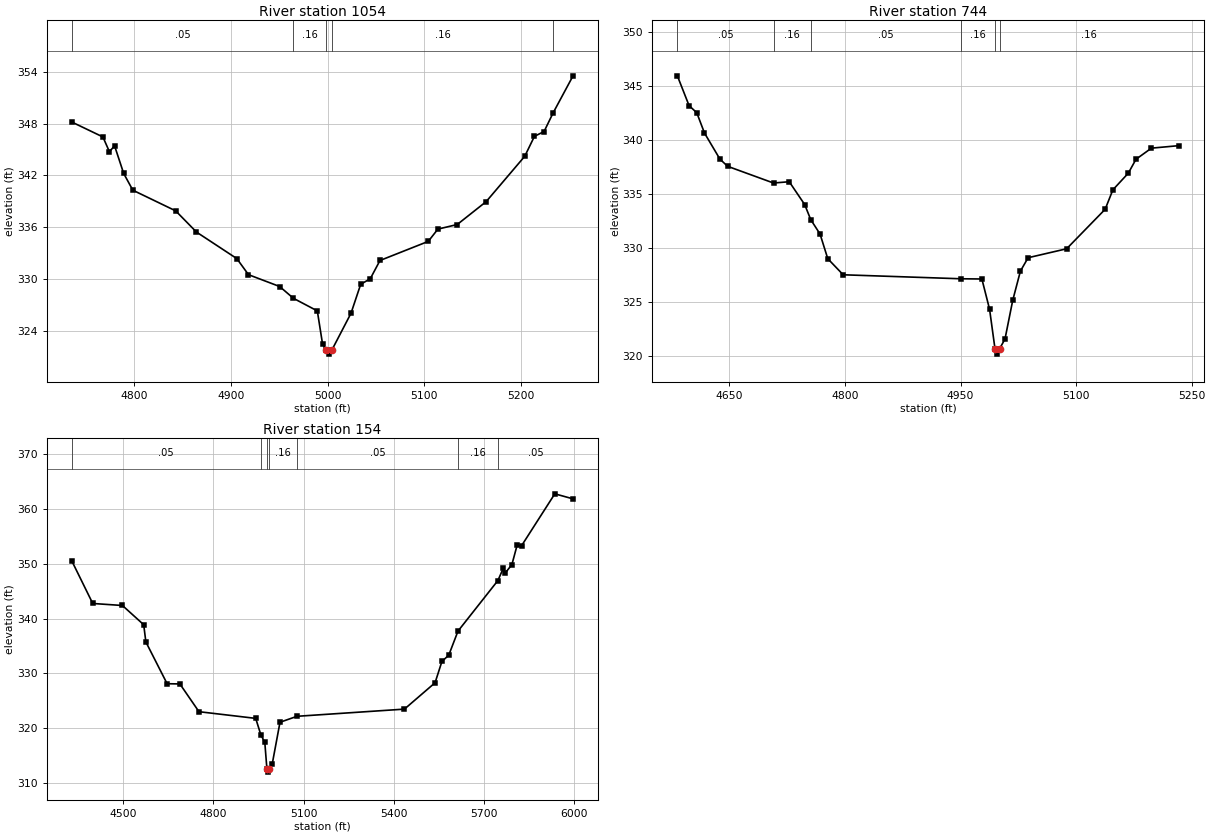
Type RM Length L Ch R = 1,1054,310,310,310
BEGIN DESCRIPTION:
UNT 122 IN BOCR 2.0
END DESCRIPTION:
XS GIS Cut Line= 3
      3737299.61     10637010.19      3737049.61     10637110.19
      3737049.61     10637360.23
#Sta/Elev= 30
  4735.0  348.18  4767.3  346.45  4774.0  344.75  4779.4  345.42  4788.8  342.23
  4798.3  340.29  4842.7  337.90  4864.2  335.45  4906.0  332.38  4918.1  330.52
  4950.4  329.15  4964.6  327.79  4989.4  326.33  4994.8  322.51  4998.6  321.83
  5001.3  321.33  5004.6  321.83  5024.3  326.06  5034.3  329.40  5044.3  330.06
  5054.3  332.16  5104.3  334.37  5114.3  335.79  5134.3  336.32  5164.3  338.97
  5204.3  344.22  5214.3  346.52  5224.3  347.08  5233.6  349.22  5254.3  353.52
#Mann=5,-1,0
  4735.0    0.05       0  4964.6    0.16       0  4998.6    0.07       0
  5004.6    0.16       0  5233.6    0.05       0
Bank Sta=4998.6,5004.6
Exp/Cntr=0.3,0.1

Type RM Length L Ch R = 1,744,590,590,590
BEGIN DESCRIPTION:
Mapping XS 3b65adf9
END DESCRIPTION:
XS GIS Cut Line= 2
      3736791.09     10636614.99      3736791.09     10637265.59
#Sta/Elev= 30
  4582.5  345.96  4597.7  343.20  4607.7  342.54  4617.7  340.66  4637.7  338.25
  4647.7  337.58  4707.3  336.03  4727.7  336.15  4747.7  334.04  4755.6  332.64
  4767.7  331.30  4777.7  329.02  4797.7  327.53  4950.5  327.16  4977.7  327.14
  4987.7  324.33  4994.7  320.68  4997.4  320.18  5000.7  320.68  5007.7  321.58
  5017.7  325.15  5027.7  327.87  5037.7  329.11  5087.7  329.94  5137.7  333.60
  5147.7  335.40  5167.7  336.94  5177.7  338.23  5197.7  339.26  5233.1  339.49
#Mann=6,-1,0
  4582.5    0.05       0  4707.3    0.16       0  4755.6    0.05       0
  4950.5    0.16       0  4994.7    0.07       0  5000.7    0.16       0
Bank Sta=4994.7,5000.7
Exp/Cntr=0.3,0.1

Type RM Length L Ch R = 1,154,0,0,0
BEGIN DESCRIPTION:
UNT 122 IN BOCR 1.0
END DESCRIPTION:
XS GIS Cut Line= 4
      3736707.74     10636479.62      3736332.76     10636870.23
      3736301.51     10637083.77      3737124.42     10637474.39
#Sta/Elev= 30
  4328.5  350.56  4398.4  342.76  4497.2  342.39  4568.0  338.88  4575.2  335.73
  4645.9  328.10  4688.4  328.06  4751.9  322.99  4940.7  321.77  4957.5  318.82
  4971.0  317.37  4978.1  312.45  4980.8  311.95  4984.1  312.45  4995.8  313.47
  5021.5  321.06  5078.2  322.15  5435.6  323.46  5537.6  328.28  5560.3  332.17
  5583.1  333.31  5613.8  337.71  5746.5  346.94  5764.9  349.23  5770.4  348.28
  5793.2  349.86  5810.4  353.37  5825.3  353.30  5936.0  362.79  5996.7  361.87
#Mann=7,-1,0
  4328.5    0.05       0  4957.5    0.16       0  4978.1    0.07       0
  4984.1    0.16       0  5078.2    0.05       0  5613.8    0.16       0
  5746.5    0.05       0
Bank Sta=4978.1,4984.1
Exp/Cntr=0.3,0.1

Chan Stop Cuts=-1