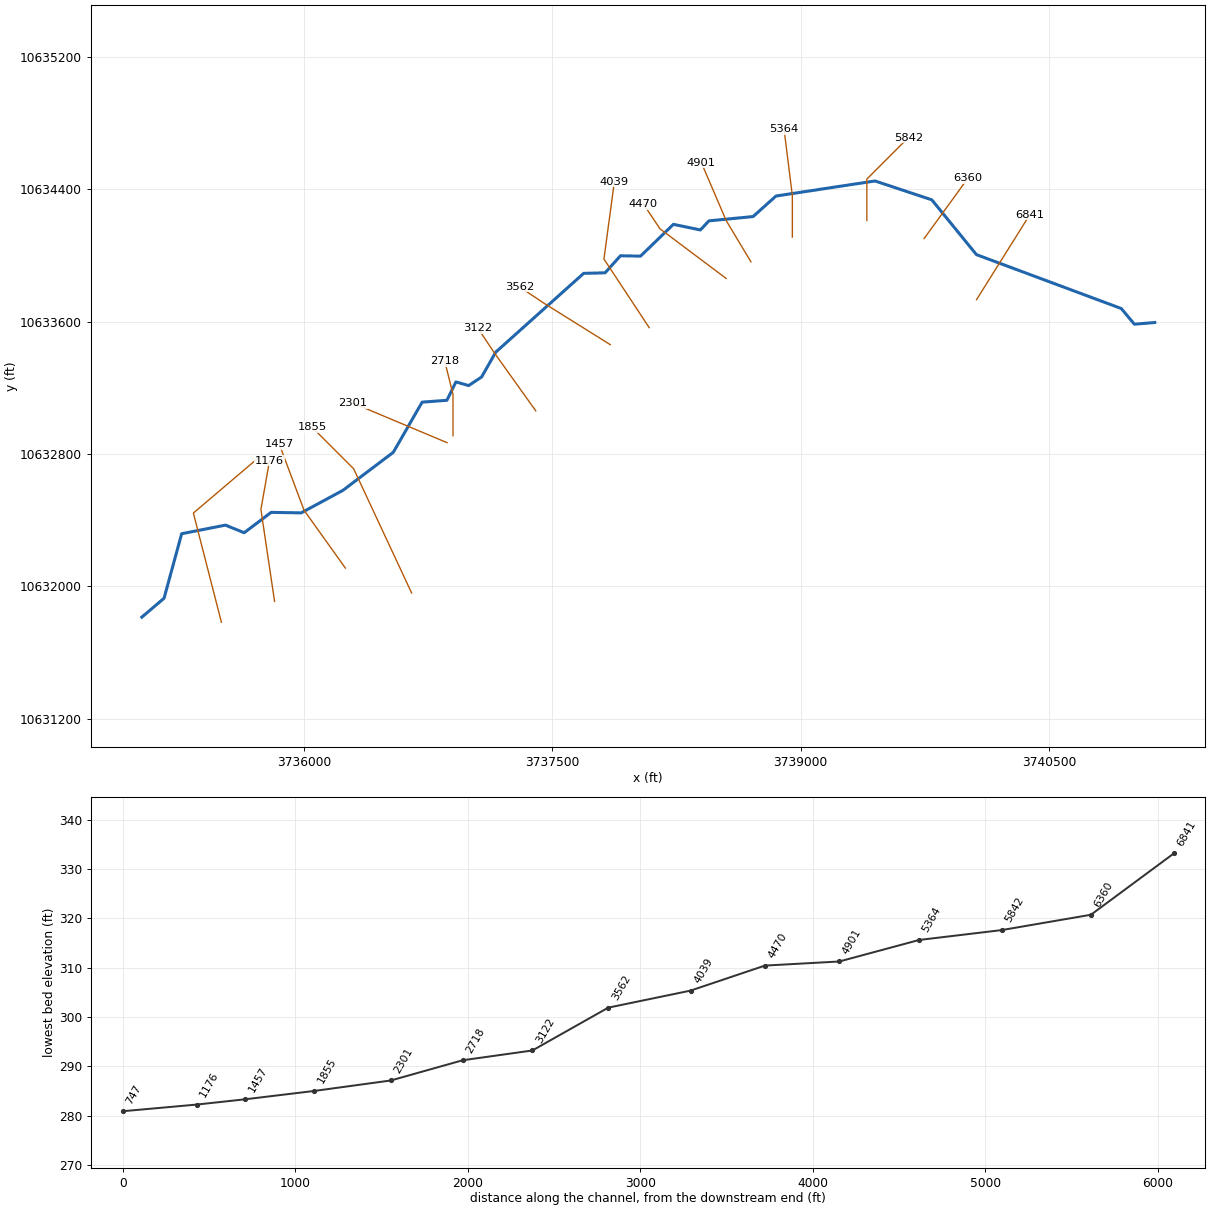
--- UNT 123 IN BOCR.prj (project) ---

Proj Title=UNT 123 IN BOCR Base Level Engineering
Current Plan=p01
Default Exp/Contr=0.3,0.1
English Units
Geom File=g01
Flow File=f01
Plan File=p01
Y Axis Title=Elevation
X Axis Title(PF)=Main Channel Distance
X Axis Title(XS)=Station
BEGIN DESCRIPTION:
UNT 123 IN BOCR
END DESCRIPTION:
DSS Export Rating Curves= 0
DSS Export Rating Curve Sorted= 0
DSS Export Volume Flow Curves= 0
DXF OffsetX= 0
DXF OffsetY= 0
DXF ScaleX= 1
DXF ScaleY= 10

--- UNT 123 IN BOCR.p01 (plan) ---

Plan Title=Multiple Run
Short Identifier=Multiple
Geom File=g01
Flow File=f01
Subcritical Flow
K Sum by GR= 0
Std Step Tol= 0.01
Critical Tol= 0.01
Num of Std Step Trials= 20
Max Error Tol= 0.3
Flow Tol Ratio= 0.001
Split Flow NTrial= 30
Split Flow Tol= 0.02
Split Flow Ratio= 0.02
Log Output Level= 0
Friction Slope Method= 1
Unsteady Friction Slope Method= 2
Unsteady Bridges Friction Slope Method= 1
Parabolic Critical Depth
Global Vel Dist=  1 , 1 , 1
Global Log Level= 0
CheckData=True
Encroach Param= -1, 0, 0, 0
BEGIN DESCRIPTION:
Multiple Run
END DESCRIPTION:

--- UNT 123 IN BOCR.f01 (steady flow) ---

Flow Title=Multiple
Program Version=4.10
Number of Profiles= 7
Profile Names=10-year,25-year,50-year,1pct_min,100-year,1pct_plu,500-year
River Rch & RM=UNT 123 IN BOCR,Reach-1         ,6841
     704     969    1192    1079    1460    1974    2195
River Rch & RM=UNT 123 IN BOCR,Reach-1         ,5364
     815    1128    1393    1264    1710    2312    2584
River Rch & RM=UNT 123 IN BOCR,Reach-1         ,1855
    1190    1678    2098    1925    2603    3520    4023
River Rch & RM=UNT 123 IN BOCR,Reach-1         ,1457
    1190    1678    2098    1925    2603    3520    4023
Boundary for River Rch & Prof#=UNT 123 IN BOCR,Reach-1         , 1
Up Type= 0
Dn Type= 3
Dn Slope=0.005
Boundary for River Rch & Prof#=UNT 123 IN BOCR,Reach-1         , 2
Up Type= 0
Dn Type= 3
Dn Slope=0.005
Boundary for River Rch & Prof#=UNT 123 IN BOCR,Reach-1         , 3
Up Type= 0
Dn Type= 3
Dn Slope=0.005
Boundary for River Rch & Prof#=UNT 123 IN BOCR,Reach-1         , 4
Up Type= 0
Dn Type= 3
Dn Slope=0.005
Boundary for River Rch & Prof#=UNT 123 IN BOCR,Reach-1         , 5
Up Type= 0
Dn Type= 3
Dn Slope=0.005
Boundary for River Rch & Prof#=UNT 123 IN BOCR,Reach-1         , 6
Up Type= 0
Dn Type= 3
Dn Slope=0.005
Boundary for River Rch & Prof#=UNT 123 IN BOCR,Reach-1         , 7
Up Type= 0
Dn Type= 3
Dn Slope=0.005
DSS Import GetInterval= 0
DSS Import GetPeak= 0
DSS Import FillOption= 0

--- UNT 123 IN BOCR.g01 (geometry) ---

Geom Title=Existing Conditions
Program Version=4.10

River Reach=UNT 123 IN BOCR ,Reach-1
Reach XY= 30
      3741138.82     10633593.95      3741015.63     10633583.75
      3740936.64     10633678.37       3740061.5       10634004.
        3739792.       10634335.        3739449.       10634449.
      3738850.75       10634358.       3738712.5       10634234.
       3738445.5       10634208.        3738394.       10634153.
        3738231.       10634187.       3738032.5       10633995.
        3737911.       10633997.      3737818.25       10633894.
        3737689.       10633891.      3737157.75       10633415.
       3737072.5       10633265.        3736994.       10633213.
      3736917.25       10633235.      3736862.75       10633124.
      3736713.25       10633113.        3736539.       10632810.
       3736234.5       10632580.       3735982.5       10632444.
        3735801.       10632447.        3735638.       10632324.
        3735525.       10632370.       3735260.5       10632318.
        3735154.       10631928.      3735019.75       10631814.

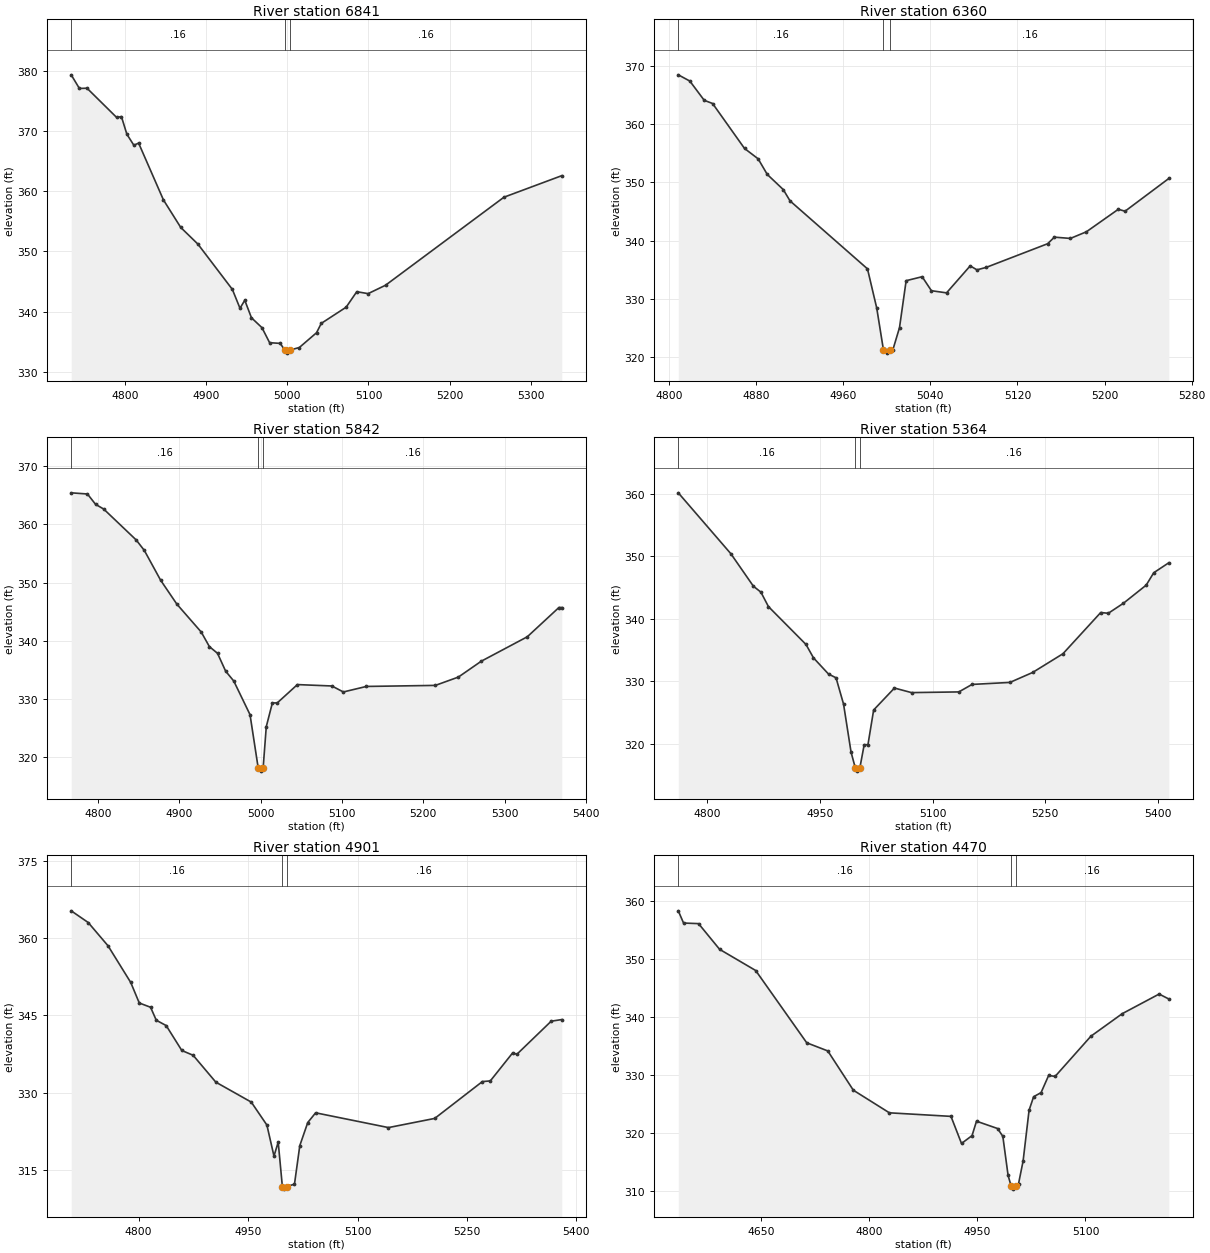
Type RM Length L Ch R = 1 ,6841    ,481,481,481
BEGIN DESCRIPTION:
UNT 123 IN BOCR 16.0
END DESCRIPTION:
XS GIS Cut Line= 2
      3740062.16     10633732.03      3740383.33     10634244.16
#Sta/Elev= 30
  4733.7   379.3  4743.8  377.04  4753.2  377.08  4789.7  372.23  4795.6  372.37
  4802.3  369.45  4810.9  367.62  4816.8  367.97  4847.4  358.54  4868.7  353.98
  4889.9  351.21  4932.3   343.7  4941.7  340.57  4947.6   341.9  4955.8     339
  4968.8  337.35  4978.2  334.86  4991.2  334.75    4997  333.63  4999.8  333.13
    5003  333.63  5014.8  334.06    5036  336.51  5041.9  338.07  5072.5  340.75
  5085.6  343.32  5099.6     343    5121  344.39    5267     359  5338.2  362.57
#Mann= 3 ,-1 , 0
  4733.7     .16       0    4997     .16       0    5003     .16       0
Bank Sta=4997,5003
XS Rating Curve= 0 ,0
Exp/Cntr=0.3,0.1

Type RM Length L Ch R = 1 ,6360    ,518,518,518
BEGIN DESCRIPTION:
UNT 123 IN BOCR 13.0
END DESCRIPTION:
XS GIS Cut Line= 2
      3739745.28     10634100.89      3740009.94     10634465.34
#Sta/Elev= 30
  4808.6  368.45  4819.2  367.38  4832.4  364.08  4840.1  363.53  4869.4  355.82
  4881.9  354.04  4890.3  351.36    4905  348.76  4911.2  346.82  4982.3  335.16
  4990.8  328.43    4997   321.2  4999.8   320.7    5003   321.2  5005.5   321.2
  5011.7  325.07  5017.8  333.13  5032.5  333.81    5041  331.41  5054.9  331.04
  5076.6  335.67  5082.8  334.99  5091.3  335.41  5147.7  339.47  5153.9   340.6
  5168.6  340.38  5183.3  341.52  5212.6  345.38  5218.8  345.05    5259  350.67
#Mann= 3 ,-1 , 0
  4808.6     .16       0    4997     .16       0    5003     .16       0
Bank Sta=4997,5003
XS Rating Curve= 0 ,0
Exp/Cntr=0.3,0.1

Type RM Length L Ch R = 1 ,5842    ,478,478,478
BEGIN DESCRIPTION:
UNT 123 IN BOCR 12.0
END DESCRIPTION:
XS GIS Cut Line= 3
      3739399.61      10634210.2      3739399.61     10634460.19
      3739649.58     10634710.16
#Sta/Elev= 30
  4766.9  365.44  4786.9  365.24  4796.9  363.46  4806.9  362.65  4846.9  357.33
  4856.9  355.53  4876.9  350.42  4896.9   346.3  4926.9   341.5  4936.9     339
  4946.9  337.85  4956.9  334.78  4966.9  333.08  4986.9   327.3    4997  318.09
  4999.8  317.59    5003  318.09  5006.9  325.24  5014.4  329.32  5020.4  329.32
  5045.2  332.47  5087.6  332.23  5101.7   331.2    5130  332.15  5214.9  332.33
  5243.2  333.76  5271.4  336.49    5328  340.69  5366.9  345.72  5370.4  345.72
#Mann= 3 ,-1 , 0
  4766.9     .16       0    4997     .16       0    5003     .16       0
Bank Sta=4997,5003
XS Rating Curve= 0 ,0
Exp/Cntr=0.3,0.1

Type RM Length L Ch R = 1 ,5364    ,463,463,463
BEGIN DESCRIPTION:
UNT 123 IN BOCR 11.0
END DESCRIPTION:
XS GIS Cut Line= 3
      3738949.61     10634110.16      3738949.61     10634360.19
      3738899.61     10634760.15
#Sta/Elev= 30
  4761.3  360.14  4831.3  350.39  4861.3  345.19  4871.3  344.24  4881.3  341.93
  4931.3  335.87  4941.3  333.72  4961.3  331.13  4971.3  330.53  4981.3  326.33
  4991.3  318.64    4997  316.09  4999.8  315.59    5003  316.09  5008.8  319.82
  5013.8  319.82  5021.4  325.38  5049.1  328.89  5071.8  328.16  5134.8  328.27
  5152.4  329.47  5202.8  329.79    5233  331.38  5273.4  334.38  5323.7  340.98
  5333.8  340.86    5354  342.47  5384.2  345.36  5394.3  347.35  5414.4  348.95
#Mann= 3 ,-1 , 0
  4761.3     .16       0    4997     .16       0    5003     .16       0
Bank Sta=4997,5003
XS Rating Curve= 0 ,0
Exp/Cntr=0.3,0.1

Type RM Length L Ch R = 1 ,4901    ,431,431,431
BEGIN DESCRIPTION:
UNT 123 IN BOCR 10.0
END DESCRIPTION:
XS GIS Cut Line= 3
      3738699.59     10633960.21      3738549.61     10634210.19
      3738399.61     10634560.18
#Sta/Elev= 30
  4707.6  365.31  4730.9  363.04  4758.1  358.51  4789.2  351.39  4800.9   347.4
  4816.4  346.57  4824.2  344.05  4837.8  343.01  4859.2  338.17  4874.7  337.24
  4905.8  332.02  4954.4  328.14  4975.8  323.68  4985.5  317.65  4991.3  320.36
    4997  311.73  4999.8  311.23    5003  311.73  5013.6   312.2  5020.9  319.69
  5031.8  324.17  5042.6  326.06  5142.4  323.19  5205.8  324.97  5271.1  332.13
    5282  332.26  5312.8  337.74  5318.3  337.42  5365.4  343.86  5379.9  344.18
#Mann= 3 ,-1 , 0
  4707.6     .16       0    4997     .16       0    5003     .16       0
Bank Sta=4997,5003
XS Rating Curve= 0 ,0
Exp/Cntr=0.3,0.1

Type RM Length L Ch R = 1 ,4470    ,431,431,431
BEGIN DESCRIPTION:
UNT 123 IN BOCR 9.0
END DESCRIPTION:
XS GIS Cut Line= 3
      3738549.58     10633860.21      3738149.61     10634160.19
      3738049.63     10634310.15
#Sta/Elev= 30
  4535.4  358.25  4542.7  356.15  4563.5  356.05  4592.7  351.63  4642.7  347.99
  4713.5  335.56  4742.7  334.16  4778.1  327.41  4828.1  323.52  4913.5  322.91
  4928.1  318.25  4942.7   319.6  4948.9  322.08  4978.1  320.82  4985.4  319.48
  4992.7  312.75    4997   310.9  4999.8   310.4    5003   310.9  5007.2  311.34
  5013.5  315.23  5021.8  323.97  5028.1  326.29  5038.4  326.99  5048.9  329.94
  5057.9  329.78  5107.5  336.69    5151  340.57  5202.1  343.94  5215.6  343.09
#Mann= 3 ,-1 , 0
  4535.4     .16       0    4997     .16       0    5003     .16       0
Bank Sta=4997,5003
XS Rating Curve= 0 ,0
Exp/Cntr=0.3,0.1

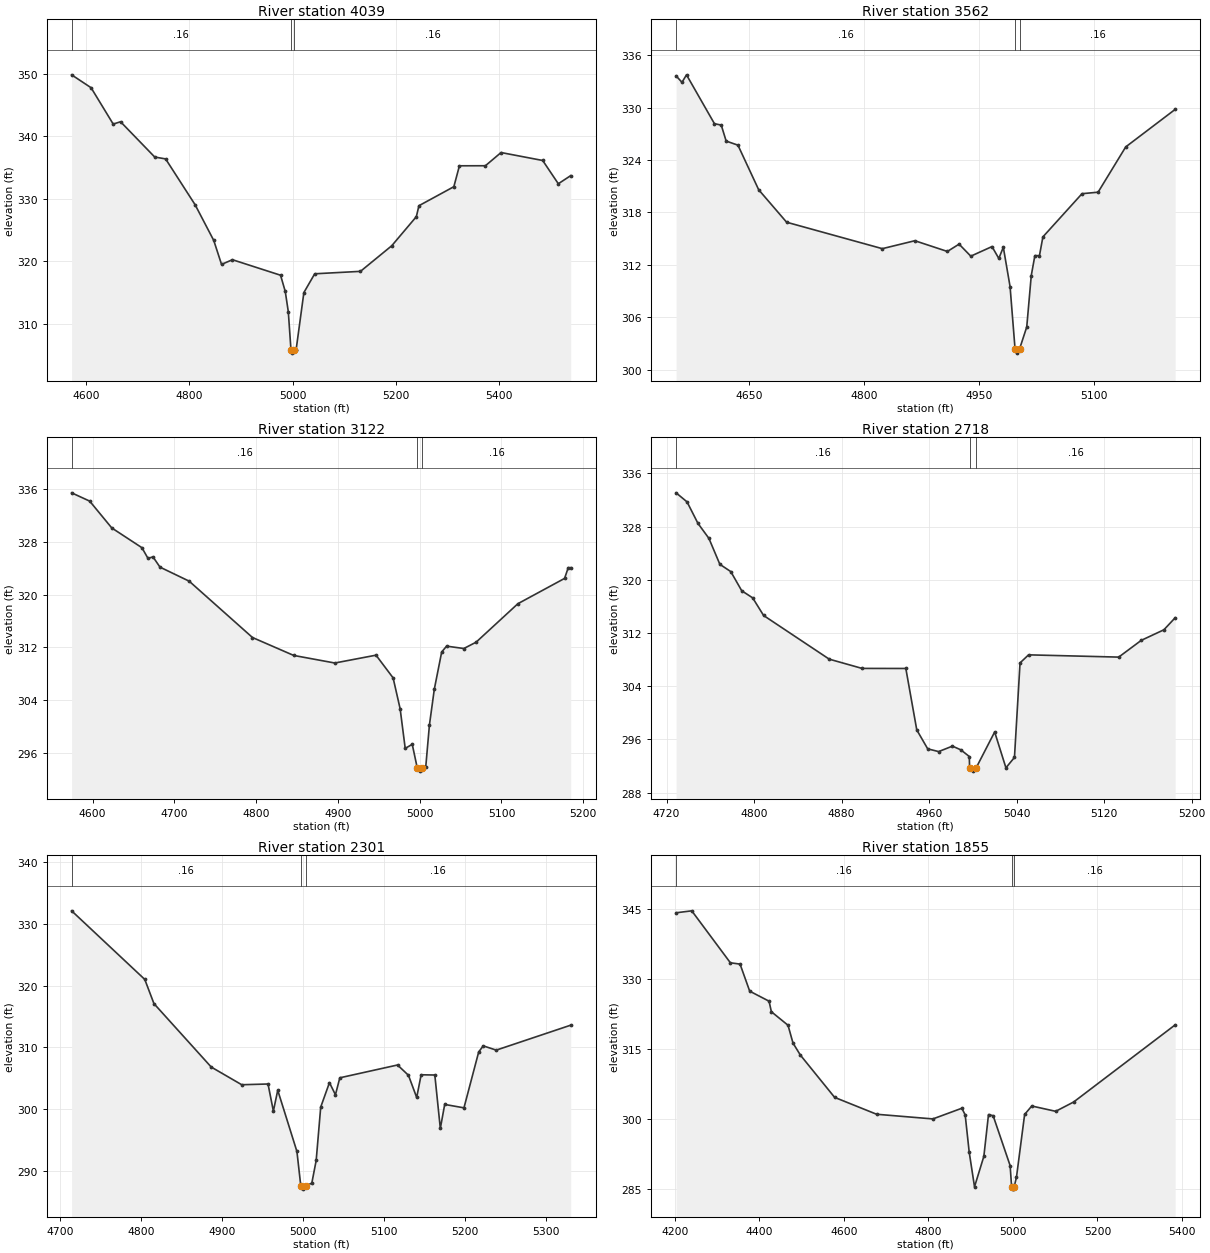
Type RM Length L Ch R = 1 ,4039    ,477,477,477
BEGIN DESCRIPTION:
UNT 123 IN BOCR 8.0
END DESCRIPTION:
XS GIS Cut Line= 3
       3738084.8     10633562.88      3737811.36     10633977.37
       3737874.3     10634443.99
#Sta/Elev= 30
  4571.8  349.81  4609.5  347.75  4652.4  341.94  4666.7  342.31  4732.9  336.67
    4754  336.37  4811.2  329.04  4847.3  323.34  4862.4  319.51  4883.5  320.26
  4976.8  317.78  4985.9  315.19  4991.8  311.96    4997  305.83  4999.8  305.33
    5003  305.83  5006.9  305.83    5022  315.01    5043  318.01  5131.7   318.4
  5192.3  322.49    5240  327.14    5245  328.89  5312.7  331.93  5323.5  335.27
  5373.9  335.28  5404.2  337.39  5484.9  336.12  5515.2   332.4  5539.2   333.7
#Mann= 3 ,-1 , 0
  4571.8     .16       0    4997     .16       0    5003     .16       0
Bank Sta=4997,5003
XS Rating Curve= 0 ,0
Exp/Cntr=0.3,0.1

Type RM Length L Ch R = 1 ,3562    ,440,440,440
BEGIN DESCRIPTION:
UNT 123 IN BOCR 7.0
END DESCRIPTION:
XS GIS Cut Line= 3
       3737849.6     10633460.19      3737449.61     10633710.19
      3737299.58     10633810.21
#Sta/Elev= 30
  4554.2  333.65  4561.9  332.91  4567.8  333.77  4604.3  328.17  4613.2  328.01
  4619.6  326.18    4635  325.71  4662.1   320.6  4698.6  316.88  4823.6  313.85
  4866.1  314.76  4908.6  313.53  4923.9  314.37  4939.2  312.99  4966.9  314.09
  4975.8  312.73  4981.7  314.01  4990.5  309.51    4997  302.38  4999.8  301.88
    5003  302.38  5012.3  304.88  5018.2  310.77  5022.9  313.05  5028.9  313.05
  5033.4   315.2  5084.5  320.15  5105.5  320.32  5141.6  325.51  5206.2  329.81
#Mann= 3 ,-1 , 0
  4554.2     .16       0    4997     .16       0    5003     .16       0
Bank Sta=4997,5003
XS Rating Curve= 0 ,0
Exp/Cntr=0.3,0.1

Type RM Length L Ch R = 1 ,3122    ,404,404,404
BEGIN DESCRIPTION:
UNT 123 IN BOCR 6.0
END DESCRIPTION:
XS GIS Cut Line= 3
      3737399.59     10633060.21      3737149.61     10633410.19
      3737049.59     10633560.22
#Sta/Elev= 30
  4574.3  335.44  4596.4  334.18  4623.4  330.11  4660.3  327.11  4667.7  325.49
  4673.8  325.72  4682.4  324.16  4718.1  322.03  4795.5  313.48  4845.9  310.76
  4896.2  309.61  4946.6   310.8  4967.5  307.35  4976.1  302.66  4982.3  296.65
  4990.9  297.27    4997   293.7  4999.8   293.2    5003   293.7  5007.4  293.81
  5011.9  300.19  5017.9  305.64  5026.9  311.28  5032.9  312.17    5054  311.81
    5069  312.77  5120.1  318.61  5177.2  322.45  5181.7  324.08  5184.7  324.08
#Mann= 3 ,-1 , 0
  4574.3     .16       0    4997     .16       0    5003     .16       0
Bank Sta=4997,5003
XS Rating Curve= 0 ,0
Exp/Cntr=0.3,0.1

Type RM Length L Ch R = 1 ,2718    ,417,417,417
BEGIN DESCRIPTION:
UNT 123 IN BOCR 5.0
END DESCRIPTION:
XS GIS Cut Line= 3
      3736899.61     10632910.18      3736899.61     10633160.19
       3736849.6     10633360.22
#Sta/Elev= 30
  4728.7  333.08  4738.7  331.72  4748.7  328.48  4758.7  326.23  4768.7  322.33
  4778.7  321.23  4788.7  318.35  4798.7  317.28  4808.7  314.63  4868.7  308.06
  4898.7  306.67  4938.7  306.66  4948.7  297.42  4958.7  294.57  4968.7  294.16
  4981.3  294.98    4989  294.42  4996.7  293.42    4997  291.72  4999.8  291.22
    5003  291.72  5019.9  297.11  5030.2  291.72    5038  293.28  5043.1   307.5
  5050.9  308.71  5133.3  308.37  5153.9  310.89  5174.6  312.48  5184.9  314.29
#Mann= 3 ,-1 , 0
  4728.7     .16       0    4997     .16       0    5003     .16       0
Bank Sta=4997,5003
XS Rating Curve= 0 ,0
Exp/Cntr=0.3,0.1

Type RM Length L Ch R = 1 ,2301    ,446,446,446
BEGIN DESCRIPTION:
UNT 123 IN BOCR 4.0
END DESCRIPTION:
XS GIS Cut Line= 2
      3736863.39     10632868.26      3736294.77     10633106.99
#Sta/Elev= 30
  4713.8  332.07  4804.2  320.99  4815.5  317.09  4886.3  306.84    4924  303.98
  4956.5   304.1  4963.1  299.72  4968.5  303.09  4992.2   293.2    4997  287.62
  4999.8  287.12    5003  287.62  5010.6  288.09    5016  291.75  5021.6  300.37
  5032.4  304.32  5039.8  302.36  5045.2   305.1  5116.5  307.17    5130  305.51
  5140.2  301.92  5145.7  305.59  5162.6  305.55  5169.4  296.92  5174.8   300.8
  5198.6  300.25  5216.8  309.27  5222.4  310.26  5238.5  309.57  5330.5   313.6
#Mann= 3 ,-1 , 0
  4713.8     .16       0    4997     .16       0    5003     .16       0
Bank Sta=4997,5003
XS Rating Curve= 0 ,0
Exp/Cntr=0.3,0.1

Type RM Length L Ch R = 1 ,1855    ,398,398,398
BEGIN DESCRIPTION:
UNT 123 IN BOCR 3.0
END DESCRIPTION:
XS GIS Cut Line= 3
      3736649.63     10631960.15      3736299.61     10632710.19
      3736049.64     10632960.16
#Sta/Elev= 30
  4202.9  344.23    4240  344.65  4331.4  333.51  4354.3  333.23  4377.1  327.43
  4422.9  325.28  4428.4  323.02  4467.8  320.12  4479.6   316.3    4497  313.73
  4578.1  304.66  4677.5  301.04  4810.7  300.04  4879.2  302.33  4887.1  300.91
  4896.6  292.93  4909.2  285.49  4931.3  292.02  4942.3  300.98  4953.3  300.72
  4993.5  290.03    4997  285.49  4999.8  284.99    5003  285.49  5008.5  287.54
  5027.8     301  5044.7  302.81  5101.3  301.67  5143.7  303.66  5384.1   320.2
#Mann= 3 ,-1 , 0
  4202.9     .16       0    4997     .16       0    5003     .16       0
Bank Sta=4997,5003
XS Rating Curve= 0 ,0
Exp/Cntr=0.3,0.1

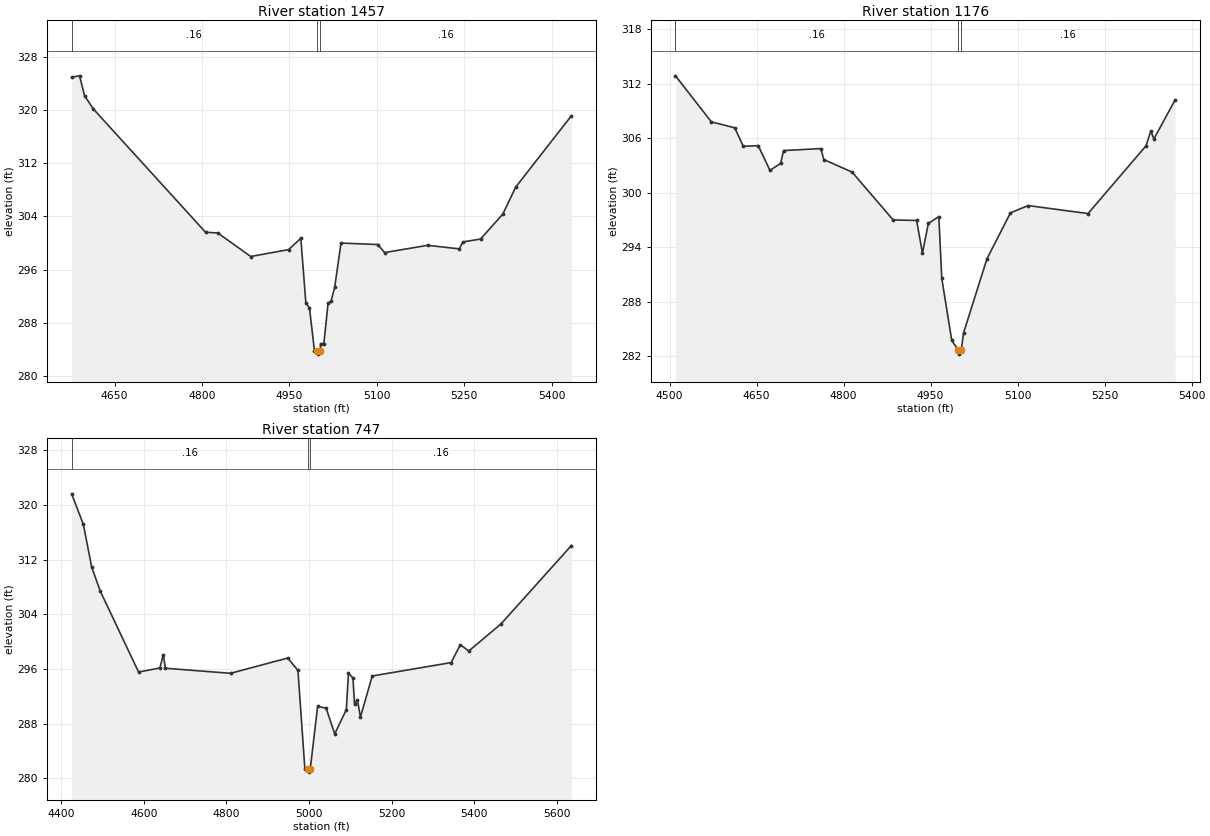
Type RM Length L Ch R = 1 ,1457    ,281,281,281
BEGIN DESCRIPTION:
UNT 123 IN BOCR 2.0
END DESCRIPTION:
XS GIS Cut Line= 3
      3736249.59     10632110.22      3735999.61     10632460.19
       3735849.6     10632860.21
#Sta/Elev= 30
  4576.3  324.93  4589.8  325.13  4598.4  322.17  4613.1  320.19  4806.1  301.62
    4827  301.52  4883.5  297.98  4948.6  299.02  4969.5  300.71  4978.1  291.02
  4984.3  290.26  4992.9  283.81    4997  283.81  4999.8  283.31    5003  283.81
  5003.3  284.88    5009  284.88  5016.2  290.94  5021.5   291.3  5027.7  293.42
  5038.4     300  5101.6  299.78  5113.2  298.57    5187  299.66  5241.3  299.13
  5247.6  300.17  5277.8   300.6  5316.1  304.36  5338.3  308.43  5433.6  319.12
#Mann= 3 ,-1 , 0
  4576.3     .16       0    4997     .16       0    5003     .16       0
Bank Sta=4997,5003
XS Rating Curve= 0 ,0
Exp/Cntr=0.3,0.1

Type RM Length L Ch R = 1 ,1176    ,429,429,429
BEGIN DESCRIPTION:
Mapping XS 742f0fa0
END DESCRIPTION:
XS GIS Cut Line= 3
      3735821.68      10631909.1      3735739.22     10632464.63
       3735791.3     10632759.76
#Sta/Elev= 30
  4510.3  312.85  4572.1  307.79  4612.5  307.13  4627.1   305.1  4652.9  305.17
  4673.1  302.45  4691.5  303.22  4696.6  304.63  4760.9  304.85    4766  303.64
  4814.7  302.26  4885.5     297  4925.9  296.94    4936  293.35  4946.1  296.61
  4964.2  297.37  4969.3  290.57  4986.5  283.75    4997  282.74  4999.8  282.24
    5003  282.74  5006.8  284.57  5047.2  292.73  5087.7  297.78  5118.2  298.58
  5221.4   297.7  5321.3  305.15  5329.7  306.79  5334.8   305.9  5371.6  310.21
#Mann= 3 ,-1 , 0
  4510.3     .16       0    4997     .16       0    5003     .16       0
Bank Sta=4997,5003
XS Rating Curve= 0 ,0
Exp/Cntr=0.3,0.1

Type RM Length L Ch R = 1 ,747     ,0,0,0
BEGIN DESCRIPTION:
UNT 123 IN BOCR 1.0
END DESCRIPTION:
XS GIS Cut Line= 3
       3735500.5     10631783.22      3735331.24     10632442.93
      3735734.35     10632785.36
#Sta/Elev= 30
  4425.2  321.64  4453.6  317.15  4473.7  310.92  4494.3  307.42  4587.3  295.54
  4638.9  296.15  4647.1  298.09  4652.2   296.1  4810.1  295.36  4948.6   297.6
  4973.2  295.78  4989.9  281.39    4997  281.39  4999.8  280.89    5003  281.39
  5020.9  290.52  5041.5  290.25  5062.2  286.49  5090.3  290.04  5095.5  295.38
  5106.3  294.69  5110.2  290.89  5117.3  291.44  5124.5  288.95  5153.1  294.97
  5344.2  296.93  5366.2  299.55    5387  298.63    5465   302.6  5635.2  314.06
#Mann= 3 ,-1 , 0
  4425.2     .16       0    4997     .16       0    5003     .16       0
Bank Sta=4997,5003
XS Rating Curve= 0 ,0
Exp/Cntr=0.3,0.1

Chan Stop Cuts=-1
Use User Specified Reach Order=0
Composite Channel Slope=5