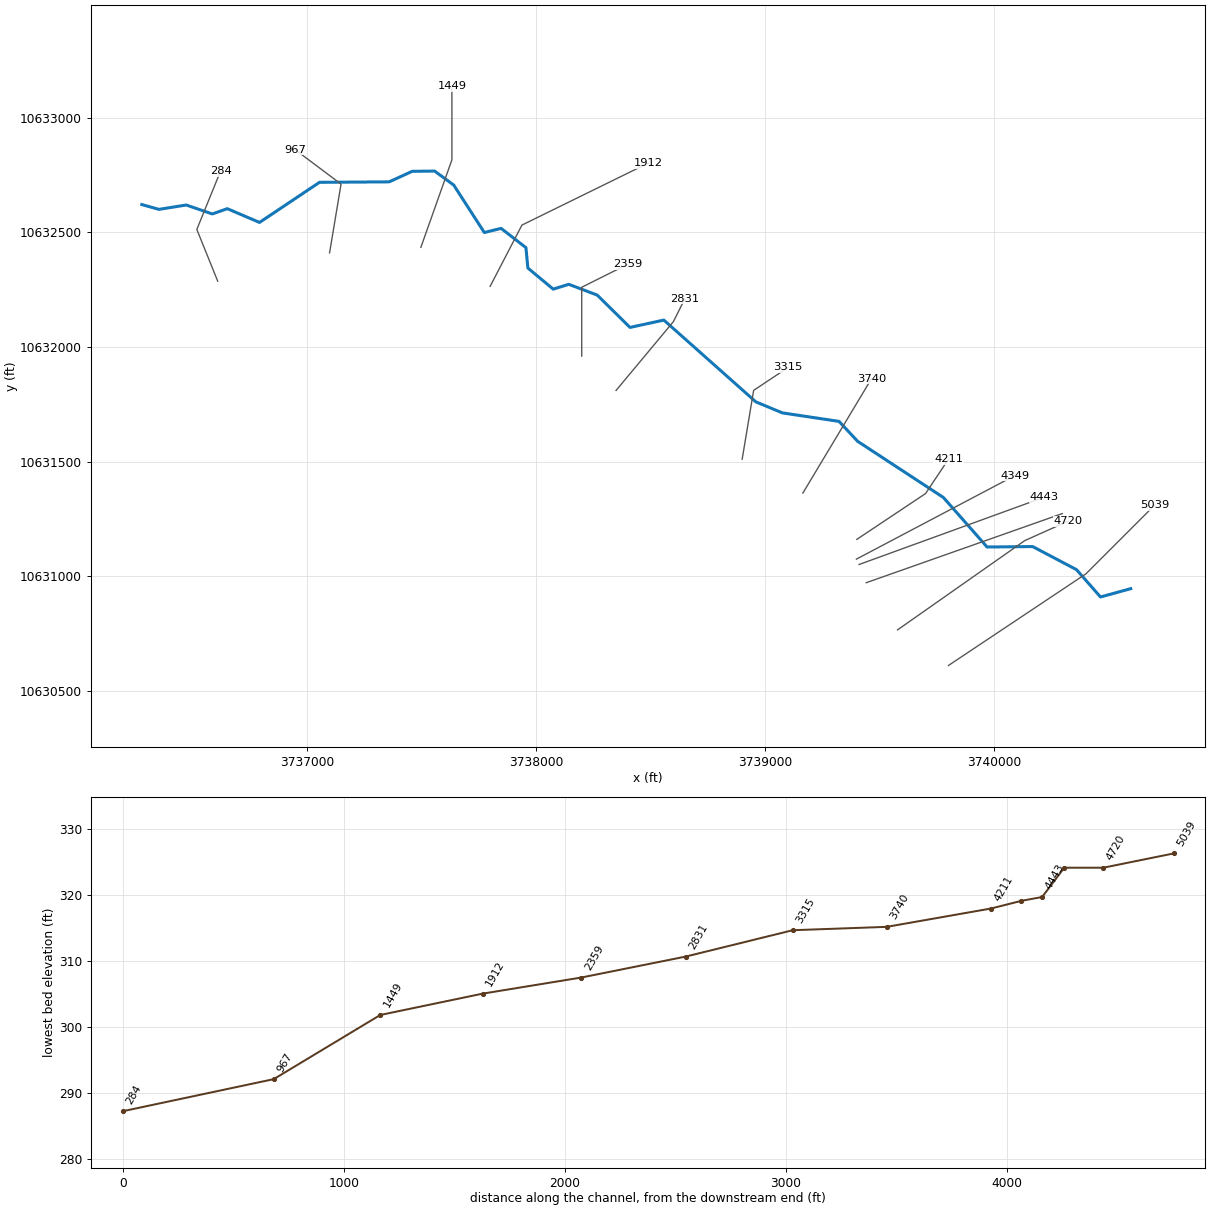
--- UNT 124 IN BOCR.prj (project) ---

Proj Title=UNT 124 IN BOCR Base Level Engineering
Current Plan=p01
Default Exp/Contr=0.3,0.1
English Units
Geom File=g01
Flow File=f01
Plan File=p01
Y Axis Title=Elevation
X Axis Title(PF)=Main Channel Distance
X Axis Title(XS)=Station
BEGIN DESCRIPTION:
UNT 124 IN BOCR
END DESCRIPTION:
DSS Export Rating Curves= 0
DSS Export Rating Curve Sorted= 0
DSS Export Volume Flow Curves= 0
DXF OffsetX= 0
DXF OffsetY= 0
DXF ScaleX= 1
DXF ScaleY= 10

--- UNT 124 IN BOCR.p01 (plan) ---

Plan Title=Multiple Run
Short Identifier=Multiple
Geom File=g01
Flow File=f01
Subcritical Flow
K Sum by GR= 0
Std Step Tol= 0.01
Critical Tol= 0.01
Num of Std Step Trials= 20
Max Error Tol= 0.3
Flow Tol Ratio= 0.001
Split Flow NTrial= 30
Split Flow Tol= 0.02
Split Flow Ratio= 0.02
Log Output Level= 0
Friction Slope Method= 1
Unsteady Friction Slope Method= 2
Unsteady Bridges Friction Slope Method= 1
Parabolic Critical Depth
Global Vel Dist=  1 , 1 , 1
Global Log Level= 0
CheckData=True
Encroach Param= -1, 0, 0, 0
BEGIN DESCRIPTION:
Multiple Run
END DESCRIPTION:

--- UNT 124 IN BOCR.f01 (steady flow) ---

Flow Title=Multiple
Program Version=4.10
Number of Profiles= 7
Profile Names=10-year,25-year,50-year,1pct_min,100-year,1pct_plu,500-year
River Rch & RM=UNT 124 IN BOCR,Reach-1         ,5039
     490     652     784     694     938    1269    1347
Boundary for River Rch & Prof#=UNT 124 IN BOCR,Reach-1         , 1
Up Type= 0
Dn Type= 3
Dn Slope=0.005
Boundary for River Rch & Prof#=UNT 124 IN BOCR,Reach-1         , 2
Up Type= 0
Dn Type= 3
Dn Slope=0.005
Boundary for River Rch & Prof#=UNT 124 IN BOCR,Reach-1         , 3
Up Type= 0
Dn Type= 3
Dn Slope=0.005
Boundary for River Rch & Prof#=UNT 124 IN BOCR,Reach-1         , 4
Up Type= 0
Dn Type= 3
Dn Slope=0.005
Boundary for River Rch & Prof#=UNT 124 IN BOCR,Reach-1         , 5
Up Type= 0
Dn Type= 3
Dn Slope=0.005
Boundary for River Rch & Prof#=UNT 124 IN BOCR,Reach-1         , 6
Up Type= 0
Dn Type= 3
Dn Slope=0.005
Boundary for River Rch & Prof#=UNT 124 IN BOCR,Reach-1         , 7
Up Type= 0
Dn Type= 3
Dn Slope=0.005
DSS Import GetInterval= 0
DSS Import GetPeak= 0
DSS Import FillOption= 0

--- UNT 124 IN BOCR.g01 (geometry) ---

Geom Title=Existing Conditions
Program Version=4.10

River Reach=UNT 124 IN BOCR ,Reach-1
Reach XY= 30
       3740594.7     10630945.26      3740462.75       10630909.
       3740358.5       10631028.      3740166.75       10631129.
        3739968.       10631127.       3739777.5       10631343.
       3739403.5       10631588.      3739322.25       10631675.
       3739075.5       10631712.       3738959.5       10631760.
        3738558.       10632117.      3738410.25       10632085.
      3738267.25       10632226.      3738143.25       10632273.
      3738075.25       10632252.      3737964.75       10632344.
      3737956.25       10632433.        3737848.       10632517.
      3737774.75       10632499.      3737641.25       10632706.
        3737558.       10632767.      3737460.25       10632766.
       3737359.5       10632720.      3737055.75       10632718.
        3736794.       10632543.       3736653.5       10632603.
        3736588.       10632580.      3736474.25       10632619.
        3736355.       10632600.       3736280.5       10632621.

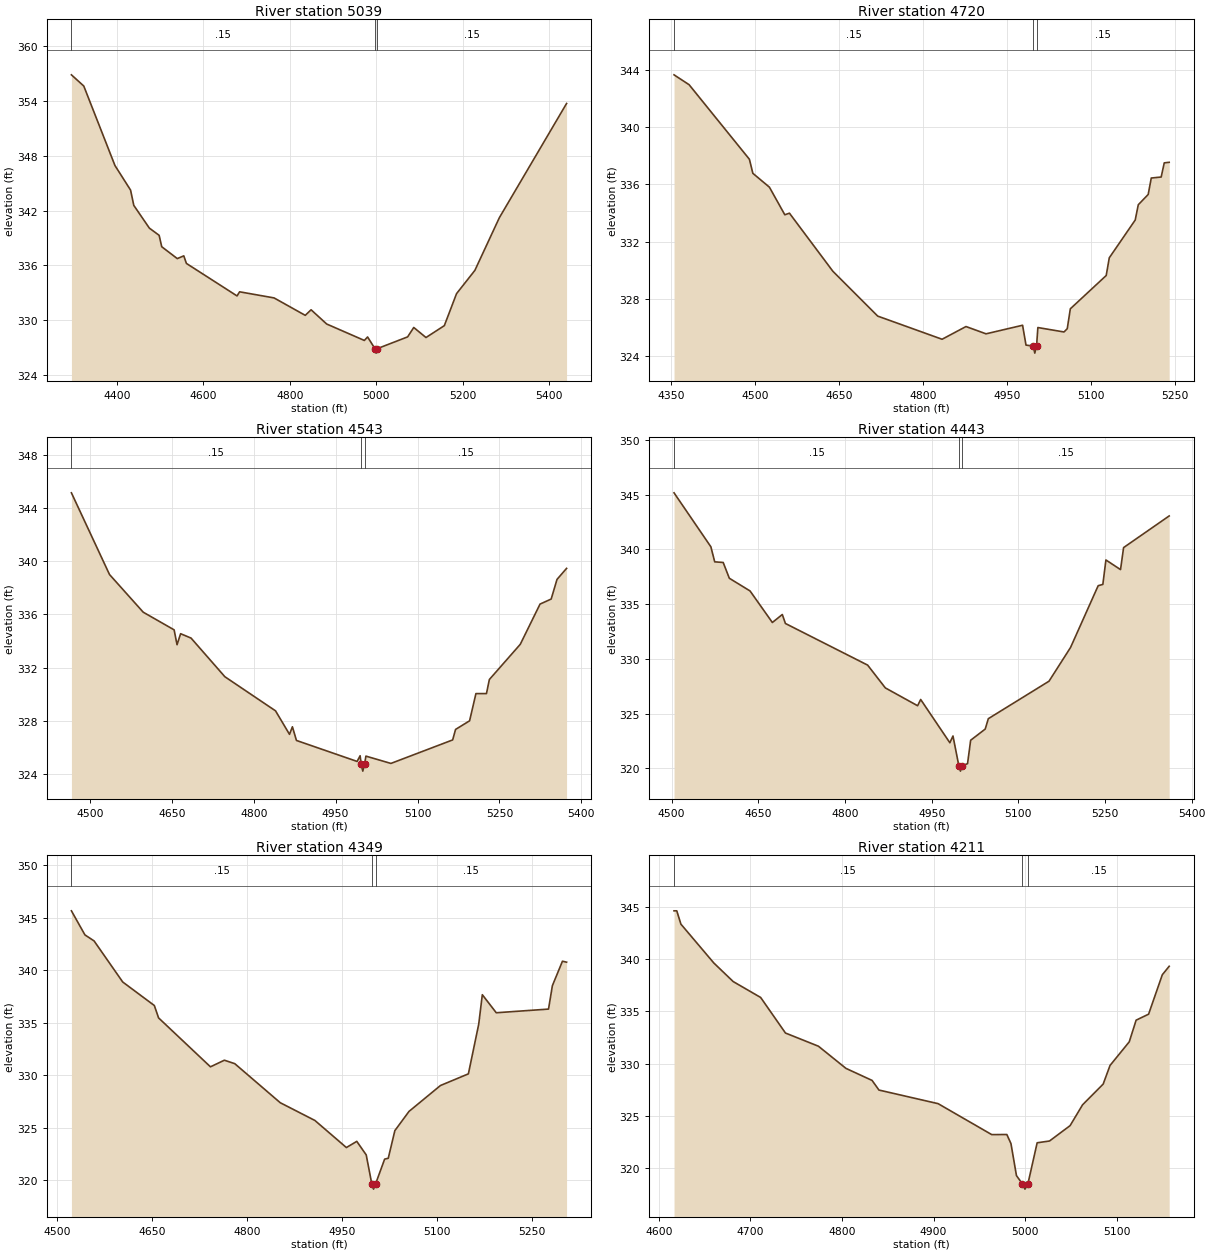
Type RM Length L Ch R = 1 ,5039    ,319,319,319
BEGIN DESCRIPTION:
UNT 124 IN BOCR 11.0
END DESCRIPTION:
XS GIS Cut Line= 3
      3739799.57     10630610.16      3740399.61     10631010.19
      3740699.59     10631310.17
#Sta/Elev= 30
    4295  356.87  4323.6  355.64  4395.7  346.93  4431.8  344.24  4439.3  342.56
  4475.3  340.07  4497.9  339.28  4503.9  338.03  4539.9  336.73  4554.9  337.03
    4561   336.2  4678.1  332.64  4684.1  333.09  4763.8  332.42  4835.9  330.51
  4849.4  331.12  4885.5  329.56  4972.6  327.76  4980.1  328.14    4997  326.87
  4999.8  326.37    5003  326.87  5072.7  328.15  5086.9  329.18  5115.2  328.08
  5157.6  329.38  5185.9  332.89  5228.3  335.44  5284.9  341.21  5440.4  353.73
#Mann= 3 ,-1 , 0
    4295     .15       0    4997     .05       0    5003     .15       0
Bank Sta=4997,5003
XS Rating Curve= 0 ,0
Exp/Cntr=0.3,0.1

Type RM Length L Ch R = 1 ,4720    ,177,177,177
BEGIN DESCRIPTION:
Mapping XS 0b84939d
END DESCRIPTION:
XS GIS Cut Line= 3
       3739577.6     10630765.53      3740132.33     10631154.89
       3740321.1     10631239.51
#Sta/Elev= 30
  4355.3  343.67  4382.2  342.98    4490  337.76  4496.1  336.78  4525.7  335.81
  4553.2  333.88  4561.5  333.99    4639  329.93  4719.2  326.79  4834.2  325.17
  4876.9  326.06  4912.7  325.55    4978  326.15  4984.1  324.76    4997   324.7
  4999.8   324.2    5003   324.7  5005.3  325.99    5052  325.68  5057.8  325.91
  5063.3   327.3  5127.4  329.63  5132.9  330.87  5179.2  333.51  5184.7  334.58
  5202.4   335.3  5207.9  336.45  5225.6  336.52  5231.1  337.51  5239.9  337.55
#Mann= 3 ,-1 , 0
  4355.3     .15       0    4997     .05       0    5003     .15       0
Bank Sta=4997,5003
XS Rating Curve= 0 ,0
Exp/Cntr=0.3,0.1

Type RM Length L Ch R = 1 ,4543    ,100,100,100
BEGIN DESCRIPTION:
Mapping XS 38872fc3
END DESCRIPTION:
XS GIS Cut Line= 2
      3739440.96      10630971.3      3740296.16     10631272.83
#Sta/Elev= 30
  4466.2  345.16  4535.9  339.01  4597.7  336.17  4654.3  334.84  4659.6  333.72
  4666.2  334.55  4685.3  334.22  4747.2  331.31    4840  328.74  4865.6  326.97
  4870.9  327.54  4878.3  326.51  4989.4  324.93  4994.9  325.36    4997   324.7
  4999.8   324.2    5003   324.7  5005.5  325.33  5051.3  324.78  5164.4  326.55
  5169.7  327.34  5195.4  327.99    5207  330.04  5226.3  330.04  5231.6   331.1
  5288.2  333.75  5324.4  336.78  5344.8  337.16  5355.5  338.64    5373  339.47
#Mann= 3 ,-1 , 0
  4466.2     .15       0    4997     .05       0    5003     .15       0
Bank Sta=4997,5003
XS Rating Curve= 0 ,0
Exp/Cntr=0.3,0.1

Type RM Length L Ch R = 1 ,4443    ,94,94,94
BEGIN DESCRIPTION:
UNT 124 IN BOCR 10.0
END DESCRIPTION:
XS GIS Cut Line= 2
      3739409.65     10631050.71      3740215.09     10631343.48
#Sta/Elev= 30
  4504.1  345.16  4567.9  340.23  4574.5  338.86  4589.2   338.8  4599.8  337.36
  4635.7   336.2  4674.3  333.32  4691.5  334.05  4696.9  333.23  4839.2  329.43
  4869.8  327.35  4925.7  325.72    4931  326.29  4981.5  322.34  4986.9  322.96
    4997  320.25  4999.8  319.75    5003  320.25  5012.1  320.43  5017.5  322.57
  5042.7  323.59  5048.1  324.54  5153.1  327.96  5190.4  331.04  5238.2  336.68
  5246.3   336.8  5251.6  339.03  5276.9  338.15  5282.2  340.16  5361.1  343.05
#Mann= 3 ,-1 , 0
  4504.1     .15       0    4997     .05       0    5003     .15       0
Bank Sta=4997,5003
XS Rating Curve= 0 ,0
Exp/Cntr=0.3,0.1

Type RM Length L Ch R = 1 ,4349    ,138,138,138
BEGIN DESCRIPTION:
Mapping XS 168ace37
END DESCRIPTION:
XS GIS Cut Line= 2
      3739397.93     10631074.14      3740089.39     10631438.75
#Sta/Elev= 30
  4522.8  345.68  4544.1  343.39  4558.6  342.81  4603.8   338.9  4653.7  336.66
  4660.4  335.48  4742.3  330.82  4764.3  331.45  4780.7  331.12  4852.5   327.4
  4907.2  325.71  4956.9  323.13  4973.3  323.72  4988.2  322.43    4997  319.67
  4999.8  319.17    5003  319.67  5017.3  322.03    5023  322.11  5033.4  324.74
  5055.7  326.57  5105.4  329.04  5149.5  330.15  5165.8  334.88  5171.5  337.69
  5193.5  335.97    5276  336.32  5282.1  338.55    5298  340.88  5304.5  340.79
#Mann= 3 ,-1 , 0
  4522.8     .15       0    4997     .05       0    5003     .15       0
Bank Sta=4997,5003
XS Rating Curve= 0 ,0
Exp/Cntr=0.3,0.1

Type RM Length L Ch R = 1 ,4211    ,471,471,471
BEGIN DESCRIPTION:
UNT 124 IN BOCR 9.0
END DESCRIPTION:
XS GIS Cut Line= 3
      3739399.63     10631160.21      3739699.61     10631360.19
      3739799.61     10631510.19
#Sta/Elev= 30
  4616.5   344.6  4619.5   344.6    4624  343.33    4660  339.61  4681.1  337.84
  4711.1  336.32  4738.2  332.92  4774.2  331.66  4804.3  329.54  4832.8  328.39
  4840.3  327.47  4904.9  326.17  4963.5  323.21    4980  323.22  4984.5  322.35
  4990.5  319.29    4997   318.5  4999.8     318    5003   318.5  5013.1  322.43
  5026.6   322.6  5049.1  324.07  5062.7  326.06  5085.2  328.04  5092.7  329.82
  5113.7  332.08  5121.2  334.15  5134.8  334.72  5149.8  338.49  5157.3   339.3
#Mann= 3 ,-1 , 0
  4616.5     .15       0    4997     .05       0    5003     .15       0
Bank Sta=4997,5003
XS Rating Curve= 0 ,0
Exp/Cntr=0.3,0.1

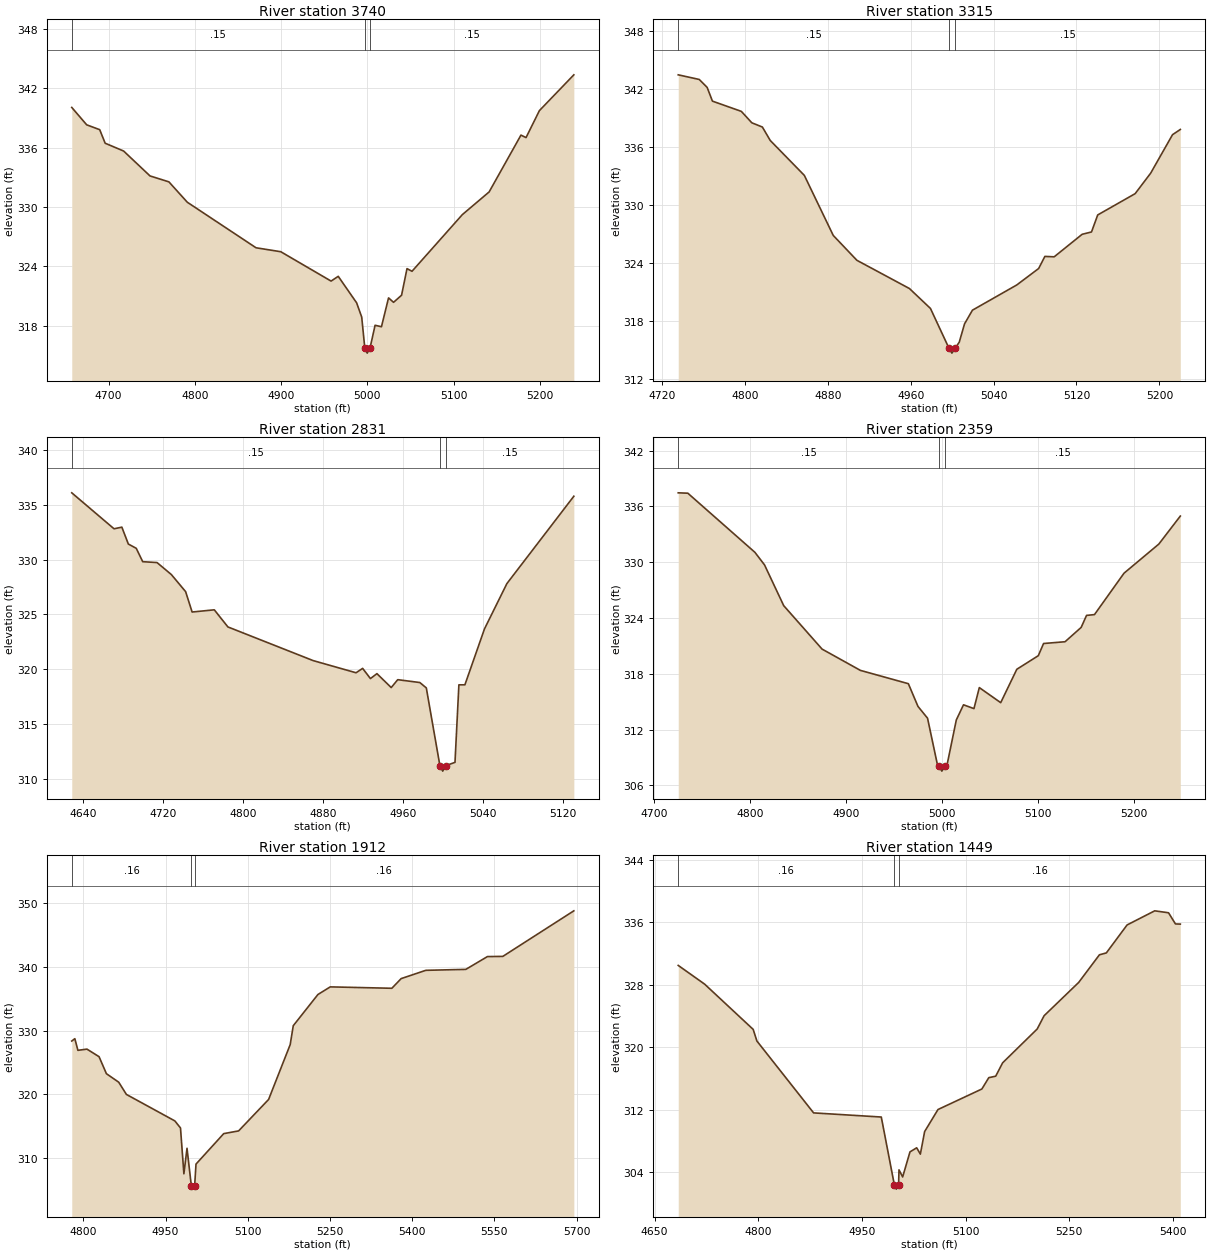
Type RM Length L Ch R = 1 ,3740    ,425,425,425
BEGIN DESCRIPTION:
UNT 124 IN BOCR 8.0
END DESCRIPTION:
XS GIS Cut Line= 2
      3739164.47     10631362.39      3739463.91     10631861.45
#Sta/Elev= 30
  4657.3  340.08  4674.6  338.32  4689.7  337.83    4696  336.46  4717.4  335.67
    4748  333.15  4769.9  332.55  4791.2  330.49  4870.9  325.88  4899.6  325.48
  4957.9  322.51  4966.2  322.99  4987.5  320.31  4993.4  318.87    4997  315.72
  4999.8  315.22    5003  315.72  5008.9  318.04  5016.3  317.89  5024.5  320.81
  5030.3  320.36  5039.6  321.08  5045.9  323.77  5051.7   323.5    5110  329.23
  5141.1  331.53    5178  337.28  5183.9  337.03  5199.4  339.76  5239.3  343.38
#Mann= 3 ,-1 , 0
  4657.3     .15       0    4997     .05       0    5003     .15       0
Bank Sta=4997,5003
XS Rating Curve= 0 ,0
Exp/Cntr=0.3,0.1

Type RM Length L Ch R = 1 ,3315    ,484,484,484
BEGIN DESCRIPTION:
UNT 124 IN BOCR 7.0
END DESCRIPTION:
XS GIS Cut Line= 3
       3738899.6     10631510.14      3738949.61     10631810.19
      3739099.64     10631910.21
#Sta/Elev= 30
  4735.7  343.49    4756  343.01  4763.6  342.19  4768.7  340.77  4796.6  339.71
  4806.7  338.53  4816.9  338.09  4824.5   336.7  4857.4  333.09  4885.3  326.88
  4908.1  324.31  4958.8  321.39  4979.1  319.33    4997  315.21  4999.8  314.71
    5003  315.21  5006.9  315.85    5012  317.74  5019.6  319.15  5062.4  321.76
  5083.5  323.46  5089.5  324.71  5098.5  324.67  5125.5     327  5134.5  327.24
  5140.5     329  5176.6   331.2  5191.6  333.32  5212.7   337.3  5220.2  337.84
#Mann= 3 ,-1 , 0
  4735.7     .15       0    4997     .05       0    5003     .15       0
Bank Sta=4997,5003
XS Rating Curve= 0 ,0
Exp/Cntr=0.3,0.1

Type RM Length L Ch R = 1 ,2831    ,472,472,472
BEGIN DESCRIPTION:
UNT 124 IN BOCR 6.0
END DESCRIPTION:
XS GIS Cut Line= 3
       3738349.6     10631810.17      3738599.61     10632110.19
      3738649.59     10632210.16
#Sta/Elev= 30
  4628.7  336.09    4671  332.81  4678.8  332.96  4685.3  331.42  4693.2  331.03
  4699.7  329.81    4714  329.73  4728.3  328.64  4742.6  327.08  4749.1  325.22
  4771.3  325.42  4784.9  323.86  4870.2  320.79  4913.1  319.68  4919.7  320.08
  4927.5  319.15    4934   319.6  4948.3  318.33  4954.8  319.05  4976.9  318.79
  4983.4   318.3    4997  311.21  4999.8  310.71    5003  311.21  5012.1  311.51
    5016  318.58    5022  318.58  5041.6  323.68    5064  327.81    5131  335.78
#Mann= 3 ,-1 , 0
  4628.7     .15       0    4997     .05       0    5003     .15       0
Bank Sta=4997,5003
XS Rating Curve= 0 ,0
Exp/Cntr=0.3,0.1

Type RM Length L Ch R = 1 ,2359    ,447,447,447
BEGIN DESCRIPTION:
UNT 124 IN BOCR 5.0
END DESCRIPTION:
XS GIS Cut Line= 3
      3738199.61      10631960.2      3738199.61     10632260.19
      3738399.62     10632360.19
#Sta/Elev= 30
  4724.9  337.45  4734.9  337.41  4804.9  331.05  4814.9   329.7  4834.9  325.32
  4874.9  320.65  4914.9  318.36  4964.9  316.93  4974.9  314.49  4984.9  313.22
  4994.9  308.37    4997  308.03  4999.8  307.53    5003  308.03  5004.9  308.03
  5014.9  313.03  5022.4  314.66  5033.3  314.25  5038.9  316.51  5061.2  314.89
    5078  318.48  5100.4  319.94  5105.9  321.25  5128.3  321.44  5145.1  322.98
  5150.7  324.27    5159  324.36  5189.8  328.81  5226.1  331.94  5248.5  334.95
#Mann= 3 ,-1 , 0
  4724.9     .15       0    4997     .05       0    5003     .15       0
Bank Sta=4997,5003
XS Rating Curve= 0 ,0
Exp/Cntr=0.3,0.1

Type RM Length L Ch R = 1 ,1912    ,463,463,463
BEGIN DESCRIPTION:
UNT 124 IN BOCR 4.0
END DESCRIPTION:
XS GIS Cut Line= 3
        3737800.     10632264.13      3737938.88     10632531.47
      3738490.97     10632802.31
#Sta/Elev= 30
  4778.8  328.35  4784.4  328.72    4790  326.89  4806.5  327.08  4828.6  325.89
    4842  323.22  4864.5  321.88  4878.5  319.96  4966.9   315.8  4977.2  314.69
  4983.4  307.49  4989.1   311.5    4997  305.58  4999.8  305.08    5003  305.58
  5005.5  309.01  5056.1   313.8  5083.3  314.23    5138  319.17  5177.4  327.79
    5183  330.76    5228  335.66  5250.5  336.86  5362.9  336.64  5379.9  338.16
  5424.8  339.46  5497.9  339.61  5537.3  341.62  5565.4  341.65    5695  348.81
#Mann= 3 ,-1 , 0
  4778.8     .16       0    4997     .16       0    5003     .16       0
Bank Sta=4997,5003
XS Rating Curve= 0 ,0
Exp/Cntr=0.3,0.1

Type RM Length L Ch R = 1 ,1449    ,482,482,482
BEGIN DESCRIPTION:
UNT 124 IN BOCR 3.0
END DESCRIPTION:
XS GIS Cut Line= 3
      3737497.91     10632434.27      3737633.32     10632816.19
      3737633.32     10633137.18
#Sta/Elev= 30
  4684.3  330.48  4722.4  328.09  4792.7  322.29  4798.1   320.8  4880.1   311.6
    4978  311.07    4997  302.34  4999.8  301.84    5003  302.34  5003.6  304.31
  5008.9   303.4  5019.5  306.61  5029.2  307.13  5034.5  306.32  5040.7  309.21
    5060  312.03  5123.5  314.66  5133.5  316.11  5143.5   316.3  5153.5  318.01
  5203.5  322.34  5213.5  324.04  5263.5   328.3  5293.5  331.84  5303.5  332.08
  5333.5  335.66  5373.5  337.47  5393.5  337.22  5403.5  335.79  5410.5  335.77
#Mann= 3 ,-1 , 0
  4684.3     .16       0    4997     .16       0    5003     .16       0
Bank Sta=4997,5003
XS Rating Curve= 0 ,0
Exp/Cntr=0.3,0.1

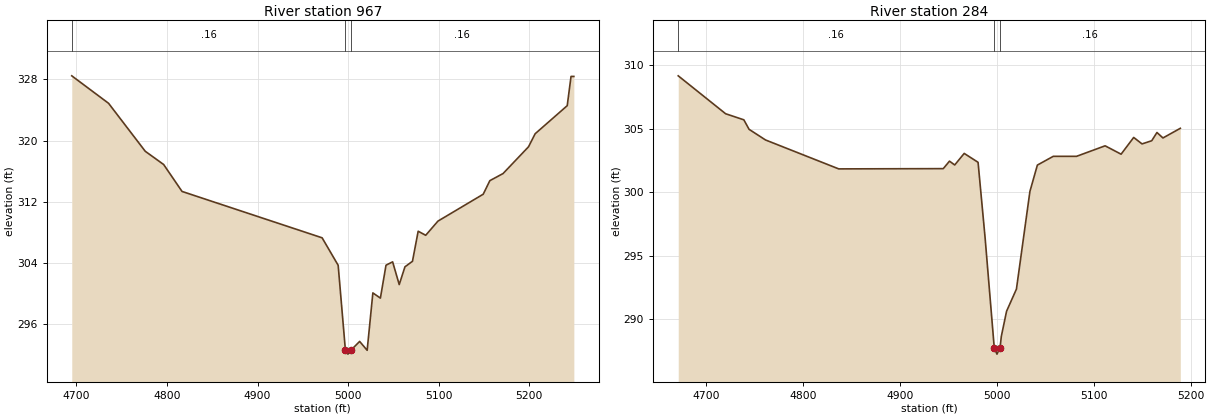
Type RM Length L Ch R = 1 ,967     ,683,683,683
BEGIN DESCRIPTION:
UNT 124 IN BOCR 2.0
END DESCRIPTION:
XS GIS Cut Line= 3
      3737099.61     10632410.18      3737149.61     10632710.19
      3736949.64     10632860.16
#Sta/Elev= 30
    4695  328.47  4735.6  324.88  4776.1  318.61  4796.4  316.88  4816.7  313.36
  4971.3   307.3    4989  303.71    4997   292.6  4999.8   292.1    5003   292.6
  5012.7  293.76    5021   292.6  5027.3   300.1  5035.6  299.42  5041.8  303.72
  5049.1  304.16  5056.4  301.19  5062.7  303.51    5071  304.23  5077.3  308.16
  5085.6  307.63  5099.1  309.48  5149.1     313  5156.4  314.77    5171   315.7
  5199.1   319.2  5206.4   320.9  5241.8  324.57    5246  328.39  5249.1  328.39
#Mann= 3 ,-1 , 0
    4695     .16       0    4997     .16       0    5003     .16       0
Bank Sta=4997,5003
XS Rating Curve= 0 ,0
Exp/Cntr=0.3,0.1

Type RM Length L Ch R = 1 ,284     ,0,0,0
BEGIN DESCRIPTION:
UNT 124 IN BOCR 1.0
END DESCRIPTION:
XS GIS Cut Line= 3
      3736611.64     10632286.64      3736520.47     10632512.37
      3736623.96     10632766.78
#Sta/Elev= 30
  4670.9  309.18  4719.8  306.19  4738.6  305.71    4744  304.96    4761  304.12
  4836.5  301.84  4944.4  301.86  4950.8  302.45  4956.2  302.15    4966  303.06
  4980.3  302.36  4987.6  296.37    4997  287.73  4999.8  287.23    5003  287.73
  5004.3  288.63  5009.7  290.61  5019.9  292.36  5033.8  300.06  5041.5  302.14
  5057.9  302.83  5081.9  302.83  5111.4  303.66  5127.9     303  5140.9  304.32
  5149.5  303.81  5159.5  304.06  5164.9  304.71  5171.1  304.28    5189  305.04
#Mann= 3 ,-1 , 0
  4670.9     .16       0    4997     .16       0    5003     .16       0
Bank Sta=4997,5003
XS Rating Curve= 0 ,0
Exp/Cntr=0.3,0.1

Chan Stop Cuts=-1
Use User Specified Reach Order=0
Composite Channel Slope=5