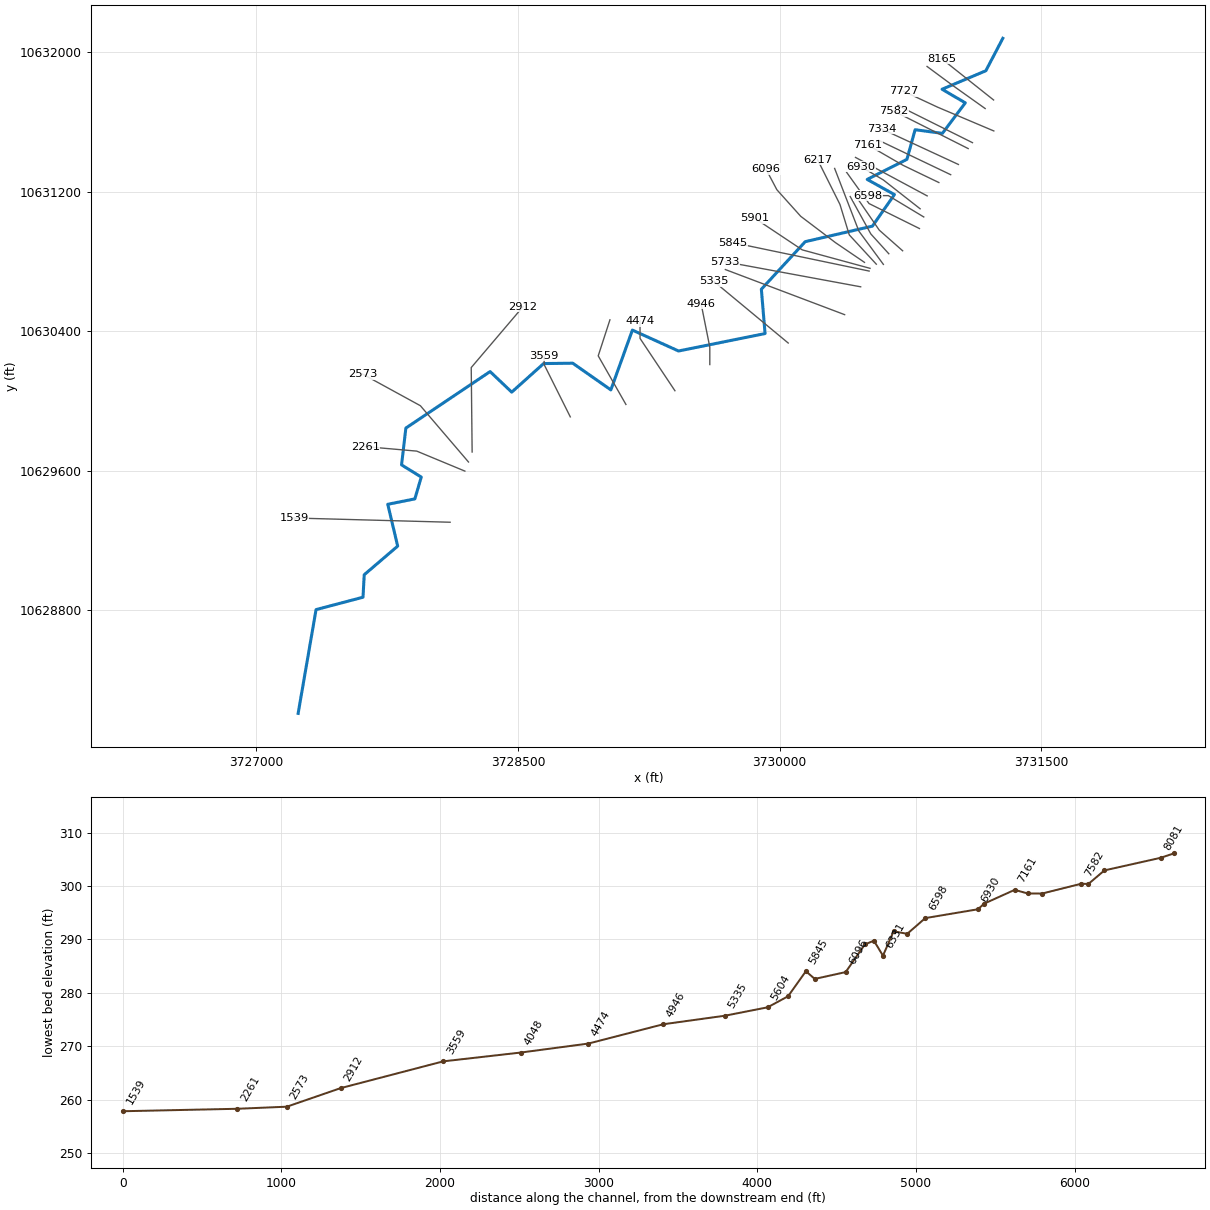
--- UNT 125 IN BOCR.prj (project) ---

Proj Title=UNT 125 IN BOCR Base Level Engineering
Current Plan=p01
Default Exp/Contr=0.3,0.1
English Units
Geom File=g01
Flow File=f01
Plan File=p01
Y Axis Title=Elevation
X Axis Title(PF)=Main Channel Distance
X Axis Title(XS)=Station
BEGIN DESCRIPTION:
UNT 125 IN BOCR
END DESCRIPTION:
DSS Export Rating Curves= 0
DSS Export Rating Curve Sorted= 0
DSS Export Volume Flow Curves= 0
DXF OffsetX= 0
DXF OffsetY= 0
DXF ScaleX= 1
DXF ScaleY= 10

--- UNT 125 IN BOCR.p01 (plan) ---

Plan Title=Multiple Run
Short Identifier=Multiple
Geom File=g01
Flow File=f01
Subcritical Flow
K Sum by GR= 0
Std Step Tol= 0.01
Critical Tol= 0.01
Num of Std Step Trials= 20
Max Error Tol= 0.3
Flow Tol Ratio= 0.001
Split Flow NTrial= 30
Split Flow Tol= 0.02
Split Flow Ratio= 0.02
Log Output Level= 0
Friction Slope Method= 1
Unsteady Friction Slope Method= 2
Unsteady Bridges Friction Slope Method= 1
Parabolic Critical Depth
Global Vel Dist=  1 , 1 , 1
Global Log Level= 0
CheckData=True
Encroach Param= -1, 0, 0, 0
BEGIN DESCRIPTION:
Multiple Run
END DESCRIPTION:

--- UNT 125 IN BOCR.f01 (steady flow) ---

Flow Title=Multiple
Number of Profiles=7
Profile Names=10-year,25-year,50-year,1pct_min,100-year,1pct_plu,500-year
River Rch & RM= UNT 125 IN BOCR,Reach-1,8165
     535     721     873     779    1053    1424    1536
River Rch & RM= UNT 125 IN BOCR,Reach-1,2573
     659     896    1093     981    1326    1793    1958
Boundary for River Rch & Prof#=UNT 125 IN BOCR,Reach-1,1
Up Type=0
Dn Type=3
Dn Slope=0.005
Boundary for River Rch & Prof#=UNT 125 IN BOCR,Reach-1,2
Up Type=0
Dn Type=3
Dn Slope=0.005
Boundary for River Rch & Prof#=UNT 125 IN BOCR,Reach-1,3
Up Type=0
Dn Type=3
Dn Slope=0.005
Boundary for River Rch & Prof#=UNT 125 IN BOCR,Reach-1,4
Up Type=0
Dn Type=3
Dn Slope=0.005
Boundary for River Rch & Prof#=UNT 125 IN BOCR,Reach-1,5
Up Type=0
Dn Type=3
Dn Slope=0.005
Boundary for River Rch & Prof#=UNT 125 IN BOCR,Reach-1,6
Up Type=0
Dn Type=3
Dn Slope=0.005
Boundary for River Rch & Prof#=UNT 125 IN BOCR,Reach-1,7
Up Type=0
Dn Type=3
Dn Slope=0.005

--- UNT 125 IN BOCR.g01 (geometry) ---

Geom Title=Existing Conditions
Program Version=4.10

River Reach=UNT 125 IN BOCR ,Reach-1
Reach XY= 30
      3731279.84     10632080.94       3731182.5       10631895.
       3730931.5       10631789.      3731064.75       10631711.
      3730933.25       10631536.        3730777.       10631557.
        3730730.       10631387.      3730502.25       10631272.
       3730658.5       10631185.        3730532.       10631004.
      3730146.75       10630915.      3729895.25       10630642.
       3729916.5       10630388.      3729420.25       10630288.
      3729155.75       10630408.      3729032.25       10630065.
      3728813.75       10630218.      3728646.75       10630216.
      3728463.75       10630052.      3728339.75       10630170.
      3727856.75       10629846.        3727832.       10629635.
        3727945.       10629565.      3727908.25       10629440.
        3727753.       10629409.      3727809.75       10629169.
        3727618.       10629005.        3727611.       10628876.
      3727341.75       10628805.        3727239.       10628210.

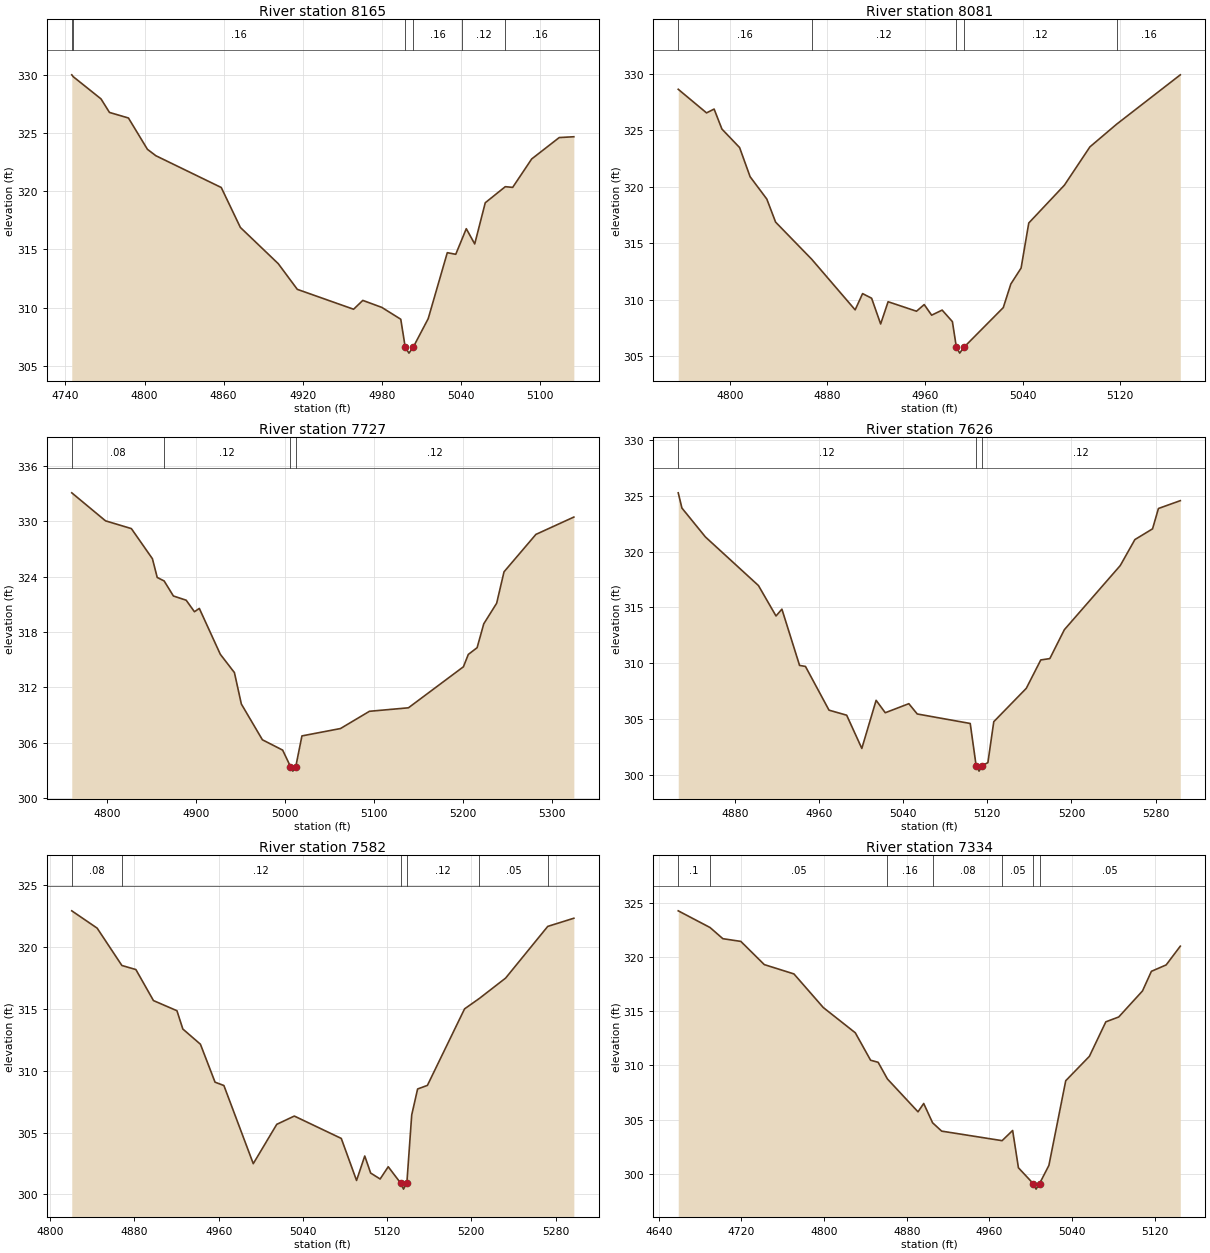
Type RM Length L Ch R = 1 ,8165    ,84,84,84
BEGIN DESCRIPTION:
UNT 125 IN BOCR 16.0
END DESCRIPTION:
XS GIS Cut Line= 2
      3731226.99     10631727.44       3730928.8     10631964.44
#Sta/Elev= 30
  4744.8     330  4745.9  329.84    4767  327.93  4773.4  326.77  4787.8  326.29
  4802.2   323.6  4808.6  323.05  4858.2  320.32  4872.7  316.89  4901.5  313.77
  4915.9  311.57  4958.6  309.86  4965.6  310.62    4980  310.02  4994.4     309
  4997.8  306.59  5000.6  306.09  5003.8  306.59  5015.2  309.05  5029.7  314.72
  5036.1  314.58  5040.9   315.9  5044.1  316.78  5050.5  315.47  5058.5  319.01
  5073.7  320.39  5079.3  320.33  5093.7  322.77  5114.6  324.61  5125.7  324.68
#Mann= 6 ,-1 , 0
  4744.8     .08       0  4745.9     .16       0  4997.8     .07       0
  5003.8     .16       0  5040.9     .12       0  5073.7     .16       0
Bank Sta=4997.8,5003.8
XS Rating Curve= 0 ,0
Exp/Cntr=0.3,0.1

Type RM Length L Ch R = 1 ,8081    ,354,354,354
BEGIN DESCRIPTION:
Mapping XS 8a47d09b
END DESCRIPTION:
XS GIS Cut Line= 3
      3731178.76     10631678.31      3730995.61     10631808.52
      3730845.46     10631919.61
#Sta/Elev= 30
  4757.7  328.62  4780.9  326.53  4787.1  326.87  4793.5   325.1    4808  323.46
  4816.6  320.88  4830.3   318.9  4837.5  316.86  4867.2  313.56  4902.7  309.09
  4908.8  310.53  4916.2  310.12  4923.6  307.84  4929.7  309.81    4953  308.97
  4959.3  309.56  4965.4  308.62    4974  309.07  4982.4  308.05  4985.7  305.76
  4988.4  305.26  4991.7  305.76  5024.1  309.29  5030.3  311.38  5038.7  312.79
    5045  316.78  5074.2  320.13  5095.1  323.52  5116.9  325.52  5169.2   329.9
#Mann= 5 ,-1 , 0
  4757.7     .16       0  4867.2     .12       0  4985.7     .07       0
  4991.7     .12       0  5116.9     .16       0
Bank Sta=4985.7,4991.7
XS Rating Curve= 0 ,0
Exp/Cntr=0.3,0.1

Type RM Length L Ch R = 1 ,7727    ,101,101,101
BEGIN DESCRIPTION:
Mapping XS 244ac868
END DESCRIPTION:
XS GIS Cut Line= 3
      3731228.24     10631549.84       3730906.2     10631686.12
       3730710.9     10631777.26
#Sta/Elev= 30
  4759.9   333.1  4797.9  330.06    4827  329.22  4850.7  325.95  4856.1  323.92
  4863.9  323.54  4874.3  321.91  4888.7  321.45    4898   320.2  4903.5  320.56
  4927.1  315.59    4943   313.6  4950.8  310.19  4974.5  306.31  4997.3  305.19
  5006.1  303.41  5008.8  302.91  5012.1  303.41    5019  306.73  5062.4  307.53
    5095   309.4  5138.9  309.78  5200.8  314.23  5206.3  315.57  5216.2   316.3
  5223.7  318.89  5238.2  321.12  5246.5  324.53  5282.4  328.59  5325.1  330.47
#Mann= 4 ,-1 , 0
  4759.9     .08       0  4863.9     .12       0  5006.1     .07       0
  5012.1     .12       0
Bank Sta=5006.1,5012.1
XS Rating Curve= 0 ,0
Exp/Cntr=0.3,0.1

Type RM Length L Ch R = 1 ,7626    ,44,44,44
BEGIN DESCRIPTION:
Mapping XS 96efaf77
END DESCRIPTION:
XS GIS Cut Line= 2
      3731105.87     10631482.67      3730678.52      10631695.7
#Sta/Elev= 30
    4826  325.25  4829.5  323.89  4851.9   321.3  4902.3  316.96    4919  314.24
  4924.6  314.85  4941.4  309.82    4947  309.73  4969.4  305.82  4986.2  305.37
  5000.6   302.4  5014.2   306.7  5022.9  305.59  5045.3   306.4  5053.3  305.48
  5103.7  304.63  5109.3  300.87  5112.1  300.37  5115.3  300.87  5120.5  301.13
  5126.1  304.79    5157  307.77  5170.8  310.31  5179.4  310.43  5193.2  313.01
  5246.4  318.75  5260.3  321.07  5277.1  322.03  5282.7  323.85  5303.5  324.55
#Mann= 3 ,-1 , 0
    4826     .12       0  5109.3     .07       0  5115.3     .12       0
Bank Sta=5109.3,5115.3
XS Rating Curve= 0 ,0
Exp/Cntr=0.3,0.1

Type RM Length L Ch R = 1 ,7582    ,248,248,248
BEGIN DESCRIPTION:
UNT 125 IN BOCR 15.0
END DESCRIPTION:
XS GIS Cut Line= 2
      3731081.15     10631448.81      3730655.38     10631663.65
#Sta/Elev= 30
  4820.5  322.93  4844.6  321.53  4868.1  318.51  4881.4  318.18  4898.1  315.67
  4920.4  314.85    4926  313.37  4942.7  312.14  4956.6  309.07    4965   308.8
  4992.9  302.48  5015.2  305.66  5031.9  306.33  5076.5  304.52    5091  301.12
  5098.8   303.1  5104.4  301.72  5113.4  301.24  5121.1  302.23  5132.8  300.92
  5135.6  300.42  5138.8  300.92  5143.4  306.42    5149  308.52  5158.3  308.81
  5193.6     315  5207.6  315.84  5232.6  317.49  5272.6  321.67  5297.4  322.33
#Mann= 6 ,-1 , 0
  4820.5     .08       0  4868.1     .12       0  5132.8     .07       0
  5138.8     .12       0  5207.6     .05       0  5272.6     .12       0
Bank Sta=5132.8,5138.8
XS Rating Curve= 0 ,0
Exp/Cntr=0.3,0.1

Type RM Length L Ch R = 1 ,7334    ,91,91,91
BEGIN DESCRIPTION:
Mapping XS ff7146d5
END DESCRIPTION:
XS GIS Cut Line= 2
      3731025.18     10631357.66      3730584.18      10631561.9
#Sta/Elev= 30
  4658.8  324.25  4689.6  322.71    4702  321.68  4719.4  321.43  4742.1  319.29
  4770.8  318.43  4799.2  315.33  4830.2     313    4845  310.47  4852.3  310.28
  4861.3  308.74  4890.9  305.71  4896.4  306.48    4905   304.7  4913.8  303.93
  4972.3  303.05  4982.5  303.99  4988.1  300.55  5002.5  299.08  5005.2  298.58
  5008.5  299.08  5017.6  300.77  5033.9  308.58  5056.8  310.83  5072.7  314.01
  5085.2  314.46  5108.2  316.86  5116.8  318.67  5131.1  319.26  5144.8  320.99
#Mann= 7 ,-1 , 0
  4658.8      .1       0  4689.6     .05       0  4861.3     .16       0
    4905     .08       0  4972.3     .05       0  5002.5     .04       0
  5008.5     .05       0
Bank Sta=5002.5,5008.5
XS Rating Curve= 0 ,0
Exp/Cntr=0.3,0.1

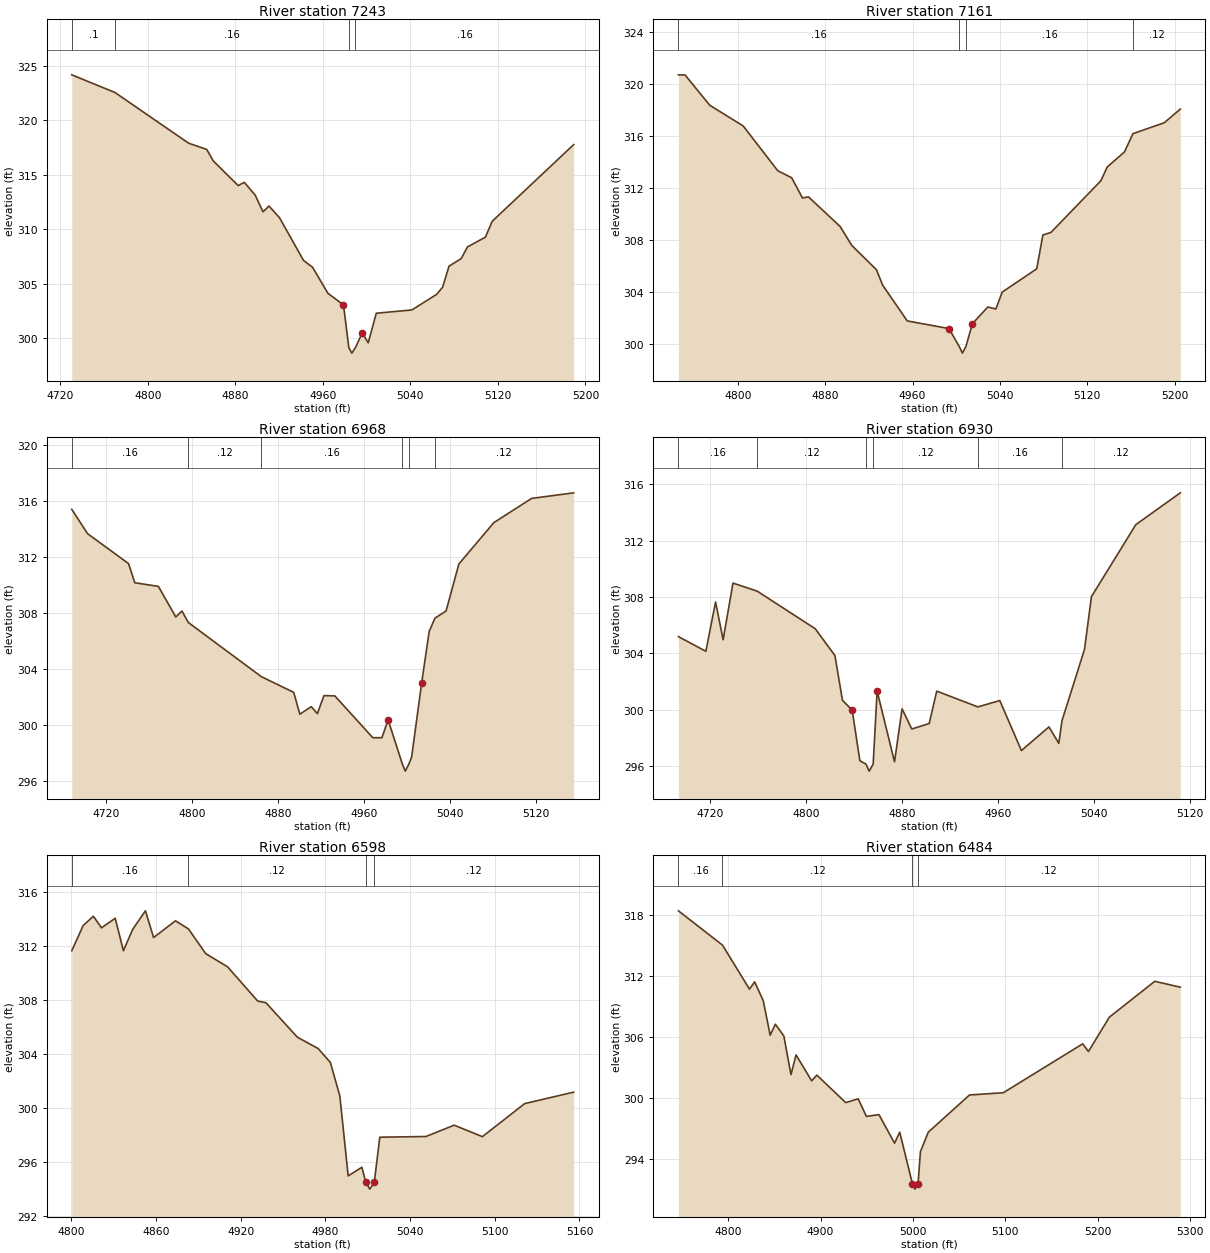
Type RM Length L Ch R = 1 ,7243    ,82,82,82
BEGIN DESCRIPTION:
Mapping XS afa7e4bb
END DESCRIPTION:
XS GIS Cut Line= 2
      3730980.92     10631299.06      3730566.79       10631497.
#Sta/Elev= 30
  4730.3   324.2  4769.9  322.57  4837.2  317.91  4853.7  317.34  4859.8  316.27
  4882.5  314.01  4888.1  314.31    4898  313.14  4905.2   311.6  4910.7  312.13
  4920.2  311.07  4942.3  307.12  4950.5   306.5  4964.5  304.11  4978.8  303.03
  4983.7   299.1  4986.4   298.6  4989.7   299.1  4995.9  300.46  5001.4  299.55
  5008.8  302.27  5041.3  302.57  5063.9     304  5069.5  304.67  5075.3   306.6
  5086.4  307.29  5092.2  308.37  5108.6  309.27  5114.8  310.73  5189.3  317.78
#Mann= 4 ,-1 , 0
  4730.3      .1       0  4769.9     .16       0  4983.7     .07       0
  4989.7     .16       0
Bank Sta=4978.8,4995.9
XS Rating Curve= 0 ,0
Exp/Cntr=0.3,0.1

Type RM Length L Ch R = 1 ,7161    ,193,193,193
BEGIN DESCRIPTION:
Mapping XS 1f390359
END DESCRIPTION:
XS GIS Cut Line= 3
      3730913.15     10631254.05      3730707.39     10631353.02
      3730506.89      10631468.9
#Sta/Elev= 30
  4745.4   320.7  4751.5  320.69  4774.1  318.36  4804.8  316.76  4836.4  313.32
  4849.2  312.77  4859.1  311.22  4864.6   311.3  4893.6  309.02  4904.3  307.56
  4926.9  305.69  4932.5  304.51  4955.1  301.75  4993.3  301.16  5002.8  299.77
  5005.6  299.27  5008.8  299.77  5014.8  301.54  5028.9  302.82  5036.3  302.67
  5042.1  303.97  5073.7  305.76  5079.4  308.37  5086.7  308.56  5132.5  312.54
  5138.3   313.6  5154.1  314.76  5161.9  316.17  5190.6  317.01  5205.3  318.06
#Mann= 4 ,-1 , 0
  4745.4     .16       0  5002.8     .07       0  5008.8     .16       0
  5161.9     .12       0
Bank Sta=4993.3,5014.8
XS Rating Curve= 0 ,0
Exp/Cntr=0.3,0.1

Type RM Length L Ch R = 1 ,6968    ,38,38,38
BEGIN DESCRIPTION:
UNT 125 IN BOCR 14.0
END DESCRIPTION:
XS GIS Cut Line= 2
      3730846.14     10631177.45      3730435.12      10631398.1
#Sta/Elev= 30
  4688.2   315.4  4702.9  313.66    4741  311.52  4746.8  310.15  4768.7  309.89
  4784.9   307.7  4790.6  308.13  4796.5  307.31  4864.3  303.44  4894.5  302.31
  4900.2  300.75  4910.8  301.29  4916.5  300.79  4922.6  302.08  4932.7  302.06
    4968  299.07  4976.5  299.07  4982.2  300.35  4995.5  297.18  4998.2  296.68
  5001.5  297.18  5004.1  297.69  5013.4  302.98  5020.4  306.67  5025.8  307.62
  5036.1  308.13    5048  311.49  5080.5  314.45  5115.6  316.18  5154.7  316.58
#Mann= 6 ,-1 , 0
  4688.2     .16       0  4796.5     .12       0  4864.3     .16       0
  4995.5     .07       0  5001.5     .16       0  5025.8     .12       0
Bank Sta=4982.2,5013.4
XS Rating Curve= 0 ,0
Exp/Cntr=0.3,0.1

Type RM Length L Ch R = 1 ,6930    ,332,332,332
BEGIN DESCRIPTION:
Mapping XS 328e22eb
END DESCRIPTION:
XS GIS Cut Line= 4
      3730805.73     10631103.51      3730715.89     10631173.82
      3730594.79     10631268.88      3730465.43     10631345.72
#Sta/Elev= 30
  4693.6  305.19  4716.5  304.15  4724.6  307.65  4730.9  304.97  4739.1  308.99
  4759.3  308.42  4807.7  305.75  4824.1  303.85  4830.4  300.67  4838.5  299.97
  4844.9  296.38    4850  296.14  4852.7  295.64    4856  296.14  4859.3  301.32
  4873.8   296.3  4880.1  300.06  4888.2  298.63  4902.7  299.02    4909  301.32
  4943.3   300.2  4961.6  300.65  4979.6   297.1  5002.6  298.78  5010.8  297.61
  5013.4  299.21  5032.2  304.28    5038  308.03    5075  313.14  5112.1   315.4
#Mann= 6 ,-1 , 0
  4693.6     .16       0  4759.3     .12       0    4850     .07       0
    4856     .12       0  4943.3     .16       0  5013.4     .12       0
Bank Sta=4838.5,4859.3
XS Rating Curve= 0 ,0
Exp/Cntr=0.3,0.1

Type RM Length L Ch R = 1 ,6598    ,114,114,114
BEGIN DESCRIPTION:
Mapping XS e832c75c
END DESCRIPTION:
XS GIS Cut Line= 3
      3730826.58     10631056.63      3730623.44     10631179.03
      3730504.91     10631179.03
#Sta/Elev= 30
  4800.2  311.66  4808.3  313.53  4815.5  314.22  4821.3  313.36    4831  314.07
  4836.8  311.66  4843.4  313.25  4852.4  314.62  4858.2  312.64  4873.7  313.88
  4882.9  313.28  4895.1  311.45  4910.6  310.47    4932  307.93  4937.8  307.81
  4960.1  305.25  4974.7  304.42  4983.5  303.38  4990.2  300.88  4996.1  294.97
  5005.8  295.61  5008.6  294.49  5011.4  293.99  5014.6  294.49  5018.5  297.84
  5051.2  297.89  5071.2  298.73  5091.2  297.88  5121.2  300.33  5155.9  301.18
#Mann= 4 ,-1 , 0
  4800.2     .16       0  4882.9     .12       0  5008.6     .07       0
  5014.6     .12       0
Bank Sta=5008.6,5014.6
XS Rating Curve= 0 ,0
Exp/Cntr=0.3,0.1

Type RM Length L Ch R = 1 ,6484    ,86,86,86
BEGIN DESCRIPTION:
Mapping XS aa1b1a30
END DESCRIPTION:
XS GIS Cut Line= 3
      3730801.86     10630990.21      3730512.76     10631133.46
      3730384.26     10631312.59
#Sta/Elev= 30
  4746.2  318.42  4793.9  315.05  4823.1  310.72  4828.7  311.43    4838  309.59
  4845.5  306.19  4851.1  307.27  4860.3  306.11    4868  302.31  4873.5  304.25
  4890.4   301.7    4896  302.26  4927.3  299.56  4940.8  299.93  4949.6   298.2
  4963.2  298.38  4980.1  295.57  4985.7  296.65  4999.5  291.55  5002.2  291.05
  5005.5  291.55  5008.1  294.74  5016.6  296.65  5061.2  300.31  5097.8  300.53
  5183.7  305.34  5189.9  304.58  5212.5  307.96  5261.7  311.49  5289.3  310.91
#Mann= 4 ,-1 , 0
  4746.2     .16       0  4793.9     .12       0  4999.5     .07       0
  5005.5     .12       0
Bank Sta=4999.5,5005.5
XS Rating Curve= 0 ,0
Exp/Cntr=0.3,0.1

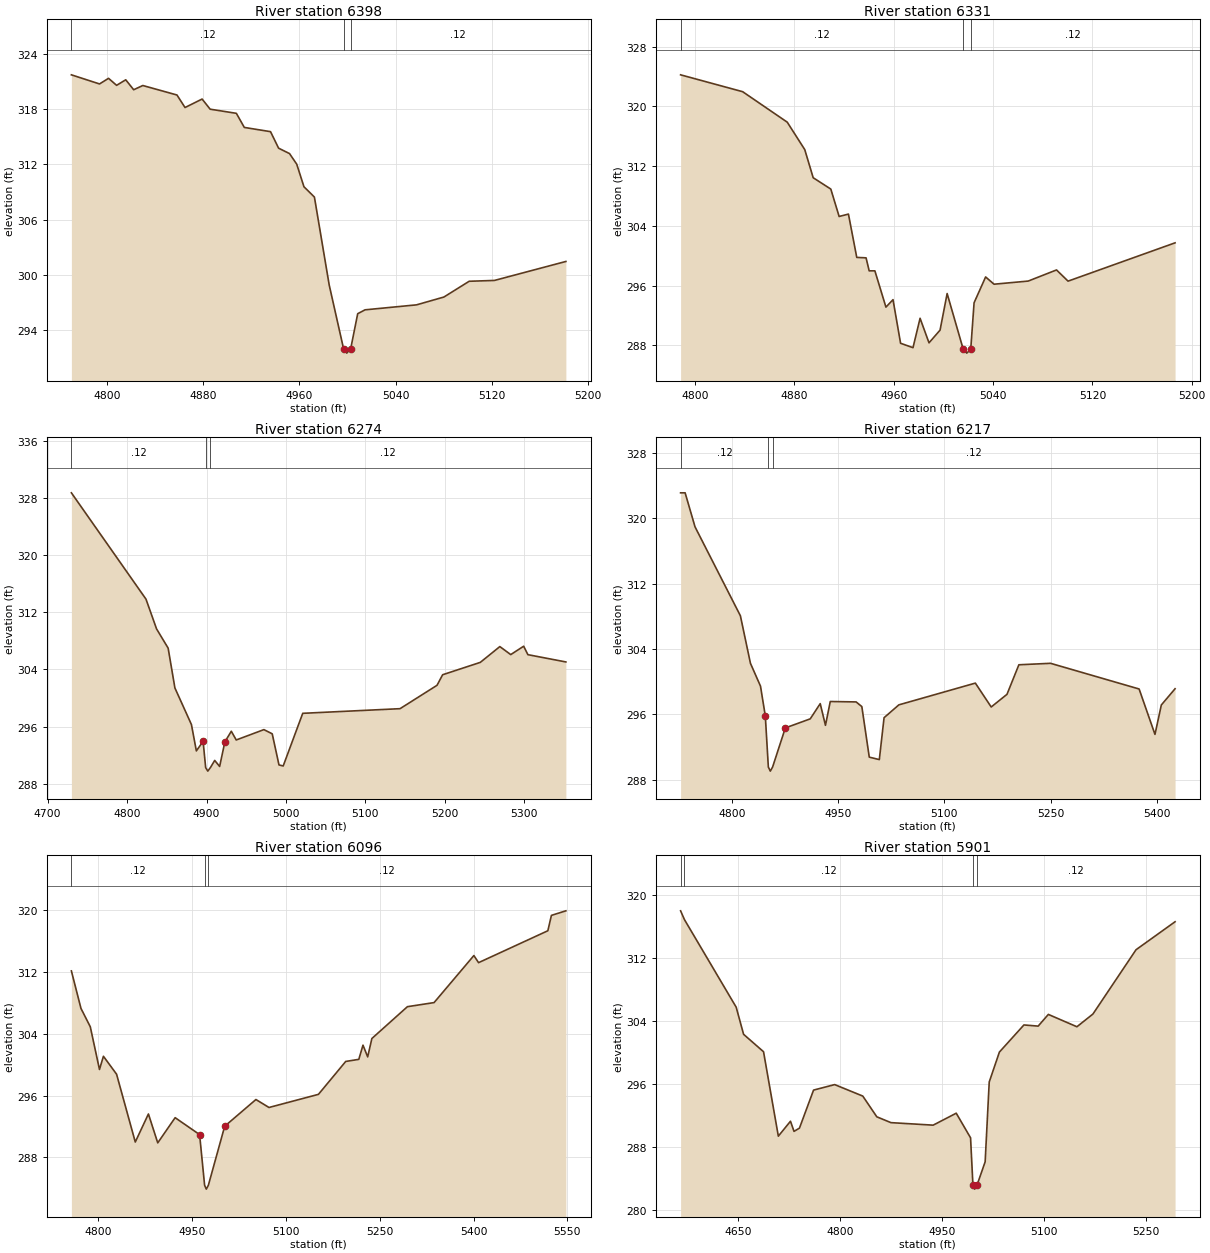
Type RM Length L Ch R = 1 ,6398    ,67,67,67
BEGIN DESCRIPTION:
Mapping XS 1e8b946f
END DESCRIPTION:
XS GIS Cut Line= 3
      3730705.45     10630862.64      3730571.36     10630981.11
      3730439.83     10631172.55
#Sta/Elev= 30
  4770.4  321.73  4793.8  320.74  4801.3  321.35    4808  320.59  4815.6  321.19
  4822.2  320.11  4829.8  320.57  4858.2  319.54  4864.9  318.18  4879.1   319.1
  4885.8     318  4907.6  317.55  4914.2  316.02    4936  315.56  4942.7  313.77
  4951.8  313.18  4957.8  312.03  4963.8  309.58  4972.5  308.46  4984.8  298.91
  4996.7  292.02  4999.4  291.52  5002.7  292.02  5008.5   295.8  5014.6  296.22
  5057.4  296.76  5080.2  297.61  5101.2  299.32  5122.2  299.41  5181.6  301.47
#Mann= 3 ,-1 , 0
  4770.4     .12       0  4996.7     .07       0  5002.7     .12       0
Bank Sta=4996.7,5002.7
XS Rating Curve= 0 ,0
Exp/Cntr=0.3,0.1

Type RM Length L Ch R = 1 ,6331    ,57,57,57
BEGIN DESCRIPTION:
Mapping XS bfb097ae
END DESCRIPTION:
XS GIS Cut Line= 3
      3730626.03     10630845.71      3730523.18     10630958.98
      3730404.71     10631173.78
#Sta/Elev= 30
  4788.3  324.22  4838.3  321.96  4874.2  317.88  4888.3  314.21  4895.1  310.44
  4909.3  308.92    4916  305.25  4923.5  305.57  4930.2  299.77  4937.7  299.71
  4940.2  297.97  4944.8  297.97  4953.7  293.11  4959.4  294.11  4965.5  288.27
  4975.5  287.68  4981.2  291.62  4988.4  288.33  4997.3  290.03    5003  294.93
    5016  287.45  5018.8  286.95    5022  287.45  5024.7  293.69    5034  297.15
  5040.8  296.18  5068.3   296.6  5091.1  298.09  5100.4  296.59  5186.6  301.72
#Mann= 3 ,-1 , 0
  4788.3     .12       0    5016     .07       0    5022     .12       0
Bank Sta=5016,5022
XS Rating Curve= 0 ,0
Exp/Cntr=0.3,0.1

Type RM Length L Ch R = 1 ,6274    ,57,57,57
BEGIN DESCRIPTION:
Mapping XS 9ef8807c
END DESCRIPTION:
XS GIS Cut Line= 3
      3730595.02     10630784.58       3730454.4     10630975.55
      3730315.52     10631334.89
#Sta/Elev= 30
  4729.9  328.71  4823.8  313.83  4837.1  309.67  4851.7  306.97  4860.2   301.4
    4881  296.28  4887.2  292.59  4895.7  293.93  4898.9  290.26  4901.6  289.76
  4904.9  290.26  4910.3  291.26  4916.5  290.41  4923.1  293.86  4931.2  295.34
  4937.4  294.12  4972.2  295.57  4982.7  294.98  4991.2  290.63  4996.5  290.48
  5021.1  297.85  5143.6   298.5  5190.1  301.77  5197.2  303.25  5244.6  304.98
  5269.2  307.19  5282.9  306.07  5299.2  307.24  5304.5  306.06  5352.3  305.04
#Mann= 3 ,-1 , 0
  4729.9     .12       0  4898.9     .07       0  4904.9     .12       0
Bank Sta=4895.7,4923.1
XS Rating Curve= 0 ,0
Exp/Cntr=0.3,0.1

Type RM Length L Ch R = 1 ,6217    ,121,121,121
BEGIN DESCRIPTION:
Mapping XS 153e6528
END DESCRIPTION:
XS GIS Cut Line= 4
      3730554.43      10630785.8      3730399.48     10630953.77
      3730346.09     10631128.25      3730217.42     10631385.59
#Sta/Elev= 30
  4727.2  323.09  4733.6  323.09  4747.6  318.93  4811.7  308.06  4825.9  302.25
  4840.1  299.46  4846.9  295.82  4851.2  289.57    4854  289.07  4857.2  289.57
  4875.2  294.35  4910.4  295.46  4924.5  297.32  4931.9  294.67  4938.7  297.58
  4975.2  297.53  4983.3  296.96  4993.8  290.78    5008  290.48  5014.7   295.6
  5035.6  297.17  5143.7  299.83  5166.1  296.91  5188.4  298.46  5205.2  302.07
  5249.9  302.25  5375.1  299.11  5397.5  293.56  5406.5  297.16  5425.9  299.14
#Mann= 3 ,-1 , 0
  4727.2     .12       0  4851.2     .07       0  4857.2     .12       0
Bank Sta=4846.9,4875.2
XS Rating Curve= 0 ,0
Exp/Cntr=0.3,0.1

Type RM Length L Ch R = 1 ,6096    ,195,195,195
BEGIN DESCRIPTION:
Mapping XS b8bc3481
END DESCRIPTION:
XS GIS Cut Line= 5
       3730486.7     10630796.23      3730320.05      10630909.5
      3730120.83     10631060.54      3729984.12     10631212.89
       3729921.6     10631331.41
#Sta/Elev= 30
  4757.3  312.14  4772.6  307.29  4787.5  304.91  4802.2  299.38  4808.5  301.09
  4829.5  298.77  4859.4  289.99  4880.4  293.62  4895.3  289.88  4923.1  293.14
  4962.2  290.95  4970.2  284.39  4972.9  283.89  4976.2  284.39  5002.3  292.03
  5052.2  295.49  5073.1  294.46  5152.1  296.16  5195.7  300.42  5216.6  300.69
  5223.3  302.53  5230.8  301.01  5237.5  303.39  5294.3  307.51  5336.9  308.04
  5400.5  314.13    5408  313.21  5518.7  317.34  5524.4  319.33  5547.5  319.92
#Mann= 3 ,-1 , 0
  4757.3     .12       0  4970.2     .07       0  4976.2     .12       0
Bank Sta=4962.2,5002.3
XS Rating Curve= 0 ,0
Exp/Cntr=0.3,0.1

Type RM Length L Ch R = 1 ,5901    ,56,56,56
BEGIN DESCRIPTION:
Mapping XS a8e78322
END DESCRIPTION:
XS GIS Cut Line= 3
      3730518.59     10630762.02      3730129.74     10630867.91
      3729858.91     10631048.47
#Sta/Elev= 30
  4564.9  318.02  4570.6   316.9  4646.8  305.76  4657.7  302.31  4687.1  300.09
  4708.9  289.35  4726.8  291.25    4732  289.96    4740  290.37  4760.8  295.21
  4791.9  295.91  4833.3  294.45    4854  291.81  4874.8  291.07    4937  290.75
    4971  292.27  4992.1  289.14  4995.6  283.11  4998.3  282.61  5001.6  283.11
  5013.6  286.09  5019.6  296.24  5034.6  300.05  5070.7   303.5  5091.7  303.35
  5106.7  304.84  5148.8  303.27  5172.4  304.89  5235.9  313.07  5293.4  316.63
#Mann= 4 ,-1 , 0
  4564.9     .05       0  4570.6     .12       0  4995.6     .07       0
  5001.6     .12       0
Bank Sta=4995.6,5001.6
XS Rating Curve= 0 ,0
Exp/Cntr=0.3,0.1

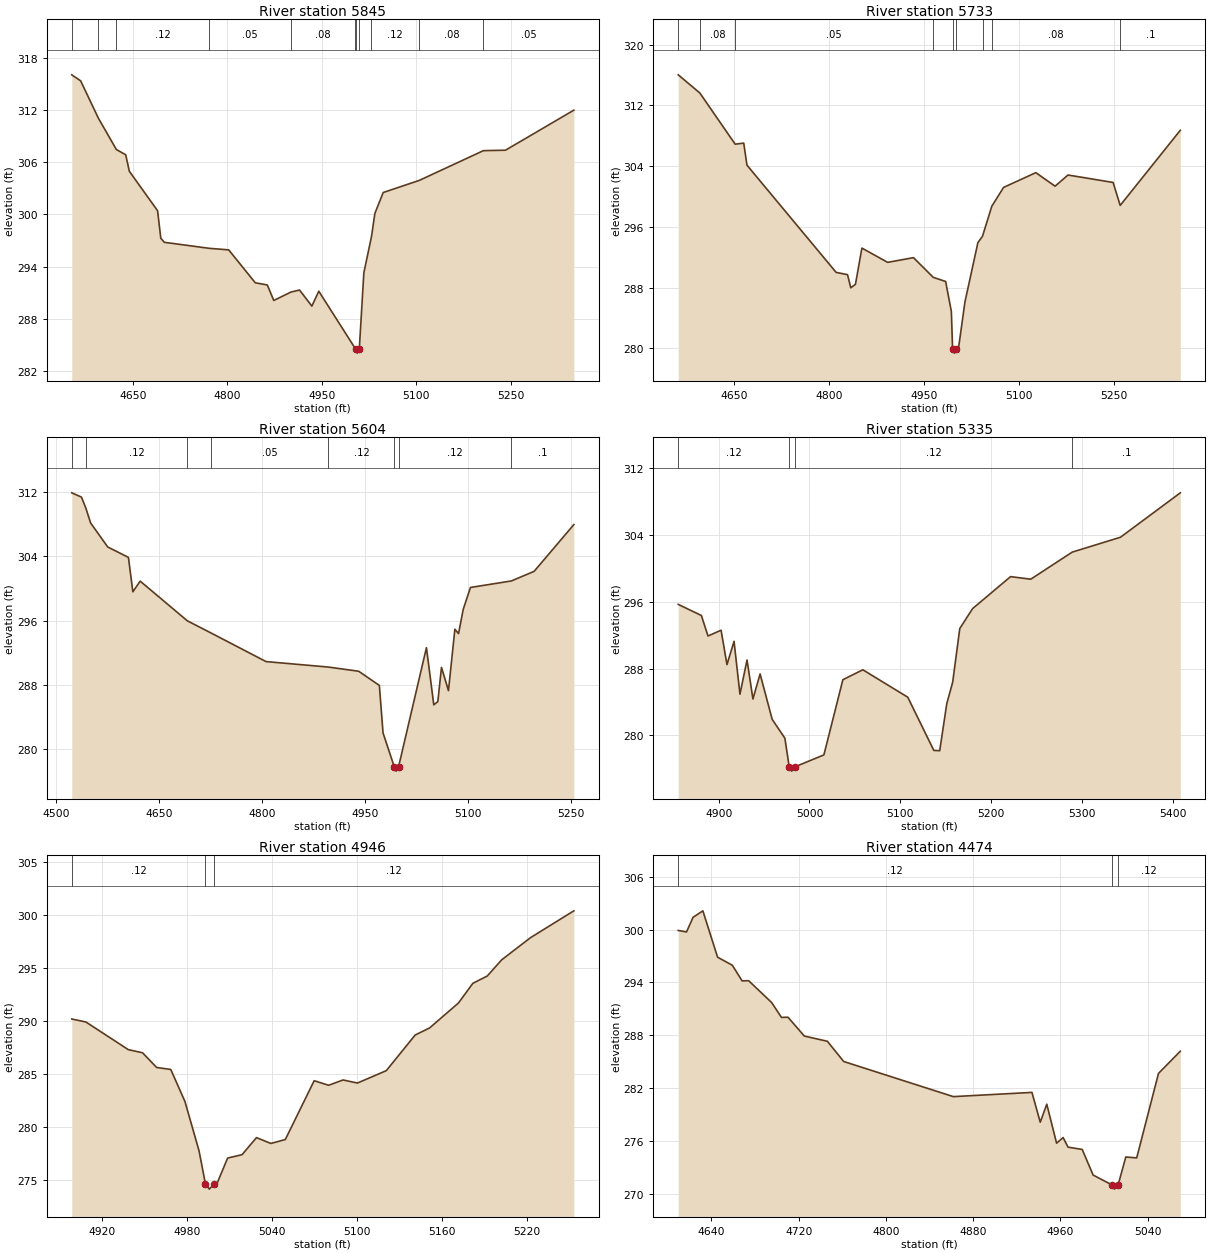
Type RM Length L Ch R = 1 ,5845    ,112,112,112
BEGIN DESCRIPTION:
Mapping XS c5a987c2
END DESCRIPTION:
XS GIS Cut Line= 2
      3730513.44     10630746.38      3729733.37     10630909.33
#Sta/Elev= 30
  4553.2  316.02  4567.3  315.33  4595.3  311.06    4624  307.44  4638.8  306.84
  4644.6  304.94  4689.4  300.41  4694.5  297.25  4700.1  296.78  4771.4  296.09
  4802.3  295.91  4844.5  292.13  4863.6  291.88  4873.8   290.1    4901  291.06
  4914.7   291.3  4934.3  289.45  4945.3  291.16  5002.9  284.61  5003.6  284.55
  5006.4  284.05  5009.6  284.55  5016.8  293.28  5028.9  297.43  5034.3   300.1
  5047.5   302.5  5104.7  303.89  5206.6  307.31  5241.6  307.36  5350.1  311.96
#Mann= 11 ,-1 , 0
  4553.2     .05       0  4595.3     .08       0    4624     .12       0
  4771.4     .05       0    4901     .08       0  5002.9      .1       0
  5003.6     .07       0  5009.6      .1       0  5028.9     .12       0
  5104.7     .08       0  5206.6     .05       0
Bank Sta=5003.6,5009.6
XS Rating Curve= 0 ,0
Exp/Cntr=0.3,0.1

Type RM Length L Ch R = 1 ,5733    ,129,129,129
BEGIN DESCRIPTION:
Mapping XS e4957ae8
END DESCRIPTION:
XS GIS Cut Line= 2
       3730464.8     10630656.11       3729685.3     10630800.21
#Sta/Elev= 30
  4561.9  316.01    4596  313.62  4651.8  306.88  4665.3  307.02  4670.4  304.12
  4811.2     290  4829.2   289.7  4834.3  287.97  4841.7  288.43  4851.9   293.2
  4892.6  291.32  4933.3  291.94  4964.5  289.35  4984.1   288.8  4993.1  284.86
  4995.1  279.87  4997.9  279.37  5001.1  279.87  5004.5  280.07  5014.6  286.12
    5035  293.91  5042.3  294.76    5057  298.71  5075.6  301.19  5126.5  303.13
  5156.9  301.35  5177.3  302.82  5248.5  301.84  5259.7  298.82  5354.6  308.71
#Mann= 9 ,-1 , 0
  4561.9     .16       0    4596     .08       0  4651.8     .05       0
  4964.5     .12       0  4995.1     .07       0  5001.1     .12       0
  5042.3      .1       0    5057     .08       0  5259.7      .1       0
Bank Sta=4995.1,5001.1
XS Rating Curve= 0 ,0
Exp/Cntr=0.3,0.1

Type RM Length L Ch R = 1 ,5604    ,269,269,269
BEGIN DESCRIPTION:
Mapping XS 41f5ffd8
END DESCRIPTION:
XS GIS Cut Line= 2
      3730372.81     10630496.38      3729688.79     10630755.06
#Sta/Elev= 30
  4523.3  311.88  4537.4  311.35  4543.6  310.03  4550.8  308.13  4575.7  305.15
  4605.8  303.86  4612.3  299.58  4622.9  300.91  4691.6  295.98  4726.7  294.44
  4806.3  290.91  4897.1  290.23  4941.2  289.71  4971.3  287.95  4976.7  282.04
  4993.2   277.8  4995.9   277.3  4999.2   277.8  5039.9  292.64  5050.6  285.54
  5056.5  285.94  5061.8  290.19    5072   287.3  5081.3  294.93  5086.7  294.39
  5093.4  297.38    5104  300.12  5163.6  300.93  5196.7  302.12  5254.6  307.93
#Mann= 8 ,-1 , 0
  4523.3     .16       0  4543.6     .12       0  4691.6     .07       0
  4726.7     .05       0  4897.1     .12       0  4993.2     .07       0
  4999.2     .12       0  5163.6      .1       0
Bank Sta=4993.2,4999.2
XS Rating Curve= 0 ,0
Exp/Cntr=0.3,0.1

Type RM Length L Ch R = 1 ,5335    ,389,389,389
BEGIN DESCRIPTION:
Mapping XS 3e084af0
END DESCRIPTION:
XS GIS Cut Line= 2
      3730049.26      10630333.7      3729623.43     10630686.83
#Sta/Elev= 30
  4855.4  295.67  4880.9  294.34  4888.2  291.89  4902.6  292.58  4909.1  288.47
  4916.9  291.25  4923.4  284.93  4931.2  289.02  4937.7  284.35  4945.6  287.35
  4958.9  281.92  4972.9  279.67  4977.7  276.23  4980.5  275.73  4983.7  276.23
  5015.9  277.67  5036.8  286.66  5058.8  287.85  5108.3  284.57    5137  278.21
  5143.5  278.17  5151.3   283.8  5157.8  286.37  5165.6  292.78  5179.7  295.16
  5221.6  298.99  5243.8  298.68  5289.5  301.92  5342.7   303.7  5408.6  309.01
#Mann= 4 ,-1 , 0
  4855.4     .12       0  4977.7     .07       0  4983.7     .12       0
  5289.5      .1       0
Bank Sta=4977.7,4983.7
XS Rating Curve= 0 ,0
Exp/Cntr=0.3,0.1

Type RM Length L Ch R = 1 ,4946    ,472,472,472
BEGIN DESCRIPTION:
UNT 125 IN BOCR 10.0
END DESCRIPTION:
XS GIS Cut Line= 3
      3729599.61     10630210.16      3729599.61     10630310.19
       3729549.6     10630560.21
#Sta/Elev= 30
  4898.3  290.18  4908.3   289.9  4938.3  287.29  4948.3     287  4958.3  285.61
  4968.3  285.42  4978.3  282.41  4988.3  277.74  4992.8  274.63  4995.6  274.13
  4998.8  274.63  5000.9  274.63  5008.5  277.06  5018.7  277.38  5028.9  278.99
  5039.1  278.44  5049.3  278.81  5069.7  284.36  5079.9  283.93  5090.1  284.43
  5100.3  284.14  5120.7  285.31  5141.1  288.67  5151.3  289.34  5171.7  291.69
  5181.9  293.55  5192.1  294.24  5202.3  295.77  5222.7  297.86  5253.3  300.39
#Mann= 3 ,-1 , 0
  4898.3     .12       0  4992.8     .07       0  4998.8     .12       0
Bank Sta=4992.8,4998.8
XS Rating Curve= 0 ,0
Exp/Cntr=0.3,0.1

Type RM Length L Ch R = 1 ,4474    ,426,426,426
BEGIN DESCRIPTION:
UNT 125 IN BOCR 9.0
END DESCRIPTION:
XS GIS Cut Line= 3
      3729399.63     10630060.15      3729199.61     10630360.19
      3729199.61     10630460.19
#Sta/Elev= 30
  4609.5  299.91  4617.1  299.74  4623.1   301.4  4632.1  302.14  4645.6  296.87
  4659.1  295.96  4668.1  294.18  4674.1   294.2  4695.2  291.72  4704.2  290.03
  4710.2  290.05  4725.2  287.91  4746.3  287.32  4761.3  285.02  4861.9  281.03
    4934  281.51  4941.6  278.12  4947.6  280.17  4956.6  275.74  4962.6  276.38
  4967.1  275.29  4980.1  275.03  4990.1  272.12  5007.1  271.02  5009.8  270.52
  5013.1  271.02  5020.1  274.17  5030.1  274.07  5050.1  283.67  5070.1  286.19
#Mann= 3 ,-1 , 0
  4609.5     .12       0  5007.1     .07       0  5013.1     .12       0
Bank Sta=5007.1,5013.1
XS Rating Curve= 0 ,0
Exp/Cntr=0.3,0.1

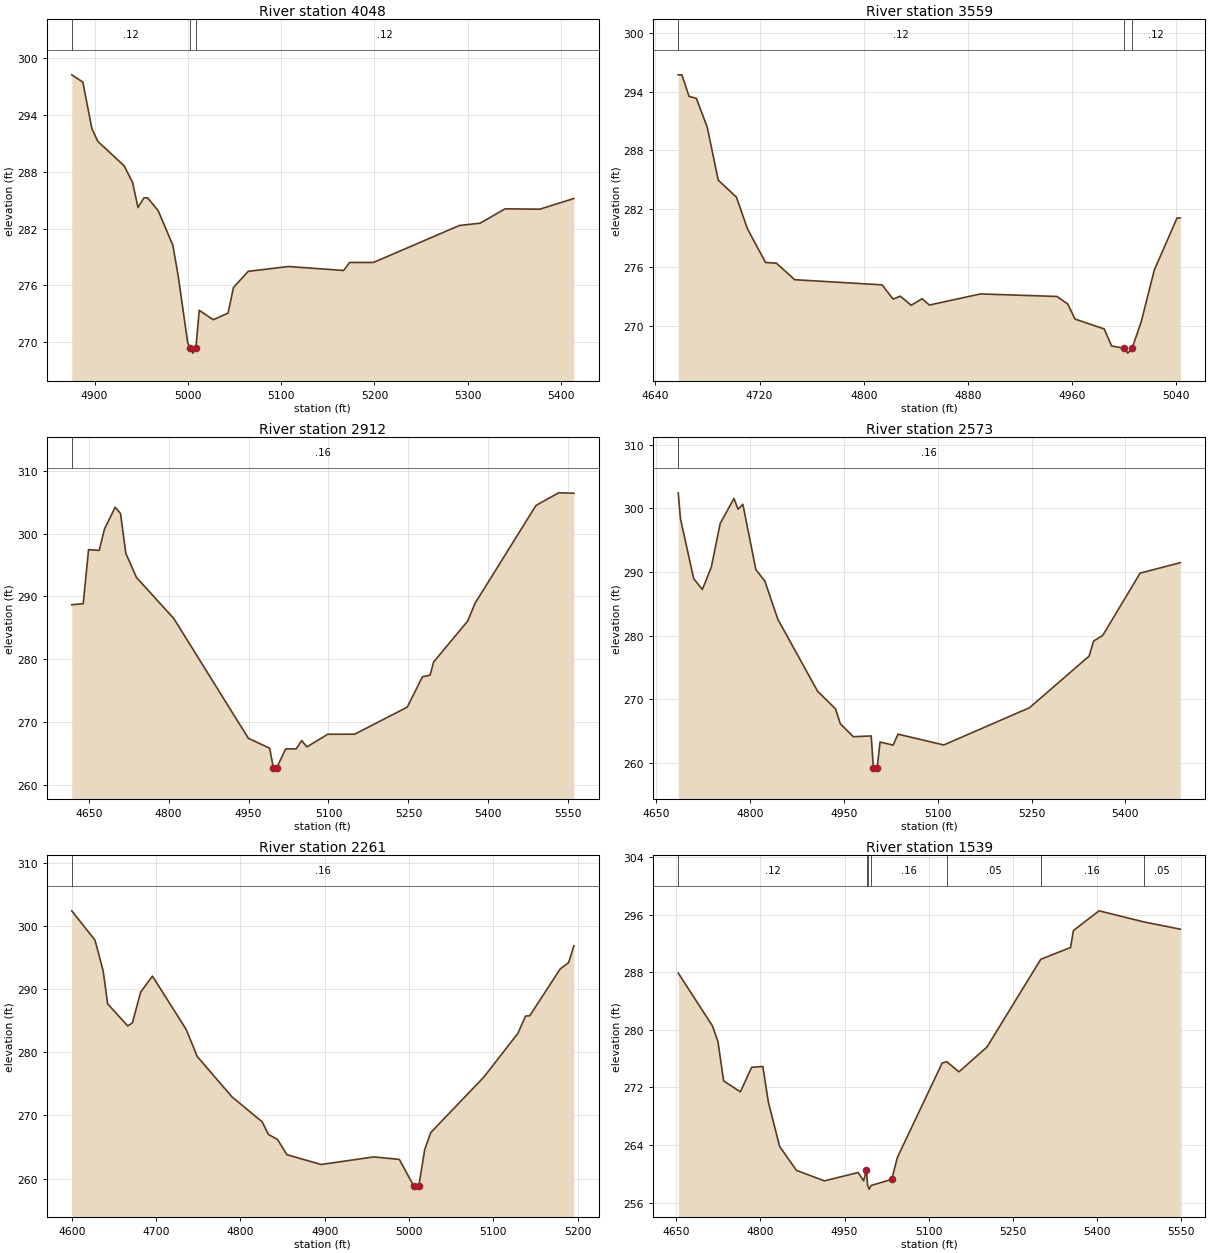
Type RM Length L Ch R = 1 ,4048    ,489,489,489
BEGIN DESCRIPTION:
UNT 125 IN BOCR 8.0
END DESCRIPTION:
XS GIS Cut Line= 4
      3729118.59     10629981.48      3729078.33     10630052.09
      3728959.73     10630260.12      3729026.91     10630466.83
#Sta/Elev= 30
  4875.6  298.27  4887.5   297.5  4897.1  292.61  4903.4  291.25  4931.7  288.65
  4940.8  286.89  4946.6  284.23  4952.9  285.26  4956.9  285.26  4968.2  283.91
    4984  280.23  4989.8  276.91  4999.9  269.92  5002.6  269.34  5005.4  268.84
  5008.6  269.34  5012.2  273.37  5027.2  272.37  5043.1  273.07  5048.9  275.78
  5064.7  277.49  5107.9     278    5167  277.58  5173.4  278.43    5199  278.43
  5291.1  282.34  5313.3  282.58    5340   284.1  5377.2  284.06  5413.7  285.19
#Mann= 3 ,-1 , 0
  4875.6     .12       0  5002.6     .07       0  5008.6     .12       0
Bank Sta=5002.6,5008.6
XS Rating Curve= 0 ,0
Exp/Cntr=0.3,0.1

Type RM Length L Ch R = 1 ,3559    ,647,647,647
BEGIN DESCRIPTION:
UNT 125 IN BOCR 7.0
END DESCRIPTION:
XS GIS Cut Line= 3
      3728799.59     10629910.22      3728649.61     10630210.19
      3728649.61     10630260.21
#Sta/Elev= 30
  4657.6  295.73  4660.4  295.73  4665.9  293.52  4671.5  293.32  4679.9  290.35
  4688.3  284.93  4702.3  283.18  4710.7  279.95  4724.6  276.49    4733  276.41
    4747  274.72  4814.1  274.19  4822.5  272.73  4828.1  273.03  4836.4   272.1
  4844.8  272.77  4850.4  272.12  4889.6  273.26  4948.3     273  4956.6  272.23
  4962.2  270.68  4984.6  269.67  4990.2  267.93    5000  267.69  5002.7  267.19
    5006  267.69    5013  270.41    5023   275.7  5040.5  281.05    5043  281.05
#Mann= 3 ,-1 , 0
  4657.6     .12       0    5000     .07       0    5006     .12       0
Bank Sta=5000,5006
XS Rating Curve= 0 ,0
Exp/Cntr=0.3,0.1

Type RM Length L Ch R = 1 ,2912    ,339,339,339
BEGIN DESCRIPTION:
UNT 125 IN BOCR 6.0
END DESCRIPTION:
XS GIS Cut Line= 3
      3728236.76     10629708.72      3728231.56     10630193.07
      3728528.41       10630542.
#Sta/Elev= 30
  4618.1  288.68  4639.6  288.85  4649.6  297.44  4669.6  297.34  4679.6  300.75
  4699.6  304.21  4709.6  303.21  4719.6  296.86  4739.6  293.02  4809.6  286.49
  4949.6  267.41  4989.6  265.83  4996.6  262.68  4999.3  262.18  5002.6  262.68
  5019.6  265.71  5039.6  265.73  5049.6  267.04  5059.6  266.04  5098.5  268.05
  5149.1  268.06  5247.9  272.37  5276.4  277.21  5290.7  277.46  5297.3  279.55
  5361.3  286.08  5375.3  288.93  5489.5  304.49    5532   306.5  5560.6  306.44
#Mann= 1 ,-1 , 0
  4618.1     .16       0
Bank Sta=4996.6,5002.6
XS Rating Curve= 0 ,0
Exp/Cntr=0.3,0.1

Type RM Length L Ch R = 1 ,2573    ,312,312,312
BEGIN DESCRIPTION:
UNT 125 IN BOCR 5.0
END DESCRIPTION:
XS GIS Cut Line= 3
       3728215.9     10629651.44      3727939.89     10629974.32
      3727607.87     10630155.89
#Sta/Elev= 30
  4684.8  302.43  4688.3  298.41  4709.5  288.95  4723.4  287.24  4737.7  290.75
  4751.9  297.61  4773.9  301.54  4780.5  299.86  4788.2  300.63    4809  290.36
  4823.3  288.58  4844.1  282.58  4907.8  271.25  4936.4   268.5  4944.1  266.16
  4964.9  264.12  4993.5  264.24    4997  259.21  4999.8  258.71    5003  259.21
  5007.7  263.28  5028.6   262.8  5036.3  264.52  5109.6  262.82  5246.7  268.67
  5342.1  276.78  5349.2  279.13  5363.9  280.03  5423.7  289.81    5488  291.46
#Mann= 1 ,-1 , 0
  4684.8     .16       0
Bank Sta=4997,5003
XS Rating Curve= 0 ,0
Exp/Cntr=0.3,0.1

Type RM Length L Ch R = 1 ,2261    ,722,722,722
BEGIN DESCRIPTION:
UNT 125 IN BOCR 4.0
END DESCRIPTION:
XS GIS Cut Line= 3
      3728195.07     10629599.34      3727919.06     10629713.91
      3727623.43     10629739.84
#Sta/Elev= 30
    4600  302.37  4627.6  297.72  4637.2  292.88  4642.6  287.64  4666.4  284.15
  4671.9  284.63  4681.7   289.5  4695.7  292.04  4735.8  283.58  4748.9   279.3
    4790  272.93  4825.9  268.97  4833.3  266.97  4844.1  266.18  4855.2  263.77
  4895.8  262.22  4958.5  263.42  4988.6  263.02  5005.7  258.82  5008.5  258.32
  5011.7  258.82  5018.7   264.6  5025.9  267.28    5089  276.08  5129.2  282.98
  5138.3  285.71  5143.3  285.76  5179.4  293.17  5189.4  294.17  5195.6  296.83
#Mann= 1 ,-1 , 0
    4600     .16       0
Bank Sta=5005.7,5011.7
XS Rating Curve= 0 ,0
Exp/Cntr=0.3,0.1

Type RM Length L Ch R = 1 ,1539    ,140,140,140
BEGIN DESCRIPTION:
Mapping XS 1cc6399d
END DESCRIPTION:
XS GIS Cut Line= 2
      3728110.54     10629306.08      3727214.67     10629330.39
#Sta/Elev= 30
  4653.2  287.91  4714.2  280.57  4724.2  278.35  4734.2  272.92  4764.2  271.39
  4784.2   274.8  4804.2  274.92  4814.2  269.92  4834.2  263.79  4864.2  260.47
  4914.2  259.01  4974.3  260.17  4984.1  259.03  4989.1  260.49  4989.8  259.81
  4991.3  258.36    4994  257.86  4997.3  258.36  5034.3  259.22  5044.3  262.25
  5124.3  275.39  5132.4  275.58  5154.3  274.17  5204.3  277.62  5300.3  289.82
  5353.5  291.46  5358.5  293.81  5404.4  296.56  5484.2  295.02  5549.4  294.01
#Mann= 7 ,-1 , 0
  4653.2     .12       0  4989.8     .16       0  4991.3     .07       0
  4997.3     .16       0  5132.4     .05       0  5300.3     .16       0
  5484.2     .05       0
Bank Sta=4989.1,5034.3
XS Rating Curve= 0 ,0
Exp/Cntr=0.3,0.1