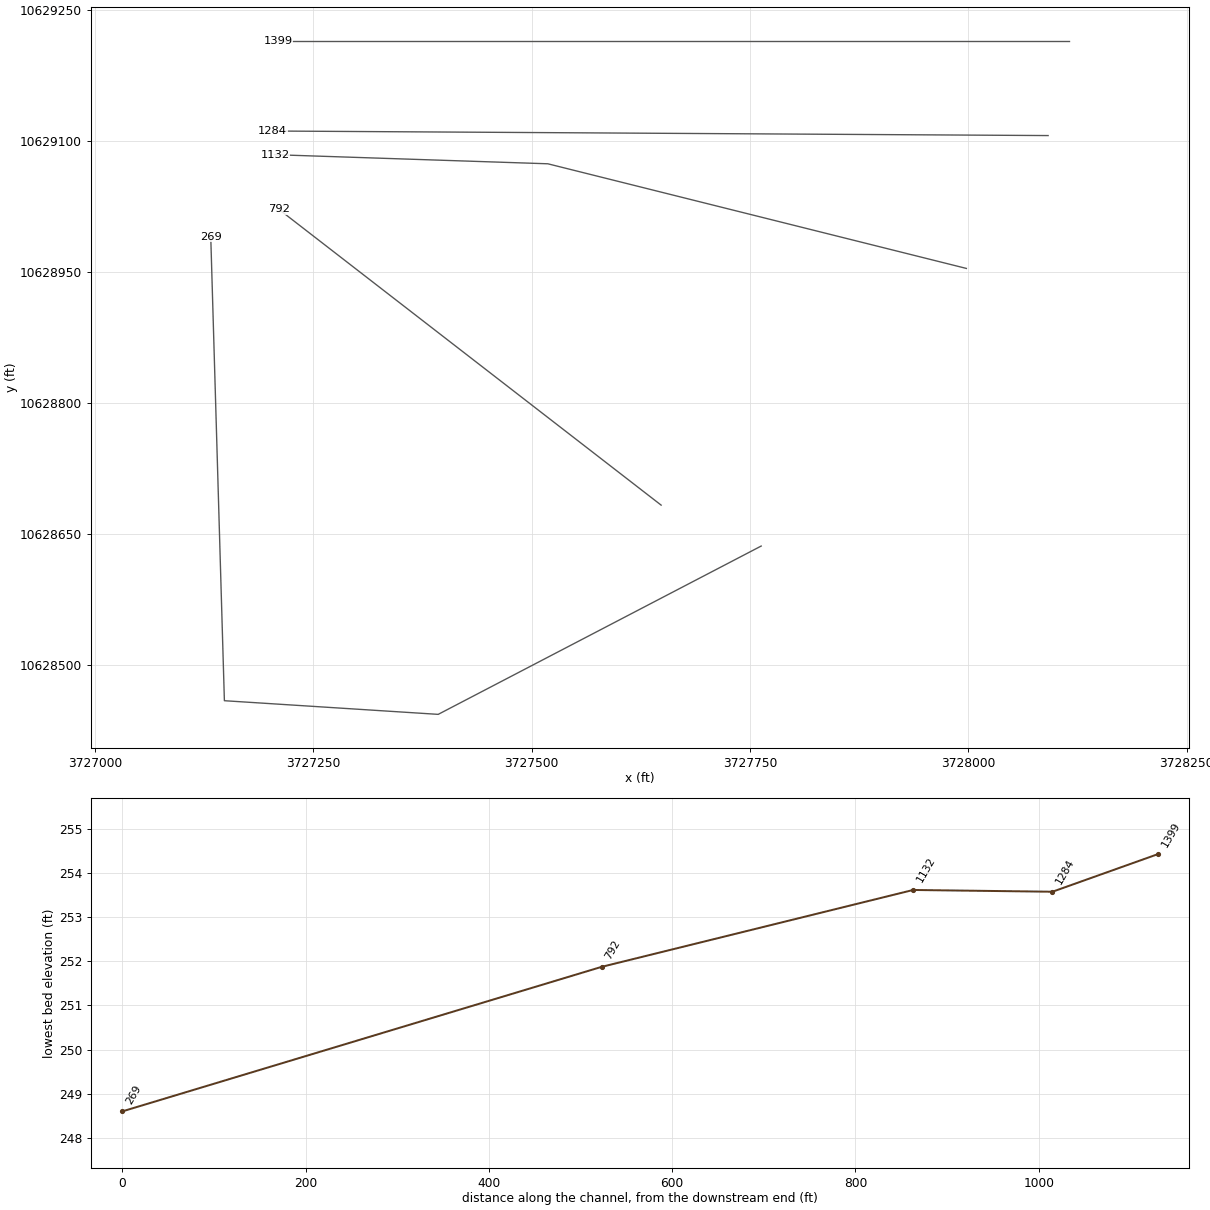
HEC-RAS study UNT 125 IN BOCR.prj: UNT 125 IN BOCR Base Level Engineering

--- UNT 125 IN BOCR.g01 (geometry) --- (continued)

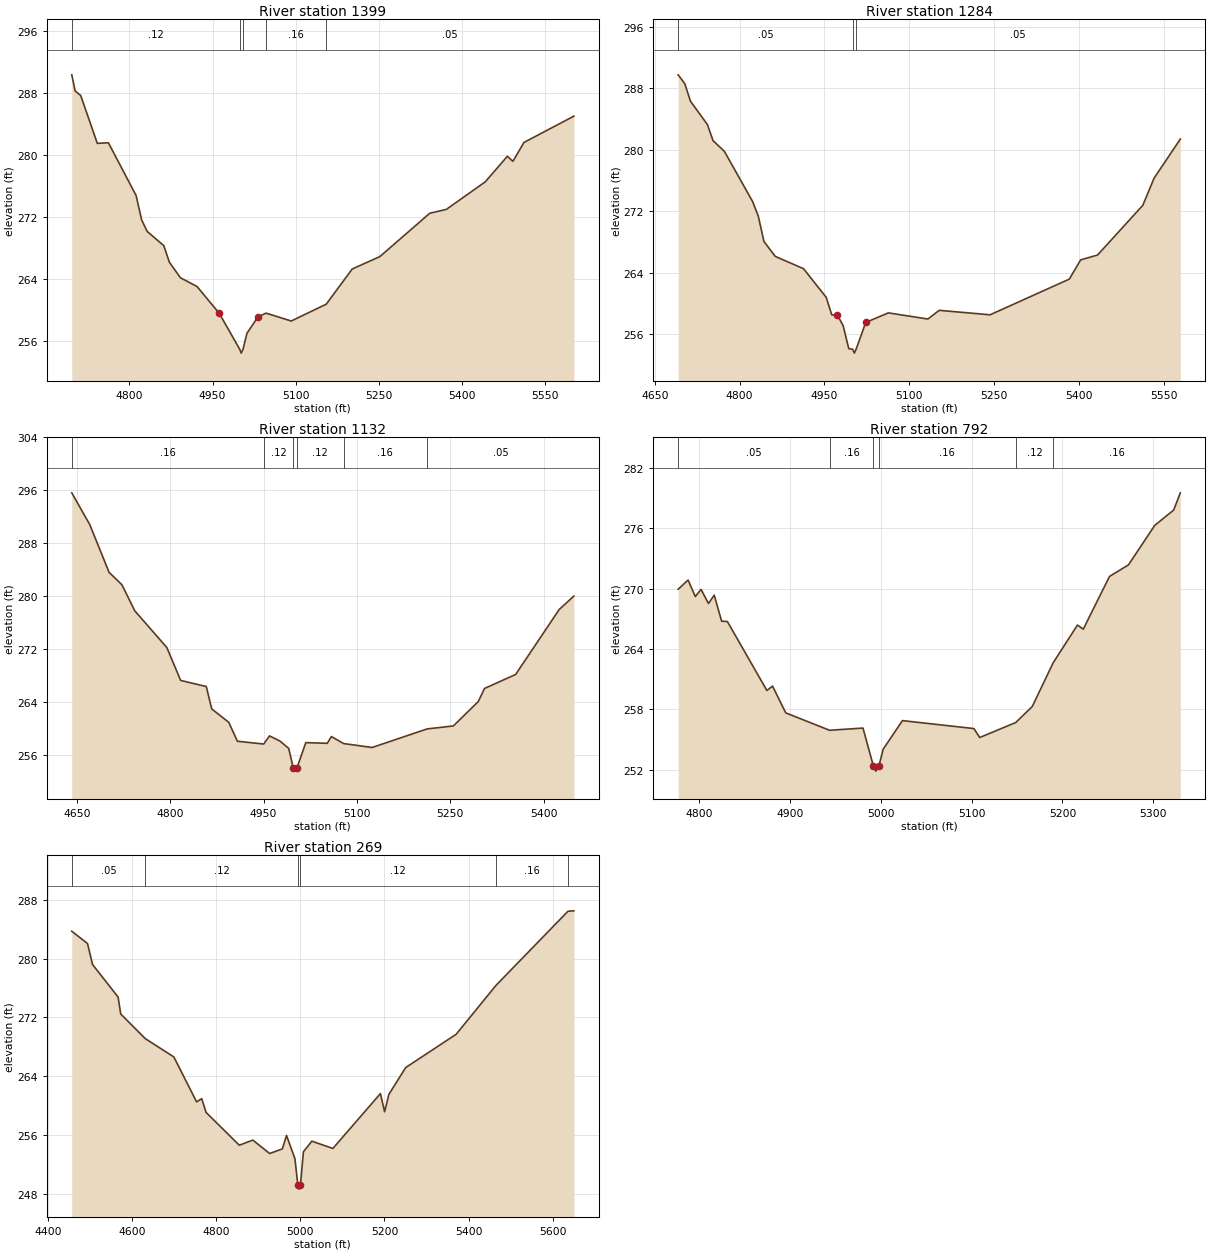
Type RM Length L Ch R = 1 ,1399    ,115,115,115
BEGIN DESCRIPTION:
UNT 125 IN BOCR 3.0
END DESCRIPTION:
XS GIS Cut Line= 2
      3728115.74     10629214.07      3727209.54     10629214.07
#Sta/Elev= 30
  4695.9  290.39    4702   288.3    4712  287.72    4742  281.53    4762  281.61
    4812  274.79    4822  271.64    4832  270.15    4862  268.31    4872  266.18
    4892  264.16    4922  263.03    4962  259.57    4999  254.92  5001.8  254.42
    5005  254.92    5012  256.98    5032   259.1  5046.5  259.59    5092  258.57
  5155.2  260.75    5202  265.29    5252   266.9    5342   272.5    5372     273
    5442  276.55    5482  279.86    5492  279.21    5512  281.65  5602.1  285.05
#Mann= 5 ,-1 , 0
  4695.9     .12       0    4999     .07       0    5005     .12       0
  5046.5     .16       0  5155.2     .05       0
Bank Sta=4962,5032
XS Rating Curve= 0 ,0
Exp/Cntr=0.3,0.1

Type RM Length L Ch R = 1 ,1284    ,152,152,152
BEGIN DESCRIPTION:
UNT 125 IN BOCR 2.0
END DESCRIPTION:
XS GIS Cut Line= 2
      3728091.35     10629105.76      3727203.26     10629110.96
#Sta/Elev= 30
  4691.5  289.73  4703.2  288.58  4713.2  286.31  4743.2  283.27  4753.2  281.18
  4773.2  279.79  4823.2  273.26  4833.2  271.37  4843.2  268.08  4863.2  266.14
  4913.2  264.54  4953.2  260.83  4963.2  258.54  4973.2  258.49  4983.2  257.16
  4993.2  254.16  5000.2  254.07    5003  253.57  5006.2  254.07  5023.2  257.55
  5063.2   258.8  5133.2     258  5153.2  259.13  5243.2  258.55  5383.3  263.19
  5403.3  265.68  5433.3  266.32  5513.3  272.78  5533.3  276.31  5579.6  281.38
#Mann= 3 ,-1 , 0
  4691.5     .05       0  5000.2     .04       0  5006.2     .05       0
Bank Sta=4973.2,5023.2
XS Rating Curve= 0 ,0
Exp/Cntr=0.3,0.1

Type RM Length L Ch R = 1 ,1132    ,340,340,340
BEGIN DESCRIPTION:
Mapping XS 38e79fd1
END DESCRIPTION:
XS GIS Cut Line= 3
      3727997.74     10628953.64      3727518.53     10629073.45
      3727206.06     10629083.86
#Sta/Elev= 30
  4641.9  295.62  4670.9  290.81  4701.8  283.62  4722.4  281.75  4743.1  277.81
  4794.6  272.27  4816.8   267.3    4858  266.38  4866.7     263  4894.1  260.98
    4908  258.12  4950.2   257.7  4959.5  258.93  4976.5  258.14  4990.4  257.04
  4997.7  254.11  5000.5  253.61  5003.7  254.11  5017.8  257.91  5052.3  257.81
    5059  258.83  5078.6  257.77  5124.4  257.18  5212.7  259.98  5254.8  260.43
  5294.9  264.11  5304.9  266.09  5354.9   268.2  5424.9  278.01  5448.5  280.04
#Mann= 6 ,-1 , 0
  4641.9     .16       0  4950.2     .12       0  4997.7     .07       0
  5003.7     .12       0  5078.6     .16       0  5212.7     .05       0
Bank Sta=4997.7,5003.7
XS Rating Curve= 0 ,0
Exp/Cntr=0.3,0.1

Type RM Length L Ch R = 1 ,792     ,523,523,523
BEGIN DESCRIPTION:
Mapping XS 6c6270b2
END DESCRIPTION:
XS GIS Cut Line= 2
      3727648.25     10628682.64      3727210.74     10629021.19
#Sta/Elev= 30
  4776.6  269.95  4787.5  270.86  4795.5  269.22  4801.8  269.93    4810  268.53
  4816.3  269.36  4824.5  266.77  4830.8  266.74  4874.3  259.89  4880.6  260.32
  4895.1  257.66  4943.4  255.93  4980.2  256.15  4991.7  252.37  4994.4  251.87
  4997.7  252.37  5002.5  254.06  5023.7  256.89  5102.4   256.1  5108.8  255.21
  5148.5   256.7  5166.7  258.29  5189.7  262.63  5216.5  266.39  5222.9  265.98
  5251.8  271.22  5272.7  272.37  5301.6  276.29  5322.5  277.82  5329.8  279.53
#Mann= 6 ,-1 , 0
  4776.6     .05       0  4943.4     .16       0  4991.7     .07       0
  4997.7     .16       0  5148.5     .12       0  5189.7     .16       0
Bank Sta=4991.7,4997.7
XS Rating Curve= 0 ,0
Exp/Cntr=0.3,0.1

Type RM Length L Ch R = 1 ,269     ,0,0,0
BEGIN DESCRIPTION:
UNT 125 IN BOCR 1.0
END DESCRIPTION:
XS GIS Cut Line= 4
       3727762.8     10628635.78      3727393.01     10628443.07
      3727148.22      10628458.7       3727132.6     10628989.99
#Sta/Elev= 30
  4456.6  283.72    4494  282.05  4506.1  279.18  4566.7  274.76    4573  272.45
  4631.3   269.1  4699.3   266.6  4753.4  260.48  4765.6  260.92  4775.9  259.05
  4854.9  254.58    4887  255.28  4927.1  253.45  4957.2  254.08  4967.2  255.91
  4987.2  252.73  4994.2   249.1    4997   248.6  5000.2   249.1  5007.3  253.68
  5027.3  255.13  5077.4  254.14  5190.4  261.61  5200.4  259.13  5210.4  261.49
  5250.4  265.15  5370.5  269.69  5465.2  276.35  5636.3  286.44  5650.4   286.5
#Mann= 6 ,-1 , 0
  4456.6     .05       0  4631.3     .12       0  4994.2     .07       0
  5000.2     .12       0  5465.2     .16       0  5636.3     .05       0
Bank Sta=4994.2,5000.2
XS Rating Curve= 0 ,0
Exp/Cntr=0.3,0.1

Chan Stop Cuts=-1
Use User Specified Reach Order=0
Composite Channel Slope=5