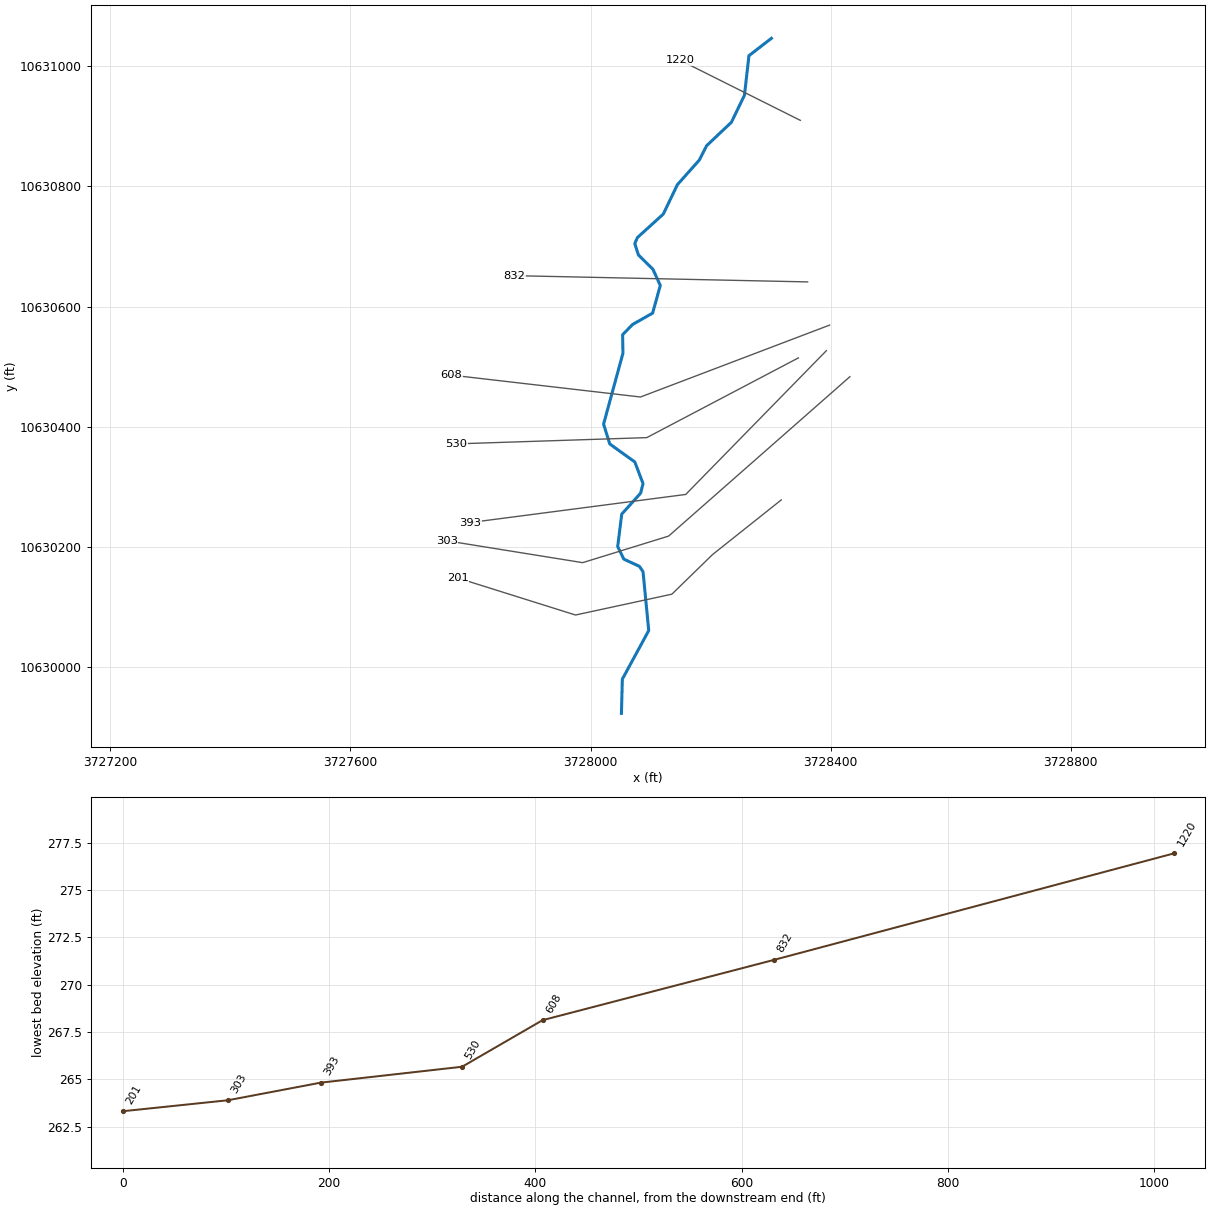
--- UNT 126 IN BOCR.prj (project) ---

Proj Title=UNT 126 IN BOCR Base Level Engineering
Current Plan=p01
Default Exp/Contr=0.3,0.1
English Units
Geom File=g01
Flow File=f01
Plan File=p01
Y Axis Title=Elevation
X Axis Title(PF)=Main Channel Distance
X Axis Title(XS)=Station
BEGIN DESCRIPTION:
UNT 126 IN BOCR
END DESCRIPTION:
DSS Export Rating Curves= 0
DSS Export Rating Curve Sorted= 0
DSS Export Volume Flow Curves= 0
DXF OffsetX= 0
DXF OffsetY= 0
DXF ScaleX= 1
DXF ScaleY= 10

--- UNT 126 IN BOCR.p01 (plan) ---

Plan Title=Multiple Run
Short Identifier=Multiple
Geom File=g01
Flow File=f01
Subcritical Flow
K Sum by GR= 0
Std Step Tol= 0.01
Critical Tol= 0.01
Num of Std Step Trials= 20
Max Error Tol= 0.3
Flow Tol Ratio= 0.001
Split Flow NTrial= 30
Split Flow Tol= 0.02
Split Flow Ratio= 0.02
Log Output Level= 0
Friction Slope Method= 1
Unsteady Friction Slope Method= 2
Unsteady Bridges Friction Slope Method= 1
Parabolic Critical Depth
Global Vel Dist=  1 , 1 , 1
Global Log Level= 0
CheckData=True
Encroach Param= -1, 0, 0, 0
BEGIN DESCRIPTION:
Multiple Run
END DESCRIPTION:

--- UNT 126 IN BOCR.f01 (steady flow) ---

Flow Title=Multiple
Program Version=4.10
Number of Profiles= 7
Profile Names=10-year,25-year,50-year,1pct_min,100-year,1pct_plu,500-year
River Rch & RM=UNT 126 IN BOCR,Reach-1         ,1220
     210     266     310     267     361     488     488
River Rch & RM=UNT 126 IN BOCR,Reach-1         ,201
     659     896    1093     981    1326    1793    1958
Boundary for River Rch & Prof#=UNT 126 IN BOCR,Reach-1         , 1
Up Type= 0
Dn Type= 3
Dn Slope=0.007
Boundary for River Rch & Prof#=UNT 126 IN BOCR,Reach-1         , 2
Up Type= 0
Dn Type= 3
Dn Slope=0.007
Boundary for River Rch & Prof#=UNT 126 IN BOCR,Reach-1         , 3
Up Type= 0
Dn Type= 3
Dn Slope=0.007
Boundary for River Rch & Prof#=UNT 126 IN BOCR,Reach-1         , 4
Up Type= 0
Dn Type= 3
Dn Slope=0.007
Boundary for River Rch & Prof#=UNT 126 IN BOCR,Reach-1         , 5
Up Type= 0
Dn Type= 3
Dn Slope=0.007
Boundary for River Rch & Prof#=UNT 126 IN BOCR,Reach-1         , 6
Up Type= 0
Dn Type= 3
Dn Slope=0.007
Boundary for River Rch & Prof#=UNT 126 IN BOCR,Reach-1         , 7
Up Type= 0
Dn Type= 3
Dn Slope=0.007
DSS Import GetInterval= 0
DSS Import GetPeak= 0
DSS Import FillOption= 0

--- UNT 126 IN BOCR.g01 (geometry) ---

Geom Title=Existing Conditions
Program Version=4.10

River Reach=UNT 126 IN BOCR ,Reach-1
Reach XY= 30
       3728301.4     10631046.87        3728264.       10631018.
       3728256.5       10630952.      3728234.75       10630907.
       3728193.5       10630868.      3728181.25       10630844.
      3728144.75       10630803.      3728121.25       10630754.
      3728078.25       10630715.      3728073.75       10630705.
      3728079.75       10630686.        3728104.       10630662.
      3728116.25       10630635.       3728103.5       10630589.
        3728070.       10630570.       3728053.5       10630553.
        3728054.       10630522.      3728021.75       10630404.
        3728032.       10630371.      3728073.75       10630341.
       3728087.5       10630305.       3728083.5       10630289.
        3728052.       10630254.      3728045.25       10630200.
       3728055.5       10630179.       3728081.5       10630167.
       3728087.5       10630158.        3728097.       10630060.
        3728053.       10629979.       3728051.5       10629922.

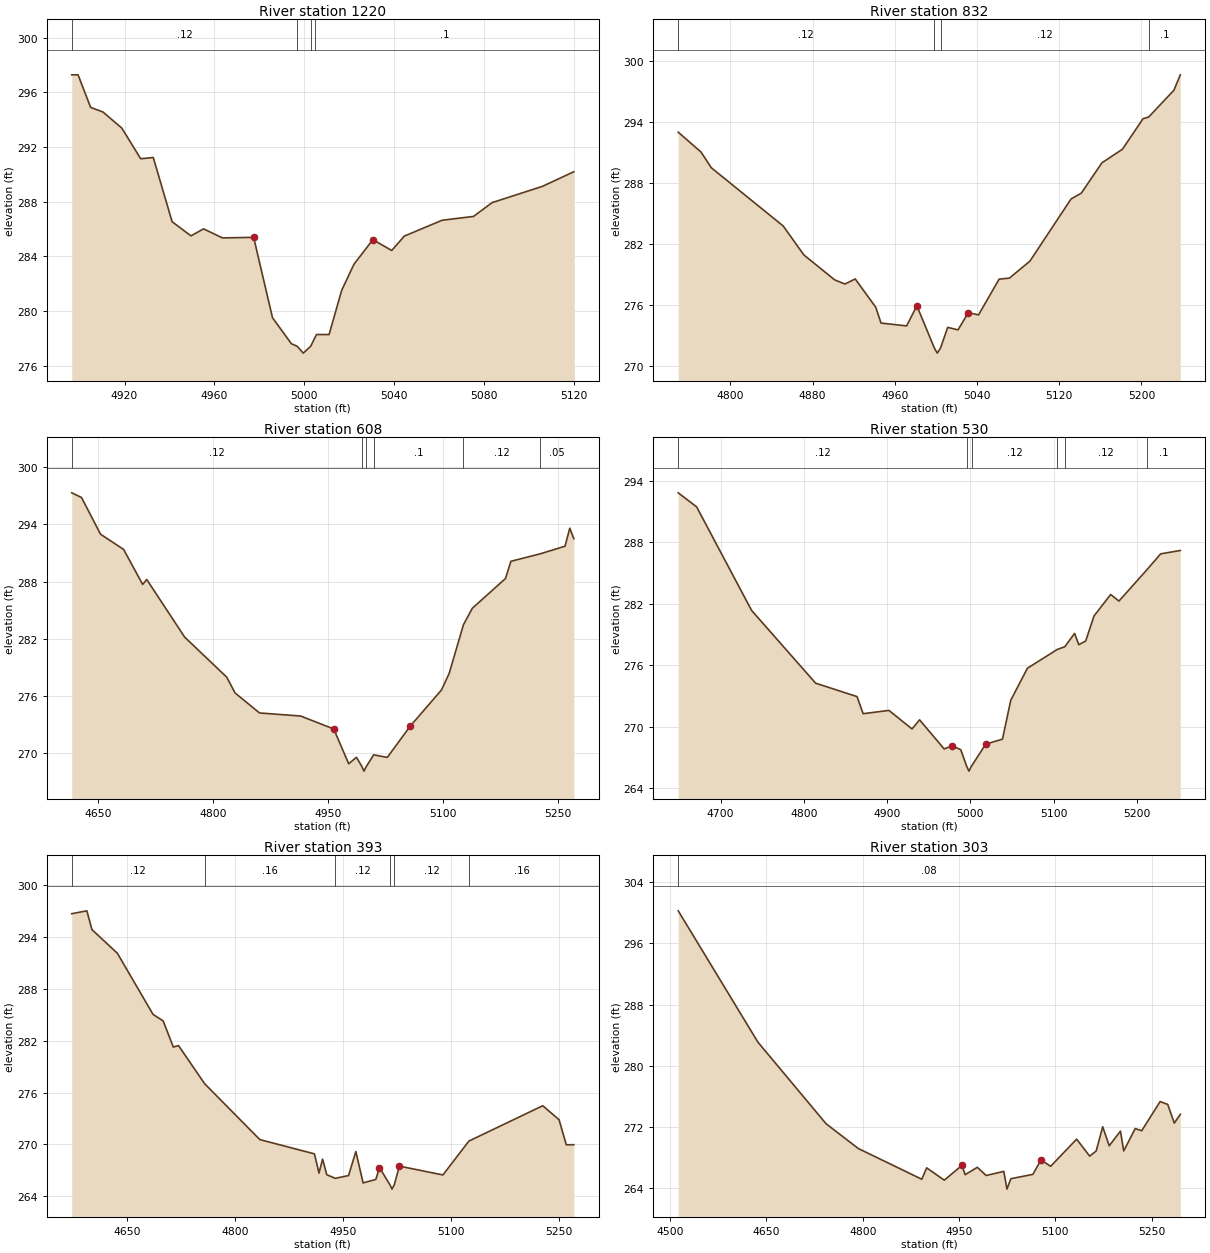
Type RM Length L Ch R = 1 ,1220    ,388,388,388
BEGIN DESCRIPTION:
UNT 126 IN BOCR 2.0
END DESCRIPTION:
XS GIS Cut Line= 3
      3728349.58      10630910.2      3728249.61     10630960.19
      3728149.59      10631010.2
#Sta/Elev= 30
  4896.5  297.29  4899.3  297.29  4904.9  294.91  4910.4  294.57  4918.8  293.39
  4927.2  291.15  4932.8  291.24  4941.2  286.54  4949.6  285.51  4955.2  286.02
  4963.6  285.36  4977.5   285.4  4985.9  279.52  4994.3  277.62  4996.9  277.43
  4999.6  276.93  5002.9  277.43  5004.7  278.03  5005.5  278.29  5011.1  278.29
  5016.7  281.52  5022.2  283.44  5030.6  285.23    5039  284.44  5044.6  285.49
  5061.4  286.65  5075.4  286.93  5083.7  287.94  5106.1  289.13  5120.1   290.2
#Mann= 4 ,-1 , 0
  4896.5     .12       0  4996.9     .07       0  5002.9     .12       0
  5004.7      .1       0
Bank Sta=4977.5,5030.6
XS Rating Curve= 0 ,0
Exp/Cntr=0.3,0.1

Type RM Length L Ch R = 1 ,832     ,224,224,224
BEGIN DESCRIPTION:
Mapping XS 29b85033
END DESCRIPTION:
XS GIS Cut Line= 2
      3728361.76     10630640.99      3727873.37     10630651.38
#Sta/Elev= 30
  4749.3  292.98  4771.5  291.03  4781.5  289.49  4851.5  283.77  4871.5  280.94
  4901.5  278.49  4911.5  278.08  4921.5  278.58  4941.5   275.8  4946.6  274.25
  4971.5  273.97  4981.5  275.94  4998.5   271.8  5001.3   271.3  5004.5   271.8
  5011.5  273.83  5021.5  273.58  5031.5  275.27  5041.5  275.05  5061.5  278.56
  5071.5  278.66  5091.5  280.33  5131.5  286.43  5141.5     287  5161.5  289.97
  5181.5  291.31  5201.5   294.3    5207  294.47  5231.6   297.1  5237.8  298.61
#Mann= 4 ,-1 , 0
  4749.3     .12       0  4998.5     .07       0  5004.5     .12       0
    5207      .1       0
Bank Sta=4981.5,5031.5
XS Rating Curve= 0 ,0
Exp/Cntr=0.3,0.1

Type RM Length L Ch R = 1 ,608     ,78,78,78
BEGIN DESCRIPTION:
Mapping XS 553eda05
END DESCRIPTION:
XS GIS Cut Line= 3
      3728398.34     10630568.99      3728083.26     10630449.21
      3727768.15     10630485.67
#Sta/Elev= 30
  4616.2  297.31  4628.9  296.82  4653.7  292.97  4683.8  291.37  4708.6   287.7
  4713.9  288.22  4763.4  282.17  4818.1  277.98    4829  276.32  4860.9  274.22
  4914.4   273.9  4957.6  272.54  4977.1  268.89  4987.2  269.57  4994.2  268.62
    4997  268.12  5000.2  268.62  5009.6  269.83  5027.4  269.56  5057.6  272.87
  5097.9  276.62    5108  278.36  5126.6  283.47  5138.2   285.2  5181.4  288.32
  5188.5  290.13  5226.6  290.91    5259  291.71  5265.2   293.6  5270.5   292.5
#Mann= 6 ,-1 , 0
  4616.2     .12       0  4994.2     .07       0  5000.2     .12       0
  5009.6      .1       0  5126.6     .12       0  5226.6     .05       0
Bank Sta=4957.6,5057.6
XS Rating Curve= 0 ,0
Exp/Cntr=0.3,0.1

Type RM Length L Ch R = 1 ,530     ,137,137,137
BEGIN DESCRIPTION:
Mapping XS bf9365a7
END DESCRIPTION:
XS GIS Cut Line= 3
      3728346.31     10630514.33      3728093.68      10630381.5
      3727775.97     10630371.08
#Sta/Elev= 30
    4649  292.84  4671.1  291.47  4737.2  281.35  4814.1  274.25  4863.8  272.94
  4871.2  271.27  4902.2  271.59  4929.9  269.78    4939  270.67  4968.5  267.83
  4978.5  268.13  4988.5  267.75  4995.5  266.16  4998.3  265.66  5001.5  266.16
  5018.5   268.3  5038.6  268.78  5048.6  272.59  5068.6  275.71  5104.4  277.54
  5113.5  277.81  5125.3  279.11  5130.3  278.01  5138.6  278.37  5148.6  280.81
  5168.6  282.91  5178.6  282.27  5212.3  285.34  5228.7  286.88  5252.3  287.21
#Mann= 6 ,-1 , 0
    4649     .12       0  4995.5     .07       0  5001.5     .12       0
  5104.4      .1       0  5113.5     .12       0  5212.3      .1       0
Bank Sta=4978.5,5018.5
XS Rating Curve= 0 ,0
Exp/Cntr=0.3,0.1

Type RM Length L Ch R = 1 ,393     ,90,90,90
BEGIN DESCRIPTION:
UNT 126 IN BOCR 1.0
END DESCRIPTION:
XS GIS Cut Line= 3
      3728393.01      10630526.4      3728158.64     10630286.82
      3727799.23     10630239.94
#Sta/Elev= 30
  4573.6  296.69  4594.6  297.02  4601.6  294.85    4637  292.11  4686.5  285.04
  4700.6  284.28  4714.7  281.26  4721.9  281.43  4758.2  277.02  4834.9  270.55
  4910.8   268.9  4917.1  266.68  4922.1  268.29  4927.9  266.49  4939.7  266.07
  4958.2  266.39  4968.3  269.17  4978.4  265.54  4996.1  265.94  5001.1  267.32
  5015.7  265.32  5018.5  264.82  5021.7  265.32  5028.8  267.48  5089.3  266.46
  5125.4  270.38    5228  274.47  5250.7  272.85  5260.7  269.95  5271.2  269.96
#Mann= 6 ,-1 , 0
  4573.6     .12       0  4758.2     .16       0  4939.7     .12       0
  5015.7     .07       0  5021.7     .12       0  5125.4     .16       0
Bank Sta=5001.1,5028.8
XS Rating Curve= 0 ,0
Exp/Cntr=0.3,0.1

Type RM Length L Ch R = 1 ,303     ,102,102,102
BEGIN DESCRIPTION:
Mapping XS 24b31c44
END DESCRIPTION:
XS GIS Cut Line= 4
      3728432.22     10630483.06      3728130.13     10630217.44
      3727986.91     10630173.16       3727760.3     10630209.63
#Sta/Elev= 30
  4512.8  300.25  4636.8   283.1    4743  272.43  4793.3  269.19    4892  265.18
  4899.6  266.67    4927  265.06  4954.4  266.98  4959.6  265.78  4978.4  266.74
  4992.3  265.67  5019.7  266.21  5024.6  263.89  5030.7  265.25    5065  265.82
  5077.6  267.71  5092.6  266.87  5133.1  270.42  5153.4   268.2  5163.5  268.87
  5173.7  272.04  5183.8  269.55  5201.3  271.47  5206.4  268.88  5224.3   271.8
  5234.4  271.52  5263.1  275.33  5274.9  274.96  5285.1  272.52  5294.5  273.66
#Mann= 1 ,-1 , 0
  4512.8     .08       0
Bank Sta=4954.4,5077.6
XS Rating Curve= 0 ,0
Exp/Cntr=0.3,0.1

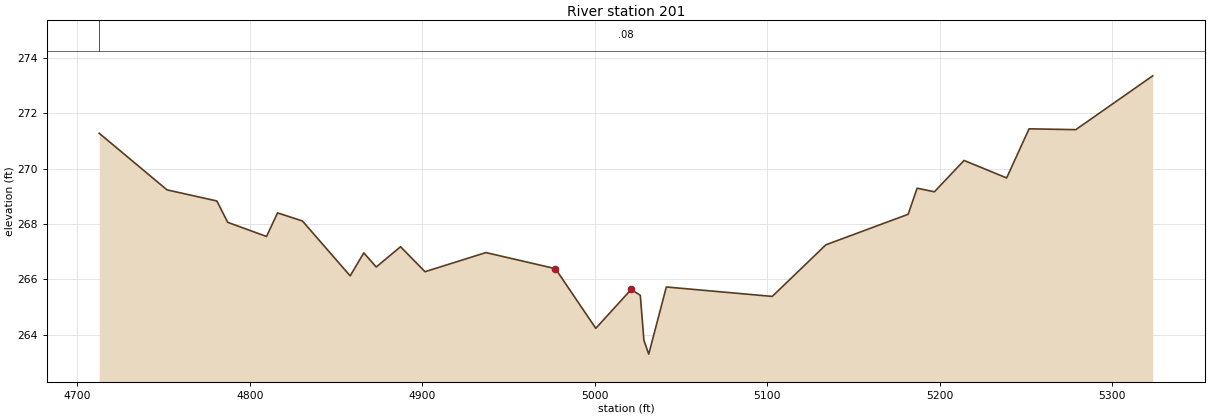
Type RM Length L Ch R = 1 ,201     ,0,0,0
BEGIN DESCRIPTION:
Mapping XS 451e64dc
END DESCRIPTION:
XS GIS Cut Line= 5
      3728317.83     10630277.72      3728203.28      10630186.6
      3728135.57     10630120.63      3727974.98     10630085.91
      3727778.83     10630147.53
#Sta/Elev= 30
  4712.6  271.27  4751.9  269.23  4780.8  268.83  4787.1  268.06  4809.6  267.55
    4816   268.4  4830.4  268.11  4858.1  266.13    4866  266.96  4873.2  266.45
  4887.3  267.18  4901.5  266.28  4936.8  266.97  4977.1  266.39  5000.5  264.24
    5021  265.64  5026.3  265.43  5028.4  263.81  5031.2  263.31  5041.4  265.73
  5102.8  265.39  5133.9  267.25  5181.6  268.35  5186.8  269.29  5196.8  269.16
    5214  270.29  5238.7  269.66  5251.7  271.43  5278.8   271.4  5323.4  273.34
#Mann= 1 ,-1 , 0
  4712.6     .08       0
Bank Sta=4977.1,5021
XS Rating Curve= 0 ,0
Exp/Cntr=0.3,0.1

Chan Stop Cuts=-1
Use User Specified Reach Order=0
Composite Channel Slope=5