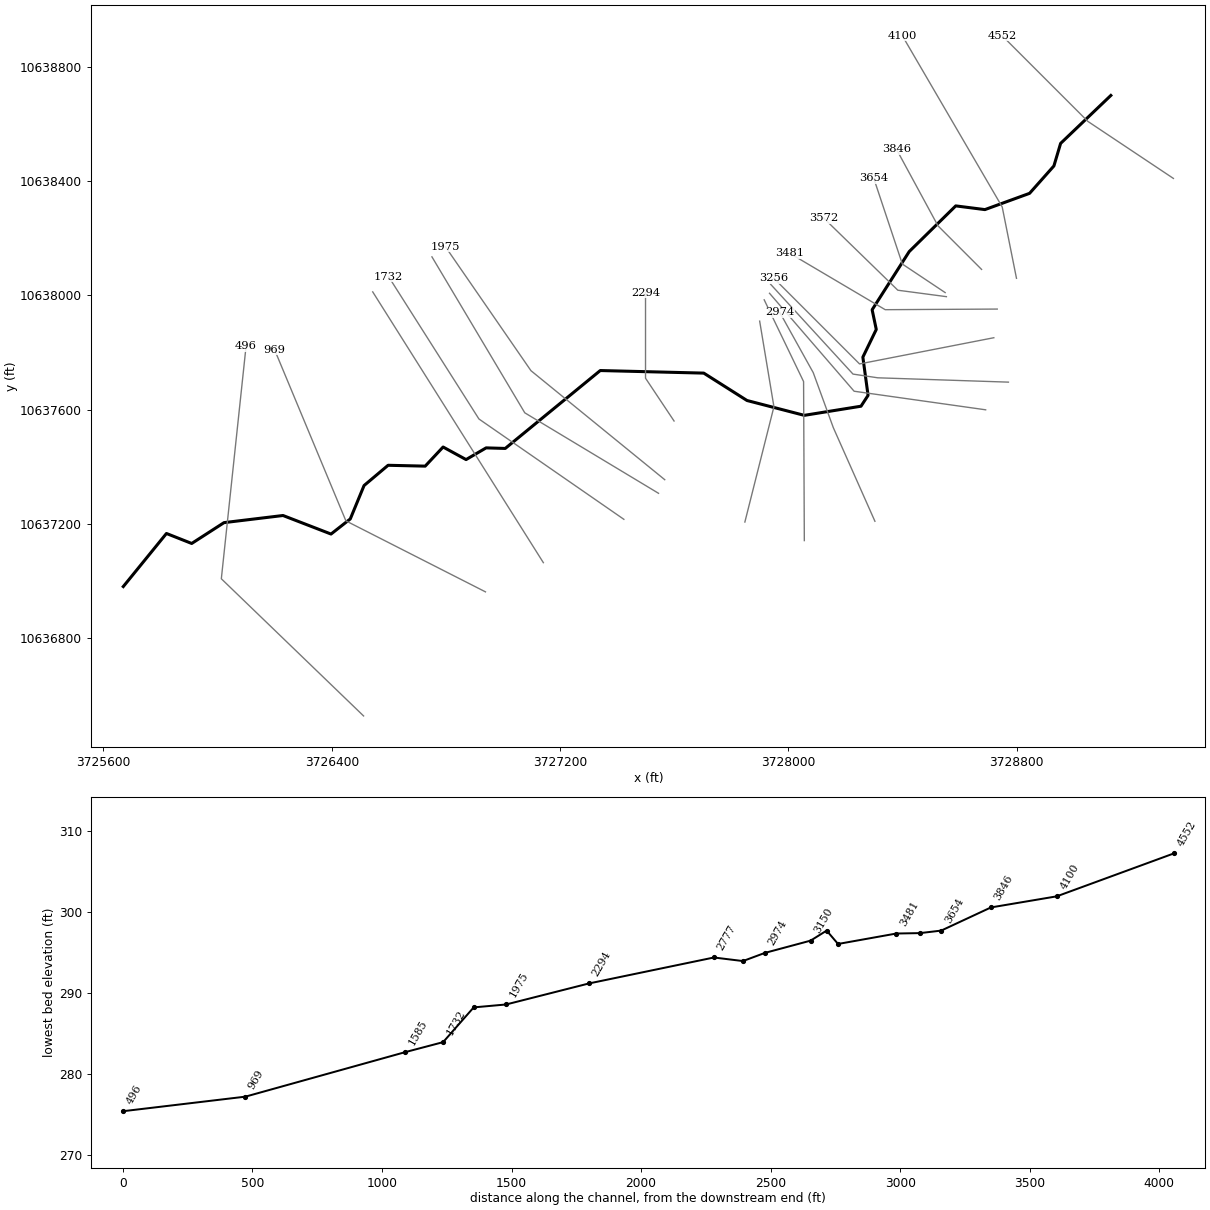
--- UNT 128 IN BOCR.prj (project) ---

Proj Title=UNT 128 IN BOCR Base Level Engineering
Current Plan=p01
Default Exp/Contr=0.3,0.1
English Units
Geom File=g01
Flow File=f01
Plan File=p01
Y Axis Title=Elevation
X Axis Title(PF)=Main Channel Distance
X Axis Title(XS)=Station
BEGIN DESCRIPTION:
UNT 128 IN BOCR
END DESCRIPTION:
DSS Export Rating Curves= 0
DSS Export Rating Curve Sorted= 0
DSS Export Volume Flow Curves= 0
DXF OffsetX= 0
DXF OffsetY= 0
DXF ScaleX= 1
DXF ScaleY= 10

--- UNT 128 IN BOCR.p01 (plan) ---

Plan Title=Multiple Run
Short Identifier=Multiple
Geom File=g01
Flow File=f01
Subcritical Flow
K Sum by GR= 0
Std Step Tol= 0.01
Critical Tol= 0.01
Num of Std Step Trials= 20
Max Error Tol= 0.3
Flow Tol Ratio= 0.001
Split Flow NTrial= 30
Split Flow Tol= 0.02
Split Flow Ratio= 0.02
Log Output Level= 0
Friction Slope Method= 1
Unsteady Friction Slope Method= 2
Unsteady Bridges Friction Slope Method= 1
Parabolic Critical Depth
Global Vel Dist=  1 , 1 , 1
Global Log Level= 0
CheckData=True
Encroach Param= -1, 0, 0, 0
BEGIN DESCRIPTION:
Multiple Run
END DESCRIPTION:

--- UNT 128 IN BOCR.f01 (steady flow) ---

Flow Title=Multiple
Program Version=4.10
Number of Profiles= 7
Profile Names=10-year,25-year,50-year,1pct_min,100-year,1pct_plu,500-year
River Rch & RM=UNT 128 IN BOCR,Reach-1         ,4552
     578     784     955     856    1158    1566    1707
Boundary for River Rch & Prof#=UNT 128 IN BOCR,Reach-1         , 1
Up Type= 0
Dn Type= 3
Dn Slope=0.008
Boundary for River Rch & Prof#=UNT 128 IN BOCR,Reach-1         , 2
Up Type= 0
Dn Type= 3
Dn Slope=0.008
Boundary for River Rch & Prof#=UNT 128 IN BOCR,Reach-1         , 3
Up Type= 0
Dn Type= 3
Dn Slope=0.008
Boundary for River Rch & Prof#=UNT 128 IN BOCR,Reach-1         , 4
Up Type= 0
Dn Type= 3
Dn Slope=0.008
Boundary for River Rch & Prof#=UNT 128 IN BOCR,Reach-1         , 5
Up Type= 0
Dn Type= 3
Dn Slope=0.008
Boundary for River Rch & Prof#=UNT 128 IN BOCR,Reach-1         , 6
Up Type= 0
Dn Type= 3
Dn Slope=0.008
Boundary for River Rch & Prof#=UNT 128 IN BOCR,Reach-1         , 7
Up Type= 0
Dn Type= 3
Dn Slope=0.008
DSS Import GetInterval= 0
DSS Import GetPeak= 0
DSS Import FillOption= 0

--- UNT 128 IN BOCR.g01 (geometry) ---

Geom Title=Existing Conditions
Program Version=4.10

River Reach=UNT 128 IN BOCR ,Reach-1
Reach XY= 30
      3729130.25       10638701.      3728954.25       10638533.
      3728930.75       10638454.       3728845.5       10638358.
        3728689.       10638301.      3728586.75       10638314.
      3728423.75       10638154.      3728293.75       10637950.
      3728308.25       10637881.      3728261.25       10637784.
       3728279.5       10637650.      3728254.75       10637612.
        3728056.       10637580.      3727855.25       10637632.
      3727703.75       10637728.        3727341.       10637737.
        3727008.       10637464.        3726941.       10637466.
      3726870.75       10637425.      3726790.25       10637469.
       3726727.5       10637402.       3726597.5       10637405.
      3726513.25       10637334.        3726465.       10637217.
       3726397.5       10637164.      3726229.25       10637229.
       3726022.5       10637204.      3725909.25       10637131.
      3725820.75       10637166.       3725669.5       10636980.

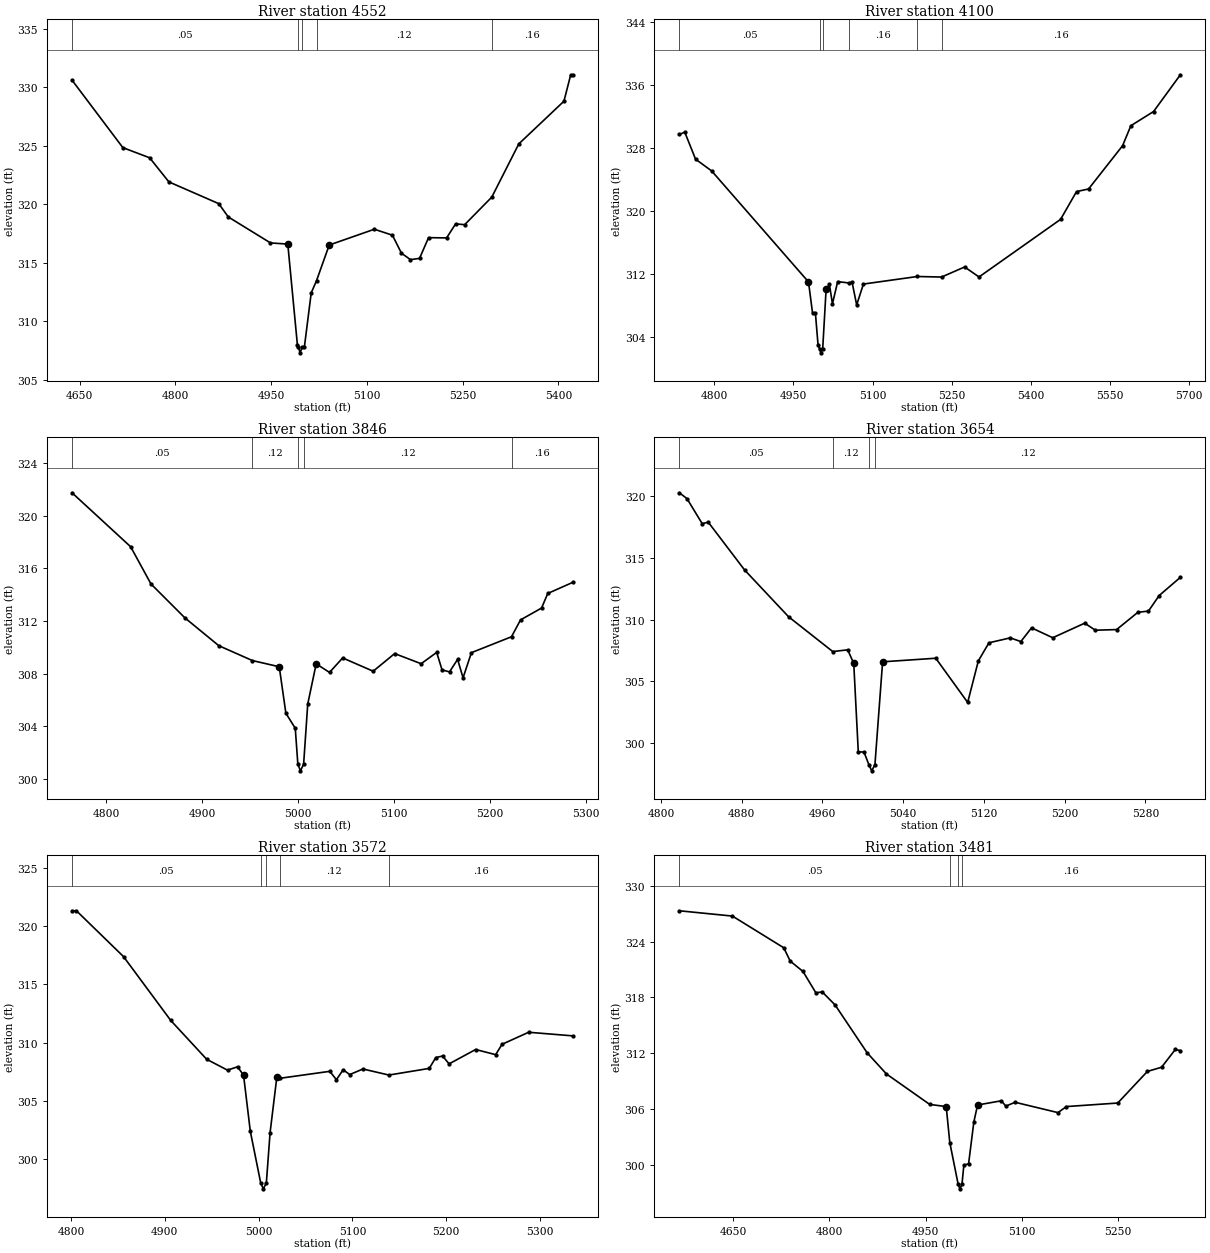
Type RM Length L Ch R = 1 ,4552    ,452,452,452
BEGIN DESCRIPTION:
UNT 128 IN BOCR 10.0
END DESCRIPTION:
XS GIS Cut Line= 3
      3729349.57     10638410.21      3729049.61     10638610.19
      3728749.59     10638910.21
#Sta/Elev= 30
  4638.2  330.61  4717.8  324.84  4759.8  323.97  4789.9  321.91    4868  320.05
    4883  318.91  4949.1  316.69  4976.2  316.59  4991.2     308  4992.7  307.79
  4995.5  307.29  4998.7  307.79  5002.2  307.79  5012.9  312.42  5021.2  313.46
  5041.1  316.51  5111.8  317.86  5140.1  317.35  5154.3  315.81  5168.4  315.26
  5182.6  315.37  5196.7  317.14    5225  317.12  5239.1  318.32  5253.3  318.25
  5295.8  320.61  5338.1  325.16  5408.8  328.81  5419.4  331.07    5423  331.07
#Mann= 5 ,-1 , 0
  4638.2     .05       0  4992.7     .03       0  4998.7     .05       0
  5021.2     .12       0  5295.8     .16       0
Bank Sta=4976.2,5041.1
XS Rating Curve= 0 ,0
Exp/Cntr=0.3,0.1

Type RM Length L Ch R = 1 ,4100    ,254,254,254
BEGIN DESCRIPTION:
UNT 128 IN BOCR 9.0
END DESCRIPTION:
XS GIS Cut Line= 3
       3728799.6     10638060.23      3728749.61     10638310.19
      3728399.63     10638910.16
#Sta/Elev= 30
  4733.9  329.74  4744.1  330.03  4764.5   326.6  4795.1   325.1  4978.6     311
  4986.3  307.03  4991.7  307.03  4996.7  302.99  4999.5  302.49  5002.2  301.99
  5005.5  302.49    5012  310.09  5018.2  310.69    5024  308.22  5033.9  311.04
  5054.9  310.87  5061.2  310.96  5069.9  308.08  5082.7  310.73  5185.1  311.69
  5230.8  311.62  5274.5   312.9  5301.8  311.63  5456.4  318.95  5486.6  322.48
  5509.4  322.81  5573.9  328.31  5589.6  330.85  5632.6  332.65  5683.4  337.32
#Mann= 6 ,-1 , 0
  4733.9     .05       0  4999.5     .03       0  5005.5     .05       0
  5054.9     .16       0  5185.1     .12       0  5230.8     .16       0
Bank Sta=4978.6,5012
XS Rating Curve= 0 ,0
Exp/Cntr=0.3,0.1

Type RM Length L Ch R = 1 ,3846    ,192,192,192
BEGIN DESCRIPTION:
Mapping XS bc86f977
END DESCRIPTION:
XS GIS Cut Line= 3
      3728677.24     10638091.39      3728524.45     10638244.18
      3728378.59     10638513.32
#Sta/Elev= 30
  4764.2  321.75  4825.3  317.65  4846.5  314.82  4881.9  312.24  4917.2  310.13
  4952.2     309  4980.2  308.53  4987.1     305  4996.9  303.85  4999.6  301.12
  5002.3  300.62  5005.6  301.12  5009.9   305.7  5018.7  308.75  5032.6   308.1
  5046.3   309.2  5078.1  308.19  5100.5  309.53  5128.1  308.76  5144.3  309.62
  5149.9  308.29  5157.7  308.14  5166.1  309.09  5171.8  307.69  5180.5   309.6
  5222.3  310.81  5231.7  312.09  5253.6  312.99  5260.1   314.1  5286.4  314.95
#Mann= 5 ,-1 , 0
  4764.2     .05       0  4952.2     .12       0  4999.6     .07       0
  5005.6     .12       0  5222.3     .16       0
Bank Sta=4980.2,5018.7
XS Rating Curve= 0 ,0
Exp/Cntr=0.3,0.1

Type RM Length L Ch R = 1 ,3654    ,82,82,82
BEGIN DESCRIPTION:
UNT 128 IN BOCR 8.0
END DESCRIPTION:
XS GIS Cut Line= 3
      3728549.64     10638010.17      3728399.61     10638110.19
      3728299.62     10638410.15
#Sta/Elev= 30
  4818.2  320.28  4825.7  319.81  4840.8  317.78  4846.8   317.9  4882.8  314.03
  4926.4  310.24  4970.2  307.42    4985  307.56    4991  306.46  4995.5  299.29
  5001.1  299.29    5006  298.26  5008.8  297.76    5012  298.26  5019.6  306.59
  5072.3  306.88  5103.9   303.3  5114.5  306.67    5125  308.13  5146.1  308.53
  5156.6  308.23  5167.2  309.34  5188.2  308.54  5219.9  309.72  5230.4  309.15
  5251.5   309.2  5272.6   310.6  5283.1   310.7  5293.7  311.96  5314.7  313.43
#Mann= 4 ,-1 , 0
  4818.2     .05       0  4970.2     .12       0    5006     .07       0
    5012     .12       0
Bank Sta=4991,5019.6
XS Rating Curve= 0 ,0
Exp/Cntr=0.3,0.1

Type RM Length L Ch R = 1 ,3572    ,91,91,91
BEGIN DESCRIPTION:
Mapping XS c43511d1
END DESCRIPTION:
XS GIS Cut Line= 3
      3728553.99     10637995.91      3728383.82     10638018.48
      3728124.03     10638271.35
#Sta/Elev= 30
    4801   321.3  4805.7   321.3  4855.9  317.37  4906.3  311.89  4944.6  308.56
  4966.8  307.63  4977.5  307.92  4983.9   307.2  4991.1  302.39  5002.2  297.95
    5005  297.45  5008.2  297.95  5012.2  302.28  5019.4  307.04  5022.5  306.93
  5075.9  307.53  5082.9  306.81  5090.1  307.66  5097.1  307.25  5111.2  307.73
  5138.9  307.21  5181.9  307.78  5188.9  308.71  5196.1  308.84  5203.1  308.17
  5231.4   309.4  5252.7  308.96  5259.6  309.85  5287.9  310.88  5335.2  310.57
#Mann= 5 ,-1 , 0
    4801     .05       0  5002.2     .03       0  5008.2     .05       0
  5022.5     .12       0  5138.9     .16       0
Bank Sta=4983.9,5019.4
XS Rating Curve= 0 ,0
Exp/Cntr=0.3,0.1

Type RM Length L Ch R = 1 ,3481    ,225,225,225
BEGIN DESCRIPTION:
Mapping XS 3e6a8da4
END DESCRIPTION:
XS GIS Cut Line= 3
       3728732.3     10637952.43      3728339.55     10637950.26
      3728005.38     10638147.72
#Sta/Elev= 30
  4566.3  327.31    4649  326.74    4729  323.33    4739   321.9    4759  320.78
    4779  318.49    4789  318.58    4809  317.18    4859  312.03    4889  309.76
  4956.5  306.48  4982.2  306.25  4987.8  302.38  5000.8   297.9  5003.6   297.4
  5006.8   297.9  5009.7  299.94  5017.1   300.1  5025.3   304.6  5031.1  306.42
  5068.2  306.87  5075.1   306.3  5089.6  306.71  5156.4   305.6  5169.6  306.25
  5249.6  306.63  5295.8  310.03  5317.9  310.48  5339.3  312.39  5347.2  312.27
#Mann= 4 ,-1 , 0
  4566.3     .05       0  4987.8     .16       0  5000.8     .07       0
  5006.8     .16       0
Bank Sta=4982.2,5031.1
XS Rating Curve= 0 ,0
Exp/Cntr=0.3,0.1

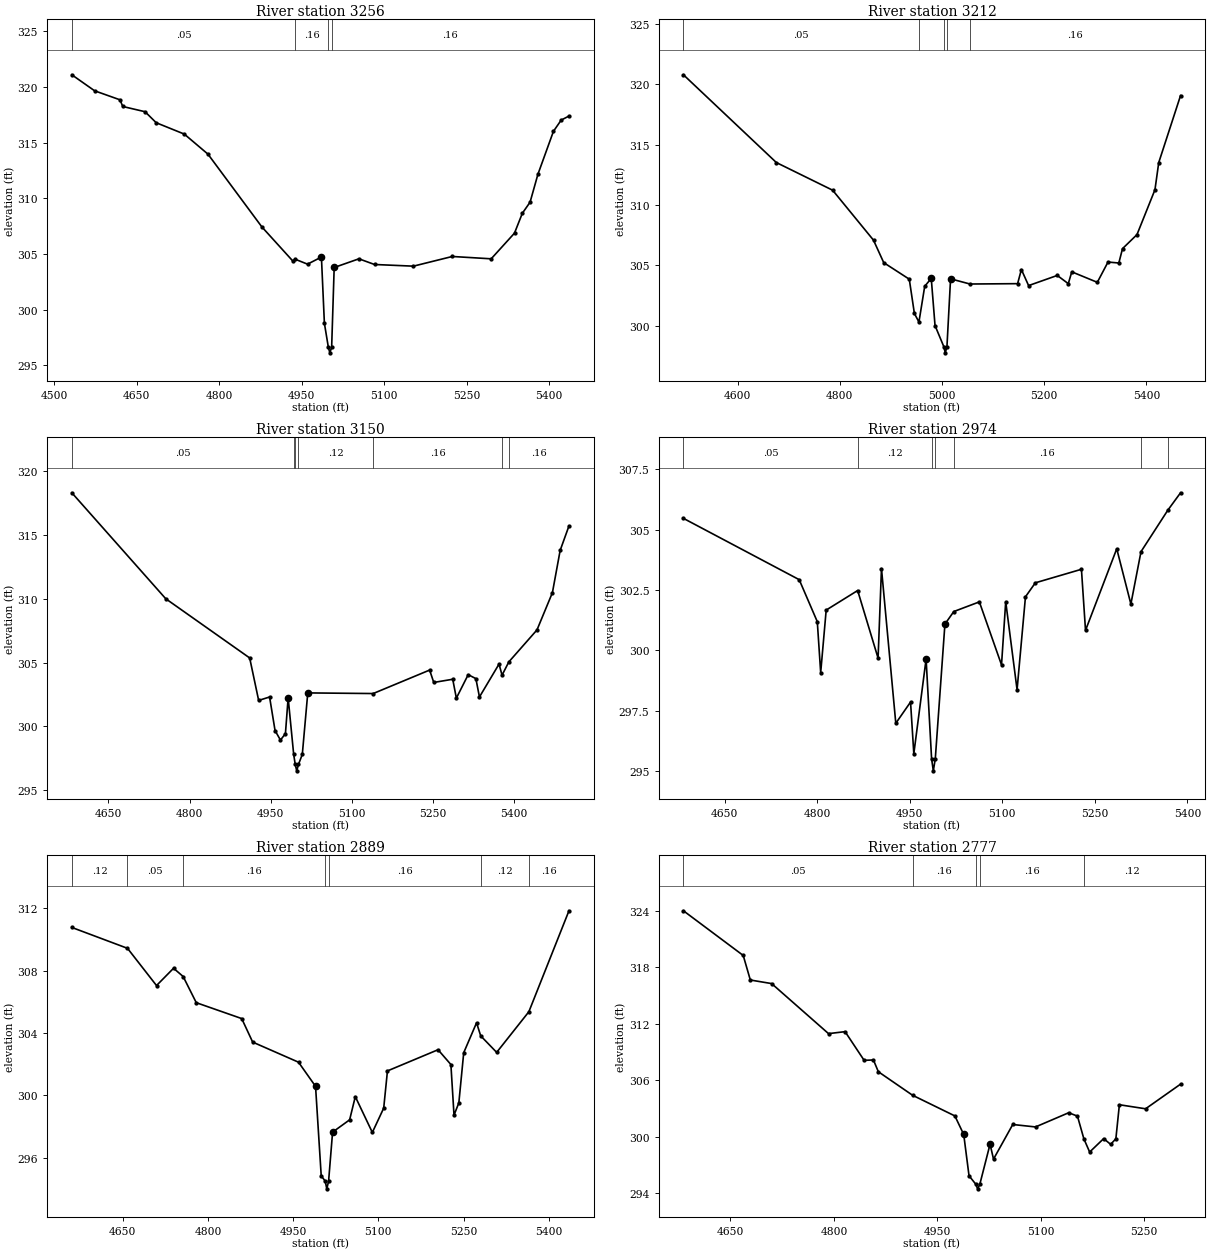
Type RM Length L Ch R = 1 ,3256    ,44,44,44
BEGIN DESCRIPTION:
UNT 128 IN BOCR 7.0
END DESCRIPTION:
XS GIS Cut Line= 3
       3728720.2     10637852.01      3728249.61     10637760.19
      3727949.63     10638060.16
#Sta/Elev= 30
  4532.1   321.1  4573.5  319.66  4619.6  318.85  4624.7  318.25  4665.2  317.78
  4685.5  316.79  4736.5  315.77  4779.5  313.97  4877.5  307.43  4934.2  304.34
  4937.7  304.53  4960.6  304.08  4985.8  304.72  4991.2  298.77  4998.4  296.61
  5001.1  296.11  5004.4  296.61    5009  303.78    5054  304.56  5082.3  304.05
    5153   303.9  5223.7  304.77  5294.4  304.56  5336.8  306.87    5351  308.65
  5365.1  309.65  5379.3  312.15  5407.6  316.02  5421.7  317.03  5435.8  317.39
#Mann= 4 ,-1 , 0
  4532.1     .05       0  4937.7     .16       0  4998.4     .07       0
  5004.4     .16       0
Bank Sta=4985.8,5009
XS Rating Curve= 0 ,0
Exp/Cntr=0.3,0.1

Type RM Length L Ch R = 1 ,3212    ,62,62,62
BEGIN DESCRIPTION:
Mapping XS fe690b41
END DESCRIPTION:
XS GIS Cut Line= 4
      3728771.41     10637696.36      3728313.51     10637711.55
       3728226.7     10637724.57      3727938.09     10638039.22
#Sta/Elev= 30
  4493.9  320.79  4675.8  313.52  4785.9  311.23  4865.9  307.09  4885.9  305.23
  4935.9  303.86  4945.9  301.02  4954.8  300.31  4966.1  303.27  4978.9  303.93
  4986.3  300.02  5003.6  298.26  5006.3  297.76  5009.6  298.26  5016.7  303.89
  5054.7  303.46  5147.9  303.49  5155.3  304.66  5169.4  303.33  5225.5  304.17
  5247.1  303.49  5253.9  304.47  5303.9   303.6  5324.8  305.28    5346   305.2
  5353.2  306.39  5381.5  307.55  5416.7  311.27  5424.1  313.52  5466.8  319.07
#Mann= 5 ,-1 , 0
  4493.9     .05       0  4954.8     .12       0  5003.6     .07       0
  5009.6     .12       0  5054.7     .16       0
Bank Sta=4978.9,5016.7
XS Rating Curve= 0 ,0
Exp/Cntr=0.3,0.1

Type RM Length L Ch R = 1 ,3150    ,176,176,176
BEGIN DESCRIPTION:
Mapping XS 589b01a3
END DESCRIPTION:
XS GIS Cut Line= 3
      3728691.57      10637599.4       3728230.6     10637664.51
      3727934.14     10638007.77
#Sta/Elev= 30
  4582.3  318.32    4756  310.01  4911.1  305.37  4927.7  302.04  4947.9  302.31
    4958  299.68    4968  298.93  4977.2  299.44  4982.2  302.25  4992.4  297.83
  4995.3  297.02  4998.1  296.52  5001.3  297.02  5008.4  297.81  5018.5  302.63
  5139.4  302.58  5243.8  304.42  5251.4  303.45  5286.5   303.7  5293.2  302.22
  5315.1  304.06  5329.3  303.75  5335.9  302.31  5372.1  304.89  5377.7  304.02
  5390.2  305.06  5442.3  307.57  5470.8  310.49  5485.1   313.8  5501.4  315.72
#Mann= 7 ,-1 , 0
  4582.3     .05       0  4992.4     .12       0  4995.3     .07       0
  5001.3     .12       0  5139.4     .16       0  5377.7     .12       0
  5390.2     .16       0
Bank Sta=4982.2,5018.5
XS Rating Curve= 0 ,0
Exp/Cntr=0.3,0.1

Type RM Length L Ch R = 1 ,2974    ,85,85,85
BEGIN DESCRIPTION:
Mapping XS b2164af3
END DESCRIPTION:
XS GIS Cut Line= 4
      3728303.51     10637208.78      3728157.68     10637536.91
      3728087.37     10637729.61      3727970.19     10637940.54
#Sta/Elev= 30
  4583.4  305.47    4771  302.93  4800.3  301.19  4805.8  299.08  4814.7  301.67
  4865.7  302.48  4898.8  299.68  4904.3  303.39  4927.5  296.98  4951.4  297.86
  4956.7  295.72  4976.6  299.64  4985.5  295.51  4988.3  295.01  4991.5  295.51
  5007.1  301.09  5021.5  301.61  5062.9  302.01  5098.8   299.4  5105.6  302.02
    5124  298.37  5137.6  302.22  5153.6   302.8  5228.3  303.36  5234.9  300.83
  5285.5  304.21  5308.4  301.92  5324.8  304.09  5368.3  305.81  5388.9  306.53
#Mann= 7 ,-1 , 0
  4583.4     .05       0  4865.7     .12       0  4985.5     .07       0
  4991.5     .12       0  5021.5     .16       0  5324.8     .12       0
  5368.3     .16       0
Bank Sta=4976.6,5007.1
XS Rating Curve= 0 ,0
Exp/Cntr=0.3,0.1

Type RM Length L Ch R = 1 ,2889    ,112,112,112
BEGIN DESCRIPTION:
Mapping XS 201a458d
END DESCRIPTION:
XS GIS Cut Line= 3
      3728056.12     10637141.06      3728053.51     10637698.36
      3727915.49     10637984.83
#Sta/Elev= 30
  4560.3  310.78  4658.3  309.44  4709.4  307.05  4739.4  308.16  4756.3  307.63
  4779.4  305.95  4859.4  304.93  4878.7  303.42  4959.4  302.13  4989.4  300.58
  4999.4  294.83  5006.4   294.5  5009.2     294  5012.4   294.5  5019.4  297.64
  5049.4  298.43  5059.4  299.92  5089.4  297.62  5109.4  299.18    5116  301.57
  5205.1  302.93  5227.7  301.98  5233.2  298.73  5241.7  299.52  5250.3  302.74
  5272.9  304.66  5280.2  303.82  5308.3  302.76    5365  305.37  5435.6  311.85
#Mann= 7 ,-1 , 0
  4560.3     .12       0  4658.3     .05       0  4756.3     .16       0
  5006.4     .07       0  5012.4     .16       0  5280.2     .12       0
    5365     .16       0
Bank Sta=4989.4,5019.4
XS Rating Curve= 0 ,0
Exp/Cntr=0.3,0.1

Type RM Length L Ch R = 1 ,2777    ,483,483,483
BEGIN DESCRIPTION:
UNT 128 IN BOCR 6.0
END DESCRIPTION:
XS GIS Cut Line= 3
      3727847.78     10637206.15      3727949.61     10637610.19
      3727899.61     10637910.18
#Sta/Elev= 30
  4581.8     324  4668.5  319.25  4678.8  316.64  4709.7  316.26  4792.2  310.94
  4816.2  311.15  4843.8   308.1  4857.3  308.14  4864.4  306.89    4914  304.39
  4975.4  302.19  4988.2  300.22  4995.9  295.83  5005.6  294.94  5008.4  294.44
  5011.6  294.94  5026.4  299.19  5031.4   297.6  5059.3  301.28  5092.3  301.02
  5140.4  302.53  5153.1  302.17  5162.4  299.76  5170.8  298.35  5191.1  299.78
  5201.2  299.17  5208.8  299.76  5213.9  303.38  5251.9  302.95  5302.6  305.57
#Mann= 5 ,-1 , 0
  4581.8     .05       0    4914     .16       0  5005.6     .07       0
  5011.6     .16       0  5162.4     .12       0
Bank Sta=4988.2,5026.4
XS Rating Curve= 0 ,0
Exp/Cntr=0.3,0.1

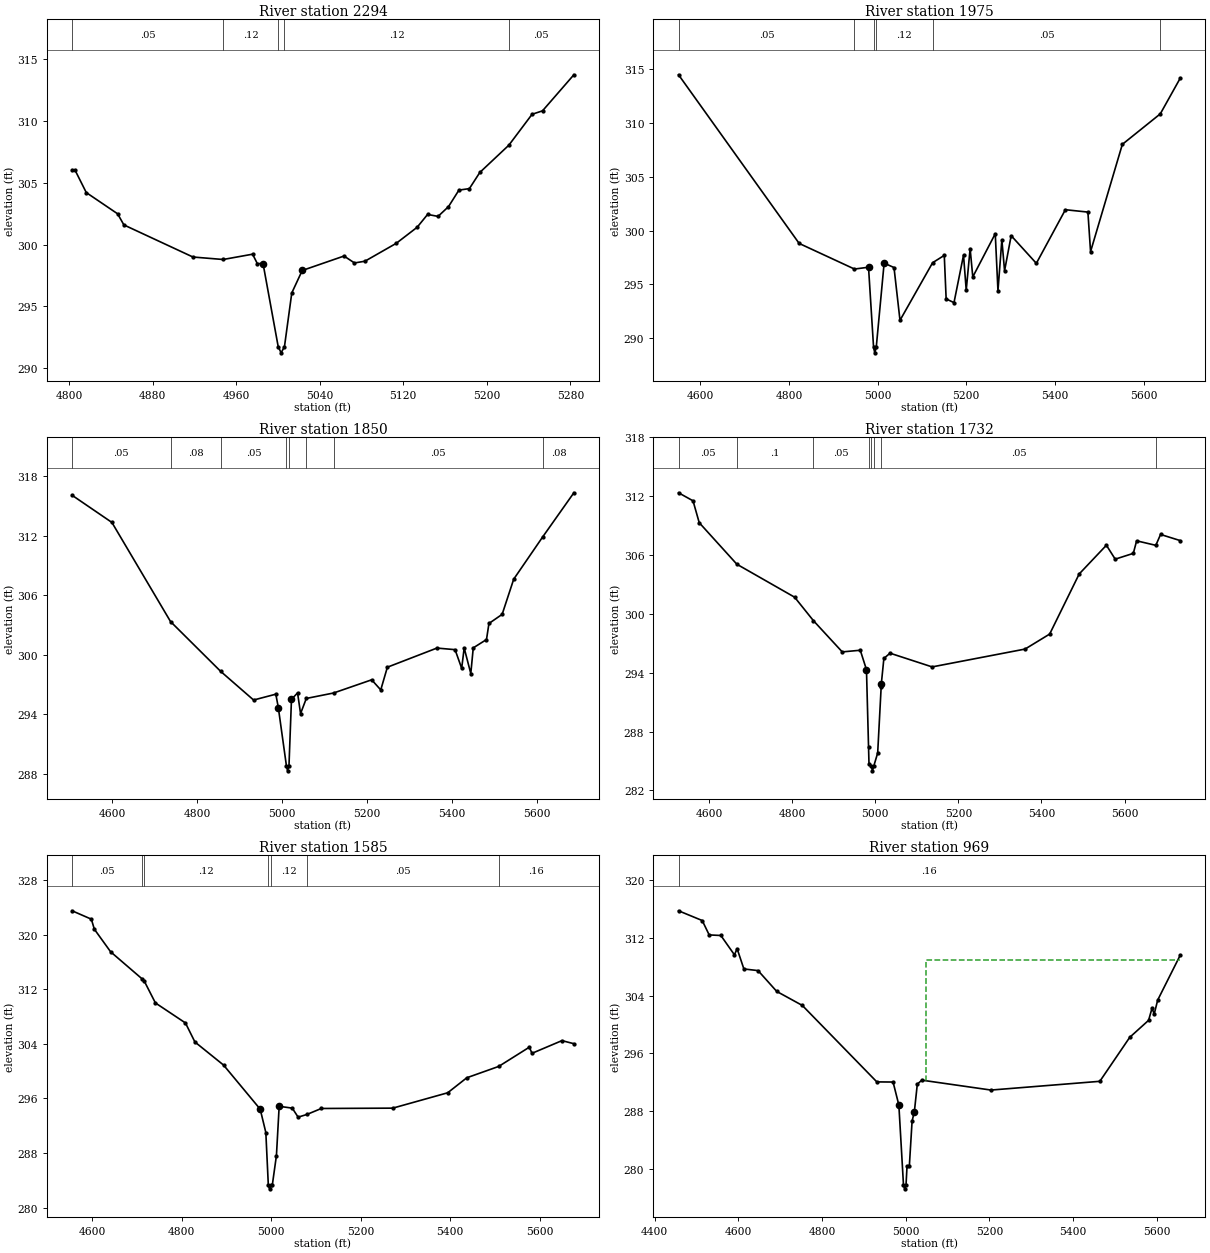
Type RM Length L Ch R = 1 ,2294    ,319,319,319
BEGIN DESCRIPTION:
UNT 128 IN BOCR 5.0
END DESCRIPTION:
XS GIS Cut Line= 3
      3727599.63     10637560.15      3727499.61     10637710.19
      3727499.61     10638010.17
#Sta/Elev= 30
    4803     306    4806     306  4816.6  304.21  4846.6  302.49  4852.6  301.59
  4918.7  298.99  4947.6  298.79  4975.8  299.22  4980.3  298.46  4985.8  298.46
  5000.3  291.73  5003.1  291.23  5006.3  291.73  5013.3  296.08  5023.3   297.9
  5063.3  299.07  5073.3  298.51  5083.3  298.65  5113.3   300.1  5133.3   301.4
  5143.3  302.44  5153.3  302.28  5163.3  303.07  5173.3  304.41  5183.3  304.53
  5193.3  305.84  5221.1  308.05  5243.3  310.55  5253.3  310.83  5283.3  313.75
#Mann= 5 ,-1 , 0
    4803     .05       0  4947.6     .12       0  5000.3     .07       0
  5006.3     .12       0  5221.1     .05       0
Bank Sta=4985.8,5023.3
XS Rating Curve= 0 ,0
Exp/Cntr=0.3,0.1

Type RM Length L Ch R = 1 ,1975    ,125,125,125
BEGIN DESCRIPTION:
Mapping XS eeb66930
END DESCRIPTION:
XS GIS Cut Line= 3
      3727566.95     10637354.51      3727098.16     10637736.48
       3726798.7     10638170.49
#Sta/Elev= 30
    4551  314.46  4823.1   298.8  4947.9  296.42  4979.6  296.59    4991  289.14
  4993.7  288.64    4997  289.14  5014.8  296.97  5037.1  296.56  5050.6  291.66
  5124.2  297.01  5150.5  297.69  5154.7  293.65  5172.4   293.3  5193.9  297.71
    5200  294.46  5208.8  298.32  5214.8  295.69  5265.5   299.7  5271.6  294.41
  5280.4  299.13  5286.5  296.26  5301.4  299.52  5358.2  296.95  5423.7  301.93
  5474.5  301.71  5480.5  298.04  5552.2     308  5637.8  310.83    5683  314.16
#Mann= 6 ,-1 , 0
    4551     .05       0  4947.9     .12       0    4991     .07       0
    4997     .12       0  5124.2     .05       0  5637.8     .08       0
Bank Sta=4979.6,5014.8
XS Rating Curve= 0 ,0
Exp/Cntr=0.3,0.1

Type RM Length L Ch R = 1 ,1850    ,118,118,118
BEGIN DESCRIPTION:
Mapping XS 31f164b5
END DESCRIPTION:
XS GIS Cut Line= 3
      3727545.18     10637306.81      3727076.46     10637588.91
      3726751.14     10638135.46
#Sta/Elev= 30
  4504.9  316.07  4598.8  313.33  4737.1  303.33  4855.3  298.31  4932.9  295.42
  4985.3  296.01  4991.2  294.66  5010.3  288.78    5013  288.28  5016.3  288.78
  5022.2  295.49  5036.6  296.14  5043.6  294.05  5057.2  295.58  5121.5  296.13
  5211.3  297.46  5232.7  296.44  5248.3  298.73  5365.1  300.66  5407.9   300.5
  5423.5  298.62  5429.4  300.67    5445  298.09  5450.8  300.68    5482  301.52
  5487.8  303.14  5518.9  304.06  5546.2  307.61    5615   311.9    5688  316.32
#Mann= 8 ,-1 , 0
  4504.9     .05       0  4737.1     .08       0  4855.3     .05       0
  5010.3     .04       0  5016.3     .05       0  5057.2     .12       0
  5121.5     .05       0    5615     .08       0
Bank Sta=4991.2,5022.2
XS Rating Curve= 0 ,0
Exp/Cntr=0.3,0.1

Type RM Length L Ch R = 1 ,1732    ,147,147,147
BEGIN DESCRIPTION:
Mapping XS a3fd9efb
END DESCRIPTION:
XS GIS Cut Line= 3
      3727423.72     10637215.62      3726915.87     10637567.21
       3726599.4     10638065.76
#Sta/Elev= 30
  4526.2  312.35  4561.1  311.53    4576   309.3  4666.7  305.06  4805.7   301.7
  4850.9  299.31  4920.4  296.12  4963.8  296.29  4978.7  294.31  4983.7  286.42
  4984.8  284.69  4990.4  284.49  4993.1  283.99  4996.4  284.49  5005.7  285.81
  5014.1  292.56  5014.5  292.88  5020.6  295.45  5035.4  295.99  5136.8  294.59
  5360.6  296.41  5419.8  297.94  5490.9  304.07  5556.4     307  5577.6  305.58
  5621.2  306.17  5629.2  307.45  5675.4  306.99  5686.8   308.1  5734.4  307.47
#Mann= 8 ,-1 , 0
  4526.2     .05       0  4666.7      .1       0  4850.9     .05       0
  4983.7     .12       0  4990.4     .07       0  4996.4     .12       0
  5014.1     .05       0  5675.4     .16       0
Bank Sta=4978.7,5014.5
XS Rating Curve= 0 ,0
Exp/Cntr=0.3,0.1

Type RM Length L Ch R = 1 ,1585    ,616,616,616
BEGIN DESCRIPTION:
Mapping XS a54f1ad3
END DESCRIPTION:
XS GIS Cut Line= 2
      3727141.56     10637063.75      3726543.61     10638012.67
#Sta/Elev= 30
  4554.8  323.48  4597.9  322.25  4604.6  320.78    4641  317.47  4710.9  313.53
  4716.4  313.15  4741.1  309.98  4808.2  307.05  4829.4  304.26  4893.4  300.88
  4975.3  294.42  4987.9     291  4993.5  283.25  4996.3  282.75  4999.5  283.25
  5002.5  283.36  5011.6  287.63  5017.7  294.84    5047  294.57  5060.1  293.25
  5079.9  293.65  5111.9  294.52  5271.6  294.57  5394.4  296.82  5437.1  299.02
  5508.4  300.68  5576.9   303.5  5582.8   302.6  5649.8  304.46  5676.4  304.01
#Mann= 7 ,-1 , 0
  4554.8     .05       0  4710.9      .1       0  4716.4     .12       0
  4993.5     .07       0  4999.5     .12       0  5079.9     .05       0
  5508.4     .16       0
Bank Sta=4975.3,5017.7
XS Rating Curve= 0 ,0
Exp/Cntr=0.3,0.1

Type RM Length L Ch R = 1 ,969     ,473,473,473
BEGIN DESCRIPTION:
UNT 128 IN BOCR 2.0
END DESCRIPTION:
XS GIS Cut Line= 3
       3726938.7     10636961.42      3726449.61     10637210.19
      3726199.62     10637810.17
#Sta/Elev= 30
  4457.3  315.74  4513.9  314.39  4530.5   312.4  4558.4  312.32  4590.9  309.64
  4597.2   310.5  4613.4  307.69  4647.3  307.46  4691.9  304.58    4753  302.64
    4931  292.06  4969.8  292.04  4983.6  288.86  4994.7  277.76  4997.5  277.26
  5000.7  277.76  5003.2  280.44  5008.7  280.44  5015.2  286.62  5020.7  287.96
  5027.7  291.75  5038.5   292.3  5203.7  290.93  5463.7  292.14  5535.2  298.23
  5580.2  300.58  5588.3  302.24  5593.7  301.47  5601.9  303.38    5656  309.62
#Mann= 1 ,-1 , 0
  4457.3     .16       0
#XS Ineff= 2 , 0
                         5047.31          308.93
Permanent Ineff=
       F       F
Bank Sta=4983.6,5020.7
XS Rating Curve= 0 ,0
Exp/Cntr=0.3,0.1

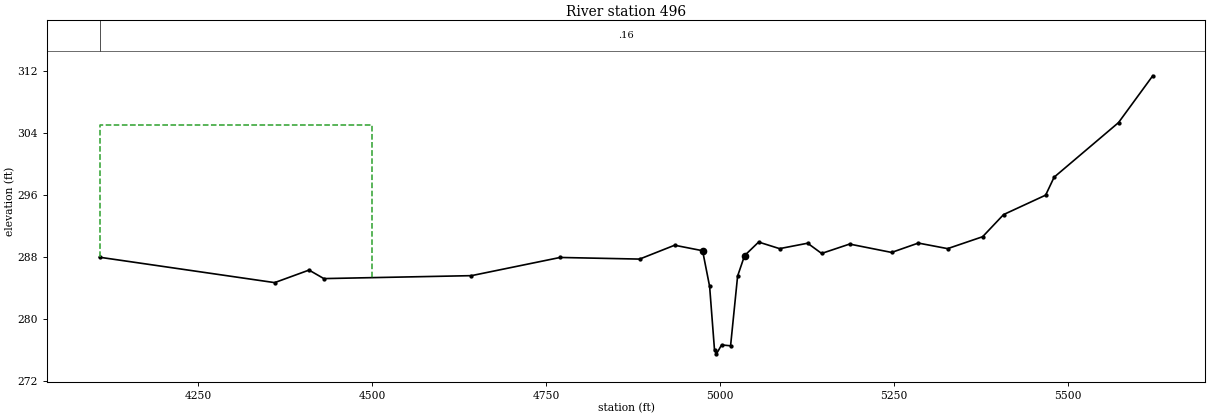
Type RM Length L Ch R = 1 ,496     ,0,0,0
BEGIN DESCRIPTION:
UNT 128 IN BOCR 1.0
END DESCRIPTION:
XS GIS Cut Line= 3
      3726511.59     10636526.55      3726013.09     10637007.31
       3726099.9     10637823.25
#Sta/Elev= 30
  4108.2  287.94  4359.8  284.66  4409.2  286.28  4430.5  285.18  4642.5  285.56
  4769.9  287.91  4884.1   287.7  4934.4  289.49  4974.6  288.78  4984.7  284.16
  4991.7  275.96  4994.5  275.46  5001.9  276.61  5014.8   276.5  5024.9  285.51
  5034.9  288.15  5055.1   289.9  5085.2  289.05  5125.5  289.75  5145.6  288.43
  5185.8  289.64  5246.1  288.56  5284.5  289.77  5326.6  289.05  5376.9  290.59
    5407  293.45  5467.4  295.96  5479.6  298.28  5572.1  305.33  5621.3  311.38
#Mann= 1 ,-1 , 0
  4108.2     .16       0
#XS Ineff= 2 , 0
       0    4500     305               0
Permanent Ineff=
       F       F
Bank Sta=4974.6,5034.9
XS Rating Curve= 0 ,0
Exp/Cntr=0.3,0.1

Chan Stop Cuts=-1
Use User Specified Reach Order=0
Composite Channel Slope=5