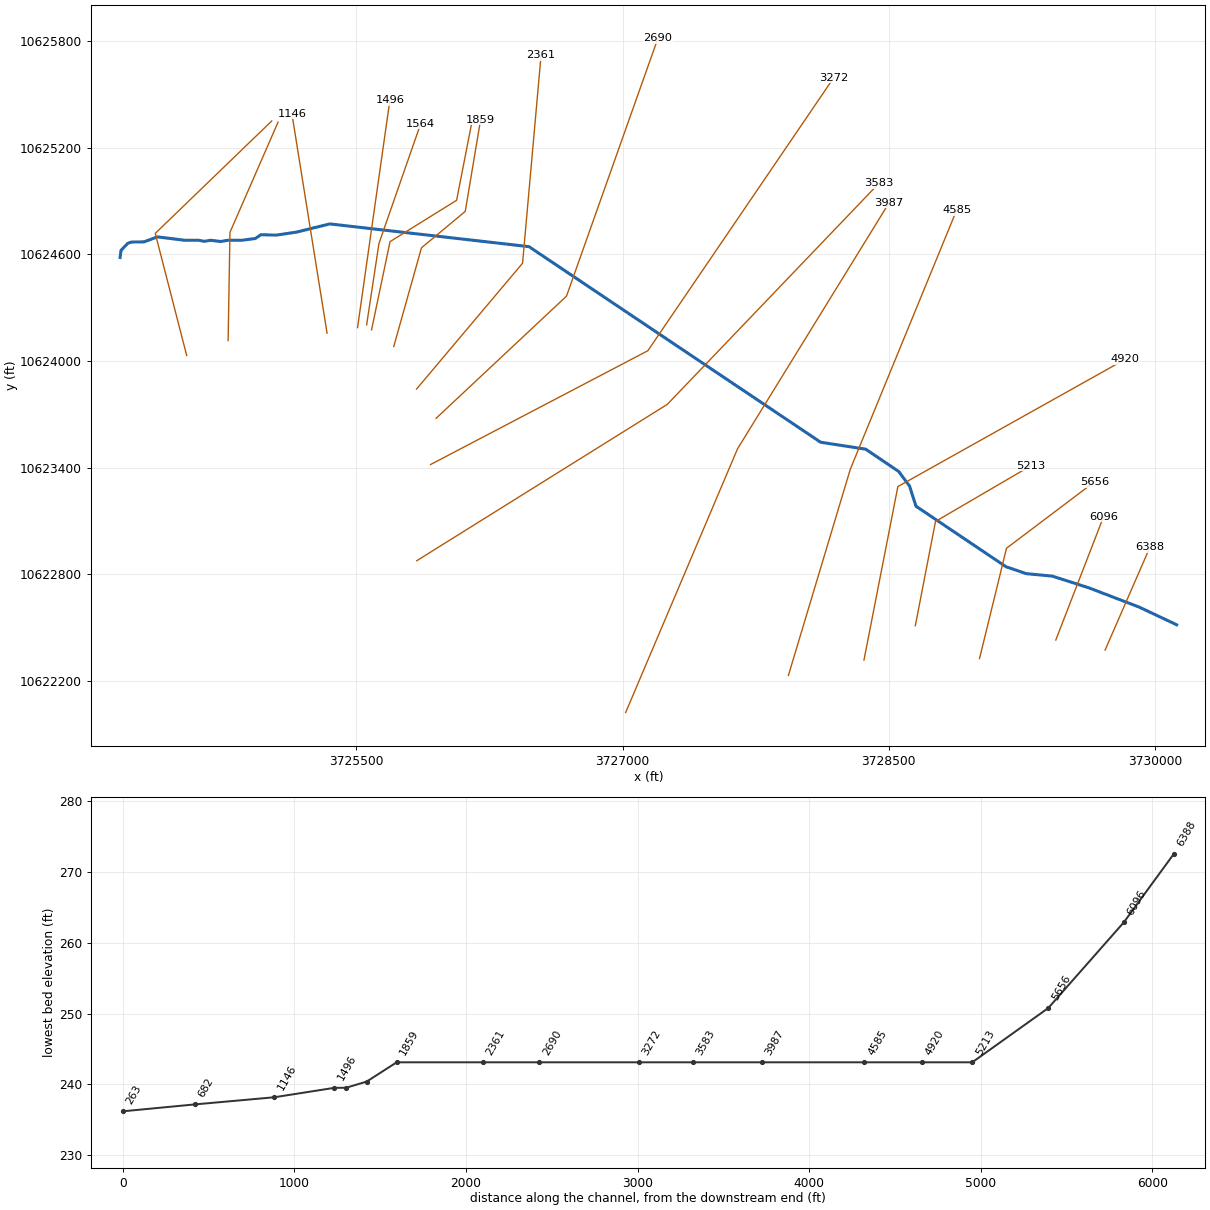
--- UNT 129 IN BOCR.prj (project) ---

Proj Title=UNT 129 IN BOCR Base Level Engineering
Current Plan=p01
Default Exp/Contr=0.3,0.1
English Units
Geom File=g01
Flow File=f01
Plan File=p01
Y Axis Title=Elevation
X Axis Title(PF)=Main Channel Distance
X Axis Title(XS)=Station
BEGIN DESCRIPTION:
UNT 129 IN BOCR
END DESCRIPTION:
DSS Export Rating Curves= 0
DSS Export Rating Curve Sorted= 0
DSS Export Volume Flow Curves= 0
DXF OffsetX= 0
DXF OffsetY= 0
DXF ScaleX= 1
DXF ScaleY= 10

--- UNT 129 IN BOCR.p01 (plan) ---

Plan Title=Multiple Run
Short Identifier=Multiple
Geom File=g01
Flow File=f01
Subcritical Flow
K Sum by GR= 0
Std Step Tol= 0.01
Critical Tol= 0.01
Num of Std Step Trials= 20
Max Error Tol= 0.3
Flow Tol Ratio= 0.001
Split Flow NTrial= 30
Split Flow Tol= 0.02
Split Flow Ratio= 0.02
Log Output Level= 0
Friction Slope Method= 1
Unsteady Friction Slope Method= 2
Unsteady Bridges Friction Slope Method= 1
Parabolic Critical Depth
Global Vel Dist=  1 , 1 , 1
Global Log Level= 0
CheckData=True
Encroach Param= -1, 0, 0, 0
BEGIN DESCRIPTION:
Multiple Run
END DESCRIPTION:

--- UNT 129 IN BOCR.f01 (steady flow) ---

Flow Title=Multiple
Program Version=4.10
Number of Profiles= 7
Profile Names=10-year,25-year,50-year,1pct_min,100-year,1pct_plu,500-year
River Rch & RM=UNT 129 IN BOCR,Reach-1         ,6388
     429     565     674     591     799    1081    1128
Boundary for River Rch & Prof#=UNT 129 IN BOCR,Reach-1         , 1
Up Type= 0
Dn Type= 3
Dn Slope=0.005
Boundary for River Rch & Prof#=UNT 129 IN BOCR,Reach-1         , 2
Up Type= 0
Dn Type= 3
Dn Slope=0.005
Boundary for River Rch & Prof#=UNT 129 IN BOCR,Reach-1         , 3
Up Type= 0
Dn Type= 3
Dn Slope=0.005
Boundary for River Rch & Prof#=UNT 129 IN BOCR,Reach-1         , 4
Up Type= 0
Dn Type= 3
Dn Slope=0.005
Boundary for River Rch & Prof#=UNT 129 IN BOCR,Reach-1         , 5
Up Type= 0
Dn Type= 3
Dn Slope=0.005
Boundary for River Rch & Prof#=UNT 129 IN BOCR,Reach-1         , 6
Up Type= 0
Dn Type= 3
Dn Slope=0.005
Boundary for River Rch & Prof#=UNT 129 IN BOCR,Reach-1         , 7
Up Type= 0
Dn Type= 3
Dn Slope=0.005
DSS Import GetInterval= 0
DSS Import GetPeak= 0
DSS Import FillOption= 0

--- UNT 129 IN BOCR.g01 (geometry) ---

Geom Title=Existing Conditions

River Reach=UNT 129 IN BOCR,Reach-1
Reach XY= 30
      3730121.78     10622515.46      3729911.10     10622614.88
      3729628.05     10622723.20      3729421.40     10622789.29
      3729274.66     10622803.30      3729160.75     10622842.00
      3728653.25     10623183.00      3728617.25     10623296.00
      3728556.50     10623378.00      3728370.00     10623504.00
      3728116.25     10623543.00      3726473.25     10624644.00
      3725351.00     10624772.00      3725164.50     10624726.00
      3725049.50     10624709.00      3724963.00     10624711.00
      3724931.50     10624690.00      3724855.50     10624680.00
      3724779.00     10624680.00      3724735.00     10624673.00
      3724679.75     10624680.00      3724644.75     10624674.00
      3724610.25     10624680.00      3724533.75     10624680.00
      3724380.00     10624699.00      3724305.00     10624671.00
      3724234.00     10624670.00      3724213.25     10624663.00
      3724174.75     10624623.00      3724169.50     10624583.00

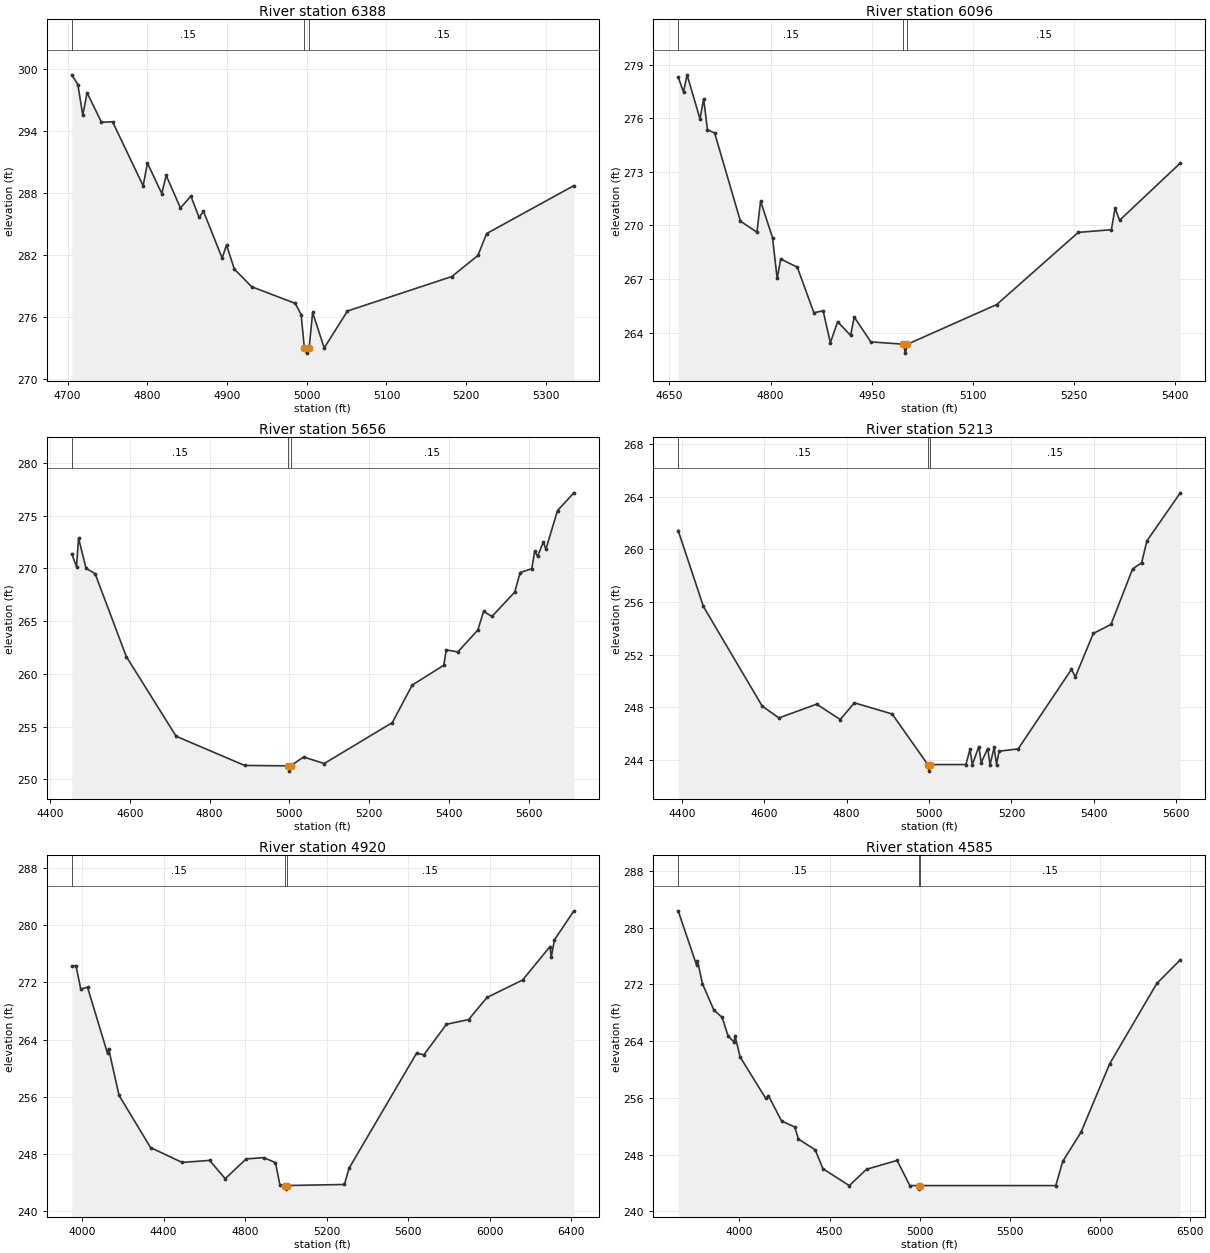
Type RM Length L Ch R = 1,6388,292,292,292
BEGIN DESCRIPTION:
UNT 129 IN BOCR 14.0
END DESCRIPTION:
XS GIS Cut Line= 2
      3729718.80     10622373.26      3729970.55     10622950.55
#Sta/Elev= 30
  4705.3  299.48  4712.9  298.54  4719.1  295.57  4724.5  297.75  4742.5  294.89
  4756.5  294.93  4794.8  288.73  4800.2  290.93  4818.2  287.98  4823.7  289.74
  4841.6  286.58  4854.7  287.73  4865.0  285.66  4870.5  286.26  4893.9  281.73
  4899.4  282.99  4909.2  280.66  4931.0  278.95  4985.6  277.34  4993.0  276.25
  4997.0  273.02  4999.8  272.52  5003.0  273.02  5007.4  276.46  5021.9  273.02
  5051.1  276.60  5182.0  279.94  5214.7  281.98  5225.6  284.10  5335.1  288.75
#Mann=3,-1,0
  4705.3    0.15       0  4997.0    0.05       0  5003.0    0.15       0
Bank Sta=4997,5003
Exp/Cntr=0.3,0.1

Type RM Length L Ch R = 1,6096,440,440,440
BEGIN DESCRIPTION:
UNT 129 IN BOCR 13.0
END DESCRIPTION:
XS GIS Cut Line= 2
      3729441.04     10622429.72      3729710.11     10623124.11
#Sta/Elev= 30
  4662.9  278.30  4670.8  277.47  4676.1  278.43  4695.3  275.96  4700.7  277.09
  4706.3  275.36  4717.0  275.17  4755.2  270.24  4779.7  269.62  4785.1  271.36
  4802.8  269.32  4809.7  267.03  4815.0  268.12  4839.6  267.66  4864.2  265.11
  4877.9  265.22  4888.6  263.43  4899.4  264.61  4918.6  263.84  4924.0  264.87
  4948.6  263.48  4997.0  263.35  4999.8  262.85  5003.0  263.35  5135.3  265.57
  5256.3  269.61  5305.4  269.76  5310.8  270.96  5317.6  270.29  5407.6  273.49
#Mann=3,-1,0
  4662.9    0.15       0  4997.0    0.05       0  5003.0    0.15       0
Bank Sta=4997,5003
Exp/Cntr=0.3,0.1

Type RM Length L Ch R = 1,5656,443,443,443
BEGIN DESCRIPTION:
UNT 129 IN BOCR 12.0
END DESCRIPTION:
XS GIS Cut Line= 3
      3729011.33     10622325.51      3729163.25     10622946.19
      3729658.05     10623319.46
#Sta/Elev= 30
  4454.6  271.40  4466.5  270.17  4471.6  272.87  4490.3  270.02  4513.2  269.49
  4591.3  261.64  4716.2  254.08  4887.8  251.31  4997.0  251.27  4999.8  250.77
  5003.0  251.27  5035.9  252.11  5087.4  251.49  5258.1  255.37  5308.0  258.93
  5387.1  260.81  5393.4  262.27  5422.5  262.08  5472.5  264.15  5487.0  265.93
  5507.9  265.44  5565.0  267.75  5578.7  269.61  5607.8  269.97  5615.1  271.63
  5622.3  271.15  5636.9  272.50  5643.2  271.82  5672.3  275.49  5713.4  277.17
#Mann=3,-1,0
  4454.6    0.15       0  4997.0    0.05       0  5003.0    0.15       0
Bank Sta=4997,5003
Exp/Cntr=0.3,0.1

Type RM Length L Ch R = 1,5213,293,293,293
BEGIN DESCRIPTION:
UNT 129 IN BOCR 11.0
END DESCRIPTION:
XS GIS Cut Line= 3
      3728649.60     10622510.15      3728763.27     10623097.06
      3729299.63     10623410.20
#Sta/Elev= 30
  4391.1  261.44  4452.3  255.66  4594.9  248.08  4635.6  247.17  4727.3  248.22
  4784.4  247.05  4818.9  248.32  4910.6  247.47  4997.0  243.62  4999.8  243.12
  5003.0  243.62  5089.5  243.62  5099.4  244.77  5105.2  243.62  5120.9  244.99
  5126.7  243.77  5142.4  244.84  5148.2  243.62  5158.1  244.93  5163.9  243.62
  5170.0  244.64  5216.3  244.81  5345.8  250.87  5355.2  250.30  5398.7  253.60
  5441.7  254.29  5494.2  258.52  5516.1  258.98  5528.9  260.65  5610.0  264.31
#Mann=3,-1,0
  4391.1    0.15       0  4997.0    0.05       0  5003.0    0.15       0
Bank Sta=4997,5003
Exp/Cntr=0.3,0.1

Type RM Length L Ch R = 1,4920,335,335,335
BEGIN DESCRIPTION:
UNT 129 IN BOCR 10.0
END DESCRIPTION:
XS GIS Cut Line= 3
      3728360.29     10622316.81      3728551.27     10623293.41
      3729831.61     10624009.53
#Sta/Elev= 30
  3949.9  274.27  3970.5  274.33  3994.1  271.04  4027.1  271.31  4125.1  262.08
  4130.2  262.75  4181.7  256.21  4336.3  248.92  4490.9  246.85  4625.8  247.13
  4702.1  244.58  4805.1  247.34  4890.8  247.52  4948.7  246.82  4970.4  243.72
  4997.0  243.62  4999.8  243.12  5003.0  243.62  5286.8  243.77  5309.7  246.05
  5640.7  262.11  5676.4  261.87  5786.9  266.14  5895.4  266.79  5985.8  269.88
  6160.3  272.32  6295.0  276.99  6300.8  275.49  6316.7  277.93  6412.0  281.98
#Mann=3,-1,0
  3949.9    0.15       0  4997.0    0.05       0  5003.0    0.15       0
Bank Sta=4997,5003
Exp/Cntr=0.3,0.1

Type RM Length L Ch R = 1,4585,598,598,598
BEGIN DESCRIPTION:
Mapping XS 4ea07409
END DESCRIPTION:
XS GIS Cut Line= 3
      3727934.53     10622230.11      3728283.48     10623391.53
      3728882.45     10624849.91
#Sta/Elev= 30
  3659.4  282.39  3761.3  274.75  3766.5  275.37  3794.3  272.10  3857.9  268.38
  3903.9  267.35  3936.9  264.70  3970.0  263.88  3975.2  264.78  4003.0  261.79
  4145.6  255.93  4160.7  256.32  4233.8  252.73  4306.9  251.89  4327.7  250.18
  4420.4  248.67  4463.9  245.99  4609.7  243.62  4705.6  245.92  4875.6  247.17
  4946.3  243.62  4997.0  243.62  4999.8  243.12  5003.0  243.62  5757.1  243.62
  5795.7  247.05  5896.9  251.14  6057.0  260.84  6318.3  272.15  6448.7  275.48
#Mann=3,-1,0
  3659.4    0.15       0  4997.0    0.05       0  5003.0    0.15       0
Bank Sta=4997,5003
Exp/Cntr=0.3,0.1

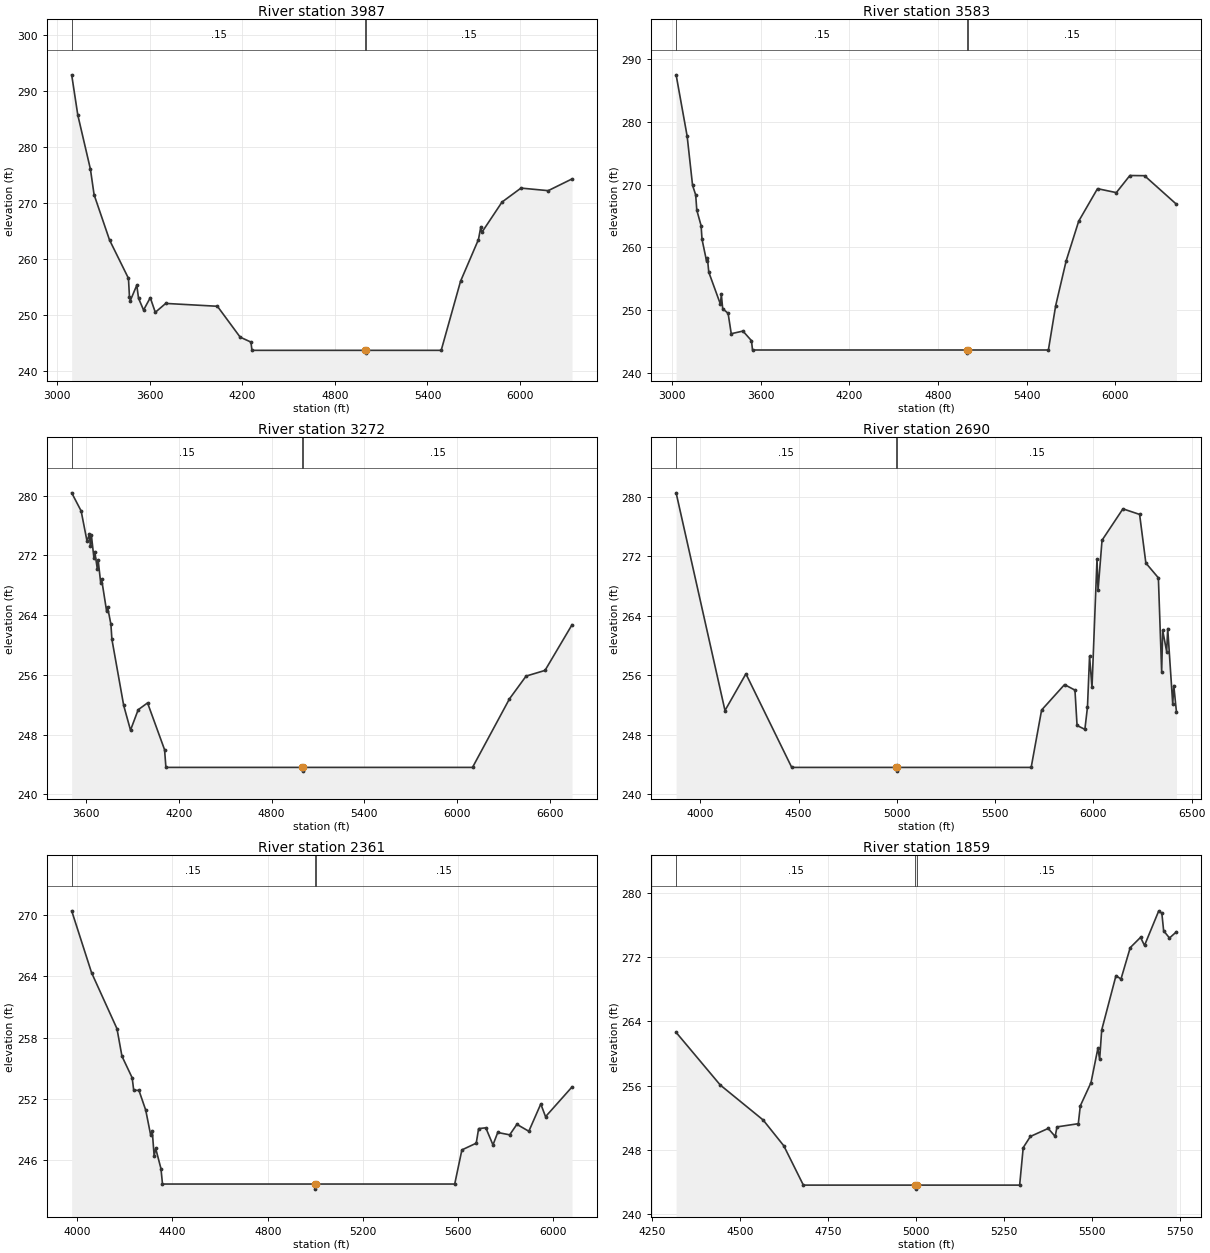
Type RM Length L Ch R = 1,3987,404,404,404
BEGIN DESCRIPTION:
Mapping XS c90045a0
END DESCRIPTION:
XS GIS Cut Line= 3
      3727017.85     10622021.74      3727648.06     10623506.12
      3728502.23     10624891.54
#Sta/Elev= 30
  3095.9  292.95  3135.5  285.75  3217.3  276.05  3241.0  271.49  3341.1  263.37
  3463.6  256.51  3470.2  253.12  3475.7  252.53  3517.5  255.28  3528.8  252.96
  3561.4  250.83  3604.8  253.05  3637.4  250.43  3704.9  252.02  4039.6  251.51
  4187.0  245.98  4256.7  245.10  4263.4  243.62  4997.0  243.62  4999.8  243.12
  5003.0  243.62  5488.9  243.62  5614.3  256.00  5730.2  263.46  5745.6  265.76
  5751.5  264.72  5882.8  270.17  6005.6  272.67  6181.8  272.21  6336.1  274.31
#Mann=3,-1,0
  3095.9    0.15       0  4997.0    0.05       0  5003.0    0.15       0
Bank Sta=4997,5003
Exp/Cntr=0.3,0.1

Type RM Length L Ch R = 1,3583,311,311,311
BEGIN DESCRIPTION:
Mapping XS 10bf2b5f
END DESCRIPTION:
XS GIS Cut Line= 3
      3725840.78     10622875.91      3727252.23     10623756.12
      3728444.74     10625000.71
#Sta/Elev= 30
  3028.0  287.54  3102.7  277.75  3139.3  269.91  3160.5  268.37  3168.0  265.94
  3197.1  263.47  3203.4  261.29  3233.7  257.86  3239.6  258.36  3249.0  256.05
  3328.1  250.92  3334.0  252.51  3343.4  250.21  3380.0  249.47  3401.2  246.22
  3480.3  246.64  3538.1  245.11  3545.2  243.62  4997.0  243.62  4999.8  243.12
  5003.0  243.62  5548.2  243.62  5597.6  250.71  5668.4  257.84  5753.3  264.18
  5880.6  269.37  6008.0  268.74  6099.8  271.47  6198.9  271.44  6415.1  266.88
#Mann=3,-1,0
  3028.0    0.15       0  4997.0    0.05       0  5003.0    0.15       0
Bank Sta=4997,5003
Exp/Cntr=0.3,0.1

Type RM Length L Ch R = 1,3272,582,582,582
BEGIN DESCRIPTION:
Mapping XS c6abb43e
END DESCRIPTION:
XS GIS Cut Line= 3
      3725918.86     10623417.56      3727142.85     10624058.20
      3728189.72     10625594.64
#Sta/Elev= 30
  3504.6  280.37  3565.9  277.94  3604.3  273.86  3618.3  274.83  3626.4  273.21
  3632.1  274.71  3648.5  271.68  3654.1  272.50  3670.6  270.18  3676.2  271.32
  3692.6  268.31  3698.3  268.83  3731.1  264.50  3736.8  265.10  3758.8  262.76
  3765.0  260.78  3841.5  251.91  3885.6  248.60  3935.4  251.34  3996.0  252.25
  4106.3  245.98  4114.9  243.62  4997.0  243.62  4999.8  243.12  5003.0  243.62
  6100.8  243.62  6340.0  252.79  6447.8  255.84  6570.4  256.60  6745.3  262.71
#Mann=3,-1,0
  3504.6    0.15       0  4997.0    0.05       0  5003.0    0.15       0
Bank Sta=4997,5003
Exp/Cntr=0.3,0.1

Type RM Length L Ch R = 1,2690,329,329,329
BEGIN DESCRIPTION:
UNT 129 IN BOCR 5.0
END DESCRIPTION:
XS GIS Cut Line= 3
      3725950.11     10623677.96      3726684.52     10624365.49
      3727199.54     10625816.91
#Sta/Elev= 30
  3876.6  280.50  4125.3  251.26  4231.8  256.19  4464.9  243.62  4997.0  243.62
  4999.8  243.12  5003.0  243.62  5683.4  243.62  5736.5  251.33  5853.2  254.74
  5906.2  254.00  5916.9  249.25  5956.7  248.73  5969.9  251.72  5980.5  258.55
  5992.9  254.36  6018.4  271.62  6023.7  267.41  6044.0  274.13  6150.3  278.35
  6235.2  277.60  6267.0  271.07  6330.7  269.08  6347.4  256.47  6352.7  262.01
  6372.9  259.17  6378.2  262.27  6403.8  252.12  6409.1  254.62  6422.7  251.06
#Mann=3,-1,0
  3876.6    0.15       0  4997.0    0.05       0  5003.0    0.15       0
Bank Sta=4997,5003
Exp/Cntr=0.3,0.1

Type RM Length L Ch R = 1,2361,502,502,502
BEGIN DESCRIPTION:
UNT 129 IN BOCR 4.0
END DESCRIPTION:
XS GIS Cut Line= 3
      3725839.75     10623842.42      3726436.99     10624550.77
      3726541.15     10625720.91
#Sta/Elev= 30
  3976.7  270.44  4060.3  264.36  4166.9  258.87  4187.8  256.17  4230.7  254.05
  4237.2  252.83  4259.2  252.81  4287.7  250.87  4308.7  248.39  4315.2  248.79
  4323.0  246.38  4329.5  247.11  4351.6  245.14  4358.1  243.62  4997.0  243.62
  4999.8  243.12  5003.0  243.62  5585.3  243.62  5615.5  246.97  5675.7  247.63
  5685.7  249.06  5715.9  249.14  5746.0  247.46  5766.0  248.68  5816.2  248.45
  5846.4  249.48  5896.6  248.80  5946.8  251.48  5966.8  250.23  6078.0  253.15
#Mann=3,-1,0
  3976.7    0.15       0  4997.0    0.05       0  5003.0    0.15       0
Bank Sta=4997,5003
Exp/Cntr=0.3,0.1

Type RM Length L Ch R = 1,1859,175,175,175
BEGIN DESCRIPTION:
Mapping XS 3e2bf8f8
END DESCRIPTION:
XS GIS Cut Line= 4
      3725711.29     10624082.02      3725867.54     10624637.57
      3726114.07     10624842.44      3726200.87     10625359.76
#Sta/Elev= 30
  4319.0  262.62  4444.5  256.07  4566.4  251.72  4625.1  248.51  4680.7  243.62
  4997.0  243.62  4999.8  243.12  5003.0  243.62  5295.5  243.62  5305.6  248.28
  5325.9  249.67  5376.6  250.67  5396.5  249.67  5401.6  250.86  5462.2  251.26
  5467.9  253.48  5498.3  256.37  5517.8  260.62  5522.9  259.28  5528.7  262.91
  5569.3  269.68  5583.5  269.25  5609.8  273.16  5639.1  274.44  5650.4  273.43
  5690.9  277.74  5699.7  277.43  5704.8  275.25  5721.4  274.36  5741.2  275.13
#Mann=3,-1,0
  4319.0    0.15       0  4997.0    0.05       0  5003.0    0.15       0
Bank Sta=4997,5003
Exp/Cntr=0.3,0.1

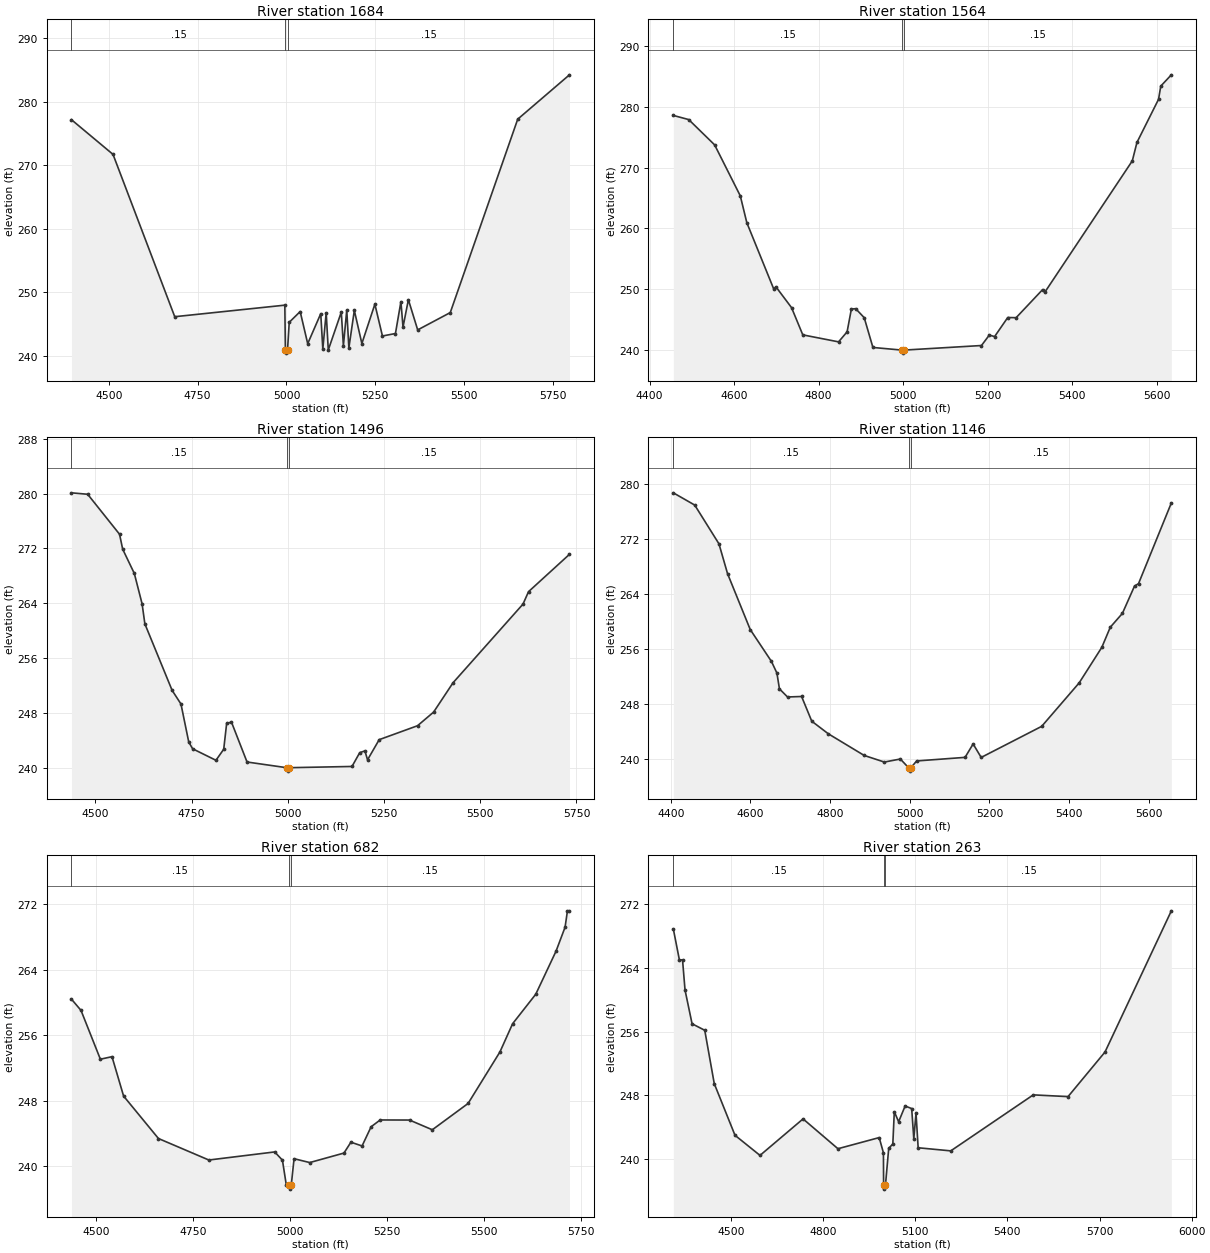
Type RM Length L Ch R = 1,1684,120,120,120
BEGIN DESCRIPTION:
Mapping XS f74a0837
END DESCRIPTION:
XS GIS Cut Line= 4
      3725586.28     10624175.73      3725690.46     10624672.30
      3726065.46     10624904.94      3726152.26     10625349.36
#Sta/Elev= 30
  4394.9  277.19  4511.9  271.72  4685.6  246.14  4995.4  247.96  4997.0  240.90
  4999.8  240.40  5003.0  240.90  5007.8  245.26  5038.6  246.95  5059.8  241.89
  5096.5  246.62  5102.3  241.05  5111.8  246.77  5117.7  240.90  5154.3  246.86
  5160.2  241.56  5169.7  247.19  5175.6  241.21  5191.0  247.13  5212.2  241.91
  5248.8  248.11  5270.1  243.10  5306.7  243.49  5322.1  248.51  5328.0  244.50
  5343.1  248.82  5369.3  244.06  5461.0  246.79  5650.8  277.27  5796.4  284.26
#Mann=3,-1,0
  4394.9    0.15       0  4997.0    0.05       0  5003.0    0.15       0
Bank Sta=4997,5003
Exp/Cntr=0.3,0.1

Type RM Length L Ch R = 1,1564,68,68,68
BEGIN DESCRIPTION:
Mapping XS 4062860d
END DESCRIPTION:
XS GIS Cut Line= 3
      3725558.51     10624203.50      3725627.96     10624661.88
      3725863.42     10625337.09
#Sta/Elev= 30
  4456.4  278.57  4492.8  277.89  4554.2  273.73  4614.9  265.36  4630.3  260.96
  4694.1  250.05  4699.1  250.43  4736.2  247.00  4762.8  242.53  4847.5  241.38
  4867.7  243.03  4877.8  246.77  4888.0  246.83  4908.2  245.35  4928.8  240.46
  4997.0  240.03  4999.8  239.53  5003.0  240.03  5185.7  240.78  5204.2  242.49
  5216.8  242.25  5247.9  245.38  5267.7  245.35  5330.5  249.97  5335.8  249.55
  5542.7  271.11  5553.7  274.14  5604.8  281.22  5610.1  283.39  5635.1  285.24
#Mann=3,-1,0
  4456.4    0.15       0  4997.0    0.05       0  5003.0    0.15       0
Bank Sta=4997,5003
Exp/Cntr=0.3,0.1

Type RM Length L Ch R = 1,1496,350,350,350
BEGIN DESCRIPTION:
Mapping XS d15c15ac
END DESCRIPTION:
XS GIS Cut Line= 2
      3725507.44     10624188.43      3725689.72     10625469.63
#Sta/Elev= 30
  4437.7  280.11  4479.9  279.90  4562.7  274.07  4570.8  271.90  4601.1  268.35
  4621.3  263.92  4628.5  261.00  4699.3  251.30  4722.3  249.31  4742.5  243.77
  4752.6  242.78  4813.2  241.10  4833.4  242.71  4841.0  246.48  4853.6  246.66
  4894.0  240.85  4997.0  240.02  4999.8  239.52  5003.0  240.02  5166.7  240.20
  5186.9  242.22  5200.3  242.47  5207.1  241.17  5237.4  244.11  5337.0  246.14
  5378.8  248.13  5429.3  252.41  5611.2  263.89  5625.4  265.69  5731.8  271.14
#Mann=3,-1,0
  4437.7    0.15       0  4997.0    0.05       0  5003.0    0.15       0
Bank Sta=4997,5003
Exp/Cntr=0.3,0.1

Type RM Length L Ch R = 1,1146,464,464,464
BEGIN DESCRIPTION:
Mapping XS 17e83262
END DESCRIPTION:
XS GIS Cut Line= 2
      3725335.57     10624157.12      3725137.64     10625391.55
#Sta/Elev= 30
  4406.5  278.65  4460.2  276.87  4521.0  271.24  4542.6  266.90  4599.5  258.78
  4652.7  254.15  4666.5  252.45  4672.9  250.15  4693.2  248.97  4728.5  249.04
  4754.0  245.45  4795.5  243.62  4885.6  240.47  4936.2  239.51  4976.4  239.95
  4997.0  238.69  4999.8  238.19  5003.0  238.69  5017.3  239.67  5138.8  240.19
  5159.1  242.14  5179.3  240.18  5331.2  244.70  5425.3  251.02  5482.2  256.19
  5503.4  259.11  5533.8  261.12  5564.2  265.09  5574.3  265.45  5656.7  277.18
#Mann=3,-1,0
  4406.5    0.15       0  4997.0    0.05       0  5003.0    0.15       0
Bank Sta=4997,5003
Exp/Cntr=0.3,0.1

Type RM Length L Ch R = 1,682,419,419,419
BEGIN DESCRIPTION:
Mapping XS 03fc6d71
END DESCRIPTION:
XS GIS Cut Line= 3
      3724778.27     10624115.48      3724788.68     10624724.87
      3725059.54     10625344.70
#Sta/Elev= 30
  4435.4  260.42  4460.1  259.04  4510.1  253.07  4540.1  253.38  4570.1  248.56
  4660.1  243.37  4790.2  240.74  4960.2  241.73  4980.2  240.72  4990.2  237.68
  4997.0  237.68  4999.8  237.18  5003.0  237.68  5010.2  240.90  5050.7  240.43
  5139.0  241.59  5157.0  242.92  5185.8  242.46  5209.2  244.81  5232.6  245.64
  5308.3  245.63  5367.2  244.44  5459.6  247.66  5541.8  253.96  5574.5  257.41
  5634.3  261.02  5686.6  266.28  5710.0  269.22  5716.1  271.22  5721.3  271.22
#Mann=3,-1,0
  4435.4    0.15       0  4997.0    0.05       0  5003.0    0.15       0
Bank Sta=4997,5003
Exp/Cntr=0.3,0.1

Type RM Length L Ch R = 1,263,0,0,0
BEGIN DESCRIPTION:
UNT 129 IN BOCR 1.0
END DESCRIPTION:
XS GIS Cut Line= 3
      3724544.81     10624031.10      3724367.72     10624718.65
      3725023.94     10625351.43
#Sta/Elev= 30
  4312.3  268.92  4332.0  265.04  4342.3  265.03  4350.4  261.24  4373.3  257.00
  4414.6  256.18  4445.6  249.47  4513.1  242.98  4594.5  240.45  4734.7  245.04
  4848.3  241.29  4982.6  242.69  4996.4  240.78  4997.0  236.71  4999.8  236.21
  5003.0  236.71  5013.6  241.33  5027.0  241.89  5031.8  245.94  5045.9  244.68
  5067.0  246.66  5088.4  246.34  5095.3  242.54  5102.5  245.77  5109.5  241.41
  5215.7  241.02  5484.3  248.06  5597.5  247.84  5717.9  253.45  5933.9  271.20
#Mann=3,-1,0
  4312.3    0.15       0  4997.0    0.05       0  5003.0    0.15       0
Bank Sta=4997,5003
Exp/Cntr=0.3,0.1

Chan Stop Cuts=-1