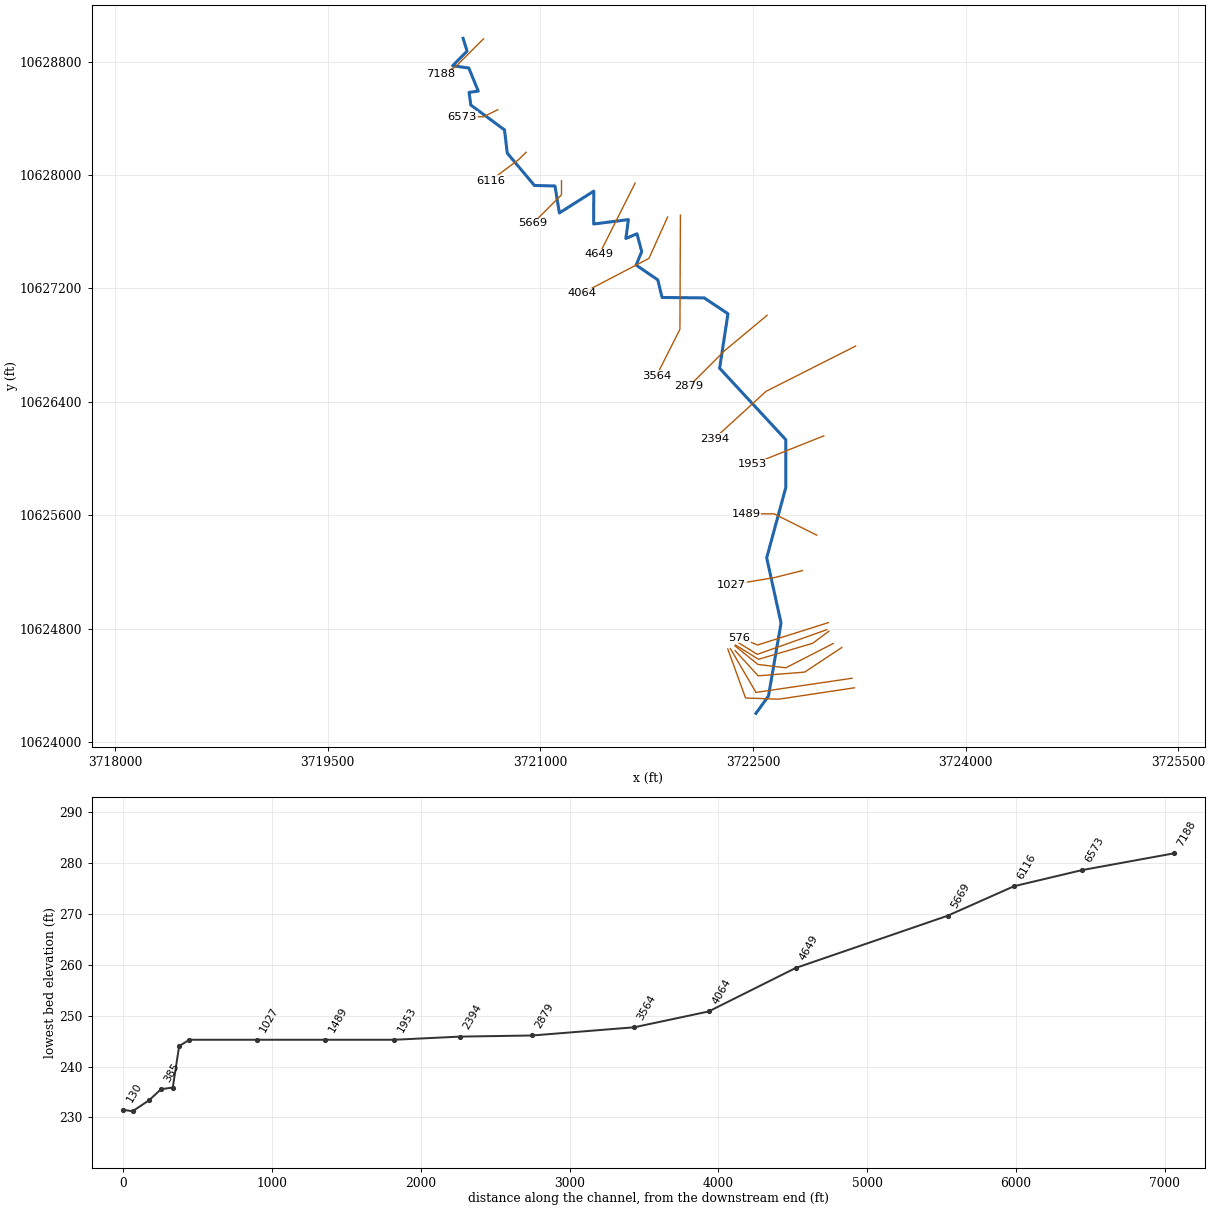
--- UNT 130 IN BOCR.prj (project) ---

Proj Title=UNT 130 IN BOCR Base Level Engineering
Current Plan=p01
Default Exp/Contr=0.3,0.1
English Units
Geom File=g01
Flow File=f01
Plan File=p01
Y Axis Title=Elevation
X Axis Title(PF)=Main Channel Distance
X Axis Title(XS)=Station
BEGIN DESCRIPTION:
UNT 130 IN BOCR
END DESCRIPTION:
DSS Export Rating Curves= 0
DSS Export Rating Curve Sorted= 0
DSS Export Volume Flow Curves= 0
DXF OffsetX= 0
DXF OffsetY= 0
DXF ScaleX= 1
DXF ScaleY= 10

--- UNT 130 IN BOCR.p01 (plan) ---

Plan Title=Multiple Run
Short Identifier=Multiple
Geom File=g01
Flow File=f01
Subcritical Flow
K Sum by GR= 0
Std Step Tol= 0.01
Critical Tol= 0.01
Num of Std Step Trials= 20
Max Error Tol= 0.3
Flow Tol Ratio= 0.001
Split Flow NTrial= 30
Split Flow Tol= 0.02
Split Flow Ratio= 0.02
Log Output Level= 0
Friction Slope Method= 1
Unsteady Friction Slope Method= 2
Unsteady Bridges Friction Slope Method= 1
Parabolic Critical Depth
Global Vel Dist=  1 , 1 , 1
Global Log Level= 0
CheckData=True
Encroach Param= -1, 0, 0, 0
BEGIN DESCRIPTION:
Multiple Run
END DESCRIPTION:

--- UNT 130 IN BOCR.f01 (steady flow) ---

Flow Title=Multiple
Number of Profiles=7
Profile Names=10-year,25-year,50-year,1pct_min,100-year,1pct_plu,500-year
River Rch & RM= UNT 130 IN BOCR,Reach-1,7188
     327     425     504     439     594     804     829
River Rch & RM= UNT 130 IN BOCR,Reach-1,2879
     549     736     889     789    1067    1443    1542
Boundary for River Rch & Prof#=UNT 130 IN BOCR,Reach-1,1
Up Type=0
Dn Type=3
Dn Slope=0.005
Boundary for River Rch & Prof#=UNT 130 IN BOCR,Reach-1,2
Up Type=0
Dn Type=3
Dn Slope=0.005
Boundary for River Rch & Prof#=UNT 130 IN BOCR,Reach-1,3
Up Type=0
Dn Type=3
Dn Slope=0.005
Boundary for River Rch & Prof#=UNT 130 IN BOCR,Reach-1,4
Up Type=0
Dn Type=3
Dn Slope=0.005
Boundary for River Rch & Prof#=UNT 130 IN BOCR,Reach-1,5
Up Type=0
Dn Type=3
Dn Slope=0.005
Boundary for River Rch & Prof#=UNT 130 IN BOCR,Reach-1,6
Up Type=0
Dn Type=3
Dn Slope=0.005
Boundary for River Rch & Prof#=UNT 130 IN BOCR,Reach-1,7
Up Type=0
Dn Type=3
Dn Slope=0.005

--- UNT 130 IN BOCR.g01 (geometry) ---

Geom Title=Existing Conditions
Program Version=4.10

River Reach=UNT 130 IN BOCR ,Reach-1
Reach XY= 30
      3720455.54     10628963.38       3720483.5       10628873.
      3720381.75       10628770.      3720495.75       10628754.
       3720562.5       10628591.      3720497.75       10628582.
      3720509.75       10628493.       3720747.5       10628318.
        3720767.       10628154.       3720958.5       10627926.
       3721103.5       10627922.      3721134.75       10627732.
      3721377.25       10627886.      3721376.25       10627654.
       3721621.5       10627685.       3721603.5       10627552.
        3721682.       10627585.       3721715.5       10627459.
      3721675.91     10627364.34        3721829.       10627260.
      3721858.75       10627136.        3722156.       10627133.
      3722323.75       10627021.        3722265.       10626637.
      3722731.75       10626133.      3722731.75       10625795.
        3722597.       10625300.      3722698.25       10624840.
      3722609.75       10624326.       3722521.5       10624203.

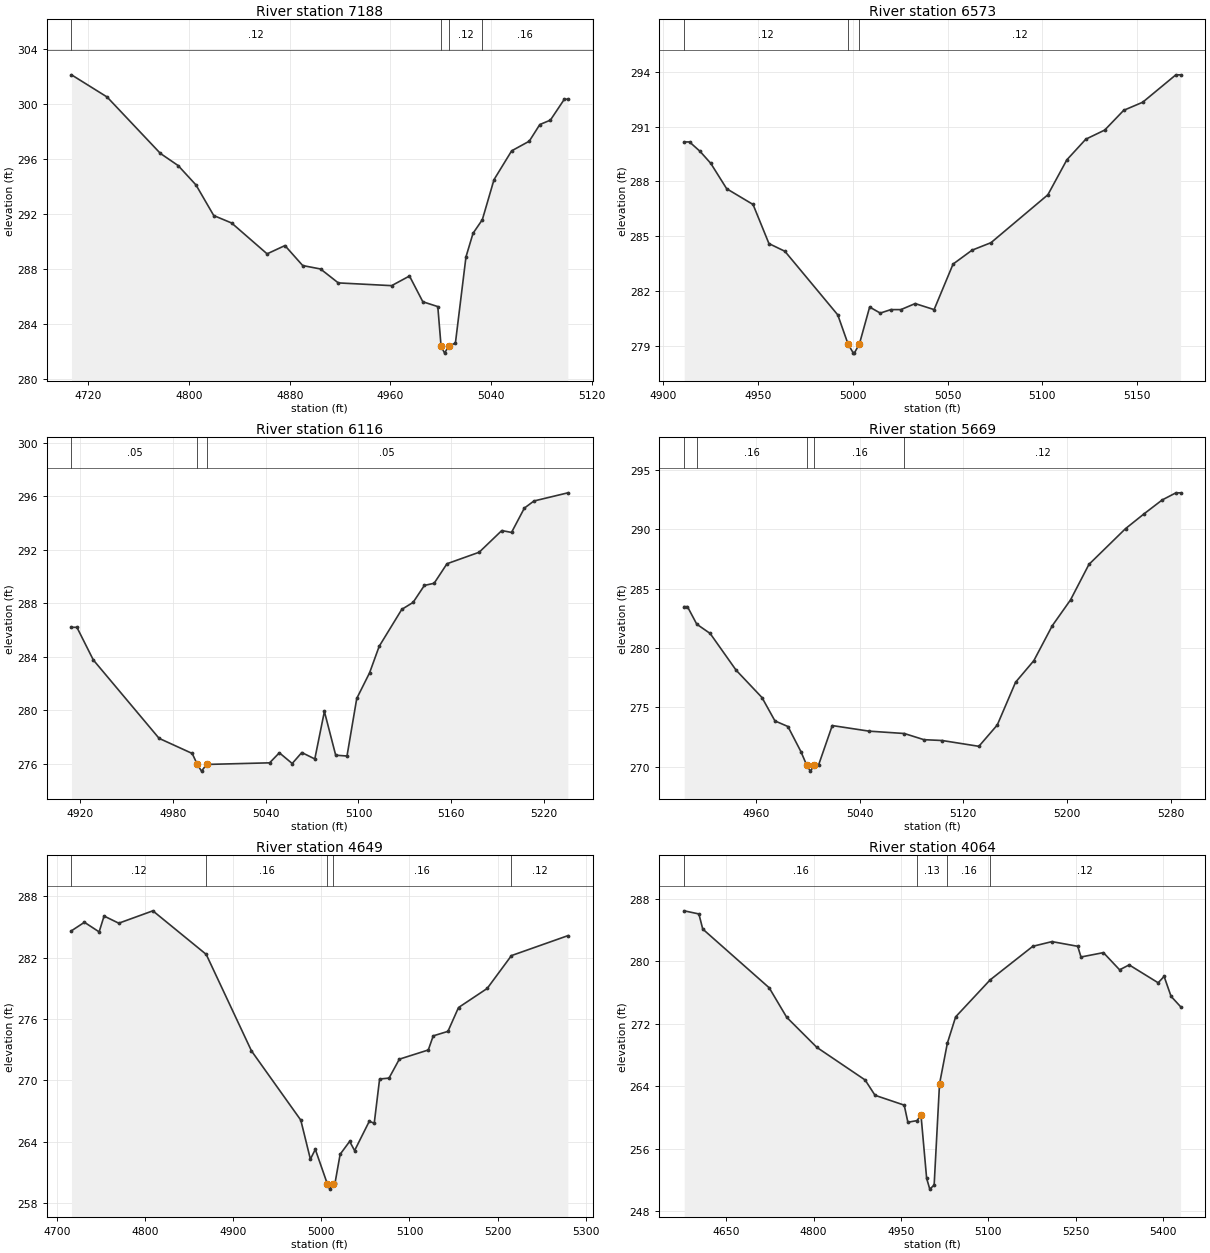
Type RM Length L Ch R = 1 ,7188    ,615,615,615
BEGIN DESCRIPTION:
UNT 130 IN BOCR 13.0
END DESCRIPTION:
XS GIS Cut Line= 3
       3720599.6     10628960.18      3720399.61     10628760.19
      3720299.64      10628710.2
#Sta/Elev= 30
  4706.5   302.1  4734.8  300.49  4777.2  296.39  4791.3  295.51  4805.5   294.1
  4819.6  291.88  4833.8  291.34    4862   289.1  4876.2   289.7  4890.3  288.25
  4904.5     288  4918.6  286.99    4961  286.79  4975.2  287.49  4985.8  285.62
  4997.7  285.27  5000.3  282.39  5003.1  281.89  5006.3  282.39  5011.7  282.62
  5020.1  288.88  5025.7  290.59  5033.1  291.58  5042.4  294.49  5056.4  296.58
  5070.4  297.28  5078.8  298.49  5087.2  298.81  5098.3  300.33  5101.1  300.33
#Mann= 4 ,-1 , 0
  4706.5     .12       0  5000.3     .07       0  5006.3     .12       0
  5033.1     .16       0
Bank Sta=5000.3,5006.3
XS Rating Curve= 0 ,0
Exp/Cntr=0.3,0.1

Type RM Length L Ch R = 1 ,6573    ,457,457,457
BEGIN DESCRIPTION:
UNT 130 IN BOCR 12.0
END DESCRIPTION:
XS GIS Cut Line= 3
       3720699.6     10628460.18      3720599.61     10628410.19
       3720449.6     10628410.19
#Sta/Elev= 30
  4911.1  290.16  4913.9  290.16  4919.5  289.64  4925.1  288.99  4933.5   287.6
  4947.4  286.74  4955.8   284.6  4964.2  284.18  4992.1   280.7  4997.5  279.11
  5000.3  278.61  5000.8  278.61  5003.5  279.11  5008.9  281.13  5014.5   280.8
  5020.1  280.99  5025.4  280.99  5032.9  281.32  5042.9  280.99  5052.9  283.48
  5062.9  284.24  5072.9  284.65  5102.9  287.27  5112.9  289.18  5122.9  290.31
  5132.9  290.81  5142.9  291.89  5152.9  292.33  5170.4  293.83  5172.9  293.83
#Mann= 3 ,-1 , 0
  4911.1     .12       0  4997.5     .07       0  5003.5     .12       0
Bank Sta=4997.5,5003.5
XS Rating Curve= 0 ,0
Exp/Cntr=0.3,0.1

Type RM Length L Ch R = 1 ,6116    ,447,447,447
BEGIN DESCRIPTION:
UNT 130 IN BOCR 11.0
END DESCRIPTION:
XS GIS Cut Line= 3
      3720899.61     10628160.19      3720849.61     10628110.19
      3720649.62     10627960.19
#Sta/Elev= 30
  4914.6  286.19  4918.1  286.19  4928.7  283.75  4971.2  277.89  4992.6  276.76
  4995.9  275.94  4998.6  275.44  5001.9  275.94  5042.6  276.06  5048.9  276.81
  5057.2  276.01  5063.4  276.83  5071.8  276.35    5078   279.9  5085.3  276.63
  5092.6  276.57  5098.9  280.87  5107.2  282.79  5113.4  284.77    5128  287.53
  5135.3  288.05  5142.6  289.32  5148.9  289.48  5157.2  290.94    5178   291.8
  5192.6  293.42  5198.9  293.28  5207.2   295.1  5213.4  295.63  5235.3  296.24
#Mann= 3 ,-1 , 0
  4914.6     .05       0  4995.9     .03       0  5001.9     .05       0
Bank Sta=4995.9,5001.9
XS Rating Curve= 0 ,0
Exp/Cntr=0.3,0.1

Type RM Length L Ch R = 1 ,5669    ,1020,1020,1020
BEGIN DESCRIPTION:
UNT 130 IN BOCR 10.0
END DESCRIPTION:
XS GIS Cut Line= 3
      3721149.61     10627960.22      3721149.61     10627860.19
      3720949.59     10627660.17
#Sta/Elev= 30
  4904.7  283.49  4907.2  283.49  4914.4  282.01  4924.7  281.23  4944.7  278.14
  4964.7  275.83  4974.7  273.86  4984.7  273.39  4994.7  271.28  4999.2  270.13
    5002  269.63  5005.2  270.13  5008.3  270.13  5018.9  273.47  5047.2     273
  5074.5   272.8  5089.6  272.28  5103.7  272.21    5132  271.72  5146.2  273.52
  5160.3  277.12  5174.4  278.94  5188.6  281.88  5202.7  284.06  5216.9  287.05
  5245.1  290.06  5259.3   291.3  5273.4  292.48    5284  293.08  5287.6  293.08
#Mann= 5 ,-1 , 0
  4904.7     .05       0  4914.4     .16       0  4999.2     .07       0
  5005.2     .16       0  5074.5     .12       0
Bank Sta=4999.2,5005.2
XS Rating Curve= 0 ,0
Exp/Cntr=0.3,0.1

Type RM Length L Ch R = 1 ,4649    ,585,585,585
BEGIN DESCRIPTION:
Mapping XS 65c3f98f
END DESCRIPTION:
XS GIS Cut Line= 2
      3721669.01     10627942.74      3721415.52     10627439.25
#Sta/Elev= 30
  4716.2  284.64  4730.9  285.47  4747.6  284.53  4753.2  286.08  4769.9  285.38
  4808.6  286.59  4869.2  282.33  4920.6  272.89  4976.6  266.12  4987.5   262.3
  4993.1  263.26  5006.8  259.87  5009.6  259.37  5012.8  259.87  5015.4  259.93
  5021.3  262.78  5032.1  264.04  5037.7  263.14  5054.4  266.01    5060  265.81
  5066.1  270.14  5076.8  270.23  5088.5  272.08  5121.4  272.98    5127  274.36
  5143.7   274.8  5155.7  277.13  5188.3     279  5215.8  282.21  5279.9  284.16
#Mann= 5 ,-1 , 0
  4716.2     .12       0  4869.2     .16       0  5006.8     .07       0
  5012.8     .16       0  5215.8     .12       0
Bank Sta=5006.8,5012.8
XS Rating Curve= 0 ,0
Exp/Cntr=0.3,0.1

Type RM Length L Ch R = 1 ,4064    ,500,500,500
BEGIN DESCRIPTION:
Mapping XS 8b7c7bba
END DESCRIPTION:
XS GIS Cut Line= 3
      3721898.17     10627703.15      3721766.23      10627411.5
      3721294.55     10627165.25
#Sta/Elev= 30
    4578  286.44  4603.2  286.04  4609.8  284.11  4723.9  276.59  4753.9  272.82
  4805.6  268.97  4888.6  264.79  4905.6  262.83  4955.7  261.57    4962  259.38
  4977.7  259.59  4984.5  260.31  4994.2   252.2  4999.6  250.82  5007.1  251.34
  5016.3  264.27  5029.7  269.48    5044  272.87  5103.2   277.6  5176.5   281.9
  5209.4   282.5  5253.6   281.9  5259.2  280.53  5297.7  281.09  5325.5  278.89
  5341.9  279.52  5391.7  277.23  5401.9  278.05  5413.8   275.5  5430.2  274.17
#Mann= 4 ,-1 , 0
    4578     .16       0  4977.7     .13       0  5029.7     .16       0
  5103.2     .12       0
Bank Sta=4984.5,5016.3
XS Rating Curve= 0 ,0
Exp/Cntr=0.3,0.1

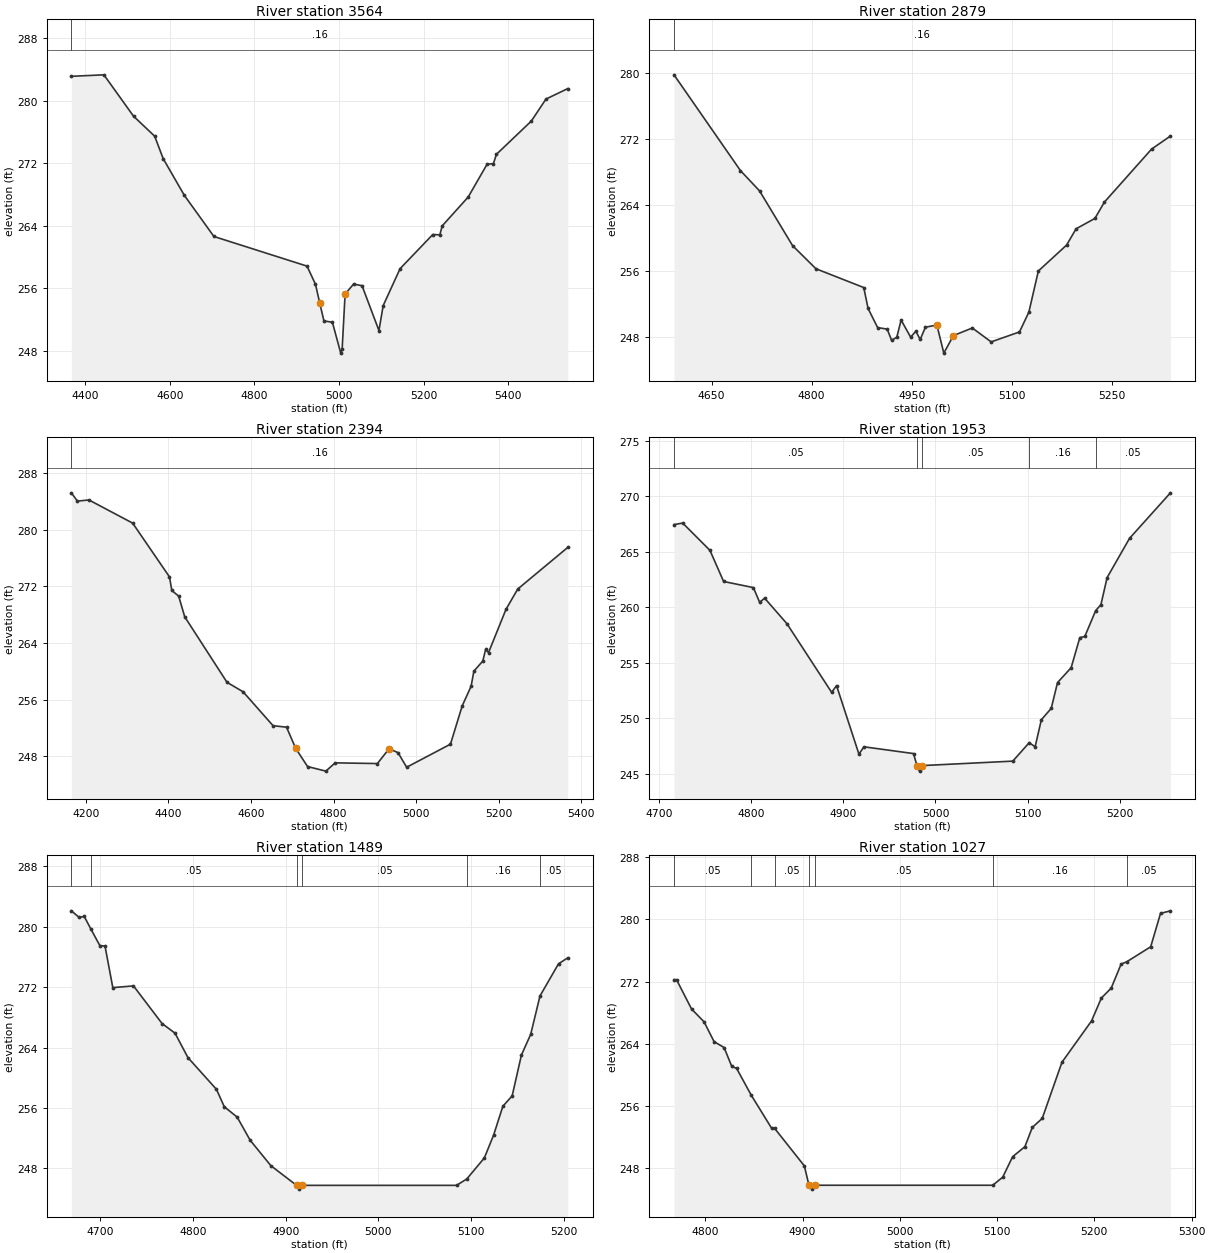
Type RM Length L Ch R = 1 ,3564    ,685,685,685
BEGIN DESCRIPTION:
UNT 130 IN BOCR 7.0
END DESCRIPTION:
XS GIS Cut Line= 3
      3721988.45     10627717.07      3721984.98      10626911.5
      3721819.19     10626583.38
#Sta/Elev= 30
  4367.4  283.12  4444.3  283.31  4514.3  278.02  4564.3  275.46  4584.3   272.6
  4634.3   267.9  4704.3  262.63  4924.3  258.84  4944.3  256.52  4954.3  254.13
  4964.3  251.83  4984.3  251.66    5004  247.71  5007.3  248.21  5014.3  255.26
  5034.3  256.54  5054.3  256.34  5094.3   250.6  5104.3  253.79  5144.3  258.52
  5221.5  262.88  5238.2  262.84  5243.8  263.99  5305.1  267.67  5349.7  271.86
  5364.9  271.96  5371.9  273.14  5454.5   277.4    5489  280.21  5540.6  281.55
#Mann= 1 ,-1 , 0
  4367.4     .16       0
Bank Sta=4954.3,5014.3
XS Rating Curve= 0 ,0
Exp/Cntr=0.3,0.1

Type RM Length L Ch R = 1 ,2879    ,485,485,485
BEGIN DESCRIPTION:
UNT 130 IN BOCR 6.0
END DESCRIPTION:
XS GIS Cut Line= 3
      3722599.61     10627010.19      3722299.61     10626760.19
      3722049.58     10626510.16
#Sta/Elev= 30
  4593.8  279.75  4693.4  268.17    4722  265.72  4771.5   259.1  4806.6   256.3
  4878.2  254.03  4884.7   251.5    4899  249.19  4913.4     249  4919.9  247.65
  4927.7  248.01  4934.2   250.1  4948.5  248.03  4956.3  248.75  4962.8  247.75
  4970.6  249.23  4987.8   249.5  4998.2   246.1  5012.6  248.22  5040.9  249.14
  5069.2  247.46  5111.6  248.66  5125.7  251.06  5139.9  256.03  5182.3  259.17
  5196.4  261.13  5224.7  262.39  5238.9  264.36  5309.6  270.77  5337.9  272.35
#Mann= 1 ,-1 , 0
  4593.8     .16       0
Bank Sta=4987.8,5012.6
XS Rating Curve= 0 ,0
Exp/Cntr=0.3,0.1

Type RM Length L Ch R = 1 ,2394    ,441,441,441
BEGIN DESCRIPTION:
UNT 130 IN BOCR 5.0
END DESCRIPTION:
XS GIS Cut Line= 3
      3723224.55     10626793.43      3722592.62       10626474.
      3722228.01     10626140.65
#Sta/Elev= 30
  4165.1  285.21  4179.8  284.04  4207.7   284.2  4313.5  280.93  4402.7  273.33
  4408.3  271.42    4425   270.6  4439.6  267.69    4542  258.43    4581  257.09
  4653.5   252.3  4686.1  252.09  4708.5  249.08    4737  246.53  4781.3  245.88
  4803.9  247.05  4906.1  246.95  4934.5  249.05  4956.1  248.49    4977  246.43
  5083.1  249.69  5111.5   255.1    5133  257.87  5139.8  260.01  5161.4  261.44
  5168.2  263.07  5175.3  262.64  5217.5  268.74  5245.9  271.61  5367.2   277.5
#Mann= 1 ,-1 , 0
  4165.1     .16       0
Bank Sta=4708.5,4934.5
XS Rating Curve= 0 ,0
Exp/Cntr=0.3,0.1

Type RM Length L Ch R = 1 ,1953    ,464,464,464
BEGIN DESCRIPTION:
UNT 130 IN BOCR 4.0
END DESCRIPTION:
XS GIS Cut Line= 3
      3722999.58     10626160.18      3722749.61     10626060.19
       3722499.6     10625960.18
#Sta/Elev= 30
  4716.4  267.45  4725.8  267.59  4755.4  265.13  4770.2  262.33  4802.5  261.78
  4809.3  260.45  4814.7  260.83  4838.9  258.53  4887.4  252.35  4892.7  252.96
    4917  246.79  4922.4  247.45  4976.2  246.84  4979.9  245.76  4982.7  245.26
  4985.9  245.76  5083.9  246.16  5101.7  247.82  5108.1  247.45  5114.9  249.89
  5125.6  250.91  5132.4  253.23  5147.2  254.57  5156.6  257.28    5162  257.38
  5173.8  259.71  5179.5  260.25  5186.2  262.68  5210.5  266.21  5254.9  270.31
#Mann= 5 ,-1 , 0
  4716.4     .05       0  4979.9    .035       0  4985.9     .05       0
  5101.7     .16       0  5173.8     .05       0
Bank Sta=4979.9,4985.9
XS Rating Curve= 0 ,0
Exp/Cntr=0.3,0.1

Type RM Length L Ch R = 1 ,1489    ,462,462,462
BEGIN DESCRIPTION:
UNT 130 IN BOCR 3.0
END DESCRIPTION:
XS GIS Cut Line= 3
      3722949.57     10625460.21      3722649.61     10625610.19
      3722449.58     10625610.19
#Sta/Elev= 30
  4668.9  282.11  4677.2  281.25  4682.8  281.36  4689.9  279.71  4699.6  277.51
  4705.2  277.44  4713.6  271.94  4735.9  272.17  4766.7  267.19  4780.7  265.91
  4794.6  262.68  4825.4  258.47  4833.8  256.17  4847.7   254.8  4861.7  251.74
  4884.1  248.36  4911.8  245.76  4914.6  245.26  4917.8  245.76  5084.3  245.76
  5095.3   246.6  5114.3  249.39  5124.3  252.42  5134.3  256.24  5144.3  257.61
  5154.3  263.02  5164.3  265.76  5174.3  270.84  5194.3   275.1  5204.3  275.89
#Mann= 6 ,-1 , 0
  4668.9     .08       0  4689.9     .05       0  4911.8    .033       0
  4917.8     .05       0  5095.3     .16       0  5174.3     .05       0
Bank Sta=4911.8,4917.8
XS Rating Curve= 0 ,0
Exp/Cntr=0.3,0.1

Type RM Length L Ch R = 1 ,1027    ,451,451,451
BEGIN DESCRIPTION:
UNT 130 IN BOCR 2.0
END DESCRIPTION:
XS GIS Cut Line= 3
      3722849.59     10625210.18      3722649.61     10625160.19
      3722349.58     10625110.18
#Sta/Elev= 30
  4767.9  272.24  4770.5  272.24  4785.9  268.47  4798.8  266.81  4809.1  264.26
  4819.4   263.5  4827.2  261.09  4832.3   260.8  4847.3  257.36  4868.4  253.07
  4871.3  253.09  4901.9  248.25  4906.6  245.76  4909.4  245.26  4912.6  245.76
  5095.5  245.76  5105.8   246.8    5116  249.44  5128.6  250.73  5136.2  253.21
  5146.4  254.37  5166.7  261.61  5197.1  266.93  5207.2  269.88  5217.3  271.15
  5227.5  274.25  5233.2  274.54  5257.9  276.48    5268  280.78  5278.2  281.11
#Mann= 7 ,-1 , 0
  4767.9     .05       0  4847.3     .16       0  4871.3     .05       0
  4906.6    .033       0  4912.6     .05       0  5095.5     .16       0
  5233.2     .05       0
Bank Sta=4906.6,4912.6
XS Rating Curve= 0 ,0
Exp/Cntr=0.3,0.1

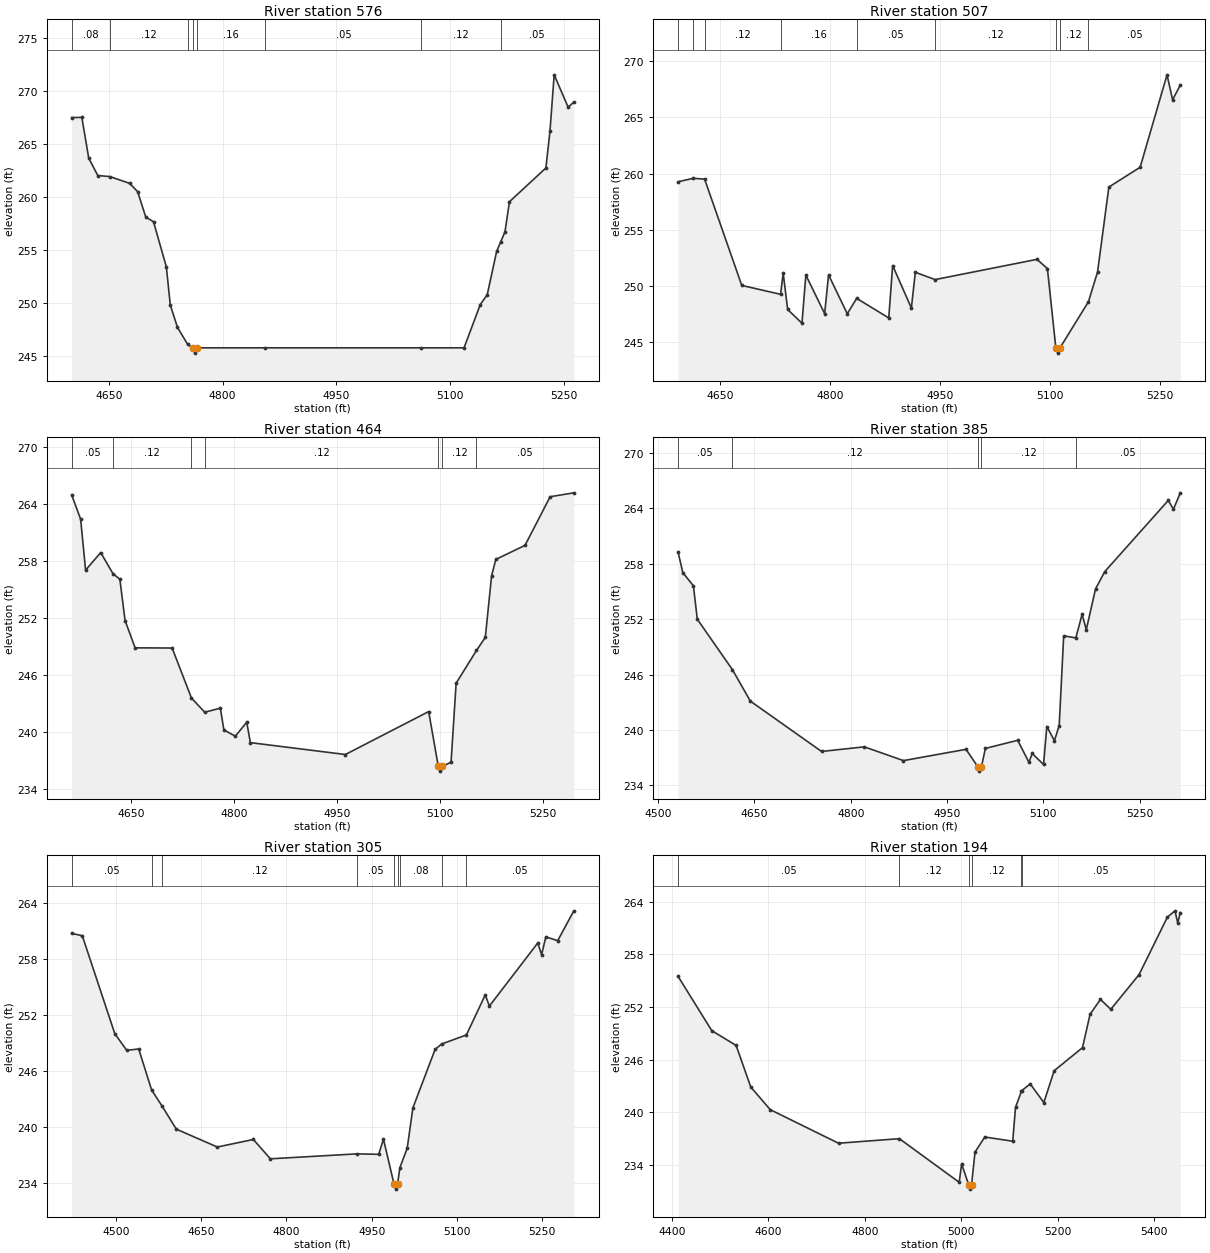
Type RM Length L Ch R = 1 ,576     ,69,69,69
BEGIN DESCRIPTION:
Mapping XS 5e6c9fe4
END DESCRIPTION:
XS GIS Cut Line= 3
      3723032.43     10624843.09      3722532.43     10624685.11
      3722405.68      10624737.2
#Sta/Elev= 30
  4601.2  267.46  4614.6  267.48  4623.7  263.64  4635.6     262  4651.5   261.9
  4677.6  261.26  4688.1  260.48  4698.8  258.09    4709  257.64  4725.9   253.4
  4731.1   249.8  4740.5   247.7    4754  246.08  4760.5  245.76  4763.2  245.26
  4766.5  245.76  4856.5  245.76  5061.5  245.76    5118  245.76  5139.4  249.84
  5148.5  250.76    5161  254.87  5166.3  255.75  5171.9  256.69  5177.8  259.53
  5225.8  262.71  5231.2  266.21  5236.7  271.49  5255.1  268.44  5262.6  268.92
#Mann= 8 ,-1 , 0
  4601.2     .08       0  4651.5     .12       0    4754     .16       0
  4760.5    .033       0  4766.5     .16       0  4856.5     .05       0
  5061.5     .12       0  5166.3     .05       0
Bank Sta=4760.5,4766.5
XS Rating Curve= 0 ,0
Exp/Cntr=0.3,0.1

Type RM Length L Ch R = 1 ,507     ,43,43,43
BEGIN DESCRIPTION:
Mapping XS 945d8a45
END DESCRIPTION:
XS GIS Cut Line= 3
      3723020.26     10624792.74       3722530.7     10624619.14
      3722390.66     10624705.58
#Sta/Elev= 30
  4593.2  259.27  4613.9  259.58  4629.3   259.5  4679.9  250.05  4732.8  249.26
  4736.3  251.15  4742.4  247.91  4761.9  246.69  4767.2  250.97  4792.8  247.54
  4798.1  250.99  4823.6  247.53  4836.4   248.9  4880.1  247.16  4885.4  251.82
  4910.9  248.04  4916.3  251.22  4943.2  250.57    5082  252.37  5096.2  251.55
  5107.6  244.53  5110.3  244.03  5113.6  244.53  5152.1   248.6  5164.5  251.25
  5179.9   258.8  5222.5  260.56  5259.1  268.78  5266.7  266.56  5277.2  267.87
#Mann= 9 ,-1 , 0
  4593.2     .08       0  4613.9     .05       0  4629.3     .12       0
  4732.8     .16       0  4836.4     .05       0  4943.2     .12       0
  5107.6     .07       0  5113.6     .12       0  5152.1     .05       0
Bank Sta=5107.6,5113.6
XS Rating Curve= 0 ,0
Exp/Cntr=0.3,0.1

Type RM Length L Ch R = 1 ,464     ,79,79,79
BEGIN DESCRIPTION:
Mapping XS defe1ce4
END DESCRIPTION:
XS GIS Cut Line= 4
      3723035.94     10624782.36      3722921.32     10624697.26
      3722539.38     10624584.41      3722377.93      10624685.1
#Sta/Elev= 30
  4563.7  264.96  4576.8  262.39    4584  257.03    4606  258.88  4623.9  256.66
  4633.9  256.07  4641.5  251.72  4656.1  248.85    4710  248.83  4738.2  243.56
  4757.5  242.07  4780.2   242.5  4785.4   240.2  4802.1  239.55  4818.7  241.02
  4823.9  238.87  4962.3  237.62  5083.6  242.14  5097.6  236.37  5100.4  235.87
  5103.6  236.37  5116.2  236.81  5123.6  245.13  5153.2  248.57  5166.1  249.95
  5175.2  256.43  5181.4  258.16  5223.9  259.64  5260.5  264.76    5295  265.17
#Mann= 7 ,-1 , 0
  4563.7     .05       0  4623.9     .12       0  4738.2     .16       0
  4757.5     .12       0  5097.6     .07       0  5103.6     .12       0
  5153.2     .05       0
Bank Sta=5097.6,5103.6
XS Rating Curve= 0 ,0
Exp/Cntr=0.3,0.1

Type RM Length L Ch R = 1 ,385     ,80,80,80
BEGIN DESCRIPTION:
Mapping XS 1385d9d0
END DESCRIPTION:
XS GIS Cut Line= 4
      3723066.24      10624695.8      3722732.06     10624524.37
      3722534.57     10624548.24      3722373.21     10624679.49
#Sta/Elev= 30
    4531  259.24  4538.4  257.03  4554.8  255.61  4560.9  251.99  4615.5  246.54
  4643.6  243.12  4754.5  237.67  4821.1  238.17  4882.1  236.68  4979.6   237.9
  4997.7  236.04  5000.5  235.54  5003.7  236.04  5009.8     238  5060.1  238.88
  5077.6   236.5  5082.7  237.45  5100.4  236.26  5105.5  240.37  5117.4  238.84
  5124.8  240.48  5131.8  250.19  5150.7  249.97  5160.5  252.52    5167  250.86
  5181.4  255.27  5195.7  257.14  5294.8  264.86  5302.8   263.9  5313.5  265.68
#Mann= 5 ,-1 , 0
    4531     .05       0  4615.5     .12       0  4997.7     .07       0
  5003.7     .12       0  5150.7     .05       0
Bank Sta=4997.7,5003.7
XS Rating Curve= 0 ,0
Exp/Cntr=0.3,0.1

Type RM Length L Ch R = 1 ,305     ,111,111,111
BEGIN DESCRIPTION:
Mapping XS 1e411021
END DESCRIPTION:
XS GIS Cut Line= 4
      3723127.01      10624667.6      3722864.44     10624493.99
      3722536.74     10624467.95      3722374.63     10624645.19
#Sta/Elev= 30
    4422  260.71  4440.7  260.46  4497.9  249.99  4518.9  248.21    4540  248.35
  4562.7  243.97  4581.4  242.22  4606.2  239.78  4678.4  237.87  4741.7  238.68
  4771.7  236.61  4924.4  237.14  4962.3  237.09  4970.7  238.71  4989.4  233.87
  4992.2  233.37  4995.4  233.87  4999.6  235.66  5012.5  237.75  5022.5  242.06
  5061.6  248.31    5073  248.88  5116.6  249.85  5149.8  254.13  5157.1  252.94
  5242.2  259.68    5249  258.43  5256.4  260.34  5277.3  259.93  5305.7  263.12
#Mann= 9 ,-1 , 0
    4422     .05       0  4562.7     .08       0  4581.4     .12       0
  4924.4     .05       0  4989.4     .07       0  4995.4     .05       0
  4999.6     .08       0    5073     .12       0  5116.6     .05       0
Bank Sta=4989.4,4995.4
XS Rating Curve= 0 ,0
Exp/Cntr=0.3,0.1

Type RM Length L Ch R = 1 ,194     ,64,64,64
BEGIN DESCRIPTION:
Mapping XS d51b548d
END DESCRIPTION:
XS GIS Cut Line= 3
      3723198.62     10624450.58      3722521.55     10624350.76
      3722341.44      10624658.9
#Sta/Elev= 30
  4412.7  255.49  4482.5   249.3    4533  247.61  4563.3  242.87  4603.8  240.28
  4745.3  236.45  4871.5  236.97  4995.5  231.99  5000.6  234.09  5015.2  231.71
  5017.9  231.21  5021.2  231.71  5028.3  235.43  5048.5  237.16  5106.5  236.68
  5112.3  240.53  5124.6  242.39  5125.4  242.46  5142.8  243.22    5171  241.09
  5192.5  244.73  5251.2  247.36  5266.9  251.17  5288.4  252.87  5309.9  251.74
  5368.5   255.7  5427.2  262.26  5442.9  262.98  5448.7   261.6    5454  262.78
#Mann= 6 ,-1 , 0
  4412.7     .05       0  4871.5     .12       0  5015.2     .07       0
  5021.2     .12       0  5124.6     .08       0  5125.4     .05       0
Bank Sta=5015.2,5021.2
XS Rating Curve= 0 ,0
Exp/Cntr=0.3,0.1

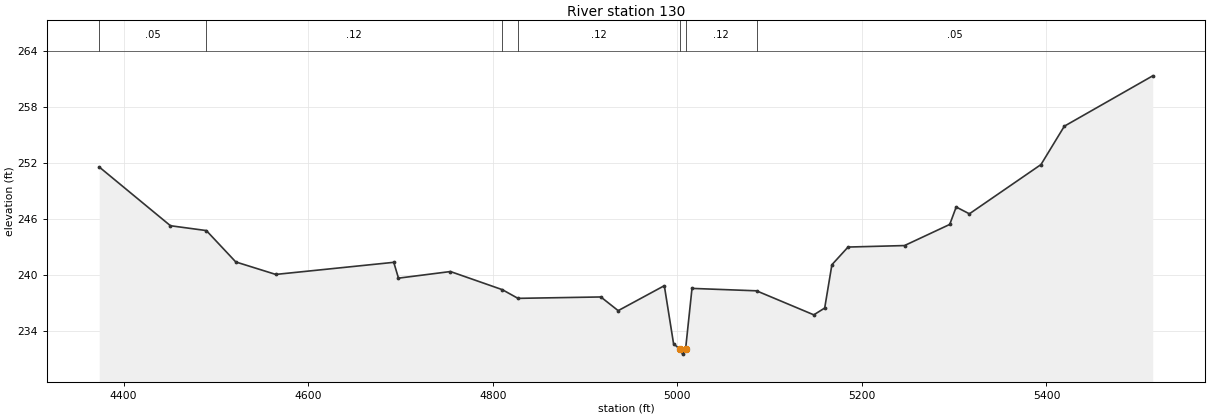
Type RM Length L Ch R = 1 ,130     ,0,0,0
BEGIN DESCRIPTION:
UNT 130 IN BOCR 1.0
END DESCRIPTION:
XS GIS Cut Line= 4
      3723215.97     10624383.31      3722682.14     10624303.02
      3722447.77      10624311.7      3722322.58     10624657.04
#Sta/Elev= 30
  4373.5  251.59  4450.7  245.28  4489.6  244.76  4521.5  241.39  4564.8  240.05
  4692.7  241.35  4697.8  239.65  4754.1  240.36  4810.4  238.41  4827.3  237.48
  4917.1  237.63  4935.9  236.16  4985.9  238.84  4995.9  232.62  5002.9  231.99
  5005.7  231.49  5008.9  231.99  5015.9  238.55  5085.8  238.29  5147.9  235.71
  5159.7  236.44  5167.5  241.09    5185  242.99  5246.2  243.15  5295.2  245.42
  5302.2  247.29  5316.5  246.56  5394.1  251.85  5419.4  255.97  5515.2  261.38
#Mann= 7 ,-1 , 0
  4373.5     .05       0  4489.6     .12       0  4810.4     .16       0
  4827.3     .12       0  5002.9     .07       0  5008.9     .12       0
  5085.8     .05       0
Bank Sta=5002.9,5008.9
XS Rating Curve= 0 ,0
Exp/Cntr=0.3,0.1

Chan Stop Cuts=-1
Use User Specified Reach Order=0
Composite Channel Slope=5