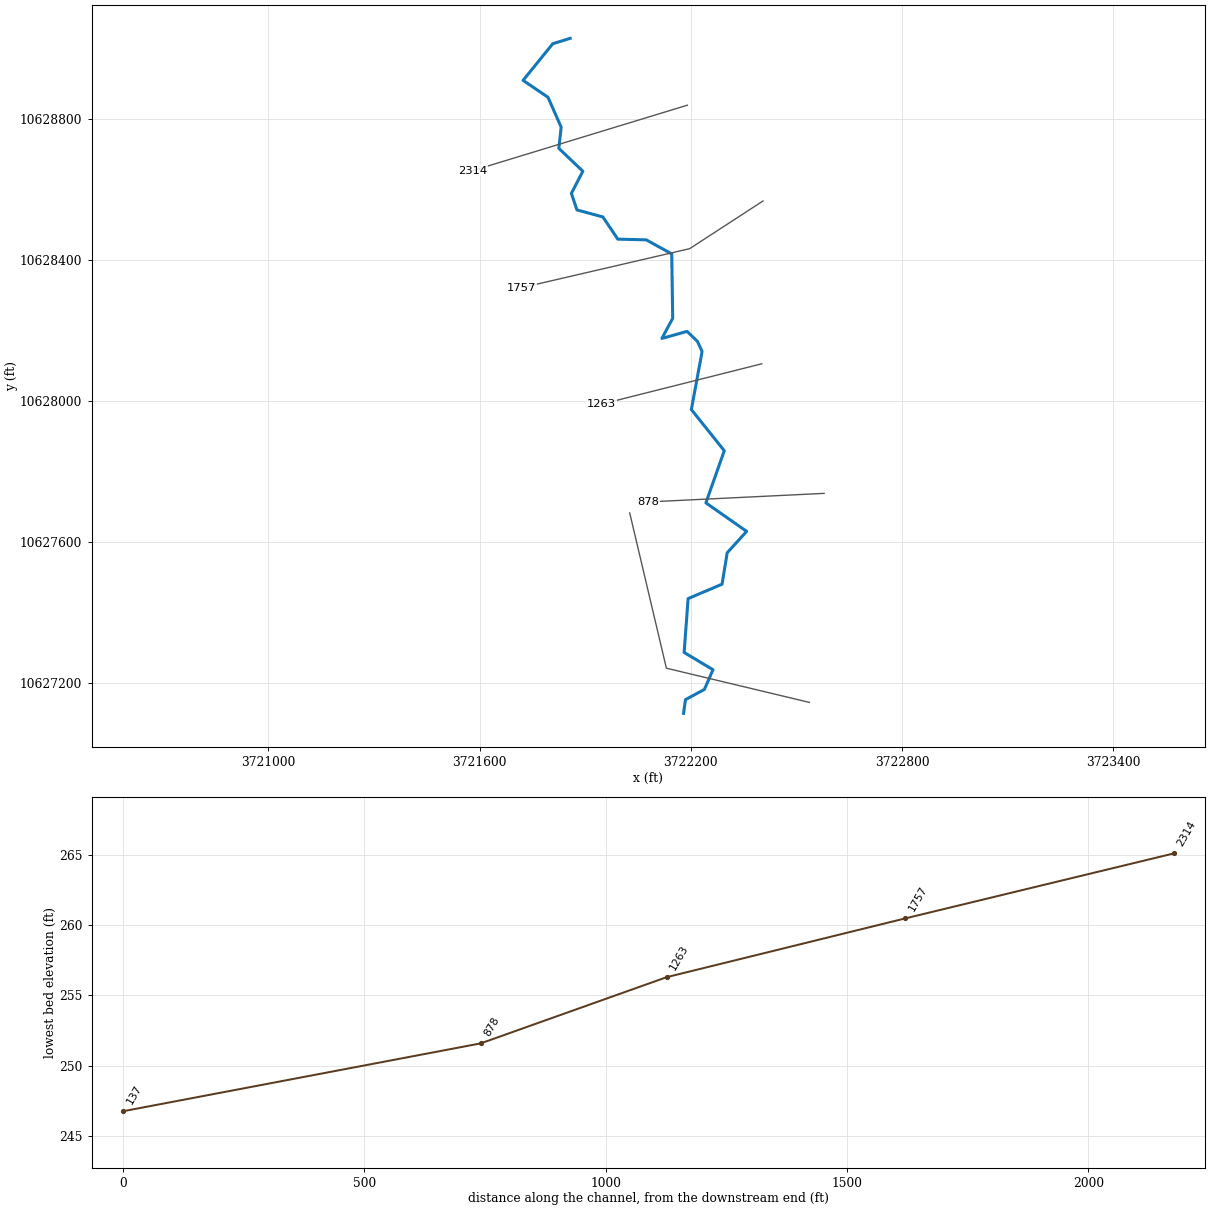
--- UNT 131 IN BOCR.prj (project) ---

Proj Title=UNT 131 IN BOCR Base Level Engineering
Current Plan=p01
Default Exp/Contr=0.3,0.1
English Units
Geom File=g01
Flow File=f01
Plan File=p01
Y Axis Title=Elevation
X Axis Title(PF)=Main Channel Distance
X Axis Title(XS)=Station
BEGIN DESCRIPTION:
UNT 131 IN BOCR
END DESCRIPTION:
DSS Export Rating Curves= 0
DSS Export Rating Curve Sorted= 0
DSS Export Volume Flow Curves= 0
DXF OffsetX= 0
DXF OffsetY= 0
DXF ScaleX= 1
DXF ScaleY= 10

--- UNT 131 IN BOCR.p01 (plan) ---

Plan Title=Multiple Run
Short Identifier=Multiple
Geom File=g01
Flow File=f01
Subcritical Flow
K Sum by GR= 0
Std Step Tol= 0.01
Critical Tol= 0.01
Num of Std Step Trials= 20
Max Error Tol= 0.3
Flow Tol Ratio= 0.001
Split Flow NTrial= 30
Split Flow Tol= 0.02
Split Flow Ratio= 0.02
Log Output Level= 0
Friction Slope Method= 1
Unsteady Friction Slope Method= 2
Unsteady Bridges Friction Slope Method= 1
Parabolic Critical Depth
Global Vel Dist=  1 , 1 , 1
Global Log Level= 0
CheckData=True
Encroach Param= -1, 0, 0, 0
BEGIN DESCRIPTION:
Multiple Run
END DESCRIPTION:

--- UNT 131 IN BOCR.f01 (steady flow) ---

Flow Title=Multiple
Number of Profiles=7
Profile Names=10-year,25-year,50-year,1pct_min,100-year,1pct_plu,500-year
River Rch & RM= UNT 131 IN BOCR,Reach-1,2314
     277     357     420     364     493     667     679
Boundary for River Rch & Prof#=UNT 131 IN BOCR,Reach-1,1
Up Type=0
Dn Type=3
Dn Slope=0.005
Boundary for River Rch & Prof#=UNT 131 IN BOCR,Reach-1,2
Up Type=0
Dn Type=3
Dn Slope=0.005
Boundary for River Rch & Prof#=UNT 131 IN BOCR,Reach-1,3
Up Type=0
Dn Type=3
Dn Slope=0.005
Boundary for River Rch & Prof#=UNT 131 IN BOCR,Reach-1,4
Up Type=0
Dn Type=3
Dn Slope=0.005
Boundary for River Rch & Prof#=UNT 131 IN BOCR,Reach-1,5
Up Type=0
Dn Type=3
Dn Slope=0.005
Boundary for River Rch & Prof#=UNT 131 IN BOCR,Reach-1,6
Up Type=0
Dn Type=3
Dn Slope=0.005
Boundary for River Rch & Prof#=UNT 131 IN BOCR,Reach-1,7
Up Type=0
Dn Type=3
Dn Slope=0.005

--- UNT 131 IN BOCR.g01 (geometry) ---

Geom Title=Existing Conditions
Program Version=4.10

River Reach=UNT 131 IN BOCR ,Reach-1
Reach XY= 30
      3721857.58      10629030.4        3721808.       10629015.
      3721723.75       10628911.       3721794.5       10628863.
        3721832.       10628778.      3721825.25       10628718.
       3721893.5       10628653.        3721861.       10628590.
      3721876.75       10628543.       3721950.5       10628523.
      3721992.75       10628460.      3722073.75       10628458.
        3722146.       10628418.      3722148.75       10628235.
        3722118.       10628178.       3722189.5       10628198.
      3722218.75       10628170.      3722232.25       10628141.
      3722201.75       10627976.      3722295.25       10627859.
        3722243.       10627711.      3722358.75       10627630.
       3722303.5       10627569.        3722289.       10627480.
       3722192.5       10627439.      3722181.25       10627286.
      3722263.25       10627237.      3722238.75       10627181.
        3722185.       10627152.       3722179.5       10627113.

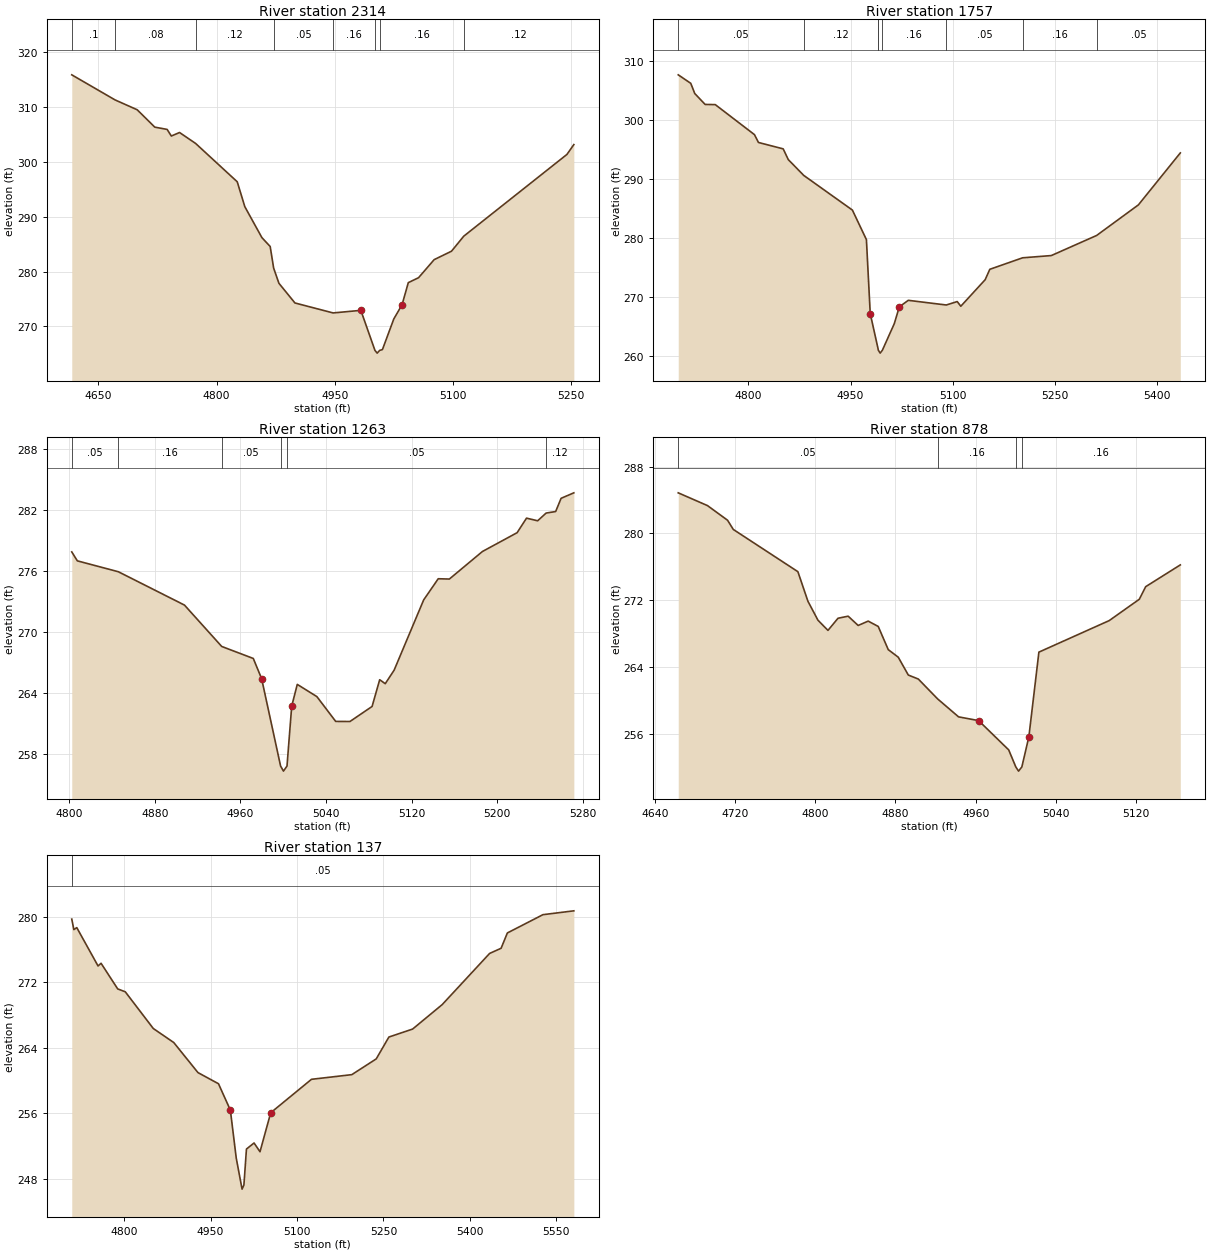
Type RM Length L Ch R = 1 ,2314    ,557,557,557
BEGIN DESCRIPTION:
UNT 131 IN BOCR 4.0
END DESCRIPTION:
XS GIS Cut Line= 2
      3722190.36     10628840.49      3721581.15     10628654.74
#Sta/Elev= 30
  4616.4  315.92  4671.3  311.34  4699.4  309.54  4721.7  306.37  4737.4  305.95
  4742.7  304.74  4753.1  305.39  4773.5  303.39  4826.3  296.39  4835.9  291.85
  4857.6  286.19  4868.1  284.57  4872.5  280.62  4879.2  277.85  4899.5  274.26
  4947.9  272.44  4983.1  272.91    5001   265.6  5003.8   265.1    5007   265.6
  5010.5  265.75  5024.9  271.34  5035.4  273.94  5043.3  277.97  5056.3  278.87
  5076.1  282.17  5098.1  283.71  5113.7  286.46  5244.5  301.38  5253.3  303.18
#Mann= 8 ,-1 , 0
  4616.4      .1       0  4671.3     .08       0  4773.5     .12       0
  4872.5     .05       0  4947.9     .16       0    5001     .07       0
    5007     .16       0  5113.7     .12       0
Bank Sta=4983.1,5035.4
XS Rating Curve= 0 ,0
Exp/Cntr=0.3,0.1

Type RM Length L Ch R = 1 ,1757    ,494,494,494
BEGIN DESCRIPTION:
UNT 131 IN BOCR 3.0
END DESCRIPTION:
XS GIS Cut Line= 3
      3722405.19     10628568.35      3722196.85     10628432.93
      3721720.32     10628322.26
#Sta/Elev= 30
  4696.8  307.65  4715.2  306.21  4721.1  304.48  4736.3  302.63  4751.2   302.6
  4808.8  297.51  4814.7  296.18    4851   295.1  4858.5  293.28  4881.2   290.6
  4952.7  284.72  4973.3  279.71  4978.9  267.18  4989.9  261.48  4990.8  260.97
  4993.5  260.47  4996.8  260.97  5014.3  265.48  5021.6  268.31  5034.8  269.42
  5090.6  268.63  5106.7  269.21    5112  268.42  5147.8  272.92  5154.6  274.68
  5202.8  276.63    5245  277.01  5311.6  280.42  5372.9   285.6  5434.5  294.41
#Mann= 8 ,-1 , 0
  4696.8     .05       0  4881.2     .12       0  4989.9     .16       0
  4990.8     .07       0  4996.8     .16       0  5090.6     .05       0
  5202.8     .16       0  5311.6     .05       0
Bank Sta=4978.9,5021.6
XS Rating Curve= 0 ,0
Exp/Cntr=0.3,0.1

Type RM Length L Ch R = 1 ,1263    ,385,385,385
BEGIN DESCRIPTION:
Mapping XS 244ec072
END DESCRIPTION:
XS GIS Cut Line= 2
      3722401.68     10628105.95      3721946.79     10627991.36
#Sta/Elev= 30
  4802.5  277.85  4807.7  276.97    4846   275.9  4907.8  272.62  4942.6  268.55
  4972.1  267.37  4979.9  265.38  4997.6  256.79  5000.3  256.29  5003.6  256.79
    5008  262.68  5013.2  264.82  5031.5  263.62  5049.1  261.18  5062.4  261.17
  5083.1  262.65  5090.2  265.28  5095.4  264.89  5103.7  266.22  5131.3  273.13
  5144.9  275.21  5155.3  275.18  5186.2  277.89  5218.6  279.74  5227.4  281.17
  5237.8  280.91  5245.7  281.67  5254.6  281.82  5259.7  283.12  5271.6  283.66
#Mann= 6 ,-1 , 0
  4802.5     .05       0    4846     .16       0  4942.6     .05       0
  4997.6     .03       0  5003.6     .05       0  5245.7     .12       0
Bank Sta=4979.9,5008
XS Rating Curve= 0 ,0
Exp/Cntr=0.3,0.1

Type RM Length L Ch R = 1 ,878     ,741,741,741
BEGIN DESCRIPTION:
Mapping XS 6c952e8d
END DESCRIPTION:
XS GIS Cut Line= 2
      3722578.76     10627737.89      3722078.75     10627713.58
#Sta/Elev= 30
  4663.4  284.86  4692.6  283.33  4712.6  281.58  4718.3  280.48  4782.7  275.43
  4792.7   271.9  4802.7  269.63  4812.7  268.41  4822.7  269.86  4832.8  270.11
  4842.8     269  4852.8  269.52  4862.8  268.88  4872.8  266.11  4882.8   265.2
  4892.8  263.07  4902.8  262.59    4922  260.22  4942.9  258.07  4962.9  257.62
  4992.9  254.12    5000  252.08  5002.7  251.58    5006  252.08    5013  255.68
    5023  265.81  5093.1  269.58  5123.1  272.13  5129.5  273.64    5164  276.24
#Mann= 4 ,-1 , 0
  4663.4     .05       0    4922     .16       0    5000     .07       0
    5006     .16       0
Bank Sta=4962.9,5013
XS Rating Curve= 0 ,0
Exp/Cntr=0.3,0.1

Type RM Length L Ch R = 1 ,137     ,0,0,0
BEGIN DESCRIPTION:
UNT 131 IN BOCR 1.0
END DESCRIPTION:
XS GIS Cut Line= 3
      3722537.11     10627144.13      3722130.81     10627241.36
      3722026.64     10627682.35
#Sta/Elev= 30
  4709.3   279.7  4712.9  278.42    4718  278.66  4754.9  273.98  4760.1  274.31
    4789  271.18  4802.1  270.83  4850.7  266.35  4886.2  264.64  4928.2  260.97
  4963.8  259.61  4984.4  256.39  4994.6  250.54  5004.7  246.75  5007.9  247.25
  5012.3  251.64  5025.5  252.38  5035.8  251.31  5054.4  256.07  5125.1  260.15
  5195.1  260.72  5237.4  262.64  5259.4  265.31  5300.5  266.28  5351.9  269.27
  5434.1  275.51    5454  276.14  5464.9  278.01  5526.6  280.24  5580.2  280.71
#Mann= 1 ,-1 , 0
  4709.3     .05       0
Bank Sta=4984.4,5054.4
XS Rating Curve= 0 ,0
Exp/Cntr=0.3,0.1

Chan Stop Cuts=-1
Use User Specified Reach Order=0
Composite Channel Slope=5