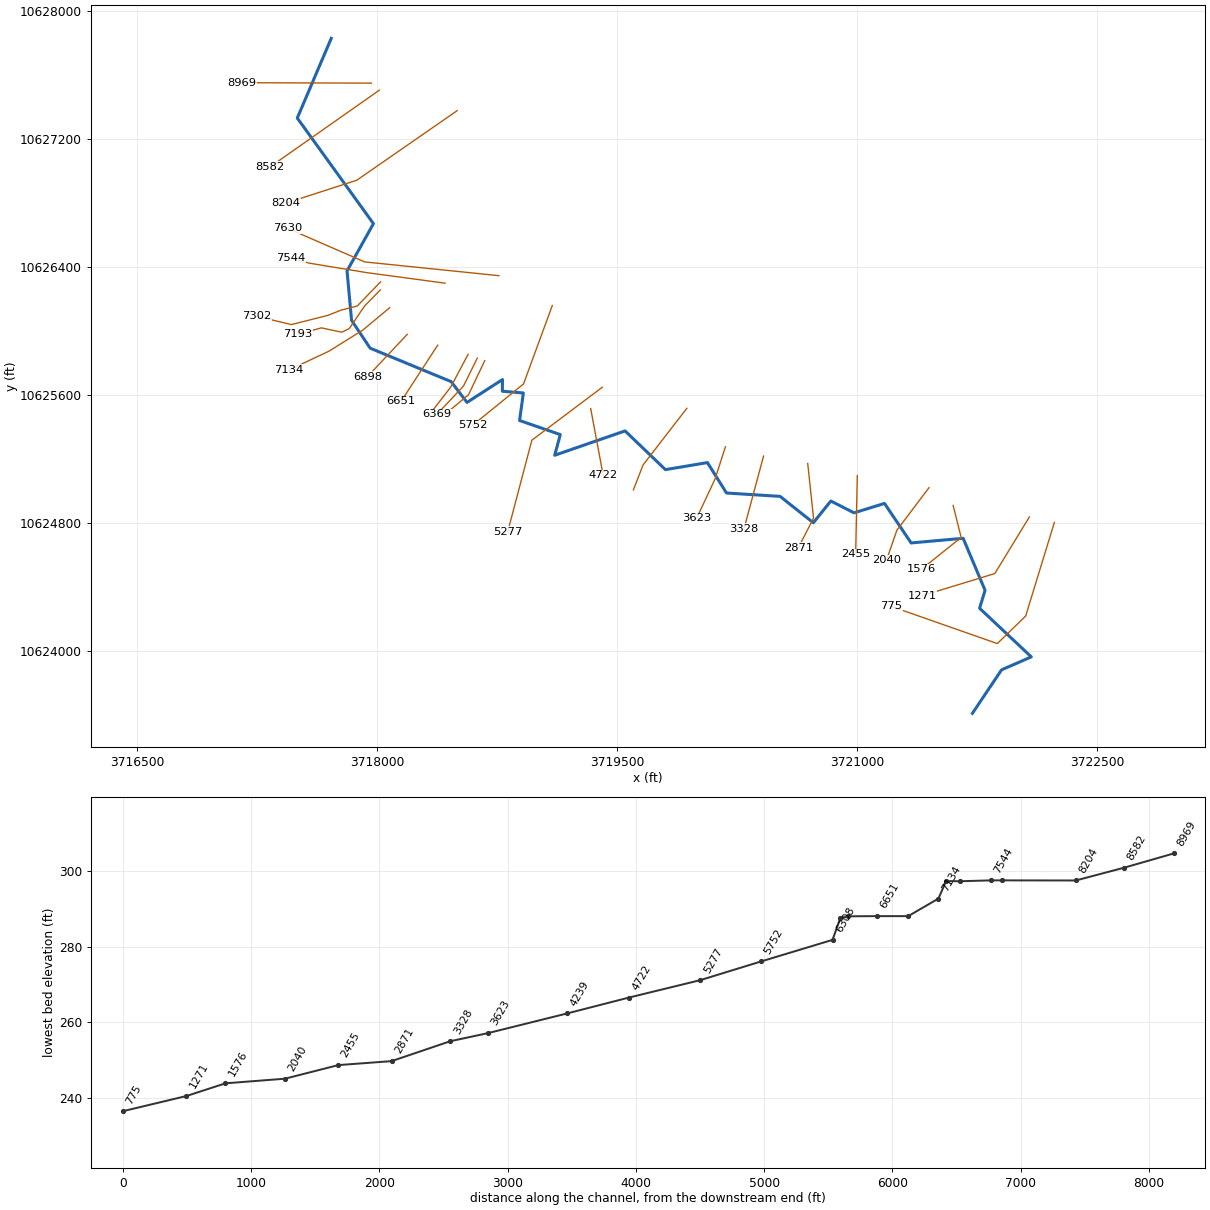
--- UNT 132 IN BOCR.prj (project) ---

Proj Title=UNT 132 IN BOCR Base Level Engineering
Current Plan=p01
Default Exp/Contr=0.3,0.1
English Units
Geom File=g01
Flow File=f01
Plan File=p01
Y Axis Title=Elevation
X Axis Title(PF)=Main Channel Distance
X Axis Title(XS)=Station
BEGIN DESCRIPTION:
UNT 132 IN BOCR
END DESCRIPTION:
DSS Export Rating Curves= 0
DSS Export Rating Curve Sorted= 0
DSS Export Volume Flow Curves= 0
DXF OffsetX= 0
DXF OffsetY= 0
DXF ScaleX= 1
DXF ScaleY= 10

--- UNT 132 IN BOCR.p01 (plan) ---

Plan Title=Multiple Run
Short Identifier=Multiple
Geom File=g01
Flow File=f01
Subcritical Flow
K Sum by GR= 0
Std Step Tol= 0.01
Critical Tol= 0.01
Num of Std Step Trials= 20
Max Error Tol= 0.3
Flow Tol Ratio= 0.001
Split Flow NTrial= 30
Split Flow Tol= 0.02
Split Flow Ratio= 0.02
Log Output Level= 0
Friction Slope Method= 1
Unsteady Friction Slope Method= 2
Unsteady Bridges Friction Slope Method= 1
Parabolic Critical Depth
Global Vel Dist=  1 , 1 , 1
Global Log Level= 0
CheckData=True
Encroach Param= -1, 0, 0, 0
BEGIN DESCRIPTION:
Multiple Run
END DESCRIPTION:

--- UNT 132 IN BOCR.f01 (steady flow) ---

Flow Title=Multiple
Number of Profiles=7
Profile Names=10-year,25-year,50-year,1pct_min,100-year,1pct_plu,500-year
River Rch & RM= UNT 132 IN BOCR,Reach-1,8969
     144     176     200     168     227     307     291
River Rch & RM= UNT 132 IN BOCR,Reach-1,4722
     321     415     489     424     574     776     792
Boundary for River Rch & Prof#=UNT 132 IN BOCR,Reach-1,1
Up Type=0
Dn Type=3
Dn Slope=0.005
Boundary for River Rch & Prof#=UNT 132 IN BOCR,Reach-1,2
Up Type=0
Dn Type=3
Dn Slope=0.005
Boundary for River Rch & Prof#=UNT 132 IN BOCR,Reach-1,3
Up Type=0
Dn Type=3
Dn Slope=0.005
Boundary for River Rch & Prof#=UNT 132 IN BOCR,Reach-1,4
Up Type=0
Dn Type=3
Dn Slope=0.005
Boundary for River Rch & Prof#=UNT 132 IN BOCR,Reach-1,5
Up Type=0
Dn Type=3
Dn Slope=0.005
Boundary for River Rch & Prof#=UNT 132 IN BOCR,Reach-1,6
Up Type=0
Dn Type=3
Dn Slope=0.005
Boundary for River Rch & Prof#=UNT 132 IN BOCR,Reach-1,7
Up Type=0
Dn Type=3
Dn Slope=0.005

--- UNT 132 IN BOCR.g01 (geometry) ---

Geom Title=Existing Conditions
Program Version=4.10

River Reach=UNT 132 IN BOCR ,Reach-1
Reach XY= 30
      3717713.04     10627829.13      3717500.75       10627331.
      3717976.75       10626671.      3717811.75       10626376.
        3717840.       10626067.      3717956.25       10625893.
      3718462.25       10625684.      3718561.25       10625554.
      3718783.25       10625697.      3718782.25       10625624.
       3718913.5       10625613.        3718890.       10625441.
       3719144.5       10625353.       3719109.5       10625224.
      3719549.25       10625376.       3719801.5       10625134.
        3720064.       10625178.      3720183.25       10624988.
        3720518.       10624967.      3720725.75       10624802.
      3720835.25       10624938.      3720980.25       10624864.
       3721170.5       10624923.        3721337.       10624676.
        3721662.       10624705.        3721799.       10624380.
      3721764.75       10624268.        3722088.       10623964.
        3721902.       10623883.      3721719.75       10623611.

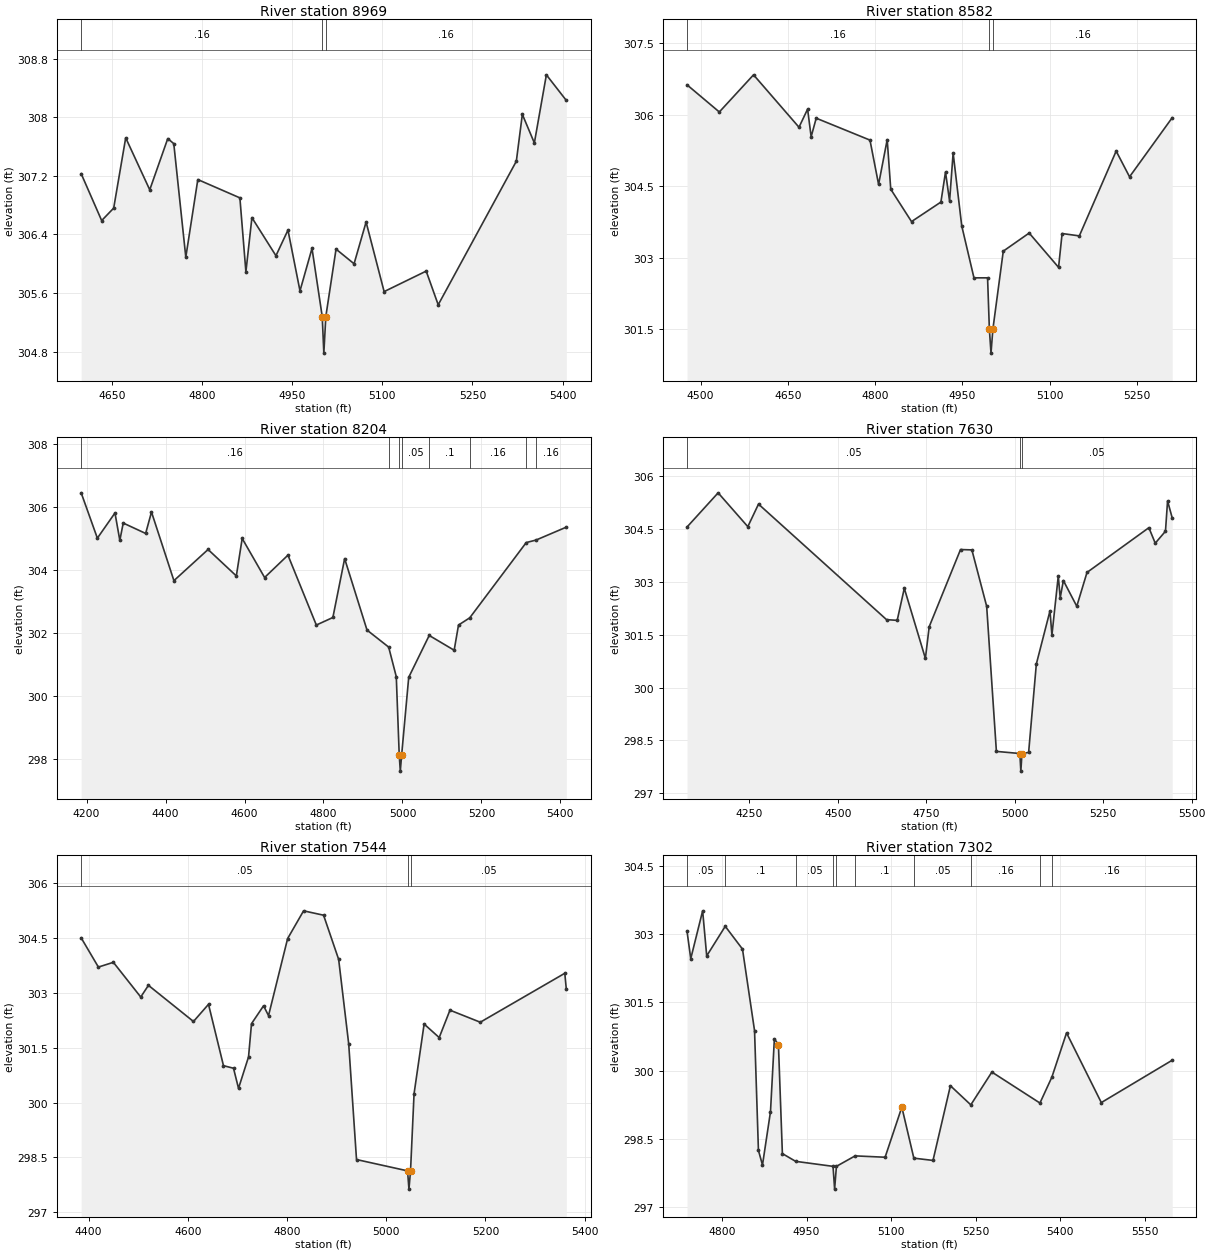
Type RM Length L Ch R = 1 ,8969    ,387,387,387
BEGIN DESCRIPTION:
UNT 132 IN BOCR 17.0
END DESCRIPTION:
XS GIS Cut Line= 2
      3717963.66     10627549.21      3717156.37     10627551.81
#Sta/Elev= 30
  4598.9  307.23    4633  306.59    4653  306.76    4673  307.72    4713  307.01
    4743  307.71    4753  307.64    4773  306.09    4793  307.15    4863   306.9
    4873  305.89    4883  306.63    4923  306.11    4943  306.46    4963  305.63
    4983  306.21    5000  305.28  5002.7  304.78    5006  305.28    5023   306.2
    5053     306    5073  306.57    5103  305.62    5173   305.9    5193  305.44
    5323   307.4    5333  308.04    5353  307.65    5373  308.58  5406.2  308.23
#Mann= 3 ,-1 , 0
  4598.9     .16       0    5000     .07       0    5006     .16       0
Bank Sta=5000,5006
XS Rating Curve= 0 ,0
Exp/Cntr=0.3,0.1

Type RM Length L Ch R = 1 ,8582    ,378,378,378
BEGIN DESCRIPTION:
UNT 132 IN BOCR 16.0
END DESCRIPTION:
XS GIS Cut Line= 2
      3718013.15     10627504.95      3717330.81     10627025.75
#Sta/Elev= 30
  4476.7  306.63  4532.2  306.06    4591  306.84  4669.1  305.74  4683.9  306.12
    4690  305.54  4698.7  305.93  4791.1  305.47  4805.9  304.54  4820.7  305.48
  4826.8  304.44  4862.5  303.76    4913  304.17  4920.9   304.8  4927.9  304.19
    4934   305.2  4948.8  303.67  4969.8  302.58  4993.2  302.58  4996.3   301.5
  4999.1     301  5002.3   301.5  5020.2  303.14  5064.7  303.52  5115.2   302.8
  5121.3  303.51  5150.9  303.46  5214.2  305.24  5237.2   304.7  5310.5  305.94
#Mann= 3 ,-1 , 0
  4476.7     .16       0  4996.3     .07       0  5002.3     .16       0
Bank Sta=4996.3,5002.3
XS Rating Curve= 0 ,0
Exp/Cntr=0.3,0.1

Type RM Length L Ch R = 1 ,8204    ,574,574,574
BEGIN DESCRIPTION:
UNT 132 IN BOCR 15.0
END DESCRIPTION:
XS GIS Cut Line= 3
      3718500.07      10627377.3      3717872.51     10626942.44
      3717429.81     10626799.21
#Sta/Elev= 30
  4186.3  306.44  4227.3     305  4271.9   305.8  4284.2  304.93  4292.8  305.48
  4349.6  305.15  4364.4  305.83  4421.2  303.65  4507.7  304.64  4579.3   303.8
  4594.1  304.99  4650.9  303.75    4710  304.46  4781.9  302.24  4823.8  302.48
  4853.6  304.35  4910.3  302.08  4965.1  301.54  4984.4   300.6  4991.9   298.1
  4994.6   297.6  4997.9   298.1  5015.9  300.58  5067.8  301.91    5131  301.44
    5142  302.24  5170.5  302.47  5313.5  304.86  5338.4  304.94  5415.1  305.35
#Mann= 8 ,-1 , 0
  4186.3     .16       0  4965.1     .05       0  4991.9     .03       0
  4997.9     .05       0  5067.8      .1       0  5170.5     .16       0
  5313.5     .05       0  5338.4     .16       0
Bank Sta=4991.9,4997.9
XS Rating Curve= 0 ,0
Exp/Cntr=0.3,0.1

Type RM Length L Ch R = 1 ,7630    ,86,86,86
BEGIN DESCRIPTION:
UNT 132 IN BOCR 14.0
END DESCRIPTION:
XS GIS Cut Line= 3
      3718760.56     10626346.08      3717921.99     10626432.02
      3717437.59     10626642.97
#Sta/Elev= 30
  4073.7  304.56  4161.6  305.53  4245.5  304.57  4275.7  305.21  4637.6  301.93
  4667.7  301.91  4687.8  302.82  4747.4  300.83  4758.2  301.73  4846.7  303.92
  4878.8  303.91  4920.6  302.31  4948.1  298.19  5014.4  298.13  5017.2  297.63
  5020.4  298.13  5039.2  298.16    5061  300.67  5099.6  302.18    5105  301.49
    5123  303.17  5128.5  302.55  5137.4  303.04  5175.3  302.31  5204.2  303.27
  5379.1  304.54  5397.1   304.1    5426  304.44  5431.9   305.3    5445  304.82
#Mann= 3 ,-1 , 0
  4073.7     .05       0  5014.4     .03       0  5020.4     .05       0
Bank Sta=5014.4,5020.4
XS Rating Curve= 0 ,0
Exp/Cntr=0.3,0.1

Type RM Length L Ch R = 1 ,7544    ,242,242,242
BEGIN DESCRIPTION:
Mapping XS b52482b5
END DESCRIPTION:
XS GIS Cut Line= 4
      3718423.97      10626299.2      3717934.35     10626365.17
      3717576.71      10626424.2      3717459.18     10626455.31
#Sta/Elev= 30
  4385.1  304.51  4419.8  303.71    4450  303.84  4505.2  302.89  4520.7  303.21
  4611.5  302.22  4641.8  302.69    4672  301.01  4692.2  300.94  4702.3  300.39
  4722.5  301.25  4728.5  302.16  4752.8  302.65  4762.8  302.38  4801.3  304.49
  4833.5  305.25  4873.8  305.13  4904.2  303.92  4924.5   301.6  4940.2  298.44
  5043.1  298.13  5045.9  297.63  5049.1  298.13  5056.2  300.24  5076.5  302.15
  5106.9  301.78  5128.6  302.53  5189.7   302.2  5360.1  303.54  5363.2   303.1
#Mann= 3 ,-1 , 0
  4385.1     .05       0  5043.1    .033       0  5049.1     .05       0
Bank Sta=5043.1,5049.1
XS Rating Curve= 0 ,0
Exp/Cntr=0.3,0.1

Type RM Length L Ch R = 1 ,7302    ,109,109,109
BEGIN DESCRIPTION:
Mapping XS 2750c89b
END DESCRIPTION:
XS GIS Cut Line= 6
      3718021.43     10626307.61      3717875.61     10626156.58
      3717774.63      10626130.8       3717691.3     10626097.81
      3717463.86     10626040.52      3717247.29     10626092.33
#Sta/Elev= 30
  4737.9  303.06  4744.5  302.46  4765.6  303.51  4772.8  302.52  4805.7  303.17
  4836.3  302.67  4857.7  300.88  4864.6  298.25  4871.8  297.93    4886   299.1
  4892.9   300.7  4900.1  300.57  4907.1  298.18  4930.6  298.01    4997   297.9
  4999.8   297.4    5003   297.9  5036.2  298.13  5089.4   298.1  5119.1   299.2
  5140.4  298.08  5174.4  298.03  5205.3  299.67  5241.5  299.25  5278.9  299.97
  5364.2  299.29  5385.4  299.86  5411.4  300.83  5473.1   299.3  5598.9  300.23
#Mann= 10 ,-1 , 0
  4737.9     .05       0  4805.7      .1       0  4930.6     .05       0
    4997    .033       0    5003     .05       0  5036.2      .1       0
  5140.4     .05       0  5241.5     .16       0  5364.2     .12       0
  5385.4     .16       0
Bank Sta=4900.1,5119.1
XS Rating Curve= 0 ,0
Exp/Cntr=0.3,0.1

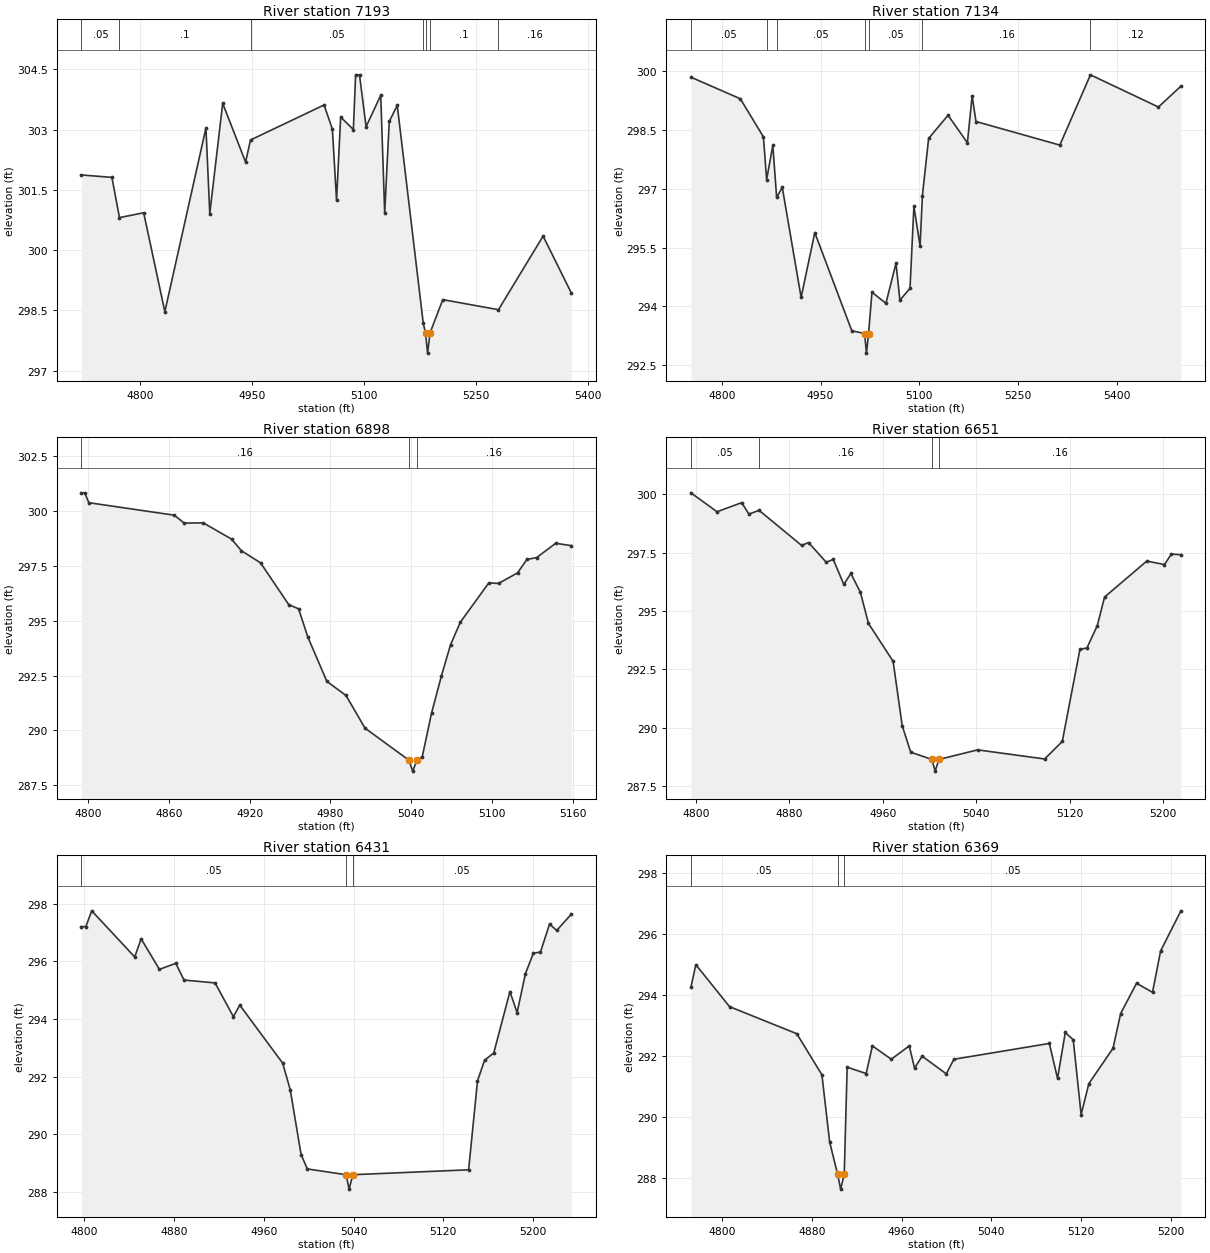
Type RM Length L Ch R = 1 ,7193    ,59,59,59
BEGIN DESCRIPTION:
Mapping XS b3d91360
END DESCRIPTION:
XS GIS Cut Line= 6
      3718020.08     10626257.55      3717921.32     10626156.63
      3717825.84     10626015.57      3717779.18     10625992.78
      3717651.14     10626019.91      3717503.03     10625979.12
#Sta/Elev= 30
  4721.9  301.87  4762.7  301.81  4772.8  300.81  4805.2  300.93  4833.5  298.47
  4888.5  303.04  4893.6  300.91  4910.9  303.65  4941.5  302.19  4948.1  302.74
  5046.5  303.61  5057.6  303.01  5063.2  301.24  5068.7  303.31  5085.7     303
  5088.7  304.36  5093.9  304.36  5102.7  303.07  5122.3  303.85  5127.6  300.92
  5133.7   303.2  5144.4   303.6  5179.2  298.18  5182.2  297.94    5185  297.44
  5188.2  297.94  5205.3  298.77  5279.8  298.52  5339.5  300.35  5377.4  298.93
#Mann= 7 ,-1 , 0
  4721.9     .05       0  4772.8      .1       0  4948.1     .05       0
  5179.2      .1       0  5182.2     .03       0  5188.2      .1       0
  5279.8     .16       0
Bank Sta=5182.2,5188.2
XS Rating Curve= 0 ,0
Exp/Cntr=0.3,0.1

Type RM Length L Ch R = 1 ,7134    ,236,236,236
BEGIN DESCRIPTION:
Mapping XS cfe653d0
END DESCRIPTION:
XS GIS Cut Line= 4
      3718078.73     10626146.17      3717909.46     10626005.54
      3717699.16     10625874.38      3717448.66     10625756.66
#Sta/Elev= 30
    4753  299.84  4828.1  299.29  4863.2  298.32  4868.1  297.23  4877.5   298.1
  4883.3  296.78  4891.9  297.03  4920.5  294.23  4941.3  295.88  4997.5  293.38
    5017  293.31  5019.8  292.81    5023  293.31  5028.2  294.36  5049.4  294.08
  5064.7   295.1  5070.6  294.16    5086  294.46  5091.9  296.55  5101.3  295.54
  5104.8  296.82  5114.3  298.28  5143.8  298.87  5173.2  298.17  5180.4  299.36
  5186.3  298.71  5313.7  298.11  5360.2   299.9  5463.5  299.08  5497.7  299.61
#Mann= 7 ,-1 , 0
    4753     .05       0  4868.1      .1       0  4883.3     .05       0
    5017     .03       0    5023     .05       0  5104.8     .16       0
  5360.2     .12       0
Bank Sta=5017,5023
XS Rating Curve= 0 ,0
Exp/Cntr=0.3,0.1

Type RM Length L Ch R = 1 ,6898    ,247,247,247
BEGIN DESCRIPTION:
Mapping XS 2c259332
END DESCRIPTION:
XS GIS Cut Line= 2
       3718188.1     10625979.49      3717938.69      10625714.5
#Sta/Elev= 30
  4795.1  300.83  4797.6  300.83  4800.6  300.38  4864.1  299.81  4871.4  299.45
  4885.6  299.46  4906.6  298.72  4913.9  298.19  4928.1  297.64  4949.1  295.73
  4956.4  295.54  4963.2  294.26  4977.4  292.23  4991.6  291.59  5005.7   290.1
  5038.3  288.64  5041.1  288.14  5044.3  288.64  5048.2  288.79  5055.1  290.78
  5062.4  292.47  5069.2   293.9  5076.5  294.93  5097.6  296.72  5104.9   296.7
    5119  297.18  5125.9  297.79  5133.2  297.88  5147.3  298.53    5159  298.42
#Mann= 3 ,-1 , 0
  4795.1     .16       0  5038.3     .07       0  5044.3     .16       0
Bank Sta=5038.3,5044.3
XS Rating Curve= 0 ,0
Exp/Cntr=0.3,0.1

Type RM Length L Ch R = 1 ,6651    ,220,220,220
BEGIN DESCRIPTION:
Mapping XS 211a8605
END DESCRIPTION:
XS GIS Cut Line= 2
      3718378.21     10625911.79      3718149.02     10625560.19
#Sta/Elev= 30
  4795.7  300.06  4818.1  299.25  4839.2  299.64  4845.4  299.15  4854.1  299.31
  4890.5  297.81  4896.5  297.93  4911.6  297.09  4917.6  297.21  4926.7  296.14
  4932.7  296.61  4940.9   295.8  4947.8  294.47  4968.9  292.85  4976.7  290.09
    4984  288.96  5002.1  288.65  5004.9  288.15  5008.1  288.65  5041.3  289.06
  5098.7  288.67  5113.8  289.42  5128.9  293.36  5134.9  293.42  5143.8  294.38
    5150   295.6  5186.2  297.14  5201.3  296.99  5207.3  297.44  5215.4  297.41
#Mann= 4 ,-1 , 0
  4795.7     .05       0  4854.1     .16       0  5002.1     .07       0
  5008.1     .16       0
Bank Sta=5002.1,5008.1
XS Rating Curve= 0 ,0
Exp/Cntr=0.3,0.1

Type RM Length L Ch R = 1 ,6431    ,62,62,62
BEGIN DESCRIPTION:
Mapping XS 75ba2298
END DESCRIPTION:
XS GIS Cut Line= 3
      3718568.31     10625854.48      3718458.94     10625648.77
      3718334.29     10625487.76
#Sta/Elev= 30
  4797.5   297.2  4801.4   297.2  4806.7  297.75    4845  296.15  4850.7  296.78
    4867  295.72  4881.6  295.93  4888.9  295.35  4916.6  295.25  4932.9  294.08
  4938.6  294.48  4976.8  292.47  4983.6  291.54  4993.2   289.3  4998.8   288.8
  5033.3   288.6    5036   288.1  5039.3   288.6  5142.5  288.77  5150.4  291.85
  5156.7  292.57  5164.9  292.82  5179.3  294.95  5185.7  294.22  5193.1  295.57
  5200.2  296.28  5206.5  296.32  5214.6  297.29    5221  297.07  5234.1  297.64
#Mann= 3 ,-1 , 0
  4797.5     .05       0  5033.3     .03       0  5039.3     .05       0
Bank Sta=5033.3,5039.3
XS Rating Curve= 0 ,0
Exp/Cntr=0.3,0.1

Type RM Length L Ch R = 1 ,6369    ,61,61,61
BEGIN DESCRIPTION:
UNT 132 IN BOCR 11.0
END DESCRIPTION:
XS GIS Cut Line= 3
      3718625.61     10625831.07      3718539.67     10625656.58
      3718373.82     10625480.36
#Sta/Elev= 30
  4772.3  294.25  4776.7     295  4806.7  293.62  4866.6  292.73    4889  291.38
  4895.9  289.17  4902.9  288.12  4905.7  287.62  4908.9  288.12  4911.5  291.63
  4928.4  291.42    4934  292.33  4950.8  291.89  4966.8  292.33  4971.5   291.6
  4978.3  291.99  4999.8  291.41  5006.6  291.89  5091.6  292.41  5098.9  291.26
  5105.8  292.77  5112.9  292.53  5119.9  290.07  5126.8  291.09  5148.3  292.25
  5155.1  293.39  5169.3  294.39  5183.5  294.09  5190.7  295.45  5208.8  296.77
#Mann= 3 ,-1 , 0
  4772.3     .05       0  4902.9     .03       0  4908.9     .05       0
Bank Sta=4902.9,4908.9
XS Rating Curve= 0 ,0
Exp/Cntr=0.3,0.1

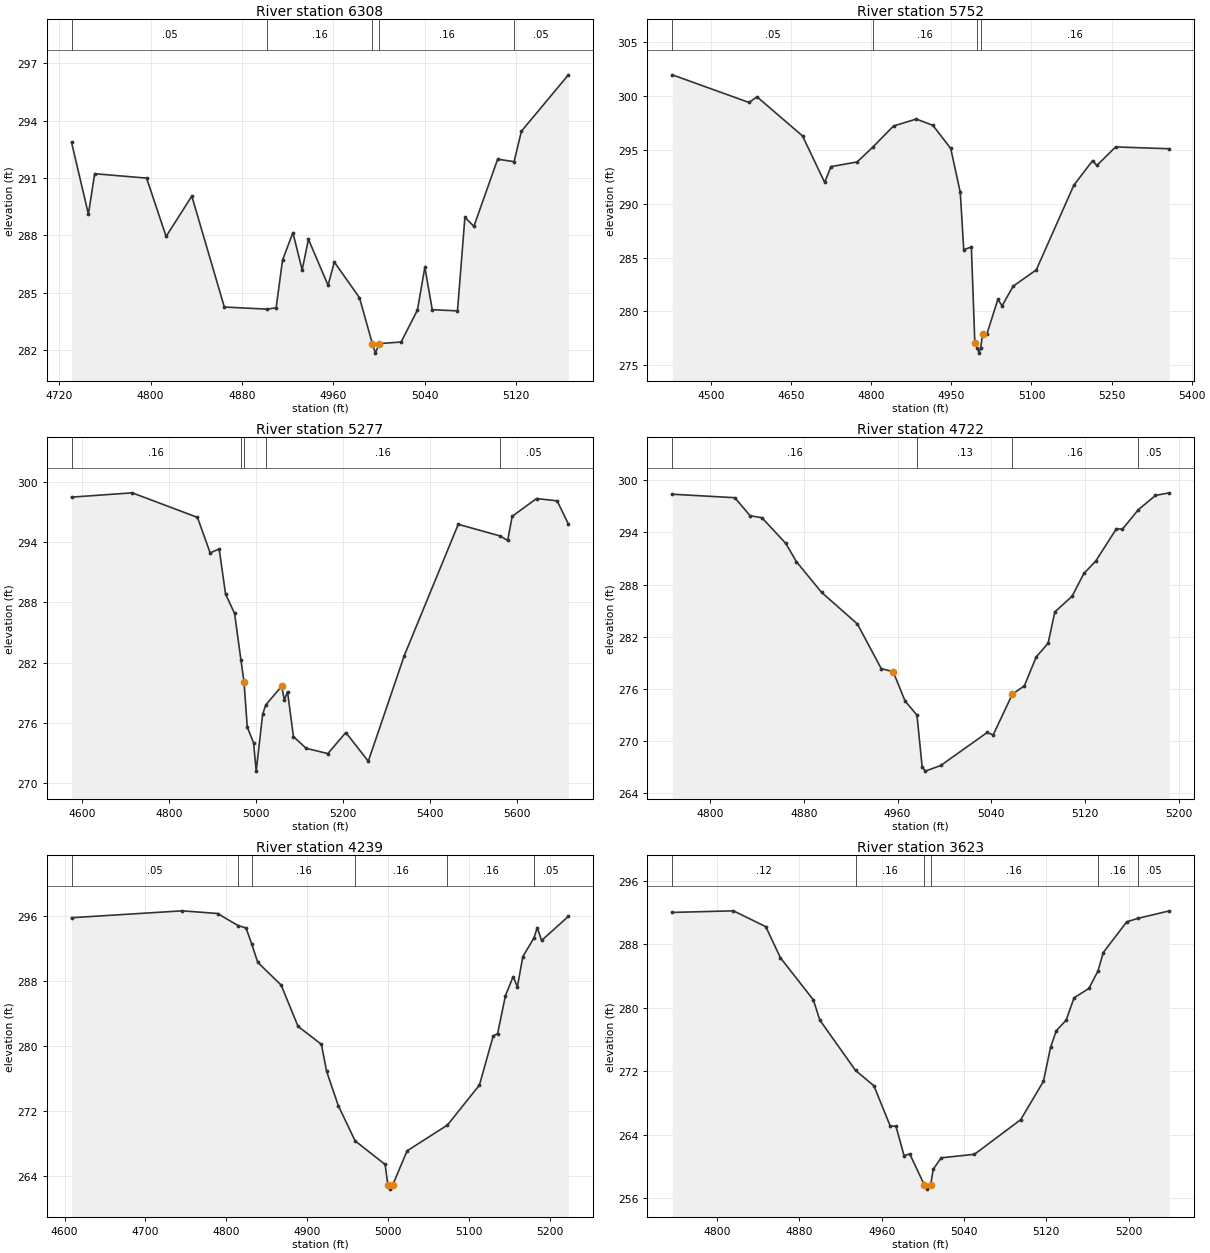
Type RM Length L Ch R = 1 ,6308    ,556,556,556
BEGIN DESCRIPTION:
Mapping XS e005f9ac
END DESCRIPTION:
XS GIS Cut Line= 3
      3718672.47      10625815.4      3718570.92     10625601.89
      3718417.85     10625474.77
#Sta/Elev= 30
  4730.7  292.88  4745.5  289.12    4751  291.23  4796.5     291  4813.6  287.95
  4836.1  290.06  4864.6  284.26  4902.2  284.15    4910  284.22  4915.6  286.71
  4924.7  288.15  4932.8   286.2  4938.3   287.8  4955.5   285.4    4961  286.61
    4983  284.75  4994.3  282.35    4997  281.85  5000.3  282.35  5019.5  282.43
  5033.8   284.1  5040.3  286.34  5046.8  284.12  5068.9  284.06  5075.4  288.95
  5083.3  288.48  5104.1  291.99  5118.5  291.86  5124.9  293.45  5166.1   296.4
#Mann= 5 ,-1 , 0
  4730.7     .05       0  4902.2     .16       0  4994.3     .07       0
  5000.3     .16       0  5118.5     .05       0
Bank Sta=4994.3,5000.3
XS Rating Curve= 0 ,0
Exp/Cntr=0.3,0.1

Type RM Length L Ch R = 1 ,5752    ,475,475,475
BEGIN DESCRIPTION:
UNT 132 IN BOCR 10.0
END DESCRIPTION:
XS GIS Cut Line= 3
      3719094.36     10626159.18      3718914.67      10625669.6
      3718596.94     10625411.77
#Sta/Elev= 30
  4427.2  301.93  4570.8  299.37  4585.9  299.89  4671.1  296.27  4712.6  291.96
  4724.4  293.42  4773.5  293.86  4802.6  295.22  4841.6  297.19  4884.2  297.83
  4915.3  297.25  4948.7  295.11  4966.6  291.04  4973.1  285.72  4987.4  285.98
  4993.9  277.05  4998.8  276.64  5001.6  276.14  5004.8  276.64  5008.3  277.89
  5016.2  277.87    5037  281.12  5044.9  280.53  5065.8  282.35  5108.9  283.85
  5179.3   291.7  5214.4  293.98  5222.4  293.53  5257.6  295.25  5357.9  295.08
#Mann= 4 ,-1 , 0
  4427.2     .05       0  4802.6     .16       0  4998.8     .07       0
  5004.8     .16       0
Bank Sta=4993.9,5008.3
XS Rating Curve= 0 ,0
Exp/Cntr=0.3,0.1

Type RM Length L Ch R = 1 ,5277    ,555,555,555
BEGIN DESCRIPTION:
UNT 132 IN BOCR 9.0
END DESCRIPTION:
XS GIS Cut Line= 3
      3719406.84     10625648.76      3718966.75     10625318.04
      3718815.71     10624745.12
#Sta/Elev= 30
  4576.4   298.5  4716.1  298.93  4866.1  296.48  4895.3  292.94  4916.1  293.33
  4930.7  288.84  4951.5   286.9  4966.1  282.26  4973.2  280.07  4980.7  275.56
  4995.2     274  5001.2  271.17  5016.1  276.85  5023.3  277.78  5059.8  279.64
    5066  278.27  5073.3  279.09  5086.9  274.62    5116  273.45    5166  272.92
  5207.4  275.02  5259.1  272.16  5341.9   282.7    5466  295.79  5562.1  294.63
  5579.7  294.18  5590.1  296.59  5646.1  298.36  5693.5  298.13  5719.4  295.81
#Mann= 5 ,-1 , 0
  4576.4     .16       0  4966.1     .13       0  4973.2     .13       0
  5023.3     .16       0  5562.1     .05       0
#Block Obstruct= 2 , 0
       0                    5060       0     278
Bank Sta=4973.2,5059.8
XS Rating Curve= 0 ,0
Exp/Cntr=0.3,0.1

Type RM Length L Ch R = 1 ,4722    ,483,483,483
BEGIN DESCRIPTION:
UNT 132 IN BOCR 8.0
END DESCRIPTION:
XS GIS Cut Line= 2
      3719334.35     10625515.41      3719412.49     10625098.68
#Sta/Elev= 30
  4767.8  298.38  4821.2  297.98  4834.2  295.91  4844.3  295.68  4864.7  292.72
  4873.7  290.63  4895.2   287.1  4925.7  283.48  4946.1  278.34  4956.3  277.98
  4966.4  274.63  4976.6  272.99    4981  267.06  4983.7  266.56  4996.9  267.21
  5036.5     271  5041.6  270.72    5058  275.41  5068.2  276.35  5078.3  279.67
  5088.5  281.26  5094.2  284.85  5108.9  286.65    5119  289.27  5129.2  290.71
  5146.8  294.42  5151.8  294.35  5165.5   296.6  5180.1  298.24  5191.8  298.54
#Mann= 4 ,-1 , 0
  4767.8     .16       0  4976.6     .13       0    5058     .16       0
  5165.5     .05       0
Bank Sta=4956.3,5058
XS Rating Curve= 0 ,0
Exp/Cntr=0.3,0.1

Type RM Length L Ch R = 1 ,4239    ,616,616,616
BEGIN DESCRIPTION:
UNT 132 IN BOCR 7.0
END DESCRIPTION:
XS GIS Cut Line= 3
      3719935.47     10625517.53      3719662.05     10625163.82
      3719601.29     10625007.58
#Sta/Elev= 30
  4608.6  295.83  4745.7  296.68  4789.2  296.35  4814.8  294.85  4824.5  294.57
  4831.6  292.57    4839  290.32    4868  287.51  4888.8  282.43  4917.8   280.2
  4924.1   276.9  4938.6  272.65  4959.4   268.3  4996.6  265.38  4999.9  262.84
  5002.7  262.34  5005.9  262.84  5023.7  267.06  5073.7  270.25  5113.2  275.18
  5130.3  281.25  5135.7  281.53  5145.4  286.21  5154.9  288.56  5160.2  287.31
  5166.9  291.03  5180.6  293.32  5184.8   294.6  5190.1  293.02  5223.3     296
#Mann= 6 ,-1 , 0
  4608.6     .05       0  4814.8     .12       0  4831.6     .16       0
  4959.4     .16       0  5073.7     .16       0  5180.6     .05       0
Bank Sta=4999.9,5005.9
XS Rating Curve= 0 ,0
Exp/Cntr=0.3,0.1

Type RM Length L Ch R = 1 ,3623    ,295,295,295
BEGIN DESCRIPTION:
UNT 132 IN BOCR 6.0
END DESCRIPTION:
XS GIS Cut Line= 3
      3720176.39     10625276.71      3720111.27     10625074.84
      3719996.24     10624829.58
#Sta/Elev= 30
  4756.4  292.02  4815.8  292.22  4847.3  290.22  4861.5   286.3  4893.5     281
  4899.8  278.45  4934.5   272.1  4952.4  270.16  4968.3  265.07  4973.8  265.07
  4981.7  261.34  4987.2  261.57  5001.5  257.63  5004.3  257.13  5007.5  257.63
    5010  259.63  5017.8  261.08  5050.1  261.52  5095.1  265.89  5117.2  270.73
  5124.1  275.02  5129.6  277.09  5139.3  278.45  5146.9  281.25  5161.4  282.44
  5170.2  284.64  5175.3  286.96  5198.1  290.83    5209  291.27  5239.4  292.21
#Mann= 6 ,-1 , 0
  4756.4     .12       0  4934.5     .16       0  5001.5     .07       0
  5007.5     .16       0  5170.2     .16       0    5209     .05       0
Bank Sta=5001.5,5007.5
XS Rating Curve= 0 ,0
Exp/Cntr=0.3,0.1

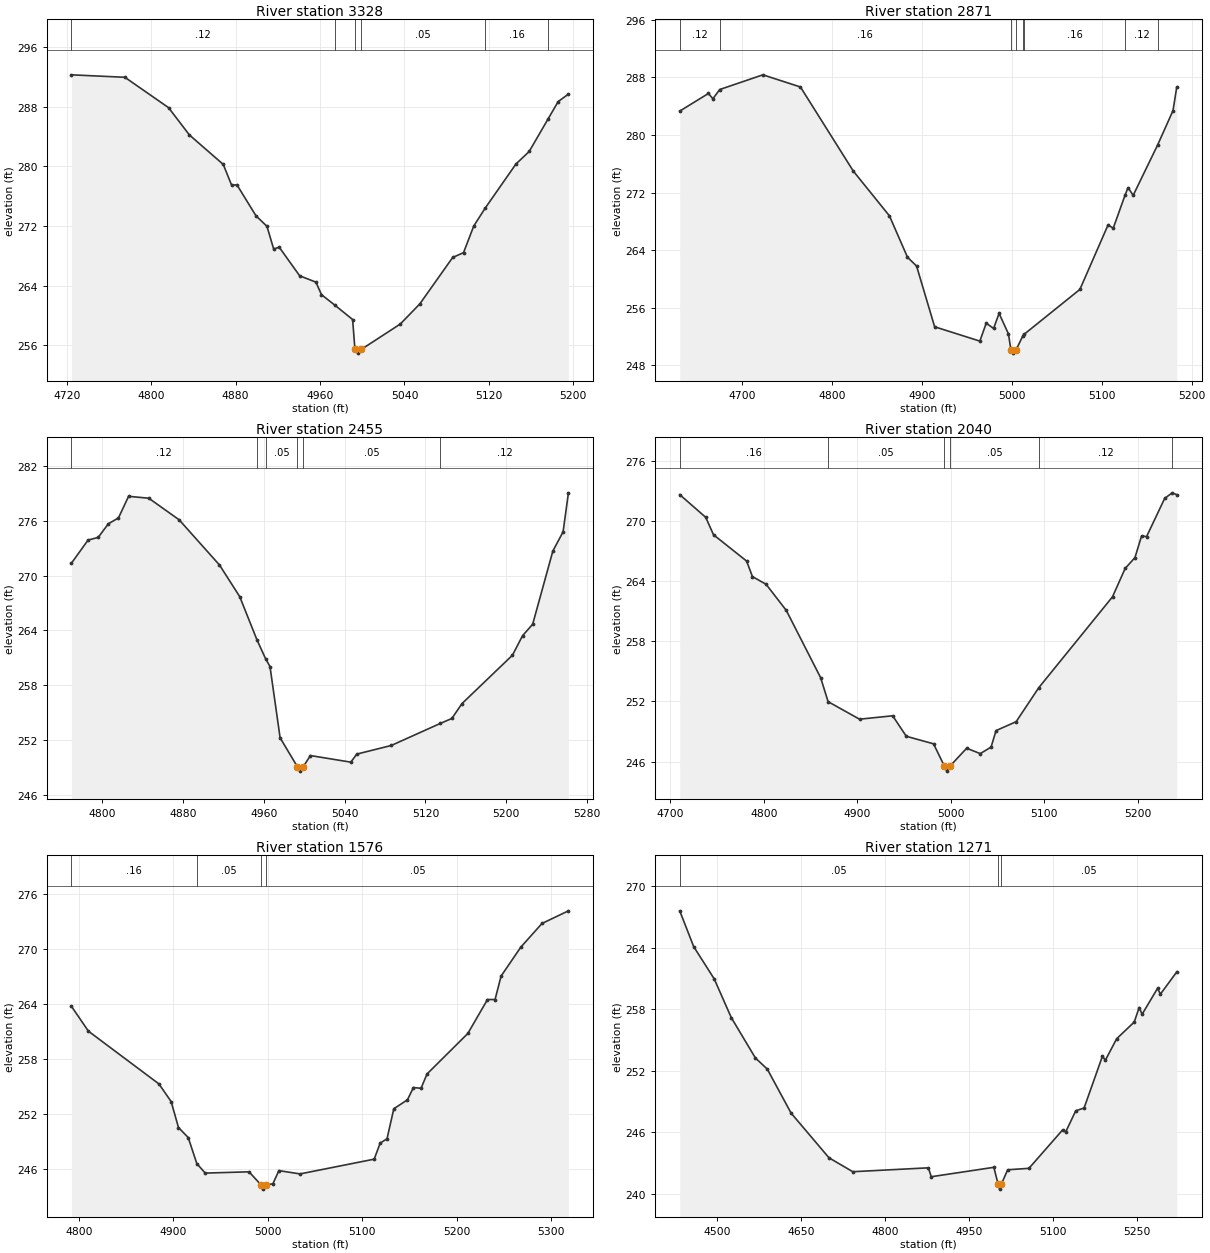
Type RM Length L Ch R = 1 ,3328    ,457,457,457
BEGIN DESCRIPTION:
Mapping XS a5452928
END DESCRIPTION:
XS GIS Cut Line= 2
      3720414.68     10625219.12      3720292.51     10624764.24
#Sta/Elev= 30
  4724.4  292.25  4775.1  291.92  4816.5  287.85  4836.2   284.2  4868.3  280.25
  4876.2  277.48  4881.3  277.51  4899.3  273.37  4909.7  271.96  4916.1  268.91
  4921.3  269.17  4940.7  265.33  4956.1  264.48  4961.4   262.8  4974.4  261.36
  4990.9  259.47  4993.1  255.47  4995.9  254.97  4999.1  255.47  5036.1  258.87
  5054.6  261.57  5085.7  267.78    5096  268.43  5105.7     272  5116.4  274.37
  5145.7  280.31  5158.2  281.98  5175.9  286.29  5185.7  288.67  5195.4  289.67
#Mann= 6 ,-1 , 0
  4724.4     .12       0  4974.4     .05       0  4993.1     .03       0
  4999.1     .05       0  5116.4     .16       0  5175.9     .05       0
Bank Sta=4993.1,4999.1
XS Rating Curve= 0 ,0
Exp/Cntr=0.3,0.1

Type RM Length L Ch R = 1 ,2871    ,416,416,416
BEGIN DESCRIPTION:
Mapping XS 8fb83208
END DESCRIPTION:
XS GIS Cut Line= 3
      3720690.71     10625172.19      3720727.17     10624831.06
      3720631.22     10624644.34
#Sta/Elev= 30
  4630.4  283.32  4662.3  285.77  4667.3  285.04  4674.9  286.32  4722.9  288.36
  4764.7  286.67  4823.5  274.99  4863.7  268.77  4883.8  263.02  4893.9   261.8
    4914  253.36  4964.3  251.37  4971.4  253.86  4979.6  253.13  4985.7  255.22
  4996.1  252.38  4998.8   250.2  5001.5   249.7  5004.8   250.2  5011.9  252.04
  5013.6  252.32  5075.6  258.55    5107  267.52  5112.7  267.05  5126.1  271.73
  5129.2  272.69  5134.9  271.62    5162  278.59  5179.2  283.39  5183.4  286.68
#Mann= 8 ,-1 , 0
  4630.4     .12       0  4674.9     .16       0  4998.8     .07       0
  5004.8     .16       0  5011.9     .05       0  5013.6     .16       0
  5126.1     .12       0    5162     .05       0
Bank Sta=4998.8,5004.8
XS Rating Curve= 0 ,0
Exp/Cntr=0.3,0.1

Type RM Length L Ch R = 1 ,2455    ,415,415,415
BEGIN DESCRIPTION:
Mapping XS 03434592
END DESCRIPTION:
XS GIS Cut Line= 2
      3721000.61     10625096.73       3720990.2     10624604.84
#Sta/Elev= 30
  4769.5  271.34    4786  273.87    4796  274.16  4806.1  275.65  4816.1  276.29
  4826.1  278.65  4846.1  278.44  4876.1  276.09  4916.1  271.15  4936.1   267.7
  4953.1     263  4961.7  260.92  4966.1  260.06  4976.1  252.28  4993.1  249.14
  4995.8  248.64  4999.1  249.14  5006.1  250.34  5046.1  249.62    5052   250.5
  5086.1  251.44  5134.7  253.85  5146.1  254.39  5156.1  256.01  5206.1   261.3
  5216.1  263.43  5226.1  264.68  5246.1  272.68  5256.2  274.77  5261.5  279.03
#Mann= 6 ,-1 , 0
  4769.5     .12       0  4953.1     .16       0  4961.7     .05       0
  4993.1     .03       0  4999.1     .05       0  5134.7     .12       0
Bank Sta=4993.1,4999.1
XS Rating Curve= 0 ,0
Exp/Cntr=0.3,0.1

Type RM Length L Ch R = 1 ,2040    ,464,464,464
BEGIN DESCRIPTION:
Mapping XS 9c76b651
END DESCRIPTION:
XS GIS Cut Line= 3
       3721448.5     10625021.13        3721248.     10624755.54
      3721182.88       10624568.
#Sta/Elev= 30
  4710.2  272.67    4738   270.4  4746.3  268.66  4781.7  266.03  4787.9  264.48
  4802.5  263.71  4824.1   261.1  4860.8  254.38  4868.8  251.98  4902.4  250.23
  4937.8  250.57  4952.4  248.52  4981.5  247.77  4993.1  245.54  4995.8  245.04
  4999.1  245.54  5016.9  247.33  5031.4  246.79    5043  247.44  5048.3  249.09
  5069.8  249.98    5094  253.38  5172.8  262.46  5186.3  265.29  5196.8  266.38
  5203.9  268.55  5209.2  268.47  5228.6   272.3  5236.7  272.85  5241.5  272.66
#Mann= 6 ,-1 , 0
  4710.2     .16       0  4868.8     .05       0  4993.1     .03       0
  4999.1     .05       0    5094     .12       0  5236.7     .05       0
Bank Sta=4993.1,4999.1
XS Rating Curve= 0 ,0
Exp/Cntr=0.3,0.1

Type RM Length L Ch R = 1 ,1576    ,305,305,305
BEGIN DESCRIPTION:
UNT 132 IN BOCR 2.0
END DESCRIPTION:
XS GIS Cut Line= 3
      3721599.62     10624910.16      3721649.61     10624710.19
      3721399.59     10624510.18
#Sta/Elev= 30
    4792  263.77    4810  261.05  4884.7  255.29  4897.6  253.37  4905.4  250.53
  4915.7  249.44  4924.8   246.6  4933.7  245.56  4980.1   245.7  4992.5  244.31
  4995.3  243.81  4998.5  244.31  5005.3  244.38  5011.7  245.83  5034.1  245.47
  5112.6  247.08    5119  248.84  5126.2   249.3  5133.4  252.58  5147.8  253.55
  5154.2   254.9  5162.2  254.81  5168.6  256.38  5211.8   260.8  5232.6   264.5
  5240.6   264.5    5247  267.06  5267.9  270.22  5290.3   272.8  5318.3  274.18
#Mann= 4 ,-1 , 0
    4792     .16       0  4924.8     .05       0  4992.5     .03       0
  4998.5     .05       0
Bank Sta=4992.5,4998.5
XS Rating Curve= 0 ,0
Exp/Cntr=0.3,0.1

Type RM Length L Ch R = 1 ,1271    ,496,496,496
BEGIN DESCRIPTION:
Mapping XS afcdecc1
END DESCRIPTION:
XS GIS Cut Line= 3
       3722076.1     10624838.83      3721859.98      10624484.7
      3721406.81     10624346.67
#Sta/Elev= 30
  4432.7  267.61  4457.6  264.12  4494.4  260.96  4524.8  257.19  4567.9  253.25
  4589.2  252.16  4631.8  247.86  4699.5   243.5  4742.1  242.14  4877.2  242.52
  4882.4  241.65  4994.3  242.57  5001.8  240.94  5004.5  240.44  5007.8  240.94
    5019  242.33    5057  242.47  5117.5  246.24  5122.7  246.02  5140.7  248.09
  5155.6  248.36  5188.4  253.42  5193.6  253.02  5213.8  255.12  5245.2  256.75
  5254.1  258.17  5259.3  257.51  5286.9  260.04  5292.1  259.48  5321.3  261.65
#Mann= 3 ,-1 , 0
  4432.7     .05       0  5001.8     .03       0  5007.8     .05       0
Bank Sta=5001.8,5007.8
XS Rating Curve= 0 ,0
Exp/Cntr=0.3,0.1

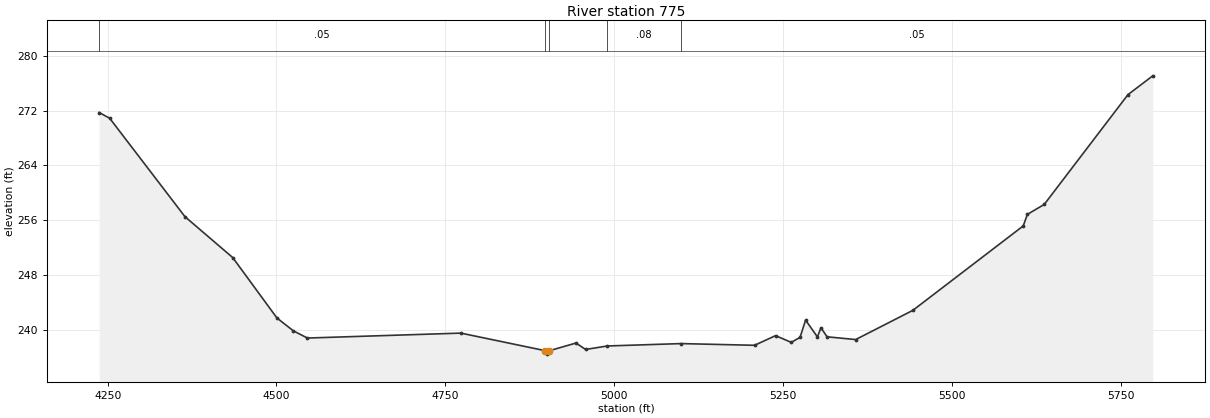
Type RM Length L Ch R = 1 ,775     ,0,0,0
BEGIN DESCRIPTION:
UNT 132 IN BOCR 1.0
END DESCRIPTION:
XS GIS Cut Line= 4
      3722232.36     10624804.97      3722052.69     10624219.08
      3721875.61      10624047.2      3721214.42     10624278.88
#Sta/Elev= 30
  4237.5  271.71    4253  270.87  4364.5  256.49  4435.2  250.52  4500.7  241.69
  4524.9  239.82  4545.8  238.76  4773.1  239.48  4898.2  236.91  4900.9  236.41
  4904.2  236.91  4943.6  238.03  4957.8  237.09  4989.8   237.6  5099.4  237.95
    5208   237.7  5239.1  239.11  5262.4  238.13  5275.4  238.86  5283.6  241.38
  5301.1  238.93  5306.4  240.26  5315.4  238.94  5357.8  238.54  5442.5  242.81
  5605.9  255.14  5612.1  256.83    5637  258.28    5761  274.32  5797.7  277.07
#Mann= 5 ,-1 , 0
  4237.5     .05       0  4898.2     .07       0  4904.2     .05       0
  4989.8     .08       0  5099.4     .05       0
Bank Sta=4898.2,4904.2
XS Rating Curve= 0 ,0
Exp/Cntr=0.3,0.1

Chan Stop Cuts=-1
Use User Specified Reach Order=0
Composite Channel Slope=5