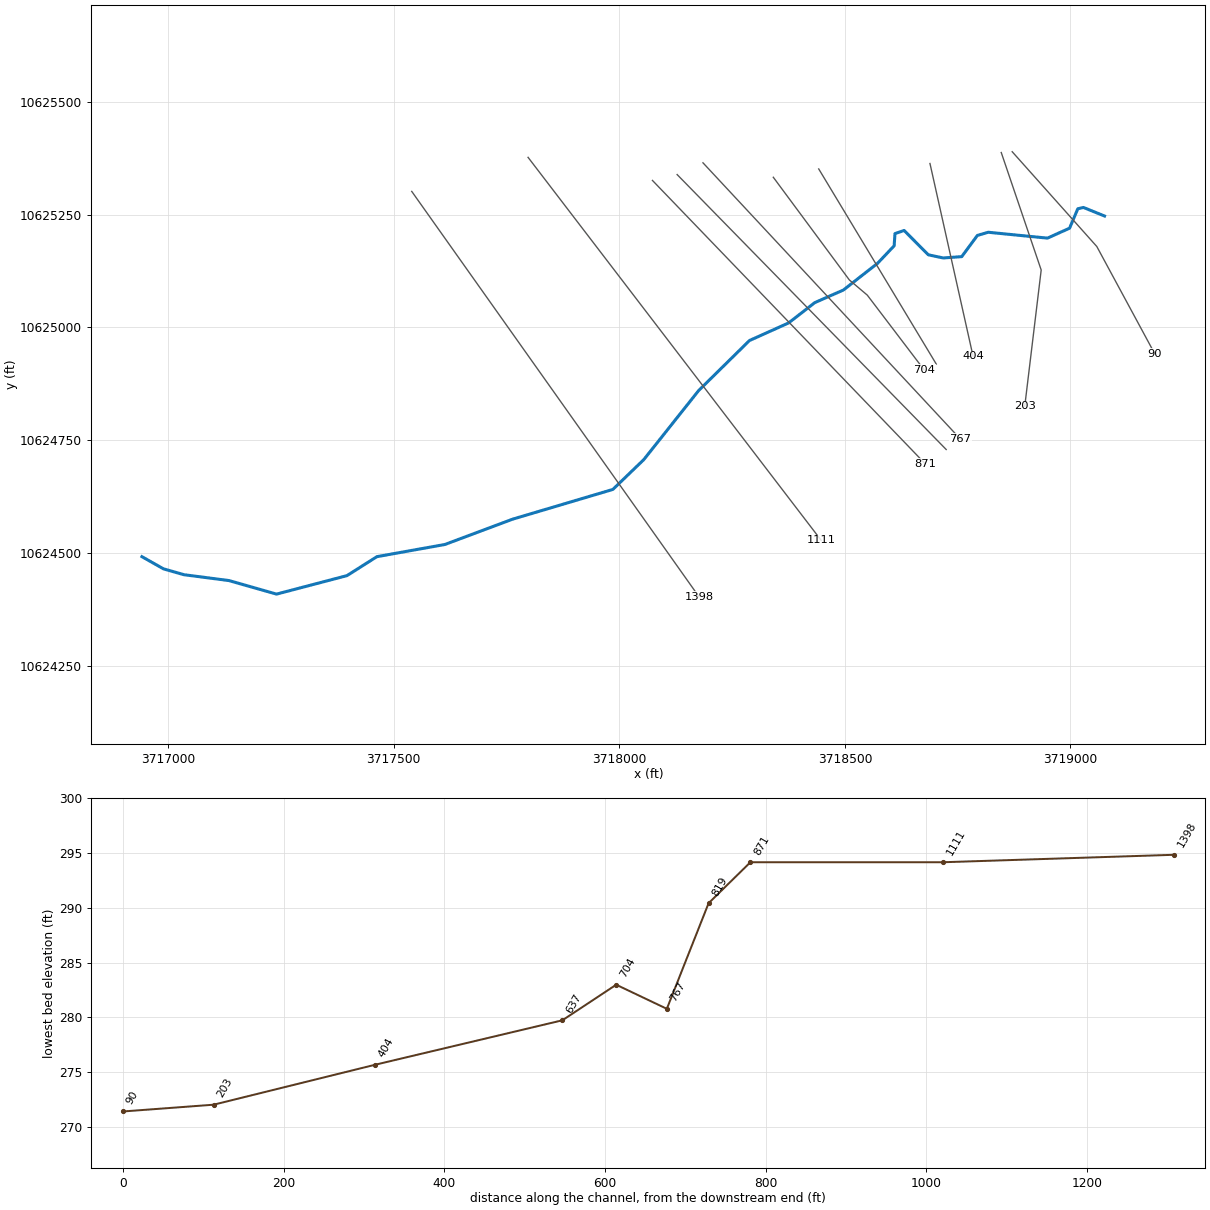
--- UNT 133 IN BOCR.prj (project) ---

Proj Title=UNT 133 IN BOCR Base Level Engineering
Current Plan=p01
Default Exp/Contr=0.3,0.1
English Units
Geom File=g01
Flow File=f01
Plan File=p01
Y Axis Title=Elevation
X Axis Title(PF)=Main Channel Distance
X Axis Title(XS)=Station
BEGIN DESCRIPTION:
UNT 133 IN BOCR
END DESCRIPTION:
DSS Export Rating Curves= 0
DSS Export Rating Curve Sorted= 0
DSS Export Volume Flow Curves= 0
DXF OffsetX= 0
DXF OffsetY= 0
DXF ScaleX= 1
DXF ScaleY= 10

--- UNT 133 IN BOCR.p01 (plan) ---

Plan Title=Multiple Run
Short Identifier=Multiple
Geom File=g01
Flow File=f01
Subcritical Flow
K Sum by GR= 0
Std Step Tol= 0.01
Critical Tol= 0.01
Num of Std Step Trials= 20
Max Error Tol= 0.3
Flow Tol Ratio= 0.001
Split Flow NTrial= 30
Split Flow Tol= 0.02
Split Flow Ratio= 0.02
Log Output Level= 0
Friction Slope Method= 1
Unsteady Friction Slope Method= 2
Unsteady Bridges Friction Slope Method= 1
Parabolic Critical Depth
Global Vel Dist=  1 , 1 , 1
Global Log Level= 0
CheckData=True
Encroach Param= -1, 0, 0, 0
BEGIN DESCRIPTION:
Multiple Run
END DESCRIPTION:

--- UNT 133 IN BOCR.f01 (steady flow) ---

Flow Title=Multiple
Program Version=4.10
Number of Profiles= 7
Profile Names=10-year,25-year,50-year,1pct_min,100-year,1pct_plu,500-year
River Rch & RM=UNT 133 IN BOCR,Reach-1         ,1398
      94     112     124     102     138     187     171
Boundary for River Rch & Prof#=UNT 133 IN BOCR,Reach-1         , 1
Up Type= 0
Dn Type= 3
Dn Slope=0.0116
Boundary for River Rch & Prof#=UNT 133 IN BOCR,Reach-1         , 2
Up Type= 0
Dn Type= 3
Dn Slope=0.0116
Boundary for River Rch & Prof#=UNT 133 IN BOCR,Reach-1         , 3
Up Type= 0
Dn Type= 3
Dn Slope=0.0116
Boundary for River Rch & Prof#=UNT 133 IN BOCR,Reach-1         , 4
Up Type= 0
Dn Type= 3
Dn Slope=0.0116
Boundary for River Rch & Prof#=UNT 133 IN BOCR,Reach-1         , 5
Up Type= 0
Dn Type= 3
Dn Slope=0.0116
Boundary for River Rch & Prof#=UNT 133 IN BOCR,Reach-1         , 6
Up Type= 0
Dn Type= 3
Dn Slope=0.0116
Boundary for River Rch & Prof#=UNT 133 IN BOCR,Reach-1         , 7
Up Type= 0
Dn Type= 3
Dn Slope=0.0116
DSS Import GetInterval= 0
DSS Import GetPeak= 0
DSS Import FillOption= 0

--- UNT 133 IN BOCR.g01 (geometry) ---

Geom Title=Existing Conditions
Program Version=4.10

River Reach=UNT 133 IN BOCR ,Reach-1
Reach XY= 30
        3716942.       10624492.      3716989.75       10624465.
      3717035.25       10624452.        3717135.       10624439.
      3717240.25       10624409.       3717396.5       10624450.
      3717462.75       10624492.       3717613.5       10624519.
      3717763.25       10624575.      3717985.75       10624641.
      3718054.25       10624707.      3718175.75       10624860.
       3718288.5       10624971.      3718375.25       10625010.
      3718433.25       10625055.      3718496.75       10625083.
      3718572.25       10625142.      3718609.25       10625181.
        3718611.       10625208.      3718631.25       10625215.
        3718685.       10625161.      3718718.25       10625154.
        3718759.       10625157.      3718793.75       10625204.
      3718817.75       10625211.        3718949.       10625198.
        3718998.       10625220.      3719016.25       10625263.
      3719028.75       10625266.       3719075.5       10625247.

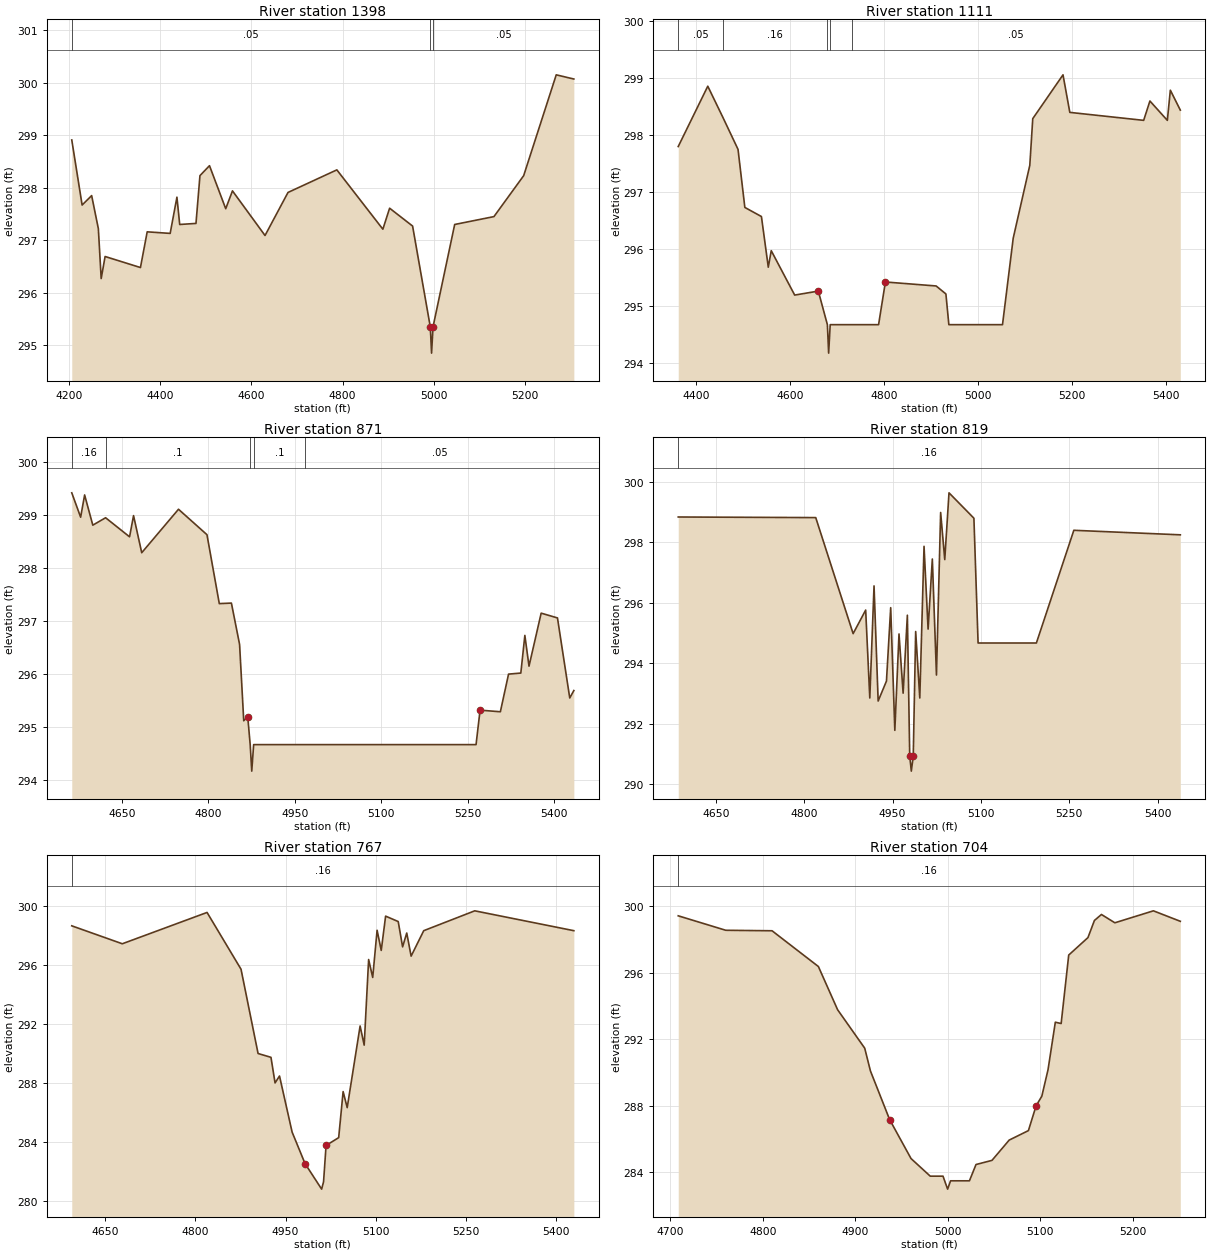
Type RM Length L Ch R = 1 ,1398    ,287,287,287
BEGIN DESCRIPTION:
UNT 133 IN BOCR 2.0
END DESCRIPTION:
XS GIS Cut Line= 2
        3717540.     10625301.54       3718176.6     10624403.24
#Sta/Elev= 30
  4206.1  298.91  4228.8  297.67  4249.7  297.85  4264.4  297.22  4270.6  296.27
  4279.2  296.69  4356.7  296.48  4371.5  297.16  4421.9  297.13  4436.7  297.82
  4442.8   297.3  4478.5  297.32  4487.2  298.23  4508.1  298.42  4543.7   297.6
  4558.5  297.94  4629.9  297.09  4680.3  297.91  4787.4  298.34  4888.3  297.21
  4903.1  297.61  4953.5  297.27  4992.3  295.35  4995.1  294.85  4998.3  295.35
  5045.8   297.3  5131.9  297.45  5197.1  298.23  5268.5  300.15  5307.1  300.07
#Mann= 3 ,-1 , 0
  4206.1     .05       0  4992.3     .03       0  4998.3     .05       0
Bank Sta=4992.3,4998.3
XS Rating Curve= 0 ,0
Exp/Cntr=0.3,0.1

Type RM Length L Ch R = 1 ,1111    ,240,240,240
BEGIN DESCRIPTION:
Mapping XS ceb3e41b
END DESCRIPTION:
XS GIS Cut Line= 2
      3717797.83     10625377.03      3718447.41     10624528.27
#Sta/Elev= 30
  4361.5   297.8  4424.4  298.86  4456.7  298.31  4488.8  297.75  4503.3  296.73
  4538.6  296.57  4553.2  295.68  4559.5  295.97  4609.4  295.19  4659.7  295.26
    4679  294.67  4681.7  294.17    4685  294.67  4730.6  294.67    4788  294.67
  4802.5  295.42  4910.5  295.35  4931.3  295.21  4937.6  294.67  5051.8  294.67
  5074.6  296.19  5109.9  297.47  5116.2  298.29  5180.6  299.06  5195.1   298.4
  5352.3  298.26  5365.6   298.6  5402.7  298.26  5409.1  298.79  5430.3  298.44
#Mann= 5 ,-1 , 0
  4361.5     .05       0  4456.7     .16       0    4679    .033       0
    4685     .16       0  4730.6     .05       0
Bank Sta=4659.7,4802.5
XS Rating Curve= 0 ,0
Exp/Cntr=0.3,0.1

Type RM Length L Ch R = 1 ,871     ,52,52,52
BEGIN DESCRIPTION:
Mapping XS 6a851eba
END DESCRIPTION:
XS GIS Cut Line= 2
      3718073.51     10625325.86      3718677.71     10624698.22
#Sta/Elev= 30
    4563  299.42  4578.4  298.96  4585.3  299.38  4599.5  298.81  4621.7  298.95
  4663.3  298.59  4670.2  298.99  4684.4  298.29  4748.2  299.11  4797.6  298.63
    4819  297.33    4840  297.34  4854.2  296.56  4861.4  295.12  4868.3   295.2
  4872.6  294.67  4875.3  294.17  4878.6  294.67  4968.3  294.67  5264.5  294.67
  5271.5  295.32  5306.7  295.29  5320.9     296  5342.2  296.02  5349.2  296.73
  5356.4  296.15  5377.5  297.15  5405.8  297.06  5427.1  295.55  5434.2  295.69
#Mann= 5 ,-1 , 0
    4563     .16       0  4621.7      .1       0  4872.6    .033       0
  4878.6      .1       0  4968.3     .05       0
Bank Sta=4868.3,5271.5
XS Rating Curve= 0 ,0
Exp/Cntr=0.3,0.1

Type RM Length L Ch R = 1 ,819     ,52,52,52
BEGIN DESCRIPTION:
Mapping XS f2f72d6e
END DESCRIPTION:
XS GIS Cut Line= 2
      3718128.21     10625338.88      3718724.54     10624729.52
#Sta/Elev= 30
    4586  298.84  4819.5  298.82    4883  294.98  4904.3  295.76  4911.3  292.85
  4918.5  296.56  4925.5  292.75  4939.6  293.41  4946.8  295.84  4953.8  291.78
  4960.9  294.97  4967.9  293.01  4975.1  295.59  4979.1  290.93  4981.8  290.43
  4985.1  290.93  4989.2  295.05  4996.2  292.85  5003.4  297.87  5010.3  295.13
  5017.5  297.45  5024.5  293.61  5031.6  298.99  5038.6  297.43  5045.8  299.64
  5088.1   298.8  5095.2  294.67  5194.2  294.67  5257.8   298.4  5438.6  298.25
#Mann= 1 ,-1 , 0
    4586     .16       0
Bank Sta=4979.1,4985.1
XS Rating Curve= 0 ,0
Exp/Cntr=0.3,0.1

Type RM Length L Ch R = 1 ,767     ,63,63,63
BEGIN DESCRIPTION:
Mapping XS 004ab141
END DESCRIPTION:
XS GIS Cut Line= 2
      3718185.49     10625364.92      3718755.78     10624752.96
#Sta/Elev= 30
  4593.9  298.68  4678.1  297.46  4819.3  299.59  4875.9  295.73  4904.3     290
  4925.8  289.74  4932.6     288    4940  288.47    4961  284.66  4982.5  282.52
  5010.2  280.78  5013.4  281.28  5017.6  283.75  5038.6  284.28    5046  287.41
  5052.8  286.32  5074.3  291.87  5081.1  290.57  5088.5  296.39  5095.3  295.17
  5102.6  298.38  5109.5  297.01  5116.8  299.34  5137.8  298.97  5145.1  297.25
    5152  298.19  5159.3  296.62  5180.3  298.35  5265.3   299.7  5430.4  298.35
#Mann= 1 ,-1 , 0
  4593.9     .16       0
Bank Sta=4982.5,5017.6
XS Rating Curve= 0 ,0
Exp/Cntr=0.3,0.1

Type RM Length L Ch R = 1 ,704     ,67,67,67
BEGIN DESCRIPTION:
Mapping XS fb37e83e
END DESCRIPTION:
XS GIS Cut Line= 4
      3718341.37      10625332.9      3718509.77     10625105.48
       3718549.7     10625071.62      3718675.46     10624906.24
#Sta/Elev= 30
  4708.4  299.42  4759.8  298.55  4809.9  298.52    4860  296.37  4880.8  293.77
  4910.1  291.46  4916.3  290.09  4937.1  287.16  4960.2  284.82    4981  283.76
  4994.8  283.76  4999.8  282.98    5003  283.48  5023.4  283.48  5030.5  284.46
  5047.8  284.71  5066.4  285.93  5087.2   286.5  5095.5  287.99  5101.7  288.57
  5108.4  290.16  5116.3  293.02  5122.6  292.94  5130.8  297.06  5151.6  298.11
  5158.6  299.14  5166.2   299.5  5180.7     299  5222.4  299.72  5251.5  299.09
#Mann= 1 ,-1 , 0
  4708.4     .16       0
Bank Sta=4937.1,5095.5
XS Rating Curve= 0 ,0
Exp/Cntr=0.3,0.1

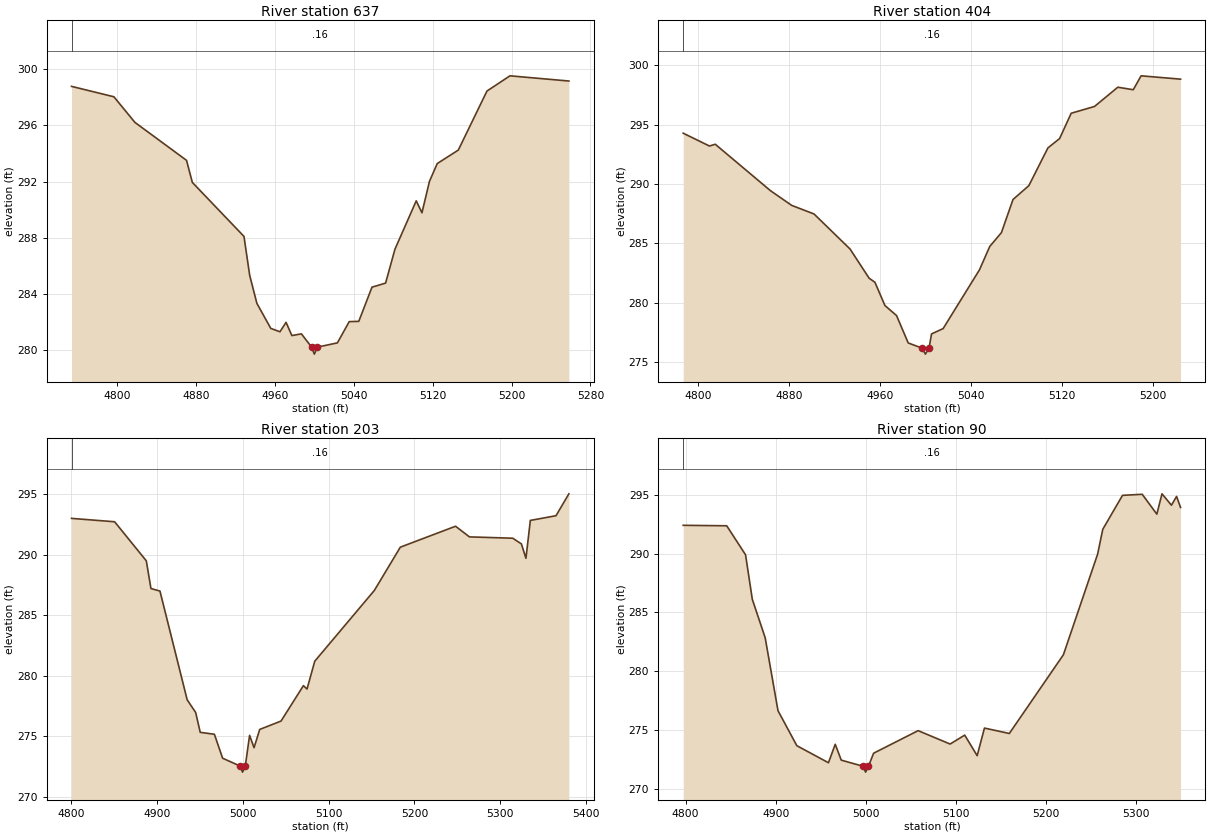
Type RM Length L Ch R = 1 ,637     ,233,233,233
BEGIN DESCRIPTION:
Mapping XS 8312b5b3
END DESCRIPTION:
XS GIS Cut Line= 2
      3718442.04     10625351.33      3718702.47     10624919.01
#Sta/Elev= 30
  4753.4  298.77  4796.4  298.03  4817.7  296.21  4870.1  293.51    4876  291.94
  4928.4   288.1  4934.2  285.33  4941.5  283.34  4955.6  281.56  4964.9  281.32
  4971.1  281.99    4977  281.05  4986.7  281.17    4997  280.23  4999.8  279.73
    5003  280.23  5023.2  280.53  5035.2  282.04  5044.9  282.06  5058.3  284.49
  5072.1  284.78  5081.6  287.19  5103.2  290.63    5109  289.78  5116.6  292.01
  5124.5  293.28  5145.9  294.24    5175  298.44  5198.3  299.52  5258.1  299.15
#Mann= 1 ,-1 , 0
  4753.4     .16       0
Bank Sta=4997,5003
XS Rating Curve= 0 ,0
Exp/Cntr=0.3,0.1

Type RM Length L Ch R = 1 ,404     ,201,201,201
BEGIN DESCRIPTION:
Mapping XS bdaa07e6
END DESCRIPTION:
XS GIS Cut Line= 2
       3718688.6      10625363.4      3718784.08     10624936.35
#Sta/Elev= 30
  4786.7  294.27  4809.8  293.19  4814.9  293.34  4863.5  289.43  4882.2  288.19
  4901.8  287.47  4933.5  284.52  4950.3  282.06  4955.4  281.72  4964.2  279.76
  4974.4  278.92  4984.7  276.61    4997  276.17  4999.8  275.67    5003  276.17
  5005.2  277.37  5015.4  277.82  5047.4  282.77  5056.4  284.73  5066.7   285.9
  5076.9  288.69  5090.8  289.85  5107.6  293.03  5117.9  293.82  5128.1  295.95
  5148.6  296.52  5169.1  298.14  5182.7  297.93  5189.6   299.1  5224.3  298.82
#Mann= 1 ,-1 , 0
  4786.7     .16       0
Bank Sta=4997,5003
XS Rating Curve= 0 ,0
Exp/Cntr=0.3,0.1

Type RM Length L Ch R = 1 ,203     ,113,113,113
BEGIN DESCRIPTION:
Mapping XS dc134fc9
END DESCRIPTION:
XS GIS Cut Line= 3
      3718846.58     10625387.73      3718935.11     10625127.33
      3718898.66     10624825.26
#Sta/Elev= 30
  4800.6     293  4850.8  292.72  4887.7  289.49  4893.1   287.2  4903.6  286.99
  4935.3     278  4945.2  276.95  4950.5  275.31    4967  275.15  4976.6  273.17
    4997  272.52  4999.8  272.02    5003  272.52    5008  275.06  5013.2  274.04
  5019.8  275.55  5044.6  276.24  5070.7  279.17  5074.9  278.89  5083.9  281.19
  5153.3  287.04  5183.6  290.62  5247.9  292.35  5264.1  291.47  5314.5  291.36
  5324.6  290.89  5329.9   289.7    5335  292.83  5364.9  293.22  5379.9  295.03
#Mann= 1 ,-1 , 0
  4800.6     .16       0
Bank Sta=4997,5003
XS Rating Curve= 0 ,0
Exp/Cntr=0.3,0.1

Type RM Length L Ch R = 1 ,90      ,0,0,0
BEGIN DESCRIPTION:
UNT 133 IN BOCR 1.0
END DESCRIPTION:
XS GIS Cut Line= 3
      3718870.87     10625389.49      3719058.38     10625179.42
      3719186.85     10624941.58
#Sta/Elev= 30
  4797.4  292.41  4845.7  292.37  4866.6   289.9  4874.1  286.11  4888.4  282.83
  4902.6  276.63  4923.5  273.65  4958.6   272.2  4966.1  273.77  4972.8  272.42
    4997   271.9  4999.8   271.4    5003   271.9  5008.7  273.01  5058.1  274.93
  5093.6  273.79  5109.8  274.55  5123.6   272.8  5131.7  275.15  5159.3  274.69
  5219.3  281.39  5257.3  289.96    5263  292.07  5284.9  294.96  5306.8  295.05
    5323  293.36  5328.7  295.09  5339.2  294.12  5344.9  294.87  5349.3  293.93
#Mann= 1 ,-1 , 0
  4797.4     .16       0
Bank Sta=4997,5003
XS Rating Curve= 0 ,0
Exp/Cntr=0.3,0.1

Chan Stop Cuts=-1
Use User Specified Reach Order=0
Composite Channel Slope=5