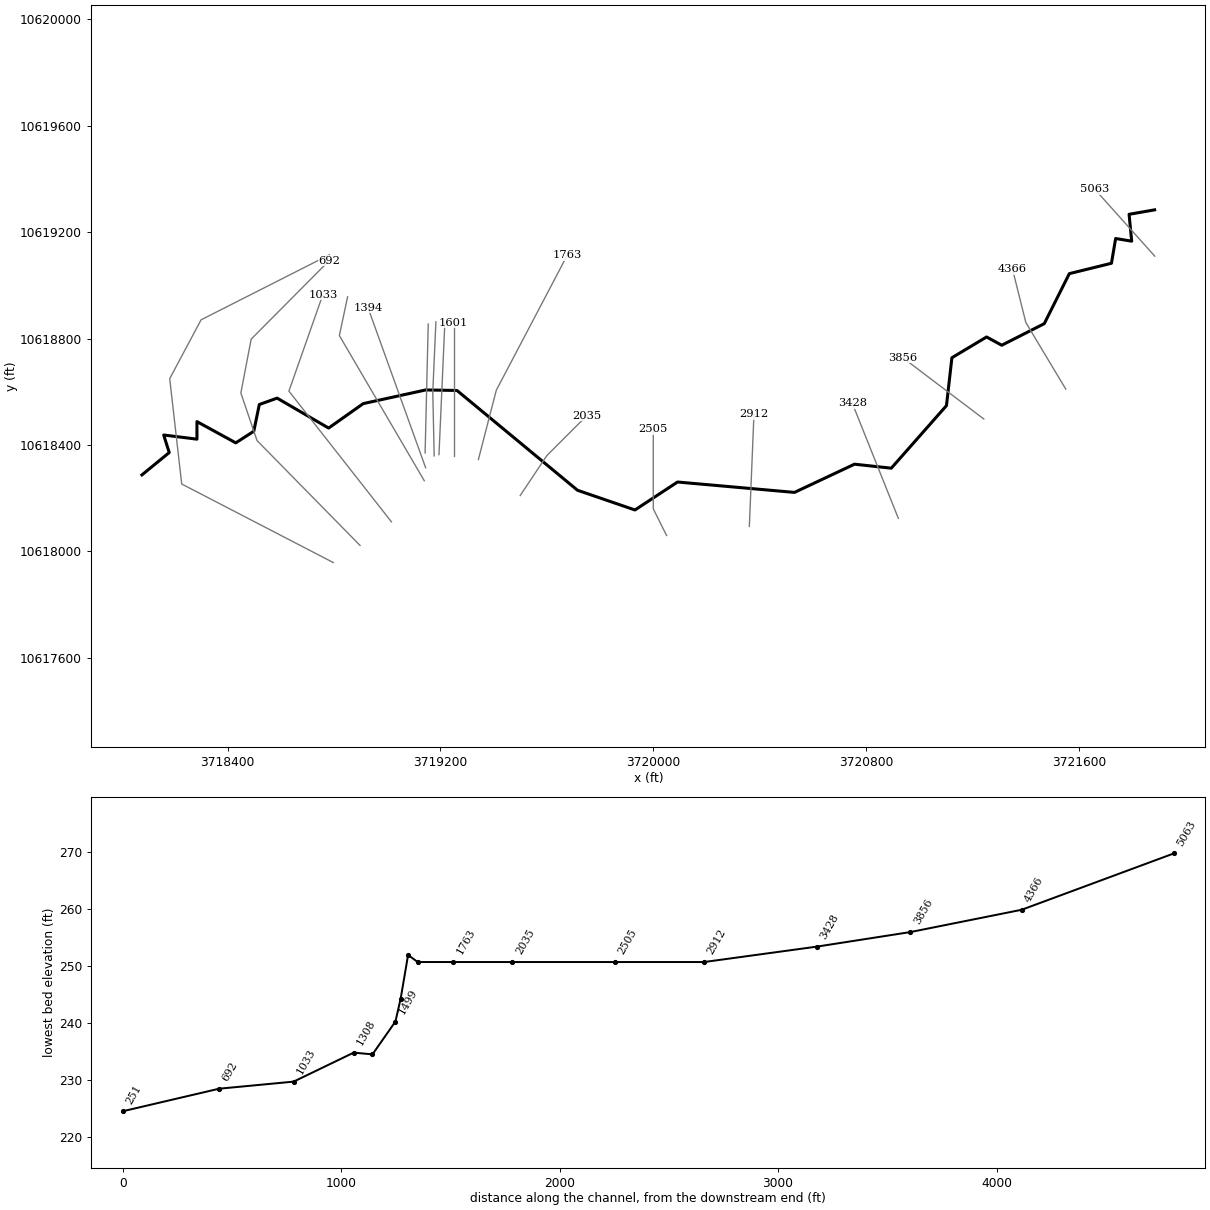
--- UNT 134 IN BOCR.prj (project) ---

Proj Title=UNT 134 IN BOCR Base Level Engineering
Current Plan=p01
Default Exp/Contr=0.3,0.1
English Units
Geom File=g01
Flow File=f01
Plan File=p01
Y Axis Title=Elevation
X Axis Title(PF)=Main Channel Distance
X Axis Title(XS)=Station
BEGIN DESCRIPTION:
UNT 134 IN BOCR
END DESCRIPTION:
DSS Export Rating Curves= 0
DSS Export Rating Curve Sorted= 0
DSS Export Volume Flow Curves= 0
DXF OffsetX= 0
DXF OffsetY= 0
DXF ScaleX= 1
DXF ScaleY= 10

--- UNT 134 IN BOCR.p01 (plan) ---

Plan Title=Multiple Run
Short Identifier=Multiple
Geom File=g01
Flow File=f01
Subcritical Flow
K Sum by GR= 0
Std Step Tol= 0.01
Critical Tol= 0.01
Num of Std Step Trials= 20
Max Error Tol= 0.3
Flow Tol Ratio= 0.001
Split Flow NTrial= 30
Split Flow Tol= 0.02
Split Flow Ratio= 0.02
Log Output Level= 0
Friction Slope Method= 1
Unsteady Friction Slope Method= 2
Unsteady Bridges Friction Slope Method= 1
Parabolic Critical Depth
Global Vel Dist=  1 , 1 , 1
Global Log Level= 0
CheckData=True
Encroach Param= -1, 0, 0, 0
BEGIN DESCRIPTION:
Multiple Run
END DESCRIPTION:

--- UNT 134 IN BOCR.f01 (steady flow) ---

Flow Title=Multiple
Program Version=4.10
Number of Profiles= 7
Profile Names=10-year,25-year,50-year,1pct_min,100-year,1pct_plu,500-year
River Rch & RM=UNT 134 IN BOCR,Reach-1         ,5063
     305     394     463     402     543     734     748
Boundary for River Rch & Prof#=UNT 134 IN BOCR,Reach-1         , 1
Up Type= 0
Dn Type= 3
Dn Slope=0.005
Boundary for River Rch & Prof#=UNT 134 IN BOCR,Reach-1         , 2
Up Type= 0
Dn Type= 3
Dn Slope=0.005
Boundary for River Rch & Prof#=UNT 134 IN BOCR,Reach-1         , 3
Up Type= 0
Dn Type= 3
Dn Slope=0.005
Boundary for River Rch & Prof#=UNT 134 IN BOCR,Reach-1         , 4
Up Type= 0
Dn Type= 3
Dn Slope=0.005
Boundary for River Rch & Prof#=UNT 134 IN BOCR,Reach-1         , 5
Up Type= 0
Dn Type= 3
Dn Slope=0.005
Boundary for River Rch & Prof#=UNT 134 IN BOCR,Reach-1         , 6
Up Type= 0
Dn Type= 3
Dn Slope=0.005
Boundary for River Rch & Prof#=UNT 134 IN BOCR,Reach-1         , 7
Up Type= 0
Dn Type= 3
Dn Slope=0.005
DSS Import GetInterval= 0
DSS Import GetPeak= 0
DSS Import FillOption= 0

--- UNT 134 IN BOCR.g01 (geometry) ---

Geom Title=Existing Conditions
Program Version=4.10

River Reach=UNT 134 IN BOCR ,Reach-1
Reach XY= 30
      3721883.44     10619283.69       3721787.5       10619267.
      3721797.25       10619166.        3721737.       10619176.
      3721721.25       10619083.        3721563.       10619044.
      3721468.75       10618856.        3721309.       10618775.
        3721252.       10618806.      3721121.75       10618728.
      3721101.25       10618548.        3720894.       10618313.
      3720755.75       10618328.      3720530.18     10618221.99
      3720090.75       10618261.      3719930.75       10618156.
        3719715.       10618230.        3719262.       10618605.
      3719144.75       10618607.      3718909.78     10618555.63
      3718779.73     10618463.73      3718586.13     10618576.25
      3718519.31     10618552.27      3718498.48     10618451.57
      3718430.77     10618408.17      3718284.94     10618488.03
      3718284.94     10618422.06      3718159.94     10618437.69
      3718180.77     10618371.71      3718078.21     10618287.71

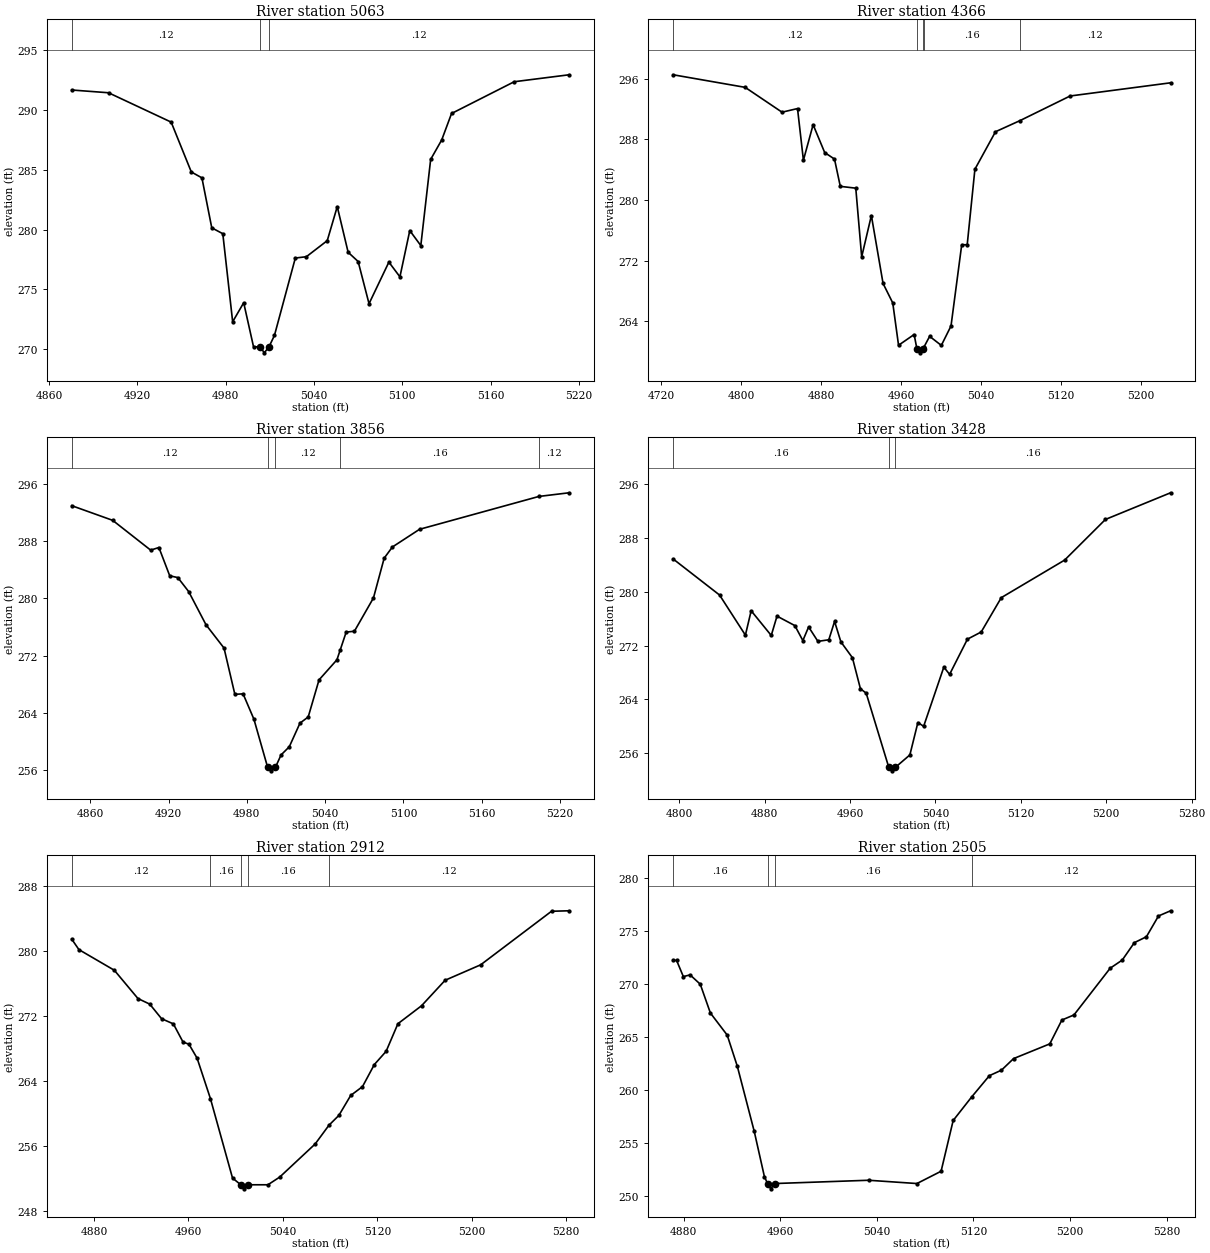
Type RM Length L Ch R = 1 ,5063    ,697,697,697
BEGIN DESCRIPTION:
UNT 134 IN BOCR 9.0
END DESCRIPTION:
XS GIS Cut Line= 2
      3721884.04     10619109.68      3721658.35     10619361.42
#Sta/Elev= 30
  4875.3  291.64  4900.3  291.41  4942.9  288.96  4956.6   284.8  4963.8  284.31
  4970.5  280.14    4978  279.65  4984.7   272.3  4992.2  273.89  4998.9  270.21
  5003.4  270.21  5006.2  269.71  5009.4  270.21  5013.1  271.16  5027.3  277.62
  5034.8  277.73    5049  279.07  5055.8  281.91  5063.2   278.1    5070  277.33
  5077.4  273.81  5090.9  277.28  5098.4  276.05  5105.1  279.91  5112.6  278.66
  5119.3  285.85  5126.8  287.47  5133.5  289.68  5176.1  292.33  5213.4  292.91
#Mann= 3 ,-1 , 0
  4875.3     .12       0  5003.4     .07       0  5009.4     .12       0
Bank Sta=5003.4,5009.4
XS Rating Curve= 0 ,0
Exp/Cntr=0.3,0.1

Type RM Length L Ch R = 1 ,4366    ,510,510,510
BEGIN DESCRIPTION:
UNT 134 IN BOCR 8.0
END DESCRIPTION:
XS GIS Cut Line= 3
      3721549.63     10618610.15      3721399.61     10618860.19
      3721349.62     10619060.15
#Sta/Elev= 30
  4732.1  296.54  4804.1  294.88    4841   291.6  4856.5  292.08  4862.4  285.26
  4872.1  289.95  4883.7  286.27  4893.5  285.41  4899.3  281.81  4914.8  281.57
  4920.7   272.5  4930.4  277.96  4942.1  268.99  4951.8  266.42  4957.6  260.83
  4973.2  262.25    4976  260.33  4978.7  259.83    4982  260.33  4982.9  260.56
  4988.7  262.01  5000.4  260.81  5010.1  263.38  5020.8   274.1  5026.3   274.1
    5034  284.07  5054.6  289.02  5079.3   290.5  5129.3  293.74  5229.8  295.48
#Mann= 5 ,-1 , 0
  4732.1     .12       0    4976     .07       0    4982     .12       0
  4982.9     .16       0  5079.3     .12       0
Bank Sta=4976,4982
XS Rating Curve= 0 ,0
Exp/Cntr=0.3,0.1

Type RM Length L Ch R = 1 ,3856    ,428,428,428
BEGIN DESCRIPTION:
Mapping XS ae1ef6a1
END DESCRIPTION:
XS GIS Cut Line= 2
      3721241.65     10618497.74      3720937.81     10618727.78
#Sta/Elev= 30
  4845.8  292.94  4877.2  290.89  4906.3  286.73  4912.6   287.1  4920.9  283.15
  4927.1   282.9  4935.4  280.95  4948.7  276.31  4962.5  273.06  4970.8   266.6
  4977.1  266.67  4985.4  263.13  4995.9  256.42  4998.6  255.92  5001.9  256.42
  5006.2  258.14  5012.5  259.28  5020.7  262.58    5027  263.44  5035.3  268.62
    5049  271.42  5051.5  272.78  5056.1  275.29  5062.4  275.41    5077  280.06
  5085.2  285.61  5091.5  287.17  5112.3  289.64  5203.8  294.23  5226.9  294.74
#Mann= 5 ,-1 , 0
  4845.8     .12       0  4995.9     .07       0  5001.9     .12       0
  5051.5     .16       0  5203.8     .12       0
Bank Sta=4995.9,5001.9
XS Rating Curve= 0 ,0
Exp/Cntr=0.3,0.1

Type RM Length L Ch R = 1 ,3428    ,516,516,516
BEGIN DESCRIPTION:
Mapping XS 4443c0f2
END DESCRIPTION:
XS GIS Cut Line= 2
       3720920.5     10618124.41      3720747.55     10618556.81
#Sta/Elev= 30
  4794.5   284.9  4837.9  279.54  4862.1  273.57  4867.5   277.2  4886.3  273.52
  4891.7   276.4  4908.4  274.99  4915.9  272.76  4921.3  274.79    4930  272.64
  4940.2  272.88  4945.6  275.61  4951.5  272.57  4962.3  270.21  4969.8  265.59
  4975.2  264.93  4996.4  253.87  4999.2  253.37  5002.4  253.87  5016.1  255.74
  5023.6  260.56    5029     260  5047.9  268.81  5053.3  267.73    5070  272.97
  5082.9  274.04  5101.7  279.15    5161  284.74  5199.2  290.79  5260.2  294.76
#Mann= 3 ,-1 , 0
  4794.5     .16       0  4996.4     .07       0  5002.4     .16       0
Bank Sta=4996.4,5002.4
XS Rating Curve= 0 ,0
Exp/Cntr=0.3,0.1

Type RM Length L Ch R = 1 ,2912    ,407,407,407
BEGIN DESCRIPTION:
Mapping XS 773edade
END DESCRIPTION:
XS GIS Cut Line= 2
      3720360.59     10618094.12      3720377.95     10618515.06
#Sta/Elev= 30
  4861.1   281.4  4867.2  280.11  4897.2  277.57  4917.2  274.09  4927.2   273.4
  4937.2  271.61  4947.2  270.97  4955.4  268.73  4960.4  268.47  4967.3  266.75
  4978.6  261.77  4997.3     252  5004.3  251.17    5007  250.67  5010.3  251.17
  5027.3  251.17  5037.3  252.12  5067.3  256.19    5079   258.5  5087.4  259.71
  5097.4  262.16  5107.4  263.25  5117.4  265.96  5127.4  267.59  5137.4  270.99
  5157.4   273.2  5177.4  276.34  5207.5  278.24  5267.5  284.83  5282.4  284.89
#Mann= 5 ,-1 , 0
  4861.1     .12       0  4978.6     .16       0  5004.3     .07       0
  5010.3     .16       0    5079     .12       0
Bank Sta=5004.3,5010.3
XS Rating Curve= 0 ,0
Exp/Cntr=0.3,0.1

Type RM Length L Ch R = 1 ,2505    ,470,470,470
BEGIN DESCRIPTION:
UNT 134 IN BOCR 4.0
END DESCRIPTION:
XS GIS Cut Line= 3
      3720049.62     10618060.16      3719999.61     10618160.19
      3719999.61     10618460.16
#Sta/Elev= 30
  4871.4  272.23  4874.2  272.23  4879.8   270.7  4885.4  270.86  4893.8  269.98
  4902.2  267.26  4916.1  265.18  4924.5  262.23  4938.5  256.09  4946.9  251.83
  4949.5  251.17  4952.2  250.67  4955.5  251.17  5033.2  251.48  5073.2  251.17
  5093.2  252.33  5103.2  257.12  5118.5  259.34  5133.2  261.35  5143.2  261.87
  5153.2  262.96  5183.2  264.35  5193.2   266.6  5203.2  267.08  5233.2  271.49
  5243.2  272.26  5253.2   273.9  5263.2  274.46  5273.2  276.42  5283.2  276.91
#Mann= 4 ,-1 , 0
  4871.4     .16       0  4949.5     .07       0  4955.5     .16       0
  5118.5     .12       0
Bank Sta=4949.5,4955.5
XS Rating Curve= 0 ,0
Exp/Cntr=0.3,0.1

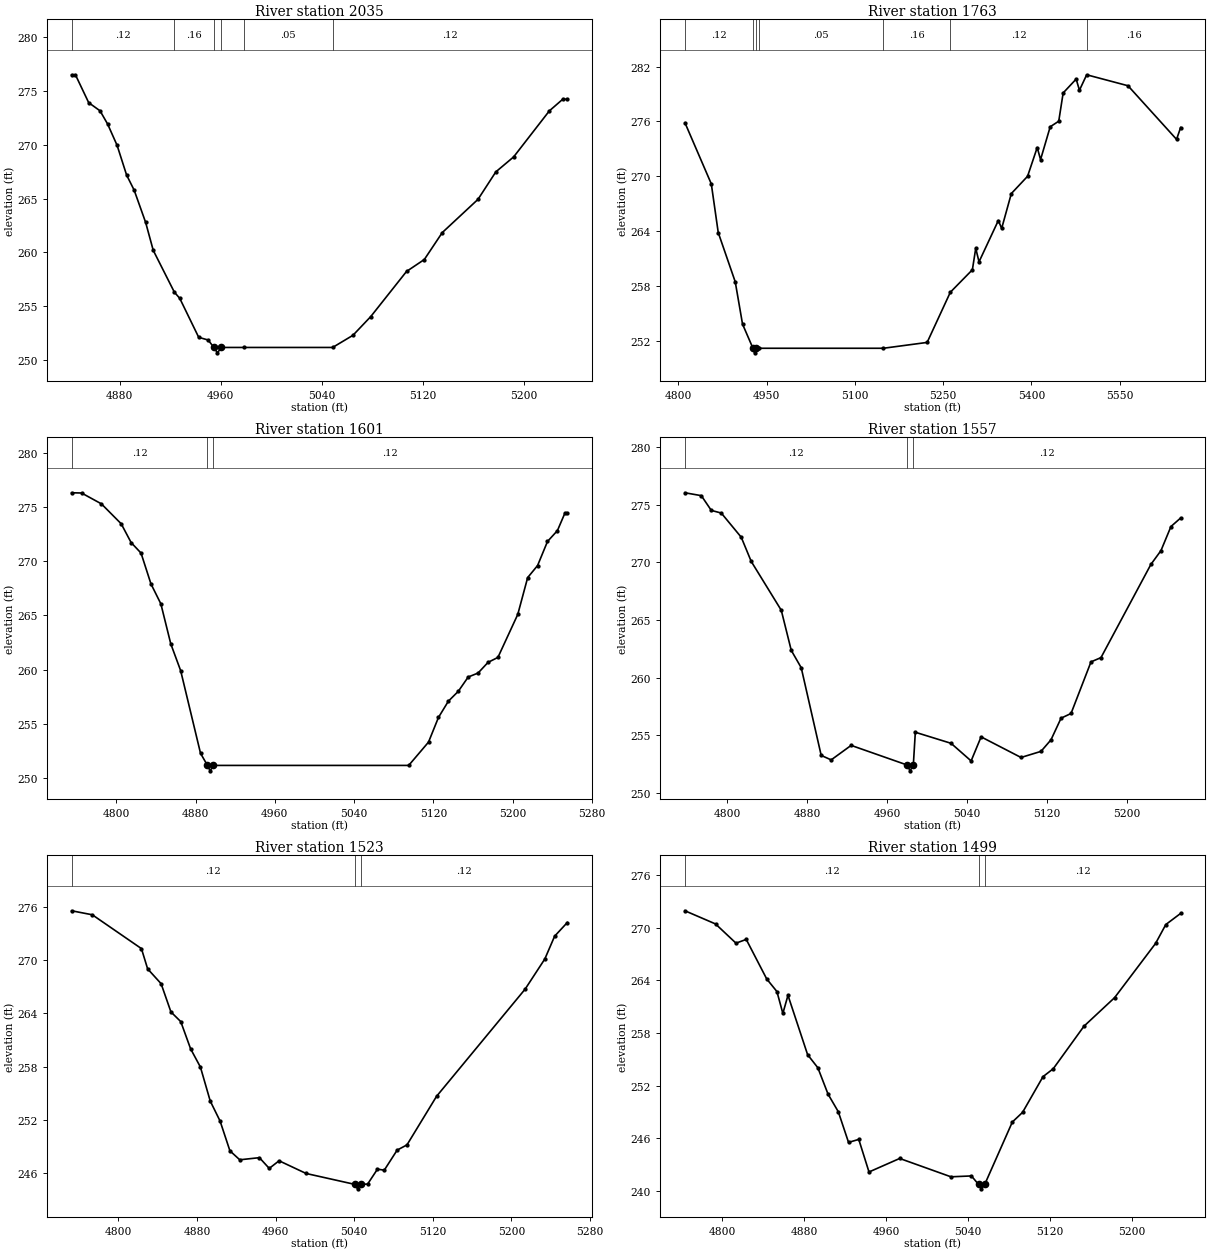
Type RM Length L Ch R = 1 ,2035    ,272,272,272
BEGIN DESCRIPTION:
UNT 134 IN BOCR 3.0
END DESCRIPTION:
XS GIS Cut Line= 3
      3719499.63     10618210.22      3719599.61     10618360.19
      3719749.63     10618510.21
#Sta/Elev= 30
  4841.9   276.5  4844.9   276.5  4855.4  273.91  4864.4  273.15  4870.4  271.92
  4877.9  269.94  4885.4  267.19  4891.4  265.78  4900.5  262.78  4906.5  260.19
  4923.2  256.31  4927.5  255.73  4942.5  252.11    4950  251.86  4954.5  251.17
  4957.3  250.67  4960.5  251.17  4978.1  251.17  5048.5  251.17  5064.6   252.3
  5078.7  254.04    5107  258.23  5121.1  259.34  5135.3  261.84  5163.6  264.93
  5177.7  267.48  5191.8  268.87  5220.1  273.15  5230.7  274.23  5234.3  274.23
#Mann= 6 ,-1 , 0
  4841.9     .12       0  4923.2     .16       0  4954.5    .033       0
  4960.5     .16       0  4978.1     .05       0  5048.5     .12       0
Bank Sta=4954.5,4960.5
XS Rating Curve= 0 ,0
Exp/Cntr=0.3,0.1

Type RM Length L Ch R = 1 ,1763    ,162,162,162
BEGIN DESCRIPTION:
Mapping XS efb392dc
END DESCRIPTION:
XS GIS Cut Line= 3
      3719342.47     10618345.39      3719409.74      10618605.8
      3719676.65     10619113.57
#Sta/Elev= 30
    4811  275.85  4855.8  269.16  4867.6  263.83  4896.5  258.44  4908.9  253.81
  4926.6  251.17  4929.3  250.67  4932.6  251.17  4937.1  251.17  5148.2  251.17
  5222.7  251.81  5262.1   257.3  5299.6  259.76  5305.3  262.11  5310.9  260.63
  5343.7  265.15  5349.4  264.29  5365.8   268.1  5393.4  269.99  5409.8  273.14
  5415.5  271.82  5431.9  275.41  5446.4  276.02  5453.9  279.11    5476  280.63
  5481.6  279.41  5493.9   281.1  5564.1   279.9  5646.7  274.03  5653.6  275.33
#Mann= 7 ,-1 , 0
    4811     .12       0  4926.6    .033       0  4932.6     .12       0
  4937.1     .05       0  5148.2     .16       0  5262.1     .12       0
  5493.9     .16       0
Bank Sta=4926.6,4932.6
XS Rating Curve= 0 ,0
Exp/Cntr=0.3,0.1

Type RM Length L Ch R = 1 ,1601    ,44,44,44
BEGIN DESCRIPTION:
UNT 134 IN BOCR 2.0
END DESCRIPTION:
XS GIS Cut Line= 3
      3719249.61     10618360.21      3719249.61     10618610.19
      3719249.61     10618860.21
#Sta/Elev= 30
    4755  276.31    4765  276.29    4785  275.29    4805  273.45    4815  271.72
    4825  270.75    4835  267.91    4845  266.07    4855  262.38    4865   259.9
    4885  252.29    4892  251.17  4894.7  250.67    4898  251.17    5095  251.17
    5115  253.32    5125  255.59    5135  257.09    5145     258    5155  259.32
    5165  259.69    5175  260.67    5185  261.13    5205  265.09    5215  268.49
    5225   269.6    5235  271.82    5245  272.82  5252.5  274.42    5255  274.42
#Mann= 3 ,-1 , 0
    4755     .12       0    4892     .07       0    4898     .12       0
Bank Sta=4892,4898
XS Rating Curve= 0 ,0
Exp/Cntr=0.3,0.1

Type RM Length L Ch R = 1 ,1557    ,34,34,34
BEGIN DESCRIPTION:
Mapping XS 1cd0c6e3
END DESCRIPTION:
XS GIS Cut Line= 2
      3719194.36     10618363.81      3719216.49     10618859.92
#Sta/Elev= 30
  4757.6  276.05    4774   275.8    4784  274.52    4794  274.29    4814  272.19
    4824  270.09  4854.1  265.85  4864.1  262.37  4874.1  260.86  4894.1  253.25
  4904.1  252.86  4924.1  254.12  4980.4  252.41  4983.1  251.91  4986.4  252.41
  4988.4  255.26  5024.2   254.3  5044.3  252.77  5054.3  254.86  5094.3  253.07
  5114.3   253.6  5124.3   254.6  5134.4  256.48  5144.4  256.89  5164.4  261.37
  5174.4  261.74  5224.4  269.83  5234.5  271.03  5244.5  273.12  5254.2  273.86
#Mann= 3 ,-1 , 0
  4757.6     .12       0  4980.4     .07       0  4986.4     .12       0
Bank Sta=4980.4,4986.4
XS Rating Curve= 0 ,0
Exp/Cntr=0.3,0.1

Type RM Length L Ch R = 1 ,1523    ,24,24,24
BEGIN DESCRIPTION:
Mapping XS ef5a086f
END DESCRIPTION:
XS GIS Cut Line= 3
      3719176.31     10618359.21       3719171.1      10618600.1
      3719182.82     10618863.09
#Sta/Elev= 30
  4752.6  275.56  4773.6  275.11  4823.6   271.3  4829.9  269.02  4843.6  267.35
  4853.6  264.17  4863.6  263.08  4873.6  260.02  4883.6  257.96  4893.6  254.13
  4903.6  251.88  4913.6  248.53  4923.6  247.52  4943.6  247.76  4953.6  246.55
  4963.6  247.41  4991.1  245.98  5040.7  244.75  5043.4  244.25  5046.7  244.75
  5053.7  244.79  5063.7  246.47  5070.6  246.35  5083.7  248.61  5093.7   249.2
  5123.8  254.67  5213.9  266.74  5233.9  270.13  5243.9   272.7  5256.8  274.24
#Mann= 3 ,-1 , 0
  4752.6     .12       0  5040.7     .07       0  5046.7     .12       0
Bank Sta=5040.7,5046.7
XS Rating Curve= 0 ,0
Exp/Cntr=0.3,0.1

Type RM Length L Ch R = 1 ,1499    ,105,105,105
BEGIN DESCRIPTION:
Mapping XS 58d05b9b
END DESCRIPTION:
XS GIS Cut Line= 2
      3719142.27     10618370.31      3719153.99     10618854.67
#Sta/Elev= 30
  4763.3  271.91  4793.2  270.41  4813.2  268.22  4823.2  268.65  4843.2  264.15
  4853.2  262.71    4859  260.22    4864  262.28  4883.2  255.52  4893.2  254.03
  4903.2  251.02  4913.2  249.02  4923.2  245.53  4933.2  245.87  4943.2  242.16
  4973.2   243.7  5023.3  241.61  5043.3  241.71  5050.3  240.74    5053  240.24
  5056.3  240.74  5083.3  247.85  5093.3  248.95  5113.3  253.02  5123.3  253.92
  5153.3  258.76  5183.3  262.02  5223.3  268.19  5233.3  270.34  5247.8  271.61
#Mann= 3 ,-1 , 0
  4763.3     .12       0  5050.3     .07       0  5056.3     .12       0
Bank Sta=5050.3,5056.3
XS Rating Curve= 0 ,0
Exp/Cntr=0.3,0.1

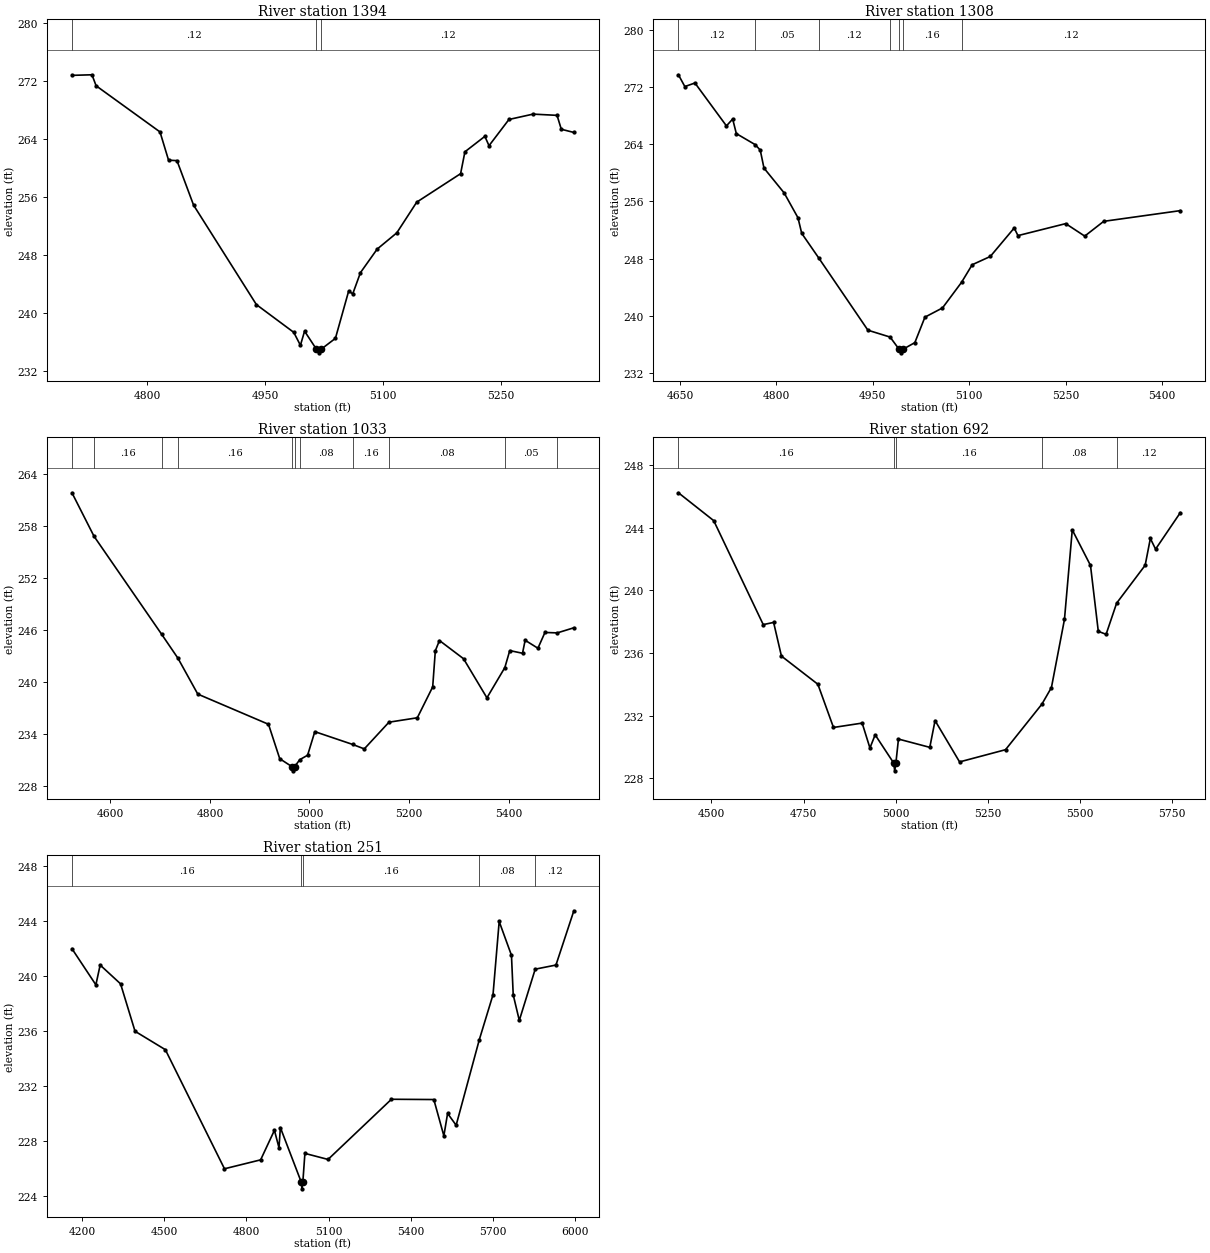
Type RM Length L Ch R = 1 ,1394    ,86,86,86
BEGIN DESCRIPTION:
Mapping XS 94b1c016
END DESCRIPTION:
XS GIS Cut Line= 2
      3719144.36     10618314.33      3718927.63     10618915.98
#Sta/Elev= 30
  4703.9  272.79  4729.4  272.87  4734.7  271.35  4816.1  264.98    4827  261.08
  4837.7  261.02  4858.9  254.87  4938.9  241.15  4986.5  237.32    4995  235.53
  5000.3  237.48  5015.4  234.99  5018.1  234.49  5021.4  234.99  5039.6  236.49
  5056.4  242.99  5061.7  242.64  5071.5  245.56  5092.8  248.81  5117.8  251.05
  5143.2  255.29  5199.1  259.22  5204.6  262.24    5230  264.37  5235.3  263.08
  5260.7   266.7  5291.4  267.44    5322  267.27  5327.4  265.35  5343.4  264.91
#Mann= 3 ,-1 , 0
  4703.9     .12       0  5015.4     .07       0  5021.4     .12       0
Bank Sta=5015.4,5021.4
XS Rating Curve= 0 ,0
Exp/Cntr=0.3,0.1

Type RM Length L Ch R = 1 ,1308    ,275,275,275
BEGIN DESCRIPTION:
Mapping XS a2af220b
END DESCRIPTION:
XS GIS Cut Line= 3
      3719139.15     10618265.72      3718820.08     10618811.33
      3718850.97     10618956.84
#Sta/Elev= 30
  4647.6  273.74  4657.6  272.09  4673.3  272.59  4722.3  266.58    4732  267.54
  4737.7   265.5  4767.1  263.95  4774.9  263.19  4780.7  260.67  4812.1  257.19
  4833.6  253.71  4839.4  251.53  4865.8  248.09  4942.4  237.96  4976.9     237
  4990.9  235.29  4993.7  234.79  4996.9  235.29  5015.4  236.22  5031.1  239.79
  5058.4  241.08    5088  244.66  5104.6  247.13  5132.8  248.29    5170  252.28
  5175.8  251.21  5250.1  252.89  5279.7  251.14  5309.2  253.21  5428.4  254.71
#Mann= 7 ,-1 , 0
  4647.6     .12       0  4767.1     .05       0  4865.8     .12       0
  4976.9     .16       0  4990.9     .07       0  4996.9     .16       0
    5088     .12       0
Bank Sta=4990.9,4996.9
XS Rating Curve= 0 ,0
Exp/Cntr=0.3,0.1

Type RM Length L Ch R = 1 ,1033    ,341,341,341
BEGIN DESCRIPTION:
Mapping XS abb6d013
END DESCRIPTION:
XS GIS Cut Line= 3
       3719015.9     10618111.19      3718630.47     10618602.53
      3718757.99     10618964.98
#Sta/Elev= 30
  4522.6  261.78    4567  256.76  4703.1  245.44  4735.6   242.7  4775.5  238.56
  4917.6  235.08  4940.2  231.11  4964.3  230.21  4967.1  229.71  4970.3  230.21
  4980.5     231  4996.2  231.51  5010.7  234.23    5087  232.75  5110.1  232.24
  5159.7  235.32  5216.7  235.83  5247.6  239.39  5252.9  243.56  5261.2  244.74
  5309.6  242.64  5356.6  238.13  5392.6  241.62  5402.5  243.58  5428.1  243.27
  5433.4  244.77  5459.1  243.85  5473.2  245.67    5498  245.62  5531.3  246.21
#Mann= 11 ,-1 , 0
  4522.6     .08       0    4567     .16       0  4703.1     .05       0
  4735.6     .16       0  4964.3     .07       0  4970.3     .16       0
  4980.5     .08       0    5087     .16       0  5159.7     .08       0
  5392.6     .05       0    5498     .12       0
Bank Sta=4964.3,4970.3
XS Rating Curve= 0 ,0
Exp/Cntr=0.3,0.1

Type RM Length L Ch R = 1 ,692     ,441,441,441
BEGIN DESCRIPTION:
Mapping XS a0e190de
END DESCRIPTION:
XS GIS Cut Line= 5
      3718897.82     10618022.68      3718510.68     10618416.77
      3718449.91     10618595.59      3718488.71     10618797.95
      3718781.86     10619093.04
#Sta/Elev= 30
  4410.2  246.23  4506.1  244.45  4640.6  237.81  4668.8  237.95    4690   235.8
    4789     234  4831.4  231.24  4909.3  231.52  4930.4  229.93  4944.6  230.77
  4994.9  228.97  4997.7  228.47  5000.9  228.97  5007.9   230.5    5093  229.97
  5107.3  231.68  5173.9  229.04  5298.7  229.82  5397.5  232.73  5423.4  233.79
  5458.8  238.14    5480  243.86  5529.5  241.59  5550.7  237.38  5571.9  237.19
  5600.5  239.18    5678   241.6  5692.1  243.31  5706.3  242.63  5773.5  244.96
#Mann= 5 ,-1 , 0
  4410.2     .16       0  4994.9     .07       0  5000.9     .16       0
  5397.5     .08       0  5600.5     .12       0
Bank Sta=4994.9,5000.9
XS Rating Curve= 0 ,0
Exp/Cntr=0.3,0.1

Type RM Length L Ch R = 1 ,251     ,0,0,0
BEGIN DESCRIPTION:
UNT 134 IN BOCR 1.0
END DESCRIPTION:
XS GIS Cut Line= 5
      3718797.15     10617958.43      3718227.69     10618253.57
      3718182.55     10618649.41      3718300.47      10618870.5
      3718782.62     10619114.85
#Sta/Elev= 30
  4163.9     242  4251.2  239.37  4266.8  240.81  4341.3  239.44    4394  235.99
  4504.6  234.65  4720.3  225.98  4852.2  226.63  4902.5  228.78  4919.2  227.51
  4924.2  228.98  5000.2  225.02  5002.9  224.52  5006.2  225.02  5013.7   227.1
  5098.1  226.66  5329.3  231.04    5484  231.02  5520.6  228.38  5534.2  230.01
  5565.4  229.15  5650.1  235.39  5699.9  238.65  5722.4  243.98  5767.2  241.52
  5773.6  238.64  5795.8  236.78  5853.8  240.51  5929.5  240.81  5994.8  244.76
#Mann= 5 ,-1 , 0
  4163.9     .16       0  5000.2     .07       0  5006.2     .16       0
  5650.1     .08       0  5853.8     .12       0
Bank Sta=5000.2,5006.2
XS Rating Curve= 0 ,0
Exp/Cntr=0.3,0.1

Chan Stop Cuts=-1
Use User Specified Reach Order=0
Composite Channel Slope=5