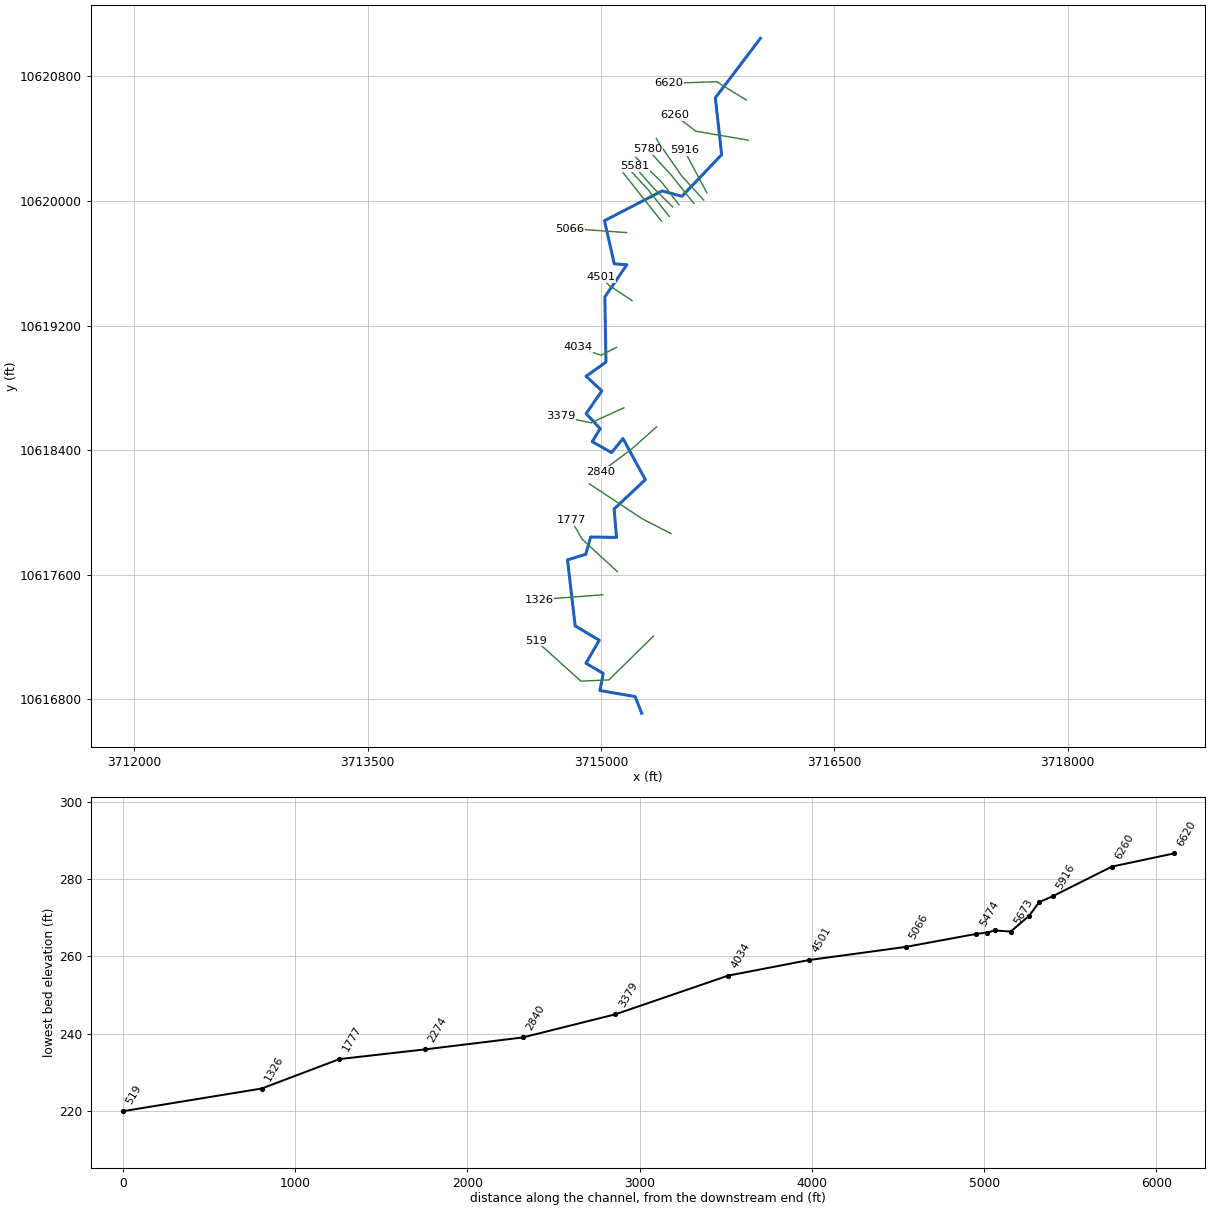
--- UNT 135 IN BOCR.prj (project) ---

Proj Title=UNT 135 IN BOCR Base Level Engineering
Current Plan=p01
Default Exp/Contr=0.3,0.1
English Units
Geom File=g01
Flow File=f01
Plan File=p01
Y Axis Title=Elevation
X Axis Title(PF)=Main Channel Distance
X Axis Title(XS)=Station
BEGIN DESCRIPTION:
UNT 135 IN BOCR
END DESCRIPTION:
DSS Export Rating Curves= 0
DSS Export Rating Curve Sorted= 0
DSS Export Volume Flow Curves= 0
DXF OffsetX= 0
DXF OffsetY= 0
DXF ScaleX= 1
DXF ScaleY= 10

--- UNT 135 IN BOCR.p01 (plan) ---

Plan Title=Multiple Run
Short Identifier=Multiple
Geom File=g01
Flow File=f01
Subcritical Flow
K Sum by GR= 0
Std Step Tol= 0.01
Critical Tol= 0.01
Num of Std Step Trials= 20
Max Error Tol= 0.3
Flow Tol Ratio= 0.001
Split Flow NTrial= 30
Split Flow Tol= 0.02
Split Flow Ratio= 0.02
Log Output Level= 0
Friction Slope Method= 1
Unsteady Friction Slope Method= 2
Unsteady Bridges Friction Slope Method= 1
Parabolic Critical Depth
Global Vel Dist=  1 , 1 , 1
Global Log Level= 0
CheckData=True
Encroach Param= -1, 0, 0, 0
BEGIN DESCRIPTION:
Multiple Run
END DESCRIPTION:

--- UNT 135 IN BOCR.f01 (steady flow) ---

Flow Title=Multiple
Number of Profiles=7
Profile Names=10-year,25-year,50-year,1pct_min,100-year,1pct_plu,500-year
River Rch & RM= UNT 135 IN BOCR,Reach-1,6620
     233     294     341     292     395     534     529
Boundary for River Rch & Prof#=UNT 135 IN BOCR,Reach-1,1
Up Type=0
Dn Type=3
Dn Slope=0.005
Boundary for River Rch & Prof#=UNT 135 IN BOCR,Reach-1,2
Up Type=0
Dn Type=3
Dn Slope=0.005
Boundary for River Rch & Prof#=UNT 135 IN BOCR,Reach-1,3
Up Type=0
Dn Type=3
Dn Slope=0.005
Boundary for River Rch & Prof#=UNT 135 IN BOCR,Reach-1,4
Up Type=0
Dn Type=3
Dn Slope=0.005
Boundary for River Rch & Prof#=UNT 135 IN BOCR,Reach-1,5
Up Type=0
Dn Type=3
Dn Slope=0.005
Boundary for River Rch & Prof#=UNT 135 IN BOCR,Reach-1,6
Up Type=0
Dn Type=3
Dn Slope=0.005
Boundary for River Rch & Prof#=UNT 135 IN BOCR,Reach-1,7
Up Type=0
Dn Type=3
Dn Slope=0.005

--- UNT 135 IN BOCR.g01 (geometry) ---

Geom Title=Existing Conditions
Program Version=4.10

River Reach=UNT 135 IN BOCR ,Reach-1
Reach XY= 30
       3716024.5       10621045.       3715734.5       10620663.
      3715775.25       10620298.        3715520.      10620030.8
      3715392.25       10620065.      3715021.75       10619874.
        3715085.       10619597.      3715165.75       10619591.
       3715024.5       10619385.       3715031.5       10618966.
       3714903.5       10618875.      3715005.25       10618781.
        3714904.       10618635.       3714994.5       10618539.
      3714943.25       10618455.       3715067.5       10618385.
        3715141.       10618475.       3715284.5       10618211.
        3715084.       10618023.      3715099.25       10617840.
        3714933.       10617843.      3714901.75       10617732.
      3714784.25       10617696.       3714833.5       10617272.
       3714988.5       10617180.      3714902.75       10617032.
      3715013.75       10616967.      3714992.75       10616857.
        3715219.       10616818.       3715261.5       10616711.

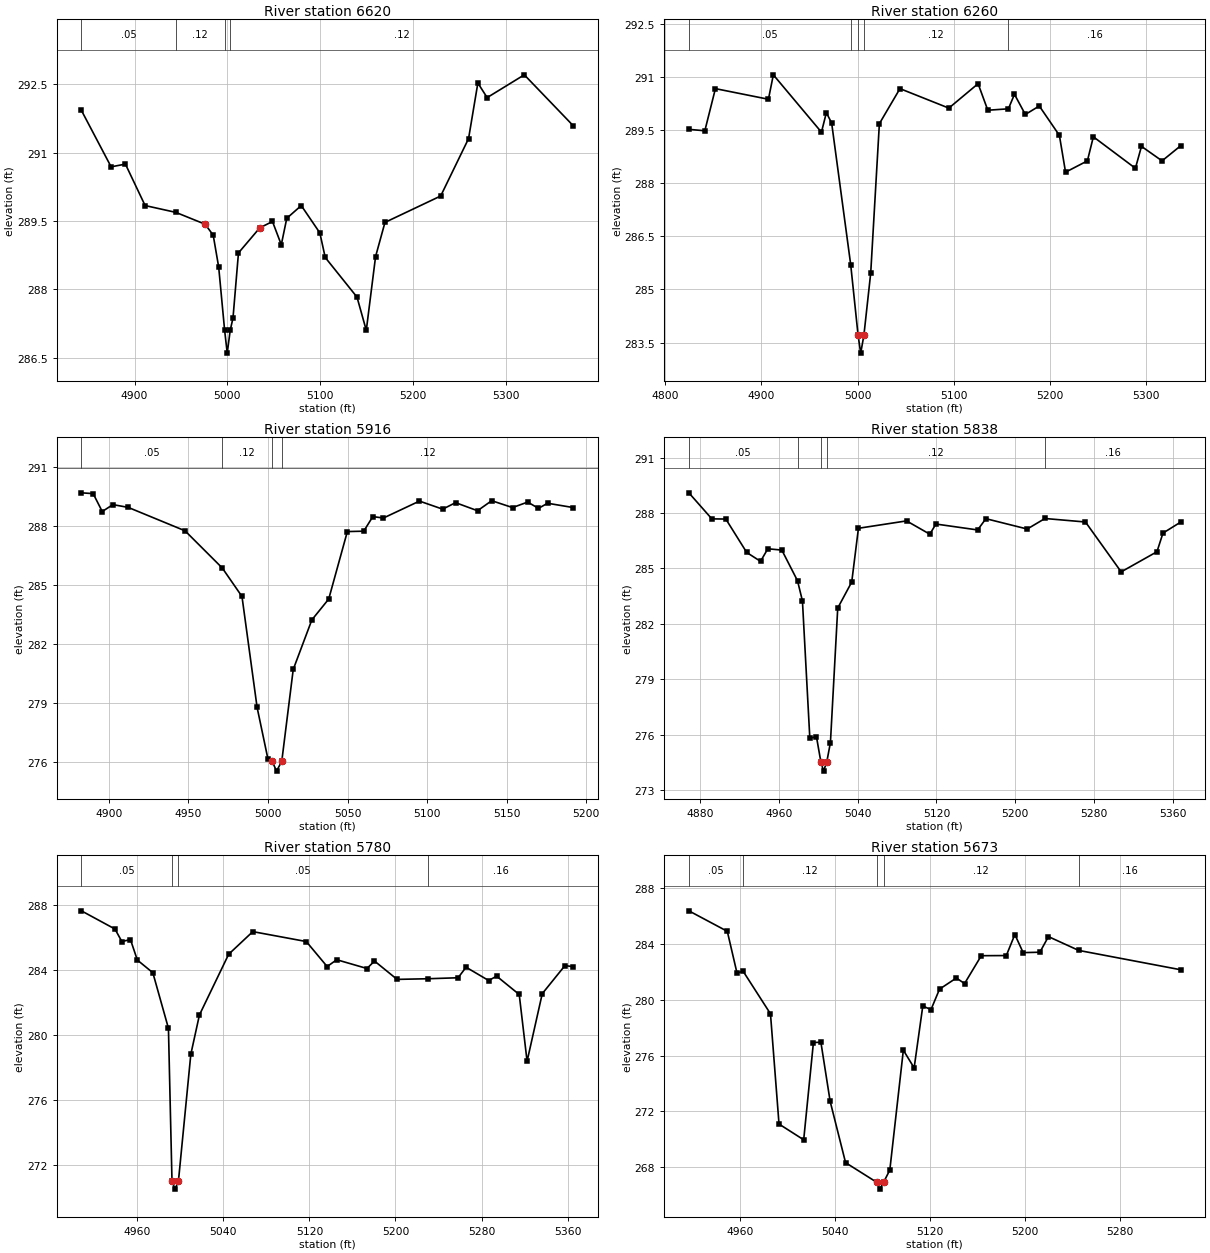
Type RM Length L Ch R = 1 ,6620    ,360,360,360
BEGIN DESCRIPTION:
UNT 135 IN BOCR 11.0
END DESCRIPTION:
XS GIS Cut Line= 3
       3715932.9     10620649.05      3715742.77     10620766.59
      3715436.89     10620755.84
#Sta/Elev= 30
  4842.8  291.93  4874.8  290.69  4890.2  290.75  4911.4  289.84  4944.5  289.69
    4976  289.43  4984.7  289.19  4990.6  288.49    4997   287.1  4999.8   286.6
    5003   287.1    5006  287.37  5011.9   288.8  5034.8  289.35  5048.5  289.49
    5058  288.98  5063.9  289.56  5079.5  289.84  5099.5  289.24  5105.3   288.7
  5139.5  287.83  5149.5   287.1  5159.5  288.72  5169.6  289.47  5229.6  290.05
  5259.6  291.31  5269.6  292.53  5279.6  292.21  5319.6  292.71  5372.4  291.59
#Mann= 4 ,-1 , 0
  4842.8     .05       0  4944.5     .12       0    4997     .07       0
    5003     .12       0
Bank Sta=4976,5034.8
XS Rating Curve= 0 ,0
Exp/Cntr=0.3,0.1

Type RM Length L Ch R = 1 ,6260    ,344,344,344
BEGIN DESCRIPTION:
Mapping XS 783117b8
END DESCRIPTION:
XS GIS Cut Line= 3
      3715945.92     10620391.24      3715609.98     10620448.53
      3715474.09     10620551.52
#Sta/Elev= 30
  4824.7  289.52  4841.3  289.48  4852.3  290.67  4907.4  290.37  4912.5  291.06
  4962.5  289.44  4967.6  289.99  4973.1   289.7  4992.9   285.7  5000.6   283.7
  5003.3   283.2  5006.6   283.7  5013.7  285.46  5022.7  289.68  5044.1  290.67
  5094.9  290.12  5125.3  290.81  5135.4  290.06  5156.8   290.1  5163.1  290.51
  5174.4  289.94  5188.9  290.18  5209.8  289.35  5216.2  288.31  5238.9  288.63
  5245.1  289.31  5288.8  288.42  5295.1  289.04  5316.5  288.63    5336  289.06
#Mann= 5 ,-1 , 0
  4824.7     .05       0  4992.9     .12       0  5000.6     .07       0
  5006.6     .12       0  5156.8     .16       0
Bank Sta=5000.6,5006.6
XS Rating Curve= 0 ,0
Exp/Cntr=0.3,0.1

Type RM Length L Ch R = 1 ,5916    ,78,78,78
BEGIN DESCRIPTION:
Mapping XS e20a494d
END DESCRIPTION:
XS GIS Cut Line= 2
      3715680.27     10620052.74      3715534.81     10620325.47
#Sta/Elev= 30
  4882.8  289.68  4890.2  289.64  4895.9  288.73  4902.6  289.08  4912.2  288.94
  4947.9  287.75  4971.3  285.86  4983.7  284.41  4993.2  278.77    5000  276.15
  5002.7  276.03  5005.4  275.53  5008.7  276.03  5015.9   280.7  5027.6  283.22
  5038.2  284.28  5049.9  287.71  5060.2  287.73  5065.9  288.47  5072.6   288.4
  5095.2  289.26  5109.8  288.85  5117.9  289.18  5131.7  288.77  5140.6  289.28
  5153.7  288.93  5163.2  289.21    5170  288.89  5175.7  289.15  5191.9  288.93
#Mann= 4 ,-1 , 0
  4882.8     .05       0  4971.3     .12       0  5002.7     .07       0
  5008.7     .12       0
Bank Sta=5002.7,5008.7
XS Rating Curve= 0 ,0
Exp/Cntr=0.3,0.1

Type RM Length L Ch R = 1 ,5838    ,58,58,58
BEGIN DESCRIPTION:
Mapping XS dac86d27
END DESCRIPTION:
XS GIS Cut Line= 5
       3715659.3      10620006.8      3715516.91     10620163.08
      3715378.02     10620364.47      3715376.29      10620366.2
      3715355.46     10620400.92
#Sta/Elev= 30
  4868.9  289.09  4892.2  287.68  4906.4  287.67  4927.6  285.86  4941.6  285.38
    4949  286.06  4963.2  285.99  4979.1  284.33  4984.1  283.24  4991.6   275.8
  4998.3  275.89  5002.8  274.52  5005.5  274.02  5008.8  274.52  5012.5  275.57
  5019.9  282.85  5034.1  284.26  5040.9  287.17  5089.7  287.57  5113.3  286.85
  5119.5   287.4  5161.8  287.08  5170.2  287.69  5212.1  287.13  5230.1   287.7
  5271.2  287.51  5307.4  284.81  5343.7   285.9  5349.8  286.91  5367.9  287.51
#Mann= 5 ,-1 , 0
  4868.9     .05       0  4979.1     .12       0  5002.8     .07       0
  5008.8     .12       0  5230.1     .16       0
Bank Sta=5002.8,5008.8
XS Rating Curve= 0 ,0
Exp/Cntr=0.3,0.1

Type RM Length L Ch R = 1 ,5780    ,107,107,107
BEGIN DESCRIPTION:
Mapping XS 99cc678c
END DESCRIPTION:
XS GIS Cut Line= 3
       3715596.8     10619984.23      3715454.41     10620163.08
      3715299.86     10620331.52
#Sta/Elev= 30
  4908.1  287.64  4939.3  286.52  4945.7  285.75  4953.7  285.87  4960.1  284.61
  4974.5  283.83    4989  280.41  4992.3  271.01  4995.1  270.51  4998.3  271.01
  5009.8  278.81  5017.8  281.23    5045  284.97  5067.4  286.36  5117.1  285.75
  5136.5  284.21  5145.4  284.63  5173.5  284.09  5180.5  284.55  5201.5  283.42
  5230.1  283.46  5258.2  283.52  5265.6  284.17  5286.6  283.35    5294  283.62
    5315  282.49  5322.3  278.38  5336.4  282.54  5357.5  284.27  5365.3   284.2
#Mann= 4 ,-1 , 0
  4908.1     .05       0  4992.3     .07       0  4998.3     .05       0
  5230.1     .16       0
Bank Sta=4992.3,4998.3
XS Rating Curve= 0 ,0
Exp/Cntr=0.3,0.1

Type RM Length L Ch R = 1 ,5673    ,92,92,92
BEGIN DESCRIPTION:
Mapping XS 70fc2c74
END DESCRIPTION:
XS GIS Cut Line= 3
       3715501.3     10619975.55      3715388.44     10620123.15
      3715223.18     10620281.52
#Sta/Elev= 30
  4916.9  286.39  4949.3  284.92  4957.5  281.92  4962.6  282.06  4985.7     279
  4992.9  271.09  5013.7  269.96  5021.9  276.94  5028.2  276.96    5036  272.72
    5049  268.32  5075.1  266.92  5077.8  266.42  5081.1  266.92  5086.3  267.79
  5097.7  276.39  5106.8  275.12  5114.1  279.56    5121   279.3  5128.2  280.77
  5142.4  281.57  5149.3  281.17  5163.4  283.17  5184.5  283.18  5191.7  284.69
  5198.7  283.39  5212.8  283.42    5220  284.54  5245.5  283.55  5331.6  282.16
#Mann= 5 ,-1 , 0
  4916.9     .05       0  4962.6     .12       0  5075.1     .07       0
  5081.1     .12       0  5245.5     .16       0
Bank Sta=5075.1,5081.1
XS Rating Curve= 0 ,0
Exp/Cntr=0.3,0.1

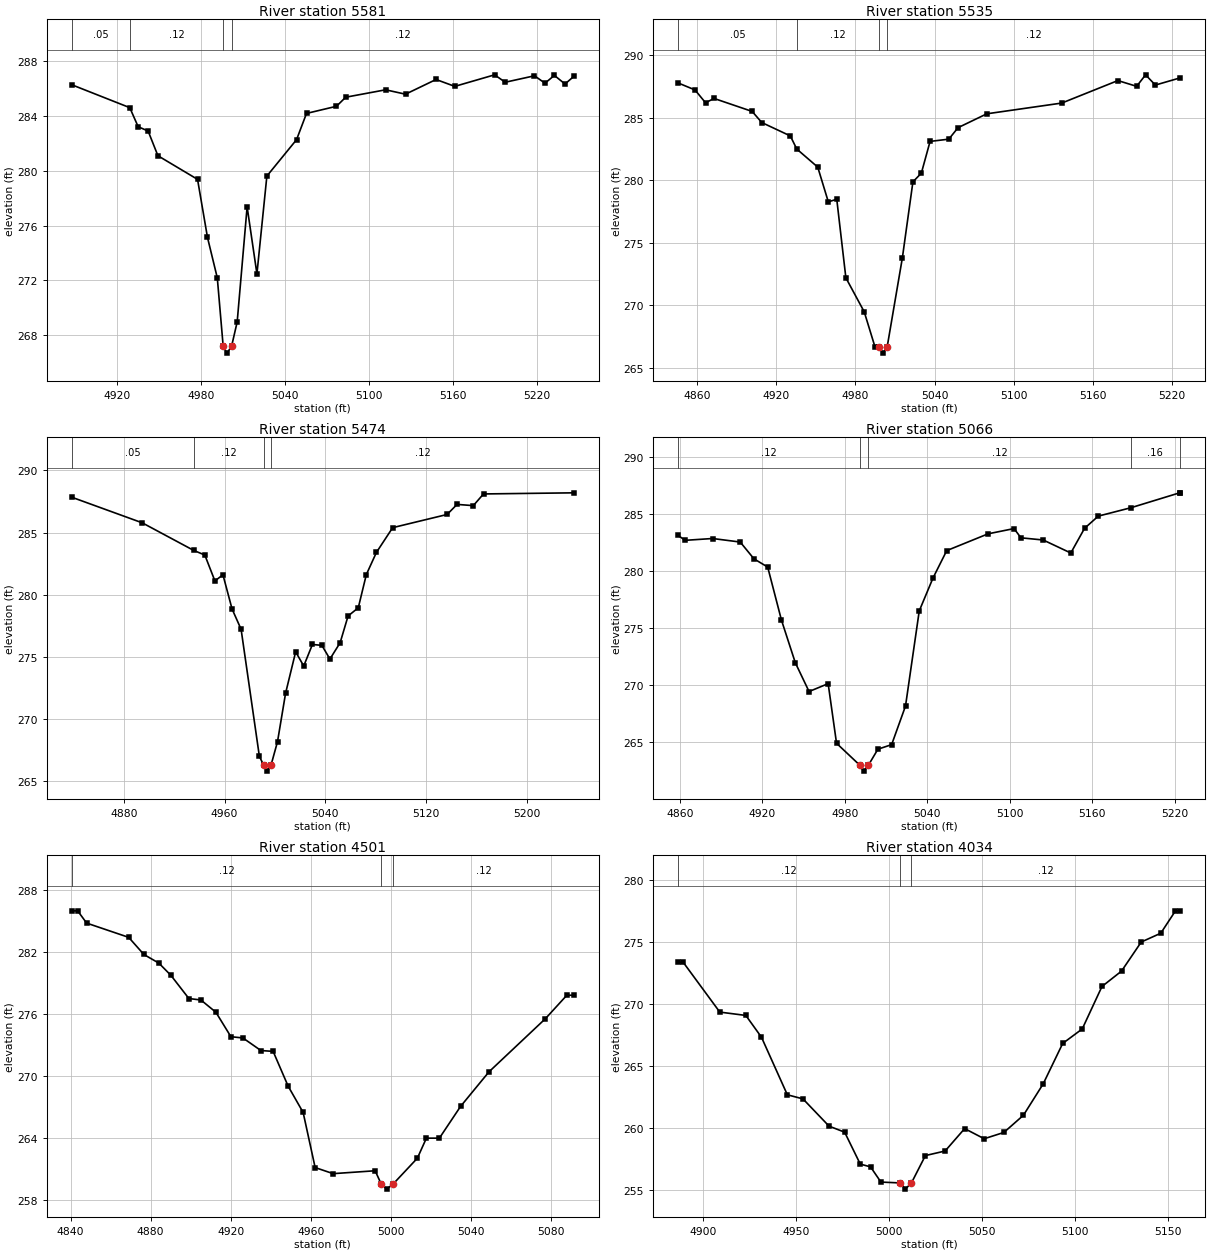
Type RM Length L Ch R = 1 ,5581    ,46,46,46
BEGIN DESCRIPTION:
Mapping XS 1d831617
END DESCRIPTION:
XS GIS Cut Line= 3
      3715459.59     10619963.02      3715334.62     10620086.69
      3715214.07     10620224.08
#Sta/Elev= 30
  4887.5  286.25    4929  284.58    4935  283.19  4942.1  282.88  4949.1  281.08
  4977.4  279.36  4984.5  275.13  4991.5  272.19  4995.7  267.21  4998.4  266.71
  5001.7  267.21  5005.7  268.98  5012.8  277.36  5019.8  272.48  5026.9   279.6
  5048.1  282.25  5055.2  284.16  5076.6  284.68  5083.2  285.34  5111.7  285.88
  5125.9  285.56  5147.7  286.63  5161.1  286.13  5189.5  286.97  5197.1  286.43
    5218   286.9  5225.5  286.36  5232.2  286.93  5239.8   286.3  5246.1  286.86
#Mann= 4 ,-1 , 0
  4887.5     .05       0    4929     .12       0  4995.7     .07       0
  5001.7     .12       0
Bank Sta=4995.7,5001.7
XS Rating Curve= 0 ,0
Exp/Cntr=0.3,0.1

Type RM Length L Ch R = 1 ,5535    ,61,61,61
BEGIN DESCRIPTION:
Mapping XS 08116601
END DESCRIPTION:
XS GIS Cut Line= 3
      3715438.81     10619900.46      3715305.97     10620068.46
      3715193.64     10620191.12
#Sta/Elev= 30
  4845.7   287.8  4858.5  287.24  4866.5  286.21  4872.9  286.56  4901.8  285.52
  4909.1  284.63  4930.7  283.56  4935.6  282.51  4951.5  281.06  4959.5  278.28
  4965.9  278.49  4972.8   272.2  4986.7  269.48  4994.8  266.69  4998.1  266.67
  5000.9  266.17  5004.1  266.67  5015.6  273.79  5023.6  279.88    5030  280.58
  5036.6  283.12  5050.8   283.3  5057.8  284.22  5079.6  285.33  5136.4  286.19
  5178.9  287.99  5193.1  287.53  5199.9  288.45  5207.3  287.63  5226.2  288.21
#Mann= 4 ,-1 , 0
  4845.7     .05       0  4935.6     .12       0  4998.1     .07       0
  5004.1     .12       0
Bank Sta=4998.1,5004.1
XS Rating Curve= 0 ,0
Exp/Cntr=0.3,0.1

Type RM Length L Ch R = 1 ,5474    ,408,408,408
BEGIN DESCRIPTION:
UNT 135 IN BOCR 10.0
END DESCRIPTION:
XS GIS Cut Line= 2
      3715388.64     10619870.38      3715141.23      10620182.9
#Sta/Elev= 30
  4838.6  287.85  4894.6  285.79  4935.5  283.57  4944.3   283.2  4952.3  281.12
  4958.7  281.61  4965.9  278.87  4973.1  277.23  4987.6  267.02  4990.9  266.33
  4993.7  265.83  4996.9  266.33    5002   268.2  5008.4  272.09  5016.4  275.42
  5022.8  274.28  5029.7  276.01  5037.2  275.94  5043.6  274.84  5051.7  276.15
    5058   278.3  5066.1  278.96  5072.5  281.63  5080.5  283.41  5093.4   285.4
  5136.6  286.46  5144.5  287.27  5157.4  287.17  5165.5  288.11  5237.2   288.2
#Mann= 4 ,-1 , 0
  4838.6     .05       0  4935.5     .12       0  4990.9     .07       0
  4996.9     .12       0
Bank Sta=4990.9,4996.9
XS Rating Curve= 0 ,0
Exp/Cntr=0.3,0.1

Type RM Length L Ch R = 1 ,5066    ,565,565,565
BEGIN DESCRIPTION:
UNT 135 IN BOCR 9.0
END DESCRIPTION:
XS GIS Cut Line= 2
      3715164.65     10619797.49      3714800.08     10619823.53
#Sta/Elev= 30
  4858.7  283.12  4863.8  282.69  4883.8  282.85  4903.9  282.54  4913.9  281.07
  4923.9  280.35  4933.9  275.71    4944  271.97    4954  269.45  4967.9  270.14
    4974  264.92  4991.1  262.98  4993.8  262.48  4997.1  262.98  5004.1   264.4
  5014.1   264.8  5024.2  268.18  5034.2  276.51  5044.2  279.39  5054.2  281.79
  5084.3  283.26  5103.2  283.72  5108.2  282.91  5124.4  282.72  5144.5  281.58
  5154.5  283.74  5164.5  284.81  5188.4  285.55  5223.7  286.85  5224.2  286.85
#Mann= 5 ,-1 , 0
  4858.7     .12       0  4991.1     .07       0  4997.1     .12       0
  5188.4     .16       0  5223.7     .12       0
Bank Sta=4991.1,4997.1
XS Rating Curve= 0 ,0
Exp/Cntr=0.3,0.1

Type RM Length L Ch R = 1 ,4501    ,467,467,467
BEGIN DESCRIPTION:
UNT 135 IN BOCR 8.0
END DESCRIPTION:
XS GIS Cut Line= 3
      3715199.61     10619360.19      3715049.61     10619460.19
       3714999.6     10619510.19
#Sta/Elev= 30
  4840.5  286.03  4843.5  286.03    4848  284.84    4869  283.46  4876.6   281.8
  4884.1  280.96  4890.1  279.78  4899.1  277.53  4905.1  277.39  4912.6   276.2
  4920.1  273.83  4926.1  273.71  4935.1  272.49  4941.2  272.41  4948.7  269.04
  4956.2  266.49  4962.2  261.15  4971.2  260.56  4992.2  260.84  4995.2  259.56
    4998  259.06  5001.2  259.56  5013.3  262.06  5017.8     264  5024.3     264
  5034.9  267.08  5049.1  270.43  5077.3  275.58    5088  277.85  5091.5  277.85
#Mann= 3 ,-1 , 0
  4840.5     .12       0  4995.2     .07       0  5001.2     .12       0
Bank Sta=4995.2,5001.2
XS Rating Curve= 0 ,0
Exp/Cntr=0.3,0.1

Type RM Length L Ch R = 1 ,4034    ,655,655,655
BEGIN DESCRIPTION:
UNT 135 IN BOCR 7.0
END DESCRIPTION:
XS GIS Cut Line= 3
      3715099.63      10619060.2      3714999.61     10619010.19
      3714849.65     10619060.17
#Sta/Elev= 30
  4886.8  273.37  4889.6  273.37  4909.2  269.36  4923.2  269.09  4931.6  267.33
  4945.5  262.68  4953.9  262.35  4967.9  260.15  4976.3  259.66  4984.7  257.08
  4990.2  256.86  4995.8  255.63  5006.2  255.56  5008.9  255.06  5012.2  255.56
  5019.7  257.77  5030.3  258.14  5040.8  259.95  5051.3  259.13  5061.9  259.64
  5072.4  261.03    5083  263.56  5093.5  266.83    5104     268  5114.6  271.43
  5125.1  272.67  5135.7  275.02  5146.2  275.73  5154.1  277.54  5156.7  277.54
#Mann= 3 ,-1 , 0
  4886.8     .12       0  5006.2     .07       0  5012.2     .12       0
Bank Sta=5006.2,5012.2
XS Rating Curve= 0 ,0
Exp/Cntr=0.3,0.1

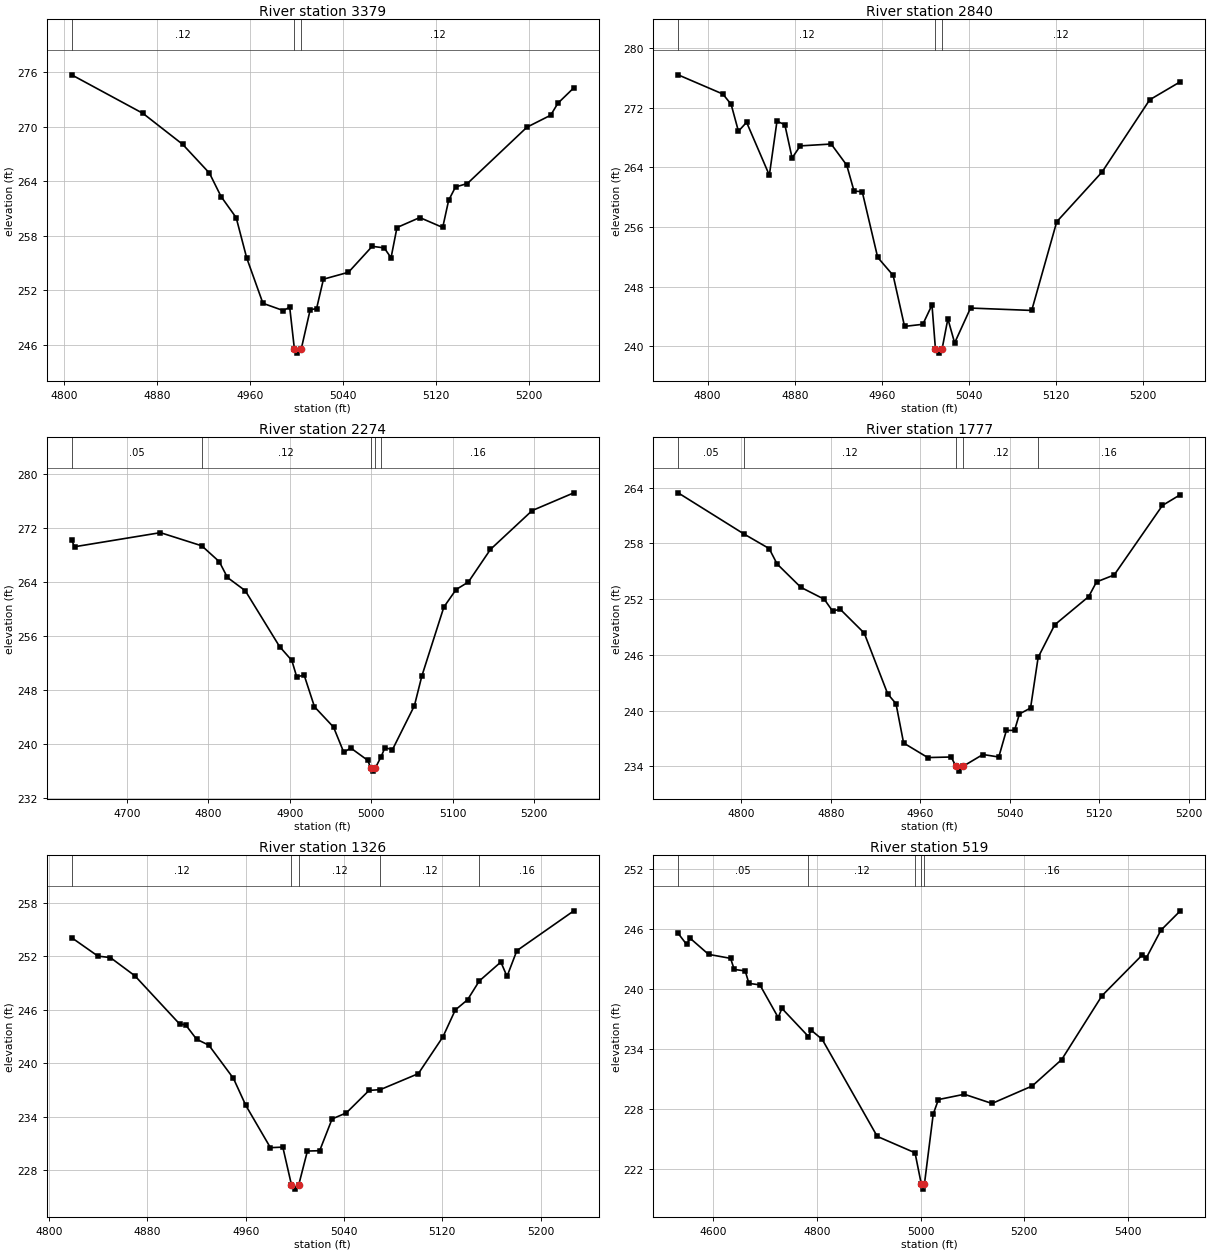
Type RM Length L Ch R = 1 ,3379    ,539,539,539
BEGIN DESCRIPTION:
UNT 135 IN BOCR 6.0
END DESCRIPTION:
XS GIS Cut Line= 3
       3715146.4     10618672.48       3714935.5     10618576.14
      3714740.16     10618617.81
#Sta/Elev= 30
  4806.7  275.73    4868  271.48  4902.1  268.07  4925.1   264.9  4935.1  262.32
  4948.1  259.99  4957.1  255.57  4971.1  250.55  4988.6  249.75  4994.1  250.12
  4998.1  245.56  5000.8  245.06  5004.1  245.56  5011.7  249.84  5017.2  249.97
  5023.1  253.21  5044.6  253.97    5065  256.83  5075.3  256.66  5081.2  255.57
  5086.3   258.9  5105.9     260  5125.6  258.91  5130.7   261.9  5136.6  263.37
  5146.8  263.75    5198  269.96  5218.4  271.28  5224.6   272.6  5238.3   274.3
#Mann= 3 ,-1 , 0
  4806.7     .12       0  4998.1     .07       0  5004.1     .12       0
Bank Sta=4998.1,5004.1
XS Rating Curve= 0 ,0
Exp/Cntr=0.3,0.1

Type RM Length L Ch R = 1 ,2840    ,566,566,566
BEGIN DESCRIPTION:
UNT 135 IN BOCR 5.0
END DESCRIPTION:
XS GIS Cut Line= 3
      3715357.44     10618550.68      3715199.61     10618410.19
      3714999.61     10618260.19
#Sta/Elev= 30
  4772.9  276.43    4814  273.85  4821.6  272.47  4828.3  268.86  4835.8  270.06
  4856.7  262.95  4863.7  270.19  4870.9  269.75  4877.6  265.27  4885.1  266.89
  4913.5  267.14  4927.8   264.3  4934.5  260.82    4942  260.75  4956.2  251.93
  4970.4  249.51  4980.9  242.66  4997.7  242.94  5006.1  245.54  5009.3  239.57
  5012.1  239.07  5015.3  239.57  5020.7  243.68  5026.9  240.44  5041.5  245.12
  5097.7   244.8  5120.7  256.71  5162.3  263.38  5206.1  273.08  5234.2   275.5
#Mann= 3 ,-1 , 0
  4772.9     .12       0  5009.3     .07       0  5015.3     .12       0
Bank Sta=5009.3,5015.3
XS Rating Curve= 0 ,0
Exp/Cntr=0.3,0.1

Type RM Length L Ch R = 1 ,2274    ,497,497,497
BEGIN DESCRIPTION:
UNT 135 IN BOCR 4.0
END DESCRIPTION:
XS GIS Cut Line= 3
      3715449.99     10617864.73      3715268.52     10617957.36
       3714923.7     10618184.59
#Sta/Elev= 30
  4632.3  270.22  4635.8  269.24  4741.3  271.33  4792.1  269.38  4813.6  267.03
  4823.6  264.69  4845.5  262.73  4887.6  254.46  4902.7  252.39  4908.7  249.96
  4917.8  250.23  4930.5  245.53  4953.9  242.52  4966.5  238.78    4975  239.43
    4996  237.59  4999.4   236.5  5002.2     236  5005.4   236.5  5012.3  238.14
  5017.1  239.48  5026.2  239.17  5053.2  245.69  5062.3  250.07  5089.4  260.31
  5104.4   262.9  5119.5  264.02  5146.6  268.85  5197.8   274.6    5249  277.23
#Mann= 5 ,-1 , 0
  4632.3     .05       0  4792.1     .12       0  4999.4     .07       0
  5005.4     .12       0  5012.3     .16       0
Bank Sta=4999.4,5005.4
XS Rating Curve= 0 ,0
Exp/Cntr=0.3,0.1

Type RM Length L Ch R = 1 ,1777    ,451,451,451
BEGIN DESCRIPTION:
UNT 135 IN BOCR 3.0
END DESCRIPTION:
XS GIS Cut Line= 3
      3715104.79     10617620.39      3714878.21     10617828.74
      3714807.88     10617951.16
#Sta/Elev= 30
  4743.5  263.45  4802.5  259.01  4824.9  257.45    4832  255.79  4853.2  253.28
  4874.2  251.99  4881.6  250.72  4888.4  250.92  4909.9  248.35  4930.9   241.8
  4938.3  240.75  4945.1  236.52  4966.7  234.95  4987.6  235.01    4992  233.99
  4994.8  233.49    4998  233.99    5016  235.28  5030.2  235.01    5037  237.87
  5044.3  237.88  5048.7  239.65  5058.6  240.28  5065.4  245.74  5080.2  249.24
  5110.6  252.28  5117.6  253.86  5133.4  254.61  5176.5  262.09  5192.5  263.25
#Mann= 5 ,-1 , 0
  4743.5     .05       0  4802.5     .12       0    4992     .07       0
    4998     .12       0  5065.4     .16       0
Bank Sta=4992,4998
XS Rating Curve= 0 ,0
Exp/Cntr=0.3,0.1

Type RM Length L Ch R = 1 ,1326    ,807,807,807
BEGIN DESCRIPTION:
UNT 135 IN BOCR 2.0
END DESCRIPTION:
XS GIS Cut Line= 2
      3715010.97     10617471.97      3714603.36     10617440.81
#Sta/Elev= 30
  4818.3  254.09  4839.7  252.02  4849.8  251.86  4869.8  249.81  4906.1  244.42
  4911.1  244.31    4920   242.7    4930  242.03    4950  238.31  4960.1  235.27
  4980.1  230.54  4990.2   230.6  4997.2  226.39  4999.9  225.89  5003.2  226.39
  5010.2  230.16  5020.2   230.2  5030.3  233.76  5041.9  234.44  5060.4  236.96
  5069.6  237.05  5100.5  238.84  5120.5  242.96  5130.6  245.98  5140.6  247.13
  5150.1  249.23  5167.7  251.36  5172.7  249.74  5180.7  252.63  5227.1   257.1
#Mann= 5 ,-1 , 0
  4818.3     .12       0  4997.2     .07       0  5003.2     .12       0
  5069.6     .12       0  5150.1     .16       0
Bank Sta=4997.2,5003.2
XS Rating Curve= 0 ,0
Exp/Cntr=0.3,0.1

Type RM Length L Ch R = 1 ,519     ,0,0,0
BEGIN DESCRIPTION:
UNT 135 IN BOCR 1.0
END DESCRIPTION:
XS GIS Cut Line= 4
      3715336.52     10617206.33      3715050.08     10616925.09
      3714870.39     10616917.28       3714582.7     10617176.46
#Sta/Elev= 30
  4532.3  245.58  4548.6  244.48  4555.7  245.08    4591  243.48  4633.5  243.08
  4640.5  241.97  4661.7  241.83  4668.8  240.58    4690  240.43  4725.3  237.17
  4732.5  238.08  4783.6  235.27    4789   235.9  4810.2  234.98  4916.3  225.29
  4989.2  223.65  5001.3  220.52    5004  220.02  5007.3  220.52  5024.3  227.52
  5034.3  228.97  5084.3   229.5  5137.6  228.58  5215.3  230.33  5272.1  232.97
  5349.8  239.35  5427.6  243.43    5435   243.1  5463.4  245.89  5500.8  247.83
#Mann= 5 ,-1 , 0
  4532.3     .05       0  4783.6     .12       0  4989.2     .16       0
  5001.3     .07       0  5007.3     .16       0
Bank Sta=5001.3,5007.3
XS Rating Curve= 0 ,0
Exp/Cntr=0.3,0.1

Chan Stop Cuts=-1
Use User Specified Reach Order=0
Composite Channel Slope=5