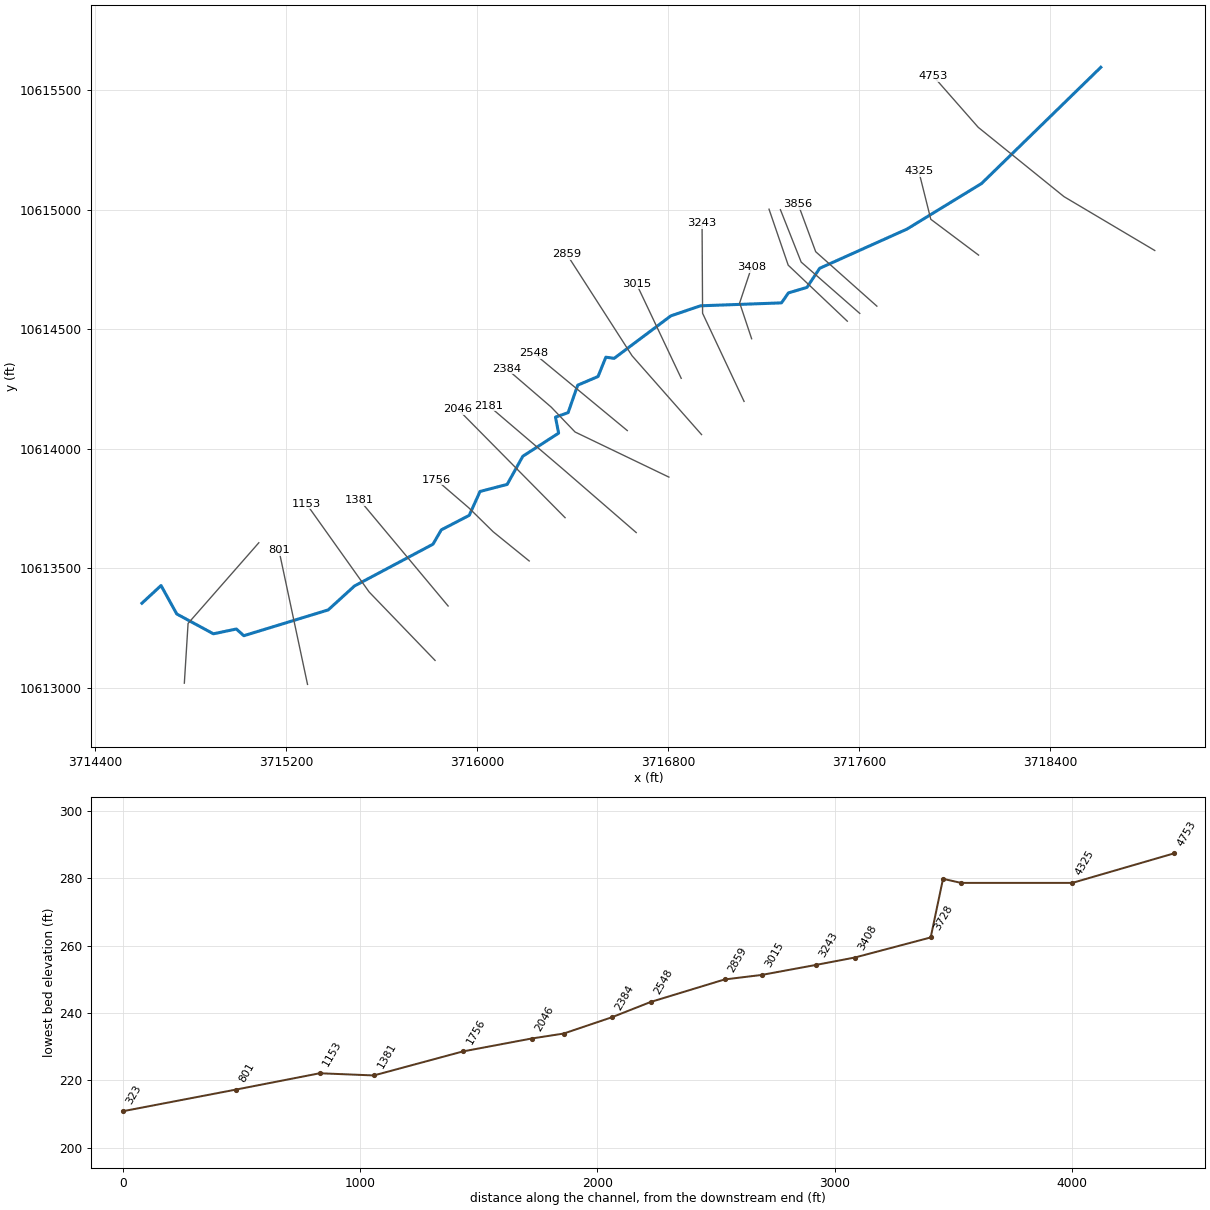
--- UNT 136 IN BOCR.prj (project) ---

Proj Title=UNT 136 IN BOCR Base Level Engineering
Current Plan=p01
Default Exp/Contr=0.3,0.1
English Units
Geom File=g01
Flow File=f01
Plan File=p01
Y Axis Title=Elevation
X Axis Title(PF)=Main Channel Distance
X Axis Title(XS)=Station
BEGIN DESCRIPTION:
UNT 136 IN BOCR
END DESCRIPTION:
DSS Export Rating Curves= 0
DSS Export Rating Curve Sorted= 0
DSS Export Volume Flow Curves= 0
DXF OffsetX= 0
DXF OffsetY= 0
DXF ScaleX= 1
DXF ScaleY= 10

--- UNT 136 IN BOCR.p01 (plan) ---

Plan Title=Multiple Run
Short Identifier=Multiple
Geom File=g01
Flow File=f01
Subcritical Flow
K Sum by GR= 0
Std Step Tol= 0.01
Critical Tol= 0.01
Num of Std Step Trials= 20
Max Error Tol= 0.3
Flow Tol Ratio= 0.001
Split Flow NTrial= 30
Split Flow Tol= 0.02
Split Flow Ratio= 0.02
Log Output Level= 0
Friction Slope Method= 1
Unsteady Friction Slope Method= 2
Unsteady Bridges Friction Slope Method= 1
Parabolic Critical Depth
Global Vel Dist=  1 , 1 , 1
Global Log Level= 0
CheckData=True
Encroach Param= -1, 0, 0, 0
BEGIN DESCRIPTION:
Multiple Run
END DESCRIPTION:

--- UNT 136 IN BOCR.f01 (steady flow) ---

Flow Title=Multiple
Program Version=4.10
Number of Profiles= 7
Profile Names=10-year,25-year,50-year,1pct_min,100-year,1pct_plu,500-year
River Rch & RM=UNT 136 IN BOCR,Reach-1         ,4753
     192     241     278     237     320     433     426
Boundary for River Rch & Prof#=UNT 136 IN BOCR,Reach-1         , 1
Up Type= 0
Dn Type= 3
Dn Slope=0.01
Boundary for River Rch & Prof#=UNT 136 IN BOCR,Reach-1         , 2
Up Type= 0
Dn Type= 3
Dn Slope=0.01
Boundary for River Rch & Prof#=UNT 136 IN BOCR,Reach-1         , 3
Up Type= 0
Dn Type= 3
Dn Slope=0.01
Boundary for River Rch & Prof#=UNT 136 IN BOCR,Reach-1         , 4
Up Type= 0
Dn Type= 3
Dn Slope=0.01
Boundary for River Rch & Prof#=UNT 136 IN BOCR,Reach-1         , 5
Up Type= 0
Dn Type= 3
Dn Slope=0.01
Boundary for River Rch & Prof#=UNT 136 IN BOCR,Reach-1         , 6
Up Type= 0
Dn Type= 3
Dn Slope=0.01
Boundary for River Rch & Prof#=UNT 136 IN BOCR,Reach-1         , 7
Up Type= 0
Dn Type= 3
Dn Slope=0.01
DSS Import GetInterval= 0
DSS Import GetPeak= 0
DSS Import FillOption= 0

--- UNT 136 IN BOCR.g01 (geometry) ---

Geom Title=Existing Conditions
Program Version=4.10

River Reach=UNT 136 IN BOCR ,Reach-1
Reach XY= 30
      3718611.25     10615596.31      3718112.25       10615110.
      3717799.75       10614919.       3717434.5       10614755.
      3717381.25       10614675.      3717303.75       10614652.
      3717274.55     10614610.17      3716935.75       10614598.
      3716811.75       10614556.      3716574.25       10614378.
      3716539.47     10614382.94      3716506.75       10614302.
       3716421.6     10614265.73       3716381.5     10614150.79
       3716328.5       10614132.      3716341.75       10614065.
      3716191.71     10613968.09      3716126.46     10613850.41
      3716012.66     10613820.72      3715967.62     10613720.81
      3715850.65     10613660.09      3715815.75       10613600.
        3715487.       10613425.      3715377.25       10613325.
        3715024.       10613217.      3714992.75       10613245.
       3714896.5       10613225.      3714743.25       10613308.
       3714677.5       10613427.       3714597.5       10613353.

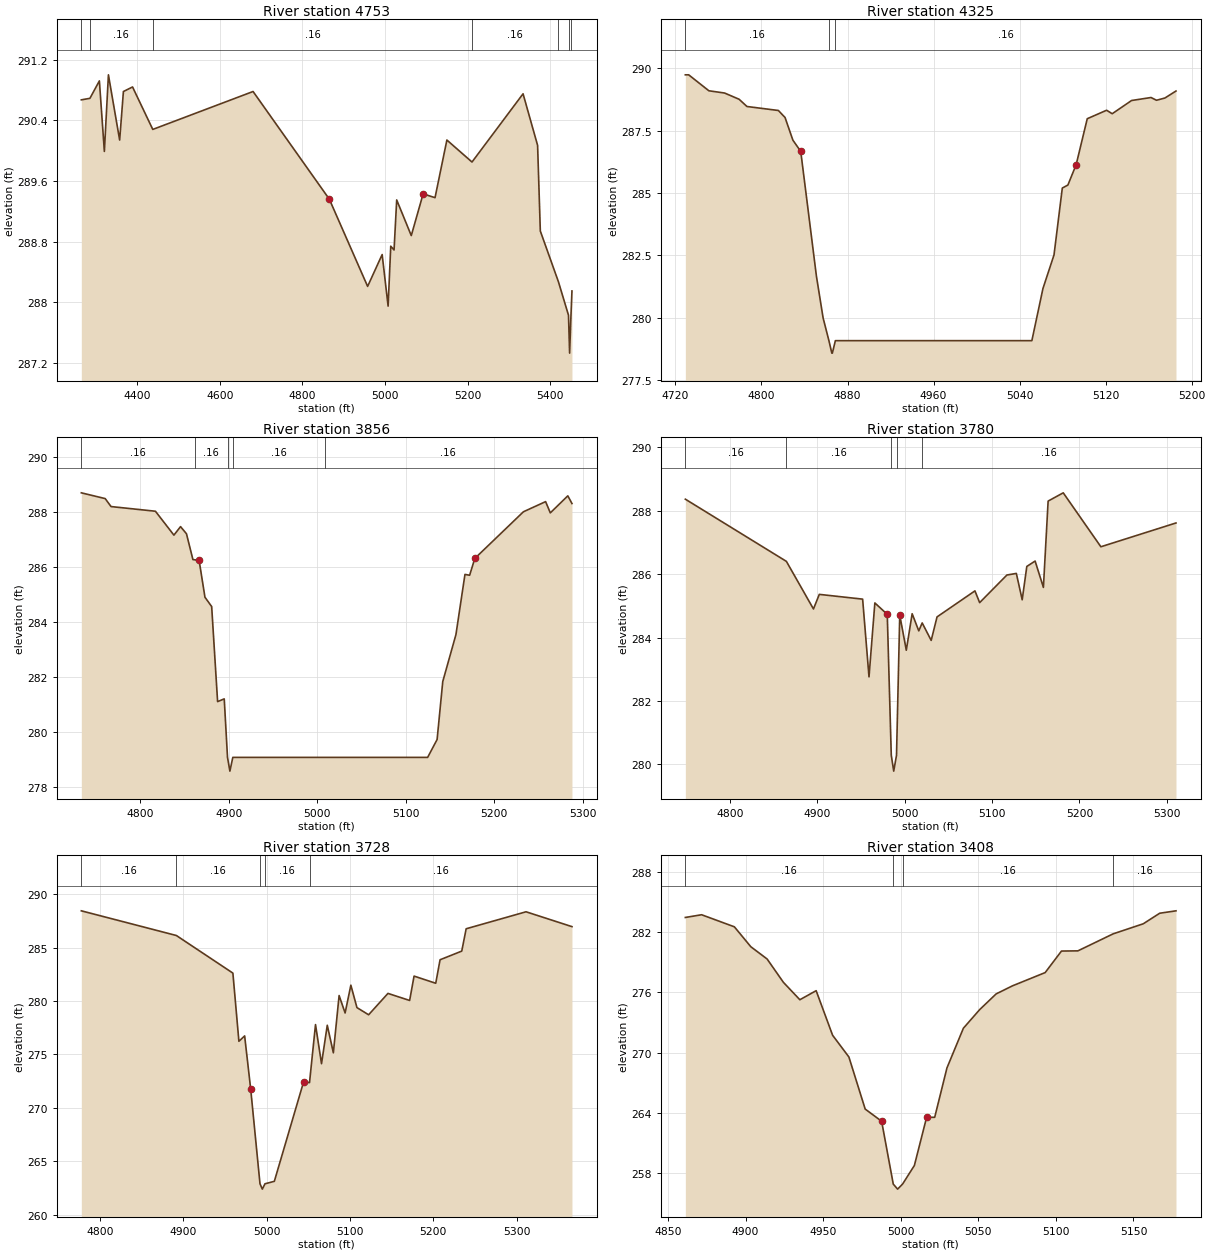
Type RM Length L Ch R = 1 ,4753    ,428,428,428
BEGIN DESCRIPTION:
UNT 136 IN BOCR 10.0
END DESCRIPTION:
XS GIS Cut Line= 4
      3718837.21     10614829.48      3718457.31     10615054.87
      3718097.96      10615345.3      3717910.51     10615558.69
#Sta/Elev= 30
  4264.6  290.67  4285.4  290.69  4308.3  290.92  4320.4  289.99  4330.2     291
  4357.4  290.14  4366.5  290.78  4388.6  290.84  4437.6  290.28  4680.4  290.78
    4865  289.36  4957.7  288.21  4992.9  288.63  5007.3  287.95  5013.7  288.74
  5021.7  288.69  5028.1  289.35  5063.4  288.88  5092.1  289.43  5120.9  289.38
  5149.6  290.14  5210.4  289.85    5334  290.75  5369.2  290.07  5375.8  288.94
  5419.7  288.27    5444  287.83  5446.7  287.33    5450  287.83  5452.4  288.15
#Mann= 7 ,-1 , 0
  4264.6     .16       0  4285.4     .16       0  4437.6     .16       0
  5210.4     .16       0  5419.7     .16       0    5444     .16       0
    5450     .16       0
Bank Sta=4865,5092.1
XS Rating Curve= 0 ,0
Exp/Cntr=0.3,0.1

Type RM Length L Ch R = 1 ,4325    ,469,469,469
BEGIN DESCRIPTION:
UNT 136 IN BOCR 9.0
END DESCRIPTION:
XS GIS Cut Line= 3
      3718099.61     10614810.19      3717899.61     10614960.19
       3717849.6     10615160.23
#Sta/Elev= 30
  4729.2  289.74  4732.3  289.74  4751.1   289.1  4765.7  289.01  4779.2  288.76
  4786.5  288.47  4815.7  288.31  4821.9  288.03  4829.2  287.12  4836.5  286.67
  4851.1  281.66  4857.3  279.99  4862.7  279.08  4865.4  278.58  4865.9  278.58
  4868.7  279.08  5051.4  279.08  5061.7  281.17    5072  282.52  5079.7   285.2
  5084.9  285.32  5092.6  286.14  5102.9  287.98  5120.9  288.32  5126.1  288.18
  5144.1  288.71  5162.2  288.83  5167.3  288.72  5175.1  288.81  5185.4  289.09
#Mann= 3 ,-1 , 0
  4729.2     .16       0  4862.7     .16       0  4868.7     .16       0
Bank Sta=4836.5,5092.6
XS Rating Curve= 0 ,0
Exp/Cntr=0.3,0.1

Type RM Length L Ch R = 1 ,3856    ,76,76,76
BEGIN DESCRIPTION:
Mapping XS 1a706725
END DESCRIPTION:
XS GIS Cut Line= 3
      3717673.91     10614596.52      3717417.81      10614824.4
      3717344.32     10615023.25
#Sta/Elev= 30
  4733.2  288.71  4760.2   288.5  4766.8  288.21    4817  288.04  4837.9  287.17
  4845.4  287.48  4852.1  287.22  4859.4  286.28  4861.9  286.27  4866.4  286.25
    4873  284.91  4880.6  284.57  4887.3  281.11  4894.8  281.21  4898.5  279.08
  4901.2  278.58  4904.5  279.08  5008.2  279.08  5124.8  279.08  5135.5  279.73
  5141.9  281.84  5156.8  283.55    5167  285.74  5172.3  285.71  5178.1  286.32
  5233.1  288.02  5258.2  288.39  5263.5  287.98  5283.3   288.6    5288  288.32
#Mann= 5 ,-1 , 0
  4733.2     .16       0  4861.9     .16       0  4898.5     .16       0
  4904.5     .16       0  5008.2     .16       0
Bank Sta=4866.4,5178.1
XS Rating Curve= 0 ,0
Exp/Cntr=0.3,0.1

Type RM Length L Ch R = 1 ,3780    ,52,52,52
BEGIN DESCRIPTION:
UNT 136 IN BOCR 8.0
END DESCRIPTION:
XS GIS Cut Line= 3
       3717602.3     10614566.13      3717357.05       10614781.
      3717270.24     10615000.17
#Sta/Elev= 30
  4748.8  288.36  4864.5   286.4  4895.5   284.9  4902.2  285.36  4951.8  285.21
  4959.1  282.76  4965.8  285.09    4980  284.73  4984.6  280.29  4987.4  279.79
  4990.6  280.29  4994.3  284.71  5001.8   283.6  5008.5  284.75  5016.1  284.21
    5020  284.46  5030.3  283.91    5037  284.65  5080.4  285.47  5085.8   285.1
    5117  285.97  5127.8  286.02  5134.5  285.19  5139.8  286.24  5149.3  286.41
  5158.8  285.58  5164.2   288.3  5181.5  288.56  5224.6  286.86  5310.6  287.61
#Mann= 5 ,-1 , 0
  4748.8     .16       0  4864.5     .16       0  4984.6     .16       0
  4990.6     .16       0    5020     .16       0
Bank Sta=4980,4994.3
XS Rating Curve= 0 ,0
Exp/Cntr=0.3,0.1

Type RM Length L Ch R = 1 ,3728    ,320,320,320
BEGIN DESCRIPTION:
Mapping XS cc3b6ad5
END DESCRIPTION:
XS GIS Cut Line= 3
      3717550.18     10614533.61      3717302.79     10614767.98
       3717222.5     10615002.33
#Sta/Elev= 30
  4777.8  288.44  4891.8  286.13  4959.6  282.61  4966.8  276.23  4973.7  276.73
    4981  271.72  4992.1  262.89  4994.9  262.39  4998.1  262.89  5009.3  263.12
  5044.5  272.45  5051.5  272.36  5058.7  277.79  5065.9  274.13  5072.8  277.73
  5080.1  275.15    5087  280.51  5094.2  278.88  5101.1  281.48  5108.4  279.38
  5122.4  278.71  5145.6  280.71  5171.6  280.05  5176.9  282.33  5202.9  281.66
  5208.1  283.86  5234.1  284.67  5239.4  286.76  5311.2  288.35  5366.3  286.96
#Mann= 5 ,-1 , 0
  4777.8     .16       0  4891.8     .16       0  4992.1     .16       0
  4998.1     .16       0  5051.5     .16       0
Bank Sta=4981,5044.5
XS Rating Curve= 0 ,0
Exp/Cntr=0.3,0.1

Type RM Length L Ch R = 1 ,3408    ,165,165,165
BEGIN DESCRIPTION:
UNT 136 IN BOCR 7.0
END DESCRIPTION:
XS GIS Cut Line= 3
      3717149.61     10614460.19      3717099.61     10614610.19
       3717149.6     10614760.17
#Sta/Elev= 30
  4861.2  283.44  4871.7  283.71  4892.8  282.51  4903.4  280.53  4913.9  279.31
  4924.4  276.99    4935  275.26  4945.5  276.16  4956.1  271.73  4966.6  269.57
  4977.1  264.39  4987.7  263.18  4995.2  256.93    4998  256.43  5001.2  256.93
  5008.8  258.78  5016.7  263.57  5021.9  263.57  5029.8  268.48  5040.4  272.43
  5050.9  274.28  5061.5  275.84    5072  276.64  5093.1  277.96  5103.6   280.1
  5114.2  280.12  5136.9  281.81  5156.3  282.81  5166.9  283.86  5177.4   284.1
#Mann= 4 ,-1 , 0
  4861.2     .16       0  4995.2     .16       0  5001.2     .16       0
  5136.9     .16       0
Bank Sta=4987.7,5016.7
XS Rating Curve= 0 ,0
Exp/Cntr=0.3,0.1

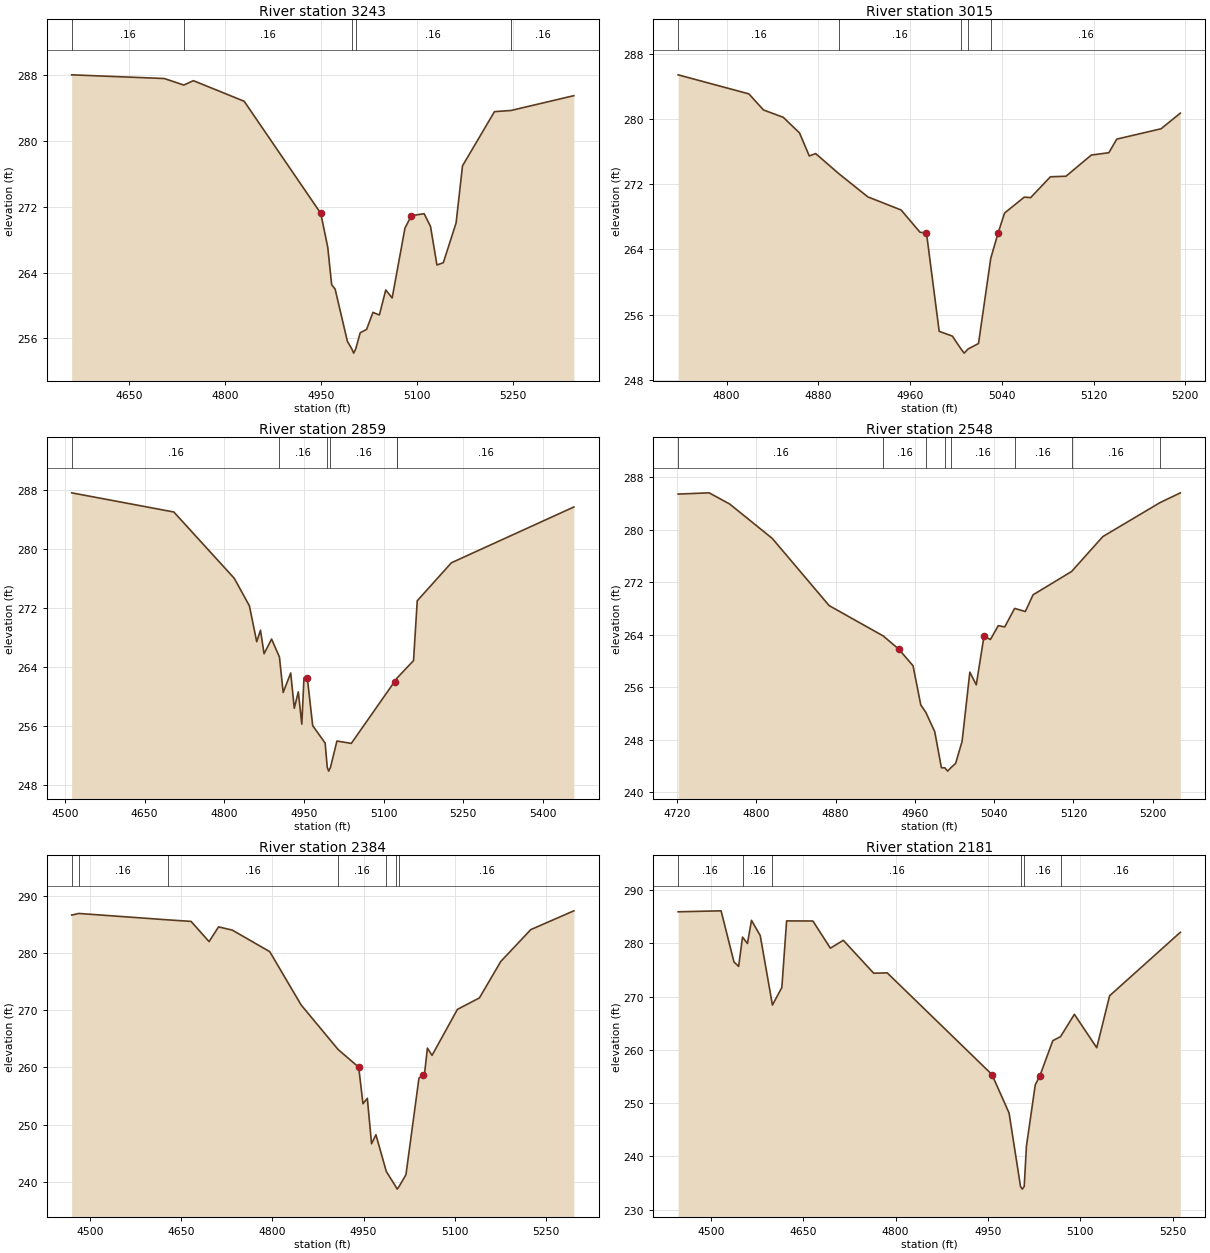
Type RM Length L Ch R = 1 ,3243    ,228,228,228
BEGIN DESCRIPTION:
Mapping XS cad7b0a8
END DESCRIPTION:
XS GIS Cut Line= 3
      3717117.97     10614197.78      3716944.36      10614566.7
      3716942.19     10614944.26
#Sta/Elev= 30
  4559.9  288.01  4704.7  287.56  4735.3  286.77  4750.3   287.3  4829.7   284.8
  4949.4   271.2  4960.4  267.07  4966.5  262.53  4971.9     262  4991.1  255.65
  4998.1  254.72  5000.9  254.22  5004.1  254.72  5011.1  256.69  5021.1   257.1
  5031.1  259.17  5041.1  258.85  5051.1  261.89  5061.1  260.92  5081.1  269.39
  5091.1  270.91  5111.1  271.15  5121.1   269.6  5131.1  264.92  5141.1   265.2
  5161.1  270.03  5171.1  276.96  5221.1  283.54  5246.9  283.68  5345.2  285.48
#Mann= 5 ,-1 , 0
  4559.9     .16       0  4735.3     .16       0  4998.1     .16       0
  5004.1     .16       0  5246.9     .16       0
Bank Sta=4949.4,5091.1
XS Rating Curve= 0 ,0
Exp/Cntr=0.3,0.1

Type RM Length L Ch R = 1 ,3015    ,156,156,156
BEGIN DESCRIPTION:
Mapping XS 6b624ea6
END DESCRIPTION:
XS GIS Cut Line= 2
      3716854.88     10614294.45      3716667.38     10614690.28
#Sta/Elev= 30
  4757.7  285.46  4819.4  283.12  4832.2  281.14  4849.4  280.24  4863.6  278.32
  4872.1  275.49  4877.7  275.78  4897.9  273.31  4923.2  270.46  4952.2  268.85
  4968.7  266.11  4974.3  266.04  4985.4  253.94  4996.9  253.35  5004.5  251.76
  5007.2  251.26  5010.5  251.76  5019.7  252.44  5030.4  262.93  5036.9  266.07
  5042.4  268.47  5059.6  270.43  5065.2  270.37  5082.4  272.93    5096     273
  5118.1   275.6  5133.4  275.89  5140.3  277.56  5178.9  278.83  5195.7  280.75
#Mann= 5 ,-1 , 0
  4757.7     .16       0  4897.9     .16       0  5004.5     .16       0
  5010.5     .16       0  5030.4     .16       0
Bank Sta=4974.3,5036.9
XS Rating Curve= 0 ,0
Exp/Cntr=0.3,0.1

Type RM Length L Ch R = 1 ,2859    ,311,311,311
BEGIN DESCRIPTION:
Mapping XS 784db718
END DESCRIPTION:
XS GIS Cut Line= 3
      3716940.05     10614058.86      3716649.22     10614388.75
       3716375.8     10614814.07
#Sta/Elev= 30
  4512.7  287.64  4705.1  285.04  4818.9  276.05  4847.3  272.33  4861.1  267.46
  4868.2  269.02  4874.9  265.83  4889.1  267.82  4903.9  265.38  4910.9  260.58
  4925.1  263.22  4931.8  258.44  4939.4  260.67    4946  256.29  4950.1  262.58
  4956.3  262.58  4966.5  256.08  4989.9  253.73  4993.9  250.42  4996.6  249.92
  4999.9  250.42  5012.1     254  5039.2  253.68  5120.6  262.05  5124.9   262.5
  5125.1  262.52  5156.3   264.9  5163.3  273.01  5227.6  278.16  5458.1  285.72
#Mann= 6 ,-1 , 0
  4512.7     .16       0  4903.9     .16       0  4993.9     .16       0
  4999.9     .16       0  5124.9     .16       0  5125.1     .16       0
Bank Sta=4956.3,5120.6
XS Rating Curve= 0 ,0
Exp/Cntr=0.3,0.1

Type RM Length L Ch R = 1 ,2548    ,164,164,164
BEGIN DESCRIPTION:
Mapping XS 60b9e75b
END DESCRIPTION:
XS GIS Cut Line= 2
       3716629.2     10614075.68      3716238.59     10614398.59
#Sta/Elev= 30
    4721  285.41  4752.3   285.6  4773.1  283.89  4816.1  278.65  4873.4  268.44
    4928  263.82  4943.7  261.81  4958.1  259.28  4965.9  253.32    4971  252.19
    4980  249.25  4986.7  243.77  4990.2  243.75    4993  243.25  4996.2  243.75
  5001.1  244.44  5007.6  247.79  5015.4  258.31  5021.9  256.38  5029.7  263.79
  5036.2  263.28  5044.1  265.39  5050.6  265.19  5060.6  268.01  5071.4  267.54
  5079.2  270.08  5118.1  273.63  5149.6  278.94  5207.3  284.11  5227.8  285.59
#Mann= 8 ,-1 , 0
    4721     .16       0    4928     .16       0    4971     .16       0
  4990.2     .16       0  4996.2     .16       0  5060.6     .16       0
  5118.1     .16       0  5207.3     .16       0
Bank Sta=4943.7,5029.7
XS Rating Curve= 0 ,0
Exp/Cntr=0.3,0.1

Type RM Length L Ch R = 1 ,2384    ,203,203,203
BEGIN DESCRIPTION:
Mapping XS f72f3abc
END DESCRIPTION:
XS GIS Cut Line= 4
      3716803.29     10613880.94       3716410.5     10614069.74
      3716310.68     10614173.91      3716124.34     10614334.24
#Sta/Elev= 30
    4470  286.68  4481.7  286.97  4628.1  285.85  4666.4  285.58    4696  282.04
  4711.6  284.62  4734.3  284.05  4795.8  280.28  4847.4  270.95  4908.2  263.15
  4942.1  260.05  4949.1  253.66  4956.3   254.6  4963.2  246.64  4970.4  248.23
  4987.5  241.79  5002.7   239.2  5005.4   238.7  5008.7   239.2  5019.8  241.23
  5041.2  258.14  5047.2  258.66  5050.1  258.66  5055.1  263.39  5062.7  262.12
  5104.4  270.17  5140.6  272.18  5175.8  278.57  5225.1  284.14  5295.9  287.43
#Mann= 7 ,-1 , 0
    4470     .16       0  4481.7     .16       0  4628.1     .16       0
  4908.2     .16       0  4987.5     .16       0  5002.7     .16       0
  5008.7     .16       0
Bank Sta=4942.1,5047.2
XS Rating Curve= 0 ,0
Exp/Cntr=0.3,0.1

Type RM Length L Ch R = 1 ,2181    ,135,135,135
BEGIN DESCRIPTION:
Mapping XS 0945048b
END DESCRIPTION:
XS GIS Cut Line= 3
      3716666.55     10613648.76      3716358.42     10613915.66
      3716048.07     10614180.44
#Sta/Elev= 30
  4446.7  285.92  4516.5   286.1  4537.4  276.51    4545  275.67  4551.3  281.17
  4559.3  279.97  4565.9  284.32  4580.1  281.45  4599.9  268.41  4615.2  271.73
  4622.9  284.21  4665.6  284.19    4694  279.09    4715  280.57  4764.4  274.39
  4786.3  274.46  4956.4  255.38  4984.2  248.16  5002.8  234.37  5005.6  233.87
  5008.8  234.37  5012.4  241.94  5026.7  253.42  5034.4  255.19  5055.2  261.73
  5067.8  262.49  5090.3  266.68  5126.6  260.41  5147.5  270.16  5262.3  282.07
#Mann= 6 ,-1 , 0
  4446.7     .16       0  4551.3     .16       0  4599.9     .16       0
  5002.8     .16       0  5008.8     .16       0  5067.8     .16       0
Bank Sta=4956.4,5034.4
XS Rating Curve= 0 ,0
Exp/Cntr=0.3,0.1

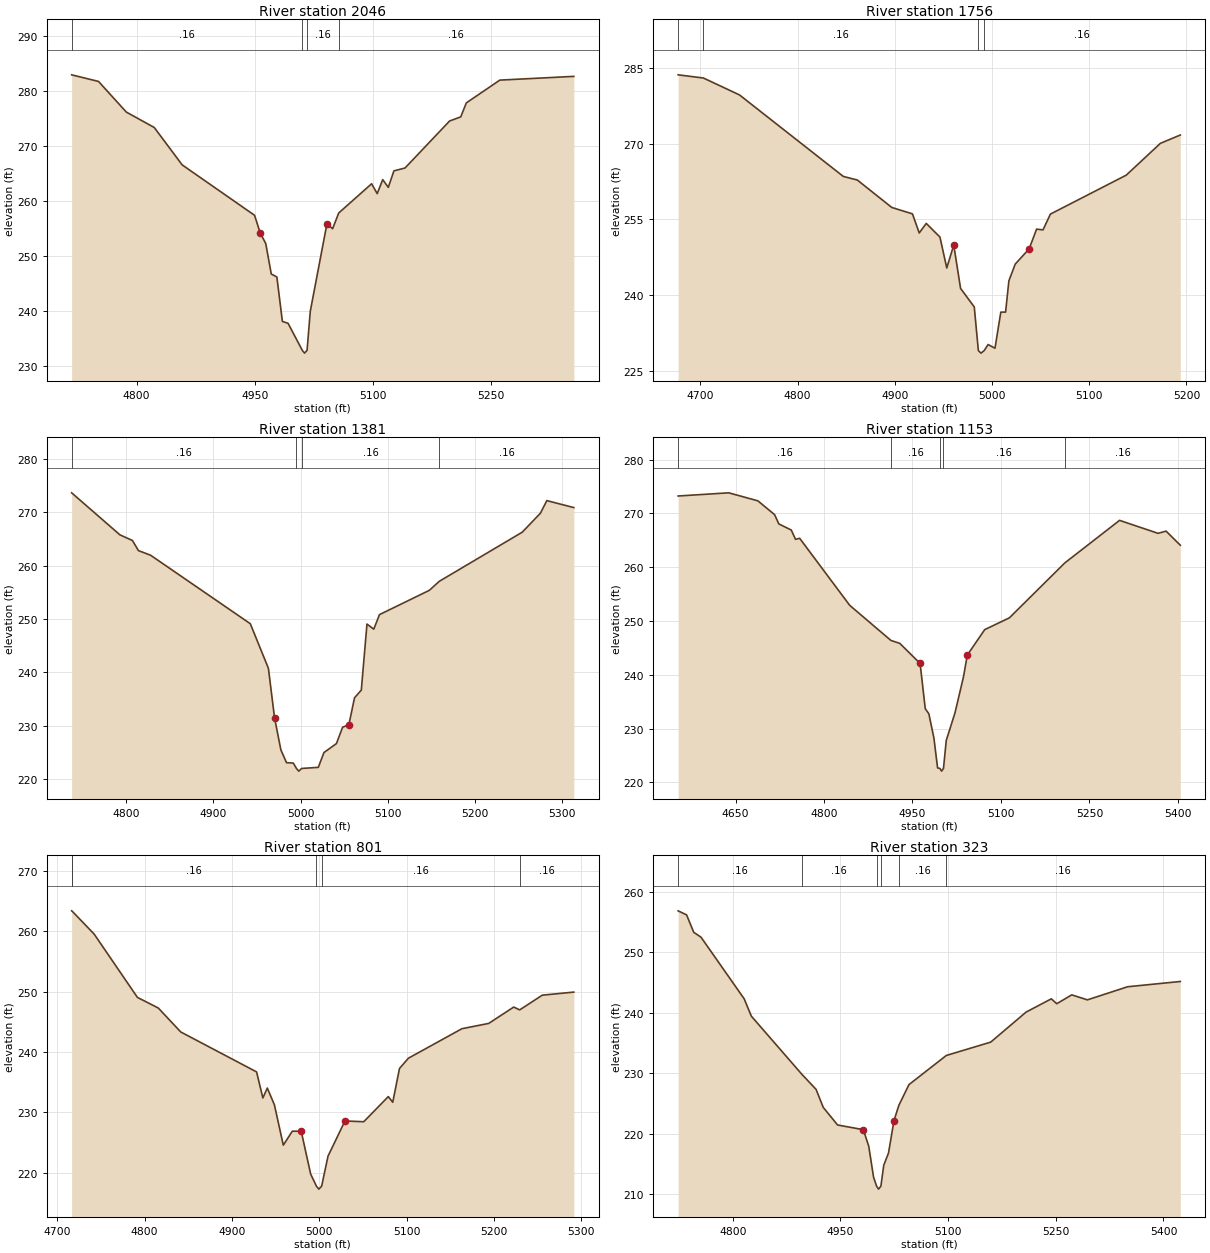
Type RM Length L Ch R = 1 ,2046    ,290,290,290
BEGIN DESCRIPTION:
Mapping XS 13aabd8a
END DESCRIPTION:
XS GIS Cut Line= 2
      3716368.78      10613711.1      3715920.83     10614164.27
#Sta/Elev= 30
  4717.5  282.88  4751.6  281.68  4786.9  276.12  4822.3  273.33  4857.7  266.55
  4949.6   257.4  4956.7  254.22  4963.8  252.27  4970.8  246.75  4977.9  246.21
  4984.9  238.15  4992.1  237.81  5010.2   232.9    5013   232.4  5016.2   232.9
  5020.3     240  5041.5  255.91  5048.6  254.96  5056.4  257.82  5098.1  263.12
  5105.2  261.33  5112.2  263.87  5119.3  262.47  5126.4  265.46  5140.5  265.98
  5197.1  274.51  5211.2  275.25  5218.3  277.79  5260.8  281.92  5354.7   282.6
#Mann= 4 ,-1 , 0
  4717.5     .16       0  5010.2     .16       0  5016.2     .16       0
  5056.4     .16       0
Bank Sta=4956.7,5041.5
XS Rating Curve= 0 ,0
Exp/Cntr=0.3,0.1

Type RM Length L Ch R = 1 ,1756    ,375,375,375
BEGIN DESCRIPTION:
Mapping XS da0ec4f6
END DESCRIPTION:
XS GIS Cut Line= 4
      3716218.63     10613529.84      3716067.62     10613652.21
      3715966.06     10613752.03      3715829.79     10613869.21
#Sta/Elev= 30
  4677.2  283.59  4703.2  282.96  4740.3  279.62  4847.1   263.5  4861.5  262.79
    4897  257.36  4918.2   256.1  4925.2  252.32  4932.4  254.21  4946.5  251.51
  4953.5   245.4  4960.7  249.93  4967.7  241.36  4981.8  237.69    4986  229.06
  4988.7  228.56    4992  229.06    4996  230.26  5003.1  229.53  5009.1  236.67
    5014  236.67  5017.4  242.86  5023.9  246.16  5038.2  249.17  5045.9  253.08
  5052.5  252.93  5060.1  256.05  5138.1  263.75  5173.2  270.04  5193.7  271.69
#Mann= 4 ,-1 , 0
  4677.2     .16       0  4703.2     .16       0    4986     .16       0
    4992     .16       0
Bank Sta=4960.7,5038.2
XS Rating Curve= 0 ,0
Exp/Cntr=0.3,0.1

Type RM Length L Ch R = 1 ,1381    ,228,228,228
BEGIN DESCRIPTION:
Mapping XS 0b34e648
END DESCRIPTION:
XS GIS Cut Line= 2
      3715879.17     10613341.34       3715509.4     10613784.02
#Sta/Elev= 30
  4737.1  273.66  4792.6  265.77  4806.9  264.72  4813.8  262.82  4827.8  261.95
  4942.3   249.1  4963.1  240.73  4970.1  231.49  4977.4  225.43  4983.9  223.03
  4991.7  222.95  4995.3  221.94    4998  221.44  5001.3  221.94  5020.4  222.15
  5026.9  224.93  5041.2   226.6  5048.3  229.67  5055.5  230.14    5062   235.2
  5069.8  236.65  5076.3  249.04  5084.1  248.08  5090.7  250.81  5147.9  255.36
  5159.4  257.06  5254.6  266.27  5275.5  269.83  5282.9   272.2  5313.9  270.89
#Mann= 4 ,-1 , 0
  4737.1     .16       0  4995.3     .16       0  5001.3     .16       0
  5159.4     .16       0
Bank Sta=4970.1,5055.5
XS Rating Curve= 0 ,0
Exp/Cntr=0.3,0.1

Type RM Length L Ch R = 1 ,1153    ,352,352,352
BEGIN DESCRIPTION:
Mapping XS 6b6aefa4
END DESCRIPTION:
XS GIS Cut Line= 3
      3715824.54     10613113.61      3715548.53     10613400.04
      3715285.48     10613769.86
#Sta/Elev= 30
  4552.6  273.25  4638.5  273.84  4687.9  272.35  4716.2  269.78  4723.4  268.06
  4744.5  266.92  4751.7  265.19  4758.7  265.39  4843.6  252.92  4913.5  246.39
  4928.5  245.85    4963  242.11  4971.7   233.7  4977.8  232.75  4986.4  228.23
  4992.6  222.69  4996.6  222.59  4999.4  222.09  5002.6  222.59  5007.3  227.79
  5022.1  232.92  5036.5  239.61    5043  243.67  5072.5   248.4  5114.3  250.59
  5208.4  260.81  5301.2  268.72  5366.4  266.31  5380.1  266.72  5404.2   264.1
#Mann= 5 ,-1 , 0
  4552.6     .16       0  4913.5     .16       0  4996.6     .16       0
  5002.6     .16       0  5208.4     .16       0
Bank Sta=4963,5043
XS Rating Curve= 0 ,0
Exp/Cntr=0.3,0.1

Type RM Length L Ch R = 1 ,801     ,478,478,478
BEGIN DESCRIPTION:
Mapping XS bec31ab8
END DESCRIPTION:
XS GIS Cut Line= 2
      3715290.65     10613013.16       3715170.9     10613575.45
#Sta/Elev= 30
  4716.6  263.39  4717.3  263.31  4742.4  259.53  4791.9  249.04  4815.8  247.28
  4841.5  243.31  4928.3  236.69  4935.5  232.37  4940.6  234.01  4948.7  231.24
  4958.9  224.55  4969.2  226.86  4979.4  226.86  4990.2  219.77  4996.8  217.76
  4999.6  217.26  5002.8  217.76  5010.1  222.73  5029.5  228.56    5051  228.43
  5079.1   232.6  5084.2  231.66  5091.9  237.25  5102.1  238.96  5163.4  243.85
  5194.1  244.73  5222.7  247.44  5229.5  246.97  5255.4  249.41  5291.5  249.92
#Mann= 5 ,-1 , 0
  4716.6     .16       0  4717.3     .16       0  4996.8     .16       0
  5002.8     .16       0  5229.5     .16       0
Bank Sta=4979.4,5029.5
XS Rating Curve= 0 ,0
Exp/Cntr=0.3,0.1

Type RM Length L Ch R = 1 ,323     ,0,0,0
BEGIN DESCRIPTION:
UNT 136 IN BOCR 1.0
END DESCRIPTION:
XS GIS Cut Line= 3
      3714775.01     10613018.39      3714790.64     10613268.41
      3715086.74     10613606.07
#Sta/Elev= 30
  4723.9  256.86  4735.7  256.19  4745.7   253.3  4755.8   252.5  4815.9  242.31
  4825.9  239.44  4896.3  229.82  4916.1  227.32  4926.1  224.34  4946.1  221.43
  4981.9  220.66  4989.5   217.9  4996.2  212.79  5000.4  211.32  5003.1  210.82
  5006.4  211.32  5010.4  214.78    5017  216.79  5024.6  222.14  5031.4  224.68
  5045.5  228.11  5097.5  232.93  5159.4  235.14  5208.7  240.11  5243.8   242.3
  5251.4  241.49  5272.3  242.96  5294.1  242.13  5350.1   244.3  5423.5  245.17
#Mann= 6 ,-1 , 0
  4723.9     .16       0  4896.3     .16       0  5000.4     .16       0
  5006.4     .16       0  5031.4     .16       0  5097.5     .16       0
Bank Sta=4981.9,5024.6
XS Rating Curve= 0 ,0
Exp/Cntr=0.3,0.1

Chan Stop Cuts=-1
Use User Specified Reach Order=0
Composite Channel Slope=5