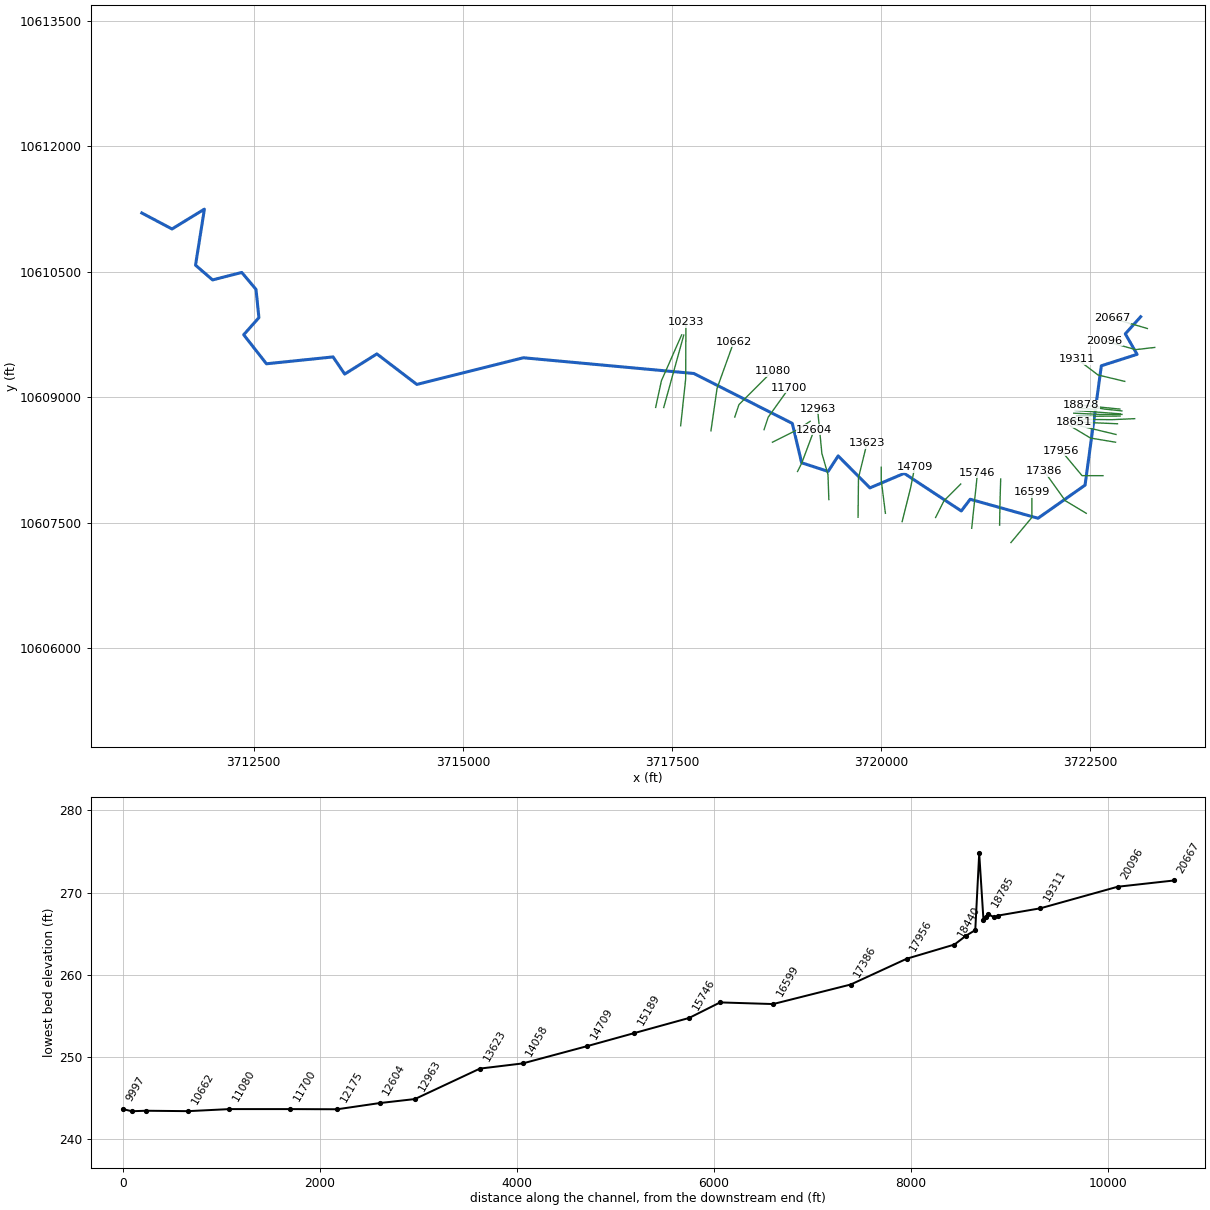
--- UNT 137 IN BOCR.prj (project) ---

Proj Title=UNT 137 IN BOCR Base Level Engineering
Current Plan=p01
Default Exp/Contr=0.3,0.1
English Units
Geom File=g01
Flow File=f01
Plan File=p01
Y Axis Title=Elevation
X Axis Title(PF)=Main Channel Distance
X Axis Title(XS)=Station
BEGIN DESCRIPTION:
UNT 137 IN BOCR
END DESCRIPTION:
DSS Export Rating Curves= 0
DSS Export Rating Curve Sorted= 0
DSS Export Volume Flow Curves= 0
DXF OffsetX= 0
DXF OffsetY= 0
DXF ScaleX= 1
DXF ScaleY= 10

--- UNT 137 IN BOCR.p01 (plan) ---

Plan Title=Multiple Run
Short Identifier=Multiple
Geom File=g01
Flow File=f01
Subcritical Flow
K Sum by GR= 0
Std Step Tol= 0.01
Critical Tol= 0.01
Num of Std Step Trials= 20
Max Error Tol= 0.3
Flow Tol Ratio= 0.001
Split Flow NTrial= 30
Split Flow Tol= 0.02
Split Flow Ratio= 0.02
Log Output Level= 0
Friction Slope Method= 1
Unsteady Friction Slope Method= 2
Unsteady Bridges Friction Slope Method= 1
Parabolic Critical Depth
Global Vel Dist=  1 , 1 , 1
Global Log Level= 0
CheckData=True
Encroach Param= -1, 0, 0, 0
BEGIN DESCRIPTION:
Multiple Run
END DESCRIPTION:

--- UNT 137 IN BOCR.f01 (steady flow) ---

Flow Title=Multiple
Program Version=4.10
Number of Profiles= 7
Profile Names=10-year,25-year,50-year,1pct_min,100-year,1pct_plu,500-year
River Rch & RM=UNT 137 IN BOCR,Reach-1         ,20667
     405     525     619     537     726     982    1000
River Rch & RM=UNT 137 IN BOCR,Reach-1         ,16599
     588     778     931     817    1105    1495    1564
River Rch & RM=UNT 137 IN BOCR,Reach-1         ,12963
     735     984    1187    1049    1418    1918    2034
River Rch & RM=UNT 137 IN BOCR,Reach-1         ,12175
     735     984    1187    1049    1418    1918    2034
River Rch & RM=UNT 137 IN BOCR,Reach-1         ,8179
     979    1335    1630    1457    1970    2665    2893
River Rch & RM=UNT 137 IN BOCR,Reach-1         ,2397
    1056    1445    1767    1583    2140    2894    3155
Boundary for River Rch & Prof#=UNT 137 IN BOCR,Reach-1         , 1
Up Type= 0
Dn Type= 3
Dn Slope=0.003
Boundary for River Rch & Prof#=UNT 137 IN BOCR,Reach-1         , 2
Up Type= 0
Dn Type= 3
Dn Slope=0.003
Boundary for River Rch & Prof#=UNT 137 IN BOCR,Reach-1         , 3
Up Type= 0
Dn Type= 3
Dn Slope=0.003
Boundary for River Rch & Prof#=UNT 137 IN BOCR,Reach-1         , 4
Up Type= 0
Dn Type= 3
Dn Slope=0.003
Boundary for River Rch & Prof#=UNT 137 IN BOCR,Reach-1         , 5
Up Type= 0
Dn Type= 3
Dn Slope=0.003
Boundary for River Rch & Prof#=UNT 137 IN BOCR,Reach-1         , 6
Up Type= 0
Dn Type= 3
Dn Slope=0.003
Boundary for River Rch & Prof#=UNT 137 IN BOCR,Reach-1         , 7
Up Type= 0
Dn Type= 3
Dn Slope=0.003
DSS Import GetInterval= 0
DSS Import GetPeak= 0
DSS Import FillOption= 0

--- UNT 137 IN BOCR.g01 (geometry) ---

Geom Title=Existing Conditions
Program Version=4.10

River Reach=UNT 137 IN BOCR ,Reach-1
Reach XY= 30
      3723099.61     10609960.19      3722916.25     10609756.09
      3723056.87     10609510.86      3722629.79     10609374.15
      3722435.25       10607947.      3721873.25       10607551.
       3721062.5       10607778.      3720956.25       10607638.
      3720274.25       10608088.       3719864.5       10607914.
        3719485.       10608296.      3719365.25       10608111.
      3719048.75       10608214.        3718937.       10608685.
      3717760.25       10609282.        3715723.       10609470.
      3714450.75       10609151.        3713973.       10609516.
       3713588.5       10609275.       3713449.5       10609480.
       3712653.5       10609398.      3712381.75       10609745.
       3712563.5       10609950.       3712528.5       10610288.
      3712358.75       10610490.      3712009.75       10610401.
        3711806.       10610577.        3711912.       10611247.
        3711525.       10611010.      3711164.25       10611201.

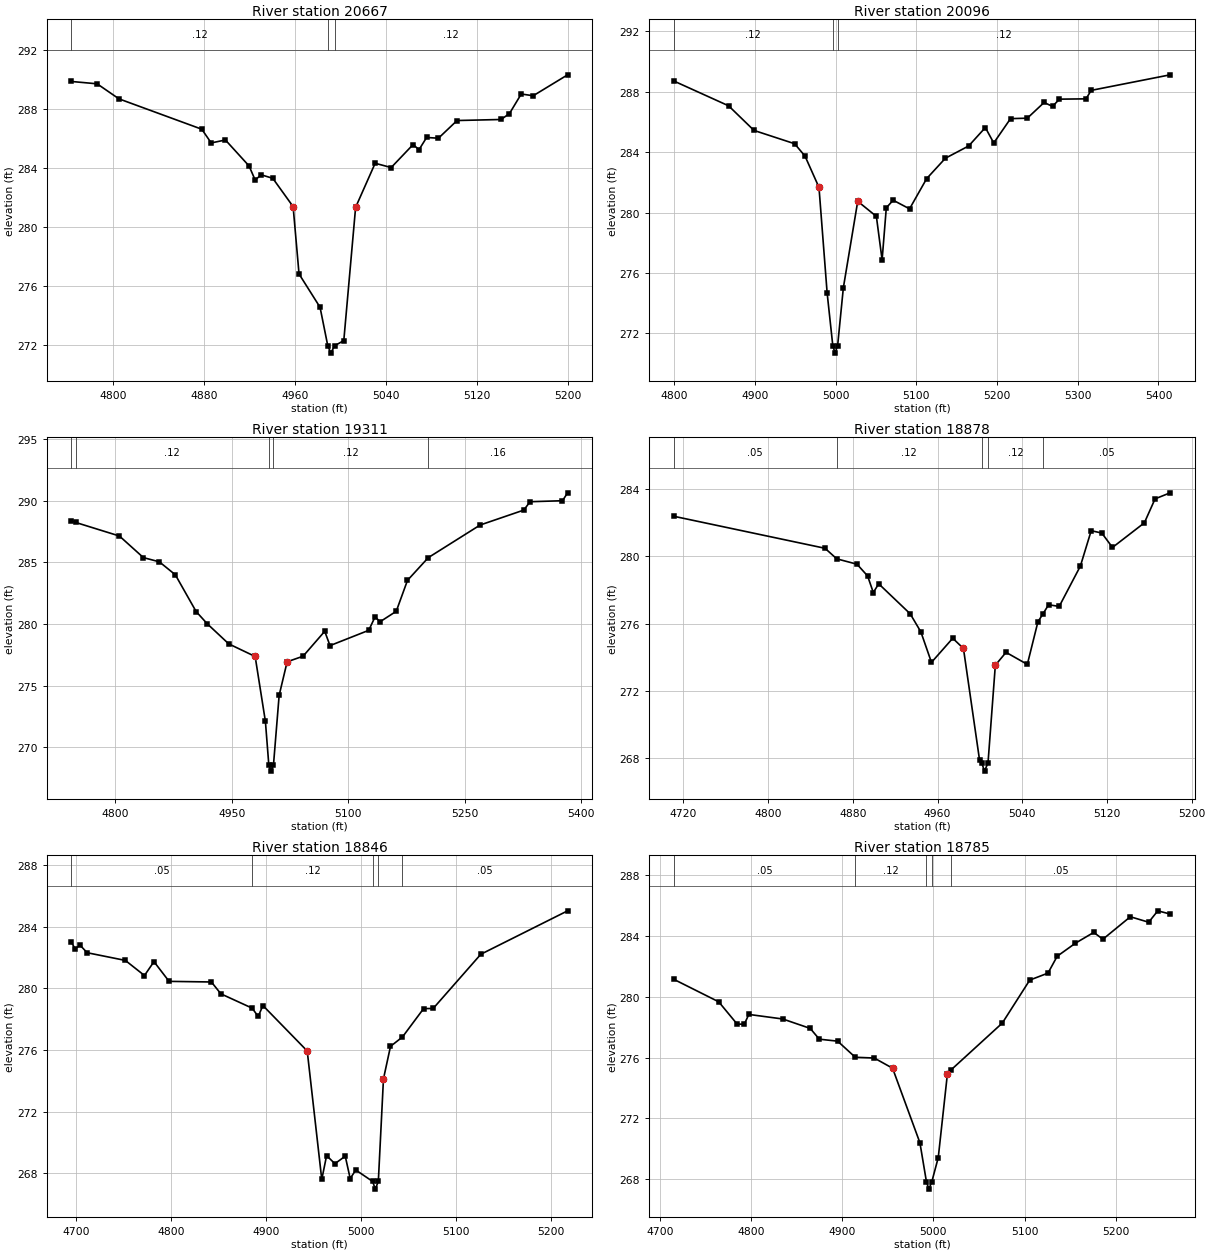
Type RM Length L Ch R = 1 ,20667   ,571,571,571
BEGIN DESCRIPTION:
UNT 137 IN BOCR 38.0
END DESCRIPTION:
XS GIS Cut Line= 2
      3723179.79     10609819.83      3722760.49     10609942.24
#Sta/Elev= 30
    4763  289.89  4785.7  289.73  4804.9  288.71  4877.8  286.65  4886.1  285.72
  4898.6  285.92  4919.4  284.16  4924.8   283.2    4930  283.56  4940.3  283.32
  4958.2   281.4  4963.4  276.83  4981.9  274.57  4988.7  271.96  4991.4  271.46
  4994.7  271.96  5002.8  272.31  5013.2  281.35  5030.4  284.34  5044.5  284.05
  5063.8  285.61    5069  285.26  5075.7  286.09  5086.1  286.04  5102.5  287.24
  5141.2  287.31  5148.6  287.71    5159  289.04  5169.5  288.92  5199.8  290.34
#Mann= 3 ,-1 , 0
    4763     .12       0  4988.7     .07       0  4994.7     .12       0
Bank Sta=4958.2,5013.2
XS Rating Curve= 0 ,0
Exp/Cntr=0.3,0.1

Type RM Length L Ch R = 1 ,20096   ,785,785,785
BEGIN DESCRIPTION:
Mapping XS c698e10c
END DESCRIPTION:
XS GIS Cut Line= 3
      3723268.26     10609593.28      3723039.12     10609567.24
      3722669.32     10609671.41
#Sta/Elev= 30
  4799.6  288.71  4867.4  287.07  4898.9  285.44  4949.2  284.56  4962.1  283.74
  4979.4  281.67  4989.5  274.68  4996.5   271.2  4999.3   270.7  5002.5   271.2
  5009.6  275.03  5027.4  280.75  5050.5  279.75  5057.6  276.87  5062.8  280.32
  5071.3  280.82  5091.6  280.25  5112.8  282.25    5136   283.6  5164.8  284.41
  5185.5  285.63  5195.9  284.61  5216.7  286.22  5237.5  286.25  5258.3  287.29
  5268.7  287.03  5277.3  287.51  5310.2  287.53  5316.6  288.09  5414.4  289.12
#Mann= 3 ,-1 , 0
  4799.6     .12       0  4996.5     .07       0  5002.5     .12       0
Bank Sta=4979.4,5027.4
XS Rating Curve= 0 ,0
Exp/Cntr=0.3,0.1

Type RM Length L Ch R = 1 ,19311   ,433,433,433
BEGIN DESCRIPTION:
UNT 137 IN BOCR 37.0
END DESCRIPTION:
XS GIS Cut Line= 3
      3722909.84     10609187.58      3722590.35     10609263.98
      3722343.33     10609452.27
#Sta/Elev= 30
  4743.4  288.37    4749  288.23  4805.3  287.13  4836.2  285.38  4856.7  285.04
  4877.3  283.99  4904.1  281.01  4918.4  280.02  4946.1  278.39  4980.1  277.37
  4993.3  272.11  4997.7  268.58  5000.4  268.08  5003.7  268.58    5011  274.22
  5021.3  276.94  5041.8  277.39  5069.7  279.41  5076.5  278.25  5126.4  279.49
  5134.6  280.59  5140.9  280.18  5161.8  281.03  5176.3  283.54  5203.1  285.38
  5269.8  288.02    5326  289.23  5334.2  289.91  5375.9  289.99  5382.5  290.63
#Mann= 5 ,-1 , 0
  4743.4     .05       0    4749     .12       0  4997.7     .07       0
  5003.7     .12       0  5203.1     .16       0
Bank Sta=4980.1,5021.3
XS Rating Curve= 0 ,0
Exp/Cntr=0.3,0.1

Type RM Length L Ch R = 1 ,18878   ,32,32,32
BEGIN DESCRIPTION:
UNT 137 IN BOCR 36.0
END DESCRIPTION:
XS GIS Cut Line= 2
       3722851.6      10608856.3      3722385.45     10608903.18
#Sta/Elev= 30
  4711.1   282.4  4853.8  280.49  4864.9  279.86    4884  279.54    4894  278.84
  4899.4  277.85  4904.5  278.37  4934.2  276.58  4944.3   275.5  4954.3  273.68
  4974.4  275.12  4984.5  274.51  4999.7  267.85  5001.7  267.69  5004.4  267.19
  5007.7  267.69  5014.6  273.51  5024.7  274.28  5044.8  273.56  5054.8   276.1
  5059.6  276.58  5064.9  277.12  5074.9  277.02  5094.9  279.43  5105.1  281.54
  5115.1   281.4  5125.2  280.54  5155.3  282.01  5165.4  283.44  5179.6   283.8
#Mann= 5 ,-1 , 0
  4711.1     .05       0  4864.9     .12       0  5001.7     .07       0
  5007.7     .12       0  5059.6     .05       0
Bank Sta=4984.5,5014.6
XS Rating Curve= 0 ,0
Exp/Cntr=0.3,0.1

Type RM Length L Ch R = 1 ,18846   ,61,61,61
BEGIN DESCRIPTION:
Mapping XS 3b85200c
END DESCRIPTION:
XS GIS Cut Line= 5
      3722876.09     10608834.52       3722666.7     10608856.22
      3722597.26     10608868.16      3722544.09     10608854.05
      3722358.53     10608867.07
#Sta/Elev= 30
  4695.4  283.01  4699.4  282.56  4704.4  282.82    4712  282.32  4752.2  281.82
  4772.3  280.84  4782.3  281.74  4798.2  280.46  4842.7  280.42  4852.7  279.65
  4885.6  278.72  4891.9  278.18  4896.9  278.89  4943.5  275.94  4958.8   267.6
  4963.9  269.15  4972.6  268.62  4983.5  269.11  4988.7  267.66  4994.6  268.21
  5012.3  267.47  5015.1  266.97  5018.3  267.47  5023.7  274.13  5031.1  276.24
  5043.7  276.85  5065.9  278.69    5076   278.7  5126.1  282.22  5217.4  285.04
#Mann= 5 ,-1 , 0
  4695.4     .05       0  4885.6     .12       0  5012.3     .07       0
  5018.3     .12       0  5043.7     .05       0
Bank Sta=4943.5,5023.7
XS Rating Curve= 0 ,0
Exp/Cntr=0.3,0.1

Type RM Length L Ch R = 1 ,18785   ,27,27,27
BEGIN DESCRIPTION:
Mapping XS dac99cf4
END DESCRIPTION:
XS GIS Cut Line= 2
      3722858.67     10608799.12      3722316.14     10608840.35
#Sta/Elev= 30
  4715.5  281.16  4764.7  279.68  4784.8  278.22  4792.7   278.2  4797.7  278.85
  4834.9  278.55    4865  277.93    4875  277.22  4895.1  277.09  4914.4  276.03
  4935.2  275.98  4955.3  275.31  4985.3   270.4  4992.4  267.85  4995.1  267.35
  4998.4  267.85  5005.4  269.43  5015.4  274.92  5018.9  275.17  5075.6  278.28
  5105.7  281.11  5125.7  281.57  5135.8  282.68  5155.8  283.54  5175.9  284.25
  5185.9   283.8    5216  285.28  5236.1  284.92  5246.1  285.67  5259.6  285.46
#Mann= 5 ,-1 , 0
  4715.5     .05       0  4914.4     .12       0  4992.4     .07       0
  4998.4     .12       0  5018.9     .05       0
Bank Sta=4955.3,5015.4
XS Rating Curve= 0 ,0
Exp/Cntr=0.3,0.1

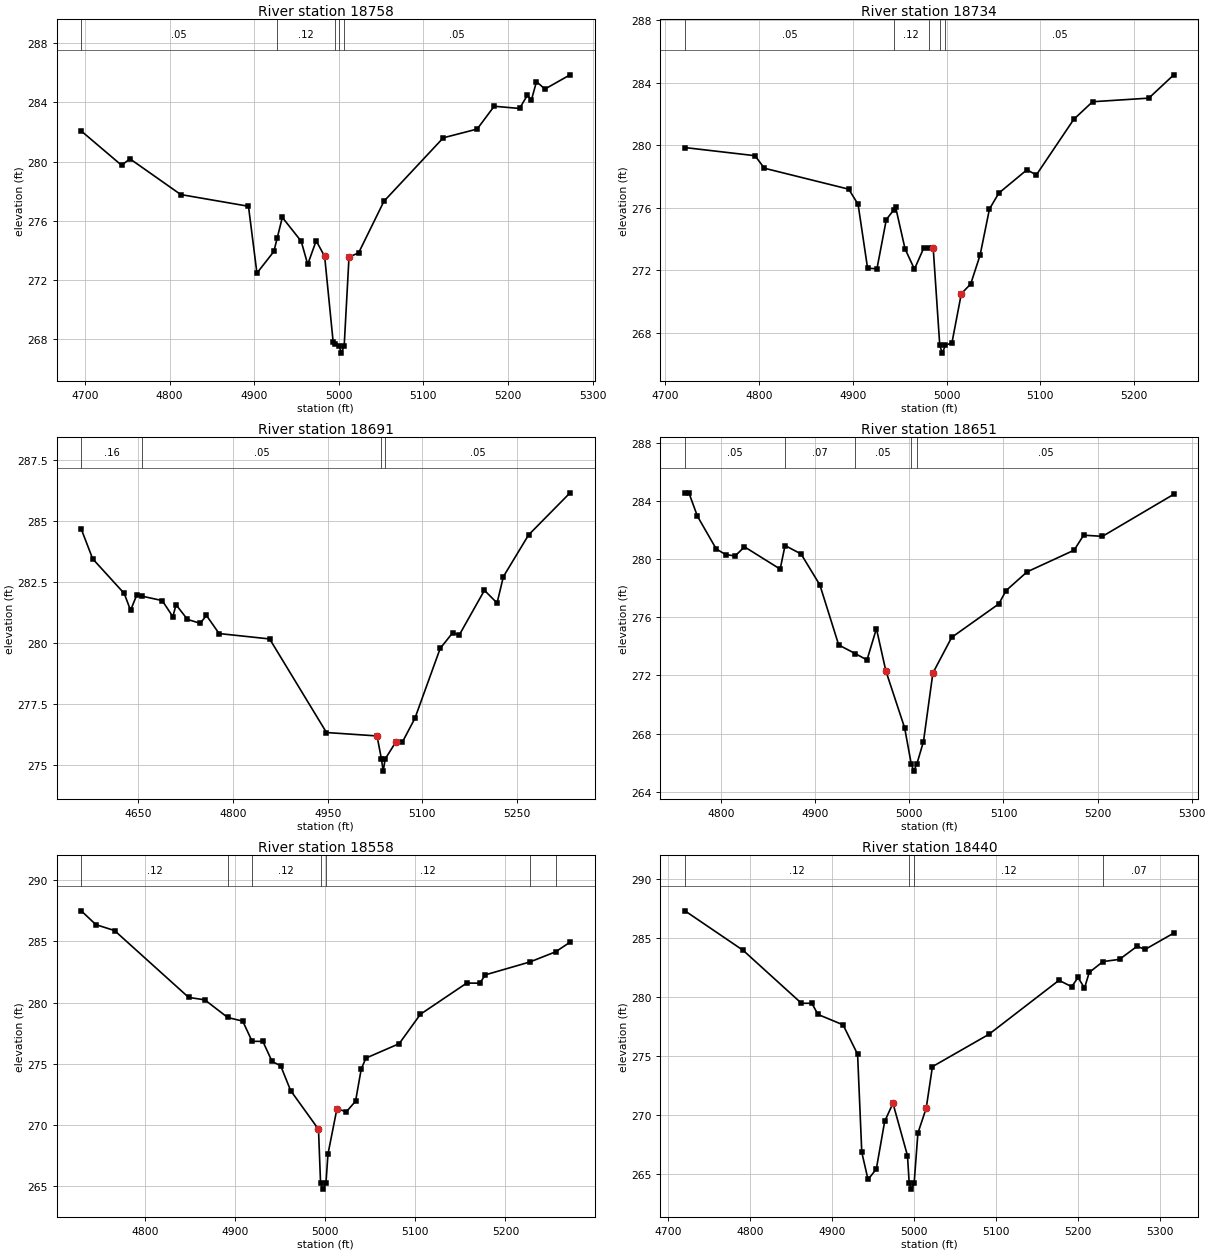
Type RM Length L Ch R = 1 ,18758   ,24,24,24
BEGIN DESCRIPTION:
Mapping XS 65a2f2a7
END DESCRIPTION:
XS GIS Cut Line= 3
      3722877.22      10608792.2      3722620.05      10608792.2
      3722299.98     10608807.39
#Sta/Elev= 30
  4695.7  282.06  4743.3  279.75  4753.3  280.18  4813.3  277.77  4893.3  276.98
  4903.3  272.47  4923.3  273.93  4927.3  274.85  4933.3  276.23  4955.6  274.62
  4963.3  273.06  4973.3  274.65  4983.3   273.6  4993.4   267.8  4996.1  267.71
  5000.4  267.57  5003.1  267.07  5006.4  267.57  5012.1  273.56  5023.4  273.83
  5053.4  277.32  5123.5   281.6  5163.5  282.19  5183.6  283.73  5213.6  283.58
  5222.7  284.46  5227.7  284.17  5233.6  285.39  5243.6  284.89  5273.3  285.85
#Mann= 5 ,-1 , 0
  4695.7     .05       0  4927.3     .12       0  4996.1     .05       0
  5000.4     .03       0  5006.4     .05       0
Bank Sta=4983.3,5012.1
XS Rating Curve= 0 ,0
Exp/Cntr=0.3,0.1

Type RM Length L Ch R = 1 ,18734   ,43,43,43
BEGIN DESCRIPTION:
Mapping XS 064ac48d
END DESCRIPTION:
XS GIS Cut Line= 2
      3722854.35     10608773.08      3722332.97     10608768.75
#Sta/Elev= 30
    4721  279.85  4795.7  279.33  4805.7  278.53  4895.7  277.19  4905.7  276.22
  4915.8  272.14  4925.8   272.1  4935.8  275.25  4943.7  275.86  4945.8  276.02
  4955.8  273.37  4965.8  272.08  4975.8  273.44  4981.2  273.43  4985.8  273.43
  4992.8  267.21  4995.5  266.71  4998.8  267.21  5005.8  267.37  5015.8  270.51
  5025.8  271.13  5035.8  272.97  5045.8  275.92  5055.8  276.94  5085.8  278.43
  5095.8   278.1  5135.8  281.66  5155.8  282.78  5215.8  283.01  5242.4   284.5
#Mann= 5 ,-1 , 0
    4721     .05       0  4943.7     .12       0  4981.2     .05       0
  4992.8     .03       0  4998.8     .05       0
Bank Sta=4985.8,5015.8
XS Rating Curve= 0 ,0
Exp/Cntr=0.3,0.1

Type RM Length L Ch R = 1 ,18691   ,40,40,40
BEGIN DESCRIPTION:
Mapping XS 13f76296
END DESCRIPTION:
XS GIS Cut Line= 3
      3723027.67     10608741.77       3722756.8     10608729.62
      3722253.97     10608734.82
#Sta/Elev= 30
  4559.8  284.66  4577.9  283.44  4627.9  282.02  4637.9  281.33  4647.9  281.97
  4656.1  281.91    4688  281.73  4704.9  281.07  4709.9  281.56    4728  280.96
    4748   280.8  4758.1  281.12  4778.1  280.38  4858.1  280.16  4948.1  276.33
  5028.1  276.19  5035.1  275.25  5037.9  274.75  5041.1  275.25  5058.1  275.95
  5068.1  275.93  5088.1  276.91  5128.1  279.77  5148.1  280.42  5158.1  280.31
  5198.2  282.15  5218.2  281.63  5228.2  282.71  5268.2  284.42  5333.8  286.14
#Mann= 4 ,-1 , 0
  4559.8     .16       0  4656.1     .05       0  5035.1     .03       0
  5041.1     .05       0
Bank Sta=5028.1,5058.1
XS Rating Curve= 0 ,0
Exp/Cntr=0.3,0.1

Type RM Length L Ch R = 1 ,18651   ,93,93,93
BEGIN DESCRIPTION:
Mapping XS 26362bfc
END DESCRIPTION:
XS GIS Cut Line= 2
      3722822.89     10608680.84      3722303.84     10608702.52
#Sta/Elev= 30
  4761.5  284.55  4765.7  284.55  4774.8  282.94  4794.8  280.69  4804.8  280.31
  4814.8  280.21  4824.8  280.84  4862.7  279.31  4867.9  280.93  4884.9  280.35
  4904.9  278.22  4924.9   274.1  4942.3  273.51    4955  273.07    4965  275.22
    4975  272.32    4995   268.4    5002  265.93  5004.7  265.43    5008  265.93
    5015  267.46    5025  272.17    5045  274.62  5095.1  276.92  5102.7  277.83
  5125.1  279.12  5175.1  280.61  5185.2  281.64  5205.2  281.56    5281  284.45
#Mann= 5 ,-1 , 0
  4761.5     .05       0  4867.9     .07       0  4942.3     .05       0
    5002     .03       0    5008     .05       0
Bank Sta=4975,5025
XS Rating Curve= 0 ,0
Exp/Cntr=0.3,0.1

Type RM Length L Ch R = 1 ,18558   ,118,118,118
BEGIN DESCRIPTION:
Mapping XS e181ddd6
END DESCRIPTION:
XS GIS Cut Line= 2
      3722805.47     10608552.81      3722278.19     10608678.67
#Sta/Elev= 30
  4729.6  287.49  4745.9  286.36  4766.5  285.88  4848.7  280.42  4866.6  280.22
    4892  278.78  4908.7  278.48  4919.1  276.83    4931  276.83  4941.2  275.19
  4950.8  274.83  4961.8  272.81  4992.7  269.65    4995  265.26  4997.8  264.76
    5001  265.26  5003.2  267.62  5013.2  271.34  5023.5  271.07  5033.8  271.94
  5040.1  274.57  5045.3  275.46  5082.2  276.64  5105.7  279.04  5157.1  281.59
  5171.6  281.58  5177.7  282.26    5227  283.31  5255.6  284.14  5271.7  284.93
#Mann= 7 ,-1 , 0
  4729.6     .12       0    4892     .07       0  4919.1     .12       0
    4995     .07       0    5001     .12       0    5227     .07       0
  5255.6     .05       0
Bank Sta=4992.7,5013.2
XS Rating Curve= 0 ,0
Exp/Cntr=0.3,0.1

Type RM Length L Ch R = 1 ,18440   ,484,484,484
BEGIN DESCRIPTION:
UNT 137 IN BOCR 35.0
END DESCRIPTION:
XS GIS Cut Line= 3
      3722799.65     10608460.18      3722499.61     10608510.19
      3722249.63     10608660.17
#Sta/Elev= 30
  4720.7  287.31  4791.7  283.95  4862.7  279.46  4875.3  279.46  4882.9  278.51
  4913.4  277.63  4931.1  275.13  4936.2  266.81  4943.8   264.5  4953.9  265.38
  4964.1  269.43  4974.2  270.97  4991.9  266.52    4994  264.18  4996.7  263.68
    5000  264.18  5004.6  268.44  5014.7  270.55  5022.3  274.08    5091  276.82
  5176.5  281.41    5192  280.87  5199.8  281.65  5207.6  280.75  5213.4  282.08
  5230.1     283  5250.3  283.19  5271.7   284.3  5281.4  284.03  5316.4  285.42
#Mann= 4 ,-1 , 0
  4720.7     .12       0    4994     .07       0    5000     .12       0
  5230.1     .07       0
Bank Sta=4974.2,5014.7
XS Rating Curve= 0 ,0
Exp/Cntr=0.3,0.1

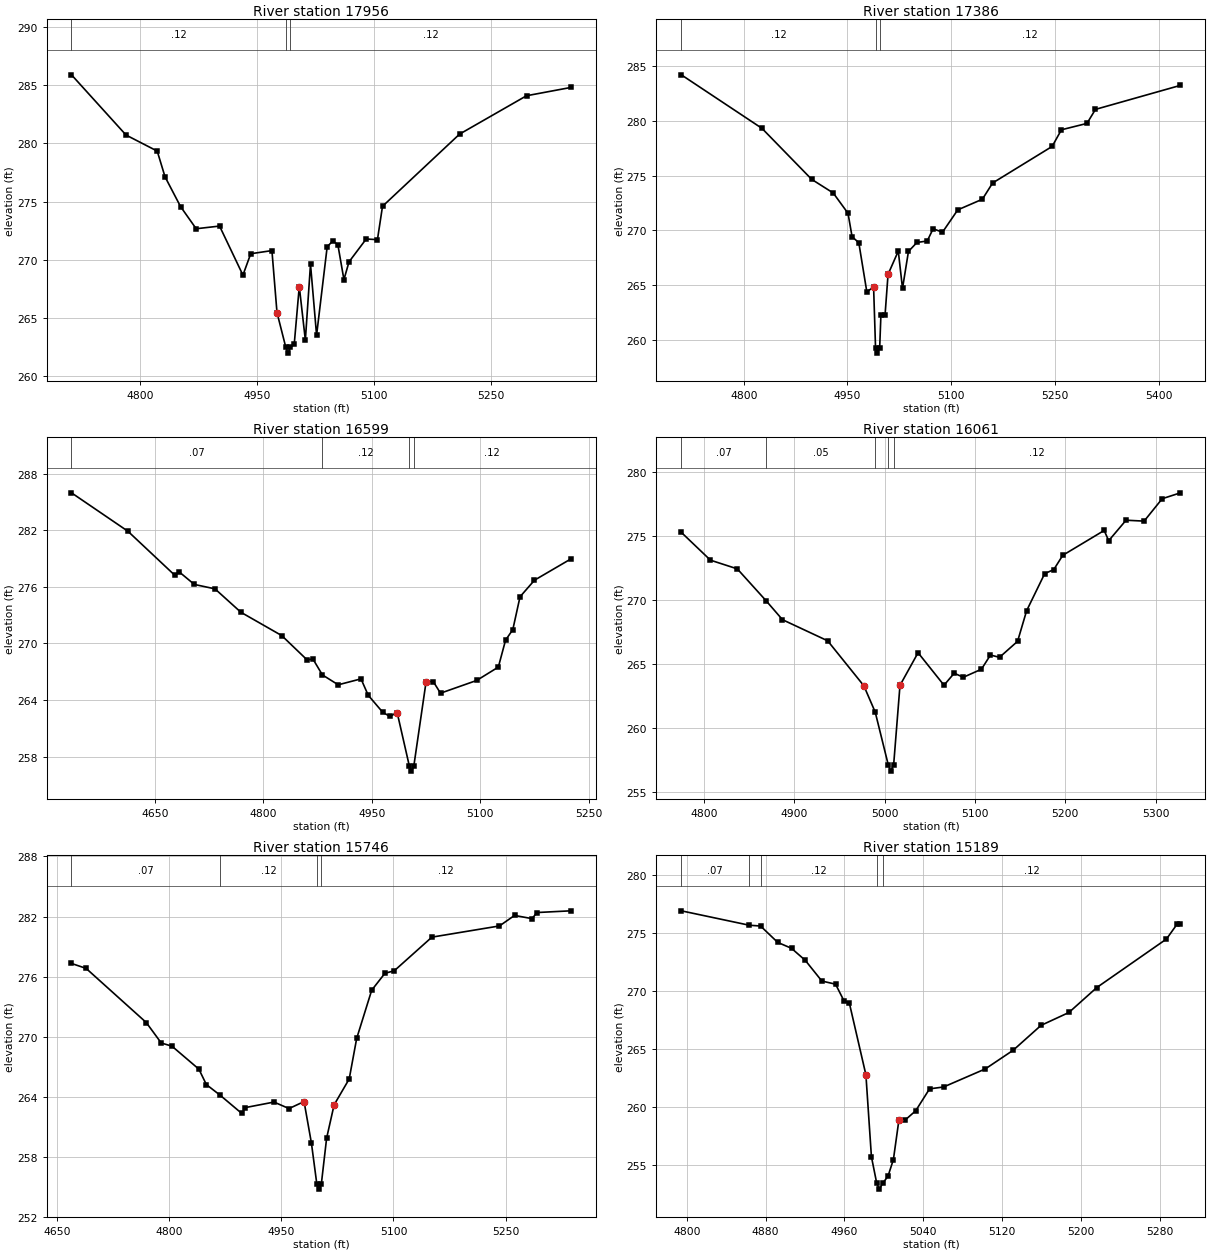
Type RM Length L Ch R = 1 ,17956   ,570,570,570
BEGIN DESCRIPTION:
UNT 137 IN BOCR 34.0
END DESCRIPTION:
XS GIS Cut Line= 3
      3722649.64     10608060.19      3722399.61     10608060.19
      3722149.63     10608360.16
#Sta/Elev= 30
  4712.1   285.9  4782.1  280.72  4822.1  279.34  4832.1  277.13  4852.1  274.56
  4872.1  272.66  4902.1  272.89  4932.1  268.67  4942.1  270.51  4969.3  270.78
  4975.8  265.45  4987.1  262.46  4989.9  261.96  4993.1  262.46  4997.9  262.71
  5004.4  267.69  5012.2  263.08  5018.8  269.61  5026.6   263.5  5040.2  271.11
  5047.4  271.61  5053.9  271.29  5061.7  268.28  5068.2  269.81  5090.3  271.78
  5104.7  271.72  5111.2  274.59  5210.1   280.8    5296   284.1  5352.6  284.81
#Mann= 3 ,-1 , 0
  4712.1     .12       0  4987.1     .07       0  4993.1     .12       0
Bank Sta=4975.8,5004.4
XS Rating Curve= 0 ,0
Exp/Cntr=0.3,0.1

Type RM Length L Ch R = 1 ,17386   ,787,787,787
BEGIN DESCRIPTION:
UNT 137 IN BOCR 33.0
END DESCRIPTION:
XS GIS Cut Line= 3
      3722449.62     10607610.18      3722199.61     10607760.19
       3721949.6     10608110.21
#Sta/Elev= 30
  4709.8  284.19  4826.4  279.31  4898.3  274.66  4929.4  273.42  4950.8  271.57
  4956.7  269.43  4966.4  268.89    4978  264.41  4987.8  264.84  4990.6  259.32
  4993.3  258.82  4996.6  259.32  4998.4  262.33  5004.4  262.33  5008.7     266
  5023.5  268.12  5029.6  264.72  5038.2  268.09  5050.5  268.91  5065.3  269.04
  5073.9  270.16  5087.4  269.84  5109.5  271.88  5145.1  272.85  5159.9  274.33
  5245.9  277.66  5259.4  279.18  5296.3  279.76  5308.6  281.04  5431.5  283.23
#Mann= 3 ,-1 , 0
  4709.8     .12       0  4990.6     .07       0  4996.6     .12       0
Bank Sta=4987.8,5008.7
XS Rating Curve= 0 ,0
Exp/Cntr=0.3,0.1

Type RM Length L Ch R = 1 ,16599   ,538,538,538
BEGIN DESCRIPTION:
UNT 137 IN BOCR 32.0
END DESCRIPTION:
XS GIS Cut Line= 3
      3721549.62      10607260.2      3721799.61     10607560.19
      3721799.61     10607860.19
#Sta/Elev= 30
  4534.6  285.98  4612.7   281.9  4677.1  277.26  4683.6  277.59  4704.5  276.26
  4733.1  275.79  4768.9  273.31  4825.5  270.83  4860.7  268.24  4868.5  268.36
  4881.7  266.66  4903.6  265.61  4935.1  266.24  4945.1   264.5  4965.1   262.7
  4975.1  262.25  4985.1  262.67  5002.1  256.95  5004.8  256.45  5008.1  256.95
  5025.1  265.91  5035.1  265.95  5045.1  264.72  5095.1  266.07  5125.1  267.49
  5135.1  270.35  5145.1  271.46  5155.1  274.95  5175.1  276.71  5225.1  278.95
#Mann= 4 ,-1 , 0
  4534.6     .07       0  4881.7     .12       0  5002.1     .07       0
  5008.1     .12       0
Bank Sta=4985.1,5025.1
XS Rating Curve= 0 ,0
Exp/Cntr=0.3,0.1

Type RM Length L Ch R = 1 ,16061   ,315,315,315
BEGIN DESCRIPTION:
UNT 137 IN BOCR 31.0
END DESCRIPTION:
XS GIS Cut Line= 3
      3721414.12      10607468.3      3721419.33     10607762.55
      3721427.14     10608020.34
#Sta/Elev= 30
  4775.2   275.3  4807.4  273.13  4837.1  272.45  4869.1  269.95  4887.1  268.48
  4937.1  266.83  4977.1  263.32  4989.7  261.26  5004.1  257.15  5006.9  256.65
  5010.1  257.15  5017.1  263.35  5037.1   265.9  5065.8  263.36  5077.1   264.3
  5087.1  263.98  5107.2  264.61  5117.2  265.72  5127.2  265.54  5147.2  266.79
  5157.2  269.18  5177.2  272.08  5187.2  272.39  5197.2  273.51    5243  275.45
    5248  274.65  5267.2  276.25  5287.2  276.18  5307.2  277.93  5327.4  278.39
#Mann= 5 ,-1 , 0
  4775.2     .07       0  4869.1     .05       0  4989.7     .12       0
  5004.1     .07       0  5010.1     .12       0
Bank Sta=4977.1,5017.1
XS Rating Curve= 0 ,0
Exp/Cntr=0.3,0.1

Type RM Length L Ch R = 1 ,15746   ,557,557,557
BEGIN DESCRIPTION:
UNT 137 IN BOCR 30.0
END DESCRIPTION:
XS GIS Cut Line= 2
      3721080.72     10607430.75      3721150.17     10608094.83
#Sta/Elev= 30
  4669.3  277.31  4688.8  276.82  4769.3  271.41  4789.4  269.36  4803.6  269.05
  4839.7  266.75  4849.7  265.21  4868.2  264.14    4897  262.33    4902  262.91
  4940.2  263.46  4960.3  262.81  4980.4  263.51  4990.3  259.34  4997.5  255.26
  5000.3  254.76  5003.5  255.26  5010.6  259.86  5020.6  263.18  5040.8  265.77
  5050.8  269.82  5070.9  274.64  5088.6  276.33  5101.1  276.58  5151.4  279.94
  5241.8  281.06    5262  282.11  5285.3  281.79  5292.1   282.4    5337  282.57
#Mann= 4 ,-1 , 0
  4669.3     .07       0  4868.2     .12       0  4997.5     .07       0
  5003.5     .12       0
Bank Sta=4980.4,5020.6
XS Rating Curve= 0 ,0
Exp/Cntr=0.3,0.1

Type RM Length L Ch R = 1 ,15189   ,480,480,480
BEGIN DESCRIPTION:
UNT 137 IN BOCR 29.0
END DESCRIPTION:
XS GIS Cut Line= 3
       3720649.6     10607560.17      3720749.61     10607760.19
      3720949.63     10607960.21
#Sta/Elev= 30
  4794.5   276.9  4863.4  275.66  4874.9  275.59  4892.3  274.18  4906.3  273.67
  4920.3  272.63  4937.1  270.85    4951  270.58  4959.4  269.17    4965  268.95
  4981.8  262.77  4987.4  255.71  4992.8  253.42  4995.5  252.92  4998.8  253.42
  5004.2  254.03  5009.7  255.47  5015.3  258.88  5021.7  258.88  5032.3  259.67
  5046.4  261.56  5060.6  261.72    5103  263.28  5131.3  264.89  5159.5  267.03
  5187.8  268.14  5216.1  270.29  5286.8  274.47  5297.4  275.73    5301  275.73
#Mann= 5 ,-1 , 0
  4794.5     .07       0  4863.4     .05       0  4874.9     .12       0
  4992.8     .07       0  4998.8     .12       0
Bank Sta=4981.8,5015.3
XS Rating Curve= 0 ,0
Exp/Cntr=0.3,0.1

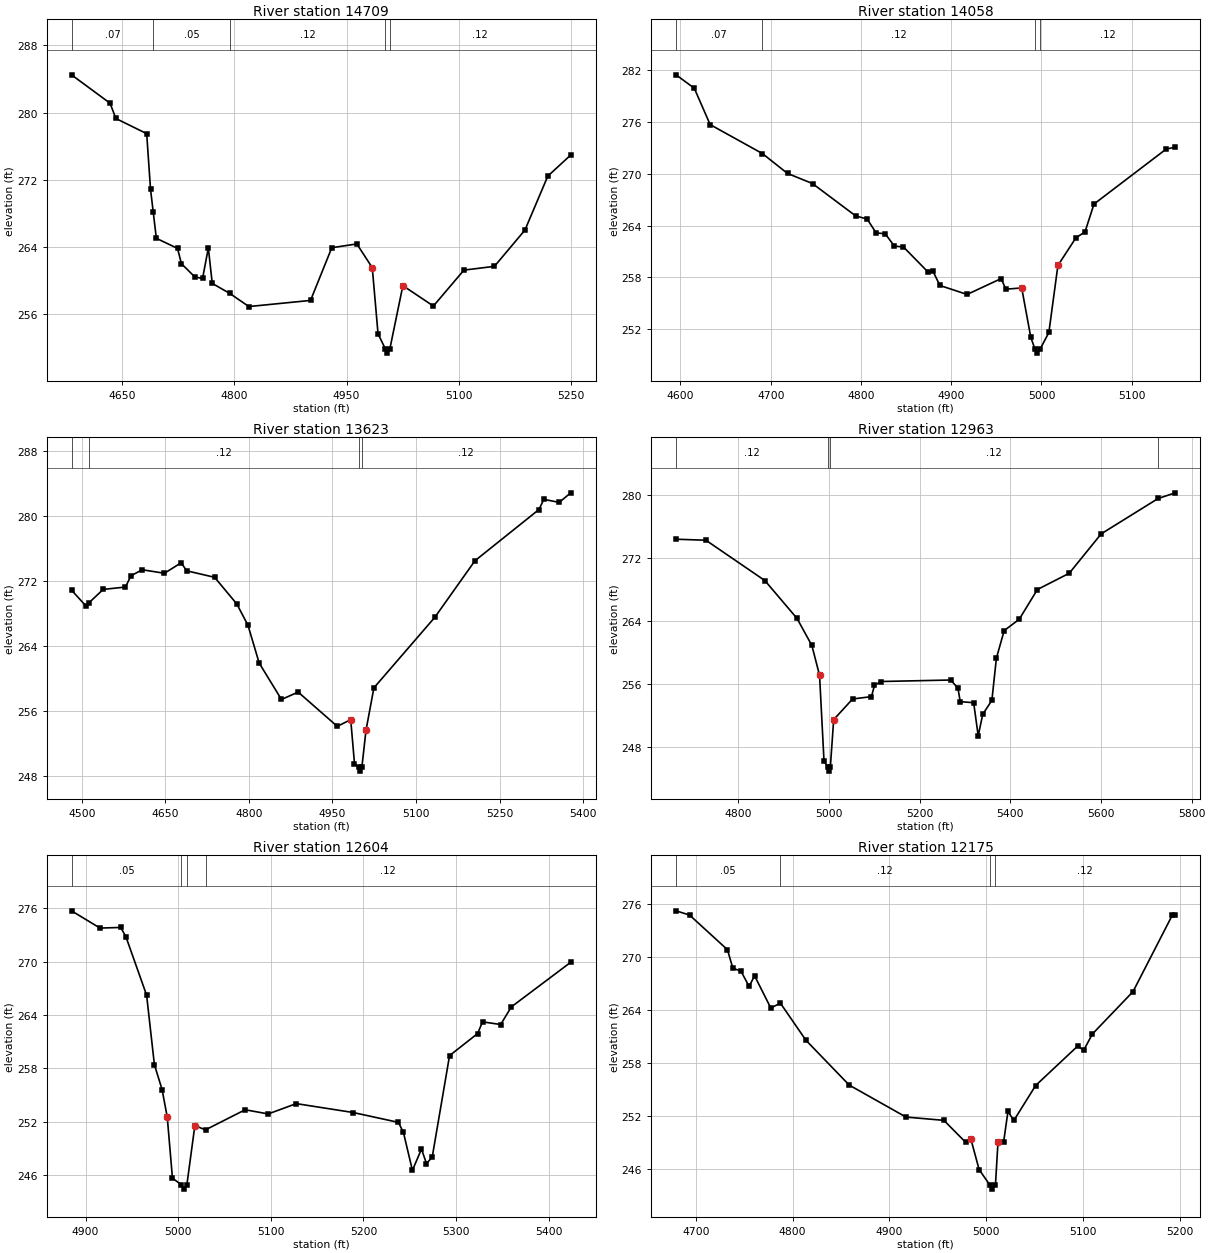
Type RM Length L Ch R = 1 ,14709   ,651,651,651
BEGIN DESCRIPTION:
UNT 137 IN BOCR 28.0
END DESCRIPTION:
XS GIS Cut Line= 3
      3720249.61     10607510.21      3720349.61     10607910.19
       3720399.6     10608160.15
#Sta/Elev= 30
  4582.4  284.49  4633.9  281.11  4641.7  279.29  4682.9  277.48    4688  270.87
  4691.7  268.09  4695.8  265.01  4724.1  263.81  4729.3  261.99  4747.3   260.4
  4757.6  260.23  4765.3  263.87  4770.5  259.64  4793.8  258.45  4819.5  256.88
  4901.9  257.61  4930.3  263.89  4963.8  264.34  4984.4  261.51  4992.1  253.64
  5001.9  251.83  5004.6  251.33  5007.9  251.83  5025.3  259.37  5066.1  256.94
  5106.9  261.22  5147.7  261.67  5188.5     266    5219  272.42  5249.6  274.93
#Mann= 5 ,-1 , 0
  4582.4     .07       0  4691.7     .05       0  4793.8     .12       0
  5001.9     .07       0  5007.9     .12       0
Bank Sta=4984.4,5025.3
XS Rating Curve= 0 ,0
Exp/Cntr=0.3,0.1

Type RM Length L Ch R = 1 ,14058   ,435,435,435
BEGIN DESCRIPTION:
UNT 137 IN BOCR 27.0
END DESCRIPTION:
XS GIS Cut Line= 3
      3720049.61     10607610.16      3719999.61     10608010.19
      3719999.61     10608160.15
#Sta/Elev= 30
  4595.1  281.44  4615.3  279.89  4632.9  275.68  4690.8  272.33  4718.6  270.03
  4746.3  268.86  4794.2  265.11  4806.8  264.76  4816.8  263.15  4826.9  263.05
    4837  261.62  4847.1  261.52  4874.8  258.57  4879.8  258.72  4887.4  257.07
  4917.6  256.03  4955.4  257.87  4960.4  256.64  4978.1  256.78  4988.2  251.05
  4992.7  249.74  4995.5  249.24  4998.7  249.74  5008.2  251.63  5018.2  259.38
  5038.2  262.59  5048.2  263.26  5058.2  266.49  5138.2  272.85  5148.2  273.07
#Mann= 4 ,-1 , 0
  4595.1     .07       0  4690.8     .12       0  4992.7     .07       0
  4998.7     .12       0
Bank Sta=4978.1,5018.2
XS Rating Curve= 0 ,0
Exp/Cntr=0.3,0.1

Type RM Length L Ch R = 1 ,13623   ,660,660,660
BEGIN DESCRIPTION:
UNT 137 IN BOCR 26.0
END DESCRIPTION:
XS GIS Cut Line= 3
      3719722.71     10607563.39      3719727.92     10608034.78
      3719829.04     10608447.05
#Sta/Elev= 30
  4481.6  270.89  4508.4  268.88  4513.1  269.34  4538.4  270.98  4578.4  271.27
  4588.4  272.66  4608.4   273.4  4648.4  272.97  4678.4  274.26  4688.4  273.27
  4738.4  272.47  4778.4  269.18  4798.4  266.55  4818.4  261.92  4858.4  257.43
  4888.4  258.34  4958.6  254.12  4982.7  254.95  4989.5  249.54  4996.8  249.11
  4999.5  248.61  5002.8  249.11  5010.1  253.62  5024.3  258.86  5133.6  267.54
  5205.7  274.51  5320.5  280.81  5329.3  282.07  5356.9  281.69  5377.5  282.87
#Mann= 4 ,-1 , 0
  4481.6     .05       0  4513.1     .12       0  4996.8     .07       0
  5002.8     .12       0
Bank Sta=4982.7,5010.1
XS Rating Curve= 0 ,0
Exp/Cntr=0.3,0.1

Type RM Length L Ch R = 1 ,12963   ,359,359,359
BEGIN DESCRIPTION:
UNT 137 IN BOCR 25.0
END DESCRIPTION:
XS GIS Cut Line= 4
      3719373.75     10607774.34      3719363.34     10608073.84
      3719290.42     10608326.45      3719238.33     10608862.92
#Sta/Elev= 30
  4662.2  274.36  4728.1  274.23  4858.2  269.11  4929.2   264.3  4961.9  260.87
  4978.9  257.08  4988.7  246.22  4996.7  245.41  4999.5  244.91  5002.7  245.41
  5010.1  251.45  5051.8  254.07  5093.4  254.37  5100.1  255.79  5114.2  256.29
  5268.7  256.48  5284.4  255.41  5289.4  253.73    5319   253.6    5329   249.4
  5339.1  252.13  5359.2   253.9  5369.2  259.27  5386.4  262.76  5419.5  264.19
  5459.6  267.97    5530  270.04  5600.4  275.04    5726  279.53  5763.8  280.25
#Mann= 4 ,-1 , 0
  4662.2     .12       0  4996.7     .07       0  5002.7     .12       0
    5726     .05       0
Bank Sta=4978.9,5010.1
XS Rating Curve= 0 ,0
Exp/Cntr=0.3,0.1

Type RM Length L Ch R = 1 ,12604   ,429,429,429
BEGIN DESCRIPTION:
UNT 137 IN BOCR 24.0
END DESCRIPTION:
XS GIS Cut Line= 3
       3718999.6     10608110.17      3719049.61     10608210.19
       3719199.6     10608610.17
#Sta/Elev= 30
  4884.8  275.73  4915.6  273.79  4937.9  273.86  4943.5  272.83  4965.9  266.24
  4974.3  258.43  4982.6  255.62  4988.2  252.52  4993.8  245.65  5003.4  244.92
  5006.2  244.42  5009.4  244.92    5018  251.57  5029.5  251.09  5072.3  253.35
  5097.2  252.88  5127.5  254.04  5188.9  253.04  5237.8  251.93  5243.2   250.8
  5252.9  246.53  5262.7  248.93  5268.1  247.29  5274.3  248.03    5293  259.44
  5323.3  261.92  5328.6  263.24  5348.2  262.94  5359.7  264.92  5423.8  269.94
#Mann= 4 ,-1 , 0
  4884.8     .05       0  5003.4     .03       0  5009.4     .05       0
  5029.5     .12       0
Bank Sta=4988.2,5018
XS Rating Curve= 0 ,0
Exp/Cntr=0.3,0.1

Type RM Length L Ch R = 1 ,12175   ,475,475,475
BEGIN DESCRIPTION:
UNT 137 IN BOCR 23.0
END DESCRIPTION:
XS GIS Cut Line= 3
      3718699.59     10608460.18      3718999.61     10608610.19
       3719149.6     10608710.18
#Sta/Elev= 30
  4679.6  275.23  4693.6  274.75  4732.7  270.82  4738.3  268.72  4746.7  268.39
  4755.1  266.65  4760.7  267.87  4777.5  264.21  4787.4  264.76  4813.8  260.55
  4858.5  255.47  4917.2  251.84  4956.3  251.47  4978.7  248.99  4984.3   249.3
  4992.7  245.89  5003.6  244.17  5006.4  243.67  5009.6  244.17  5012.2  249.01
    5018  249.01  5022.5  252.48  5028.6  251.46  5051.1  255.42  5094.7  259.91
  5100.7  259.41  5109.7  261.26  5151.7  266.07  5192.3  274.74  5195.3  274.74
#Mann= 4 ,-1 , 0
  4679.6     .05       0  4787.4     .12       0  5003.6     .07       0
  5009.6     .12       0
Bank Sta=4984.3,5012.2
XS Rating Curve= 0 ,0
Exp/Cntr=0.3,0.1

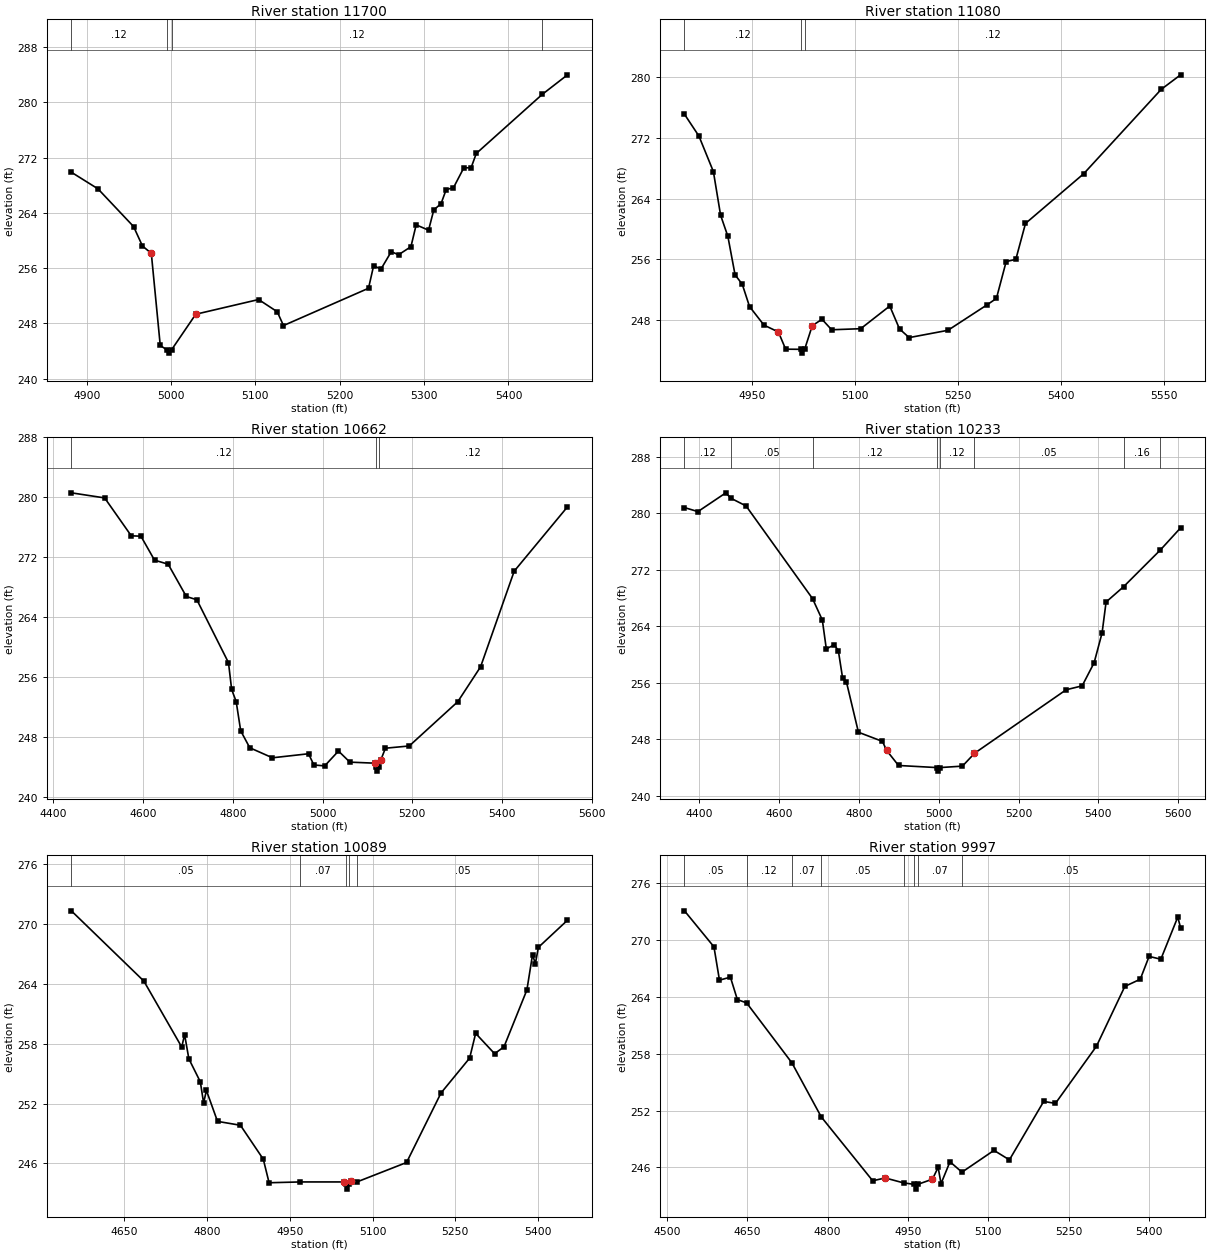
Type RM Length L Ch R = 1 ,11700   ,620,620,620
BEGIN DESCRIPTION:
UNT 137 IN BOCR 22.0
END DESCRIPTION:
XS GIS Cut Line= 3
      3718599.62     10608610.22      3718649.61     10608760.19
      3718899.61     10609110.19
#Sta/Elev= 30
  4881.8  269.88  4913.4  267.47  4955.6  262.01  4966.1   259.2  4976.6  258.14
  4987.2   244.8  4994.7  244.19  4997.5  243.69  5000.7  244.19  5029.3  249.32
  5103.8  251.45  5125.9  249.68  5133.3  247.68  5234.1  253.08  5240.2  256.36
  5248.8  255.84  5261.1  258.38  5269.7  257.93  5284.4   259.1  5290.6  262.26
  5305.3  261.49  5311.5  264.42  5320.1  265.33  5326.2  267.37  5334.8  267.63
  5347.1  270.52  5355.7  270.52  5361.9   272.6    5440  281.14    5470  283.98
#Mann= 4 ,-1 , 0
  4881.8     .12       0  4994.7     .07       0  5000.7     .12       0
    5440     .05       0
Bank Sta=4976.6,5029.3
XS Rating Curve= 0 ,0
Exp/Cntr=0.3,0.1

Type RM Length L Ch R = 1 ,11080   ,418,418,418
BEGIN DESCRIPTION:
UNT 137 IN BOCR 21.0
END DESCRIPTION:
XS GIS Cut Line= 3
       3718249.6     10608760.18      3718299.61     10608910.19
       3718699.6     10609310.18
#Sta/Elev= 30
    4851  275.08  4872.1  272.21  4893.2  267.54  4903.7  261.81  4914.3  259.04
  4924.8  253.98  4935.3  252.74  4945.9  249.81    4967  247.37    4988  246.47
  4998.6  244.21  5020.3  244.19    5023  243.69  5026.3  244.19  5037.4  247.29
  5051.6  248.14  5065.7  246.76  5108.1   246.9  5150.5  249.88  5164.7  246.87
  5178.8  245.73  5235.4  246.69    5292  250.01  5306.1  250.88  5320.3  255.72
  5334.4  256.01  5348.5  260.73  5433.4  267.26  5546.5  278.35  5574.8  280.26
#Mann= 3 ,-1 , 0
    4851     .12       0  5020.3     .07       0  5026.3     .12       0
Bank Sta=4988,5037.4
XS Rating Curve= 0 ,0
Exp/Cntr=0.3,0.1

Type RM Length L Ch R = 1 ,10662   ,429,429,429
BEGIN DESCRIPTION:
UNT 137 IN BOCR 20.0
END DESCRIPTION:
XS GIS Cut Line= 3
      3717965.11     10608596.72      3718038.04     10609104.57
      3718238.55     10609661.84
#Sta/Elev= 30
  4440.4   280.6  4514.6  279.92  4573.9  274.86  4595.4  274.81  4625.7  271.61
  4656.1  271.07  4696.5  266.76    4720  266.32  4790.5  257.92  4797.5  254.35
  4807.6  252.73  4817.7  248.82  4837.9  246.56  4888.4  245.22  4968.8  245.76
  4980.7  244.26  5004.8  244.14  5035.5  246.12  5060.9  244.64    5117   244.5
  5119.4  243.94  5122.1  243.44  5125.4  243.94  5129.5  244.88  5140.1   246.5
  5193.2   246.8  5301.3  252.71  5352.1  257.37    5427  270.14  5545.7  278.73
#Mann= 3 ,-1 , 0
  4440.4     .12       0  5119.4     .07       0  5125.4     .12       0
Bank Sta=5117,5129.5
XS Rating Curve= 0 ,0
Exp/Cntr=0.3,0.1

Type RM Length L Ch R = 1 ,10233   ,144,144,144
BEGIN DESCRIPTION:
UNT 137 IN BOCR 19.0
END DESCRIPTION:
XS GIS Cut Line= 3
      3717603.14     10608656.66      3717663.04     10609219.15
      3717665.63     10609896.98
#Sta/Elev= 30
  4362.5  280.83  4396.2  280.26  4466.2  282.92  4478.7  282.16  4516.9  281.06
  4683.4  267.94    4708   264.9    4718  260.81  4738.1  261.39  4748.2  260.54
  4758.7  256.73  4768.3  256.15  4798.5     249  4858.8   247.7  4868.9  246.44
    4899  244.29  4996.2  243.99    4999  243.49  5002.2  243.99  5059.2   244.2
  5087.8  245.91  5089.2  246.01  5319.2  255.02  5359.2  255.57  5389.2  258.84
  5409.2  263.08  5419.2  267.45  5463.1  269.62  5555.2  274.82    5606  277.96
#Mann= 8 ,-1 , 0
  4362.5     .12       0  4478.7     .05       0  4683.4     .12       0
  4996.2     .07       0  5002.2     .12       0  5087.8     .05       0
  5463.1     .16       0  5555.2     .05       0
Bank Sta=4868.9,5089.2
XS Rating Curve= 0 ,0
Exp/Cntr=0.3,0.1

Type RM Length L Ch R = 1 ,10089   ,92,92,92
BEGIN DESCRIPTION:
Mapping XS ab17ad54
END DESCRIPTION:
XS GIS Cut Line= 2
      3717400.58     10608875.05      3717640.18     10609741.01
#Sta/Elev= 30
  4554.6  271.32  4685.9  264.28  4754.5  257.67  4759.7  258.92  4767.4  256.49
  4788.2  254.18  4794.1  252.07  4799.2  253.32  4819.3  250.22  4860.8  249.83
  4902.2  246.43  4912.7  244.07  4969.4  244.15  5047.6  244.15    5052  243.93
  5054.7  243.43    5058  243.93  5060.2  244.22  5072.2  244.16  5161.7   246.1
    5224  253.06  5275.9  256.56  5286.8  259.04  5321.1     257  5338.1  257.69
  5379.6  263.39  5389.8  266.93  5394.9  266.02  5400.4  267.66  5453.1  270.38
#Mann= 5 ,-1 , 0
  4554.6     .05       0  4969.4     .07       0    5052     .07       0
    5058     .07       0  5072.2     .05       0
Bank Sta=5047.6,5060.2
XS Rating Curve= 0 ,0
Exp/Cntr=0.3,0.1

Type RM Length L Ch R = 1 ,9997    ,86,86,86
BEGIN DESCRIPTION:
Mapping XS e03ca5ca
END DESCRIPTION:
XS GIS Cut Line= 3
      3717304.23     10608876.39      3717373.25     10609195.41
      3717615.04     10609743.99
#Sta/Elev= 30
  4532.9  273.08  4587.9  269.28  4598.2  265.76  4618.6  266.08  4631.6  263.71
  4648.9  263.36  4733.4  257.03  4788.1  251.33  4884.2  244.58  4907.5  244.88
  4941.7  244.36  4962.1   244.2  4964.8   243.7  4968.1   244.2  4995.7  244.75
  5006.3     246  5011.7  244.28  5028.4  246.59  5050.7  245.49  5110.5  247.79
  5139.3  246.79  5203.3  252.96  5225.2  252.75  5301.7  258.78  5354.7   265.1
  5383.5  265.86    5400  268.27  5421.9  267.97  5453.5  272.42  5458.8  271.28
#Mann= 8 ,-1 , 0
  4532.9     .05       0  4648.9     .12       0  4733.4     .07       0
  4788.1     .05       0  4941.7     .07       0  4962.1     .07       0
  4968.1     .07       0  5050.7     .05       0
Bank Sta=4907.5,4995.7
XS Rating Curve= 0 ,0
Exp/Cntr=0.3,0.1