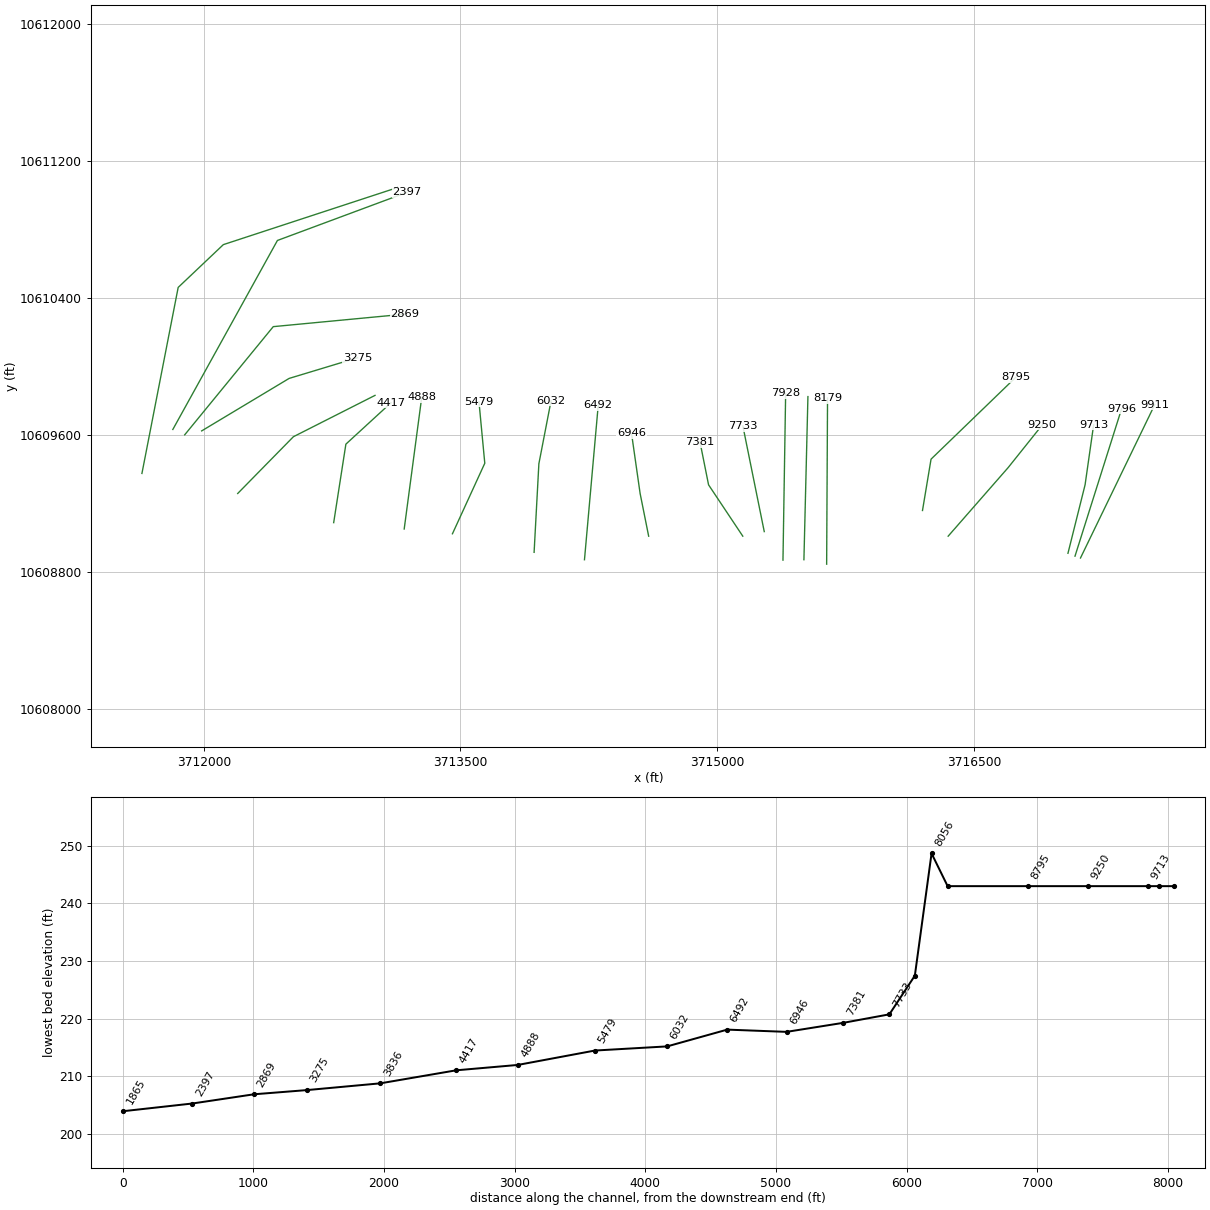
HEC-RAS study UNT 137 IN BOCR.prj: UNT 137 IN BOCR Base Level Engineering

--- UNT 137 IN BOCR.g01 (geometry) --- (continued)

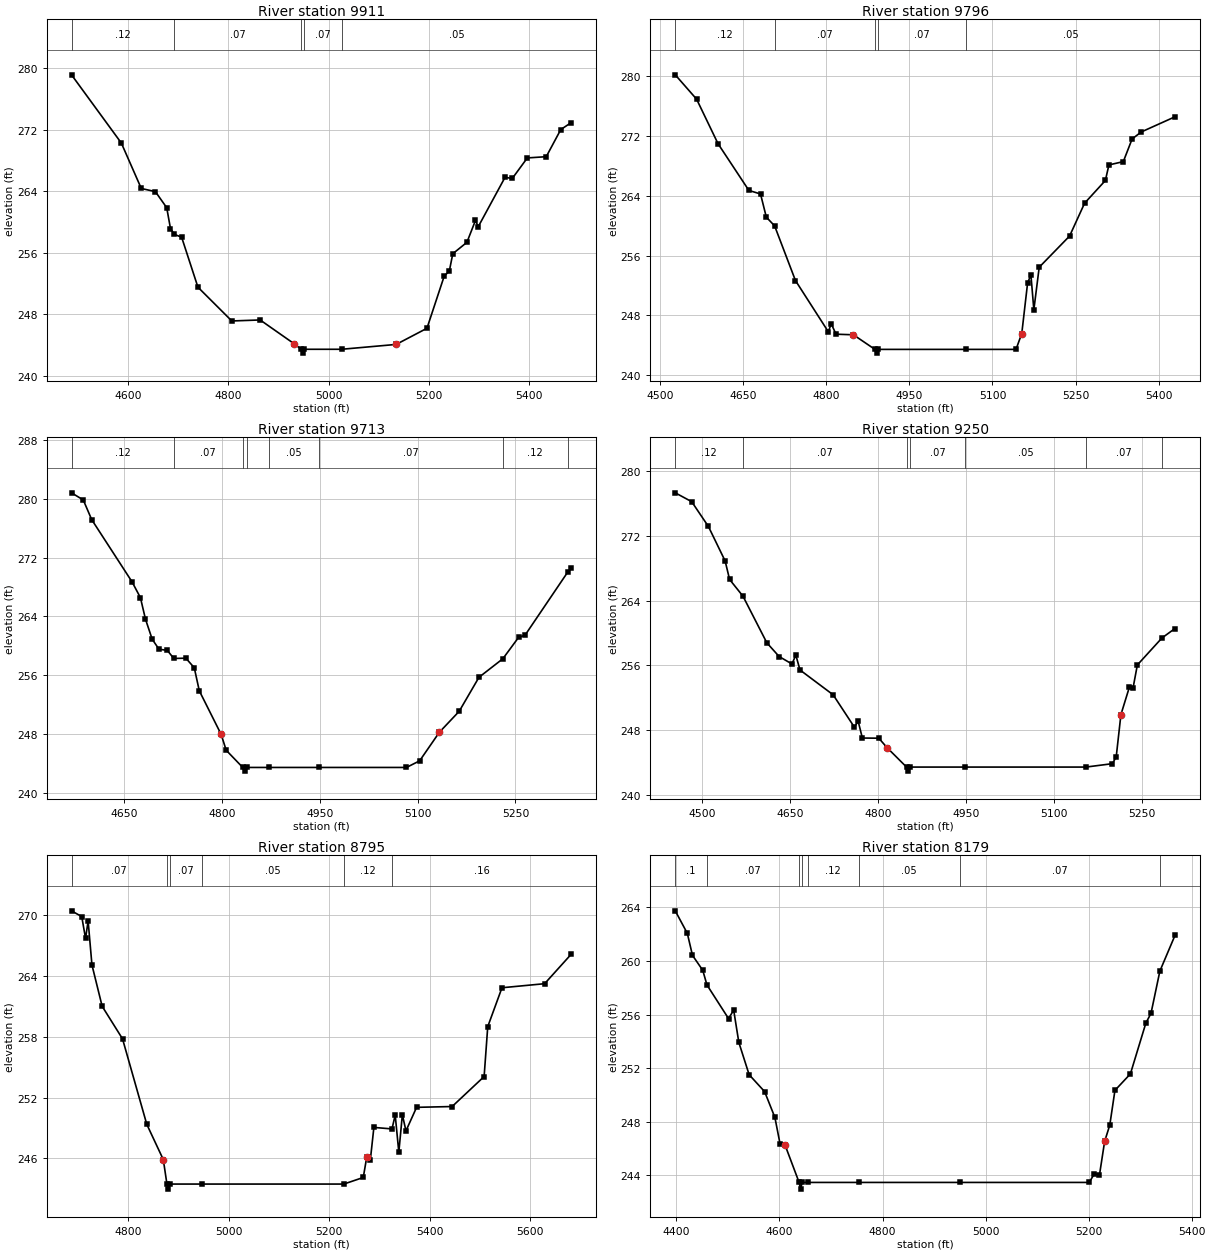
Type RM Length L Ch R = 1 ,9911    ,115,115,115
BEGIN DESCRIPTION:
Mapping XS 4c0bde65
END DESCRIPTION:
XS GIS Cut Line= 2
      3717122.81     10608882.68      3717556.82     10609778.92
#Sta/Elev= 30
  4487.7  279.14    4587  270.27  4626.7  264.37  4654.8  263.96  4677.4  261.87
  4684.9  259.16  4692.6   258.4  4707.1  258.04  4739.6  251.54  4807.1  247.15
  4863.6  247.28  4931.3  244.19  4945.4  243.47  4948.1  242.97  4951.4  243.47
  5025.8  243.47  5134.6   244.1    5196   246.2  5230.5     253  5240.5  253.62
  5247.5  255.89  5275.6  257.37  5292.7  260.22  5298.2   259.4  5351.6  265.82
    5366  265.67    5396  268.34  5433.7   268.5  5462.7  272.03  5483.5  272.93
#Mann= 5 ,-1 , 0
  4487.7     .12       0  4692.6     .07       0  4945.4     .07       0
  4951.4     .07       0  5025.8     .05       0
Bank Sta=4931.3,5134.6
XS Rating Curve= 0 ,0
Exp/Cntr=0.3,0.1

Type RM Length L Ch R = 1 ,9796    ,83,83,83
BEGIN DESCRIPTION:
Mapping XS 0da774d0
END DESCRIPTION:
XS GIS Cut Line= 2
      3717090.71     10608893.36      3717362.82     10609753.97
#Sta/Elev= 30
    4527  280.16  4565.6   276.9  4604.3  270.95    4660  264.71    4681  264.24
  4691.5  261.14  4706.5  259.97  4744.1  252.67  4803.5  245.82  4808.7  246.91
  4817.3   245.5  4848.8  245.42  4887.7  243.47  4890.5  242.97  4893.7  243.47
  5051.8  243.47  5142.5  243.47  5152.9  245.59  5163.4  252.33  5169.4  253.45
  5174.7  248.76  5184.4  254.45  5239.3  258.62  5266.4  263.01  5303.9  266.04
  5310.3  268.12  5336.3  268.56  5352.2  271.59  5368.6  272.52  5429.6  274.55
#Mann= 5 ,-1 , 0
    4527     .12       0  4706.5     .07       0  4887.7     .07       0
  4893.7     .07       0  5051.8     .05       0
Bank Sta=4848.8,5152.9
XS Rating Curve= 0 ,0
Exp/Cntr=0.3,0.1

Type RM Length L Ch R = 1 ,9713    ,463,463,463
BEGIN DESCRIPTION:
UNT 137 IN BOCR 18.0
END DESCRIPTION:
XS GIS Cut Line= 3
      3717049.62     10608910.23      3717149.61     10609310.19
      3717199.61     10609660.17
#Sta/Elev= 30
  4569.7  280.79  4587.7  279.82  4600.6  277.15  4662.4   268.7  4675.3  266.54
    4683  263.63  4693.3   260.9  4703.7  259.54  4716.5  259.38  4726.4  258.28
  4744.9  258.32  4757.8  257.02  4765.5  253.89    4799  247.96  4806.7  245.81
  4832.1  243.47  4834.8  242.97  4838.1  243.47  4871.8  243.47  4948.3  243.47
    5083  243.47  5103.2  244.37  5133.5  248.26  5163.8   251.1  5194.1  255.72
  5230.7  258.24  5254.7  261.13  5264.8  261.45  5330.3  270.04  5335.5  270.52
#Mann= 8 ,-1 , 0
  4569.7     .12       0  4726.4     .07       0  4832.1     .07       0
  4838.1     .07       0  4871.8     .05       0  4948.3     .07       0
  5230.7     .12       0  5330.3     .16       0
Bank Sta=4799,5133.5
XS Rating Curve= 0 ,0
Exp/Cntr=0.3,0.1

Type RM Length L Ch R = 1 ,9250    ,455,455,455
BEGIN DESCRIPTION:
UNT 137 IN BOCR 17.0
END DESCRIPTION:
XS GIS Cut Line= 3
       3716349.6     10609010.18      3716699.61     10609410.19
      3716899.62      10609660.2
#Sta/Elev= 30
  4454.3  277.28  4482.3  276.19  4510.8  273.13  4539.3  268.88  4546.9   266.6
  4569.7  264.54  4610.4  258.79  4631.3   257.1  4653.2  256.18  4659.8  257.27
  4666.9  255.44  4723.4  252.38  4759.5   248.4  4766.1  249.11  4773.2  247.05
  4801.2  247.03  4815.5  245.85  4848.5  243.47  4851.3  242.97  4854.5  243.47
    4948  243.47  5154.3  243.47  5199.5  243.89  5205.9  244.75  5213.9  249.94
  5228.3  253.32  5234.7  253.27  5241.9  256.06  5283.9  259.39    5306  260.55
#Mann= 7 ,-1 , 0
  4454.3     .12       0  4569.7     .07       0  4848.5    .033       0
  4854.5     .07       0    4948     .05       0  5154.3     .07       0
  5283.9     .12       0
Bank Sta=4815.5,5213.9
XS Rating Curve= 0 ,0
Exp/Cntr=0.3,0.1

Type RM Length L Ch R = 1 ,8795    ,616,616,616
BEGIN DESCRIPTION:
UNT 137 IN BOCR 16.0
END DESCRIPTION:
XS GIS Cut Line= 3
       3716199.6     10609160.15      3716249.61     10609460.19
      3716745.51     10609939.13
#Sta/Elev= 30
  4687.8  270.43  4708.1  269.86  4715.7  267.71  4720.8  269.43  4728.4  265.09
  4748.7  261.01  4789.2   257.8  4837.4  249.37  4870.3  245.88  4877.5  243.47
  4880.2  242.97  4883.5  243.47  4947.3  243.47  5229.2  243.47  5267.9  244.12
  5274.8  246.13    5282  245.87    5289  249.06    5325  248.91  5331.4  250.28
  5338.6  246.61  5345.6  250.31  5352.8  248.72  5373.9  251.04  5444.6  251.12
  5508.2  254.08  5515.4     259  5543.7  262.84  5628.5  263.24  5681.4  266.15
#Mann= 6 ,-1 , 0
  4687.8     .07       0  4877.5    .033       0  4883.5     .07       0
  4947.3     .05       0  5229.2     .12       0    5325     .16       0
Bank Sta=4870.3,5274.8
XS Rating Curve= 0 ,0
Exp/Cntr=0.3,0.1

Type RM Length L Ch R = 1 ,8179    ,123,123,123
BEGIN DESCRIPTION:
UNT 137 IN BOCR 15.0
END DESCRIPTION:
XS GIS Cut Line= 2
       3715639.6     10608846.79       3715644.8     10609816.68
#Sta/Elev= 30
  4397.7  263.74  4421.1  262.06  4431.1  260.42  4451.1   259.3  4459.2  258.21
  4501.1   255.7  4511.1  256.33  4521.1  253.92  4541.1  251.51  4571.1  250.25
  4591.1  248.32  4601.1  246.35  4611.1  246.23  4638.1  243.47  4640.8  242.97
  4644.1  243.47  4655.4  243.47  4753.5  243.47  4949.7  243.47  5201.1  243.47
  5211.1  244.11  5221.1  244.03  5231.1  246.53  5241.1  247.75  5251.1  250.34
  5281.1  251.57  5311.1  255.36  5321.1  256.09  5338.3  259.24  5367.6   261.9
#Mann= 8 ,-1 , 0
  4397.7      .1       0  4459.2     .07       0  4638.1     .07       0
  4644.1     .07       0  4655.4     .12       0  4753.5     .05       0
  4949.7     .07       0  5338.3     .12       0
Bank Sta=4611.1,5231.1
XS Rating Curve= 0 ,0
Exp/Cntr=0.3,0.1

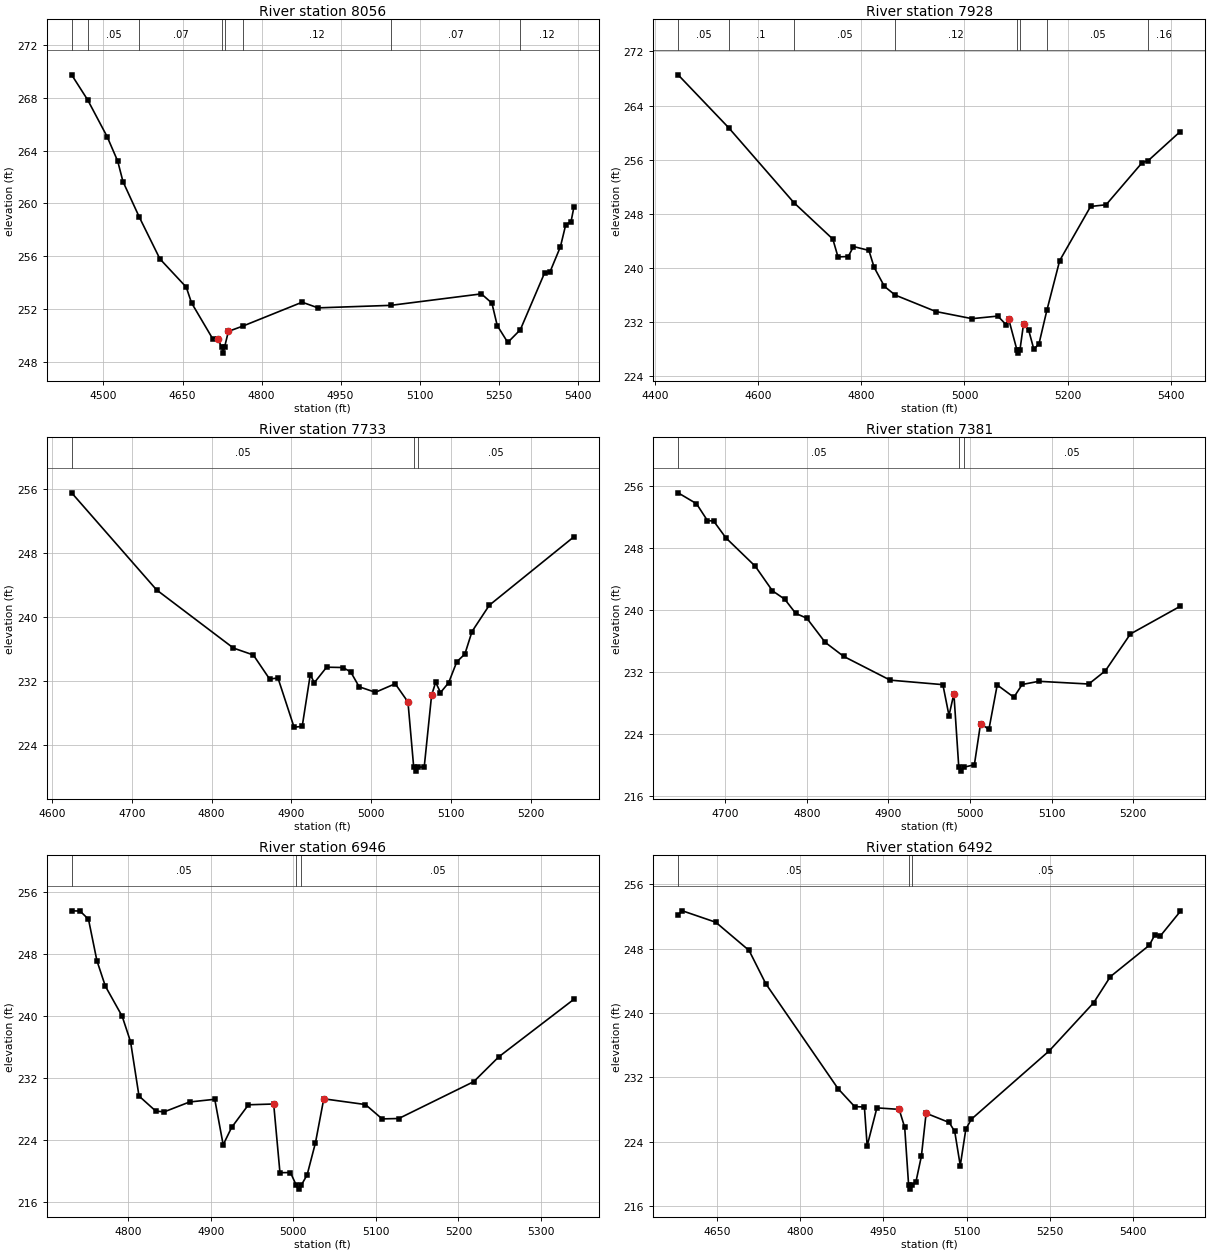
Type RM Length L Ch R = 1 ,8056    ,128,128,128
BEGIN DESCRIPTION:
Mapping XS fc1c2f98
END DESCRIPTION:
XS GIS Cut Line= 2
      3715506.79     10608872.78      3715530.22     10609825.59
#Sta/Elev= 30
  4439.6  269.74    4470  267.84    4507  265.05    4527   263.2    4537  261.65
  4568.2  258.94  4607.1  255.79  4657.1  253.65  4667.1  252.46  4707.1  249.75
  4717.1  249.69  4724.1  249.15  4726.8  248.65  4730.1  249.15  4737.1   250.3
  4764.6   250.7  4877.1  252.51  4907.1  252.08  5045.2  252.27  5217.2  253.14
  5237.2  252.44  5247.3  250.74  5267.3  249.46  5291.1  250.42  5337.3  254.74
  5347.3  254.79  5367.3  256.72  5377.3  258.38  5387.3   258.6  5392.7  259.69
#Mann= 8 ,-1 , 0
  4439.6     .12       0    4470     .05       0  4568.2     .07       0
  4724.1     .07       0  4730.1     .07       0  4764.6     .12       0
  5045.2     .07       0  5291.1     .12       0
Bank Sta=4717.1,4737.1
XS Rating Curve= 0 ,0
Exp/Cntr=0.3,0.1

Type RM Length L Ch R = 1 ,7928    ,195,195,195
BEGIN DESCRIPTION:
Mapping XS 19a6c0a4
END DESCRIPTION:
XS GIS Cut Line= 2
      3715384.39     10608870.17      3715400.01     10609844.15
#Sta/Elev= 30
  4444.6  268.54  4542.5  260.74  4669.2  249.66  4744.7  244.28  4754.7  241.65
  4774.7  241.71  4784.7  243.18  4814.7  242.61  4824.7  240.13  4844.7   237.3
  4865.5  236.02  4944.7  233.58  5014.7  232.53  5064.7  232.91  5080.7  231.65
  5085.7  232.49  5101.7  227.94  5104.5  227.44  5107.7  227.94  5114.7  231.79
  5124.7   230.8  5134.7  227.98  5144.7  228.86  5159.9  233.77  5184.7   241.1
  5244.7   249.1  5274.7  249.35  5344.7  255.57  5356.2  255.85  5418.7  260.17
#Mann= 8 ,-1 , 0
  4444.6     .05       0  4542.5      .1       0  4669.2     .05       0
  4865.5     .12       0  5101.7     .07       0  5107.7     .12       0
  5159.9     .05       0  5356.2     .16       0
Bank Sta=5085.7,5114.7
XS Rating Curve= 0 ,0
Exp/Cntr=0.3,0.1

Type RM Length L Ch R = 1 ,7733    ,352,352,352
BEGIN DESCRIPTION:
UNT 137 IN BOCR 14.0
END DESCRIPTION:
XS GIS Cut Line= 2
      3715275.01     10609036.88      3715150.01     10609654.05
#Sta/Elev= 30
  4624.6  255.54  4731.2  243.39  4827.5  236.12  4852.4  235.26  4872.8  232.25
  4883.3  232.38  4903.5  226.22  4913.7  226.33  4923.8  232.79  4928.9  231.79
  4944.3  233.73  4964.7  233.69  4974.5  233.14  4985.1  231.28  5005.5  230.59
  5030.3  231.66  5046.3  229.38  5053.5  221.23  5056.2  220.73  5059.5  221.23
  5066.7  221.25  5075.9  230.19    5081  231.85  5087.1  230.56  5097.3  231.78
  5107.5   234.4  5117.7  235.38  5126.6  238.19  5148.3  241.48  5254.3  250.03
#Mann= 3 ,-1 , 0
  4624.6     .05       0  5053.5     .03       0  5059.5     .05       0
Bank Sta=5046.3,5075.9
XS Rating Curve= 0 ,0
Exp/Cntr=0.3,0.1

Type RM Length L Ch R = 1 ,7381    ,435,435,435
BEGIN DESCRIPTION:
UNT 137 IN BOCR 13.0
END DESCRIPTION:
XS GIS Cut Line= 3
      3715149.58     10609010.23      3714949.61     10609310.19
       3714899.6     10609560.23
#Sta/Elev= 30
  4642.2  255.14  4664.7  253.74  4678.2  251.55  4685.7  251.51  4700.7  249.34
  4736.8  245.67  4757.8  242.51  4772.9  241.42  4786.4  239.59  4799.9  238.98
  4822.4  235.87    4845  234.06  4902.1  230.99  4966.7  230.41  4974.2  226.43
  4980.2  229.23  4986.2  219.76  4988.9  219.26  4992.2  219.76  5005.3  220.08
  5012.9   225.4  5023.1  224.63  5033.3  230.37  5053.7  228.78  5063.9  230.43
  5084.3  230.84  5145.5  230.49  5165.9   232.2  5196.5  236.94  5257.7  240.52
#Mann= 3 ,-1 , 0
  4642.2     .05       0  4986.2     .03       0  4992.2     .05       0
Bank Sta=4980.2,5012.9
XS Rating Curve= 0 ,0
Exp/Cntr=0.3,0.1

Type RM Length L Ch R = 1 ,6946    ,454,454,454
BEGIN DESCRIPTION:
UNT 137 IN BOCR 12.0
END DESCRIPTION:
XS GIS Cut Line= 3
      3714599.61     10609010.19      3714549.61     10609260.19
      3714499.61     10609610.18
#Sta/Elev= 30
  4731.4  253.59  4741.6  253.56  4751.8   252.5    4762  247.16  4772.2  243.88
  4792.6  239.99  4802.8   236.7    4813   229.7  4833.4  227.75  4843.6  227.66
  4874.2  228.93  4904.8  229.28    4915  223.41  4925.2  225.64  4945.6  228.57
  4976.2  228.67  4983.8  219.81  4996.5  219.83  5003.6  218.19  5006.3  217.69
  5009.6  218.19  5016.7  219.52  5026.8  223.66  5036.9  229.34  5087.4   228.6
  5107.6  226.75  5127.8   226.8  5218.7  231.56    5249  234.76  5339.9  242.17
#Mann= 3 ,-1 , 0
  4731.4     .05       0  5003.6     .03       0  5009.6     .05       0
Bank Sta=4976.2,5036.9
XS Rating Curve= 0 ,0
Exp/Cntr=0.3,0.1

Type RM Length L Ch R = 1 ,6492    ,460,460,460
BEGIN DESCRIPTION:
UNT 137 IN BOCR 11.0
END DESCRIPTION:
XS GIS Cut Line= 2
      3714224.56     10608872.46      3714305.02     10609776.09
#Sta/Elev= 30
    4579  252.24  4586.8   252.7    4647  251.28  4707.2  247.77  4737.4  243.63
  4867.9  230.58    4898  228.34  4915.5   228.3  4920.5  223.46  4938.1  228.19
  4978.3     228  4988.3  225.77  4995.4  218.58  4998.1  218.08  5001.4  218.58
  5008.4  218.92  5018.5  222.19    5027  227.52  5068.7  226.37  5078.7  225.25
  5088.7     221  5098.8  225.55  5108.8  226.78  5249.4  235.28  5329.7  241.27
  5359.8  244.51  5430.1  248.41  5440.1  249.69  5450.2  249.58  5486.2  252.63
#Mann= 3 ,-1 , 0
    4579     .05       0  4995.4     .03       0  5001.4     .05       0
Bank Sta=4978.3,5027
XS Rating Curve= 0 ,0
Exp/Cntr=0.3,0.1

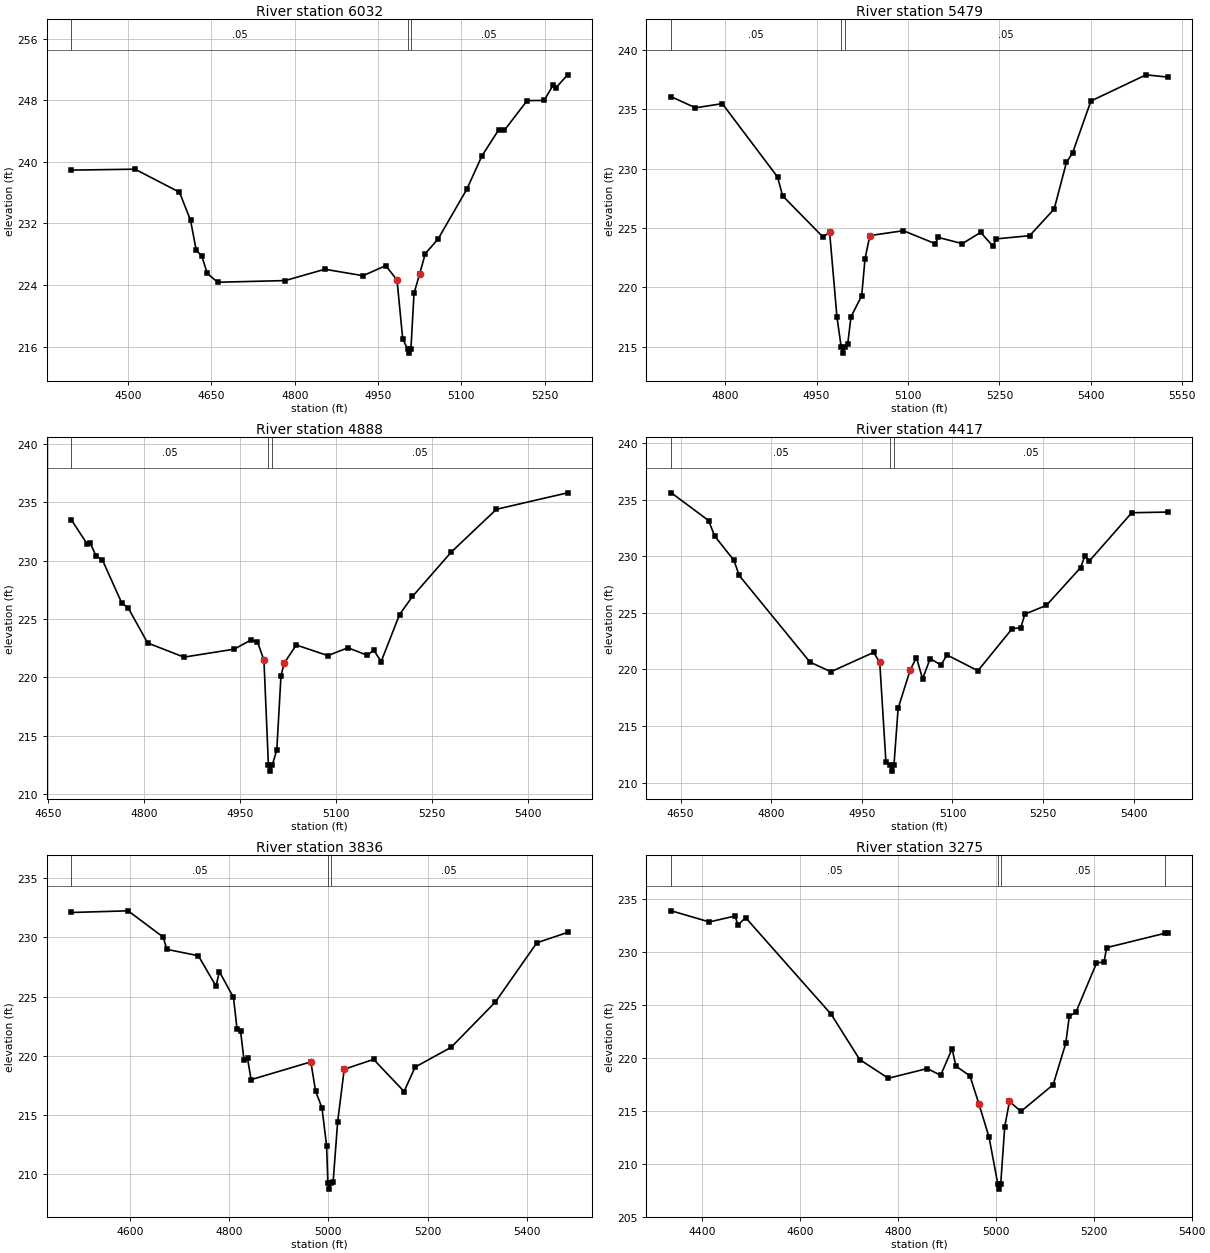
Type RM Length L Ch R = 1 ,6032    ,553,553,553
BEGIN DESCRIPTION:
UNT 137 IN BOCR 10.0
END DESCRIPTION:
XS GIS Cut Line= 3
      3713930.25     10608915.76      3713958.13     10609433.14
      3714029.38     10609801.78
#Sta/Elev= 30
  4397.8  238.93  4512.4  239.05  4592.5  236.06  4612.5  232.39  4622.6  228.54
  4632.6  227.77  4642.6  225.52  4661.2  224.37  4782.8  224.59  4854.2  226.06
  4923.1  225.22  4963.9  226.53  4984.2  224.66  4994.4  217.06  5003.2  215.67
    5006  215.17  5009.2  215.67  5014.8  222.92    5025  225.47  5035.1  228.09
    5058  229.97  5109.9  236.45    5137  240.76  5167.6   244.2  5177.7  244.12
  5218.6  247.96    5249  247.97  5265.3  249.96  5270.4  249.63  5291.4   251.3
#Mann= 3 ,-1 , 0
  4397.8     .05       0  5003.2     .03       0  5009.2     .05       0
Bank Sta=4984.2,5025
XS Rating Curve= 0 ,0
Exp/Cntr=0.3,0.1

Type RM Length L Ch R = 1 ,5479    ,591,591,591
BEGIN DESCRIPTION:
UNT 137 IN BOCR 9.0
END DESCRIPTION:
XS GIS Cut Line= 3
      3713453.14     10609024.17      3713642.14     10609436.24
      3713608.08     10609795.39
#Sta/Elev= 30
  4711.8  236.06  4751.4  235.13  4795.4  235.48  4886.1   229.3  4894.4  227.71
  4960.6  224.24  4971.5  224.63  4983.6  217.47  4990.5  214.95  4993.2  214.45
  4996.5  214.95  5001.1  215.19  5006.6  217.52  5024.1  219.28  5029.6  222.41
  5037.5  224.36  5092.5  224.77  5144.5  223.68    5150   224.2  5189.2  223.68
  5219.3  224.63  5239.4  223.46  5244.7  224.08  5299.7  224.35  5339.9   226.6
    5360  230.53    5370  231.32  5400.1   235.7  5490.5  237.91  5525.9  237.72
#Mann= 3 ,-1 , 0
  4711.8     .05       0  4990.5     .03       0  4996.5     .05       0
Bank Sta=4971.5,5037.5
XS Rating Curve= 0 ,0
Exp/Cntr=0.3,0.1

Type RM Length L Ch R = 1 ,4888    ,471,471,471
BEGIN DESCRIPTION:
UNT 137 IN BOCR 8.0
END DESCRIPTION:
XS GIS Cut Line= 2
      3713171.25     10609052.06      3713273.48     10609820.38
#Sta/Elev= 30
  4686.7  233.49  4711.1  231.44  4716.2  231.48  4725.2   230.4  4735.3  230.03
  4765.5  226.35  4775.6  225.92  4805.9  222.93  4862.6  221.72  4940.9   222.4
  4967.3  223.19  4977.4  223.02  4987.5  221.46  4994.5  212.45  4997.3  211.95
  5000.5  212.45  5007.6  213.79  5014.1  220.12  5019.1   221.2  5037.9  222.76
  5087.3  221.85  5118.6  222.52  5148.9  221.88    5159  222.31  5170.6  221.34
  5199.3  225.37  5219.5  226.92    5280  230.72  5350.6  234.39  5461.8   235.8
#Mann= 3 ,-1 , 0
  4686.7     .05       0  4994.5     .03       0  5000.5     .05       0
Bank Sta=4987.5,5019.1
XS Rating Curve= 0 ,0
Exp/Cntr=0.3,0.1

Type RM Length L Ch R = 1 ,4417    ,581,581,581
BEGIN DESCRIPTION:
UNT 137 IN BOCR 7.0
END DESCRIPTION:
XS GIS Cut Line= 3
      3712759.22     10609089.25      3712830.48     10609547.77
      3713093.79      10609789.4
#Sta/Elev= 30
  4634.6  235.61  4696.3  233.16  4706.4  231.79  4738.3  229.64  4746.9  228.31
  4864.2  220.65  4898.7   219.8  4969.5  221.51  4979.6  220.62  4989.8  211.84
  4997.1  211.52  4999.9  211.02  5003.1  211.52    5010  216.57  5030.2  219.99
  5040.4  221.05  5050.5  219.17    5063  220.96  5080.8   220.4    5091  221.28
  5142.1  219.89  5198.8  223.61    5213  223.68  5219.8  224.89  5255.5  225.67
  5312.2  229.01    5319  230.03  5326.4  229.58  5396.7  233.85    5456  233.91
#Mann= 3 ,-1 , 0
  4634.6     .05       0  4997.1     .03       0  5003.1     .05       0
Bank Sta=4979.6,5030.2
XS Rating Curve= 0 ,0
Exp/Cntr=0.3,0.1

Type RM Length L Ch R = 1 ,3836    ,561,561,561
BEGIN DESCRIPTION:
UNT 137 IN BOCR 6.0
END DESCRIPTION:
XS GIS Cut Line= 3
      3712198.48     10609259.64      3712523.78     10609591.14
      3713000.83     10609832.76
#Sta/Elev= 30
  4482.4  232.11  4596.7  232.25  4667.4  230.03  4674.5     229  4738.1  228.46
  4773.5   225.9  4780.5  227.11  4808.8  224.94    4816  222.28    4823  222.13
  4830.1  219.63  4837.1   219.8  4844.3     218  4964.6   219.5  4974.1  217.04
    4987  215.61  4996.3  212.43  4998.9  209.26  5001.7  208.76  5004.9  209.26
  5009.4  209.34  5018.6  214.45  5031.8  218.88    5091  219.71  5152.3     217
  5174.5  219.06    5247  220.73  5336.1  224.55  5419.6  229.55  5481.6  230.43
#Mann= 3 ,-1 , 0
  4482.4     .05       0  4998.9     .03       0  5004.9     .05       0
Bank Sta=4964.6,5031.8
XS Rating Curve= 0 ,0
Exp/Cntr=0.3,0.1

Type RM Length L Ch R = 1 ,3275    ,406,406,406
BEGIN DESCRIPTION:
UNT 137 IN BOCR 5.0
END DESCRIPTION:
XS GIS Cut Line= 3
      3711987.87     10609625.23        3712499.     10609931.91
      3712898.66     10610052.74
#Sta/Elev= 30
  4337.2   233.9  4414.9  232.85  4467.4  233.41  4473.3  232.55  4488.8  233.26
  4663.7  224.12    4722  219.84  4780.4  218.07    4860  218.99  4887.3  218.35
  4910.7  220.86  4918.4  219.22  4947.1   218.3  4965.3  215.67  4986.1  212.51
    5004  208.09  5006.8  207.59    5010  208.09  5018.2  213.49  5027.9  215.89
  5051.2  214.93  5117.1  217.46  5142.9  221.38    5150  223.92  5163.7  224.33
  5205.5  228.94  5221.1   229.1  5226.4  230.42  5346.4  231.79  5350.8  231.82
#Mann= 4 ,-1 , 0
  4337.2     .05       0    5004     .03       0    5010     .05       0
  5346.4     .12       0
Bank Sta=4965.3,5027.9
XS Rating Curve= 0 ,0
Exp/Cntr=0.3,0.1

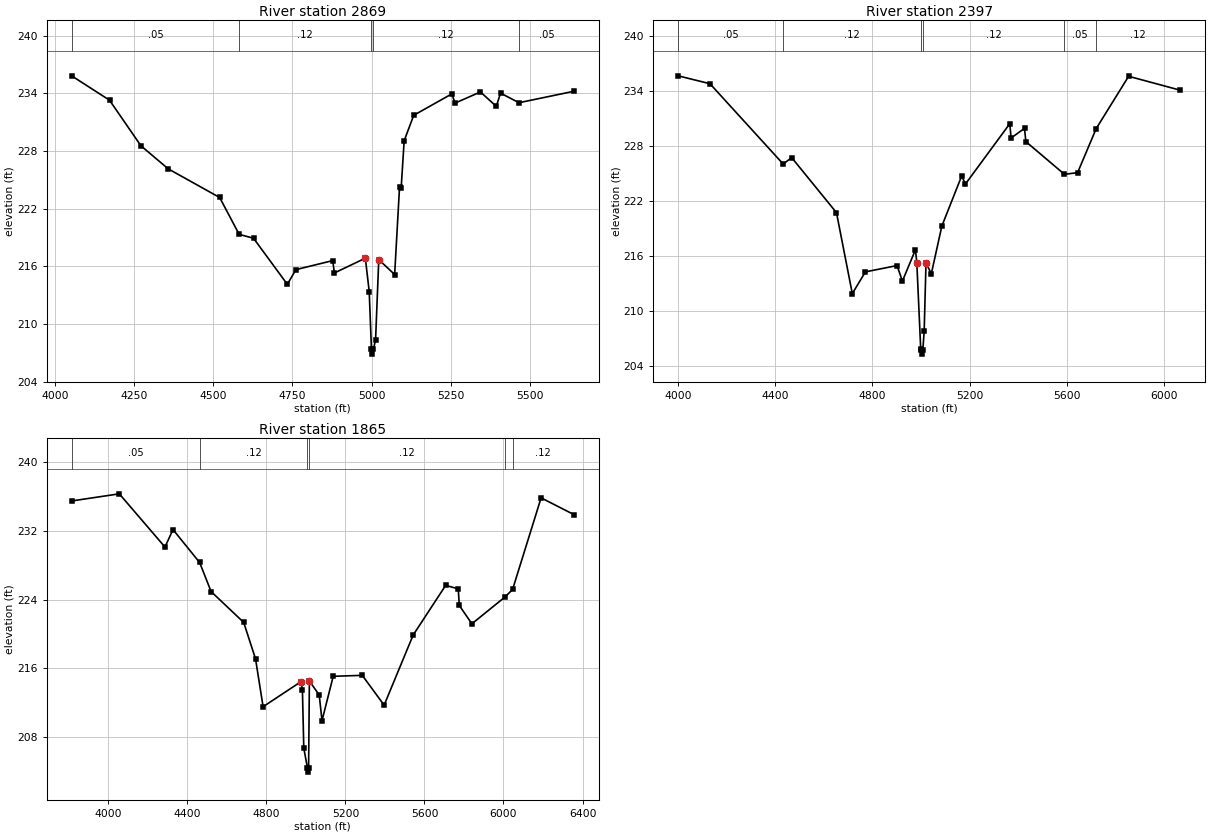
Type RM Length L Ch R = 1 ,2869    ,472,472,472
BEGIN DESCRIPTION:
UNT 137 IN BOCR 4.0
END DESCRIPTION:
XS GIS Cut Line= 3
      3711888.79     10609602.37      3712406.18     10610234.35
      3713173.57     10610307.26
#Sta/Elev= 30
  4051.9  235.84  4171.7   233.3  4270.8  228.56  4356.9  226.16  4519.8  223.17
  4581.5  219.33  4626.8  218.93  4733.7  214.13    4761  215.66  4877.3   216.6
  4882.4  215.31  4980.4  216.85  4992.6  213.38  4999.7  207.36  5002.4  206.86
  5005.7  207.36  5012.7  208.33  5022.8   216.7    5073  215.15  5088.5  224.27
  5093.6  224.16  5103.1  229.08  5133.3  231.73  5253.8  233.96  5263.9     233
  5344.2  234.16  5394.4  232.66  5407.8  234.04  5466.1  233.04  5639.5  234.23
#Mann= 5 ,-1 , 0
  4051.9     .05       0  4581.5     .12       0  4999.7     .07       0
  5005.7     .12       0  5466.1     .05       0
Bank Sta=4980.4,5022.8
XS Rating Curve= 0 ,0
Exp/Cntr=0.3,0.1

Type RM Length L Ch R = 1 ,2397    ,532,532,532
BEGIN DESCRIPTION:
UNT 137 IN BOCR 3.0
END DESCRIPTION:
XS GIS Cut Line= 3
       3711819.4     10609633.69      3712430.49     10610737.82
      3713186.06     10611018.56
#Sta/Elev= 30
  3999.6  235.61  4130.7  234.75  4432.3  225.99  4467.3  226.69  4651.7  220.69
  4716.9  211.86  4770.8  214.23  4901.3  214.92  4923.1  213.22  4976.9  216.64
  4982.6   215.2  4998.6  205.84  5001.4  205.76  5004.1  205.26  5007.4  205.76
  5012.8  207.73  5020.4  215.22  5042.2  214.02  5085.7  219.23    5167  224.67
    5183  223.82  5365.4  230.39  5370.7  228.83  5426.1  229.88  5431.5  228.44
  5590.4  224.87  5644.7  225.05  5721.1  229.85  5854.8  235.56  6067.6  234.04
#Mann= 6 ,-1 , 0
  3999.6     .05       0  4432.3     .12       0  5001.4     .07       0
  5007.4     .12       0  5590.4     .05       0  5721.1     .12       0
Bank Sta=4982.6,5020.4
XS Rating Curve= 0 ,0
Exp/Cntr=0.3,0.1

Type RM Length L Ch R = 1 ,1865    ,748,748,748
BEGIN DESCRIPTION:
UNT 137 IN BOCR 2.0
END DESCRIPTION:
XS GIS Cut Line= 4
      3711638.83     10609376.72      3711850.63     10610463.51
      3712114.52     10610713.51      3713131.86     10611046.84
#Sta/Elev= 30
  3814.7  235.47  4055.8   236.3  4286.9  230.11  4327.6  232.14  4462.4  228.31
  4520.3  224.93  4685.3  221.34  4745.3  217.09  4783.5  211.53  4975.6  214.45
  4982.5  213.49  4989.4  206.72  5007.8  204.42  5010.6  203.92  5013.8  204.42
  5017.7  214.52  5067.5   212.9  5081.6  209.91  5138.3  215.07  5285.4  215.18
    5396  211.71  5542.9  219.87  5707.4  225.65  5771.1  225.24  5776.4  223.31
    5840  221.18  6007.3  224.29    6046  225.17  6190.3  235.83    6356  233.89
#Mann= 6 ,-1 , 0
  3814.7     .05       0  4462.4     .12       0  5007.8     .07       0
  5013.8     .12       0  6007.3     .05       0    6046     .12       0
Bank Sta=4975.6,5017.7
XS Rating Curve= 0 ,0
Exp/Cntr=0.3,0.1