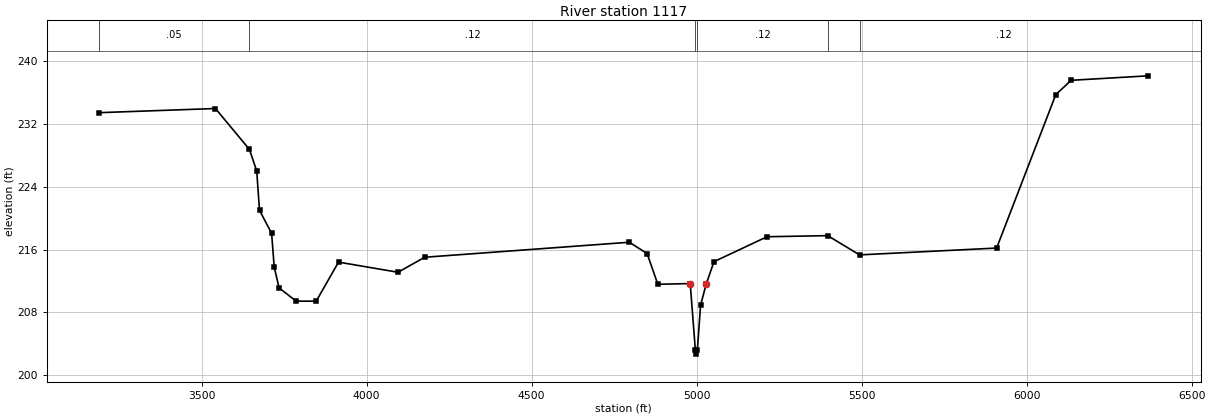
HEC-RAS study UNT 137 IN BOCR.prj: UNT 137 IN BOCR Base Level Engineering

--- UNT 137 IN BOCR.g01 (geometry) --- (continued)

Type RM Length L Ch R = 1 ,1117    ,0,0,0
BEGIN DESCRIPTION:
UNT 137 IN BOCR 1.0
END DESCRIPTION:
XS GIS Cut Line= 3
      3711046.33     10609603.03      3711733.83     10611012.75
      3713225.77     10611619.94
#Sta/Elev= 30
  3188.9  233.42  3541.8  233.95  3644.8  228.74  3666.9  225.99  3675.3  220.99
    3712  218.06  3719.8  213.79  3734.5  211.12  3786.5  209.43  3847.1  209.43
  3914.7   214.4    4095  213.11  4175.9  215.02    4796  216.93  4849.9  215.49
  4882.3  211.58  4980.5  211.67  4996.1  203.19  4998.9  202.69  5002.1  203.19
  5011.9  208.91  5028.6  211.57  5052.6  214.46  5213.2  217.63  5397.2  217.77
  5493.7  215.32    5909  216.19  6088.2  235.71  6134.7  237.54  6368.1  238.11
#Mann= 6 ,-1 , 0
  3188.9     .05       0  3644.8     .12       0  4996.1     .07       0
  5002.1     .12       0  5397.2     .07       0  5493.7     .12       0
Bank Sta=4980.5,5028.6
XS Rating Curve= 0 ,0
Exp/Cntr=0.3,0.1

Chan Stop Cuts=-1
Use User Specified Reach Order=0
Composite Channel Slope=5