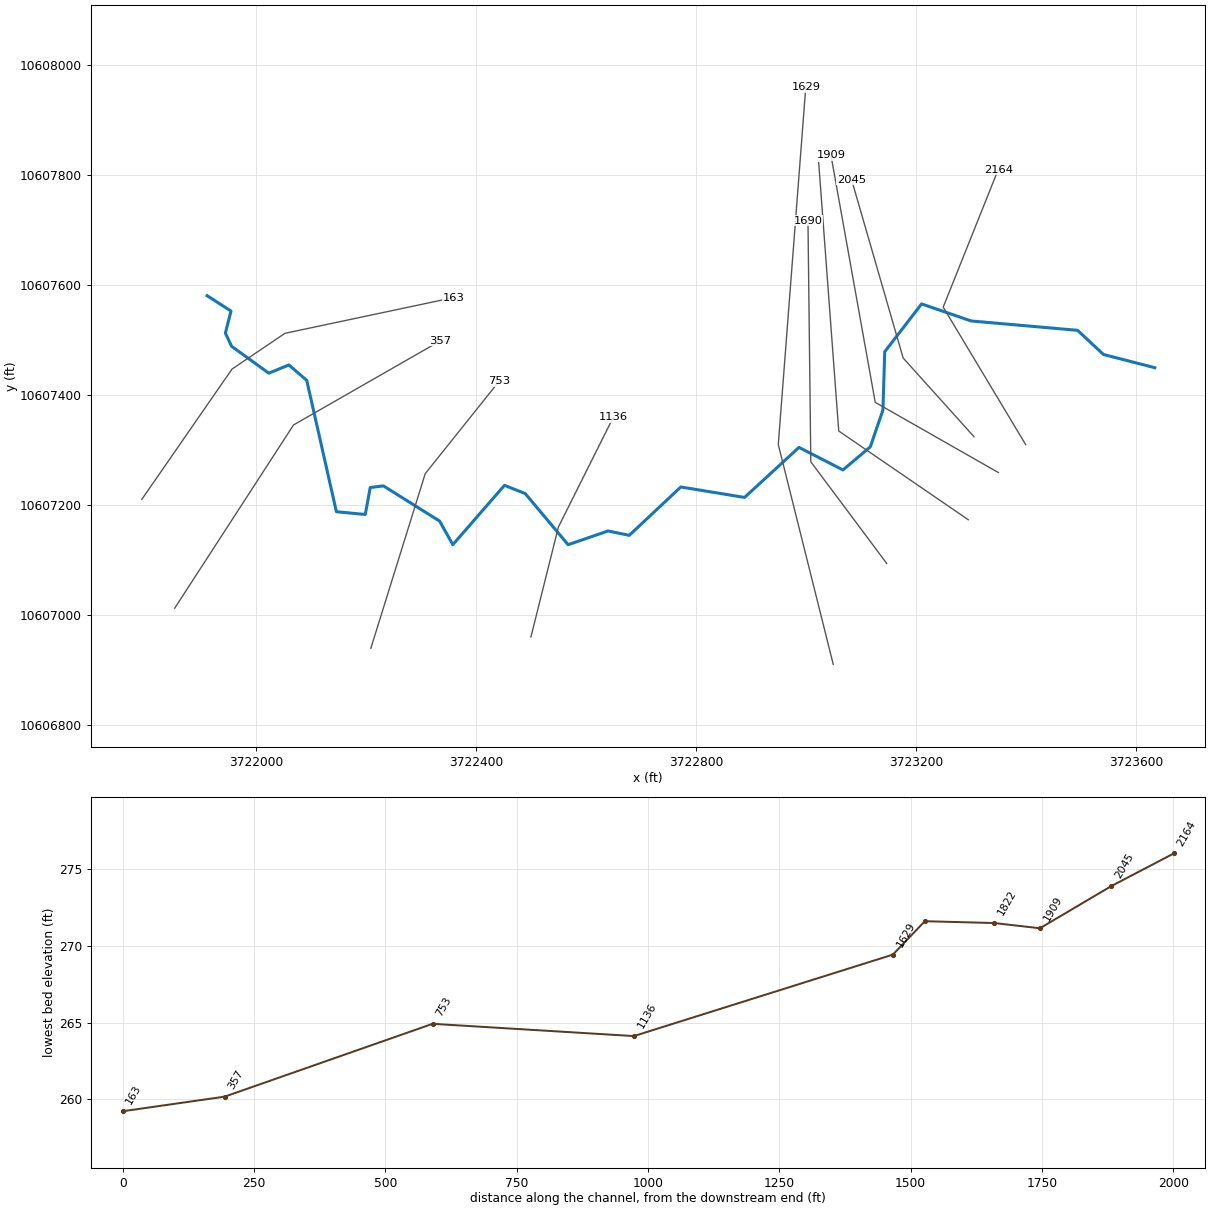
--- UNT 138 IN BOCR.prj (project) ---

Proj Title=UNT 138 IN BOCR Base Level Engineering
Current Plan=p01
Default Exp/Contr=0.3,0.1
English Units
Geom File=g01
Flow File=f01
Plan File=p01
Y Axis Title=Elevation
X Axis Title(PF)=Main Channel Distance
X Axis Title(XS)=Station
BEGIN DESCRIPTION:
UNT 138 IN BOCR
END DESCRIPTION:
DSS Export Rating Curves= 0
DSS Export Rating Curve Sorted= 0
DSS Export Volume Flow Curves= 0
DXF OffsetX= 0
DXF OffsetY= 0
DXF ScaleX= 1
DXF ScaleY= 10

--- UNT 138 IN BOCR.p01 (plan) ---

Plan Title=Multiple Run
Short Identifier=Multiple
Geom File=g01
Flow File=f01
Subcritical Flow
K Sum by GR= 0
Std Step Tol= 0.01
Critical Tol= 0.01
Num of Std Step Trials= 20
Max Error Tol= 0.3
Flow Tol Ratio= 0.001
Split Flow NTrial= 30
Split Flow Tol= 0.02
Split Flow Ratio= 0.02
Log Output Level= 0
Friction Slope Method= 1
Unsteady Friction Slope Method= 2
Unsteady Bridges Friction Slope Method= 1
Parabolic Critical Depth
Global Vel Dist=  1 , 1 , 1
Global Log Level= 0
CheckData=True
Encroach Param= -1, 0, 0, 0
BEGIN DESCRIPTION:
Multiple Run
END DESCRIPTION:

--- UNT 138 IN BOCR.f01 (steady flow) ---

Flow Title=Multiple
Program Version=4.10
Number of Profiles= 7
Profile Names=10-year,25-year,50-year,1pct_min,100-year,1pct_plu,500-year
River Rch & RM=UNT 138 IN BOCR,Reach-1         ,2164
     281     361     423     366     494     669     676
Boundary for River Rch & Prof#=UNT 138 IN BOCR,Reach-1         , 1
Up Type= 0
Dn Type= 3
Dn Slope=0.005
Boundary for River Rch & Prof#=UNT 138 IN BOCR,Reach-1         , 2
Up Type= 0
Dn Type= 3
Dn Slope=0.005
Boundary for River Rch & Prof#=UNT 138 IN BOCR,Reach-1         , 3
Up Type= 0
Dn Type= 3
Dn Slope=0.005
Boundary for River Rch & Prof#=UNT 138 IN BOCR,Reach-1         , 4
Up Type= 0
Dn Type= 3
Dn Slope=0.005
Boundary for River Rch & Prof#=UNT 138 IN BOCR,Reach-1         , 5
Up Type= 0
Dn Type= 3
Dn Slope=0.005
Boundary for River Rch & Prof#=UNT 138 IN BOCR,Reach-1         , 6
Up Type= 0
Dn Type= 3
Dn Slope=0.005
Boundary for River Rch & Prof#=UNT 138 IN BOCR,Reach-1         , 7
Up Type= 0
Dn Type= 3
Dn Slope=0.005
DSS Import GetInterval= 0
DSS Import GetPeak= 0
DSS Import FillOption= 0

--- UNT 138 IN BOCR.g01 (geometry) ---

Geom Title=Existing Conditions

River Reach=UNT 138 IN BOCR,Reach-1
Reach XY= 30
      3723634.50     10607450.00      3723541.25     10607474.00
      3723494.00     10607518.00      3723300.50     10607535.00
      3723210.25     10607566.00      3723143.25     10607479.00
      3723140.00     10607373.00      3723117.00     10607306.00
      3723067.25     10607264.00      3722987.25     10607305.00
      3722888.25     10607214.00      3722772.25     10607233.00
      3722678.50     10607145.00      3722640.00     10607153.00
      3722567.25     10607128.00      3722489.25     10607221.00
      3722451.50     10607236.00      3722357.50     10607128.00
      3722333.50     10607171.00      3722231.25     10607235.00
      3722207.25     10607232.00      3722198.25     10607183.00
      3722145.75     10607188.00      3722091.75     10607427.00
      3722059.25     10607455.00      3722022.75     10607440.00
      3721955.00     10607489.00      3721943.75     10607513.00
      3721954.00     10607553.00      3721910.50     10607581.00

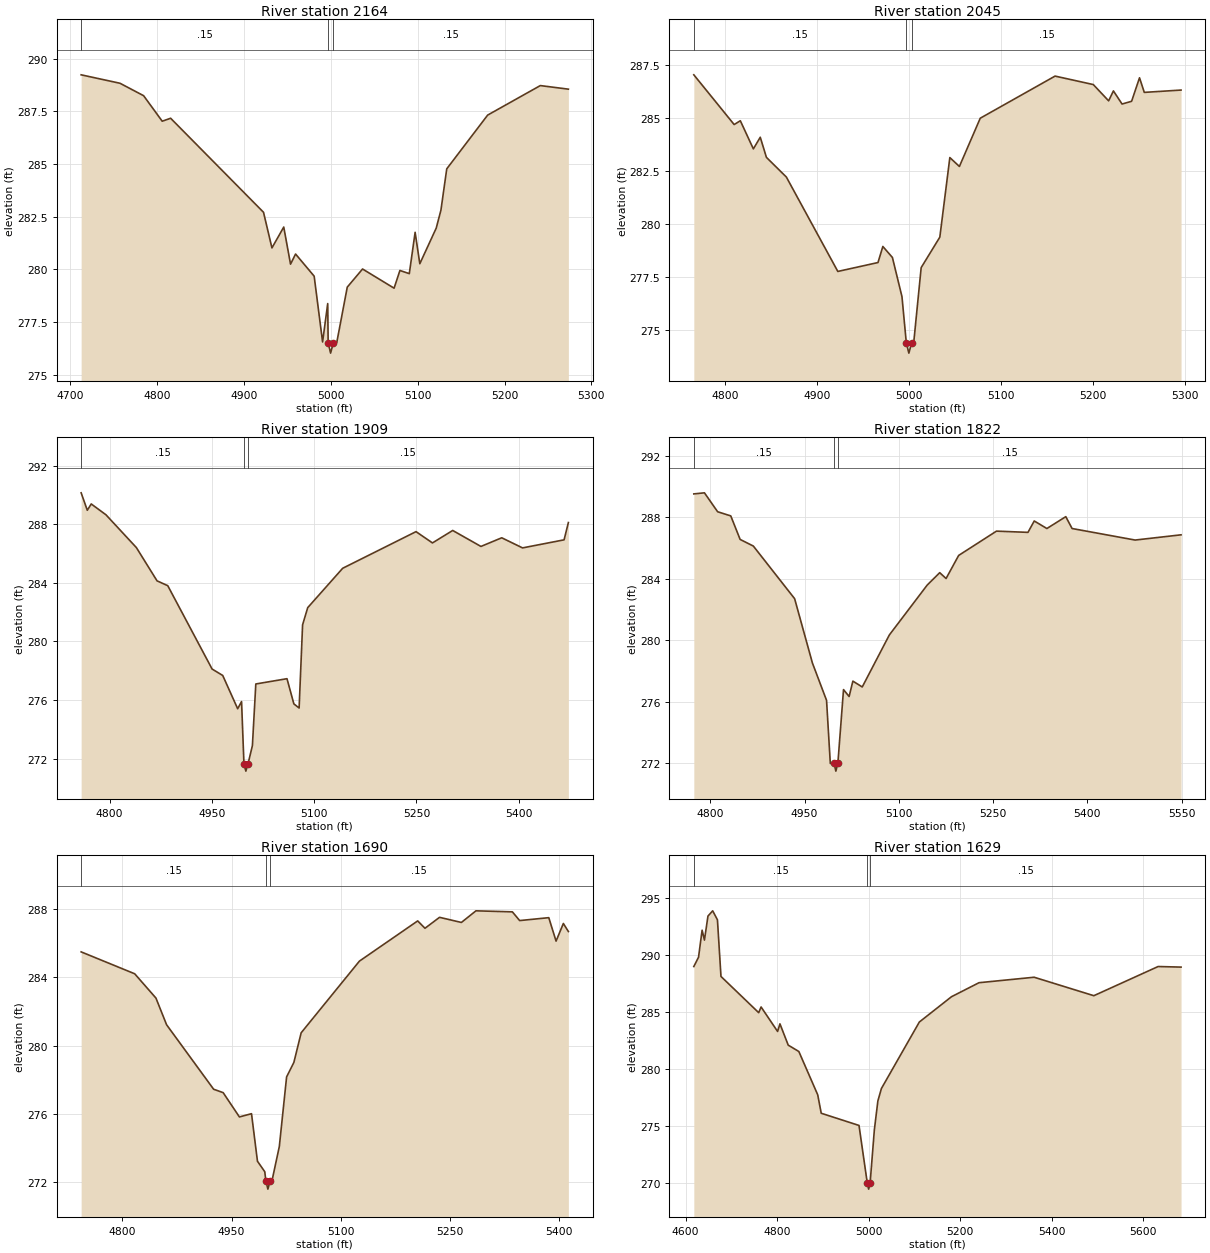
Type RM Length L Ch R = 1,2164,119,119,119
BEGIN DESCRIPTION:
UNT 138 IN BOCR 4.0
END DESCRIPTION:
XS GIS Cut Line= 3
      3723399.61     10607310.20      3723249.61     10607560.19
      3723349.61     10607810.19
#Sta/Elev= 30
  4712.7  289.23  4757.4  288.83  4784.6  288.24  4806.0  287.03  4815.7  287.17
  4922.6  282.71  4932.3  281.02  4945.9  282.01  4953.7  280.25  4959.5  280.73
  4980.9  279.68  4990.6  276.56  4996.5  278.38  4997.0  276.53  4999.8  276.03
  5003.0  276.53  5006.9  276.53  5019.0  279.16  5036.6  280.02  5072.9  279.11
  5079.6  279.95  5090.4  279.80  5097.1  281.76  5102.5  280.27  5121.4  281.96
  5126.8  282.81  5133.5  284.77  5180.6  287.32  5241.2  288.72  5273.5  288.55
#Mann=3,-1,0
  4712.7    0.15       0  4997.0    0.05       0  5003.0    0.15       0
Bank Sta=4997,5003
Exp/Cntr=0.3,0.1

Type RM Length L Ch R = 1,2045,136,136,136
BEGIN DESCRIPTION:
Mapping XS e0344df7
END DESCRIPTION:
XS GIS Cut Line= 3
      3723305.63     10607324.45      3723176.76     10607467.64
      3723082.99     10607791.91
#Sta/Elev= 30
  4765.8  287.05  4809.7  284.70  4816.4  284.88  4830.6  283.55  4838.1  284.10
  4844.8  283.15  4866.5  282.22  4922.5  277.76  4966.2  278.18  4971.5  278.94
  4981.9  278.42  4992.3  276.57  4997.0  274.40  4999.8  273.90  5003.0  274.40
  5005.1  274.40  5013.2  277.94  5033.5  279.38  5044.4  283.14  5054.8  282.72
  5077.5  285.00  5158.9  286.99  5200.5  286.59  5217.2  285.82  5222.4  286.29
  5231.8  285.67  5242.2  285.80  5250.8  286.91  5256.0  286.22  5296.0  286.33
#Mann=3,-1,0
  4765.8    0.15       0  4997.0    0.05       0  5003.0    0.15       0
Bank Sta=4997,5003
Exp/Cntr=0.3,0.1

Type RM Length L Ch R = 1,1909,87,87,87
BEGIN DESCRIPTION:
Mapping XS cc5a9a0c
END DESCRIPTION:
XS GIS Cut Line= 3
      3723349.97     10607259.29      3723125.98     10607386.91
      3723045.44     10607836.35
#Sta/Elev= 30
  4758.3  290.15  4767.3  288.96  4773.1  289.39  4794.7  288.65  4839.3  286.41
  4869.6  284.14  4885.3  283.81  4950.3  278.12  4965.9  277.68  4987.8  275.41
  4993.5  275.90  4997.0  271.65  4999.8  271.15  5003.0  271.65  5009.4  272.89
  5014.4  277.10  5060.1  277.46  5070.2  275.74  5077.9  275.46  5083.0  281.14
  5090.5  282.31  5141.8  285.00  5249.3  287.50  5273.4  286.73  5303.1  287.58
  5344.5  286.49  5375.0  287.08  5405.5  286.39  5466.4  286.94  5472.7  288.12
#Mann=3,-1,0
  4758.3    0.15       0  4997.0    0.05       0  5003.0    0.15       0
Bank Sta=4997,5003
Exp/Cntr=0.3,0.1

Type RM Length L Ch R = 1,1822,132,132,132
BEGIN DESCRIPTION:
Mapping XS 114caa25
END DESCRIPTION:
XS GIS Cut Line= 3
      3723295.24     10607173.38      3723059.57     10607334.83
      3723023.11     10607823.10
#Sta/Elev= 30
  4773.8  289.51  4790.7  289.58  4811.7  288.35  4832.6  288.08  4847.5  286.55
  4868.5  286.12  4934.2  282.70  4962.5  278.52  4985.0  276.09  4991.0  271.99
  4997.0  271.99  4999.8  271.49  5003.0  271.99  5012.0  276.79  5020.9  276.34
  5026.9  277.34  5041.8  276.96  5084.9  280.34  5145.1  283.58  5165.1  284.39
  5175.2  284.01  5195.2  285.51  5255.4  287.09  5305.5  287.01  5315.5  287.75
  5335.6  287.26  5365.7  288.03  5375.7  287.26  5476.0  286.51  5549.1  286.85
#Mann=3,-1,0
  4773.8    0.15       0  4997.0    0.05       0  5003.0    0.15       0
Bank Sta=4997,5003
Exp/Cntr=0.3,0.1

Type RM Length L Ch R = 1,1690,61,61,61
BEGIN DESCRIPTION:
Mapping XS e06b5ced
END DESCRIPTION:
XS GIS Cut Line= 3
      3723146.80     10607093.95      3723008.79     10607278.84
      3723003.60     10607717.09
#Sta/Elev= 30
  4743.4  285.48  4816.9  284.20  4846.1  282.78  4860.7  281.22  4925.3  277.45
  4938.4  277.25  4960.7  275.83  4977.3  276.02  4985.5  273.24  4995.5  272.63
  4997.0  272.11  4999.8  271.61  5003.0  272.11  5005.5  272.11  5015.5  274.10
  5025.5  278.17  5035.5  279.02  5045.5  280.75  5125.5  284.94  5205.5  287.29
  5215.5  286.86  5235.5  287.50  5265.5  287.20  5285.5  287.88  5335.5  287.82
  5345.5  287.31  5385.5  287.48  5395.5  286.11  5405.5  287.14  5412.4  286.67
#Mann=3,-1,0
  4743.4    0.15       0  4997.0    0.05       0  5003.0    0.15       0
Bank Sta=4997,5003
Exp/Cntr=0.3,0.1

Type RM Length L Ch R = 1,1629,493,493,493
BEGIN DESCRIPTION:
UNT 138 IN BOCR 3.0
END DESCRIPTION:
XS GIS Cut Line= 3
      3723049.61     10606910.18      3722949.61     10607310.19
      3722999.61     10607960.15
#Sta/Elev= 30
  4618.0  288.97  4628.3  289.79  4636.1  292.16  4641.2  291.29  4648.9  293.40
  4659.2  293.86  4669.6  293.07  4677.3  288.10  4759.7  284.92  4764.9  285.42
  4801.0  283.27  4806.1  283.94  4824.2  282.07  4847.4  281.51  4888.6  277.71
  4896.3  276.09  4978.8  275.02  4997.0  269.93  4999.8  269.43  5003.0  269.93
  5012.3  274.63  5020.0  277.17  5027.7  278.26  5110.6  284.10  5180.8  286.32
  5240.9  287.55  5361.3  288.03  5491.7  286.41  5632.1  288.97  5682.2  288.92
#Mann=3,-1,0
  4618.0    0.15       0  4997.0    0.05       0  5003.0    0.15       0
Bank Sta=4997,5003
Exp/Cntr=0.3,0.1

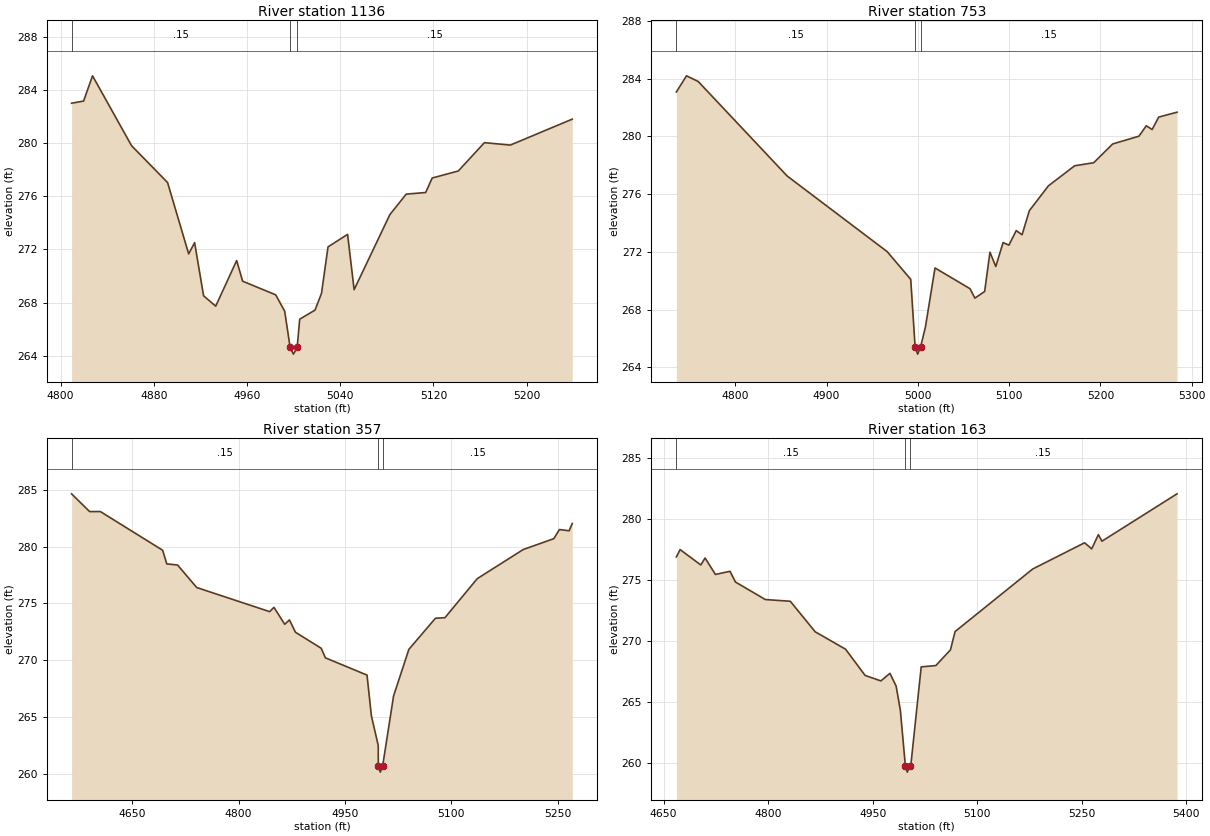
Type RM Length L Ch R = 1,1136,383,383,383
BEGIN DESCRIPTION:
UNT 138 IN BOCR 2.0
END DESCRIPTION:
XS GIS Cut Line= 3
      3722499.62     10606960.23      3722549.61     10607160.19
      3722649.60     10607360.17
#Sta/Elev= 30
  4809.4  283.00  4819.7  283.16  4827.4  285.06  4860.9  279.80  4891.8  277.03
  4909.9  271.66  4915.0  272.51  4922.7  268.51  4933.1  267.73  4951.1  271.16
  4956.2  269.61  4984.6  268.58  4992.3  267.35  4997.0  264.62  4999.8  264.12
  5003.0  264.62  5005.2  266.75  5018.3  267.43  5023.9  268.69  5029.5  272.19
  5046.3  273.13  5051.9  268.97  5082.6  274.62  5096.6  276.16  5113.3  276.28
  5118.9  277.37  5141.3  277.90  5163.7  280.03  5186.0  279.85  5239.1  281.80
#Mann=3,-1,0
  4809.4    0.15       0  4997.0    0.05       0  5003.0    0.15       0
Bank Sta=4997,5003
Exp/Cntr=0.3,0.1

Type RM Length L Ch R = 1,753,396,396,396
BEGIN DESCRIPTION:
Mapping XS ed041368
END DESCRIPTION:
XS GIS Cut Line= 3
      3722208.38     10606939.61      3722307.35     10607257.34
      3722442.17     10607425.86
#Sta/Elev= 30
  4735.4  283.08  4746.5  284.20  4759.3  283.81  4856.8  277.26  4966.4  272.02
  4992.2  270.10  4997.0  265.42  4999.8  264.92  5003.0  265.42  5008.3  266.80
  5018.8  270.89  5057.2  269.45  5062.5  268.80  5073.2  269.26  5079.0  271.98
  5085.4  270.99  5093.4  272.65  5099.8  272.47  5107.8  273.48  5114.2  273.19
  5122.2  274.86  5143.1  276.58  5171.9  277.97  5192.7  278.18  5213.5  279.48
  5242.3  280.02  5250.3  280.74  5256.7  280.48  5263.9  281.34  5284.0  281.68
#Mann=3,-1,0
  4735.4    0.15       0  4997.0    0.05       0  5003.0    0.15       0
Bank Sta=4997,5003
Exp/Cntr=0.3,0.1

Type RM Length L Ch R = 1,357,194,194,194
BEGIN DESCRIPTION:
Mapping XS f3862e29
END DESCRIPTION:
XS GIS Cut Line= 3
      3721851.61     10607012.54      3722067.77     10607345.88
      3722335.29     10607499.13
#Sta/Elev= 30
  4564.7  284.64  4590.1  283.08  4605.3  283.08  4693.0  279.68  4698.9  278.48
  4714.1  278.38  4741.1  276.40  4843.9  274.28  4849.9  274.66  4865.1  273.17
  4871.8  273.55  4880.2  272.47  4916.5  271.06  4922.4  270.22  4981.1  268.70
  4987.2  265.13  4996.9  262.51  4997.0  260.67  4999.8  260.17  5003.0  260.67
  5018.5  266.87  5040.1  270.97  5077.5  273.70  5090.9  273.75  5136.4  277.18
  5201.2  279.74  5244.4  280.70  5252.2  281.50  5265.9  281.39  5270.3  282.03
#Mann=3,-1,0
  4564.7    0.15       0  4997.0    0.05       0  5003.0    0.15       0
Bank Sta=4997,5003
Exp/Cntr=0.3,0.1

Type RM Length L Ch R = 1,163,0,0,0
BEGIN DESCRIPTION:
UNT 138 IN BOCR 1.0
END DESCRIPTION:
XS GIS Cut Line= 4
      3721791.73     10607210.47      3721955.79     10607447.45
      3722052.14     10607512.55      3722359.41     10607577.65
#Sta/Elev= 30
  4668.3  276.89  4673.7  277.49  4703.4  276.23  4709.5  276.80  4724.4  275.45
  4745.3  275.71  4753.1  274.83  4796.0  273.39  4831.8  273.25  4867.6  270.74
  4911.2  269.31  4939.2  267.16  4961.8  266.71  4974.8  267.33  4983.7  266.29
  4989.8  264.30  4997.0  259.72  4999.8  259.22  5003.0  259.72  5004.7  259.72
  5019.7  267.86  5040.7  267.97  5061.7  269.26  5068.3  270.76  5179.8  275.90
  5254.2  278.05  5264.4  277.55  5274.0  278.72  5279.1  278.18  5386.9  282.07
#Mann=3,-1,0
  4668.3    0.15       0  4997.0    0.05       0  5003.0    0.15       0
Bank Sta=4997,5003
Exp/Cntr=0.3,0.1

Chan Stop Cuts=-1