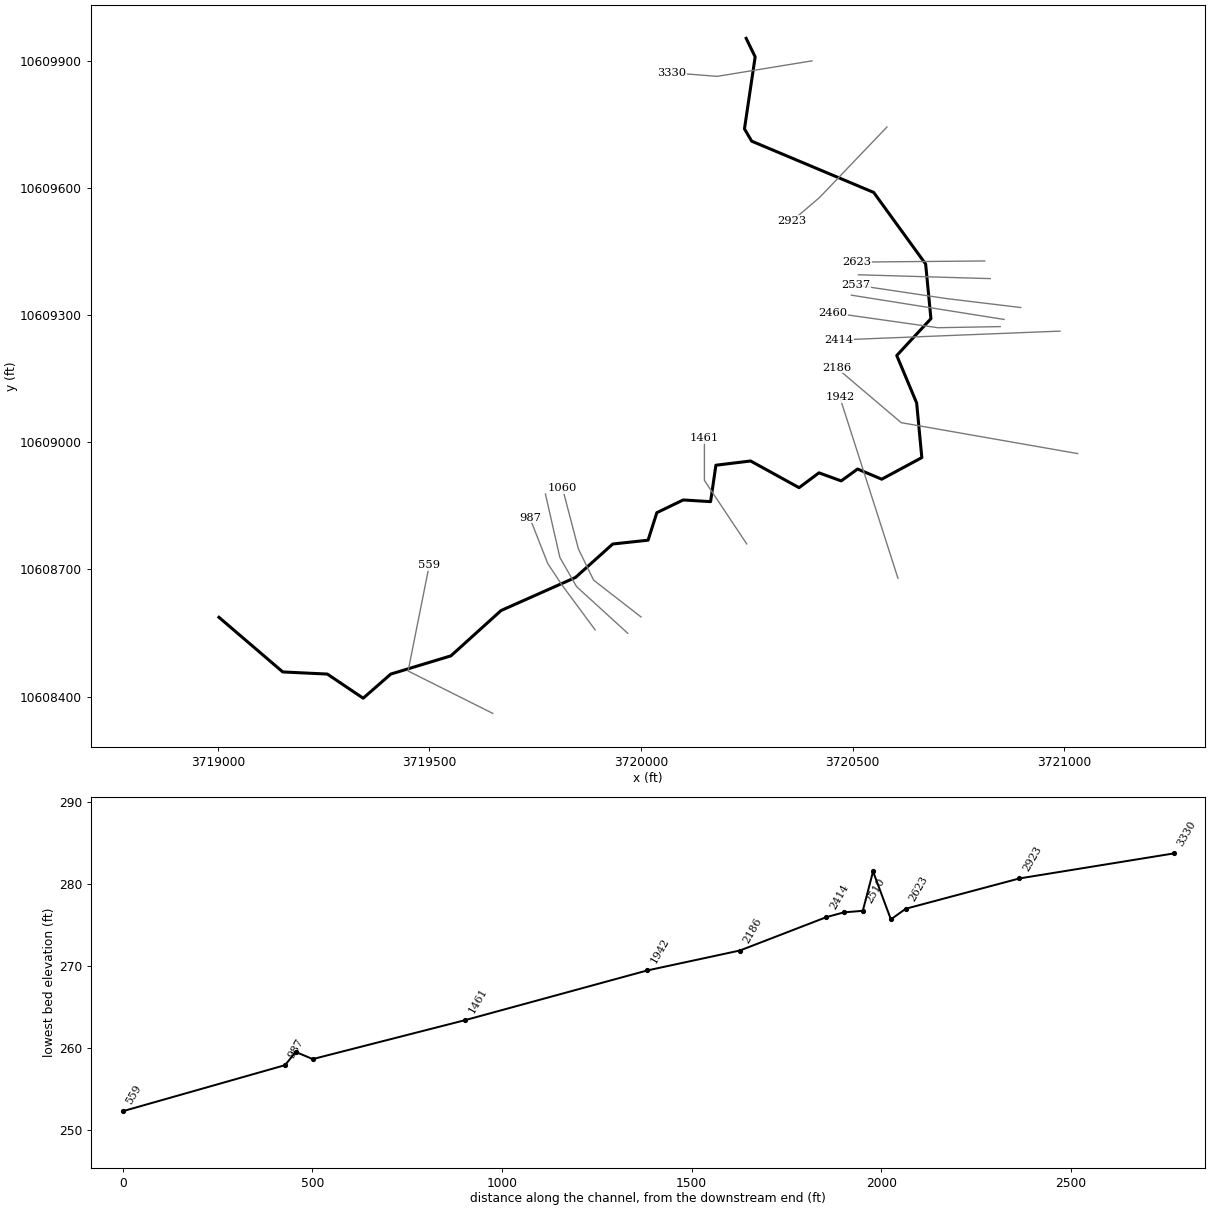
--- UNT 139 IN BOCR.prj (project) ---

Proj Title=UNT 139 IN BOCR Base Level Engineering
Current Plan=p01
Default Exp/Contr=0.3,0.1
English Units
Geom File=g01
Flow File=f01
Plan File=p01
Y Axis Title=Elevation
X Axis Title(PF)=Main Channel Distance
X Axis Title(XS)=Station
BEGIN DESCRIPTION:
UNT 139 IN BOCR
END DESCRIPTION:
DSS Export Rating Curves= 0
DSS Export Rating Curve Sorted= 0
DSS Export Volume Flow Curves= 0
DXF OffsetX= 0
DXF OffsetY= 0
DXF ScaleX= 1
DXF ScaleY= 10

--- UNT 139 IN BOCR.p01 (plan) ---

Plan Title=Multiple Run
Short Identifier=Multiple
Geom File=g01
Flow File=f01
Subcritical Flow
K Sum by GR= 0
Std Step Tol= 0.01
Critical Tol= 0.01
Num of Std Step Trials= 20
Max Error Tol= 0.3
Flow Tol Ratio= 0.001
Split Flow NTrial= 30
Split Flow Tol= 0.02
Split Flow Ratio= 0.02
Log Output Level= 0
Friction Slope Method= 1
Unsteady Friction Slope Method= 2
Unsteady Bridges Friction Slope Method= 1
Parabolic Critical Depth
Global Vel Dist=  1 , 1 , 1
Global Log Level= 0
CheckData=True
Encroach Param= -1, 0, 0, 0
BEGIN DESCRIPTION:
Multiple Run
END DESCRIPTION:

--- UNT 139 IN BOCR.f01 (steady flow) ---

Flow Title=Multiple
Number of Profiles=7
Profile Names=10-year,25-year,50-year,1pct_min,100-year,1pct_plu,500-year
River Rch & RM= UNT 139 IN BOCR,Reach-1,3330
     199     248     285     241     326     441     428
Boundary for River Rch & Prof#=UNT 139 IN BOCR,Reach-1,1
Up Type=0
Dn Type=3
Dn Slope=0.005
Boundary for River Rch & Prof#=UNT 139 IN BOCR,Reach-1,2
Up Type=0
Dn Type=3
Dn Slope=0.005
Boundary for River Rch & Prof#=UNT 139 IN BOCR,Reach-1,3
Up Type=0
Dn Type=3
Dn Slope=0.005
Boundary for River Rch & Prof#=UNT 139 IN BOCR,Reach-1,4
Up Type=0
Dn Type=3
Dn Slope=0.005
Boundary for River Rch & Prof#=UNT 139 IN BOCR,Reach-1,5
Up Type=0
Dn Type=3
Dn Slope=0.005
Boundary for River Rch & Prof#=UNT 139 IN BOCR,Reach-1,6
Up Type=0
Dn Type=3
Dn Slope=0.005
Boundary for River Rch & Prof#=UNT 139 IN BOCR,Reach-1,7
Up Type=0
Dn Type=3
Dn Slope=0.005

--- UNT 139 IN BOCR.g01 (geometry) ---

Geom Title=Existing Conditions
Program Version=4.10

River Reach=UNT 139 IN BOCR ,Reach-1
Reach XY= 30
      3720248.26     10609953.72       3720269.5       10609910.
      3720244.25       10609740.      3720261.25       10609711.
       3720549.5       10609590.      3720672.25       10609421.
      3720684.75       10609292.        3720604.       10609205.
        3720651.       10609093.      3720663.25       10608964.
       3720568.5       10608913.       3720511.5       10608937.
      3720472.75       10608909.      3720420.25       10608928.
      3720373.25       10608893.      3720258.75       10608956.
      3720176.75       10608946.      3720164.25       10608860.
       3720099.5       10608864.      3720037.25       10608834.
       3720016.5       10608769.        3719933.       10608760.
        3719845.       10608681.      3719669.25       10608603.
      3719550.75       10608496.      3719408.75       10608453.
       3719343.5       10608396.      3719258.75       10608453.
       3719153.5       10608458.      3719002.75       10608587.

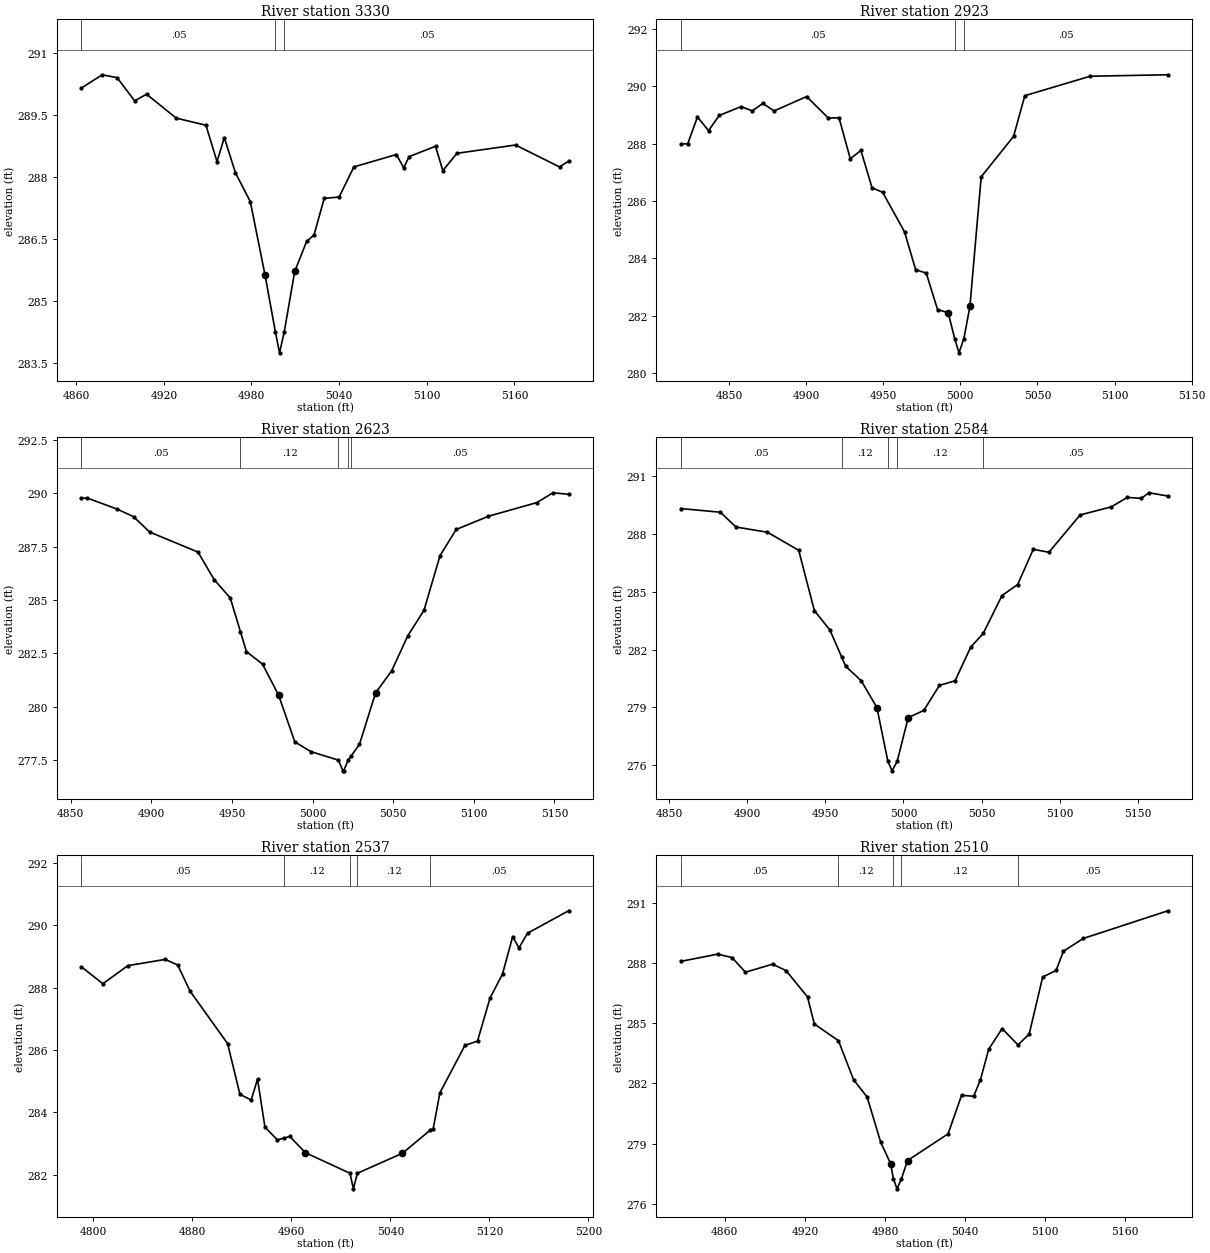
Type RM Length L Ch R = 1 ,3330    ,407,407,407
BEGIN DESCRIPTION:
UNT 139 IN BOCR 7.0
END DESCRIPTION:
XS GIS Cut Line= 3
      3720403.66     10609900.56      3720179.69     10609863.95
      3720073.46     10609872.34
#Sta/Elev= 30
  4863.6  290.16  4877.8  290.48    4888  290.41    4900  289.85  4908.2  290.01
  4928.5  289.43  4948.8  289.26  4956.4  288.38  4961.4  288.96    4969  288.11
  4979.2  287.41  4989.3  285.63  4996.4  284.25  4999.2  283.75  5002.4  284.25
  5009.6  285.72  5017.8  286.45  5022.8   286.6  5029.8  287.49    5040  287.52
  5050.1  288.25  5079.2  288.55  5084.2  288.23    5088   288.5    5106  288.75
    5111  288.16  5120.7  288.58  5160.8  288.78  5190.9  288.25  5197.1  288.39
#Mann= 3 ,-1 , 0
  4863.6     .05       0  4996.4     .03       0  5002.4     .05       0
Bank Sta=4989.3,5009.6
XS Rating Curve= 0 ,0
Exp/Cntr=0.3,0.1

Type RM Length L Ch R = 1 ,2923    ,300,300,300
BEGIN DESCRIPTION:
UNT 139 IN BOCR 6.0
END DESCRIPTION:
XS GIS Cut Line= 3
      3720580.79     10609744.32      3720421.62     10609578.03
       3720356.4     10609522.42
#Sta/Elev= 30
  4818.7  287.99  4823.2  287.99  4829.5  288.93  4836.7  288.45  4843.6  288.98
  4857.8  289.29    4865  289.14  4871.9   289.4  4879.2  289.14  4900.3  289.64
  4914.4  288.89  4921.3   288.9  4928.6  287.47  4935.5  287.76  4942.7  286.46
  4949.6   286.3  4963.8  284.92    4971   283.6  4977.9  283.48  4985.2  282.21
  4992.1   282.1  4996.3   281.2  4999.1   280.7  5002.3   281.2  5006.2  282.32
  5013.5  286.84  5034.5  288.25  5041.8  289.67  5084.2  290.35  5134.6   290.4
#Mann= 3 ,-1 , 0
  4818.7     .05       0  4996.3     .03       0  5002.3     .05       0
Bank Sta=4992.1,5006.2
XS Rating Curve= 0 ,0
Exp/Cntr=0.3,0.1

Type RM Length L Ch R = 1 ,2623    ,39,39,39
BEGIN DESCRIPTION:
Mapping XS 460611ba
END DESCRIPTION:
XS GIS Cut Line= 2
      3720811.95     10609428.15      3720509.86     10609425.55
#Sta/Elev= 30
  4856.7  289.78  4860.4  289.78    4879  289.26    4889  288.91    4899  288.19
    4929  287.25    4939  285.96    4949   285.1  4955.3  283.52    4959  282.59
    4969     282    4979  280.54    4989  278.36    4999   277.9  5016.1   277.5
  5018.8     277  5019.3     277  5022.1   277.5  5023.9  277.69  5029.1  278.24
  5039.1  280.65  5049.1  281.69  5059.1  283.33  5069.1  284.52  5079.1  287.09
  5089.1  288.31  5109.1  288.93  5139.1  289.57  5149.1  290.03  5158.8  289.96
#Mann= 5 ,-1 , 0
  4856.7     .05       0  4955.3     .12       0  5016.1     .07       0
  5022.1     .12       0  5023.9     .05       0
Bank Sta=4979,5039.1
XS Rating Curve= 0 ,0
Exp/Cntr=0.3,0.1

Type RM Length L Ch R = 1 ,2584    ,47,47,47
BEGIN DESCRIPTION:
Mapping XS b119f9c7
END DESCRIPTION:
XS GIS Cut Line= 2
      3720824.94     10609386.49      3720513.57     10609395.57
#Sta/Elev= 30
  4857.6  289.33  4882.9  289.14  4892.9  288.37    4913   288.1    4933  287.16
    4943  284.03    4953  283.01  4960.5  281.61    4963  281.14    4973  280.38
    4983  278.99    4990   276.2  4992.7   275.7    4996   276.2    5003  278.46
    5013  278.84    5023  280.14    5033  280.38    5043  282.13    5051  282.84
    5063  284.81    5073  285.38    5083  287.21    5093  287.06    5113     289
    5133  289.42  5143.1  289.91    5152  289.86    5157  290.15  5169.1  289.98
#Mann= 5 ,-1 , 0
  4857.6     .05       0  4960.5     .12       0    4990     .07       0
    4996     .12       0    5051     .05       0
Bank Sta=4983,5003
XS Rating Curve= 0 ,0
Exp/Cntr=0.3,0.1

Type RM Length L Ch R = 1 ,2537    ,27,27,27
BEGIN DESCRIPTION:
Mapping XS b89adb08
END DESCRIPTION:
XS GIS Cut Line= 3
      3720896.83     10609318.27      3720719.75     10609339.62
      3720506.77     10609371.39
#Sta/Elev= 30
  4790.3  288.67  4807.6  288.13  4827.8  288.71    4858  288.91  4868.1  288.73
  4878.1  287.89  4908.4  286.21  4918.4  284.58  4927.5   284.4  4932.6  285.07
  4938.6  283.53  4948.7  283.12  4954.3  283.18  4958.7  283.23  4971.3  282.71
  5007.3  282.05  5010.1  281.55  5013.3  282.05  5049.7  282.69  5072.1  283.43
  5074.6  283.48    5080  284.63  5100.2  286.15  5110.4  286.29  5120.5  287.67
  5130.6  288.44  5138.8  289.64  5143.9  289.28  5150.8  289.75    5184  290.47
#Mann= 5 ,-1 , 0
  4790.3     .05       0  4954.3     .12       0  5007.3     .07       0
  5013.3     .12       0  5072.1     .05       0
Bank Sta=4971.3,5049.7
XS Rating Curve= 0 ,0
Exp/Cntr=0.3,0.1

Type RM Length L Ch R = 1 ,2510    ,50,50,50
BEGIN DESCRIPTION:
Mapping XS cb456af2
END DESCRIPTION:
XS GIS Cut Line= 2
      3720857.54     10609290.13      3720496.87     10609347.42
#Sta/Elev= 30
    4827  288.08  4854.7  288.44  4865.4  288.27  4875.5  287.54  4895.8  287.94
  4905.9  287.62    4922  286.31  4927.1  284.96  4945.2  284.13  4956.5  282.19
  4966.7  281.32  4976.8  279.09  4984.3     278  4986.4  277.25  4989.1  276.75
  4992.4  277.25    4997  278.16  5027.4  279.49  5037.5  281.41  5046.5  281.36
  5051.6  282.17  5057.8   283.7  5067.9  284.73  5079.8  283.92  5088.2  284.46
  5098.3   287.3  5108.4  287.63  5113.8  288.58  5128.7  289.22  5192.2   290.6
#Mann= 5 ,-1 , 0
    4827     .05       0  4945.2     .12       0  4986.4     .07       0
  4992.4     .12       0  5079.8     .05       0
Bank Sta=4984.3,4997
XS Rating Curve= 0 ,0
Exp/Cntr=0.3,0.1

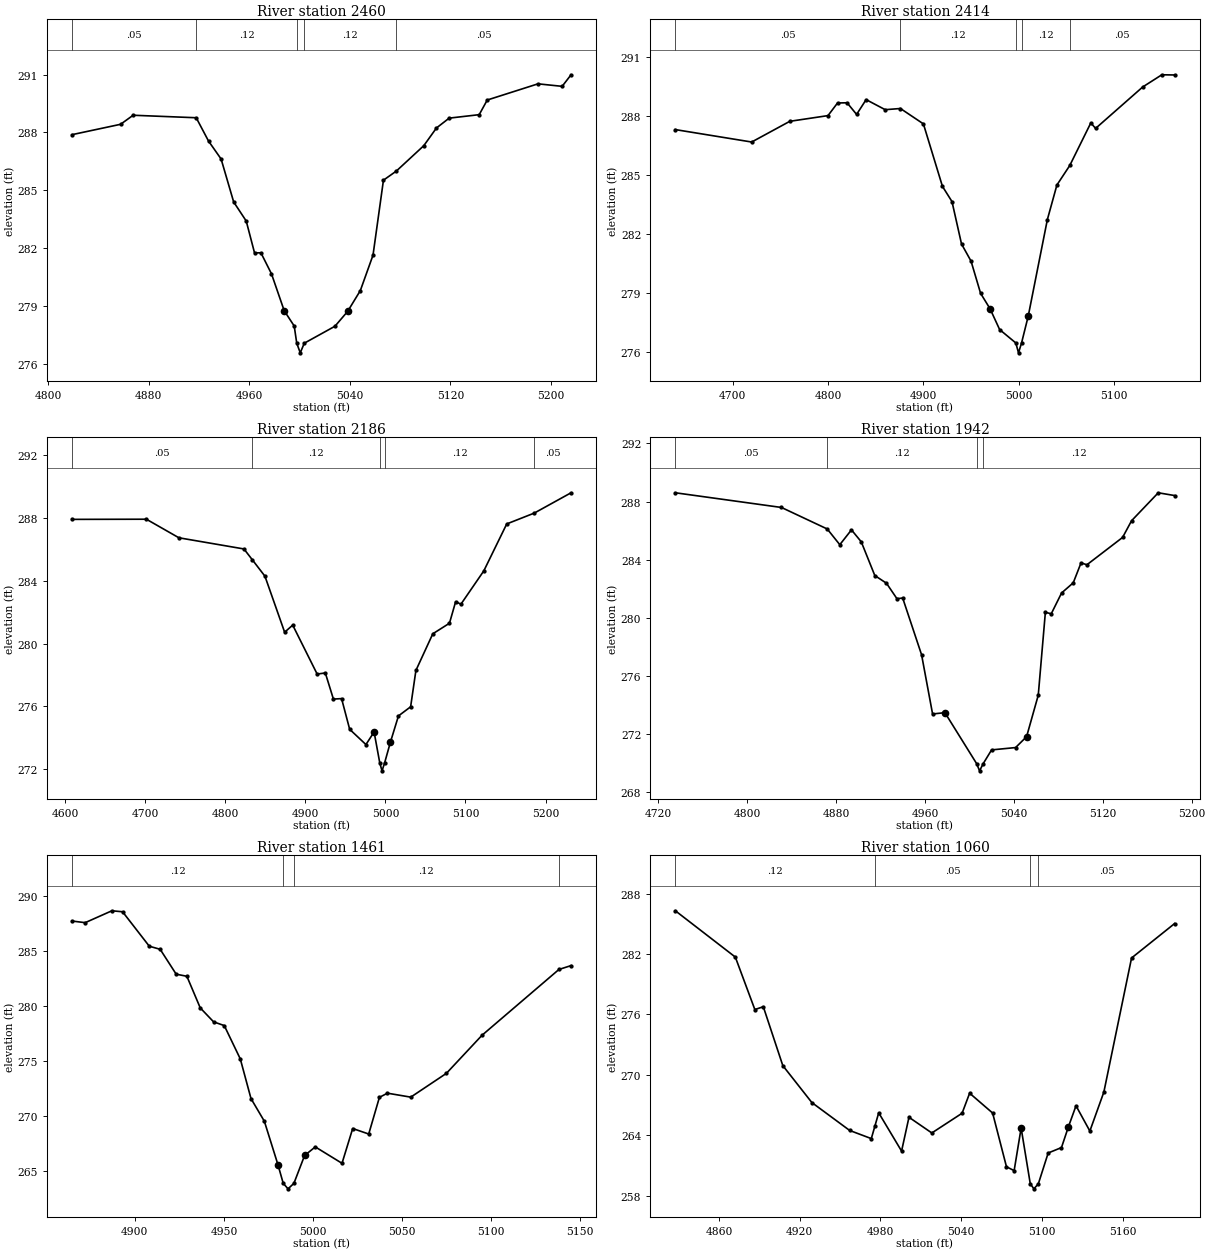
Type RM Length L Ch R = 1 ,2460    ,46,46,46
BEGIN DESCRIPTION:
Mapping XS 3c0c59e6
END DESCRIPTION:
XS GIS Cut Line= 3
      3720848.36     10609273.21      3720701.28      10609270.6
      3720453.55     10609305.62
#Sta/Elev= 30
  4818.7  287.88  4857.5  288.42  4867.5  288.89  4917.7  288.76  4927.5  287.55
  4937.5  286.62  4947.5  284.39  4957.5   283.4  4964.1  281.75  4969.2  281.75
  4977.6  280.66  4987.7  278.75  4995.7  277.95  4997.7  277.06  5000.5  276.56
  5003.7  277.06  5028.1  277.94  5038.2  278.71  5048.3  279.79  5058.4  281.63
  5066.7  285.52  5076.9  285.99  5098.8  287.31  5108.9  288.23    5119  288.74
  5142.9  288.92  5149.3  289.68  5189.7  290.52  5208.9  290.39    5216  290.99
#Mann= 5 ,-1 , 0
  4818.7     .05       0  4917.7     .12       0  4997.7     .07       0
  5003.7     .12       0  5076.9     .05       0
Bank Sta=4987.7,5038.2
XS Rating Curve= 0 ,0
Exp/Cntr=0.3,0.1

Type RM Length L Ch R = 1 ,2414    ,228,228,228
BEGIN DESCRIPTION:
UNT 139 IN BOCR 5.0
END DESCRIPTION:
XS GIS Cut Line= 2
      3720989.66     10609262.55      3720466.17     10609241.72
#Sta/Elev= 30
  4639.9   287.3    4720  286.67    4760  287.72  4800.1  288.01  4810.1  288.65
  4820.1  288.66  4830.1  288.07  4840.1  288.82  4860.1  288.31  4876.1  288.37
  4900.2  287.59  4920.2  284.42  4930.2  283.65  4940.2   281.5  4950.2  280.63
  4960.2     279  4970.2  278.21  4980.2  277.16  4997.2  276.48    5000  275.98
  5003.2  276.48  5010.2  277.84  5030.3  282.74  5040.3  284.49  5053.8  285.48
  5075.9  287.64  5080.9  287.36  5130.3  289.46  5150.4  290.08  5163.8  290.07
#Mann= 5 ,-1 , 0
  4639.9     .05       0  4876.1     .12       0  4997.2     .07       0
  5003.2     .12       0  5053.8     .05       0
Bank Sta=4970.2,5010.2
XS Rating Curve= 0 ,0
Exp/Cntr=0.3,0.1

Type RM Length L Ch R = 1 ,2186    ,244,244,244
BEGIN DESCRIPTION:
Mapping XS 2a905730
END DESCRIPTION:
XS GIS Cut Line= 3
      3721031.33     10608973.49      3720614.64     10609046.41
      3720461.85     10609175.89
#Sta/Elev= 30
  4608.5  287.89  4701.6   287.9  4742.2  286.72  4823.4  286.01  4833.9  285.32
  4849.6  284.28  4874.2  280.72  4884.3  281.17  4914.8  278.06    4925  278.13
  4935.1  276.47  4945.3   276.5  4955.4  274.55  4975.7  273.58  4985.9  274.38
    4993  272.41  4995.8  271.91    4999  272.41  5006.2  273.72  5016.3   275.4
  5031.5  275.98  5038.1  278.29  5059.2  280.62    5080  281.29  5087.7  282.66
  5094.3   282.5  5122.9  284.62  5151.5   287.6  5185.9  288.29  5231.8  289.58
#Mann= 5 ,-1 , 0
  4608.5     .05       0  4833.9     .12       0    4993     .07       0
    4999     .12       0  5185.9     .05       0
Bank Sta=4985.9,5006.2
XS Rating Curve= 0 ,0
Exp/Cntr=0.3,0.1

Type RM Length L Ch R = 1 ,1942    ,481,481,481
BEGIN DESCRIPTION:
UNT 139 IN BOCR 4.0
END DESCRIPTION:
XS GIS Cut Line= 2
      3720606.82     10608679.25      3720469.41     10609107.02
#Sta/Elev= 30
  4735.3   288.6  4830.8  287.59    4872  286.11  4883.3  285.03  4893.8  286.05
  4902.6  285.23  4914.8  282.91  4925.3  282.38  4934.7  281.32  4939.9  281.36
  4956.9  277.46  4966.8  273.39  4977.9  273.48  5006.4  269.98  5009.1  269.48
  5012.4  269.98  5019.9  270.92  5041.5  271.08  5051.4  271.83  5061.9  274.68
  5068.3  280.38  5073.6  280.28  5082.9  281.71  5093.4  282.41  5100.4  283.78
  5105.7  283.65  5137.8  285.53  5145.9  286.68  5169.9   288.6  5184.6  288.41
#Mann= 4 ,-1 , 0
  4735.3     .05       0    4872     .12       0  5006.4     .07       0
  5012.4     .12       0
Bank Sta=4977.9,5051.4
XS Rating Curve= 0 ,0
Exp/Cntr=0.3,0.1

Type RM Length L Ch R = 1 ,1461    ,401,401,401
BEGIN DESCRIPTION:
UNT 139 IN BOCR 3.0
END DESCRIPTION:
XS GIS Cut Line= 3
       3720249.6     10608760.21      3720149.61     10608910.19
      3720149.61     10609010.24
#Sta/Elev= 30
  4864.6  287.74  4872.1  287.59  4887.1  288.67  4893.1  288.58  4908.1  285.45
  4914.2  285.17  4923.2  282.91  4929.2  282.72  4936.7  279.85  4944.2  278.58
  4950.2  278.24  4959.2  275.21  4965.2  271.61  4972.7  269.55  4980.3  265.62
  4983.3  263.91    4986  263.41  4989.3  263.91  4995.3  266.44  5001.3  267.22
  5016.3  265.73  5022.3  268.89  5031.3  268.39  5037.3  271.72  5041.8   272.1
  5054.9  271.74  5074.9   273.9  5094.9  277.36  5138.1  283.34  5144.9  283.69
#Mann= 4 ,-1 , 0
  4864.6     .12       0  4983.3     .07       0  4989.3     .12       0
  5138.1     .05       0
Bank Sta=4980.3,4995.3
XS Rating Curve= 0 ,0
Exp/Cntr=0.3,0.1

Type RM Length L Ch R = 1 ,1060    ,45,45,45
BEGIN DESCRIPTION:
Mapping XS 6aee1598
END DESCRIPTION:
XS GIS Cut Line= 4
      3719999.81     10608587.86      3719887.82     10608674.76
      3719851.97     10608748.24      3719814.48     10608891.09
#Sta/Elev= 30
  4827.5  286.29  4872.1  281.69  4886.6  276.48  4892.9  276.76  4907.4  270.91
    4929  267.24  4957.1  264.47  4973.2  263.66  4975.8  264.87  4978.7  266.22
  4995.7  262.42  5001.2  265.78  5018.2  264.22  5040.7  266.18  5046.3  268.17
  5063.4   266.2  5073.7  260.86  5079.4  260.48  5084.6  264.71  5091.4  259.17
  5094.1  258.67  5097.4  259.17  5104.7  262.23  5114.6  262.77  5119.8  264.85
  5125.4  266.92  5135.7  264.41  5146.1  268.28  5166.7   281.6  5198.7  285.02
#Mann= 4 ,-1 , 0
  4827.5     .12       0  4975.8     .05       0  5091.4     .03       0
  5097.4     .05       0
Bank Sta=5084.6,5119.8
XS Rating Curve= 0 ,0
Exp/Cntr=0.3,0.1

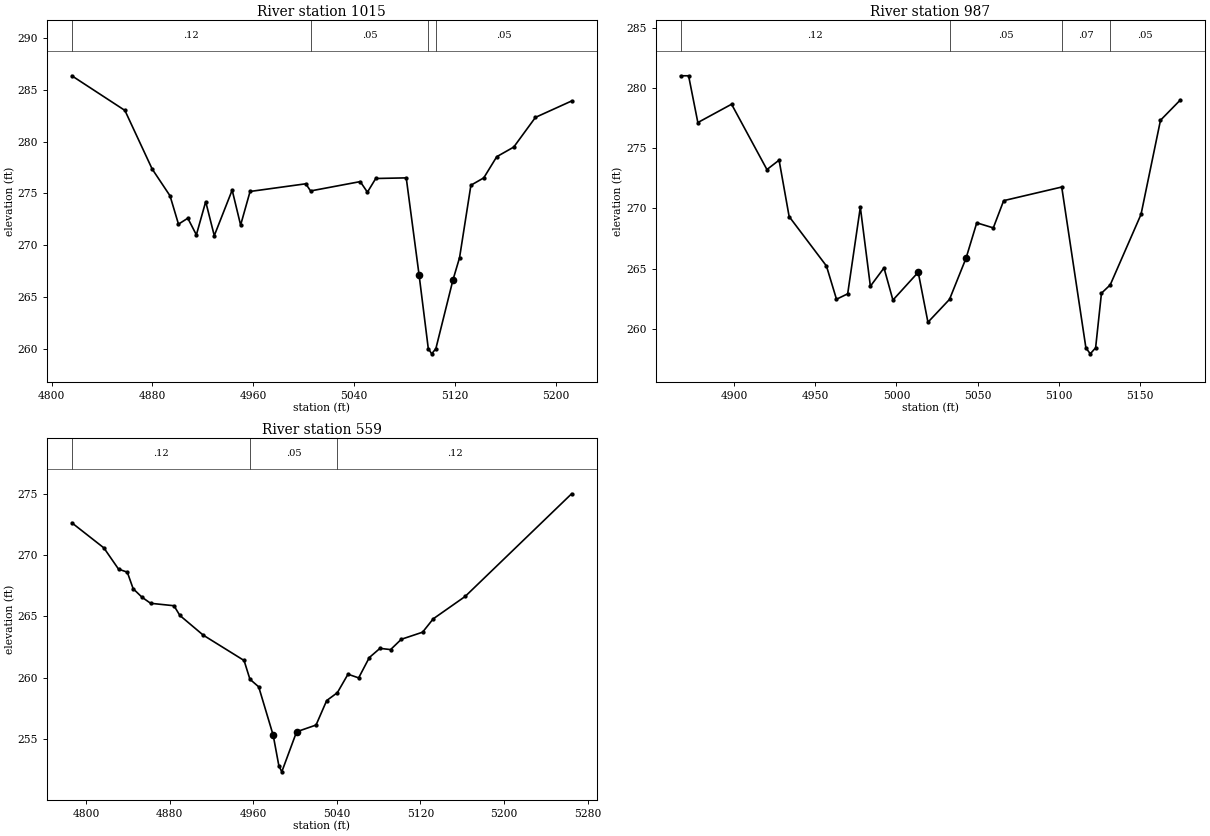
Type RM Length L Ch R = 1 ,1015    ,28,28,28
BEGIN DESCRIPTION:
Mapping XS 782ef062
END DESCRIPTION:
XS GIS Cut Line= 4
      3719968.43     10608549.35      3719847.49     10608659.53
      3719808.07     10608728.53      3719774.02     10608878.14
#Sta/Elev= 30
  4816.1  286.34  4858.2     283  4879.8  277.36    4894  274.77  4900.7  272.04
  4908.1  272.61  4914.9  271.01  4922.3  274.21  4929.1  270.93  4943.3  275.32
    4950  271.95  4957.5  275.19  5001.7  275.93  5005.5  275.24  5044.9  276.14
  5050.6  275.12  5057.2  276.44  5081.4   276.5  5091.6  267.13  5098.9  260.04
  5101.6  259.54  5104.9  260.04  5118.5  266.68  5123.7  268.81  5132.7  275.79
  5142.9   276.5  5153.2  278.54  5166.7  279.47  5183.9  282.33  5212.6  283.91
#Mann= 4 ,-1 , 0
  4816.1     .12       0  5005.5     .05       0  5098.9     .07       0
  5104.9     .05       0
Bank Sta=5091.6,5118.5
XS Rating Curve= 0 ,0
Exp/Cntr=0.3,0.1

Type RM Length L Ch R = 1 ,987     ,428,428,428
BEGIN DESCRIPTION:
Mapping XS 5230748f
END DESCRIPTION:
XS GIS Cut Line= 4
       3719891.4     10608557.38      3719812.55     10608664.01
      3719779.39     10608714.19      3719737.29     10608821.68
#Sta/Elev= 30
  4866.9     281  4871.8     281  4877.5  277.12  4898.3  278.64  4920.1  273.22
  4927.6     274  4933.8  269.32  4956.8  265.22    4963  262.46  4969.9  262.91
  4977.7   270.1  4983.9  263.54  4992.3  265.06  4997.8  262.39  5013.4   264.7
  5019.4  260.55  5032.7  262.45  5042.9  265.87  5049.5   268.8  5059.7  268.38
  5066.1  270.64  5101.9  271.77  5116.8  258.43  5119.5  257.93  5122.8  258.43
  5126.4  262.96  5131.8  263.65  5150.8   269.5  5162.8  277.31  5175.1     279
#Mann= 4 ,-1 , 0
  4866.9     .12       0  5032.7     .05       0  5101.9     .07       0
  5131.8     .05       0
#XS Ineff= 2 , 0
                         5108.92          264.54
Permanent Ineff=
       F       F
Bank Sta=5013.4,5042.9
XS Rating Curve= 0 ,0
Exp/Cntr=0.3,0.1

Type RM Length L Ch R = 1 ,559     ,0,0,0
BEGIN DESCRIPTION:
UNT 139 IN BOCR 1.0
END DESCRIPTION:
XS GIS Cut Line= 3
      3719649.59      10608360.2      3719449.61     10608460.19
       3719499.6     10608710.15
#Sta/Elev= 30
  4786.2  272.64  4816.9  270.59  4830.9  268.86  4839.3  268.61  4844.9  267.26
  4853.3  266.57  4861.6  266.07    4884  265.87  4889.6  265.08    4912  263.47
  4951.1   261.4  4956.7  259.87  4965.1  259.25    4979  255.29  4984.4  252.81
  4987.2  252.31  5001.4  255.58    5020  256.13  5030.2  258.13  5040.4  258.77
  5050.6  260.28  5060.8  259.98    5071  261.64  5081.2  262.39  5091.4  262.29
  5101.6  263.13    5122  263.71  5132.2   264.8  5162.8  266.63  5264.7  275.01
#Mann= 3 ,-1 , 0
  4786.2     .12       0  4956.7     .05       0  5040.4     .12       0
Bank Sta=4979,5001.4
XS Rating Curve= 0 ,0
Exp/Cntr=0.3,0.1

Chan Stop Cuts=-1
Use User Specified Reach Order=0
Composite Channel Slope=5