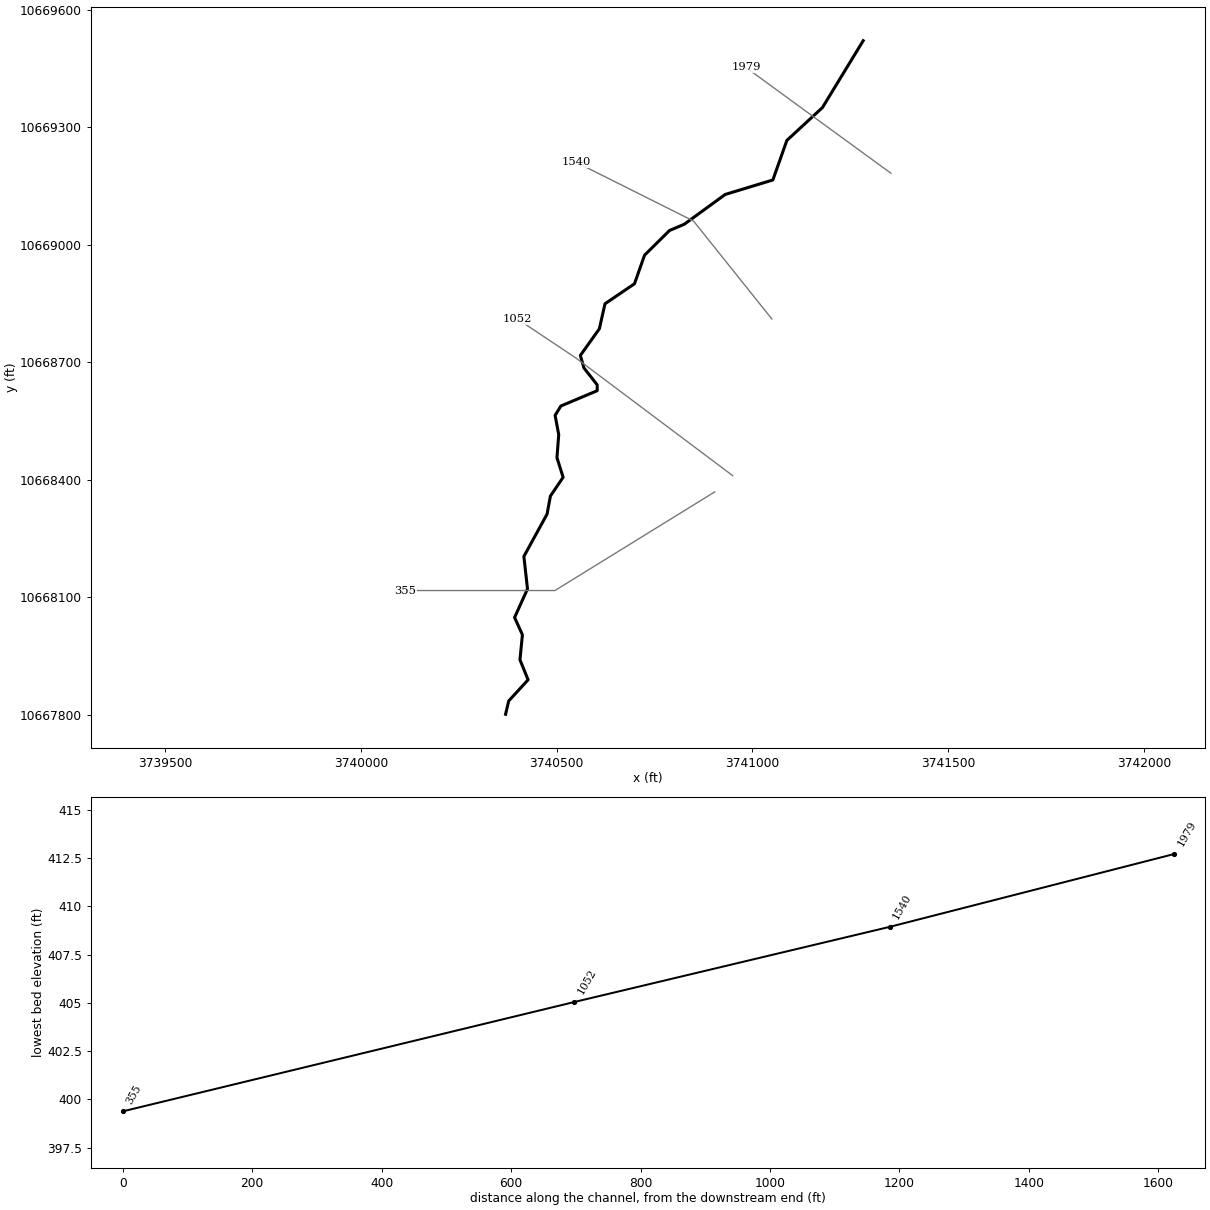
--- UNT 142 IN BOCR.prj (project) ---

Proj Title=UNT 142 IN BOCR Base Level Engineering
Current Plan=p01
Default Exp/Contr=0.3,0.1
English Units
Geom File=g01
Flow File=f01
Plan File=p01
Y Axis Title=Elevation
X Axis Title(PF)=Main Channel Distance
X Axis Title(XS)=Station
BEGIN DESCRIPTION:
UNT 142 IN BOCR
END DESCRIPTION:
DSS Export Rating Curves= 0
DSS Export Rating Curve Sorted= 0
DSS Export Volume Flow Curves= 0
DXF OffsetX= 0
DXF OffsetY= 0
DXF ScaleX= 1
DXF ScaleY= 10

--- UNT 142 IN BOCR.p01 (plan) ---

Plan Title=Multiple Run
Short Identifier=Multiple
Geom File=g01
Flow File=f01
Subcritical Flow
K Sum by GR= 0
Std Step Tol= 0.01
Critical Tol= 0.01
Num of Std Step Trials= 20
Max Error Tol= 0.3
Flow Tol Ratio= 0.001
Split Flow NTrial= 30
Split Flow Tol= 0.02
Split Flow Ratio= 0.02
Log Output Level= 0
Friction Slope Method= 1
Unsteady Friction Slope Method= 2
Unsteady Bridges Friction Slope Method= 1
Parabolic Critical Depth
Global Vel Dist=  1 , 1 , 1
Global Log Level= 0
CheckData=True
Encroach Param= -1, 0, 0, 0
BEGIN DESCRIPTION:
Multiple Run
END DESCRIPTION:

--- UNT 142 IN BOCR.f01 (steady flow) ---

Flow Title=Multiple
Program Version=4.10
Number of Profiles= 7
Profile Names=10-year,25-year,50-year,1pct_min,100-year,1pct_plu,500-year
River Rch & RM=UNT 142 IN BOCR,Reach-1         ,1979
     779    1087    1351    1235    1670    2259    2562
Boundary for River Rch & Prof#=UNT 142 IN BOCR,Reach-1         , 1
Up Type= 0
Dn Type= 3
Dn Slope=0.008
Boundary for River Rch & Prof#=UNT 142 IN BOCR,Reach-1         , 2
Up Type= 0
Dn Type= 3
Dn Slope=0.008
Boundary for River Rch & Prof#=UNT 142 IN BOCR,Reach-1         , 3
Up Type= 0
Dn Type= 3
Dn Slope=0.008
Boundary for River Rch & Prof#=UNT 142 IN BOCR,Reach-1         , 4
Up Type= 0
Dn Type= 3
Dn Slope=0.008
Boundary for River Rch & Prof#=UNT 142 IN BOCR,Reach-1         , 5
Up Type= 0
Dn Type= 3
Dn Slope=0.008
Boundary for River Rch & Prof#=UNT 142 IN BOCR,Reach-1         , 6
Up Type= 0
Dn Type= 3
Dn Slope=0.008
Boundary for River Rch & Prof#=UNT 142 IN BOCR,Reach-1         , 7
Up Type= 0
Dn Type= 3
Dn Slope=0.008
DSS Import GetInterval= 0
DSS Import GetPeak= 0
DSS Import FillOption= 0

--- UNT 142 IN BOCR.g01 (geometry) ---

Geom Title=Existing Conditions
Program Version=4.10

River Reach=UNT 142 IN BOCR ,Reach-1
Reach XY= 30
      3741282.99     10669520.58        3741179.       10669350.
        3741088.       10669266.      3741052.25       10669165.
       3740930.5       10669128.        3740826.       10669052.
      3740788.25       10669036.       3740724.5       10668973.
      3740698.75       10668900.       3740623.5       10668849.
        3740609.       10668785.       3740560.5       10668717.
      3740569.75       10668685.       3740603.5       10668642.
       3740603.5       10668627.      3740510.75       10668588.
        3740496.       10668564.      3740505.25       10668515.
      3740500.75       10668456.       3740516.5       10668406.
        3740484.       10668358.       3740475.5       10668312.
      3740416.25       10668204.       3740425.5       10668121.
       3740392.5       10668048.       3740412.5       10668004.
      3740406.25       10667940.        3740427.       10667889.
       3740377.5       10667835.       3740369.5       10667801.

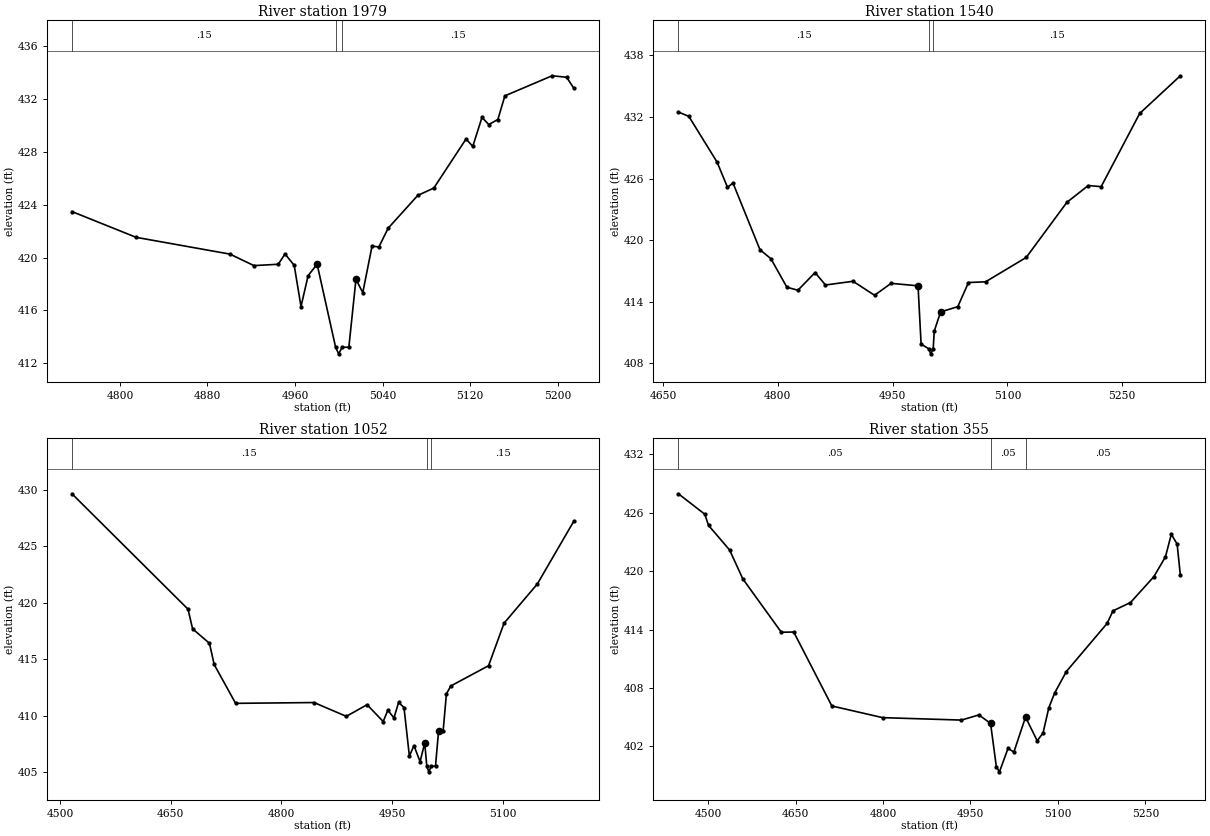
Type RM Length L Ch R = 1 ,1979    ,439,439,439
BEGIN DESCRIPTION:
UNT 142 IN BOCR 4.0
END DESCRIPTION:
XS GIS Cut Line= 2
      3741353.94     10669182.12      3740983.51     10669452.15
#Sta/Elev= 30
  4756.2  423.48  4814.8  421.53  4900.5  420.26  4922.4  419.39  4944.6  419.49
  4950.8  420.27  4959.2  419.41  4965.4  416.29  4971.9  418.63  4980.1   419.5
    4997  413.21  4999.8  412.71    5003  413.21  5009.1  413.21  5015.6  418.36
  5021.8  417.34  5030.3  420.87  5036.5   420.8    5045  422.22    5072   424.7
  5086.7  425.26  5116.1  428.97  5122.3  428.42  5130.7  430.61  5136.9  430.07
  5145.2  430.45  5151.6  432.24  5194.7  433.76    5208  433.65  5214.6  432.81
#Mann= 3 ,-1 , 0
  4756.2     .15       0    4997     .05       0    5003     .15       0
Bank Sta=4980.1,5015.6
XS Rating Curve= 0 ,0
Exp/Cntr=0.3,0.1

Type RM Length L Ch R = 1 ,1540    ,488,488,488
BEGIN DESCRIPTION:
UNT 142 IN BOCR 3.0
END DESCRIPTION:
XS GIS Cut Line= 3
      3741049.63     10668810.17      3740849.61     10669060.19
       3740549.6     10669210.19
#Sta/Elev= 30
  4670.2  432.47  4683.8  432.05  4720.7   427.6  4734.3  425.15  4741.5  425.56
  4776.7  419.08  4791.1  418.19  4811.9  415.42  4826.3  415.13  4848.7  416.85
  4862.3  415.64  4898.3     416  4926.4  414.64    4948   415.8  4983.2  415.56
  4987.2  409.89    4997  409.44  4999.8  408.94    5003  409.44  5004.4  411.16
  5012.7  413.02  5035.1  413.53  5049.1  415.88  5071.4  415.95  5124.5  418.32
  5177.7  423.69  5205.6  425.32  5222.4  425.21  5272.7  432.33  5325.8     436
#Mann= 3 ,-1 , 0
  4670.2     .15       0    4997     .05       0    5003     .15       0
Bank Sta=4983.2,5012.7
XS Rating Curve= 0 ,0
Exp/Cntr=0.3,0.1

Type RM Length L Ch R = 1 ,1052    ,697,697,697
BEGIN DESCRIPTION:
UNT 142 IN BOCR 2.0
END DESCRIPTION:
XS GIS Cut Line= 3
      3740949.58     10668410.21      3740549.61     10668710.19
      3740399.64     10668810.16
#Sta/Elev= 30
  4516.1  429.64  4673.4  419.43  4679.6  417.69  4702.5  416.41  4708.8  414.54
  4737.9   411.1  4844.2  411.17  4887.9  409.95  4916.1  410.98  4937.9  409.49
  4944.2  410.49  4952.5  409.81  4958.8  411.18  4966.1  410.73  4973.4  406.43
  4979.6  407.36  4987.9  405.94  4994.2   407.6    4997  405.54  4999.8  405.04
    5003  405.54  5008.8  405.54  5012.9  408.63  5019.1  408.63  5023.6  411.94
  5029.6  412.64  5080.7  414.43  5101.7  418.19  5146.8  421.66  5196.3  427.22
#Mann= 3 ,-1 , 0
  4516.1     .15       0    4997     .05       0    5003     .15       0
Bank Sta=4994.2,5012.9
XS Rating Curve= 0 ,0
Exp/Cntr=0.3,0.1

Type RM Length L Ch R = 1 ,355     ,0,0,0
BEGIN DESCRIPTION:
UNT 142 IN BOCR 1.0
END DESCRIPTION:
XS GIS Cut Line= 3
      3740903.64      10668368.6      3740495.69     10668116.88
      3740114.15     10668116.88
#Sta/Elev= 30
  4449.1  427.96  4494.3  425.86  4500.8  424.71  4536.9  422.18  4559.6  419.21
  4625.6  413.73  4646.9  413.75  4712.3  406.15  4799.4  404.95  4934.5   404.7
  4964.5  405.23  4984.5  404.36  4994.5  399.88  4999.8  399.38  5014.5   401.8
  5024.5  401.41  5044.5  405.01  5064.5  402.57  5074.5  403.37  5084.5  405.98
  5094.5  407.49  5114.5  409.69  5184.5  414.64  5194.5  415.93  5224.5  416.78
  5264.5  419.43  5284.5  421.48  5294.5  423.79  5304.5   422.8    5310  419.63
#Mann= 3 , 0 , 0
  4449.1     .05       0  4984.5     .05       0  5044.5     .05       0
Bank Sta=4984.5,5044.5
XS Rating Curve= 0 ,0
Exp/Cntr=0.3,0.1

Chan Stop Cuts=-1
Use User Specified Reach Order=0
Composite Channel Slope=5