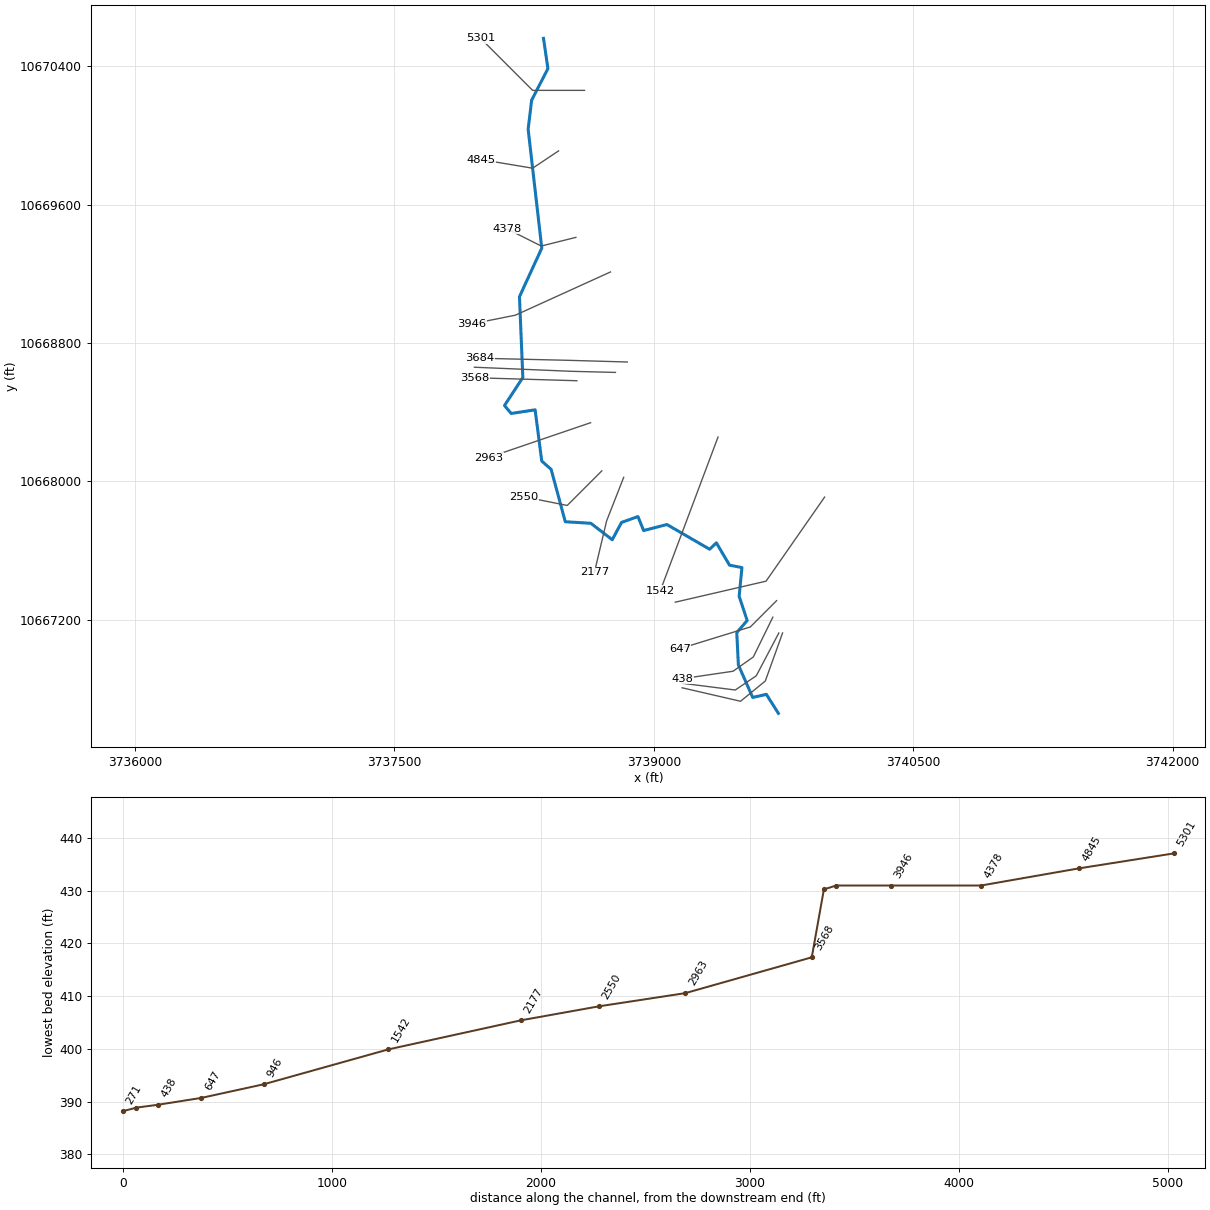
--- UNT 143 IN BOCR.prj (project) ---

Proj Title=UNT 143 IN BOCR Base Level Engineering
Current Plan=p01
Default Exp/Contr=0.3,0.1
English Units
Geom File=g01
Flow File=f01
Plan File=p01
Y Axis Title=Elevation
X Axis Title(PF)=Main Channel Distance
X Axis Title(XS)=Station
BEGIN DESCRIPTION:
UNT 143 IN BOCR
END DESCRIPTION:
DSS Export Rating Curves= 0
DSS Export Rating Curve Sorted= 0
DSS Export Volume Flow Curves= 0
DXF OffsetX= 0
DXF OffsetY= 0
DXF ScaleX= 1
DXF ScaleY= 10

--- UNT 143 IN BOCR.p01 (plan) ---

Plan Title=Multiple Run
Short Identifier=Multiple
Geom File=g01
Flow File=f01
Subcritical Flow
K Sum by GR= 0
Std Step Tol= 0.01
Critical Tol= 0.01
Num of Std Step Trials= 20
Max Error Tol= 0.3
Flow Tol Ratio= 0.001
Split Flow NTrial= 30
Split Flow Tol= 0.02
Split Flow Ratio= 0.02
Log Output Level= 0
Friction Slope Method= 1
Unsteady Friction Slope Method= 2
Unsteady Bridges Friction Slope Method= 1
Parabolic Critical Depth
Global Vel Dist=  1 , 1 , 1
Global Log Level= 0
CheckData=True
Encroach Param= -1, 0, 0, 0
BEGIN DESCRIPTION:
Multiple Run
END DESCRIPTION:

--- UNT 143 IN BOCR.f01 (steady flow) ---

Flow Title=Multiple
Number of Profiles=7
Profile Names=10-year,25-year,50-year,1pct_min,100-year,1pct_plu,500-year
River Rch & RM= UNT 143 IN BOCR,Reach-1,5301
     584     798     976     879    1189    1609    1771
Boundary for River Rch & Prof#=UNT 143 IN BOCR,Reach-1,1
Up Type=0
Dn Type=3
Dn Slope=0.005
Boundary for River Rch & Prof#=UNT 143 IN BOCR,Reach-1,2
Up Type=0
Dn Type=3
Dn Slope=0.005
Boundary for River Rch & Prof#=UNT 143 IN BOCR,Reach-1,3
Up Type=0
Dn Type=3
Dn Slope=0.005
Boundary for River Rch & Prof#=UNT 143 IN BOCR,Reach-1,4
Up Type=0
Dn Type=3
Dn Slope=0.005
Boundary for River Rch & Prof#=UNT 143 IN BOCR,Reach-1,5
Up Type=0
Dn Type=3
Dn Slope=0.005
Boundary for River Rch & Prof#=UNT 143 IN BOCR,Reach-1,6
Up Type=0
Dn Type=3
Dn Slope=0.005
Boundary for River Rch & Prof#=UNT 143 IN BOCR,Reach-1,7
Up Type=0
Dn Type=3
Dn Slope=0.005

--- UNT 143 IN BOCR.g01 (geometry) ---

Geom Title=Existing Conditions
Program Version=4.10

River Reach=UNT 143 IN BOCR ,Reach-1
Reach XY= 30
       3738362.5       10670561.        3738388.       10670386.
      3738293.75       10670203.      3738273.75       10670035.
       3738352.5       10669348.       3738223.5       10669067.
        3738243.       10668600.        3738137.       10668438.
       3738175.5       10668392.        3738314.       10668413.
      3738352.25       10668117.       3738406.5       10668069.
       3738488.5       10667766.      3738636.25       10667757.
        3738760.       10667662.      3738813.75       10667762.
      3738908.75       10667796.      3738941.25       10667715.
        3739076.       10667750.        3739323.       10667607.
        3739362.       10667644.        3739438.       10667515.
      3739509.75       10667501.      3739493.75       10667335.
        3739540.       10667195.        3739480.       10667125.
      3739489.27     10666938.09        3739572.       10666750.
        3739651.       10666768.      3739720.75       10666658.

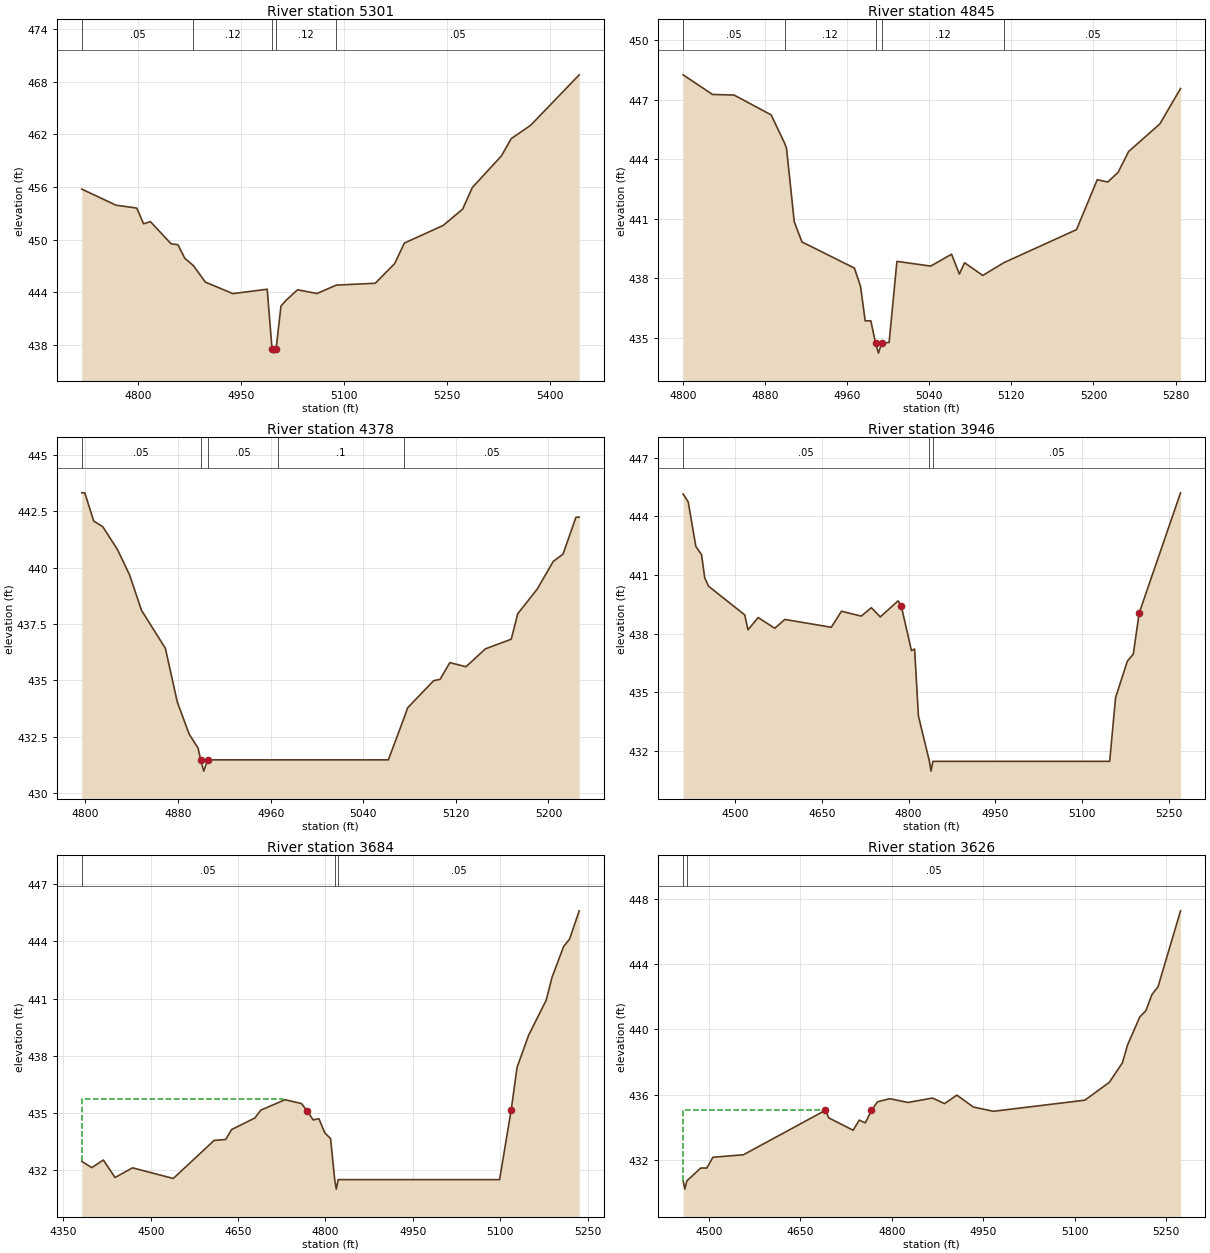
Type RM Length L Ch R = 1 ,5301    ,456,456,456
BEGIN DESCRIPTION:
UNT 143 IN BOCR 11.0
END DESCRIPTION:
XS GIS Cut Line= 3
      3738599.63     10670260.19      3738299.61     10670260.19
       3737999.6      10670560.2
#Sta/Elev= 30
  4718.3  455.76  4768.3  453.92  4798.3   453.6  4808.3  451.81  4818.3  452.05
  4848.3  449.53  4858.3  449.42  4868.3  447.88  4880.8  447.04  4898.3  445.16
  4938.3  443.85  4988.3  444.35  4995.3  437.57  4998.1  437.07  5001.3  437.57
  5008.3  442.43  5015.8  443.09  5032.5  444.29  5060.7  443.86  5088.9  444.82
  5145.6  445.03  5173.9  447.27    5188  449.61  5244.6  451.62  5272.9  453.48
    5287  455.94  5329.4  459.55  5343.6  461.51  5371.9  463.03  5442.6  468.78
#Mann= 5 ,-1 , 0
  4718.3     .05       0  4880.8     .12       0  4995.3     .07       0
  5001.3     .12       0  5088.9     .05       0
Bank Sta=4995.3,5001.3
XS Rating Curve= 0 ,0
Exp/Cntr=0.3,0.1

Type RM Length L Ch R = 1 ,4845    ,467,467,467
BEGIN DESCRIPTION:
UNT 143 IN BOCR 10.0
END DESCRIPTION:
XS GIS Cut Line= 3
      3738449.63      10669910.2      3738299.61     10669810.19
      3737999.65     10669860.18
#Sta/Elev= 30
  4800.4  448.26    4829  447.27    4850  447.24  4886.1  446.24  4899.5  444.78
  4901.1  444.55  4908.6  440.85  4916.1  439.83  4967.2  438.51  4973.2  437.58
  4977.7  435.85  4983.2  435.85  4987.8  434.72  4990.6  434.22  4993.8  434.72
    5001  434.76  5008.6  438.85  5041.5  438.61  5061.8  439.21  5069.4  438.21
  5074.5  438.78  5092.2  438.14    5113  438.79  5183.5  440.45  5203.7  442.97
  5213.9  442.85    5224  443.34  5234.2  444.39  5264.6  445.78  5284.8  447.57
#Mann= 5 ,-1 , 0
  4800.4     .05       0  4899.5     .12       0  4987.8     .07       0
  4993.8     .12       0    5113     .05       0
Bank Sta=4987.8,4993.8
XS Rating Curve= 0 ,0
Exp/Cntr=0.3,0.1

Type RM Length L Ch R = 1 ,4378    ,432,432,432
BEGIN DESCRIPTION:
UNT 143 IN BOCR 9.0
END DESCRIPTION:
XS GIS Cut Line= 3
      3738549.63     10669410.19      3738349.61     10669360.19
       3738149.6     10669460.19
#Sta/Elev= 30
  4796.8  443.32  4799.4  443.32  4807.1  442.07  4814.9  441.82  4827.7   440.8
  4838.1  439.68  4848.4  438.11    4869  436.43  4879.3  434.05  4889.6  432.62
  4897.3     432  4899.5  431.48  4902.2  430.98  4905.5  431.48  4966.7  431.48
  5061.7  431.48  5075.2  433.33  5078.4  433.79  5100.8  434.99  5106.4  435.05
  5114.8  435.79  5128.8  435.61  5145.5   436.4  5167.9  436.83  5173.5  437.96
  5190.3  439.05  5204.2  440.28  5212.6   440.6  5223.8  442.24  5226.6  442.24
#Mann= 5 ,-1 , 0
  4796.8     .05       0  4899.5     .07       0  4905.5     .05       0
  4966.7      .1       0  5075.2     .05       0
Bank Sta=4899.5,4905.5
XS Rating Curve= 0 ,0
Exp/Cntr=0.3,0.1

Type RM Length L Ch R = 1 ,3946    ,262,262,262
BEGIN DESCRIPTION:
UNT 143 IN BOCR 8.0
END DESCRIPTION:
XS GIS Cut Line= 3
       3738749.6     10669210.18      3738199.61     10668960.19
       3737949.6     10668910.19
#Sta/Elev= 30
  4410.6  445.14  4419.4  444.73  4432.6  442.46  4442.4  442.04  4447.9  440.86
  4454.5  440.43  4517.1  438.96  4522.6   438.2  4540.2  438.83  4568.8  438.28
  4586.3  438.73  4666.5  438.33  4684.1  439.15  4718.2   438.9  4735.7  439.33
  4751.1  438.86  4781.9  439.68  4787.4  439.41  4804.9  437.14  4810.4  437.22
    4817   433.8    4836  431.48  4838.7  430.98    4842  431.48  5147.3  431.48
  5157.5  434.74  5177.9   436.6  5188.1  436.96  5198.3  439.06  5269.7   445.2
#Mann= 3 ,-1 , 0
  4410.6     .05       0    4836    .033       0    4842     .05       0
Bank Sta=4787.4,5198.3
XS Rating Curve= 0 ,0
Exp/Cntr=0.3,0.1

Type RM Length L Ch R = 1 ,3684    ,58,58,58
BEGIN DESCRIPTION:
UNT 143 IN BOCR 7.0
END DESCRIPTION:
XS GIS Cut Line= 3
      3738846.68     10668689.59      3738501.26     10668699.46
      3737992.96     10668711.46
#Sta/Elev= 30
  4381.6  432.44  4398.7  432.11  4418.7  432.51  4438.7  431.59  4468.7   432.1
  4538.7  431.54  4608.8  433.54  4628.8  433.59  4638.8  434.11  4678.8  434.72
  4688.8  435.13  4730.5  435.68  4758.8  435.48  4768.8  435.08  4778.8  434.62
  4788.8  434.68  4798.8  433.94  4808.8  433.63  4815.8  431.48  4818.6  430.98
  4821.8  431.48  5098.9  431.48  5118.9  435.15  5128.9  437.38  5148.9  439.08
  5178.9  440.91  5188.9  442.11  5208.9  443.74    5219  444.12  5235.6  445.61
#Mann= 3 ,-1 , 0
  4381.6     .05       0  4815.8     .03       0  4821.8     .05       0
#XS Ineff= 2 , 0
          4727.6   435.7
Permanent Ineff=
       F       F
Bank Sta=4768.8,5118.9
XS Rating Curve= 0 ,0
Exp/Cntr=0.3,0.1

Type RM Length L Ch R = 1 ,3626    ,58,58,58
BEGIN DESCRIPTION:
Mapping XS 3a33671f
END DESCRIPTION:
XS GIS Cut Line= 3
      3738778.51      10668629.4      3738528.08     10668635.62
      3737962.79     10668659.34
#Sta/Elev= 30
  4457.6  430.73  4460.4  430.23  4463.6  430.73  4486.5  431.52  4496.5  431.52
  4506.5  432.18  4556.5  432.33  4691.1  435.05  4696.6  434.59  4736.6  433.83
  4746.6  434.45  4756.6  434.28  4766.6  435.04  4776.6  435.57  4796.7  435.76
  4826.7  435.53  4866.7   435.8  4886.7  435.46  4906.8  435.98    4934  435.25
  4966.8  434.99  5116.9  435.67    5157  436.76  5178.4  437.95    5187  439.05
    5207  440.76    5217  441.14    5227  442.13    5237  442.61  5273.9  447.25
#Mann= 2 ,-1 , 0
  4457.6     .03       0  4463.6     .05       0
#XS Ineff= 2 , 0
         4685.54  435.09
Permanent Ineff=
       F       F
Bank Sta=4691.1,4766.6
XS Rating Curve= 0 ,0
Exp/Cntr=0.3,0.1

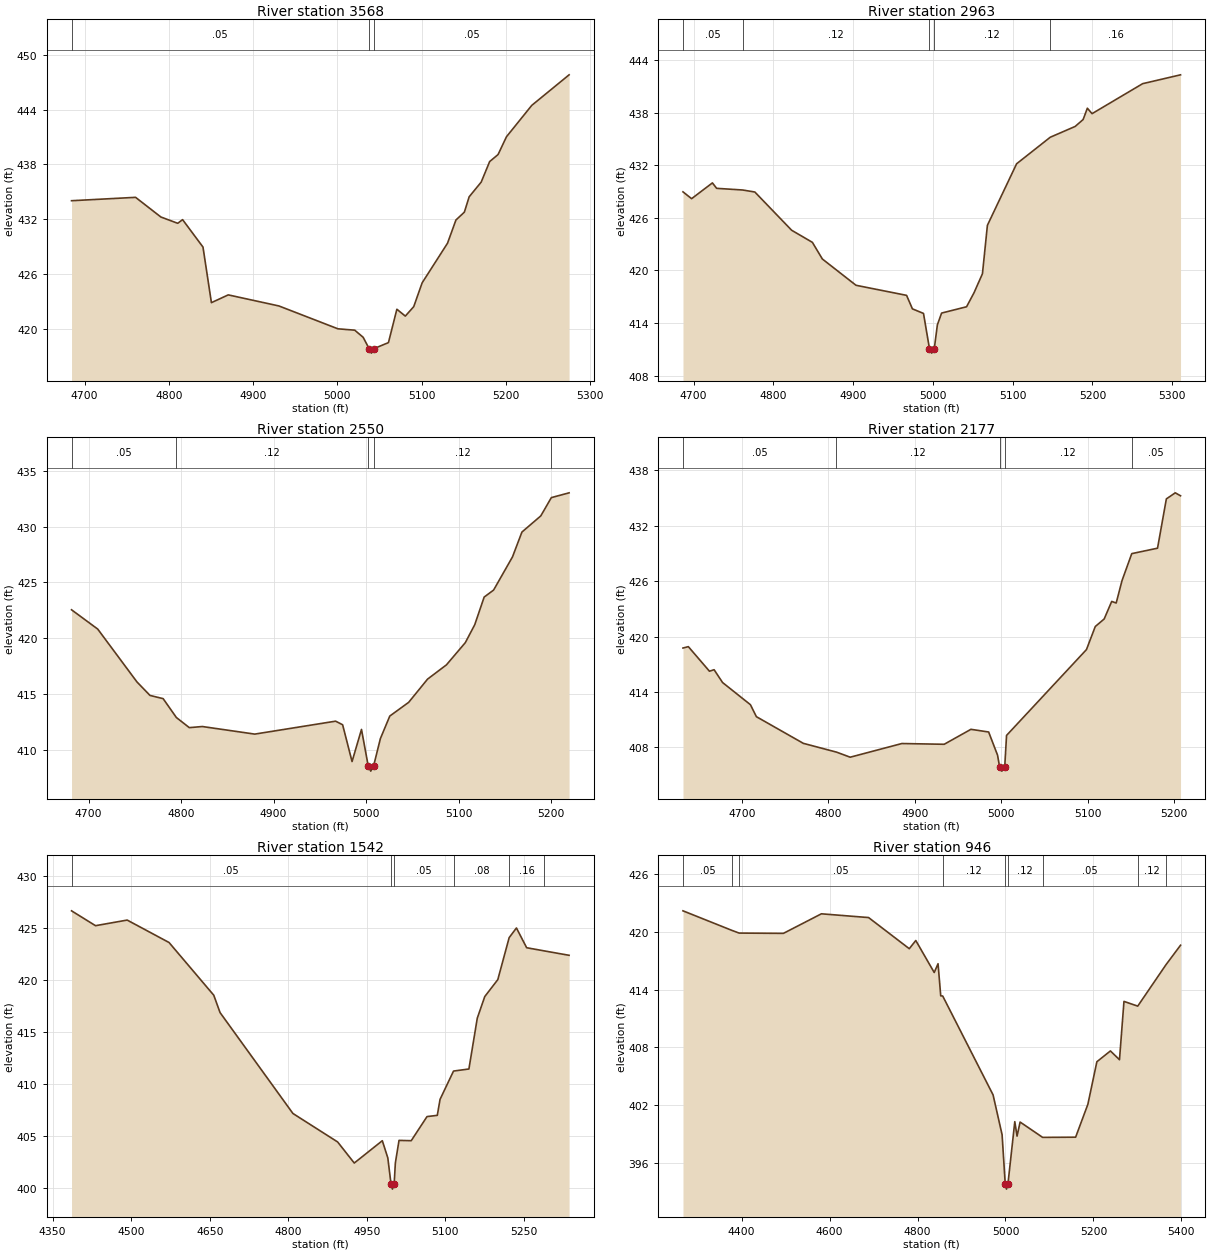
Type RM Length L Ch R = 1 ,3568    ,605,605,605
BEGIN DESCRIPTION:
Mapping XS 7c7e2dc8
END DESCRIPTION:
XS GIS Cut Line= 2
      3738555.57     10668581.29      3737965.32     10668598.65
#Sta/Elev= 30
  4684.5  434.03  4760.5   434.4  4790.5  432.25  4810.5  431.56  4816.3  431.96
  4840.5  428.96  4850.5  422.88  4870.5  423.73  4930.6  422.52  5000.6  420.02
  5020.6  419.87  5030.6  419.09  5037.6  417.86  5040.4  417.36  5043.6  417.86
  5060.6  418.51  5070.6  422.16  5080.6  421.41  5090.6  422.44  5100.6  425.05
  5130.7  429.38  5140.7  431.92  5150.7  432.78  5156.4  434.46  5170.7  436.07
  5180.7  438.31  5190.7  439.08  5200.7  441.03  5230.7  444.46    5275   447.8
#Mann= 3 ,-1 , 0
  4684.5     .05       0  5037.6     .03       0  5043.6     .05       0
Bank Sta=5037.6,5043.6
XS Rating Curve= 0 ,0
Exp/Cntr=0.3,0.1

Type RM Length L Ch R = 1 ,2963    ,413,413,413
BEGIN DESCRIPTION:
UNT 143 IN BOCR 6.0
END DESCRIPTION:
XS GIS Cut Line= 2
      3738634.92     10668338.67      3738044.63     10668137.28
#Sta/Elev= 30
  4686.7  428.97  4697.5  428.19  4723.6  429.99  4728.9  429.37  4761.5  429.18
  4776.8  428.95  4822.9  424.59  4848.9  423.21  4861.4  421.31  4903.6  418.31
    4967  417.16  4974.3  415.62  4988.2   415.1  4995.7  411.07  4998.5  410.57
  5001.7  411.07  5005.6   413.8  5010.9  415.14  5042.2  415.86  5051.6  417.47
  5062.1  419.63  5068.3  425.15  5104.9  432.17  5147.1   435.2  5178.3  436.43
  5188.3  437.22  5193.6  438.51  5199.5  437.89  5262.9  441.31  5310.4  442.32
#Mann= 5 ,-1 , 0
  4686.7     .05       0  4761.5     .12       0  4995.7     .07       0
  5001.7     .12       0  5147.1     .16       0
Bank Sta=4995.7,5001.7
XS Rating Curve= 0 ,0
Exp/Cntr=0.3,0.1

Type RM Length L Ch R = 1 ,2550    ,373,373,373
BEGIN DESCRIPTION:
UNT 143 IN BOCR 5.0
END DESCRIPTION:
XS GIS Cut Line= 3
      3738699.59     10668060.17      3738499.61     10667860.19
      3738249.58     10667910.19
#Sta/Elev= 30
  4681.6  422.54  4709.9  420.81  4752.3  416.07  4766.4  414.86  4780.6  414.57
  4794.9  412.88  4808.9  411.97    4823  412.07  4879.6  411.39    4967  412.55
  4974.6  412.23  4984.8  408.93    4995  411.81  5002.2  408.57    5005  408.07
  5008.2  408.57  5015.4  410.98  5025.6  413.01    5046  414.24  5066.4  416.32
  5086.8   417.6  5107.2  419.59  5117.4   421.2  5127.6  423.68  5137.8  424.31
  5158.2  427.28  5168.4  429.51  5188.8  430.96  5200.2   432.6  5219.4  433.03
#Mann= 5 ,-1 , 0
  4681.6     .05       0  4794.9     .12       0  5002.2     .07       0
  5008.2     .12       0  5200.2     .16       0
Bank Sta=5002.2,5008.2
XS Rating Curve= 0 ,0
Exp/Cntr=0.3,0.1

Type RM Length L Ch R = 1 ,2177    ,635,635,635
BEGIN DESCRIPTION:
UNT 143 IN BOCR 4.0
END DESCRIPTION:
XS GIS Cut Line= 3
      3738826.14     10668022.79      3738727.18     10667770.18
       3738657.1     10667474.27
#Sta/Elev= 30
  4632.1  418.76  4638.3  418.91  4662.7  416.25  4668.1  416.41  4677.9  415.02
  4710.1  412.62    4717  411.32  4771.3  408.43  4809.6  407.48  4825.5  406.93
  4885.2  408.41  4934.2  408.33  4965.1  409.95  4985.6  409.66  4995.9  407.15
  4998.2  405.92  5000.9  405.42  5004.2  405.92  5006.3  409.29  5098.7  418.59
  5108.9  421.09  5119.2  421.91  5127.9  423.81  5133.1  423.64  5139.8  426.06
  5151.1  428.99  5180.9  429.58  5191.1  434.92  5201.4  435.58  5207.5  435.26
#Mann= 5 ,-1 , 0
  4632.1     .05       0  4809.6     .12       0  4998.2     .07       0
  5004.2     .12       0  5151.1     .05       0
Bank Sta=4998.2,5004.2
XS Rating Curve= 0 ,0
Exp/Cntr=0.3,0.1

Type RM Length L Ch R = 1 ,1542    ,596,596,596
BEGIN DESCRIPTION:
UNT 143 IN BOCR 3.0
END DESCRIPTION:
XS GIS Cut Line= 2
      3739371.56      10668255.8      3739037.34     10667365.99
#Sta/Elev= 30
  4386.1  426.68  4431.9  425.25  4492.4  425.79  4572.4  423.63  4657.8  418.56
  4669.8  416.89    4809  407.18  4894.4  404.44  4926.2  402.41  4979.8  404.56
  4990.3   402.9  4996.4   400.4  4999.1   399.9  5002.4   400.4  5004.7  402.42
  5011.7  404.59    5035  404.56  5065.2  406.88  5084.8     407  5090.1  408.54
  5115.8  411.26  5145.2  411.46  5161.2  416.35  5175.5  418.43  5200.4  420.06
  5222.1   424.1    5236  425.03  5255.5  423.13  5289.6  422.82  5336.6   422.4
#Mann= 6 ,-1 , 0
  4386.1     .05       0  4996.4     .03       0  5002.4     .05       0
  5115.8     .08       0  5222.1     .16       0  5289.6     .05       0
Bank Sta=4996.4,5002.4
XS Rating Curve= 0 ,0
Exp/Cntr=0.3,0.1

Type RM Length L Ch R = 1 ,946     ,299,299,299
BEGIN DESCRIPTION:
UNT 143 IN BOCR 2.0
END DESCRIPTION:
XS GIS Cut Line= 3
      3739987.85     10667908.51      3739649.33     10667422.44
      3739124.34     10667300.95
#Sta/Elev= 30
  4266.8  422.17  4378.6  420.13  4394.6  419.86  4495.1  419.83  4581.5  421.86
  4688.8  421.47  4781.3  418.24  4796.1  419.09    4838  415.77  4846.7  416.68
  4852.8  413.35  4857.3  413.33  4971.8  403.07  4992.3  398.94  4999.5  393.79
  5002.3  393.29  5005.5  393.79  5021.2  400.29  5026.3  398.79  5033.3  400.25
  5084.5  398.66  5159.5  398.68  5187.3  402.09  5207.8  406.51  5238.6  407.63
  5259.2  406.72  5269.4  412.77  5300.7  412.28  5364.8  416.57    5398   418.6
#Mann= 9 ,-1 , 0
  4266.8     .05       0  4378.6     .08       0  4394.6     .05       0
  4857.3     .12       0  4999.5     .07       0  5005.5     .12       0
  5084.5     .05       0  5300.7     .12       0  5364.8     .16       0
Bank Sta=4999.5,5005.5
XS Rating Curve= 0 ,0
Exp/Cntr=0.3,0.1

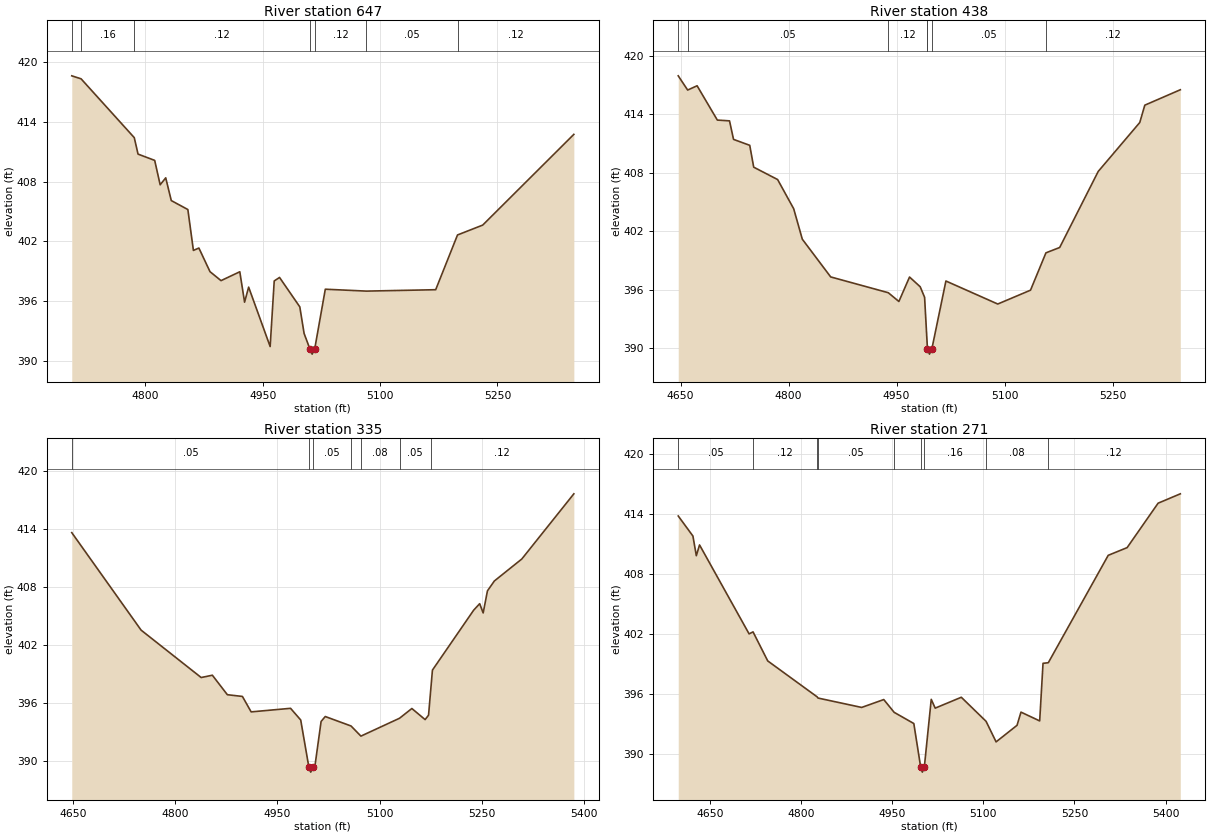
Type RM Length L Ch R = 1 ,647     ,209,209,209
BEGIN DESCRIPTION:
Mapping XS f89a64e3
END DESCRIPTION:
XS GIS Cut Line= 3
      3739710.08     10667309.57      3739558.19     10667157.68
      3739150.17      10667031.8
#Sta/Elev= 30
  4705.8  418.61  4717.7  418.31  4785.7  412.41  4790.5  410.76  4811.8  410.13
  4818.8  407.68  4825.9  408.38    4833   406.1  4854.2   405.2  4861.3   401.1
  4868.3  401.34  4882.5  398.97  4896.6  398.07  4920.6  398.96  4926.7  395.91
  4931.9  397.42  4959.4  391.46  4964.6  398.04  4971.4  398.39  4997.3  395.44
  5002.8  392.77  5010.3   391.2  5013.1   390.7  5016.3   391.2  5029.9  397.21
  5082.4  397.02    5171  397.16  5198.9  402.65  5231.1  403.64  5347.6  412.74
#Mann= 7 ,-1 , 0
  4705.8     .05       0  4717.7     .16       0  4785.7     .12       0
  5010.3     .07       0  5016.3     .12       0  5082.4     .05       0
  5198.9     .12       0
Bank Sta=5010.3,5016.3
XS Rating Curve= 0 ,0
Exp/Cntr=0.3,0.1

Type RM Length L Ch R = 1 ,438     ,103,103,103
BEGIN DESCRIPTION:
Mapping XS 50173ff2
END DESCRIPTION:
XS GIS Cut Line= 4
       3739688.4     10667214.13      3739575.55     10666984.07
      3739458.36      10666901.6      3739163.87      10666858.3
#Sta/Elev= 30
  4646.8  417.94  4659.9  416.48    4673  416.92  4701.1   413.4    4718  413.32
  4723.6  411.42  4746.1  410.81  4751.6  408.57  4784.8   407.3  4807.1  404.31
  4819.1  401.18  4858.5  397.31  4938.5  395.69  4953.2  394.79    4968   397.3
  4982.8   396.3  4988.9  395.22  4992.8  390.02  4992.9  389.89  4995.7  389.39
  4998.9  389.89  5018.5  396.89  5090.5  394.53    5136  395.95  5157.4  399.78
  5176.5  400.33    5230  408.13  5287.7  413.15  5294.7  414.93    5344  416.51
#Mann= 7 ,-1 , 0
  4646.8     .16       0  4659.9     .05       0  4938.5     .12       0
  4992.8     .05       0  4992.9     .04       0  4998.9     .05       0
  5157.4     .12       0
Bank Sta=4992.9,4998.9
XS Rating Curve= 0 ,0
Exp/Cntr=0.3,0.1

Type RM Length L Ch R = 1 ,335     ,64,64,64
BEGIN DESCRIPTION:
Mapping XS 8759914d
END DESCRIPTION:
XS GIS Cut Line= 4
      3739723.12     10667122.97      3739592.91     10666875.56
      3739471.38      10666793.1      3739163.89     10666832.07
#Sta/Elev= 30
  4648.4  413.66  4750.1  403.56  4838.2  398.65  4854.6  398.89  4876.6  396.87
  4898.7  396.69  4911.5  395.09  4969.3  395.46  4984.2  394.25  4996.2  389.35
  4998.9  388.85  5002.2  389.35  5005.2  389.56  5014.1   394.1  5020.2  394.61
    5058  393.63  5072.5  392.58  5129.1  394.43  5147.2  395.44  5166.7  394.29
  5171.7  394.75    5175  397.45  5177.4  399.42  5237.9  405.63  5246.7   406.3
  5251.8  405.34  5258.1  407.63  5268.2  408.65  5308.5  410.93  5384.8  417.68
#Mann= 7 ,-1 , 0
  4648.4     .05       0  4996.2     .04       0  5002.2     .05       0
    5058     .16       0  5072.5     .08       0  5129.1     .05       0
    5175     .12       0
Bank Sta=4996.2,5002.2
XS Rating Curve= 0 ,0
Exp/Cntr=0.3,0.1

Type RM Length L Ch R = 1 ,271     ,0,0,0
BEGIN DESCRIPTION:
UNT 143 IN BOCR 1.0
END DESCRIPTION:
XS GIS Cut Line= 4
      3739744.81     10667122.93      3739644.99     10666845.18
      3739501.76     10666727.99      3739163.94     10666805.95
#Sta/Elev= 30
  4597.4  413.83  4621.6  411.82  4627.2  409.85  4632.5  410.93  4714.1  402.02
  4720.6  402.22  4744.8  399.31  4826.2  395.71  4827.7  395.59  4899.5  394.65
  4935.9  395.44    4953  394.16  4985.4  393.04  4996.7  388.67  4999.5  388.17
  5002.7  388.67  5014.1  395.46  5020.6  394.58  5063.6  395.67  5104.4  393.26
  5120.9   391.2  5155.4  392.86  5161.9  394.18  5192.7   393.3  5198.2  399.07
  5206.9  399.13  5305.6  409.89  5336.7  410.66  5387.7  415.11  5424.3  416.05
#Mann= 9 ,-1 , 0
  4597.4     .05       0  4720.6     .12       0  4826.2     .16       0
  4827.7     .05       0    4953     .16       0  4996.7     .07       0
  5002.7     .16       0  5104.4     .08       0  5206.9     .12       0
Bank Sta=4996.7,5002.7
XS Rating Curve= 0 ,0
Exp/Cntr=0.3,0.1

Chan Stop Cuts=-1
Use User Specified Reach Order=0
Composite Channel Slope=5