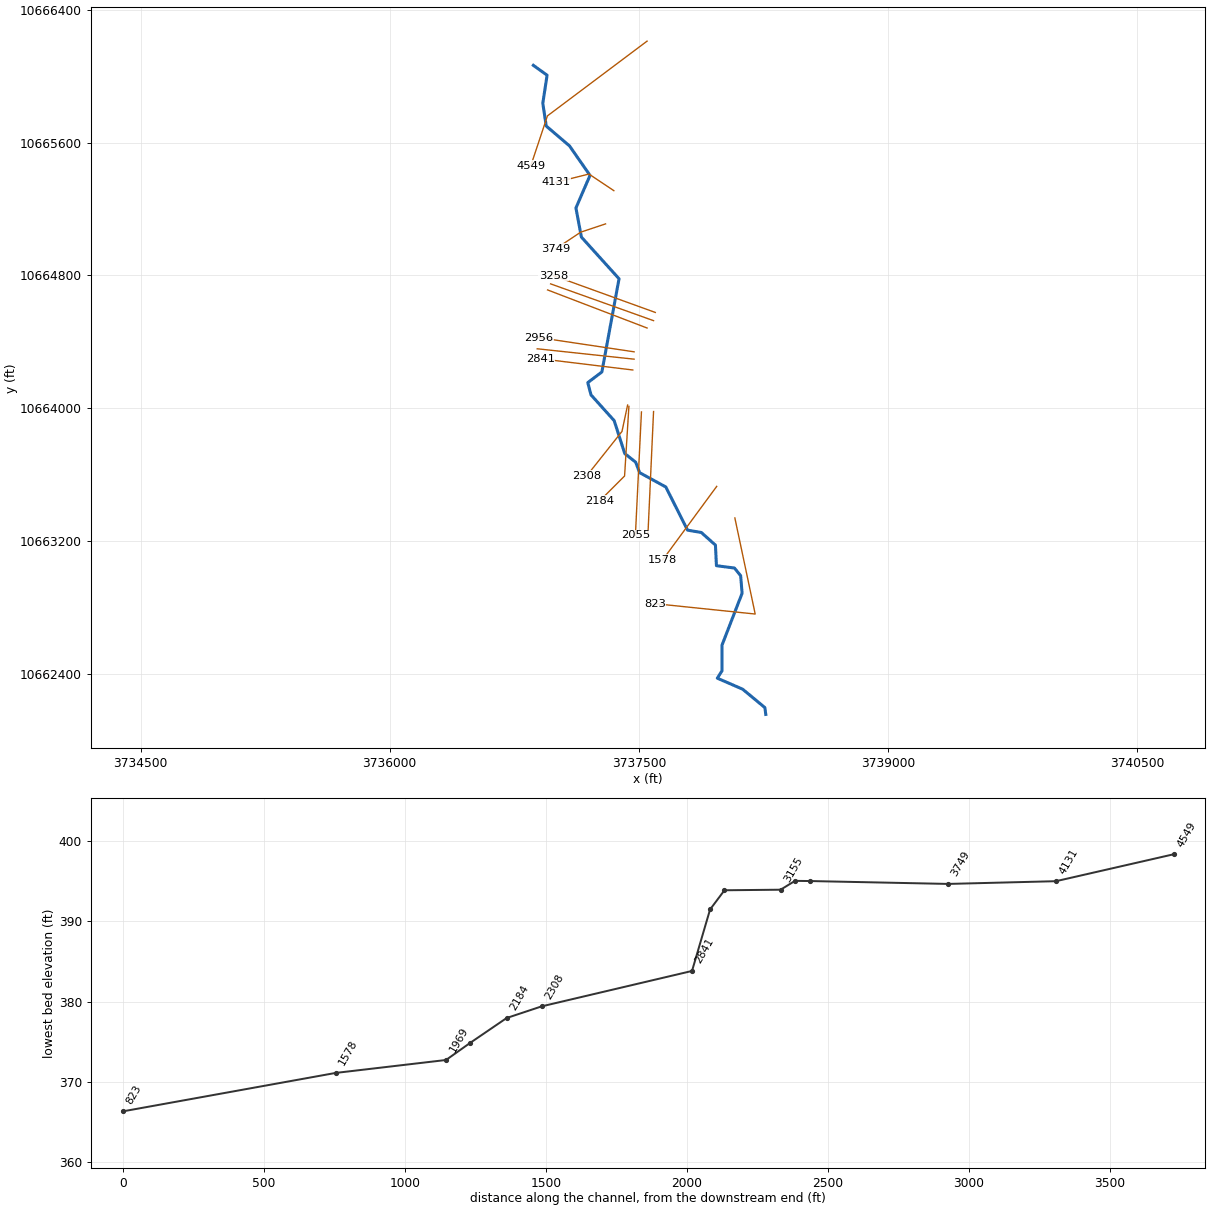
--- UNT 144 IN BOCR.prj (project) ---

Proj Title=UNT 144 IN BOCR Base Level Engineering
Current Plan=p01
Default Exp/Contr=0.3,0.1
English Units
Geom File=g01
Flow File=f01
Plan File=p01
BEGIN DESCRIPTION:
UNT 144 IN BOCR
END DESCRIPTION:

--- UNT 144 IN BOCR.p01 (plan) ---

Plan Title=Multiple Run
Short Identifier=Multiple
Geom File=g01
Flow File=f01
Subcritical Flow
K Sum by GR= 0
Std Step Tol= 0.01
Critical Tol= 0.01
Num of Std Step Trials= 20
Max Error Tol= 0.3
Flow Tol Ratio= 0.001
Split Flow NTrial= 30
Split Flow Tol= 0.02
Split Flow Ratio= 0.02
Log Output Level= 0
Friction Slope Method= 1
Unsteady Friction Slope Method= 2
Unsteady Bridges Friction Slope Method= 1
Parabolic Critical Depth
Global Vel Dist=  1 , 1 , 1
Global Log Level= 0
CheckData=True
Encroach Param= -1, 0, 0, 0
BEGIN DESCRIPTION:
Multiple Run
END DESCRIPTION:

--- UNT 144 IN BOCR.f01 (steady flow) ---

Flow Title=Multiple
Number of Profiles=7
Profile Names=10-year,25-year,50-year,1pct_min,100-year,1pct_plu,500-year
River Rch & RM= UNT 144 IN BOCR,Reach-1,4549
     444     590     709     627     848    1147    1216
Boundary for River Rch & Prof#=UNT 144 IN BOCR,Reach-1,1
Up Type=0
Dn Type=3
Dn Slope=0.005
Boundary for River Rch & Prof#=UNT 144 IN BOCR,Reach-1,2
Up Type=0
Dn Type=3
Dn Slope=0.005
Boundary for River Rch & Prof#=UNT 144 IN BOCR,Reach-1,3
Up Type=0
Dn Type=3
Dn Slope=0.005
Boundary for River Rch & Prof#=UNT 144 IN BOCR,Reach-1,4
Up Type=0
Dn Type=3
Dn Slope=0.005
Boundary for River Rch & Prof#=UNT 144 IN BOCR,Reach-1,5
Up Type=0
Dn Type=3
Dn Slope=0.005
Boundary for River Rch & Prof#=UNT 144 IN BOCR,Reach-1,6
Up Type=0
Dn Type=3
Dn Slope=0.005
Boundary for River Rch & Prof#=UNT 144 IN BOCR,Reach-1,7
Up Type=0
Dn Type=3
Dn Slope=0.005

--- UNT 144 IN BOCR.g01 (geometry) ---

Geom Title=Existing Conditions

River Reach=UNT 144 IN BOCR,Reach-1
Reach XY= 30
      3736864.77     10666064.60      3736947.50     10666005.00
      3736921.75     10665836.00      3736942.58     10665698.82
      3737082.25     10665580.00      3737206.00     10665402.00
      3737121.25     10665206.00      3737154.00     10665031.00
      3737380.75     10664780.00      3737277.50     10664219.00
      3737192.50     10664155.00      3737212.00     10664081.00
      3737351.50     10663926.00      3737415.25     10663728.00
      3737481.00     10663676.00      3737504.75     10663613.00
      3737662.25     10663527.00      3737793.25     10663267.00
      3737876.00     10663253.00      3737961.25     10663177.00
      3737967.25     10663053.00      3738075.75     10663039.00
      3738113.00     10662993.00      3738121.75     10662887.00
      3738000.75     10662575.00      3738001.00     10662421.00
      3737972.50     10662376.00      3738124.75     10662310.00
      3738259.00     10662199.00      3738264.25     10662158.00

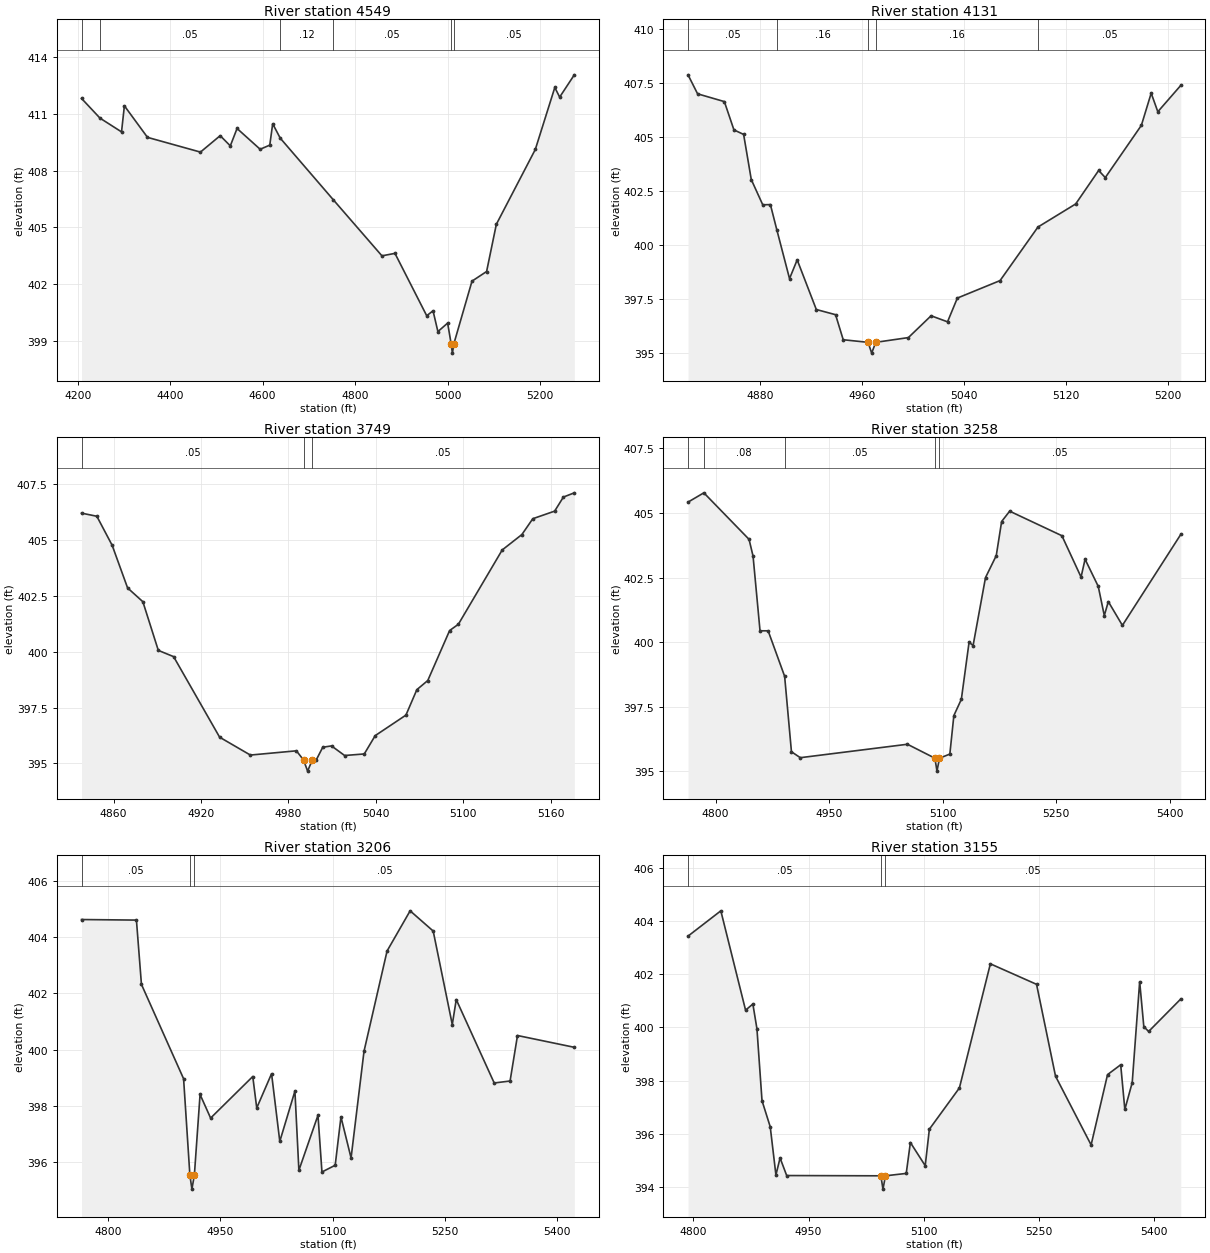
Type RM Length L Ch R = 1,4549,418,418,418
BEGIN DESCRIPTION:
UNT 144 IN BOCR 8.0
END DESCRIPTION:
XS GIS Cut Line= 3
      3737549.64     10666210.21      3736949.61     10665760.19
      3736849.60     10665460.15
#Sta/Elev= 30
  4208.1  411.83  4247.9  410.79  4294.6  410.06  4300.8  411.44  4350.8  409.77
  4465.4  408.99  4508.1  409.86  4530.0  409.32  4544.6  410.24  4594.6  409.14
  4615.4  409.36  4621.7  410.49  4638.0  409.73  4753.1  406.46  4858.1  403.50
  4886.3  403.63  4955.0  400.33  4968.7  400.59  4979.2  399.49  5000.3  399.94
  5007.8  398.85  5010.6  398.35  5013.8  398.85  5053.0  402.16  5084.6  402.67
  5105.7  405.17  5190.0  409.13  5232.2  412.41  5242.7  411.90  5274.4  413.08
#Mann=6,-1,0
  4208.1    0.08       0  4247.9    0.05       0  4638.0    0.12       0
  4753.1    0.05       0  5007.8    0.03       0  5013.8    0.05       0
Bank Sta=5007.8,5013.8
Exp/Cntr=0.3,0.1

Type RM Length L Ch R = 1,4131,382,382,382
BEGIN DESCRIPTION:
UNT 144 IN BOCR 7.0
END DESCRIPTION:
XS GIS Cut Line= 3
      3737349.60     10665310.19      3737199.61     10665410.19
      3736999.63     10665360.19
#Sta/Elev= 30
  4823.8  407.88  4831.3  407.00  4852.3  406.64  4859.8  405.33  4867.4  405.12
  4873.4  403.03  4882.4  401.86  4888.4  401.87  4893.4  400.71  4903.4  398.44
  4909.4  399.31  4924.4  397.01  4939.5  396.77  4945.5  395.61  4965.0  395.49
  4967.8  394.99  4971.0  395.49  4996.6  395.71  5014.4  396.72  5027.3  396.44
  5035.0  397.54  5068.5  398.35  5098.2  400.83  5127.8  401.90  5145.8  403.45
  5151.0  403.12  5179.3  405.54  5187.0  407.03  5192.2  406.17  5210.2  407.39
#Mann=5,-1,0
  4823.8    0.05       0  4893.4    0.16       0  4965.0    0.07       0
  4971.0    0.16       0  5098.2    0.05       0
Bank Sta=4965,4971
Exp/Cntr=0.3,0.1

Type RM Length L Ch R = 1,3749,491,491,491
BEGIN DESCRIPTION:
UNT 144 IN BOCR 6.0
END DESCRIPTION:
XS GIS Cut Line= 3
      3737299.56     10665110.17      3737149.61     10665060.19
      3736999.65     10664960.21
#Sta/Elev= 30
  4838.0  406.21  4848.5  406.07  4859.0  404.77  4869.6  402.86  4880.1  402.24
  4890.7  400.06  4901.2  399.78  4932.8  396.17  4953.9  395.37  4985.5  395.56
  4990.4  395.15  4993.2  394.65  4996.4  395.15  4999.1  395.15  5003.6  395.72
  5009.6  395.78  5018.6  395.35  5032.1  395.42  5039.6  396.24  5060.7  397.16
  5068.2  398.30  5075.7  398.71  5090.7  400.95  5096.7  401.23  5126.8  404.56
  5140.3  405.25  5147.8  405.96  5162.8  406.30  5168.8  406.93  5176.3  407.12
#Mann=3,-1,0
  4838.0    0.05       0  4990.4    0.03       0  4996.4    0.05       0
Bank Sta=4990.4,4996.4
Exp/Cntr=0.3,0.1

Type RM Length L Ch R = 1,3258,52,52,52
BEGIN DESCRIPTION:
Mapping XS 7fa73c8f
END DESCRIPTION:
XS GIS Cut Line= 2
      3737599.07     10664577.29      3736987.08     10664798.65
#Sta/Elev= 30
  4763.7  405.42  4784.6  405.78  4844.3  403.98  4849.6  403.33  4858.8  400.44
  4869.5  400.44  4891.3  398.68  4900.3  395.76  4912.0  395.53  5053.5  396.05
  5089.8  395.51  5092.5  395.01  5095.8  395.51  5109.5  395.67  5114.8  397.16
  5124.7  397.79  5134.9  400.00  5140.2  399.87  5156.6  402.50  5170.8  403.35
  5177.9  404.67  5188.5  405.07  5257.5  404.12  5282.8  402.52  5288.1  403.21
  5305.5  402.16  5313.5  401.03  5318.8  401.57  5337.4  400.65  5414.5  404.17
#Mann=5,-1,0
  4763.7    0.05       0  4784.6    0.08       0  4891.3    0.05       0
  5089.8    0.03       0  5095.8    0.05       0
Bank Sta=5089.8,5095.8
Exp/Cntr=0.3,0.1

Type RM Length L Ch R = 1,3206,51,51,51
BEGIN DESCRIPTION:
UNT 144 IN BOCR 5.0
END DESCRIPTION:
XS GIS Cut Line= 2
      3737588.66     10664527.81      3736968.80     10664749.18
#Sta/Elev= 30
  4764.8  404.63  4838.1  404.61  4844.8  402.32  4901.1  398.96  4909.5  395.53
  4912.2  395.03  4915.5  395.53  4923.1  398.40  4937.2  397.56  4993.5  399.04
  4998.8  397.92  5018.6  399.14  5029.6  396.73  5049.8  398.52  5055.1  395.70
  5080.6  397.66  5085.9  395.64  5103.6  395.88  5111.3  397.60  5124.8  396.14
  5142.1  399.94  5172.9  403.51  5203.7  404.94  5234.5  404.22  5260.0  400.89
  5265.3  401.78  5316.0  398.81  5337.2  398.88  5347.1  400.50  5423.0  400.08
#Mann=3,-1,0
  4764.8    0.05       0  4909.5    0.03       0  4915.5    0.05       0
Bank Sta=4909.5,4915.5
Exp/Cntr=0.3,0.1

Type RM Length L Ch R = 1,3155,199,199,199
BEGIN DESCRIPTION:
Mapping XS 27791d46
END DESCRIPTION:
XS GIS Cut Line= 2
      3737549.53     10664483.56      3736950.57     10664712.73
#Sta/Elev= 30
  4793.1  403.43  4835.8  404.38  4868.0  400.65  4877.5  400.88  4882.8  399.95
  4889.4  397.25  4900.1  396.27  4907.5  394.46  4912.9  395.10  4921.5  394.44
  5044.1  394.43  5046.8  393.93  5050.1  394.43  5077.1  394.52  5082.5  395.68
  5101.8  394.81  5107.2  396.18  5146.3  397.73  5186.6  402.39  5246.7  401.62
  5271.4  398.17  5317.7  395.59  5339.1  398.23  5356.2  398.60  5361.6  396.92
  5371.2  397.93  5380.9  401.72  5386.3  400.03  5392.6  399.85  5434.4  401.07
#Mann=3,-1,0
  4793.1    0.05       0  5044.1    0.03       0  5050.1    0.05       0
Bank Sta=5044.1,5050.1
Exp/Cntr=0.3,0.1

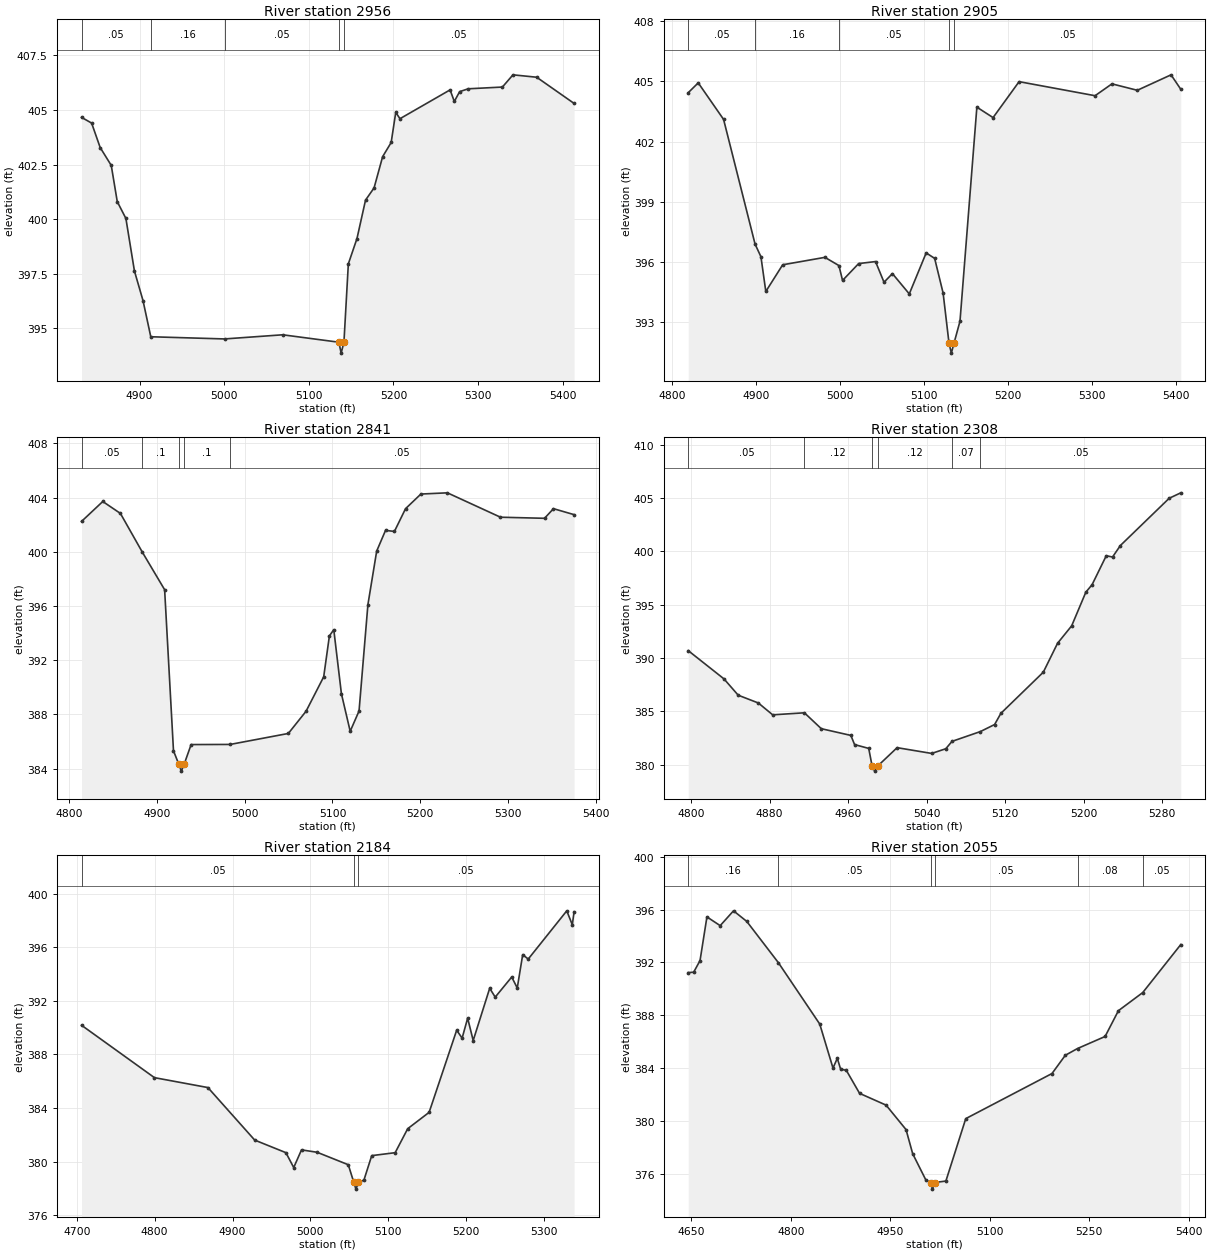
Type RM Length L Ch R = 1,2956,51,51,51
BEGIN DESCRIPTION:
Mapping XS dda357e9
END DESCRIPTION:
XS GIS Cut Line= 2
      3737471.39     10664340.33      3736895.87     10664426.26
#Sta/Elev= 30
  4831.5  404.66  4843.4  404.40  4853.5  403.28  4866.6  402.46  4873.7  400.80
  4883.9  400.03  4894.0  397.62  4904.1  396.27  4913.3  394.61  5000.4  394.51
  5069.2  394.70  5135.5  394.36  5138.2  393.86  5141.5  394.36  5146.7  397.95
  5156.9  399.11  5167.0  400.87  5177.1  401.43  5187.2  402.86  5197.3  403.51
  5202.7  404.89  5207.7  404.60  5266.9  405.92  5271.9  405.39  5278.2  405.84
  5288.3  405.97  5328.7  406.05  5341.2  406.61  5369.2  406.50  5413.4  405.30
#Mann=5,-1,0
  4831.5    0.05       0  4913.3    0.16       0  5000.4    0.05       0
  5135.5    0.07       0  5141.5    0.05       0
Bank Sta=5135.5,5141.5
Exp/Cntr=0.3,0.1

Type RM Length L Ch R = 1,2905,64,64,64
BEGIN DESCRIPTION:
UNT 144 IN BOCR 4.0
END DESCRIPTION:
XS GIS Cut Line= 2
      3737471.44     10664296.05      3736888.08     10664358.55
#Sta/Elev= 30
  4818.9  404.44  4830.8  404.93  4861.0  403.11  4898.5  396.90  4905.5  396.27
  4911.3  394.54  4931.4  395.87  4981.7  396.24  4998.4  395.83  5002.7  395.09
  5021.9  395.93  5042.0  396.03  5052.1  395.00  5062.1  395.43  5082.2  394.42
  5102.3  396.46  5112.4  396.19  5122.5  394.46  5129.5  391.97  5132.3  391.47
  5135.5  391.97  5142.6  393.06  5162.7  403.72  5182.0  403.20  5213.0  404.99
  5303.5  404.29  5323.6  404.88  5353.8  404.56  5394.0  405.33  5405.6  404.61
#Mann=5,-1,0
  4818.9    0.05       0  4898.5    0.16       0  4998.4    0.05       0
  5129.5    0.03       0  5135.5    0.05       0
Bank Sta=5129.5,5135.5
Exp/Cntr=0.3,0.1

Type RM Length L Ch R = 1,2841,533,533,533
BEGIN DESCRIPTION:
Mapping XS a9093c21
END DESCRIPTION:
XS GIS Cut Line= 2
      3737463.60     10664230.95      3736906.30     10664298.66
#Sta/Elev= 30
  4814.0  402.24  4838.2  403.71  4858.3  402.83  4883.3  399.97  4908.7  397.20
  4918.8  385.31  4924.9  384.31  4927.7  383.81  4930.9  384.31  4938.9  385.77
  4983.4  385.78  5049.7  386.59  5069.9  388.23  5090.0  390.77  5096.5  393.79
  5101.5  394.25  5110.2  389.52  5120.2  386.75  5130.3  388.25  5140.4  396.10
  5150.4  400.05  5160.5  401.58  5170.6  401.50  5183.3  403.18  5200.8  404.26
  5231.0  404.35  5291.5  402.55  5341.7  402.47  5351.9  403.18  5375.4  402.74
#Mann=5,-1,0
  4814.0    0.05       0  4883.3     0.1       0  4924.9    0.03       0
  4930.9     0.1       0  4983.4    0.05       0
Bank Sta=4924.9,4930.9
Exp/Cntr=0.3,0.1

Type RM Length L Ch R = 1,2308,124,124,124
BEGIN DESCRIPTION:
Mapping XS 41387edc
END DESCRIPTION:
XS GIS Cut Line= 3
      3737432.38     10664020.01      3737398.52     10663861.15
      3737187.59     10663595.54
#Sta/Elev= 30
  4797.2  390.70  4833.6  388.05  4848.1  386.52  4868.6  385.79  4883.2  384.68
  4915.5  384.87  4932.7  383.38  4962.8  382.75  4966.6  381.89  4981.0  381.53
  4984.4  379.90  4987.1  379.40  4990.4  379.90  5009.9  381.60  5045.1  381.06
  5059.5  381.50  5065.8  382.19  5094.7  383.11  5109.2  383.77  5115.6  384.82
  5158.8  388.68  5173.3  391.39  5187.7  393.03  5202.1  396.18  5208.5  396.89
  5222.9  399.60  5229.3  399.48  5237.3  400.56  5287.0  404.99  5298.8  405.50
#Mann=6,-1,0
  4797.2    0.05       0  4915.5    0.12       0  4984.4    0.07       0
  4990.4    0.12       0  5065.8    0.07       0  5094.7    0.05       0
Bank Sta=4984.4,4990.4
Exp/Cntr=0.3,0.1

Type RM Length L Ch R = 1,2184,129,129,129
BEGIN DESCRIPTION:
UNT 144 IN BOCR 3.0
END DESCRIPTION:
XS GIS Cut Line= 3
      3737440.19     10664012.18      3737414.15     10663592.92
      3737263.86     10663442.64
#Sta/Elev= 30
  4706.1  390.18  4799.7  386.27  4868.4  385.53  4928.5  381.61  4968.6  380.67
  4978.6  379.56  4988.6  380.88  5008.7  380.70  5048.7  379.77  5055.8  378.45
  5058.5  377.95  5061.8  378.45  5068.8  378.63  5078.8  380.45  5108.9  380.67
  5125.0  382.46  5152.5  383.68  5187.9  389.81  5194.9  389.22  5202.0  390.71
  5209.1  389.04  5230.3  392.94  5237.4  392.28  5258.6  393.78  5265.7  392.96
  5272.7  395.45  5279.8  395.12  5329.3  398.72  5336.4  397.68  5338.7  398.65
#Mann=3,-1,0
  4706.1    0.05       0  5055.8    0.04       0  5061.8    0.05       0
Bank Sta=5055.8,5061.8
Exp/Cntr=0.3,0.1

Type RM Length L Ch R = 1,2055,86,86,86
BEGIN DESCRIPTION:
UNT 144 IN BOCR 2.0
END DESCRIPTION:
XS GIS Cut Line= 2
      3737515.71     10663978.37      3737479.25     10663236.17
#Sta/Elev= 30
  4645.1  391.23  4653.3  391.26  4662.9  392.14  4673.3  395.44  4693.3  394.78
  4713.4  395.90  4733.4  395.10  4781.1  391.98  4843.5  387.34  4863.5  384.01
  4870.0  384.75  4875.0  383.93  4883.6  383.84  4903.6  382.10  4943.6  381.21
  4973.7  379.36  4983.7  377.54  5003.7  375.54  5010.7  375.36  5013.5  374.86
  5016.7  375.36  5033.8  375.47  5063.8  380.19  5193.9  383.60  5214.0  384.98
  5232.4  385.49  5274.0  386.40  5294.1  388.35  5330.8  389.72  5388.2  393.35
#Mann=6,-1,0
  4645.1    0.16       0  4781.1    0.05       0  5010.7    0.04       0
  5016.7    0.05       0  5232.4    0.08       0  5330.8    0.05       0
Bank Sta=5010.7,5016.7
Exp/Cntr=0.3,0.1

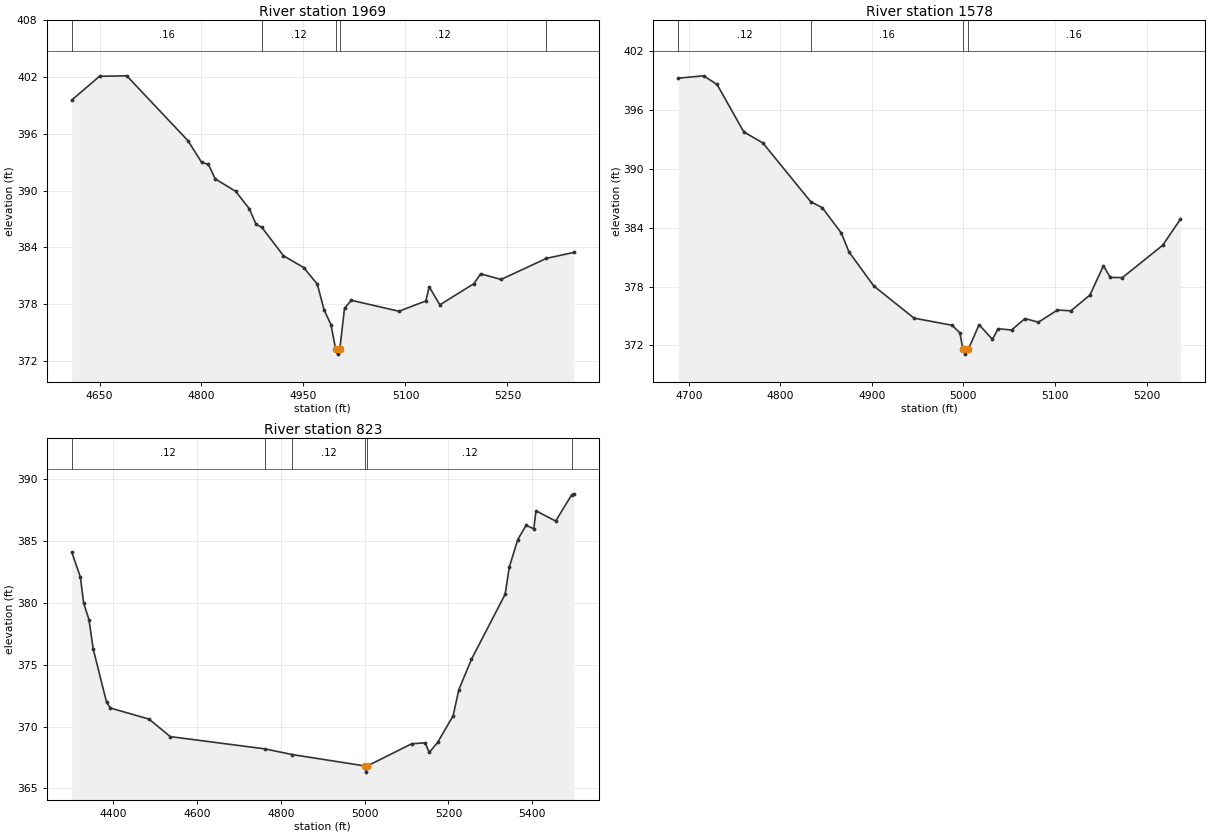
Type RM Length L Ch R = 1,1969,391,391,391
BEGIN DESCRIPTION:
Mapping XS 03641da2
END DESCRIPTION:
XS GIS Cut Line= 2
      3737588.63     10663980.97      3737554.86     10663243.25
#Sta/Elev= 30
  4609.2  399.57  4650.0  402.08  4690.1  402.13  4780.2  395.27  4800.2  392.98
  4810.2  392.77  4820.2  391.24  4850.2  389.93  4870.3  388.09  4880.3  386.43
  4888.8  386.12  4920.5  383.12  4950.3  381.87  4970.4  380.11  4980.4  377.38
  4990.4  375.85  4997.4  373.22  5000.1  372.72  5003.4  373.22  5010.4  377.57
  5020.4  378.41  5090.5  377.25  5130.0  378.34  5135.0  379.83  5150.6  377.93
  5200.6  380.16  5210.6  381.21  5240.6  380.61  5307.4  382.84  5347.7  383.47
#Mann=5,-1,0
  4609.2    0.16       0  4888.8    0.12       0  4997.4    0.07       0
  5003.4    0.12       0  5307.4    0.16       0
Bank Sta=4997.4,5003.4
Exp/Cntr=0.3,0.1

Type RM Length L Ch R = 1,1578,755,755,755
BEGIN DESCRIPTION:
Mapping XS f6a389ee
END DESCRIPTION:
XS GIS Cut Line= 2
      3737968.86     10663530.45      3737643.99     10663088.64
#Sta/Elev= 30
  4688.5  399.26  4716.2  399.50  4730.9  398.62  4760.1  393.78  4781.0  392.65
  4833.2  386.66  4845.8  386.05  4866.6  383.47  4875.0  381.54  4902.1  378.06
  4946.1  374.78  4987.8  374.05  4996.2  373.27  4999.4  371.61  5002.2  371.11
  5005.4  371.61  5017.1  374.11  5031.7  372.62  5037.9  373.70  5052.6  373.57
  5067.2  374.74  5081.9  374.37  5102.7  375.61  5117.4  375.53  5138.2  377.14
  5152.9  380.12  5160.5  378.93  5173.7  378.92  5217.7  382.22  5236.9  384.86
#Mann=4,-1,0
  4688.5    0.12       0  4833.2    0.16       0  4999.4    0.07       0
  5005.4    0.16       0
Bank Sta=4999.4,5005.4
Exp/Cntr=0.3,0.1

Type RM Length L Ch R = 1,823,0,0,0
BEGIN DESCRIPTION:
UNT 144 IN BOCR 1.0
END DESCRIPTION:
XS GIS Cut Line= 3
      3738078.22     10663340.29      3738200.60     10662762.19
      3737596.43     10662824.70
#Sta/Elev= 30
  4301.0  384.09  4321.5  382.09  4329.3  379.99  4342.0  378.65  4352.2  376.27
  4384.1  371.96  4393.1  371.50  4485.1  370.61  4536.2  369.19  4761.5  368.20
  4827.2  367.74  5000.5  366.82  5003.2  366.32  5006.5  366.82  5112.2  368.61
  5144.2  368.69  5154.3  367.91  5174.4  368.73  5211.1  370.87  5224.7  372.97
  5254.8  375.43  5335.3  380.69  5345.3  382.89  5365.4  385.11  5385.5  386.27
  5403.8  385.98  5408.8  387.44  5455.9  386.61  5494.3  388.74  5499.3  388.81
#Mann=6,-1,0
  4301.0    0.12       0  4761.5    0.16       0  4827.2    0.12       0
  5000.5    0.07       0  5006.5    0.12       0  5494.3    0.16       0
Bank Sta=5000.5,5006.5
Exp/Cntr=0.3,0.1

Chan Stop Cuts=-1