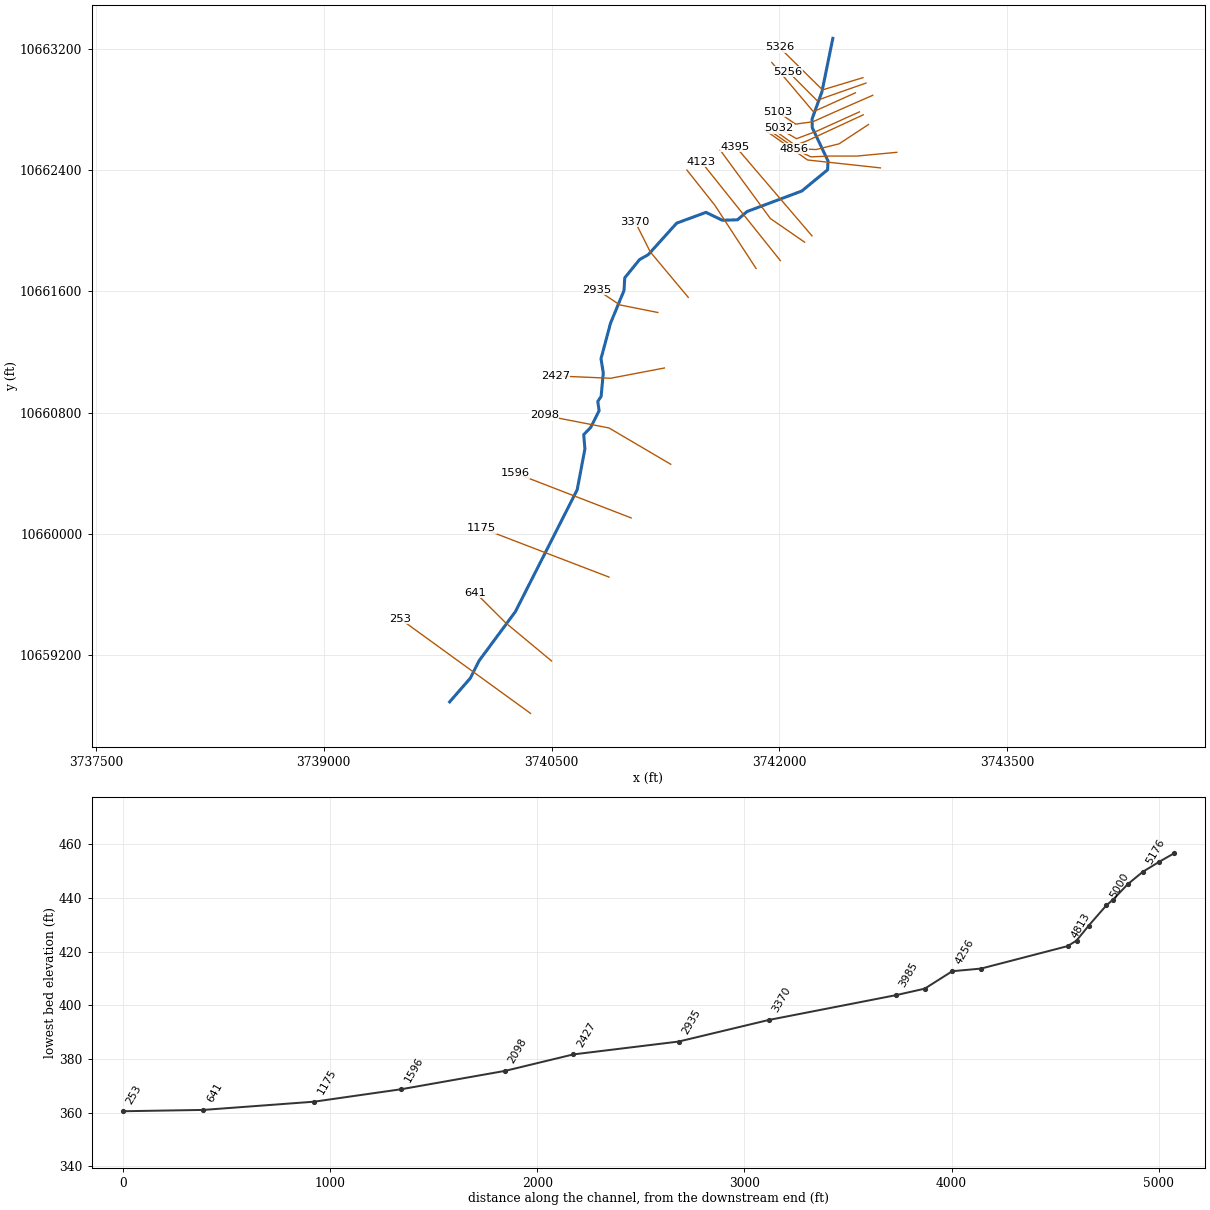
--- UNT 147 IN BOCR.prj (project) ---

Proj Title=UNT 147 IN BOCR Base Level Engineering
Current Plan=p01
Default Exp/Contr=0.3,0.1
English Units
Geom File=g01
Flow File=f01
Plan File=p01
BEGIN DESCRIPTION:
UNT 147 IN BOCR
END DESCRIPTION:

--- UNT 147 IN BOCR.p01 (plan) ---

Plan Title=Multiple Run
Short Identifier=Multiple
Geom File=g01
Flow File=f01
Subcritical Flow
K Sum by GR= 0
Std Step Tol= 0.01
Critical Tol= 0.01
Num of Std Step Trials= 20
Max Error Tol= 0.3
Flow Tol Ratio= 0.001
Split Flow NTrial= 30
Split Flow Tol= 0.02
Split Flow Ratio= 0.02
Log Output Level= 0
Friction Slope Method= 1
Unsteady Friction Slope Method= 2
Unsteady Bridges Friction Slope Method= 1
Parabolic Critical Depth
Global Vel Dist=  1 , 1 , 1
Global Log Level= 0
CheckData=True
Encroach Param= -1, 0, 0, 0
BEGIN DESCRIPTION:
Multiple Run
END DESCRIPTION:

--- UNT 147 IN BOCR.f01 (steady flow) ---

Flow Title=Multiple
Number of Profiles=7
Profile Names=10-year,25-year,50-year,1pct_min,100-year,1pct_plu,500-year
River Rch & RM= UNT 147 IN BOCR,Reach-1,5326
     514     700     856     772    1044    1411    1554
Boundary for River Rch & Prof#=UNT 147 IN BOCR,Reach-1,1
Up Type=0
Dn Type=3
Dn Slope=0.005
Boundary for River Rch & Prof#=UNT 147 IN BOCR,Reach-1,2
Up Type=0
Dn Type=3
Dn Slope=0.005
Boundary for River Rch & Prof#=UNT 147 IN BOCR,Reach-1,3
Up Type=0
Dn Type=3
Dn Slope=0.005
Boundary for River Rch & Prof#=UNT 147 IN BOCR,Reach-1,4
Up Type=0
Dn Type=3
Dn Slope=0.005
Boundary for River Rch & Prof#=UNT 147 IN BOCR,Reach-1,5
Up Type=0
Dn Type=3
Dn Slope=0.005
Boundary for River Rch & Prof#=UNT 147 IN BOCR,Reach-1,6
Up Type=0
Dn Type=3
Dn Slope=0.005
Boundary for River Rch & Prof#=UNT 147 IN BOCR,Reach-1,7
Up Type=0
Dn Type=3
Dn Slope=0.005

--- UNT 147 IN BOCR.g01 (geometry) ---

Geom Title=Existing Conditions

River Reach=UNT 147 IN BOCR,Reach-1
Reach XY= 30
      3742351.37     10663269.86      3742279.25     10662916.00
      3742214.75     10662738.00      3742216.00     10662680.00
      3742319.75     10662460.00      3742316.75     10662402.00
      3742147.00     10662262.00      3741787.11     10662126.73
      3741724.00     10662072.00      3741624.00     10662069.00
      3741516.50     10662121.00      3741323.50     10662050.00
      3741136.38     10661841.83      3741079.31     10661809.51
      3740981.75     10661689.00      3740977.00     10661606.00
      3740888.00     10661389.00      3740825.50     10661155.00
      3740840.50     10661061.00      3740826.25     10660906.00
      3740804.50     10660874.00      3740812.75     10660811.00
      3740757.25     10660701.00      3740711.75     10660654.00
      3740719.50     10660560.00      3740668.75     10660290.00
      3740261.75     10659485.00      3740022.75     10659161.00
      3739965.75     10659047.00      3739829.50     10658890.00

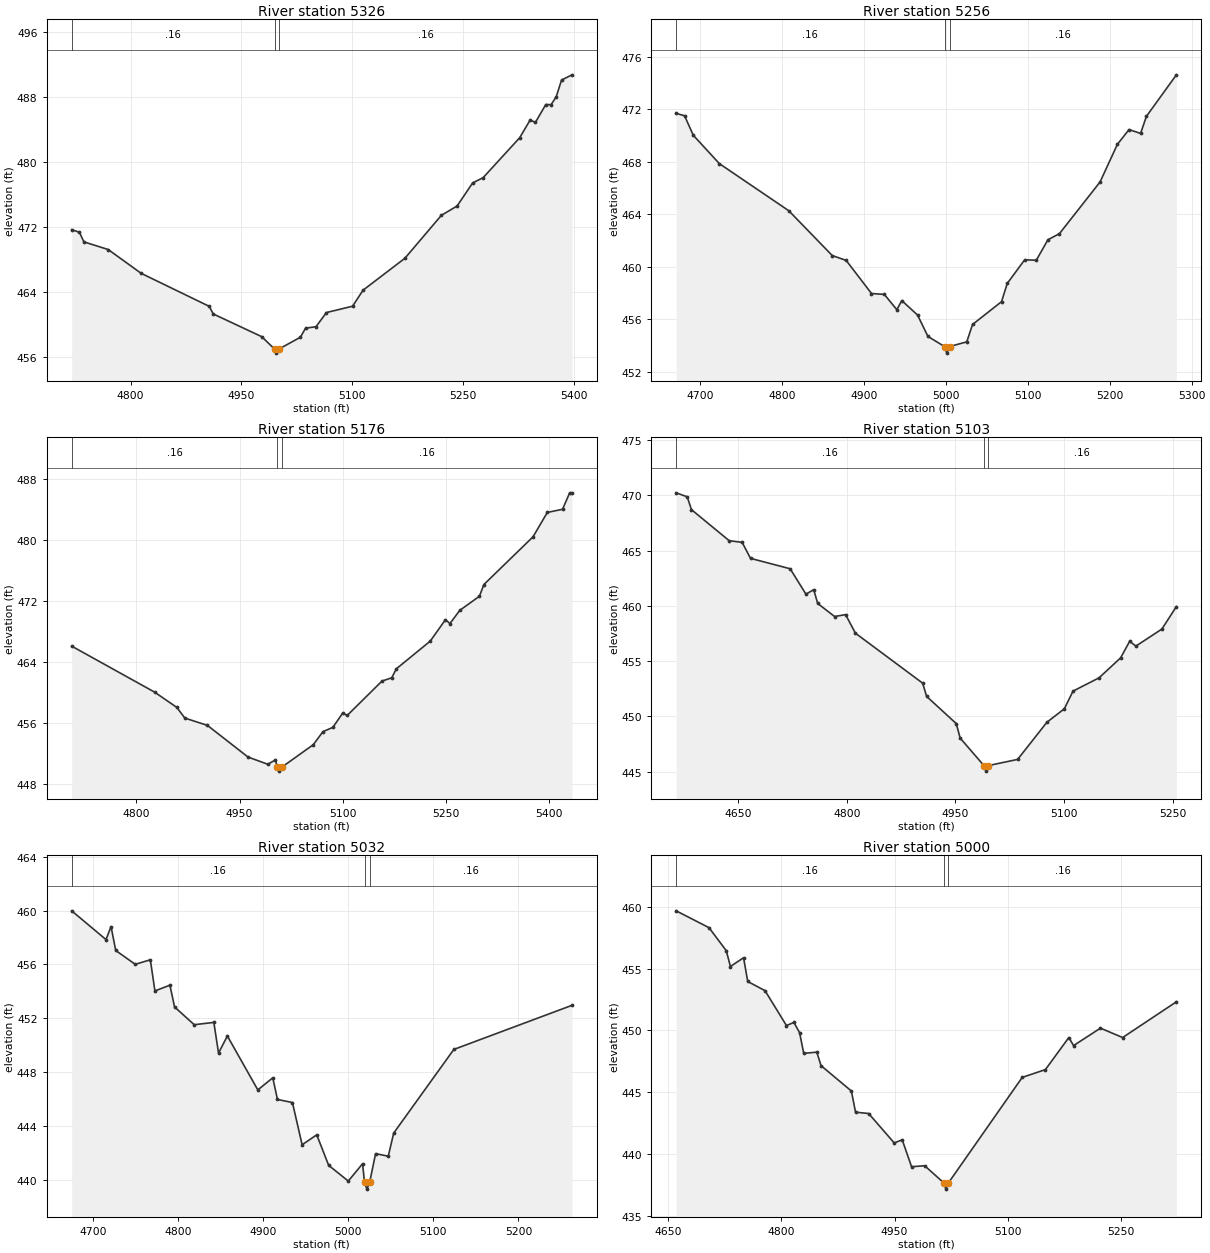
Type RM Length L Ch R = 1,5326,70,70,70
BEGIN DESCRIPTION:
UNT 147 IN BOCR 13.0
END DESCRIPTION:
XS GIS Cut Line= 3
      3742549.64     10663010.20      3742283.37     10662929.56
      3741999.61     10663210.19
#Sta/Elev= 30
  4720.2  471.69  4730.7  471.37  4736.7  470.19  4769.6  469.25  4814.3  466.32
  4906.5  462.26  4911.8  461.33  4977.6  458.53  4994.8  457.01  4997.5  456.51
  5000.8  457.01  5029.8  458.46  5036.9  459.58  5051.0  459.76  5065.1  461.50
  5100.5  462.28  5114.7  464.25  5171.3  468.17  5220.7  473.45  5242.0  474.60
  5263.1  477.44  5277.3  478.09  5326.8  483.00  5341.0  485.19  5348.0  484.87
  5362.1  487.08  5369.3  487.06  5376.3  488.05  5383.4  490.08  5397.5  490.73
#Mann=3,-1,0
  4720.2    0.16       0  4994.8    0.07       0  5000.8    0.16       0
Bank Sta=4994.8,5000.8
Exp/Cntr=0.3,0.1

Type RM Length L Ch R = 1,5256,80,80,80
BEGIN DESCRIPTION:
Mapping XS d724b7b0
END DESCRIPTION:
XS GIS Cut Line= 4
      3742569.29     10662974.52      3742321.93     10662887.30
      3742246.41     10662859.95      3742057.63     10663050.03
#Sta/Elev= 30
  4670.9  471.69  4681.2  471.50  4691.8  470.02  4723.6  467.86  4808.4  464.27
  4861.4  460.86  4878.4  460.49  4909.3  457.97  4925.0  457.90  4940.2  456.74
  4946.3  457.43  4965.5  456.33  4978.2  454.70  4998.5  453.93  5001.2  453.43
  5004.5  453.93  5025.6  454.29  5032.6  455.61  5068.0  457.35  5075.0  458.74
  5096.3  460.54  5110.4  460.50  5124.6  462.06  5138.7  462.53  5188.2  466.46
  5209.4  469.33  5223.6  470.45  5237.7  470.16  5244.8  471.46  5281.4  474.62
#Mann=3,-1,0
  4670.9    0.16       0  4998.5    0.07       0  5004.5    0.16       0
Bank Sta=4998.5,5004.5
Exp/Cntr=0.3,0.1

Type RM Length L Ch R = 1,5176,73,73,73
BEGIN DESCRIPTION:
UNT 147 IN BOCR 12.0
END DESCRIPTION:
XS GIS Cut Line= 3
      3742499.64     10662910.20      3742223.43     10662785.50
      3741949.60     10663110.20
#Sta/Elev= 30
  4705.7  466.07  4826.4  460.03  4858.8  458.02  4870.3  456.63  4903.2  455.67
  4962.2  451.52  4991.0  450.57  5002.0  451.13  5005.1  450.17  5007.9  449.67
  5011.1  450.17  5057.1  453.13  5071.4  454.86  5085.7  455.41  5100.0  457.29
  5106.5  456.97  5157.1  461.48  5171.4  461.92  5178.0  463.09  5227.4  466.73
  5249.5  469.54  5256.0  469.03  5270.3  470.76  5298.9  472.61  5305.4  474.15
  5376.9  480.41  5397.7  483.61  5419.8  484.02  5430.2  486.18  5433.5  486.18
#Mann=3,-1,0
  4705.7    0.16       0  5005.1    0.07       0  5011.1    0.16       0
Bank Sta=5005.1,5011.1
Exp/Cntr=0.3,0.1

Type RM Length L Ch R = 1,5103,71,71,71
BEGIN DESCRIPTION:
Mapping XS 1c117176
END DESCRIPTION:
XS GIS Cut Line= 5
      3742613.64     10662893.82      3742362.30     10662783.13
      3742220.37     10662719.33      3742105.79     10662703.70
      3741986.39     10662785.46
#Sta/Elev= 30
  4564.5  470.22  4579.8  469.86  4585.6  468.70  4637.7  465.89  4655.6  465.74
  4667.2  464.29  4721.9  463.35  4743.7  461.05  4754.4  461.46  4759.9  460.21
  4783.2  459.03  4798.4  459.20  4812.0  457.52  4904.8  453.00  4910.3  451.80
  4951.2  449.34  4956.6  448.03  4989.4  445.54  4992.2  445.04  4995.4  445.54
  5035.9  446.10  5076.3  449.46  5100.4  450.68  5112.4  452.28  5148.3  453.48
  5178.1  455.29  5190.6  456.79  5199.1  456.35  5235.0  457.89  5255.1  459.93
#Mann=3,-1,0
  4564.5    0.16       0  4989.4    0.07       0  4995.4    0.16       0
Bank Sta=4989.4,4995.4
Exp/Cntr=0.3,0.1

Type RM Length L Ch R = 1,5032,32,32,32
BEGIN DESCRIPTION:
Mapping XS 951b7212
END DESCRIPTION:
XS GIS Cut Line= 4
      3742526.40     10662784.45      3742247.72     10662658.13
      3742112.30     10662607.35      3741993.55     10662677.05
#Sta/Elev= 30
  4674.6  459.99  4715.0  457.85  4720.9  458.82  4726.4  457.04  4749.4  456.01
  4767.1  456.35  4772.5  454.03  4790.1  454.46  4795.6  452.84  4818.7  451.52
  4841.8  451.69  4847.3  449.41  4857.7  450.68  4893.5  446.67  4911.1  447.57
  4916.6  445.96  4934.2  445.73  4945.6  442.59  4962.8  443.33  4976.8  441.06
  4999.9  439.89  5016.7  441.18  5019.0  439.79  5021.8  439.29  5025.0  439.79
  5032.0  441.93  5046.9  441.74  5053.3  443.46  5124.0  449.68  5262.9  452.96
#Mann=3,-1,0
  4674.6    0.16       0  5019.0    0.07       0  5025.0    0.16       0
Bank Sta=5019,5025
Exp/Cntr=0.3,0.1

Type RM Length L Ch R = 1,5000,85,85,85
BEGIN DESCRIPTION:
Mapping XS 7b584cd7
END DESCRIPTION:
XS GIS Cut Line= 5
      3742551.10     10662764.90      3742310.22     10662652.92
      3742178.71     10662591.72      3742103.18     10662564.38
      3741964.08     10662664.85
#Sta/Elev= 30
  4660.7  459.67  4704.2  458.31  4727.1  456.45  4732.6  455.17  4750.0  455.88
  4755.5  453.96  4778.4  453.22  4806.8  450.40  4816.7  450.65  4824.2  449.82
  4829.7  448.15  4847.0  448.25  4852.6  447.16  4892.8  445.11  4898.3  443.40
  4915.7  443.29  4949.6  440.91  4960.1  441.17  4972.5  438.99  4989.9  439.07
  5015.3  437.68  5018.0  437.18  5021.3  437.68  5119.1  446.21  5149.8  446.84
  5180.8  449.43  5187.1  448.78  5222.7  450.19  5252.1  449.43  5323.3  452.32
#Mann=3,-1,0
  4660.7    0.16       0  5015.3    0.07       0  5021.3    0.16       0
Bank Sta=5015.3,5021.3
Exp/Cntr=0.3,0.1

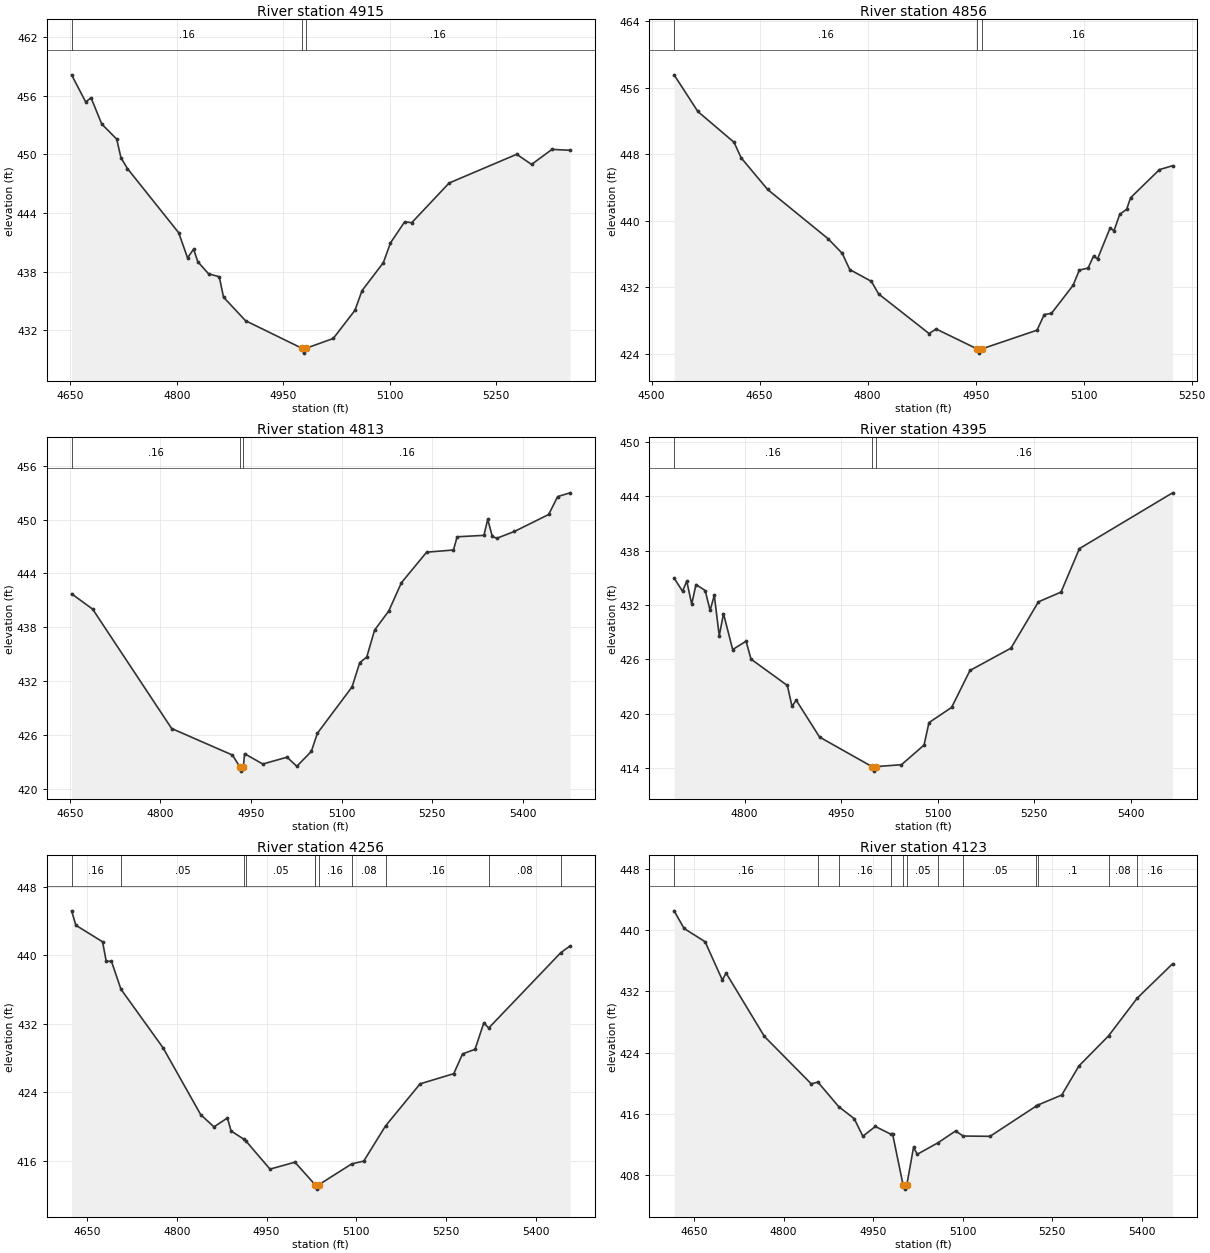
Type RM Length L Ch R = 1,4915,59,59,59
BEGIN DESCRIPTION:
Mapping XS d26cc418
END DESCRIPTION:
XS GIS Cut Line= 5
      3742586.25     10662701.09      3742392.25     10662573.49
      3742241.21     10662535.73      3742107.09     10662542.24
      3741958.62     10662645.13
#Sta/Elev= 30
  4651.6  458.14  4671.5  455.36  4679.0  455.80  4694.1  453.11  4715.2  451.56
  4721.2  449.66  4730.3  448.55  4802.6  441.98  4815.1  439.41  4823.6  440.30
  4829.6  439.01  4844.7  437.78  4859.8  437.47  4865.8  435.39  4896.8  432.98
  4976.3  430.16  4979.0  429.66  4982.3  430.16  5020.5  431.16  5051.1  434.04
  5061.1  436.06  5091.1  438.91  5101.2  440.94  5121.2  443.10  5131.2  443.01
  5183.9  447.07  5279.2  450.01  5300.1  448.97  5328.9  450.51  5354.4  450.42
#Mann=3,-1,0
  4651.6    0.16       0  4976.3    0.07       0  4982.3    0.16       0
Bank Sta=4976.3,4982.3
Exp/Cntr=0.3,0.1

Type RM Length L Ch R = 1,4856,43,43,43
BEGIN DESCRIPTION:
Mapping XS dcb84977
END DESCRIPTION:
XS GIS Cut Line= 5
      3742772.42     10662517.50      3742509.43     10662492.76
      3742329.75     10662492.76      3742207.35     10662487.56
      3742093.03     10662540.22
#Sta/Elev= 30
  4531.2  457.55  4564.2  453.14  4614.4  449.44  4624.4  447.56  4661.1  443.76
  4744.9  437.85  4764.7  436.08  4775.1  434.13  4805.2  432.71  4815.2  431.20
  4885.2  426.44  4895.2  426.98  4952.2  424.58  4954.9  424.08  4958.2  424.58
  5035.2  426.84  5045.2  428.72  5055.2  428.86  5085.3  432.24  5093.9  434.07
  5106.1  434.31  5113.7  435.76  5119.2  435.41  5136.6  439.12  5142.1  438.80
  5150.1  440.79  5159.6  441.37  5165.1  442.77  5205.2  446.15  5223.4  446.62
#Mann=3,-1,0
  4531.2    0.16       0  4952.2    0.07       0  4958.2    0.16       0
Bank Sta=4952.2,4958.2
Exp/Cntr=0.3,0.1

Type RM Length L Ch R = 1,4813,418,418,418
BEGIN DESCRIPTION:
UNT 147 IN BOCR 11.0
END DESCRIPTION:
XS GIS Cut Line= 3
      3742664.32     10662414.76      3742185.19     10662466.84
      3741904.23     10662664.55
#Sta/Elev= 30
  4653.0  441.74  4687.9  440.03  4818.7  426.75  4919.3  423.80  4931.5  422.51
  4934.2  422.01  4937.5  422.51  4939.5  423.95  4969.6  422.80  5009.8  423.56
  5026.0  422.55  5050.0  424.20  5060.1  426.23  5117.5  431.38  5130.2  434.08
  5141.8  434.70  5154.8  437.70  5178.3  439.83  5199.2  442.97  5241.0  446.37
  5285.4  446.61  5291.5  448.08  5335.9  448.24  5342.1  450.02  5349.6  448.15
  5356.9  447.91  5386.3  448.67  5443.1  450.56  5457.9  452.55  5478.5  452.97
#Mann=3,-1,0
  4653.0    0.16       0  4931.5    0.07       0  4937.5    0.16       0
Bank Sta=4931.5,4937.5
Exp/Cntr=0.3,0.1

Type RM Length L Ch R = 1,4395,139,139,139
BEGIN DESCRIPTION:
Mapping XS ba7a5d8b
END DESCRIPTION:
XS GIS Cut Line= 2
      3742213.98     10661966.18      3741711.04     10662555.83
#Sta/Elev= 30
  4690.4  434.98  4703.5  433.52  4710.1  434.64  4717.8  432.09  4724.4  434.26
  4738.7  433.60  4746.4  431.40  4752.9  433.07  4760.6  428.60  4767.2  431.04
  4781.5  427.08  4802.3  428.00  4810.0  426.02  4866.5  423.11  4873.7  420.81
  4880.3  421.48  4916.6  417.41  4998.1  414.15  5000.8  413.65  5004.1  414.15
  5043.9  414.36  5079.0  416.53  5086.7  419.01  5121.9  420.69  5150.4  424.77
  5214.1  427.23  5256.9  432.35  5292.0  433.43  5320.6  438.23  5465.4  444.39
#Mann=3,-1,0
  4690.4    0.16       0  4998.1    0.07       0  5004.1    0.16       0
Bank Sta=4998.1,5004.1
Exp/Cntr=0.3,0.1

Type RM Length L Ch R = 1,4256,133,133,133
BEGIN DESCRIPTION:
UNT 147 IN BOCR 10.0
END DESCRIPTION:
XS GIS Cut Line= 3
      3742165.41     10661924.47      3741939.70     10662080.73
      3741609.84     10662532.13
#Sta/Elev= 30
  4623.9  445.21  4631.1  443.52  4675.7  441.59  4681.8  439.32  4690.6  439.30
  4706.4  436.05  4776.9  429.19  4839.9  421.37  4862.0  419.95  4884.5  420.99
  4890.6  419.47  4912.6  418.48  4915.3  418.31  4955.7  415.01  4997.4  415.82
  5030.7  413.22  5031.0  413.17  5033.7  412.67  5037.0  413.17  5092.3  415.62
  5112.5  415.95  5148.9  420.06  5206.7  424.98  5263.0  426.17  5277.7  428.48
  5298.6  429.02  5313.2  432.10  5321.5  431.51  5442.0  440.32  5457.5  441.10
#Mann=11,-1,0
  4623.9    0.16       0  4706.4    0.05       0  4912.6    0.16       0
  4915.3    0.05       0  5030.7    0.16       0  5031.0    0.04       0
  5037.0    0.16       0  5092.3    0.08       0  5148.9    0.16       0
  5321.5    0.08       0  5442.0    0.16       0
Bank Sta=5031,5037
Exp/Cntr=0.3,0.1

Type RM Length L Ch R = 1,4123,138,138,138
BEGIN DESCRIPTION:
UNT 147 IN BOCR 9.0
END DESCRIPTION:
XS GIS Cut Line= 2
      3742005.68     10661802.95      3741485.03     10662455.50
#Sta/Elev= 30
  4616.6  442.54  4633.3  440.24  4668.5  438.50  4697.4  433.50  4703.7  434.40
  4767.8  426.13  4846.3  419.93  4857.4  420.16  4892.3  416.95  4918.3  415.38
  4932.7  413.08  4953.6  414.36  4979.1  413.37  4982.4  413.43  5000.2  406.67
  5002.9  406.17  5006.2  406.67  5017.6  411.62  5024.0  410.73  5059.0  412.25
  5088.0  413.77  5100.8  413.11  5145.7  413.07  5222.5  417.00  5225.6  417.15
  5265.8  418.47  5294.6  422.27  5344.2  426.20  5392.3  431.14  5451.4  435.62
#Mann=12,-1,0
  4616.6    0.16       0  4857.4    0.05       0  4892.3    0.16       0
  4979.1    0.05       0  5000.2    0.04       0  5006.2    0.05       0
  5059.0    0.16       0  5100.8    0.05       0  5222.5    0.08       0
  5225.6     0.1       0  5344.2    0.08       0  5392.3    0.16       0
Bank Sta=5000.2,5006.2
Exp/Cntr=0.3,0.1

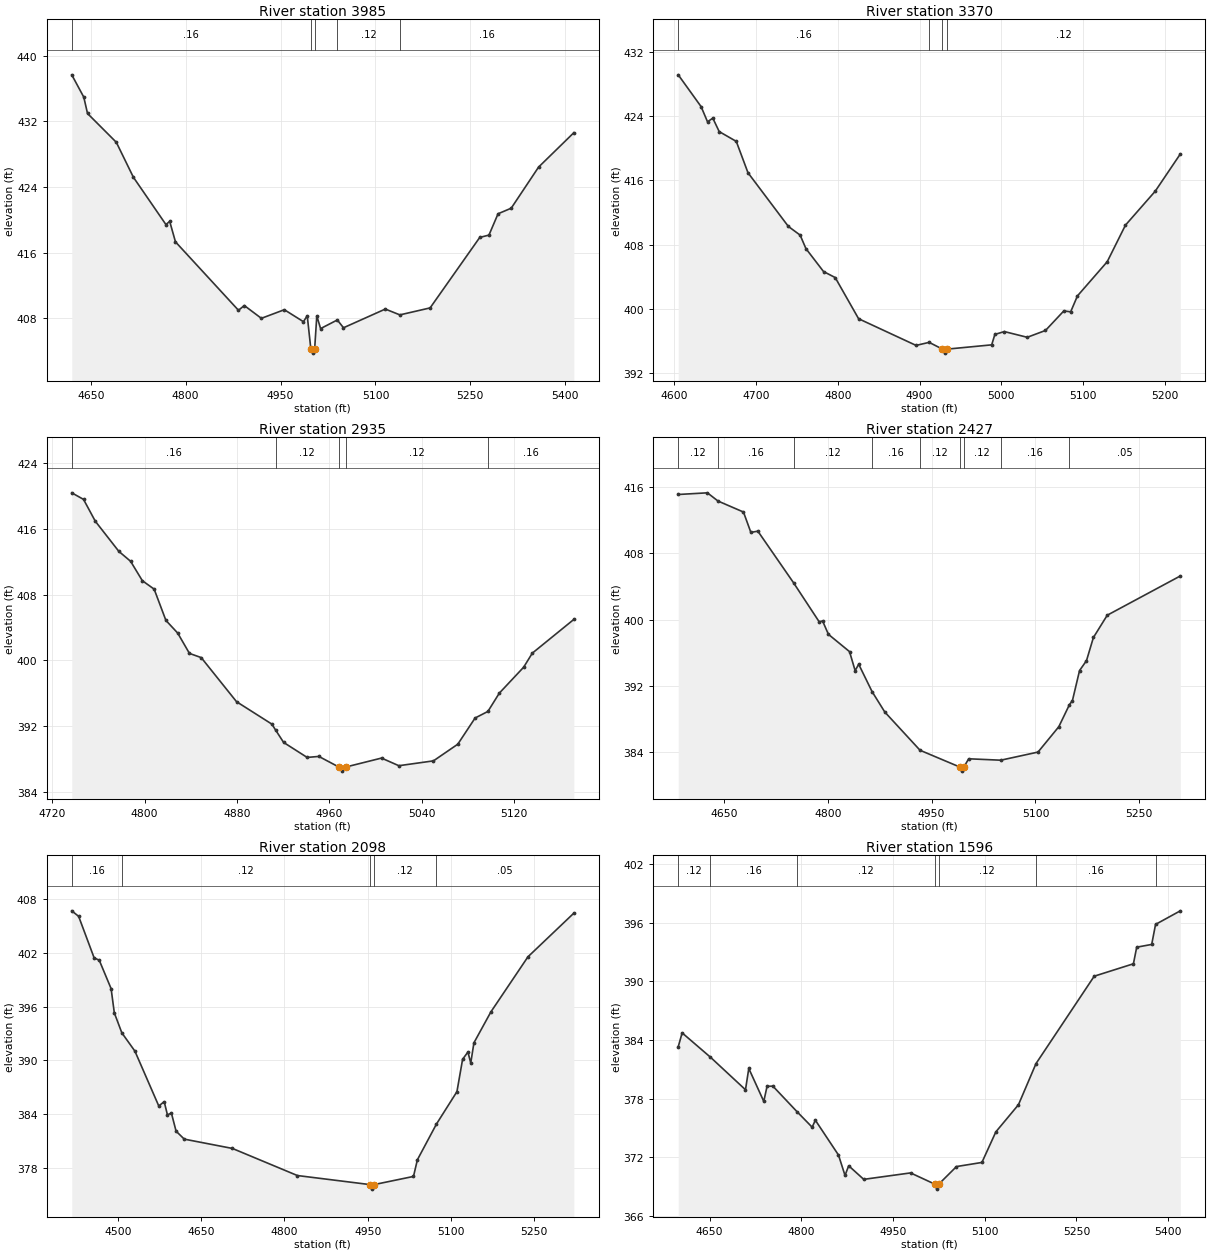
Type RM Length L Ch R = 1,3985,615,615,615
BEGIN DESCRIPTION:
Mapping XS ea2ec72d
END DESCRIPTION:
XS GIS Cut Line= 3
      3741845.97     10661750.84      3741575.12     10662167.54
      3741391.10     10662400.16
#Sta/Elev= 30
  4620.0  437.68  4639.0  434.96  4644.9  432.97  4690.4  429.46  4717.4  425.20
  4768.8  419.44  4774.8  419.82  4783.9  417.33  4883.5  408.99  4892.7  409.57
  4919.7  408.01  4956.0  409.06  4986.2  407.60  4992.2  408.33  4997.9  404.27
  5000.6  403.77  5003.9  404.27  5007.3  408.31  5013.3  406.76  5039.7  407.81
  5049.5  406.86  5115.6  409.14  5138.6  408.43  5186.4  409.28  5264.9  417.87
  5279.4  418.15  5293.8  420.75  5314.6  421.43  5357.9  426.44  5413.6  430.63
#Mann=5,-1,0
  4620.0    0.16       0  4997.9    0.07       0  5003.9    0.16       0
  5039.7    0.12       0  5138.6    0.16       0
Bank Sta=4997.9,5003.9
Exp/Cntr=0.3,0.1

Type RM Length L Ch R = 1,3370,435,435,435
BEGIN DESCRIPTION:
UNT 147 IN BOCR 8.0
END DESCRIPTION:
XS GIS Cut Line= 3
      3741399.61     10661560.18      3741149.61     10661860.19
      3741049.62     10662060.16
#Sta/Elev= 30
  4604.9  429.14  4632.9  425.18  4640.7  423.30  4647.2  423.75  4655.0  422.08
  4675.9  420.86  4690.2  416.96  4739.6  410.28  4754.0  409.20  4761.1  407.52
  4782.6  404.67  4796.9  403.92  4825.5  398.80  4895.8  395.48  4911.8  395.86
  4928.0  395.02  4930.7  394.52  4934.0  395.02  4988.3  395.55  4992.2  396.85
  5003.8  397.20  5031.8  396.49  5054.1  397.34  5076.5  399.77  5084.9  399.66
  5093.2  401.64  5129.6  405.89  5151.9  410.44  5188.3  414.66  5219.0  419.29
#Mann=4,-1,0
  4604.9    0.16       0  4911.8    0.12       0  4928.0    0.07       0
  4934.0    0.12       0
Bank Sta=4928,4934
Exp/Cntr=0.3,0.1

Type RM Length L Ch R = 1,2935,508,508,508
BEGIN DESCRIPTION:
UNT 147 IN BOCR 7.0
END DESCRIPTION:
XS GIS Cut Line= 3
      3741199.60     10661460.19      3740949.61     10661510.19
      3740799.63     10661610.18
#Sta/Elev= 30
  4736.8  420.39  4747.0  419.59  4757.2  416.93  4777.6  413.26  4787.8  412.05
  4798.0  409.68  4808.2  408.66  4818.4  404.85  4828.6  403.31  4838.8  400.83
  4849.0  400.32  4879.6  394.95  4910.2  392.22  4913.7  391.45  4920.4  389.99
  4940.8  388.16  4951.0  388.28  4968.3  386.99  4971.1  386.49  4974.3  386.99
  5005.3  388.08  5020.3  387.15  5050.3  387.74  5071.4  389.77  5086.4  392.96
  5097.5  393.76  5107.4  395.99  5128.5  399.15  5136.0  400.86  5172.0  404.97
#Mann=5,-1,0
  4736.8    0.16       0  4913.7    0.12       0  4968.3    0.07       0
  4974.3    0.12       0  5097.5    0.16       0
Bank Sta=4968.3,4974.3
Exp/Cntr=0.3,0.1

Type RM Length L Ch R = 1,2427,329,329,329
BEGIN DESCRIPTION:
UNT 147 IN BOCR 6.0
END DESCRIPTION:
XS GIS Cut Line= 3
      3741242.60     10661093.74      3740888.48     10661026.05
      3740524.25     10661041.66
#Sta/Elev= 30
  4584.1  415.12  4626.2  415.32  4641.5  414.33  4678.3  413.00  4689.0  410.54
  4699.1  410.69  4750.7  404.45  4787.6  399.75  4792.6  399.84  4801.0  398.23
  4831.5  396.14  4839.6  393.84  4844.7  394.62  4864.0  391.32  4882.4  388.85
  4933.3  384.23  4990.6  382.21  4993.3  381.71  4996.6  382.21  5003.6  383.20
  5049.9  383.03  5103.7  384.01  5133.7  387.07  5149.1  389.74  5153.4  390.23
  5163.7  393.86  5173.7  395.05  5183.7  397.85  5203.7  400.54  5309.2  405.28
#Mann=9,-1,0
  4584.1    0.12       0  4641.5    0.16       0  4750.7    0.12       0
  4864.0    0.16       0  4933.3    0.12       0  4990.6    0.07       0
  4996.6    0.12       0  5049.9    0.16       0  5149.1    0.05       0
Bank Sta=4990.6,4996.6
Exp/Cntr=0.3,0.1

Type RM Length L Ch R = 1,2098,502,502,502
BEGIN DESCRIPTION:
UNT 147 IN BOCR 5.0
END DESCRIPTION:
XS GIS Cut Line= 3
      3741284.33     10660458.33      3740878.07     10660697.92
      3740452.83     10660780.89
#Sta/Elev= 30
  4416.7  406.71  4429.1  406.09  4457.0  401.45  4466.2  401.19  4487.6  398.01
  4493.4  395.30  4506.9  393.07  4530.5  391.02  4573.5  384.89  4583.3  385.37
  4589.1  383.90  4596.3  384.09  4604.7  382.07  4619.5  381.18  4706.2  380.14
  4823.3  377.11  4955.1  376.09  4957.8  375.59  4961.1  376.09  5032.6  377.01
  5039.6  378.87  5074.0  382.87  5110.9  386.49  5121.1  390.11  5130.7  390.92
  5135.8  389.69  5141.5  391.95  5172.1  395.41  5238.9  401.57  5321.6  406.45
#Mann=5,-1,0
  4416.7    0.16       0  4506.9    0.12       0  4955.1    0.07       0
  4961.1    0.12       0  5074.0    0.05       0
Bank Sta=4955.1,4961.1
Exp/Cntr=0.3,0.1

Type RM Length L Ch R = 1,1596,421,421,421
BEGIN DESCRIPTION:
UNT 147 IN BOCR 4.0
END DESCRIPTION:
XS GIS Cut Line= 2
      3741023.94     10660104.15      3740258.29     10660401.04
#Sta/Elev= 30
  4598.8  383.32  4605.2  384.74  4651.5  382.25  4708.8  378.92  4714.2  381.10
  4738.7  377.73  4744.1  379.27  4753.6  379.29  4793.0  376.68  4817.8  375.09
  4823.1  375.80  4860.9  372.24  4871.6  370.15  4877.6  371.14  4902.2  369.75
  4978.8  370.41  5018.8  369.25  5021.6  368.75  5024.8  369.25  5053.9  371.06
  5095.5  371.48  5118.3  374.61  5155.3  377.39  5184.0  381.60  5279.2  390.54
  5343.3  391.81  5348.7  393.51  5373.2  393.79  5379.5  395.84  5420.0  397.23
#Mann=7,-1,0
  4598.8    0.12       0  4651.5    0.16       0  4793.0    0.12       0
  5018.8    0.07       0  5024.8    0.12       0  5184.0    0.16       0
  5379.5    0.05       0
Bank Sta=5018.8,5024.8
Exp/Cntr=0.3,0.1

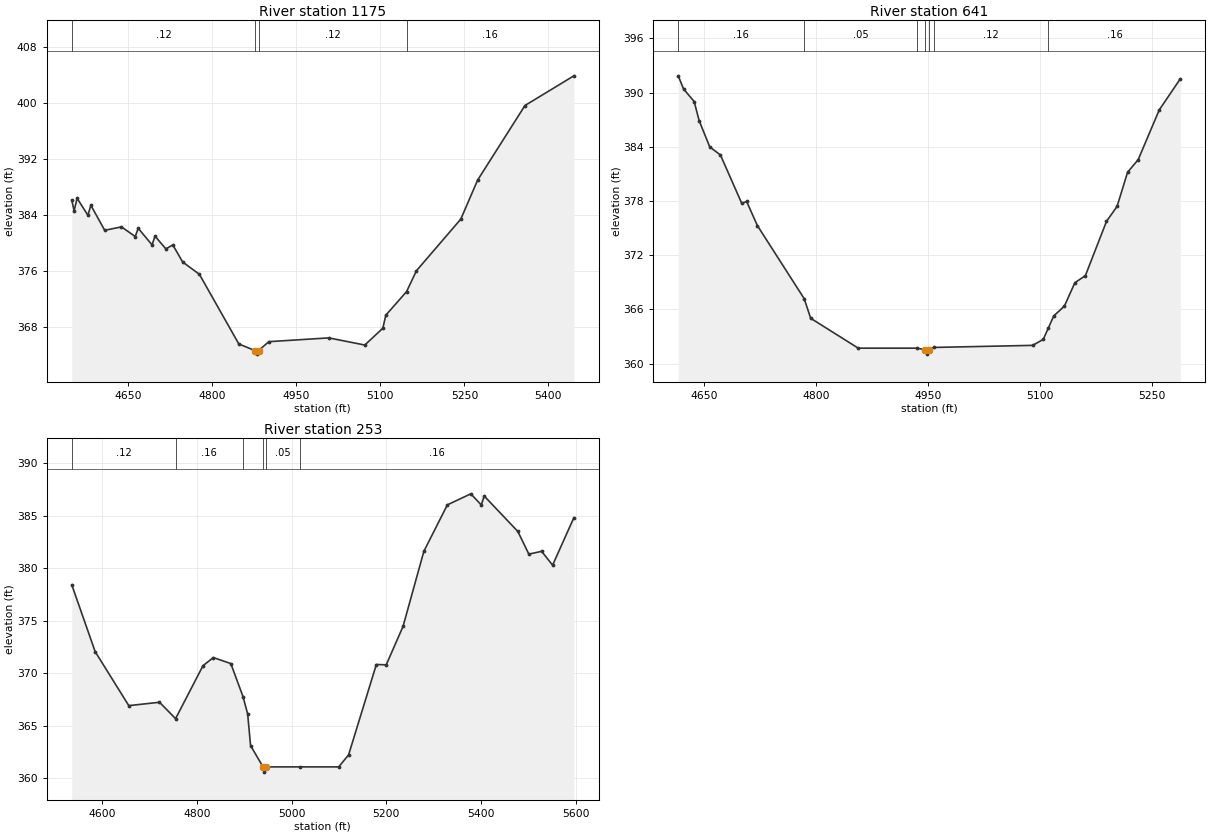
Type RM Length L Ch R = 1,1175,534,534,534
BEGIN DESCRIPTION:
UNT 147 IN BOCR 3.0
END DESCRIPTION:
XS GIS Cut Line= 2
      3740878.08     10659713.54      3740041.19     10660035.82
#Sta/Elev= 30
  4548.7  386.11  4552.9  384.59  4558.2  386.38  4577.5  383.95  4582.8  385.38
  4607.5  381.80  4637.5  382.29  4662.1  380.91  4667.4  382.09  4692.1  379.72
  4697.4  380.97  4716.7  379.15  4729.2  379.71  4746.7  377.28  4776.7  375.51
  4847.1  365.56  4876.3  364.61  4879.0  364.11  4882.3  364.61  4900.7  365.89
  5007.8  366.43  5072.1  365.41  5104.3  367.81  5109.7  369.68  5146.7  373.04
  5164.3  376.02  5243.6  383.40  5273.6  388.97  5358.2  399.63  5445.5  403.87
#Mann=4,-1,0
  4548.7    0.12       0  4876.3    0.07       0  4882.3    0.12       0
  5146.7    0.16       0
Bank Sta=4876.3,4882.3
Exp/Cntr=0.3,0.1

Type RM Length L Ch R = 1,641,388,388,388
BEGIN DESCRIPTION:
UNT 147 IN BOCR 2.0
END DESCRIPTION:
XS GIS Cut Line= 3
      3740499.58     10659160.21      3740199.61     10659410.19
      3739999.62     10659610.17
#Sta/Elev= 30
  4614.9  391.85  4622.0  390.40  4636.3  389.00  4642.9  386.90  4657.2  383.98
  4671.5  383.09  4700.1  377.73  4706.6  377.95  4721.0  375.28  4783.8  367.19
  4792.5  365.02  4856.3  361.71  4934.9  361.71  4945.8  361.55  4948.5  361.05
  4951.8  361.55  4957.4  361.79  5090.2  362.02  5104.4  362.68  5111.4  363.97
  5118.5  365.28  5132.7  366.36  5146.8  368.95  5160.9  369.74  5189.2  375.74
  5203.4  377.40  5217.5  381.18  5231.7  382.57  5259.9  388.07  5288.2  391.52
#Mann=7,-1,0
  4614.9    0.16       0  4783.8    0.05       0  4934.9    0.07       0
  4945.8    0.07       0  4951.8    0.07       0  4957.4    0.12       0
  5111.4    0.16       0
Bank Sta=4945.8,4951.8
Exp/Cntr=0.3,0.1

Type RM Length L Ch R = 1,253,0,0,0
BEGIN DESCRIPTION:
UNT 147 IN BOCR 1.0
END DESCRIPTION:
XS GIS Cut Line= 2
      3740361.59     10658813.94      3739503.44     10659438.05
#Sta/Elev= 30
  4535.4  378.42  4584.8  372.05  4655.9  366.90  4720.8  367.22  4754.8  365.66
  4812.8  370.71  4834.6  371.48  4871.5  370.91  4897.3  367.76  4907.1  366.11
  4913.3  363.09  4939.6  361.06  4942.4  360.56  4945.6  361.06  5017.4  361.06
  5099.5  361.06  5120.4  362.20  5179.1  370.82  5200.0  370.79  5235.5  374.45
  5279.6  381.62  5329.2  386.04  5378.7  387.09  5400.9  386.03  5407.1  386.88
  5478.2  383.50  5501.4  381.34  5528.4  381.61  5551.6  380.29  5596.5  384.81
#Mann=6,-1,0
  4535.4    0.12       0  4754.8    0.16       0  4897.3    0.05       0
  4939.6   0.033       0  4945.6    0.05       0  5017.4    0.16       0
Bank Sta=4939.6,4945.6
Exp/Cntr=0.3,0.1

Chan Stop Cuts=-1