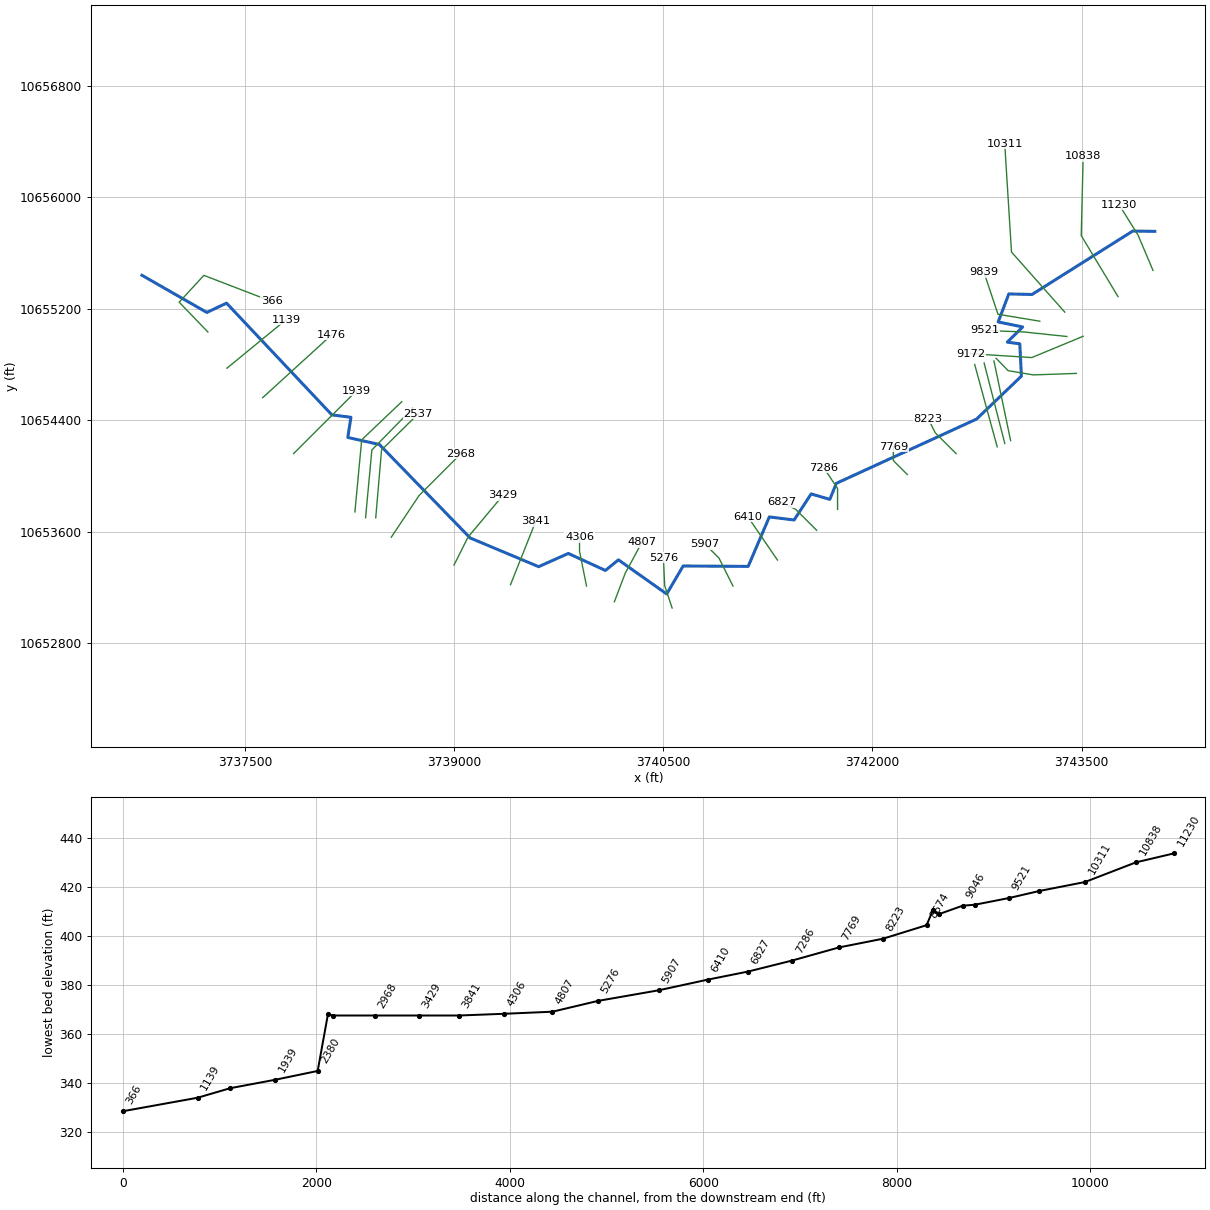
--- UNT 149 IN BOCR.prj (project) ---

Proj Title=UNT 149 IN BOCR Base Level Engineering
Current Plan=p01
Default Exp/Contr=0.3,0.1
English Units
Geom File=g01
Flow File=f01
Plan File=p01
Y Axis Title=Elevation
X Axis Title(PF)=Main Channel Distance
X Axis Title(XS)=Station
BEGIN DESCRIPTION:
UNT 149 IN BOCR
END DESCRIPTION:
DSS Export Rating Curves= 0
DSS Export Rating Curve Sorted= 0
DSS Export Volume Flow Curves= 0
DXF OffsetX= 0
DXF OffsetY= 0
DXF ScaleX= 1
DXF ScaleY= 10

--- UNT 149 IN BOCR.p01 (plan) ---

Plan Title=Multiple Run
Short Identifier=Multiple
Geom File=g01
Flow File=f01
Subcritical Flow
K Sum by GR= 0
Std Step Tol= 0.01
Critical Tol= 0.01
Num of Std Step Trials= 20
Max Error Tol= 0.3
Flow Tol Ratio= 0.001
Split Flow NTrial= 30
Split Flow Tol= 0.02
Split Flow Ratio= 0.02
Log Output Level= 0
Friction Slope Method= 1
Unsteady Friction Slope Method= 2
Unsteady Bridges Friction Slope Method= 1
Parabolic Critical Depth
Global Vel Dist=  1 , 1 , 1
Global Log Level= 0
CheckData=True
Encroach Param= -1, 0, 0, 0
BEGIN DESCRIPTION:
Multiple Run
END DESCRIPTION:

--- UNT 149 IN BOCR.f01 (steady flow) ---

Flow Title=Multiple
Program Version=4.10
Number of Profiles= 7
Profile Names=10-year,25-year,50-year,1pct_min,100-year,1pct_plu,500-year
River Rch & RM=UNT 149 IN BOCR,Reach-1         ,11230
     390     514     614     541     732     990    1041
Boundary for River Rch & Prof#=UNT 149 IN BOCR,Reach-1         , 1
Up Type= 0
Dn Type= 3
Dn Slope=0.007
Boundary for River Rch & Prof#=UNT 149 IN BOCR,Reach-1         , 2
Up Type= 0
Dn Type= 3
Dn Slope=0.007
Boundary for River Rch & Prof#=UNT 149 IN BOCR,Reach-1         , 3
Up Type= 0
Dn Type= 3
Dn Slope=0.007
Boundary for River Rch & Prof#=UNT 149 IN BOCR,Reach-1         , 4
Up Type= 0
Dn Type= 3
Dn Slope=0.007
Boundary for River Rch & Prof#=UNT 149 IN BOCR,Reach-1         , 5
Up Type= 0
Dn Type= 3
Dn Slope=0.007
Boundary for River Rch & Prof#=UNT 149 IN BOCR,Reach-1         , 6
Up Type= 0
Dn Type= 3
Dn Slope=0.007
Boundary for River Rch & Prof#=UNT 149 IN BOCR,Reach-1         , 7
Up Type= 0
Dn Type= 3
Dn Slope=0.007
DSS Import GetInterval= 0
DSS Import GetPeak= 0
DSS Import FillOption= 0

--- UNT 149 IN BOCR.g01 (geometry) ---

Geom Title=Existing Conditions
Program Version=4.10

River Reach=UNT 149 IN BOCR ,Reach-1
Reach XY= 30
        3744024.       10655755.        3743866.       10655757.
      3743143.75       10655302.       3742977.5       10655306.
      3742901.25       10655105.      3743076.75       10655069.
       3742966.5       10654960.      3743056.25       10654948.
      3743067.75       10654716.        3742746.       10654408.
      3741740.75       10653947.      3741694.25       10653832.
        3741560.       10653871.      3741438.25       10653684.
       3741260.5       10653706.      3741108.75       10653351.
       3740642.5       10653354.       3740524.5       10653153.
       3740178.5       10653398.        3740085.       10653322.
        3739819.       10653444.       3739606.5       10653349.
       3739115.5       10653555.      3738464.61     10654225.59
        3738238.       10654276.       3738260.5       10654421.
        3738124.       10654438.       3737368.5       10655240.
       3737227.5       10655173.        3736762.       10655440.

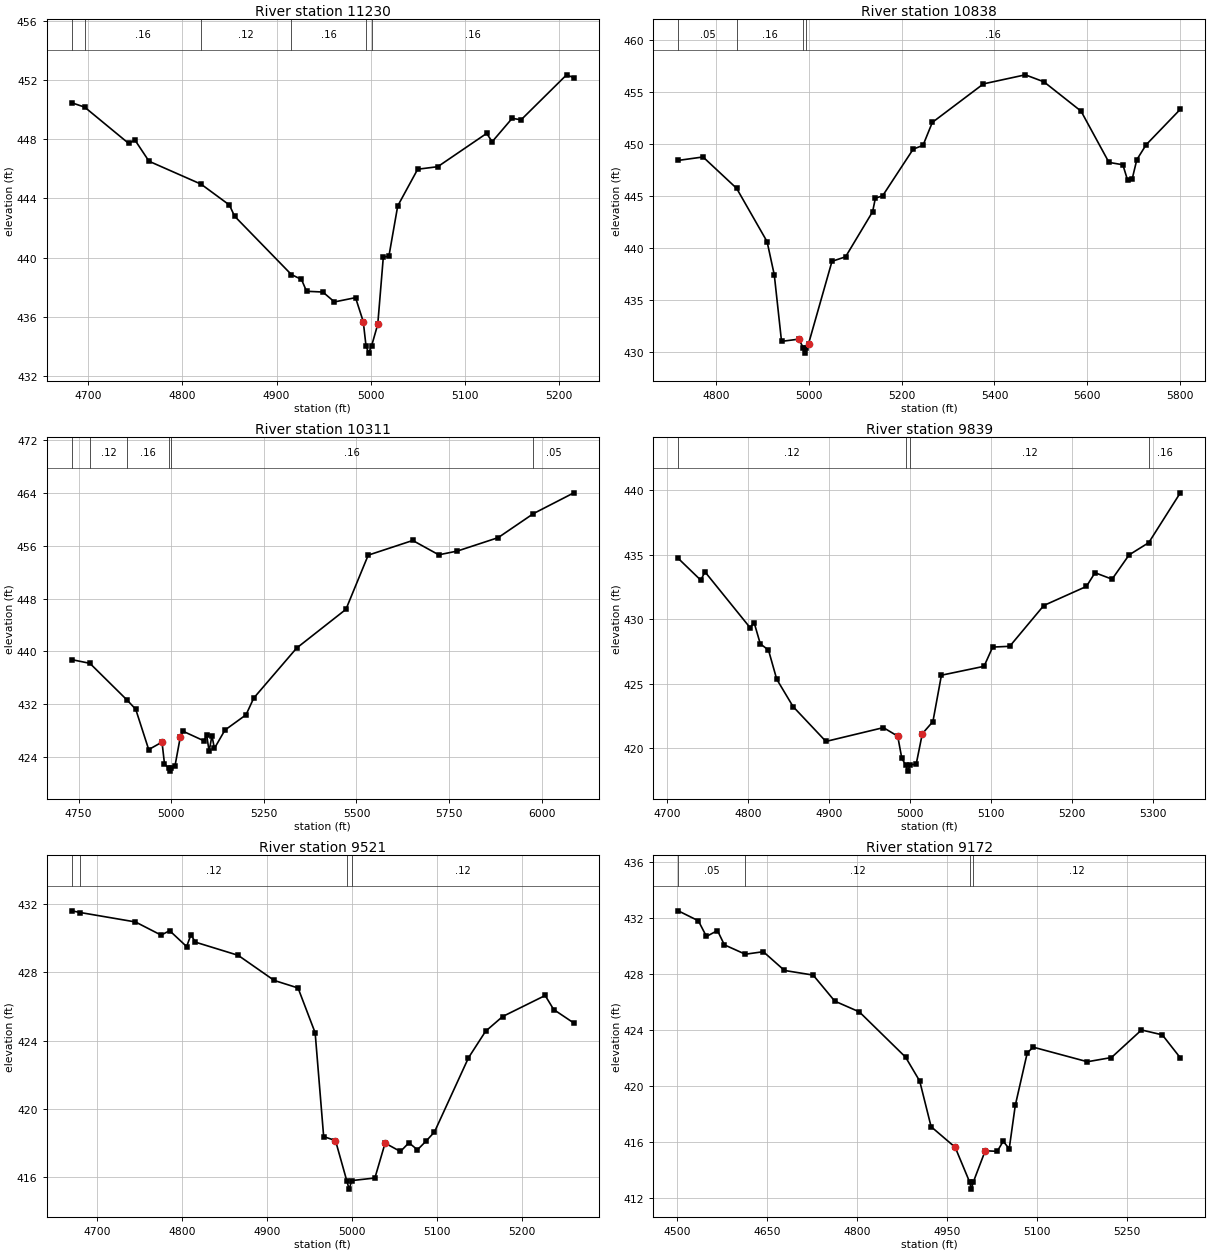
Type RM Length L Ch R = 1 ,11230   ,392,392,392
BEGIN DESCRIPTION:
UNT 149 IN BOCR 22.0
END DESCRIPTION:
XS GIS Cut Line= 3
       3744011.3     10655474.64      3743904.54     10655727.22
      3743767.56      10655946.9
#Sta/Elev= 30
  4682.5  450.46  4696.1  450.17  4742.8  447.72  4749.6  447.94  4764.5  446.51
  4819.8  444.96  4849.9  443.55  4855.3   442.8  4915.7  438.85  4926.4  438.52
  4931.8  437.72  4949.1  437.67  4961.4     437  4983.8  437.29    4992  435.67
  4994.9  434.04  4997.7  433.54  5000.9  434.04  5007.4  435.49  5013.3  440.04
  5019.2  440.08  5028.6  443.49  5049.8  445.97  5071.1  446.14    5123  448.39
  5128.9  447.83  5150.1  449.41  5159.6  449.31  5207.9  452.35  5215.6  452.15
#Mann= 6 ,-1 , 0
  4682.5     .05       0  4696.1     .16       0  4819.8     .12       0
  4915.7     .16       0  4994.9     .07       0  5000.9     .16       0
Bank Sta=4992,5007.4
XS Rating Curve= 0 ,0
Exp/Cntr=0.3,0.1

Type RM Length L Ch R = 1 ,10838   ,527,527,527
BEGIN DESCRIPTION:
UNT 149 IN BOCR 21.0
END DESCRIPTION:
XS GIS Cut Line= 3
      3743760.59     10655286.83       3743496.7     10655724.33
      3743510.59     10656293.73
#Sta/Elev= 30
  4719.4  448.41  4772.8  448.74    4845  445.73  4910.6  440.61  4926.1  437.42
  4941.7  431.03  4978.5  431.24  4988.9   430.4  4991.7   429.9  4994.9   430.4
  4999.9  430.81  5050.3  438.72  5079.5  439.15  5137.7  443.48  5143.7  444.79
  5159.1     445    5225  449.49  5246.2  449.86  5266.2  452.06  5376.2  455.76
  5466.3  456.63  5506.3  455.96  5586.3  453.14  5646.3  448.22  5676.3  447.99
  5686.3  446.53  5696.3  446.62  5706.3  448.48  5726.3  449.91  5799.9  453.32
#Mann= 4 ,-1 , 0
  4719.4     .05       0    4845     .16       0  4988.9     .07       0
  4994.9     .16       0
Bank Sta=4978.5,4999.9
XS Rating Curve= 0 ,0
Exp/Cntr=0.3,0.1

Type RM Length L Ch R = 1 ,10311   ,472,472,472
BEGIN DESCRIPTION:
UNT 149 IN BOCR 20.0
END DESCRIPTION:
XS GIS Cut Line= 3
      3743378.64     10655175.72       3742996.7     10655606.28
      3742948.09     10656384.01
#Sta/Elev= 30
  4731.7  438.75  4780.6  438.19  4880.6  432.65  4904.2  431.25  4939.3  425.14
  4975.2  426.27  4981.9  422.97  4993.1  422.38  4995.9  421.88  4999.1  422.38
  5010.4  422.72  5024.6  427.06  5031.8  427.92  5088.1  426.47  5095.7  427.33
  5102.4  424.85  5109.9  427.26  5116.6  425.32    5145  428.09  5201.9   430.4
  5222.8  432.94  5338.5   440.5  5471.5  446.36  5531.6  454.56  5651.8  456.78
    5722  454.61  5772.1  455.18  5882.3  457.21  5977.6  460.85  6086.5  463.99
#Mann= 6 ,-1 , 0
  4731.7     .05       0  4780.6     .12       0  4880.6     .16       0
  4993.1     .07       0  4999.1     .16       0  5977.6     .05       0
Bank Sta=4975.2,5024.6
XS Rating Curve= 0 ,0
Exp/Cntr=0.3,0.1

Type RM Length L Ch R = 1 ,9839    ,318,318,318
BEGIN DESCRIPTION:
UNT 149 IN BOCR 19.0
END DESCRIPTION:
XS GIS Cut Line= 3
      3743199.62     10655110.19      3742899.61     10655160.19
       3742799.6     10655460.21
#Sta/Elev= 30
  4713.6  434.71  4741.5  433.02  4746.6  433.67  4802.3  429.35  4807.4  429.73
    4815  428.09  4825.1  427.61  4835.3  425.35  4855.5  423.23  4896.1  420.53
  4967.1   421.6  4984.8  420.94  4989.9  419.21  4994.5  418.73  4997.2  418.23
  5000.5  418.73  5007.6  418.76  5015.2  421.13  5028.3  422.07  5038.8  425.66
  5091.5  426.35  5102.1  427.84  5123.2   427.9  5165.3  431.06    5218  432.54
  5228.6   433.6  5249.7   433.1  5270.7  434.98    5295  435.93    5334  439.79
#Mann= 4 ,-1 , 0
  4713.6     .12       0  4994.5     .07       0  5000.5     .12       0
    5295     .16       0
Bank Sta=4984.8,5015.2
XS Rating Curve= 0 ,0
Exp/Cntr=0.3,0.1

Type RM Length L Ch R = 1 ,9521    ,349,349,349
BEGIN DESCRIPTION:
Mapping XS 9e276ceb
END DESCRIPTION:
XS GIS Cut Line= 3
      3743394.01     10655000.49      3743085.87     10655033.04
      3742805.94     10655043.89
#Sta/Elev= 30
  4670.7  431.59  4680.8  431.49  4745.5  430.94  4775.7  430.17  4785.7  430.43
  4805.7   429.5  4810.7  430.19  4815.9  429.76  4866.2  428.99  4908.6  427.52
  4936.6  427.08  4956.7  424.46  4966.7  418.39  4980.6  418.16  4993.8  415.82
  4996.6  415.32  4999.8  415.82  5026.9  415.97  5038.9  418.01  5056.9  417.52
  5066.9  418.03  5076.9  417.62  5086.9  418.12  5096.9  418.66  5136.9     423
    5157  424.55    5177  425.41    5227  426.64    5237  425.82  5260.7  425.03
#Mann= 4 ,-1 , 0
  4670.7     .05       0  4680.8     .12       0  4993.8     .07       0
  4999.8     .12       0
Bank Sta=4980.6,5038.9
XS Rating Curve= 0 ,0
Exp/Cntr=0.3,0.1

Type RM Length L Ch R = 1 ,9172    ,126,126,126
BEGIN DESCRIPTION:
UNT 149 IN BOCR 18.0
END DESCRIPTION:
XS GIS Cut Line= 3
      3743510.59     10655002.11      3743142.53     10654849.33
      3742705.02     10654877.11
#Sta/Elev= 30
  4502.3  432.51  4535.8   431.8  4549.3  430.68  4567.7   431.1  4579.2  430.08
  4614.1  429.41  4644.1  429.59  4679.4  428.25  4727.2  427.92  4763.2  426.06
  4804.2  425.29  4881.2  422.06  4904.8  420.35  4923.8  417.09  4963.9  415.62
  4988.1  413.13  4990.8  412.63  4994.1  413.13    5014  415.37    5034  415.33
    5044  416.05    5054  415.51  5064.1  418.61  5084.1  422.37  5094.1  422.77
  5184.3  421.73  5224.4  422.03  5274.5     424  5309.2  423.65  5339.2  422.01
#Mann= 4 ,-1 , 0
  4502.3     .05       0  4614.1     .12       0  4988.1     .07       0
  4994.1     .12       0
Bank Sta=4963.9,5014
XS Rating Curve= 0 ,0
Exp/Cntr=0.3,0.1

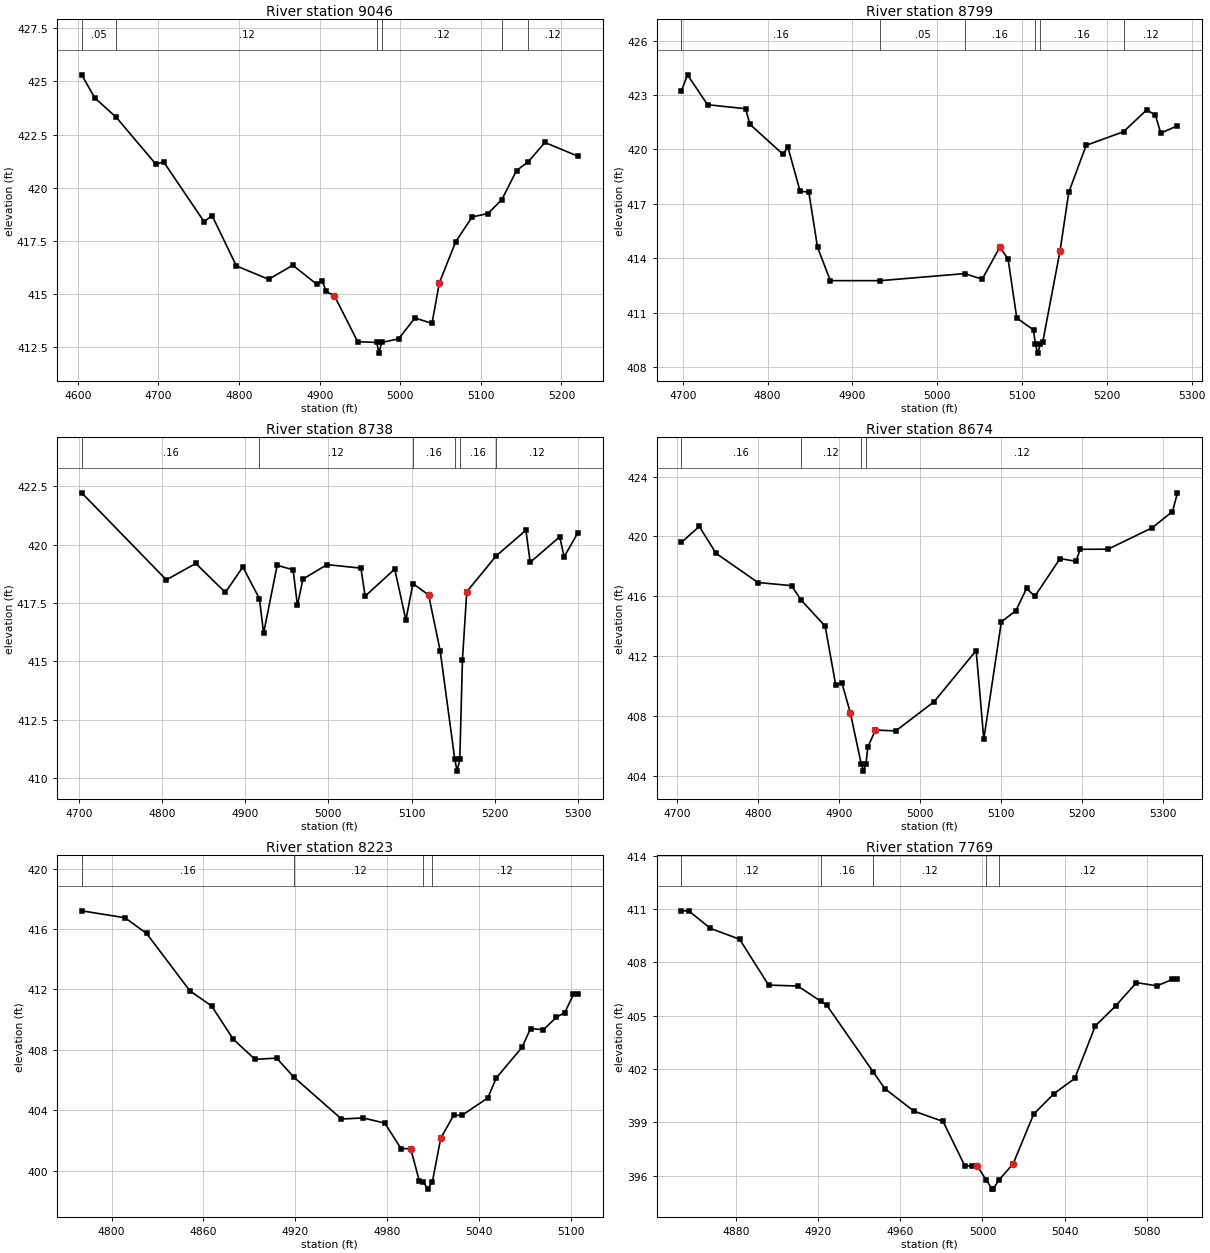
Type RM Length L Ch R = 1 ,9046    ,247,247,247
BEGIN DESCRIPTION:
Mapping XS 3923d4ff
END DESCRIPTION:
XS GIS Cut Line= 4
      3743461.34     10654735.73      3743153.14     10654724.88
      3742973.02     10654755.26      3742886.19     10654844.27
#Sta/Elev= 30
  4604.8  425.31  4620.9  424.23  4647.7  423.31  4696.6  421.12  4706.6  421.21
  4756.6  418.41  4766.6  418.69  4796.7  416.33  4836.7   415.7  4866.7  416.36
  4896.7  415.46  4903.1  415.64  4908.1  415.13  4918.4  414.92  4947.2  412.77
  4970.9  412.73  4973.6  412.23  4976.9  412.73  4997.9   412.9  5018.2  413.88
  5039.4  413.63  5048.6  415.54  5068.9  417.47  5089.2  418.63  5108.8  418.79
    5126  419.44  5144.3  420.81  5158.7  421.22  5179.5  422.13  5220.2  421.49
#Mann= 6 ,-1 , 0
  4604.8     .05       0  4647.7     .12       0  4970.9     .07       0
  4976.9     .12       0    5126     .16       0  5158.7     .12       0
Bank Sta=4918.4,5048.6
XS Rating Curve= 0 ,0
Exp/Cntr=0.3,0.1

Type RM Length L Ch R = 1 ,8799    ,61,61,61
BEGIN DESCRIPTION:
Mapping XS 8806bac1
END DESCRIPTION:
XS GIS Cut Line= 2
      3742990.49     10654253.22       3742870.8     10654825.64
#Sta/Elev= 30
  4698.5  423.24  4705.6  424.12  4729.2  422.47  4774.1  422.25  4779.2  421.39
    4818  419.74    4824  420.12  4838.4  417.69  4848.6  417.65  4858.9   414.6
    4874  412.76  4933.1  412.76  5032.5  413.15    5053  412.84  5073.9  414.61
  5083.6  413.95  5093.8   410.7  5113.6  410.04  5115.7  409.26  5118.5  408.76
  5121.7  409.26  5124.5  409.39  5144.9  414.42  5155.1  417.63  5175.6  420.23
  5219.7  420.98  5247.1  422.19  5257.3  421.89  5263.6   420.9  5283.3  421.31
#Mann= 6 ,-1 , 0
  4698.5     .16       0  4933.1     .05       0  5032.5     .16       0
  5115.7    .033       0  5121.7     .16       0  5219.7     .12       0
Bank Sta=5073.9,5144.9
XS Rating Curve= 0 ,0
Exp/Cntr=0.3,0.1

Type RM Length L Ch R = 1 ,8738    ,64,64,64
BEGIN DESCRIPTION:
Mapping XS 906c0417
END DESCRIPTION:
XS GIS Cut Line= 2
      3742948.83     10654232.38      3742800.38     10654810.53
#Sta/Elev= 30
  4703.1  422.21  4804.9  418.49  4840.4  419.19    4876  417.95    4897  419.04
  4916.9  417.69    4922  416.21  4938.3  419.11  4957.5  418.92  4962.7   417.4
  4969.3  418.52  4998.3  419.14  5039.1  418.99  5044.2  417.79  5079.8  418.95
  5093.2  416.77  5101.7  418.33  5120.6  417.84  5134.5  415.45  5152.1  410.81
  5154.9  410.31  5158.1  410.81  5161.3  415.08  5166.5  417.98  5201.8  419.51
  5237.7  420.61  5242.8  419.24  5278.4  420.33  5283.6  419.47    5300  420.49
#Mann= 6 ,-1 , 0
  4703.1     .16       0  4916.9     .12       0  5101.7     .16       0
  5152.1     .07       0  5158.1     .16       0  5201.8     .12       0
Bank Sta=5120.6,5166.5
XS Rating Curve= 0 ,0
Exp/Cntr=0.3,0.1

Type RM Length L Ch R = 1 ,8674    ,451,451,451
BEGIN DESCRIPTION:
UNT 149 IN BOCR 17.0
END DESCRIPTION:
XS GIS Cut Line= 2
      3742894.13     10654208.99      3742732.67     10654800.14
#Sta/Elev= 30
  4705.6  419.61  4727.6  420.67  4748.3  418.87  4800.1  416.92  4841.6  416.71
    4853  415.77  4883.1     414  4896.1  410.07  4903.8   410.2  4914.2   408.2
  4927.6   404.8  4930.4   404.3  4933.6   404.8  4935.8  405.91  4945.3  407.05
  4970.3  406.99  5017.8  408.95  5069.7  412.37  5079.1  406.43  5100.8  414.29
  5118.8  415.04  5131.9  416.52  5142.2     416  5173.3  418.52    5193  418.34
  5198.2  419.14  5232.7  419.15  5287.4  420.59  5312.2  421.67  5318.4  422.92
#Mann= 4 ,-1 , 0
  4705.6     .16       0    4853     .12       0  4927.6     .07       0
  4933.6     .12       0
Bank Sta=4914.2,4945.3
XS Rating Curve= 0 ,0
Exp/Cntr=0.3,0.1

Type RM Length L Ch R = 1 ,8223    ,454,454,454
BEGIN DESCRIPTION:
UNT 149 IN BOCR 16.0
END DESCRIPTION:
XS GIS Cut Line= 3
      3742599.62     10654160.18      3742449.61     10654310.19
      3742399.59     10654410.23
#Sta/Elev= 30
  4780.5   417.2  4808.8  416.74  4822.9   415.7  4851.2   411.9  4865.4   410.9
  4879.5   408.7  4893.7  407.37  4907.8  407.45  4919.1  406.19  4950.2  403.42
  4964.4  403.49  4978.5  403.15  4989.1  401.46  4995.4  401.46    5001  399.33
  5003.6  399.28  5006.4  398.78  5009.6  399.28    5015  402.14  5023.4  403.66
    5029  403.67  5045.8  404.82  5051.3  406.14  5068.1  408.16  5073.7  409.41
  5082.1  409.33  5090.5  410.15  5096.1  410.47  5101.7  411.67  5104.5  411.67
#Mann= 4 ,-1 , 0
  4780.5     .16       0  4919.1     .12       0  5003.6     .07       0
  5009.6     .12       0
Bank Sta=4995.4,5015
XS Rating Curve= 0 ,0
Exp/Cntr=0.3,0.1

Type RM Length L Ch R = 1 ,7769    ,483,483,483
BEGIN DESCRIPTION:
UNT 149 IN BOCR 15.0
END DESCRIPTION:
XS GIS Cut Line= 3
       3742249.6      10654010.2      3742149.61     10654110.19
      3742149.61     10654210.18
#Sta/Elev= 29
  4853.5   410.9    4857   410.9  4867.6  409.91  4881.8   409.3  4895.9  406.72
  4910.1  406.67  4921.2  405.82  4924.2  405.59  4946.9  401.82  4952.5  400.89
  4966.6  399.63  4980.8  399.05  4991.4  396.55  4994.9  396.55  4997.4  396.55
  5001.9  395.74  5004.7  395.24  5005.2  395.24  5007.9  395.74  5014.9  396.66
  5024.9  399.46  5034.9  400.62  5044.9  401.47  5054.9  404.42  5064.9  405.56
  5074.9  406.86  5084.9  406.68  5092.4  407.04  5094.9  407.04
#Mann= 5 ,-1 , 0
  4853.5     .12       0  4921.2     .16       0  4946.9     .12       0
  5001.9     .07       0  5007.9     .12       0
Bank Sta=4997.4,5014.9
XS Rating Curve= 0 ,0
Exp/Cntr=0.3,0.1

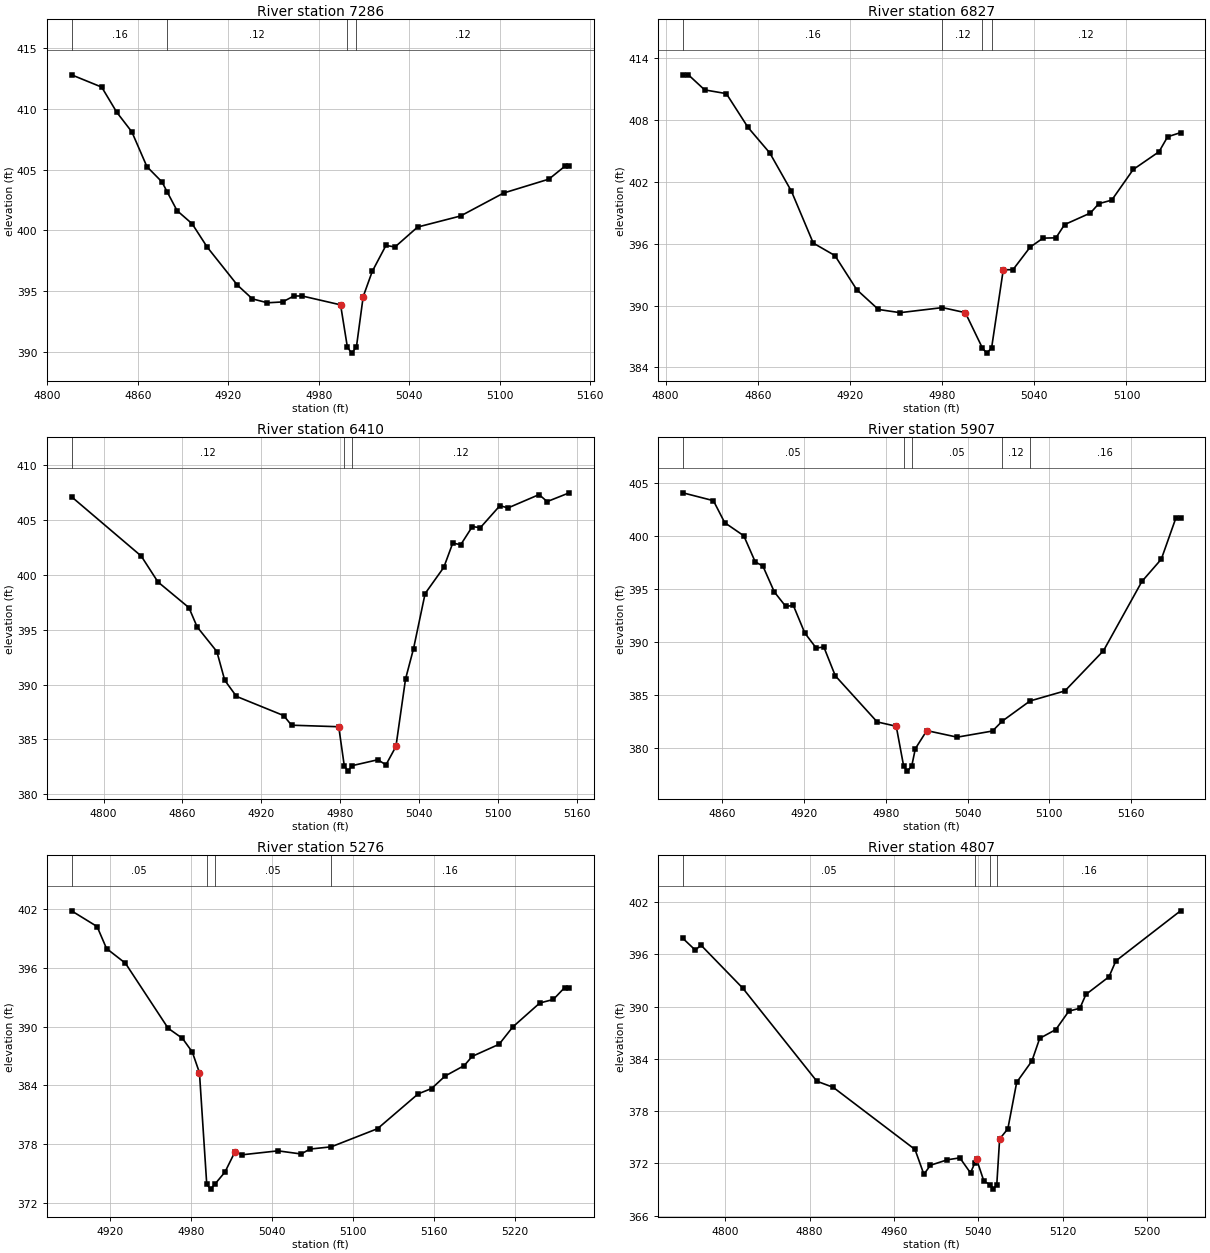
Type RM Length L Ch R = 1 ,7286    ,459,459,459
BEGIN DESCRIPTION:
UNT 149 IN BOCR 14.0
END DESCRIPTION:
XS GIS Cut Line= 3
      3741749.61     10653760.22      3741749.61     10653910.19
      3741649.64     10654060.15
#Sta/Elev= 30
    4816   412.8    4836  411.79    4846  409.72    4856  408.11    4866  405.25
    4876  403.99  4879.5  403.16    4886  401.63    4896  400.55    4906  398.63
    4926  395.51    4936  394.37    4946  394.05    4956  394.12  4963.5  394.61
    4969  394.61  4994.5  393.88    4999  390.41  5001.8  389.91    5005  390.41
  5009.5  394.56  5015.5  396.63  5024.6  398.77  5030.6  398.64  5045.6  400.28
  5074.1  401.19  5102.7  403.08  5132.7  404.22  5143.2  405.27  5146.2  405.27
#Mann= 4 ,-1 , 0
    4816     .16       0  4879.5     .12       0    4999     .07       0
    5005     .12       0
Bank Sta=4994.5,5009.5
XS Rating Curve= 0 ,0
Exp/Cntr=0.3,0.1

Type RM Length L Ch R = 1 ,6827    ,417,417,417
BEGIN DESCRIPTION:
UNT 149 IN BOCR 13.0
END DESCRIPTION:
XS GIS Cut Line= 3
      3741599.62     10653610.18      3741449.61     10653760.19
      3741349.57     10653810.21
#Sta/Elev= 30
  4811.2  412.35  4814.8  412.35  4825.4  410.89  4839.5  410.53  4853.6  407.26
  4867.8  404.78  4881.9  401.07  4896.1  396.05  4910.2  394.84  4924.4  391.54
  4938.5  389.62  4952.6  389.31  4980.2   389.8  4995.1  389.31  5006.2  385.89
    5009  385.39  5012.2  385.89  5019.8  393.47  5026.1  393.47  5037.3  395.66
  5045.7  396.53  5054.1  396.56  5059.7  397.84  5076.5  398.96    5082  399.87
  5090.4  400.21  5104.4  403.18  5121.2   404.9  5126.8  406.35  5135.2  406.75
#Mann= 4 ,-1 , 0
  4811.2     .16       0  4980.2     .12       0  5006.2     .07       0
  5012.2     .12       0
Bank Sta=4995.1,5019.8
XS Rating Curve= 0 ,0
Exp/Cntr=0.3,0.1

Type RM Length L Ch R = 1 ,6410    ,503,503,503
BEGIN DESCRIPTION:
UNT 149 IN BOCR 12.0
END DESCRIPTION:
XS GIS Cut Line= 2
      3741318.62     10653396.47      3741105.07     10653708.98
#Sta/Elev= 30
  4775.7  407.13  4828.7  401.72  4841.4  399.36    4865  397.01  4871.2  395.26
  4886.2  393.01  4892.2  390.39  4901.1  388.92    4937  387.17    4943  386.29
  4978.9  386.15  4983.1   382.6  4985.9   382.1  4989.1   382.6  5008.7  383.14
  5014.8  382.67  5022.4  384.35  5029.7   390.5  5035.8  393.28  5044.6   398.3
  5058.8  400.69  5065.6   402.9  5071.7  402.76  5080.5  404.41  5086.6  404.31
  5101.5  406.32  5107.6  406.11  5131.3  407.33  5137.4  406.69  5154.2  407.49
#Mann= 3 ,-1 , 0
  4775.7     .12       0  4983.1     .07       0  4989.1     .12       0
Bank Sta=4978.9,5022.4
XS Rating Curve= 0 ,0
Exp/Cntr=0.3,0.1

Type RM Length L Ch R = 1 ,5907    ,631,631,631
BEGIN DESCRIPTION:
UNT 149 IN BOCR 11.0
END DESCRIPTION:
XS GIS Cut Line= 3
      3740999.61      10653210.2      3740899.61     10653410.19
      3740799.62     10653510.17
#Sta/Elev= 30
  4831.2  404.09  4853.6  403.35  4861.9  401.27  4875.9  400.03  4884.3  397.56
  4889.9  397.17  4898.3  394.72  4906.7  393.35  4912.2  393.46  4920.6  390.85
    4929  389.42  4934.6  389.52    4943   386.8  4973.7  382.44  4987.7  382.03
  4993.1  378.29  4995.9  377.79  4999.1  378.29  5001.7  379.91  5010.1  381.62
  5032.4     381  5058.3  381.58  5065.4  382.51  5085.8  384.42  5111.4  385.37
  5139.7  389.17  5167.9  395.72  5182.1  397.82  5192.7  401.68  5196.2  401.68
#Mann= 5 ,-1 , 0
  4831.2     .05       0  4993.1     .03       0  4999.1     .05       0
  5065.4     .12       0  5085.8     .16       0
Bank Sta=4987.7,5010.1
XS Rating Curve= 0 ,0
Exp/Cntr=0.3,0.1

Type RM Length L Ch R = 1 ,5276    ,469,469,469
BEGIN DESCRIPTION:
UNT 149 IN BOCR 10.0
END DESCRIPTION:
XS GIS Cut Line= 3
      3740563.32     10653052.28      3740509.99     10653213.65
      3740501.09       10653412.
#Sta/Elev= 30
  4891.6  401.79  4910.5  400.19  4917.5  397.95  4931.5  396.45  4963.1  389.83
  4973.7   388.8    4981  387.41  4986.3   385.3  4991.7  373.94  4994.5  373.44
  4997.7  373.94  5005.2  375.18  5012.7  377.27    5018  376.94  5044.5  377.34
  5061.6  377.02  5068.1  377.52  5083.9  377.75  5118.2   379.6  5148.2  383.14
  5158.2  383.69  5168.2  384.96  5182.4  386.03  5188.2  386.96  5208.2   388.2
  5218.3  389.96  5238.3   392.4  5248.3  392.76  5256.7  393.97  5260.1  393.97
#Mann= 4 ,-1 , 0
  4891.6     .05       0  4991.7     .03       0  4997.7     .05       0
  5083.9     .16       0
Bank Sta=4986.3,5012.7
XS Rating Curve= 0 ,0
Exp/Cntr=0.3,0.1

Type RM Length L Ch R = 1 ,4807    ,501,501,501
BEGIN DESCRIPTION:
UNT 149 IN BOCR 9.0
END DESCRIPTION:
XS GIS Cut Line= 3
      3740149.33     10653097.01      3740227.46     10653302.74
      3740347.27     10653524.13
#Sta/Elev= 30
  4759.9  397.84  4771.7  396.49  4777.1  397.06  4816.8  392.11  4886.9  381.44
  4902.4  380.74    4980   373.6  4988.4  370.75  4994.6  371.79  5010.7  372.42
  5022.5  372.64  5032.6  370.91  5036.5     372  5038.3   372.5  5045.3  369.96
  5051.5  369.55  5054.2  369.05  5057.5  369.55  5060.2   374.8    5068  375.98
  5076.4  381.32  5090.8  383.76  5098.2  386.36  5113.5  387.37  5125.8  389.48
  5136.3  389.82    5142   391.4  5163.9  393.43  5170.4  395.25  5231.7     401
#Mann= 4 ,-1 , 0
  4759.9     .05       0  5036.5     .16       0  5051.5     .03       0
  5057.5     .16       0
Bank Sta=5038.3,5060.2
XS Rating Curve= 0 ,0
Exp/Cntr=0.3,0.1

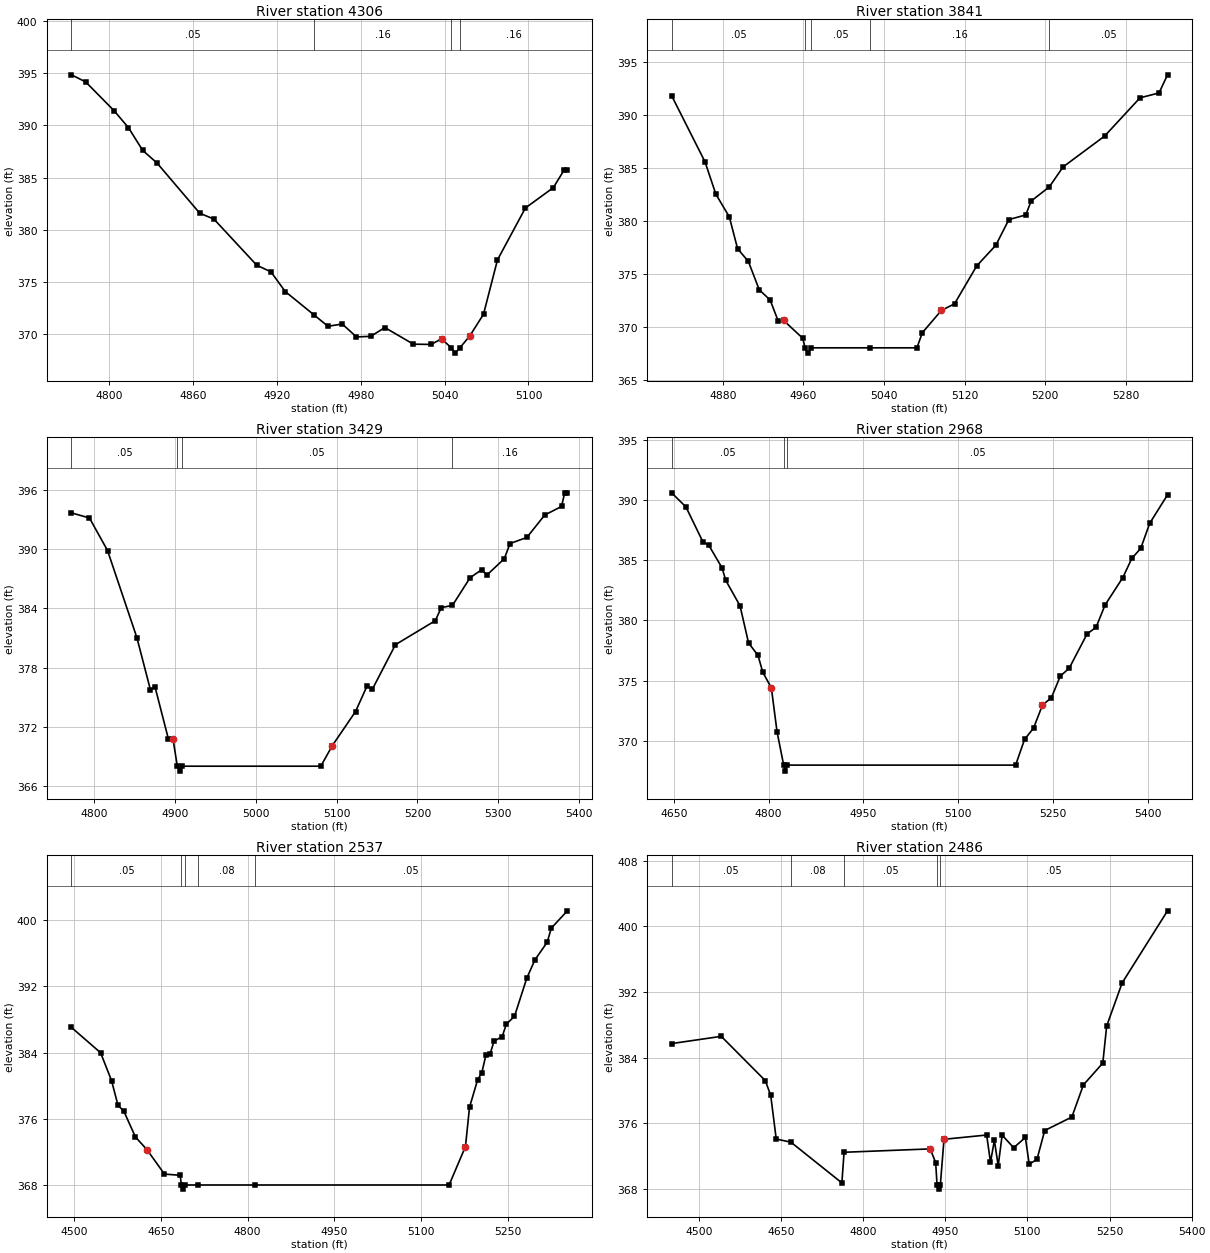
Type RM Length L Ch R = 1 ,4306    ,465,465,465
BEGIN DESCRIPTION:
UNT 149 IN BOCR 8.0
END DESCRIPTION:
XS GIS Cut Line= 3
      3739949.61      10653210.2      3739899.61     10653460.19
      3739899.61     10653560.15
#Sta/Elev= 30
  4772.9  394.85  4783.1  394.17  4803.5   391.4  4813.7  389.79  4823.9  387.61
  4834.1  386.41  4864.7   381.6  4874.9  381.03  4905.5  376.62  4915.7  375.98
  4925.9   374.1  4946.5  371.86  4956.5  370.77  4966.7  370.99  4976.9  369.75
  4987.1  369.81  4997.2  370.65  5017.6  369.06  5030.3  369.03  5037.8  369.57
  5044.8   368.7  5047.6   368.2  5050.8   368.7  5057.8  369.81  5067.8  371.92
  5077.8  377.13  5097.8   382.1  5117.8  384.05  5125.3  385.69  5127.8  385.69
#Mann= 4 ,-1 , 0
  4772.9     .05       0  4946.5     .16       0  5044.8     .07       0
  5050.8     .16       0
Bank Sta=5037.8,5057.8
XS Rating Curve= 0 ,0
Exp/Cntr=0.3,0.1

Type RM Length L Ch R = 1 ,3841    ,412,412,412
BEGIN DESCRIPTION:
UNT 149 IN BOCR 7.0
END DESCRIPTION:
XS GIS Cut Line= 2
      3739404.55     10653219.41      3739586.34     10653676.48
#Sta/Elev= 30
  4829.3  391.79  4862.4  385.55  4873.2  382.49  4886.5  380.36  4894.7  377.36
  4905.4  376.15  4916.2  373.48    4927  372.51    4935  370.53  4940.4  370.58
  4959.3  368.91  4961.7     368  4964.5   367.5  4967.7     368  5025.6     368
  5072.6     368    5078  369.43  5096.9  371.53  5109.9  372.15    5132  375.74
  5150.9  377.68  5163.8   380.1  5180.6  380.54  5185.9  381.85  5203.9  383.18
  5217.6  385.07  5258.8  387.98  5293.9  391.59  5312.8  392.05  5321.2  393.76
#Mann= 5 ,-1 , 0
  4829.3     .05       0  4961.7    .033       0  4967.7     .05       0
  5025.6     .16       0  5203.9     .05       0
Bank Sta=4940.4,5096.9
XS Rating Curve= 0 ,0
Exp/Cntr=0.3,0.1

Type RM Length L Ch R = 1 ,3429    ,461,461,461
BEGIN DESCRIPTION:
UNT 149 IN BOCR 6.0
END DESCRIPTION:
XS GIS Cut Line= 3
      3738999.63     10653360.23      3739099.61     10653560.19
      3739349.63     10653860.21
#Sta/Elev= 30
  4771.6  393.67  4793.9  393.15  4816.3  389.85  4852.6  381.03  4869.4  375.74
    4875  376.06  4891.7  370.74  4897.3  370.78  4902.7     368  4905.5   367.5
  4908.7     368  5080.4     368  5094.7  370.09  5123.4  373.54  5137.7  376.13
  5144.2  375.79  5172.8  380.31  5222.3  382.75  5229.5  384.07  5243.4  384.29
  5265.3   387.1  5279.6  387.91  5286.1  387.37  5307.6  389.02  5314.7  390.56
  5335.6  391.18  5357.7  393.45  5378.5  394.32  5382.4   395.7  5385.7   395.7
#Mann= 4 ,-1 , 0
  4771.6     .05       0  4902.7    .033       0  4908.7     .05       0
  5243.4     .16       0
Bank Sta=4897.3,5094.7
XS Rating Curve= 0 ,0
Exp/Cntr=0.3,0.1

Type RM Length L Ch R = 1 ,2968    ,431,431,431
BEGIN DESCRIPTION:
UNT 149 IN BOCR 5.0
END DESCRIPTION:
XS GIS Cut Line= 3
      3738549.59     10653560.17      3738749.61     10653860.19
      3739049.58     10654160.16
#Sta/Elev= 30
  4646.5  390.59  4669.1  389.42  4696.1  386.51  4705.1  386.26  4726.2  384.37
  4732.2  383.32  4754.7  381.22  4768.2  378.14  4783.2   377.1  4790.7  375.71
  4804.3  374.41  4813.3  370.77  4823.8     368  4826.6   367.5  4829.8     368
  5190.9     368  5205.1  370.14  5219.2  371.06  5233.4  372.98  5247.5  373.59
  5261.6  375.38  5275.8  376.05  5304.1  378.89  5318.2  379.43  5332.4  381.28
  5360.6  383.56  5374.8  385.15  5388.9  385.98  5403.1  388.06  5431.3  390.42
#Mann= 3 ,-1 , 0
  4646.5     .05       0  4823.8    .033       0  4829.8     .05       0
Bank Sta=4804.3,5233.4
XS Rating Curve= 0 ,0
Exp/Cntr=0.3,0.1

Type RM Length L Ch R = 1 ,2537    ,51,51,51
BEGIN DESCRIPTION:
Mapping XS 44110242
END DESCRIPTION:
XS GIS Cut Line= 3
      3738438.36     10653699.98      3738480.03     10654186.14
      3738743.22     10654445.86
#Sta/Elev= 30
  4495.4  387.04  4545.8  383.98  4564.7  380.62  4575.9  377.63  4585.9  376.93
    4606  373.81  4626.1  372.26  4656.2  369.32  4683.5  369.17  4685.5     368
  4688.2   367.5  4691.5     368  4714.1     368  4812.8     368  5148.6     368
  5176.9  372.65  5183.9  377.39    5198  380.73  5205.1  381.54  5212.2  383.68
  5219.3  383.79  5226.3  385.38  5240.5  385.94  5247.6  387.44  5261.7  388.38
  5282.9  392.98    5297   395.2  5318.3  397.34  5325.3  399.03  5353.1  401.13
#Mann= 5 ,-1 , 0
  4495.4     .05       0  4685.5    .033       0  4691.5     .05       0
  4714.1     .08       0  4812.8     .05       0
Bank Sta=4626.1,5176.9
XS Rating Curve= 0 ,0
Exp/Cntr=0.3,0.1

Type RM Length L Ch R = 1 ,2486    ,106,106,106
BEGIN DESCRIPTION:
UNT 149 IN BOCR 4.0
END DESCRIPTION:
XS GIS Cut Line= 3
      3738365.45     10653700.02      3738410.59     10654186.14
      3738702.23     10654484.73
#Sta/Elev= 30
  4450.3  385.72  4540.9   386.6  4621.2  381.22  4631.2  379.43  4641.3  374.09
  4668.1  373.71  4761.2  368.75  4765.2  372.48  4922.5  372.89  4932.5  371.22
    4935  368.49  4937.8  367.99    4941  368.49  4947.7  374.06  5025.6  374.58
  5032.6  371.27  5039.7  373.92  5046.7  370.85  5053.9  374.56    5075  373.03
  5096.3  374.29  5103.3  371.03  5117.5  371.61  5131.6  375.13  5181.2  376.77
  5202.3  380.69  5237.7  383.34  5244.8  387.87  5273.1  393.12  5355.9  401.89
#Mann= 5 ,-1 , 0
  4450.3     .05       0  4668.1     .08       0  4765.2     .05       0
    4935     .04       0    4941     .05       0
Bank Sta=4922.5,4947.7
XS Rating Curve= 0 ,0
Exp/Cntr=0.3,0.1

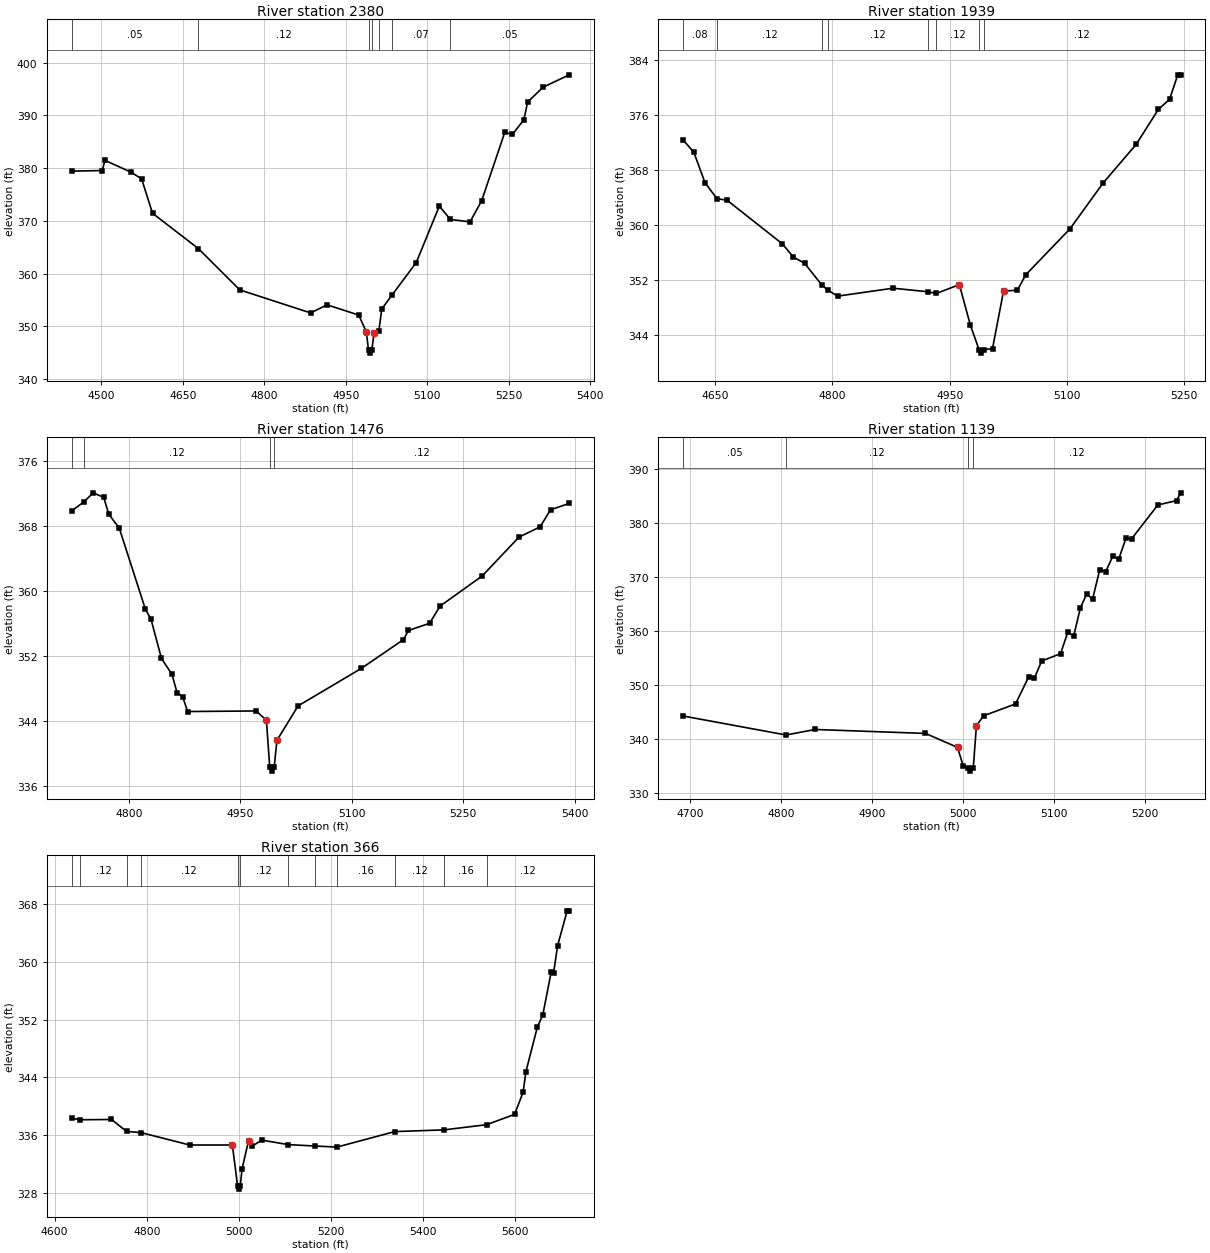
Type RM Length L Ch R = 1 ,2380    ,441,441,441
BEGIN DESCRIPTION:
Mapping XS d9121b45
END DESCRIPTION:
XS GIS Cut Line= 3
      3738289.06     10653741.72      3738337.67     10654259.06
      3738625.22     10654532.75
#Sta/Elev= 30
  4445.2  379.42  4501.7  379.53  4506.7  381.46  4554.1  379.25  4574.2  377.96
  4594.3  371.43  4678.9  364.72    4755   356.9  4885.6  352.53  4915.7  354.07
  4974.1  352.13  4988.2  348.89  4992.1  345.41  4994.9  344.91  4998.1  345.41
  5002.4  348.77  5011.1  349.06  5016.5  353.28    5035  355.87    5080  362.08
  5122.5  372.79  5142.9  370.26  5179.1   369.8  5200.5  373.81    5243  386.76
  5257.2  386.38  5278.2  389.16  5285.1  392.51  5313.4  395.32  5361.8  397.68
#Mann= 7 ,-1 , 0
  4445.2     .05       0  4678.9     .12       0  4992.1     .07       0
  4998.1     .12       0  5011.1     .05       0    5035     .07       0
  5142.9     .05       0
Bank Sta=4988.2,5002.4
XS Rating Curve= 0 ,0
Exp/Cntr=0.3,0.1

Type RM Length L Ch R = 1 ,1939    ,463,463,463
BEGIN DESCRIPTION:
UNT 149 IN BOCR 3.0
END DESCRIPTION:
XS GIS Cut Line= 3
      3737849.61     10654160.19      3738149.61     10654460.19
      3738299.61     10654610.19
#Sta/Elev= 30
  4608.8  372.35  4622.9  370.51  4637.1  366.11  4652.3  363.78  4665.4  363.54
  4736.1   357.2  4750.2  355.27  4764.4  354.38    4787  351.16  4794.9  350.42
  4806.8   349.6  4877.5  350.75  4921.7  350.24    4933  349.99  4962.4  351.27
  4976.5  345.37  4987.6  341.81  4990.4  341.31  4993.6  341.81  5004.8  341.97
  5018.9  350.34  5036.6  350.45  5047.2  352.69  5103.8  359.38  5146.2  366.05
  5188.6  371.68  5216.9  376.76  5231.1  378.21  5241.7  381.78  5245.2  381.78
#Mann= 8 ,-1 , 0
  4608.8     .08       0  4652.3     .12       0    4787     .16       0
  4794.9     .12       0  4921.7     .16       0    4933     .12       0
  4987.6     .07       0  4993.6     .12       0
Bank Sta=4962.4,5018.9
XS Rating Curve= 0 ,0
Exp/Cntr=0.3,0.1

Type RM Length L Ch R = 1 ,1476    ,337,337,337
BEGIN DESCRIPTION:
UNT 149 IN BOCR 2.0
END DESCRIPTION:
XS GIS Cut Line= 2
      3737627.62     10654561.41      3738122.45     10655012.83
#Sta/Elev= 30
  4722.7  369.88  4739.6  371.03  4751.8  372.12    4766  371.56  4772.8  369.49
    4787  367.76  4822.1  357.79  4829.5  356.61  4843.7  351.75  4857.9  349.78
  4864.7  347.54  4872.1  347.06  4878.9  345.22  4970.8  345.29  4984.9  344.17
  4989.4  338.39  4992.1  337.89  4995.4  338.39  4999.1  341.67  5027.5  345.91
  5112.6  350.52  5169.4  354.07  5176.1  355.19  5204.5  356.07  5218.7  358.19
  5275.4   361.9  5324.8  366.67  5353.2  367.93  5367.3  370.03  5392.5  370.82
#Mann= 4 ,-1 , 0
  4722.7     .16       0  4739.6     .12       0  4989.4     .07       0
  4995.4     .12       0
Bank Sta=4984.9,4999.1
XS Rating Curve= 0 ,0
Exp/Cntr=0.3,0.1

Type RM Length L Ch R = 1 ,1139    ,773,773,773
BEGIN DESCRIPTION:
Mapping XS 492e3424
END DESCRIPTION:
XS GIS Cut Line= 2
      3737371.72      10654773.2      3737794.75      10655120.3
#Sta/Elev= 30
  4691.9  344.23  4805.4   340.7  4837.4  341.72  4958.7  340.99  4993.9   338.4
  5000.3   334.9  5005.2   334.5    5008     334  5011.2   334.5  5014.7  342.41
  5022.6  344.26  5057.7  346.46  5072.1  351.45  5078.5  351.26  5086.4  354.42
  5107.2  355.78  5115.1  359.74  5121.6  359.03    5129  364.27  5135.9  366.83
  5142.4   365.9  5150.3  371.36  5156.8  370.99  5164.6  373.82  5171.1  373.28
    5179  377.14  5185.5  377.12  5214.2  383.35    5235  384.17  5239.1   385.6
#Mann= 4 ,-1 , 0
  4691.9     .05       0  4805.4     .12       0  5005.2     .07       0
  5011.2     .12       0
Bank Sta=4993.9,5014.7
XS Rating Curve= 0 ,0
Exp/Cntr=0.3,0.1

Type RM Length L Ch R = 1 ,366     ,0,0,0
BEGIN DESCRIPTION:
UNT 149 IN BOCR 1.0
END DESCRIPTION:
XS GIS Cut Line= 4
      3737234.83     10655032.98      3737029.09     10655246.54
      3737206.17     10655439.25      3737693.16     10655251.74
#Sta/Elev= 30
  4636.9  338.33  4656.3  338.12  4723.5  338.16  4756.2  336.51  4787.6  336.34
  4893.3  334.62  4985.9  334.62  4997.1     329  4999.9   328.5  5003.1     329
  5006.9   331.3  5021.1  335.23  5028.5  334.43  5049.5   335.3  5107.5  334.67
  5164.9  334.48  5212.8  334.33  5338.2  336.48  5445.9  336.72  5537.7  337.44
  5598.4  338.87  5616.8  341.94    5623  344.81  5647.6  350.94  5659.6  352.67
  5677.6  358.55    5683   358.5  5691.8  362.28  5712.4   367.1    5717   367.1
#Mann= 12 ,-1 , 0
  4636.9     .05       0  4656.3     .12       0  4756.2     .05       0
  4787.6     .12       0  4997.1     .07       0  5003.1     .12       0
  5107.5     .16       0  5164.9     .12       0  5212.8     .16       0
  5338.2     .12       0  5445.9     .16       0  5537.7     .12       0
Bank Sta=4985.9,5021.1
XS Rating Curve= 0 ,0
Exp/Cntr=0.3,0.1

Chan Stop Cuts=-1
Use User Specified Reach Order=0
Composite Channel Slope=5