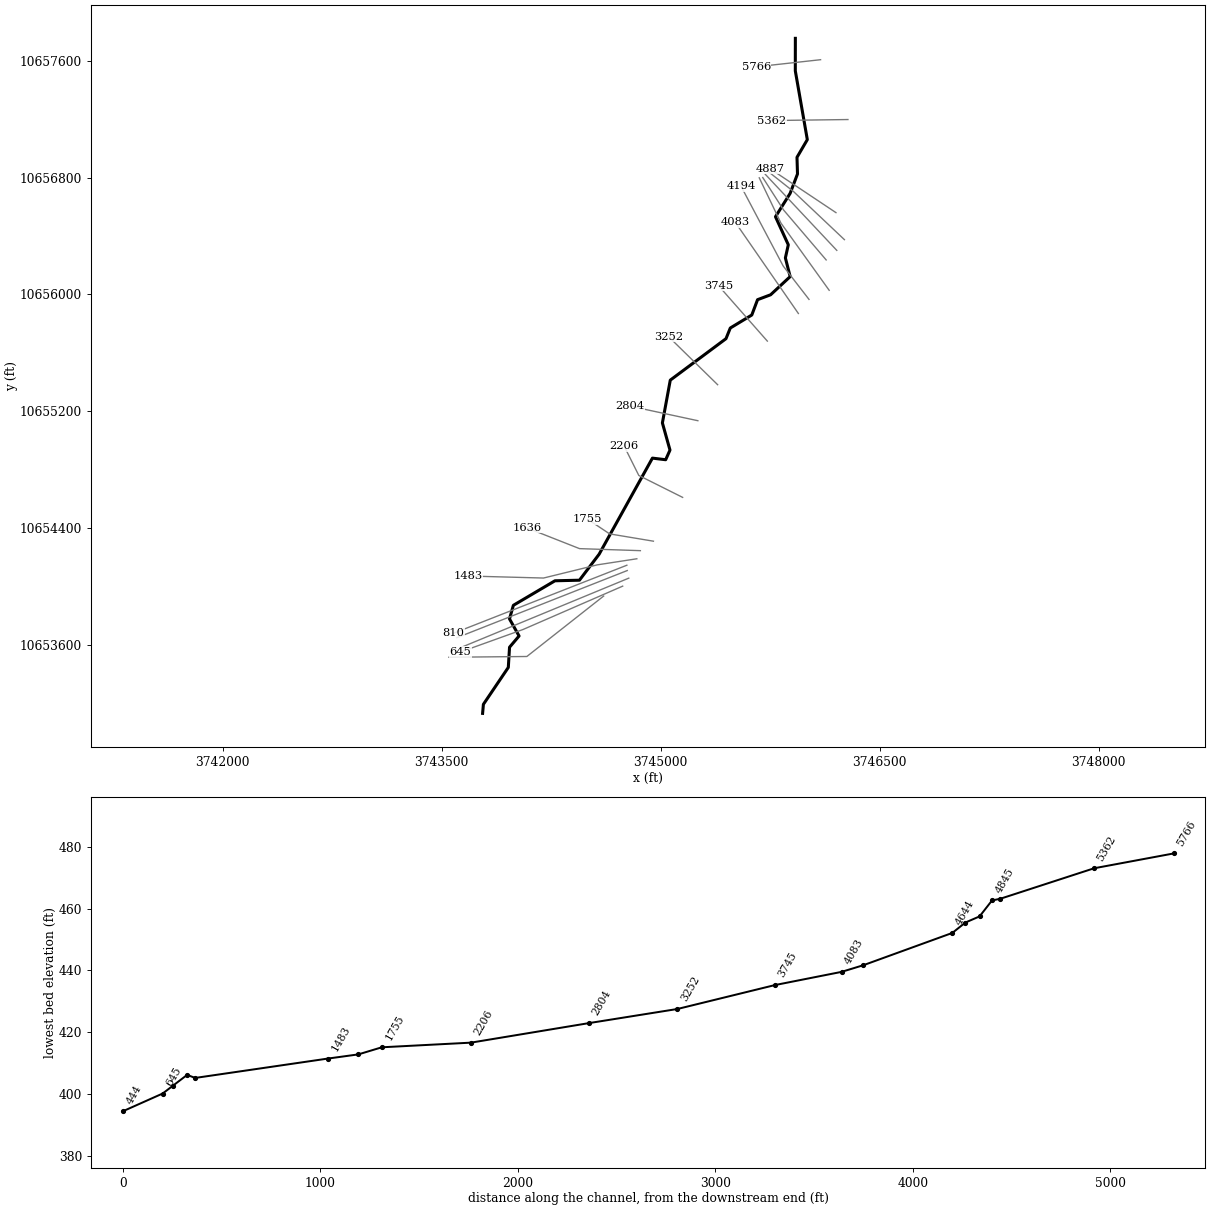
--- UNT 151 IN BOCR.prj (project) ---

Proj Title=UNT 151 IN BOCR Base Level Engineering
Current Plan=p01
Default Exp/Contr=0.3,0.1
English Units
Geom File=g01
Flow File=f01
Plan File=p01
Y Axis Title=Elevation
X Axis Title(PF)=Main Channel Distance
X Axis Title(XS)=Station
BEGIN DESCRIPTION:
UNT 151 IN BOCR
END DESCRIPTION:
DSS Export Rating Curves= 0
DSS Export Rating Curve Sorted= 0
DSS Export Volume Flow Curves= 0
DXF OffsetX= 0
DXF OffsetY= 0
DXF ScaleX= 1
DXF ScaleY= 10

--- UNT 151 IN BOCR.p01 (plan) ---

Plan Title=Multiple Run
Program Version=4.10
Short Identifier=Multiple
Geom File=g01
Flow File=f01
Subcritical Flow
K Sum by GR= 0
Std Step Tol= 0.01
Critical Tol= 0.01
Num of Std Step Trials= 20
Max Error Tol= 0.3
Flow Tol Ratio= 0.001
Split Flow NTrial= 30
Split Flow Tol= 0.02
Split Flow Ratio= 0.02
Log Output Level= 0
Friction Slope Method= 1
Unsteady Friction Slope Method= 2
Unsteady Bridges Friction Slope Method= 1
Parabolic Critical Depth
Global Vel Dist= 1 , 1 , 1
Global Log Level= 0
CheckData=True
Encroach Param=-1 ,0,0, 0
BEGIN DESCRIPTION:
Multiple Run
END DESCRIPTION:
Computation Interval=1HOUR
Output Interval=1HOUR
Run HTab= 0
Run UNet= 0
Run PostProcess= 0
Run WQNet= 0
UNET Theta= 1
UNET Theta Warmup= 1
UNET ZTol= 0.02
UNET ZSATol= 0.05
UNET MxIter= 20
UNET MaxInSteps= 0
UNET DtIC= 0
UNET DtMin= 0
UNET MaxCRTS= 20
UNET WFStab= 2
UNET SFStab= 1
UNET WFX= 1
UNET SFX= 1
UNET DSS MLevel= 4
UNET DZMax Abort= 100
UNET Convert EG Bridges= 0
UNET Use Existing IB Tables=-1
UNET Froude Reduction=False
UNET Froude Limit= 1
UNET Froude Power= 10
UNET Time Slicing=0,0, 5
UNET Junction Losses=0
Instantaneous Interval=1HOUR
Write IC File= 0
Write IC File at Sim End=0
Echo Input=False
Echo Parameters=False
Echo Output=False
Write Detailed= 0
WQ AD Non Conservative
WQ ULTIMATE=-1
WQ Max Comp Step=1HOUR
WQ Output Interval=15MIN
WQ Output Selected Increments= 0
WQ Output face flow=0
WQ Output face velocity=0
WQ Output face area=0
WQ Output face dispersion=0
WQ Output cell volume=0
WQ Output cell surface area=0
WQ Output cell continuity=0
WQ Output cumulative cell continuity=0
WQ Output face conc=0
WQ Output face dconc_dx=0
WQ Output face courant=0
WQ Output face peclet=0
WQ Output face adv mass=0
WQ Output face disp mass=0
WQ Output cell mass=0
WQ Output cell source sink temp=0
WQ Output cell source sink nsm=0
WQ Output MaxMinRange=-1
WQ Daily Max Min Mean=-1
WQ Daily Range=0
WQ Daily Time=0
WQ Create Restart=0
WQ Fixed Restart=0
WQ System Summary=0
WQ Use Fixed Temperature=0
Sorting and Armoring Iterations= 10
XS Update Threshold= 0.02
Hydraulics Update Threshold= 0.02
Energy Slope Method= 1
Volume Change Method= 0
XS Weighting Method= 0
Number of US Weighted Cross Sections= 1
Number of DS Weighted Cross Sections= 1
Upstream XS Weight=0.25
Main XS Weight=0.5
Downstream XS Weight=0.25
Number of DS XS's Weighted with US Boundary= 1
Upstream Boundary Weight= 1
Weight of XSs Associated with US Boundary= 0
Number of US XS's Weighted with DS Boundary= 1
Downstream Boundary Weight= 0.5
Weight of XSs Associated with DS Boundary= 0.5
Sediment Output Level= 4
Mass or Volume Output= 0
Output Increment Type= 1
Profile and TS Output Increment= 10
XS Output Flag= 0
XS Output Increment= 10
Disregard all LS=0
Disregard all Conn=0
Disregard all Breaches=0
Disregard all Pumps=0

--- UNT 151 IN BOCR.f01 (steady flow) ---

Flow Title=Multiple
Number of Profiles=7
Profile Names=10-year,25-year,50-year,1pct_min,100-year,1pct_plu,500-year
River Rch & RM= UNT 151 IN BOCR,Reach-1,5766
     635     873    1074     973    1315    1779    1978
Boundary for River Rch & Prof#=UNT 151 IN BOCR,Reach-1,1
Up Type=0
Dn Type=3
Dn Slope=0.005
Boundary for River Rch & Prof#=UNT 151 IN BOCR,Reach-1,2
Up Type=0
Dn Type=3
Dn Slope=0.005
Boundary for River Rch & Prof#=UNT 151 IN BOCR,Reach-1,3
Up Type=0
Dn Type=3
Dn Slope=0.005
Boundary for River Rch & Prof#=UNT 151 IN BOCR,Reach-1,4
Up Type=0
Dn Type=3
Dn Slope=0.005
Boundary for River Rch & Prof#=UNT 151 IN BOCR,Reach-1,5
Up Type=0
Dn Type=3
Dn Slope=0.005
Boundary for River Rch & Prof#=UNT 151 IN BOCR,Reach-1,6
Up Type=0
Dn Type=3
Dn Slope=0.005
Boundary for River Rch & Prof#=UNT 151 IN BOCR,Reach-1,7
Up Type=0
Dn Type=3
Dn Slope=0.005

--- UNT 151 IN BOCR.g01 (geometry) ---

Geom Title=Existing Conditions
Program Version=4.10

River Reach=UNT 151 IN BOCR ,Reach-1
Reach XY= 30
      3745921.57     10657753.77      3745921.25       10657531.
       3746003.5       10657060.      3745932.75       10656939.
      3745936.25       10656825.      3745885.75       10656692.
       3745785.5       10656532.      3745873.25       10656340.
      3745853.25       10656250.        3745886.       10656122.
      3745752.16     10655997.65      3745662.75       10655964.
      3745623.25       10655859.        3745476.       10655770.
       3745446.5       10655697.        3745065.       10655413.
        3745011.       10655120.        3745063.       10654934.
       3745033.5       10654868.      3744942.75       10654879.
      3744577.75       10654221.        3744443.       10654043.
      3744275.25       10654039.       3743990.5       10653871.
        3743964.       10653778.       3744029.5       10653661.
      3743964.25       10653584.      3743955.82     10653445.63
      3743785.25       10653193.      3743779.75       10653131.

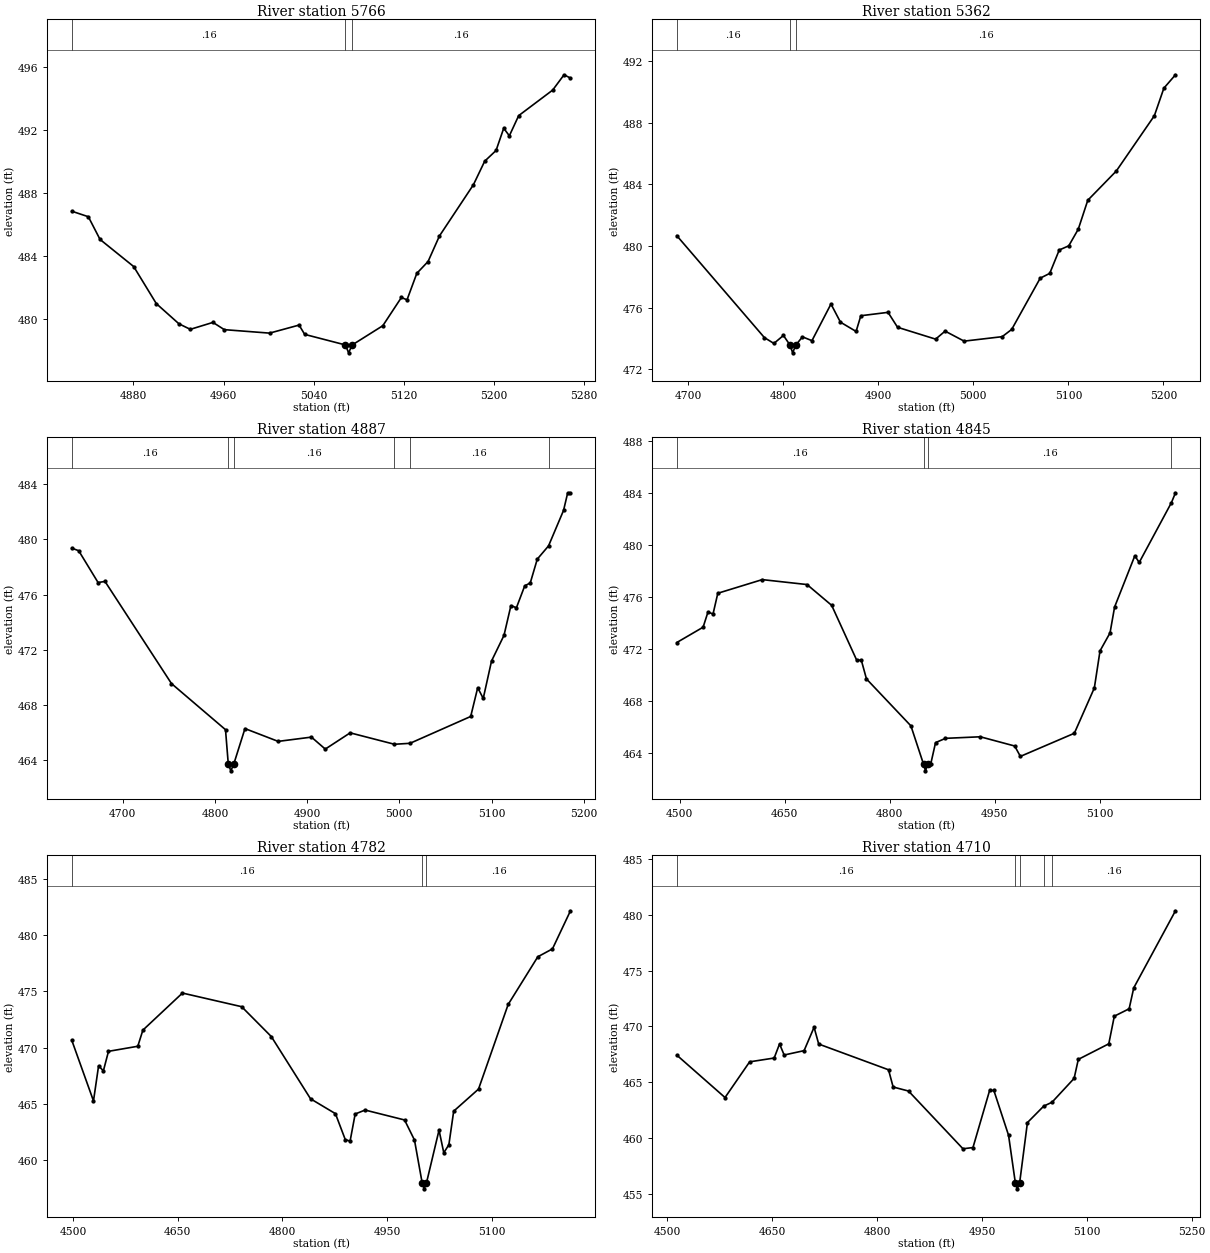
Type RM Length L Ch R = 1 ,5766    ,404,404,404
BEGIN DESCRIPTION:
UNT 151 IN BOCR 11.0
END DESCRIPTION:
XS GIS Cut Line= 2
      3746094.24     10657607.43      3745653.91     10657558.89
#Sta/Elev= 30
  4825.2  486.85  4839.9   486.5  4850.3  485.06  4880.2  483.34  4900.3  480.99
  4920.4  479.71  4930.5  479.36  4950.6   479.8  4960.7  479.34  5000.9  479.12
  5027.1  479.63  5032.1  479.04  5068.3  478.37  5071.1  477.87  5074.3  478.37
  5101.5  479.59    5118  481.38    5123  481.23  5131.7  482.91  5141.7  483.66
  5151.8  485.28    5182  488.53    5192  490.02  5202.1   490.7  5208.9  492.11
  5213.9  491.63  5222.2  492.91  5252.4  494.53  5262.5   495.5  5268.2  495.29
#Mann= 3 ,-1 , 0
  4825.2     .16       0  5068.3     .07       0  5074.3     .16       0
Bank Sta=5068.3,5074.3
XS Rating Curve= 0 ,0
Exp/Cntr=0.3,0.1

Type RM Length L Ch R = 1 ,5362    ,475,475,475
BEGIN DESCRIPTION:
UNT 151 IN BOCR 10.0
END DESCRIPTION:
XS GIS Cut Line= 2
      3746281.69      10657197.7      3745757.44     10657190.76
#Sta/Elev= 30
  4688.3  480.67  4780.4  474.05  4790.4  473.67  4800.4  474.19  4807.4  473.56
  4810.1  473.06  4813.4  473.56  4820.4   474.1  4830.4  473.85  4850.4  476.23
  4860.4  475.05  4876.8  474.45  4881.8  475.47  4910.4  475.69  4920.4  474.72
  4960.4  473.95  4970.4  474.47  4990.4  473.82  5030.4  474.11  5040.4  474.58
  5070.4  477.91  5080.4  478.22  5090.4  479.74  5100.4  480.01  5110.4  481.09
  5120.4  482.97  5150.4  484.87  5190.4  488.46  5200.4  490.25  5212.6  491.12
#Mann= 3 ,-1 , 0
  4688.3     .16       0  4807.4     .07       0  4813.4     .16       0
Bank Sta=4807.4,4813.4
XS Rating Curve= 0 ,0
Exp/Cntr=0.3,0.1

Type RM Length L Ch R = 1 ,4887    ,42,42,42
BEGIN DESCRIPTION:
UNT 151 IN BOCR 9.0
END DESCRIPTION:
XS GIS Cut Line= 3
      3746199.59      10656560.2      3745899.61     10656760.19
      3745749.62     10656860.18
#Sta/Elev= 30
  4644.8  479.37  4652.3  479.18  4673.3  476.87  4680.8  476.95  4752.9  469.53
  4811.5  466.18  4814.5  463.69  4817.3  463.19  4820.5  463.69  4832.6  466.26
  4868.6  465.33  4904.7  465.64  4919.7  464.77  4946.7  465.95  4994.7  465.12
  5011.6  465.19  5077.4  467.14    5085  469.23    5091  468.45    5100  471.17
  5113.5  473.03    5121  475.19    5127  475.04    5136  476.63    5142  476.84
  5149.6  478.57  5161.8  479.53  5178.1  482.11  5182.6  483.39  5185.6  483.39
#Mann= 6 ,-1 , 0
  4644.8     .16       0  4814.5     .07       0  4820.5     .16       0
  4994.7     .12       0  5011.6     .16       0  5161.8      .1       0
Bank Sta=4814.5,4820.5
XS Rating Curve= 0 ,0
Exp/Cntr=0.3,0.1

Type RM Length L Ch R = 1 ,4845    ,63,63,63
BEGIN DESCRIPTION:
Mapping XS 32ad67a4
END DESCRIPTION:
XS GIS Cut Line= 3
      3746257.48     10656375.16      3745908.53       10656705.
      3745726.27     10656849.08
#Sta/Elev= 30
    4496  472.51  4533.6  473.69  4540.5  474.85  4547.8  474.71  4554.6   476.3
  4618.1  477.35  4682.1  476.97  4717.3  475.37  4752.9  471.17  4759.7  471.14
    4767  469.71  4830.5   466.1  4848.6  463.14  4851.3  462.64  4854.6  463.14
  4858.8  463.16  4865.7  464.81  4879.9  465.14  4929.6  465.26  4978.8  464.55
  4986.9  463.75    5064  465.53  5092.6  469.02  5100.7  471.87    5115  473.25
  5121.5  475.24  5150.4  479.18  5156.7  478.67  5202.7  483.27  5208.5  484.03
#Mann= 4 ,-1 , 0
    4496     .16       0  4848.6     .07       0  4854.6     .16       0
  5202.7      .1       0
Bank Sta=4848.6,4854.6
XS Rating Curve= 0 ,0
Exp/Cntr=0.3,0.1

Type RM Length L Ch R = 1 ,4782    ,72,72,72
BEGIN DESCRIPTION:
Mapping XS c0b11e23
END DESCRIPTION:
XS GIS Cut Line= 2
      3746205.22     10656301.77      3745715.64      10656822.6
#Sta/Elev= 30
  4498.1  470.66  4529.2  465.28  4536.5  468.39  4543.4  467.95  4550.7  469.68
  4592.7  470.13    4600  471.56  4656.7  474.85  4741.6  473.64  4784.1  470.99
  4840.3  465.47    4876  464.15  4890.1  461.85    4897  461.71  4904.3  464.12
  4918.5  464.47  4975.1  463.59  4989.3  461.81  5000.4  457.98  5003.2  457.48
  5006.4  457.98  5024.5  462.69  5031.3  460.68  5038.6  461.39  5045.5  464.37
  5081.1  466.33  5123.6  473.84  5166.1  478.07  5187.1  478.77  5212.9  482.15
#Mann= 3 ,-1 , 0
  4498.1     .16       0  5000.4     .07       0  5006.4     .16       0
Bank Sta=5000.4,5006.4
XS Rating Curve= 0 ,0
Exp/Cntr=0.3,0.1

Type RM Length L Ch R = 1 ,4710    ,66,66,66
BEGIN DESCRIPTION:
Mapping XS 6847519d
END DESCRIPTION:
XS GIS Cut Line= 3
      3746132.49     10656236.26      3745840.82     10656578.27
      3745698.46     10656800.49
#Sta/Elev= 30
  4513.4  467.44  4582.4  463.65  4617.6  466.84  4652.7  467.18  4660.4  468.44
    4667  467.45  4695.5  467.84  4709.8  469.93  4716.4  468.43  4816.3  466.13
  4822.9  464.59  4844.9  464.23  4922.8  459.07  4937.1  459.18  4960.9  464.28
    4967  464.28    4988  460.28  4997.8  455.99  5000.5  455.49  5003.8  455.99
    5015  461.41  5038.3  462.88  5050.2  463.23  5081.8  465.36  5087.8  467.06
  5131.4  468.45  5139.3  470.92  5160.5  471.58  5167.1  473.45  5226.8  480.34
#Mann= 5 ,-1 , 0
  4513.4     .16       0  4997.8     .07       0  5003.8     .16       0
  5038.3     .05       0  5050.2     .16       0
Bank Sta=4997.8,5003.8
XS Rating Curve= 0 ,0
Exp/Cntr=0.3,0.1

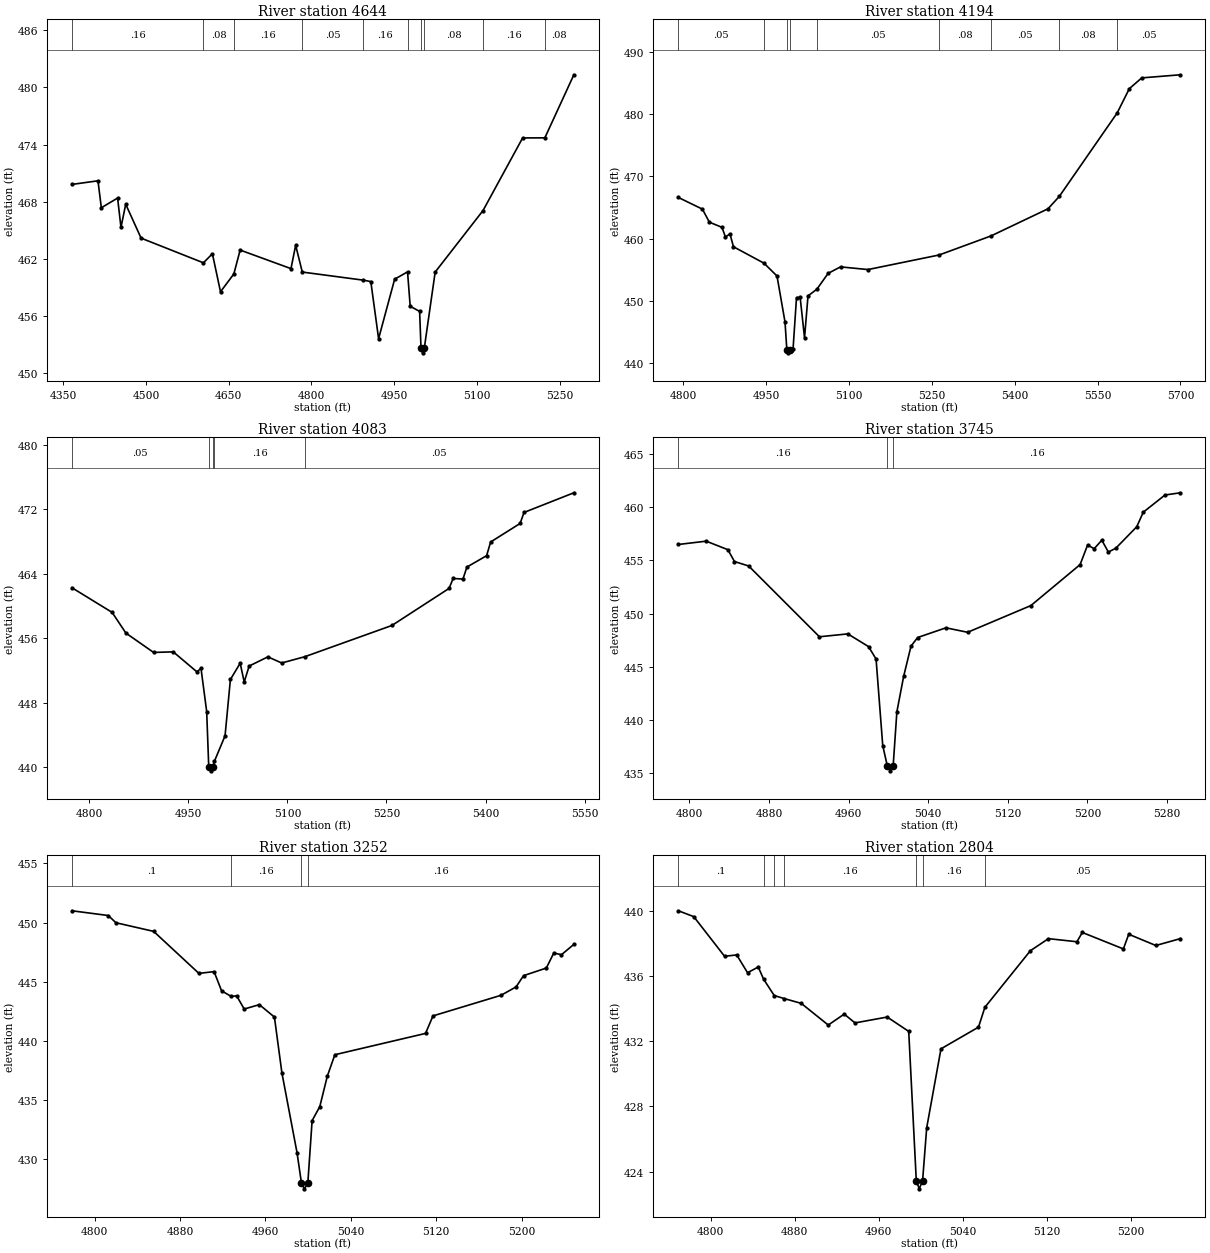
Type RM Length L Ch R = 1 ,4644    ,450,450,450
BEGIN DESCRIPTION:
UNT 151 IN BOCR 8.0
END DESCRIPTION:
XS GIS Cut Line= 3
      3746153.14     10656028.32      3745822.39     10656489.29
      3745674.28      10656798.5
#Sta/Elev= 30
  4365.8  469.81    4413  470.19  4419.1  467.36  4448.6  468.38  4454.7   465.3
  4463.3  467.73  4491.2  464.17  4604.2  461.58  4620.5  462.53  4635.2  458.54
  4659.4  460.41  4670.8  462.92    4763  460.97  4771.5  463.42  4783.5  460.61
  4894.2  459.76  4907.8  459.61  4921.9  453.62    4951  459.86  4974.4  460.63
  4979.2  457.02  4996.3  456.48  4998.8  452.63  5001.6  452.13  5004.8  452.63
  5024.5  460.61  5111.3  467.07  5183.1  474.69  5223.4   474.7    5276  481.32
#Mann= 10 ,-1 , 0
  4365.8     .16       0  4604.2     .08       0  4659.4     .16       0
  4783.5     .05       0  4894.2     .16       0  4974.4     .08       0
  4998.8     .07       0  5004.8     .08       0  5111.3     .16       0
  5223.4     .08       0
Bank Sta=4998.8,5004.8
XS Rating Curve= 0 ,0
Exp/Cntr=0.3,0.1

Type RM Length L Ch R = 1 ,4194    ,111,111,111
BEGIN DESCRIPTION:
UNT 151 IN BOCR 7.0
END DESCRIPTION:
XS GIS Cut Line= 3
      3746015.08     10655965.87      3745838.01     10656195.02
      3745548.93     10656741.92
#Sta/Elev= 30
  4791.5  466.63  4834.9  464.76  4847.6  462.66  4870.3  461.84  4876.6  460.29
  4884.8  460.79  4891.1  458.72  4946.4  456.08  4969.9  454.02  4984.4  446.64
  4987.7  442.19  4990.4  441.69  4993.7  442.19  4998.9  442.26  5005.2  450.56
  5011.8  450.59  5019.7  444.11    5026  450.83  5042.1  451.91  5062.4  454.45
  5084.8  455.49  5134.5  455.06  5263.3   457.4  5357.2  460.46  5460.2  464.81
  5480.7   466.8  5585.5  480.21  5607.4   484.1  5629.9  485.83  5699.7  486.33
#Mann= 9 ,-1 , 0
  4791.5     .05       0  4946.4     .16       0  4987.7     .07       0
  4993.7     .16       0  5042.1     .05       0  5263.3     .08       0
  5357.2     .05       0  5480.7     .08       0  5585.5     .05       0
Bank Sta=4987.7,4993.7
XS Rating Curve= 0 ,0
Exp/Cntr=0.3,0.1

Type RM Length L Ch R = 1 ,4083    ,338,338,338
BEGIN DESCRIPTION:
Mapping XS b4f6b264
END DESCRIPTION:
XS GIS Cut Line= 2
      3745942.17     10655869.52      3745509.89     10656494.49
#Sta/Elev= 30
  4773.8  462.25  4834.6  459.19  4855.5  456.62  4897.4  454.22  4927.2  454.29
    4963  451.81  4969.2  452.24  4977.8  446.88  4980.9  440.02  4983.7  439.52
  4986.9  440.02  4989.5  440.71  5005.6  443.87  5013.7  450.86  5028.5  452.88
  5034.6  450.55  5042.1  452.53  5070.4  453.67  5091.4  452.91  5126.4  453.69
  5258.3  457.57  5344.8  462.17  5350.9   463.4  5365.8  463.33  5371.8  464.82
  5401.6  466.23  5407.7  467.93  5452.3  470.23  5458.3   471.6  5533.7  474.04
#Mann= 5 ,-1 , 0
  4773.8     .05       0  4980.9     .07       0  4986.9     .05       0
  4989.5     .16       0  5126.4     .05       0
Bank Sta=4980.9,4986.9
XS Rating Curve= 0 ,0
Exp/Cntr=0.3,0.1

Type RM Length L Ch R = 1 ,3745    ,493,493,493
BEGIN DESCRIPTION:
UNT 151 IN BOCR 6.0
END DESCRIPTION:
XS GIS Cut Line= 2
       3745729.6     10655680.37      3745396.29     10656058.82
#Sta/Elev= 30
    4789  456.48  4816.9  456.79  4838.7  455.99  4845.3  454.88  4859.6  454.46
  4930.7  447.82  4959.2  448.09    4980   446.9  4987.6  445.73  4994.3  437.61
  4998.8  435.74  5001.6  435.24  5004.8  435.74  5008.5  440.78  5015.3   444.1
  5022.7  446.94  5029.4  447.75  5057.8  448.66  5079.6  448.24  5143.2  450.75
  5192.6  454.59  5200.1  456.42  5206.8  456.09  5214.4  456.88    5221  455.77
  5228.5  456.13  5249.5  458.14  5256.1  459.51  5277.9  461.12  5293.3  461.33
#Mann= 3 ,-1 , 0
    4789     .16       0  4998.8     .07       0  5004.8     .16       0
Bank Sta=4998.8,5004.8
XS Rating Curve= 0 ,0
Exp/Cntr=0.3,0.1

Type RM Length L Ch R = 1 ,3252    ,448,448,448
BEGIN DESCRIPTION:
UNT 151 IN BOCR 5.0
END DESCRIPTION:
XS GIS Cut Line= 2
      3745389.33     10655381.76      3745053.54     10655710.62
#Sta/Elev= 30
  4778.8     451  4812.8   450.6    4820  449.99  4855.3  449.26  4897.7  445.71
  4911.9  445.86  4918.9  444.24    4928  443.76    4933  443.82  4940.1   442.7
  4954.3  443.07  4968.4  442.02  4975.4  437.31  4989.6  430.55  4993.7  428.01
  4996.5  427.51  4999.7  428.01  5003.7  433.27  5010.9  434.46  5017.9  437.02
    5025  438.84  5109.9  440.64  5116.9  442.12  5180.6  443.86  5194.7  444.57
  5201.7  445.52    5223  446.16    5230  447.43  5237.2  447.29  5248.8  448.16
#Mann= 4 ,-1 , 0
  4778.8      .1       0    4928     .16       0  4993.7     .07       0
  4999.7     .16       0
Bank Sta=4993.7,4999.7
XS Rating Curve= 0 ,0
Exp/Cntr=0.3,0.1

Type RM Length L Ch R = 1 ,2804    ,598,598,598
BEGIN DESCRIPTION:
UNT 151 IN BOCR 4.0
END DESCRIPTION:
XS GIS Cut Line= 2
      3745253.91     10655135.21      3744786.87     10655235.54
#Sta/Elev= 30
  4769.3     440  4783.9  439.64  4813.2  437.21  4824.8  437.29  4835.1   436.2
  4845.3  436.55  4850.4   435.8  4860.5   434.8  4870.2  434.61  4886.2  434.32
  4911.9  432.99  4927.1  433.66  4937.4  433.12    4968  433.48  4988.5   432.6
  4995.7  423.44  4998.5  422.94  5001.7  423.44  5005.6  426.68  5019.2  431.53
  5054.9  432.86    5061  434.08  5104.3  437.55  5121.5  438.29  5148.6   438.1
  5153.7  438.67  5192.8  437.66  5197.9  438.56  5223.7  437.87    5247  438.29
#Mann= 7 ,-1 , 0
  4769.3      .1       0  4850.4     .16       0  4860.5     .12       0
  4870.2     .16       0  4995.7     .07       0  5001.7     .16       0
    5061     .05       0
Bank Sta=4995.7,5001.7
XS Rating Curve= 0 ,0
Exp/Cntr=0.3,0.1

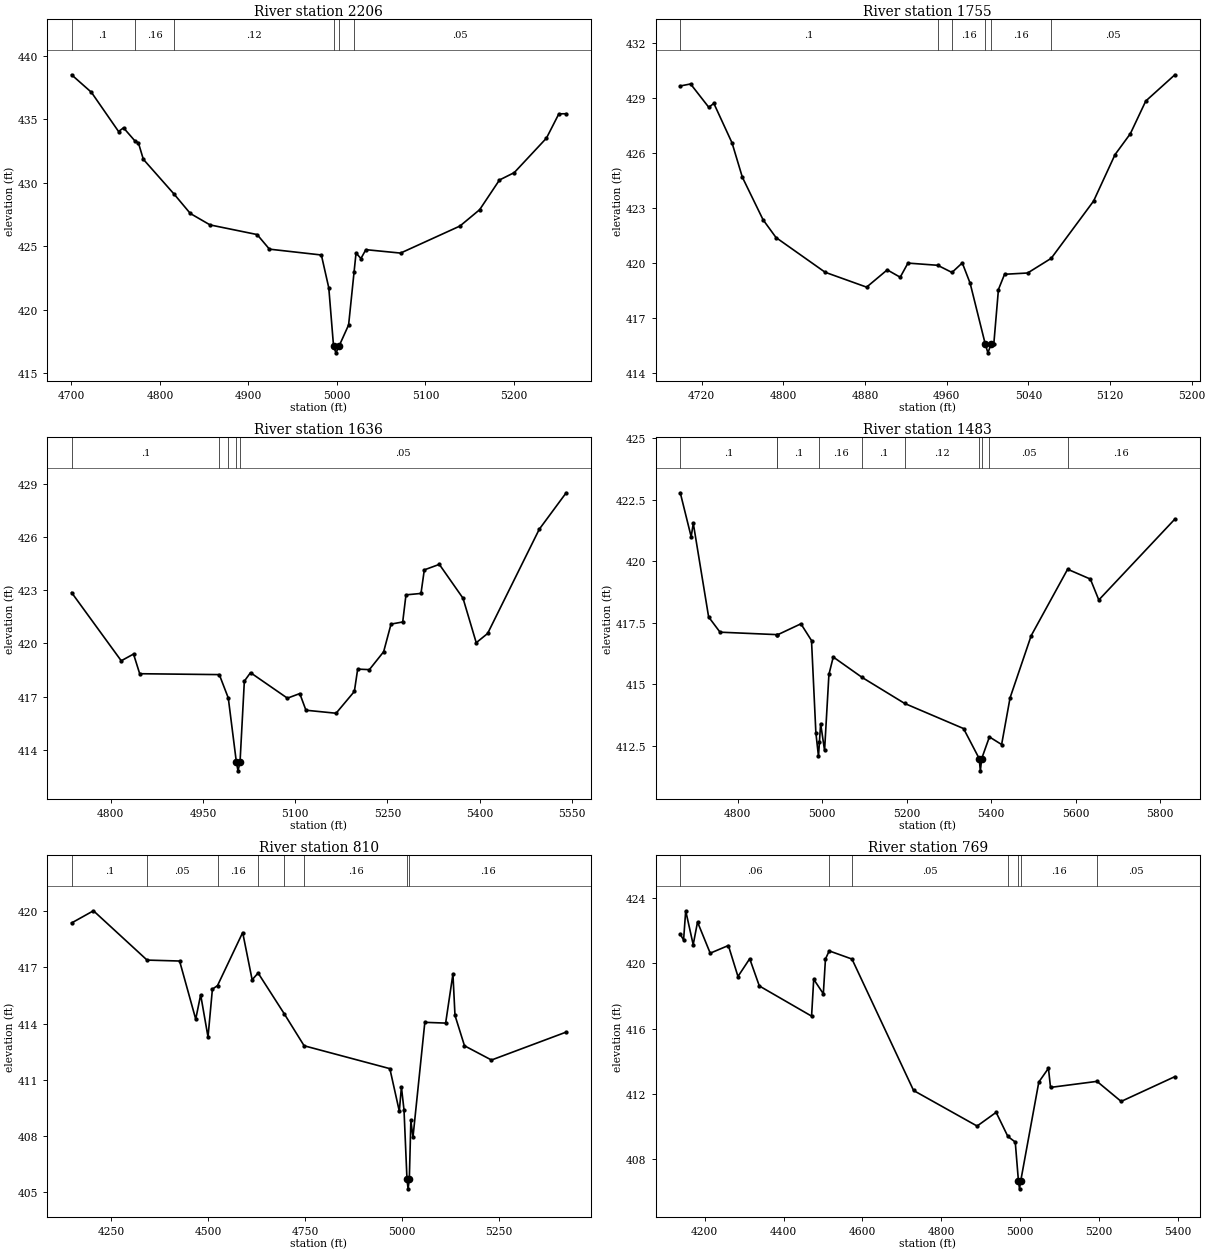
Type RM Length L Ch R = 1 ,2206    ,451,451,451
BEGIN DESCRIPTION:
UNT 151 IN BOCR 3.0
END DESCRIPTION:
XS GIS Cut Line= 3
      3745149.63     10654610.18      3744849.61     10654760.19
      3744749.63     10654960.15
#Sta/Elev= 30
  4700.1  438.52  4722.5  437.14  4753.2  434.05  4758.8  434.34  4771.8   433.3
  4775.6  433.16  4781.2  431.86  4815.8  429.13  4834.3  427.59  4856.6  426.69
  4909.8  425.93  4923.7  424.78  4982.4  424.32  4990.8  421.73  4996.2  417.11
  4998.9  416.61  5002.2  417.11  5013.2  418.81  5019.4     423  5021.6  424.48
  5027.1  424.04  5032.7  424.74  5071.9  424.47    5139   426.6  5161.3  427.89
  5183.7  430.23  5200.4  430.81  5236.8  433.53  5250.8  435.44  5259.1  435.45
#Mann= 6 ,-1 , 0
  4700.1      .1       0  4771.8     .16       0  4815.8     .12       0
  4996.2     .07       0  5002.2     .12       0  5019.4     .05       0
Bank Sta=4996.2,5002.2
XS Rating Curve= 0 ,0
Exp/Cntr=0.3,0.1

Type RM Length L Ch R = 1 ,1755    ,119,119,119
BEGIN DESCRIPTION:
UNT 151 IN BOCR 2.0
END DESCRIPTION:
XS GIS Cut Line= 3
       3744949.6     10654310.19      3744649.61     10654360.19
      3744499.61     10654460.19
#Sta/Elev= 30
  4699.1  429.65  4709.2  429.76    4727  428.49    4732   428.7  4749.8  426.55
  4759.9  424.68  4780.2  422.36  4792.9  421.39    4841   419.5  4881.6  418.69
  4901.8  419.63  4914.5  419.23  4922.1     420  4951.2  419.88  4965.2  419.49
  4975.3  420.01    4983   418.9  4997.7  415.61  5000.4  415.11  5003.7  415.61
  5006.2  415.61  5010.7  418.56  5016.7  419.39  5039.3  419.46  5062.4  420.26
  5103.9  423.38  5124.9  425.91  5139.9  427.05    5155  428.83  5183.5  430.26
#Mann= 6 ,-1 , 0
  4699.1      .1       0  4951.2     .12       0  4965.2     .16       0
  4997.7     .07       0  5003.7     .16       0  5062.4     .05       0
Bank Sta=4997.7,5003.7
XS Rating Curve= 0 ,0
Exp/Cntr=0.3,0.1

Type RM Length L Ch R = 1 ,1636    ,153,153,153
BEGIN DESCRIPTION:
Mapping XS 3521fbfb
END DESCRIPTION:
XS GIS Cut Line= 3
      3744860.26     10654245.31       3744443.6      10654259.2
      3744083.56     10654401.14
#Sta/Elev= 30
  4736.6  422.87  4817.3  419.02  4837.3   419.4  4847.3  418.29  4976.7  418.24
  4991.3  416.92  5004.4  413.31  5007.1  412.81  5010.4  413.31  5017.4  417.87
  5027.4  418.35  5087.4  416.91  5107.5  417.17  5117.5  416.23  5166.5  416.06
  5196.2  417.29  5201.6  418.55  5220.6  418.52  5243.8  419.53  5255.8  421.09
  5274.8  421.21  5280.1  422.74  5304.5  422.82  5309.9  424.15  5334.3  424.46
  5372.8  422.55  5394.3  420.04  5412.8  420.56  5496.7  426.44  5540.5   428.5
#Mann= 5 ,-1 , 0
  4736.6      .1       0  4976.7     .12       0  4991.3     .05       0
  5004.4     .03       0  5010.4     .05       0
Bank Sta=5004.4,5010.4
XS Rating Curve= 0 ,0
Exp/Cntr=0.3,0.1

Type RM Length L Ch R = 1 ,1483    ,673,673,673
BEGIN DESCRIPTION:
Mapping XS ace9ddaa
END DESCRIPTION:
XS GIS Cut Line= 4
      3744835.94     10654189.75      3744565.13     10654148.09
      3744197.07     10654057.81      3743679.72      10654071.7
#Sta/Elev= 30
  4664.1  422.78  4689.9  420.99  4694.9  421.54  4731.2  417.73  4758.2  417.11
  4893.2  417.01  4893.9     417  4949.6  417.45  4974.7  416.77    4985  413.02
  4991.2  412.06  4993.5  412.66  4996.3  413.39  5005.6   412.3  5015.9  415.39
  5026.1   416.1  5094.4  415.27  5195.3  414.21  5334.5  413.19  5371.5  411.97
  5374.3  411.47  5377.5  411.97  5395.7  412.85  5424.6  412.54  5444.6  414.44
  5494.6  416.97  5580.8  419.67  5634.6  419.27  5654.6  418.42  5834.6  421.71
#Mann= 10 ,-1 , 0
  4664.1      .1       0  4893.2     .12       0  4893.9      .1       0
  4993.5     .16       0  5094.4      .1       0  5195.3     .12       0
  5371.5     .07       0  5377.5     .12       0  5395.7     .05       0
  5580.8     .16       0
Bank Sta=5371.5,5377.5
XS Rating Curve= 0 ,0
Exp/Cntr=0.3,0.1

Type RM Length L Ch R = 1 ,810     ,41,41,41
BEGIN DESCRIPTION:
Mapping XS a59d48a3
END DESCRIPTION:
XS GIS Cut Line= 2
       3744767.7     10654145.54      3743580.21      10653679.4
#Sta/Elev= 30
  4147.5  419.37  4203.9  420.02  4342.2  417.39  4426.1  417.34  4467.7  414.24
  4480.4  415.54  4499.4  413.29  4510.7  415.84  4523.9  416.03  4588.8  418.86
  4613.2  416.34  4628.6   416.7  4695.9  414.53  4747.3  412.82  4968.4   411.6
  4992.8  409.33  4998.2  410.62  5004.9   409.4  5012.6  405.69  5015.4  405.19
  5018.6  405.69  5022.6  408.84    5028  407.94  5058.6  414.07  5112.3  414.03
  5131.1  416.65  5136.4  414.44  5160.9  412.82  5230.5  412.06  5423.2  413.55
#Mann= 8 ,-1 , 0
  4147.5      .1       0  4342.2     .05       0  4523.9     .16       0
  4628.6     .12       0  4695.9     .05       0  4747.3     .16       0
  5012.6     .07       0  5018.6     .16       0
Bank Sta=5012.6,5018.6
XS Rating Curve= 0 ,0
Exp/Cntr=0.3,0.1

Type RM Length L Ch R = 1 ,769     ,71,71,71
BEGIN DESCRIPTION:
Mapping XS f3ed9192
END DESCRIPTION:
XS GIS Cut Line= 2
      3744770.34      10654109.1      3743602.79     10653648.84
#Sta/Elev= 30
    4138  421.78  4146.4  421.43  4151.8  423.22  4170.8  421.14  4181.8  422.53
    4214  420.62  4260.1  421.09  4284.4  419.19  4314.2  420.28  4338.6  418.61
  4471.2  416.76  4476.6  419.02    4501  418.13  4506.4  420.26  4515.9  420.76
  4573.7  420.26    4730   412.2  4891.2  410.02  4939.5  410.86  4969.3  409.38
    4988  409.04    4996  406.67  4998.8  406.17    5002  406.67  5047.8  412.72
  5072.2  413.56  5077.5  412.39  5195.4  412.76  5256.7  411.53    5393  413.05
#Mann= 7 ,-1 , 0
    4138     .06       0  4515.9     .16       0  4573.7     .05       0
  4969.3     .16       0    4996     .07       0    5002     .16       0
  5195.4     .05       0
Bank Sta=4996,5002
XS Rating Curve= 0 ,0
Exp/Cntr=0.3,0.1

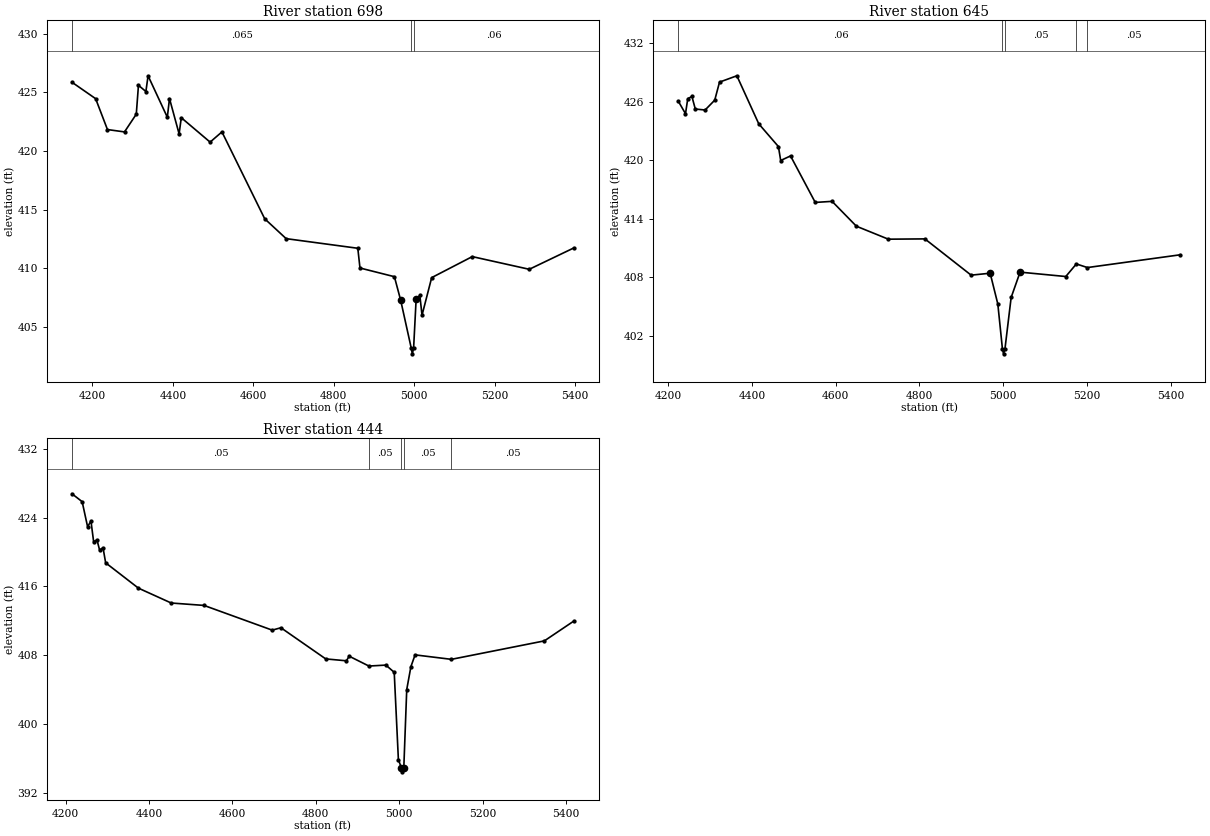
Type RM Length L Ch R = 1 ,698     ,53,53,53
BEGIN DESCRIPTION:
Mapping XS 8d266172
END DESCRIPTION:
XS GIS Cut Line= 2
      3744780.73     10654057.01      3743627.09     10653580.44
#Sta/Elev= 30
  4149.1  425.85    4208  424.45  4237.4  421.82  4279.8  421.62  4309.1  423.13
  4314.5  425.59    4333  425.06  4338.4   426.4  4386.3  422.87  4391.7  424.46
  4415.6  421.45    4421  422.83  4492.7  420.75  4522.1  421.62  4628.5  414.22
  4681.8  412.53    4860  411.71  4865.4  410.03    4951  409.29  4966.5   407.3
  4992.8  403.22  4995.6  402.72  4998.8  403.22  5005.1   407.4  5014.3  407.69
  5019.7  406.01  5043.7  409.21  5144.7     411  5286.4  409.92  5397.3  411.74
#Mann= 3 ,-1 , 0
  4149.1    .065       0  4992.8     .05       0  4998.8     .06       0
Bank Sta=4966.5,5005.1
XS Rating Curve= 0 ,0
Exp/Cntr=0.3,0.1

Type RM Length L Ch R = 1 ,645     ,201,201,201
BEGIN DESCRIPTION:
Mapping XS 244abcca
END DESCRIPTION:
XS GIS Cut Line= 3
       3744739.1     10654002.33      3744056.76     10653705.44
      3743629.68      10653551.8
#Sta/Elev= 30
  4224.7  426.03  4241.6  424.77    4247  426.31  4256.9  426.54    4265  425.25
  4288.4  425.15  4311.4  426.16  4322.8  428.01  4364.2  428.66  4416.5  423.73
  4463.4   421.4  4468.8  419.97  4492.3  420.44  4551.3  415.67  4591.5  415.78
  4649.5  413.23  4725.8   411.9    4813  411.93  4923.4  408.21  4968.8  408.41
  4987.1  405.25  4998.1  400.64  5000.8  400.14  5004.1  400.64  5018.9  405.92
  5040.2  408.52  5149.3  408.07  5174.5  409.36    5201  408.99  5422.7   410.3
#Mann= 5 ,-1 , 0
  4224.7     .06       0  4998.1     .04       0  5004.1     .05       0
  5174.5     .16       0    5201     .05       0
Bank Sta=4968.8,5040.2
XS Rating Curve= 0 ,0
Exp/Cntr=0.3,0.1

Type RM Length L Ch R = 1 ,444     ,0,0,0
BEGIN DESCRIPTION:
UNT 151 IN BOCR 1.0
END DESCRIPTION:
XS GIS Cut Line= 3
      3744608.86     10653934.62       3744082.8     10653520.54
       3743548.9     10653515.33
#Sta/Elev= 30
  4215.4  426.79  4239.9  425.87  4252.9  422.95    4261  423.62  4267.4   421.2
  4275.4  421.42  4281.8  420.22  4289.9  420.51  4296.2  418.75  4374.8   415.8
  4453.4  414.07    4532  413.79  4695.6  410.91  4716.4  411.19  4823.9  407.56
  4873.6  407.34    4880  407.88  4927.4  406.73  4968.1  406.84  4988.1     406
  4998.1  395.82  5005.1  394.91  5007.8  394.41  5011.1  394.91  5018.1  403.99
  5028.1  406.66  5038.1  408.03  5125.2  407.51  5348.1  409.66  5418.8  411.97
#Mann= 5 ,-1 , 0
  4215.4     .05       0  4927.4     .05       0  5005.1     .03       0
  5011.1     .05       0  5125.2     .05       0
Bank Sta=5005.1,5011.1
XS Rating Curve= 0 ,0
Exp/Cntr=0.3,0.1

Chan Stop Cuts=-1
Use User Specified Reach Order=0
Composite Channel Slope=5