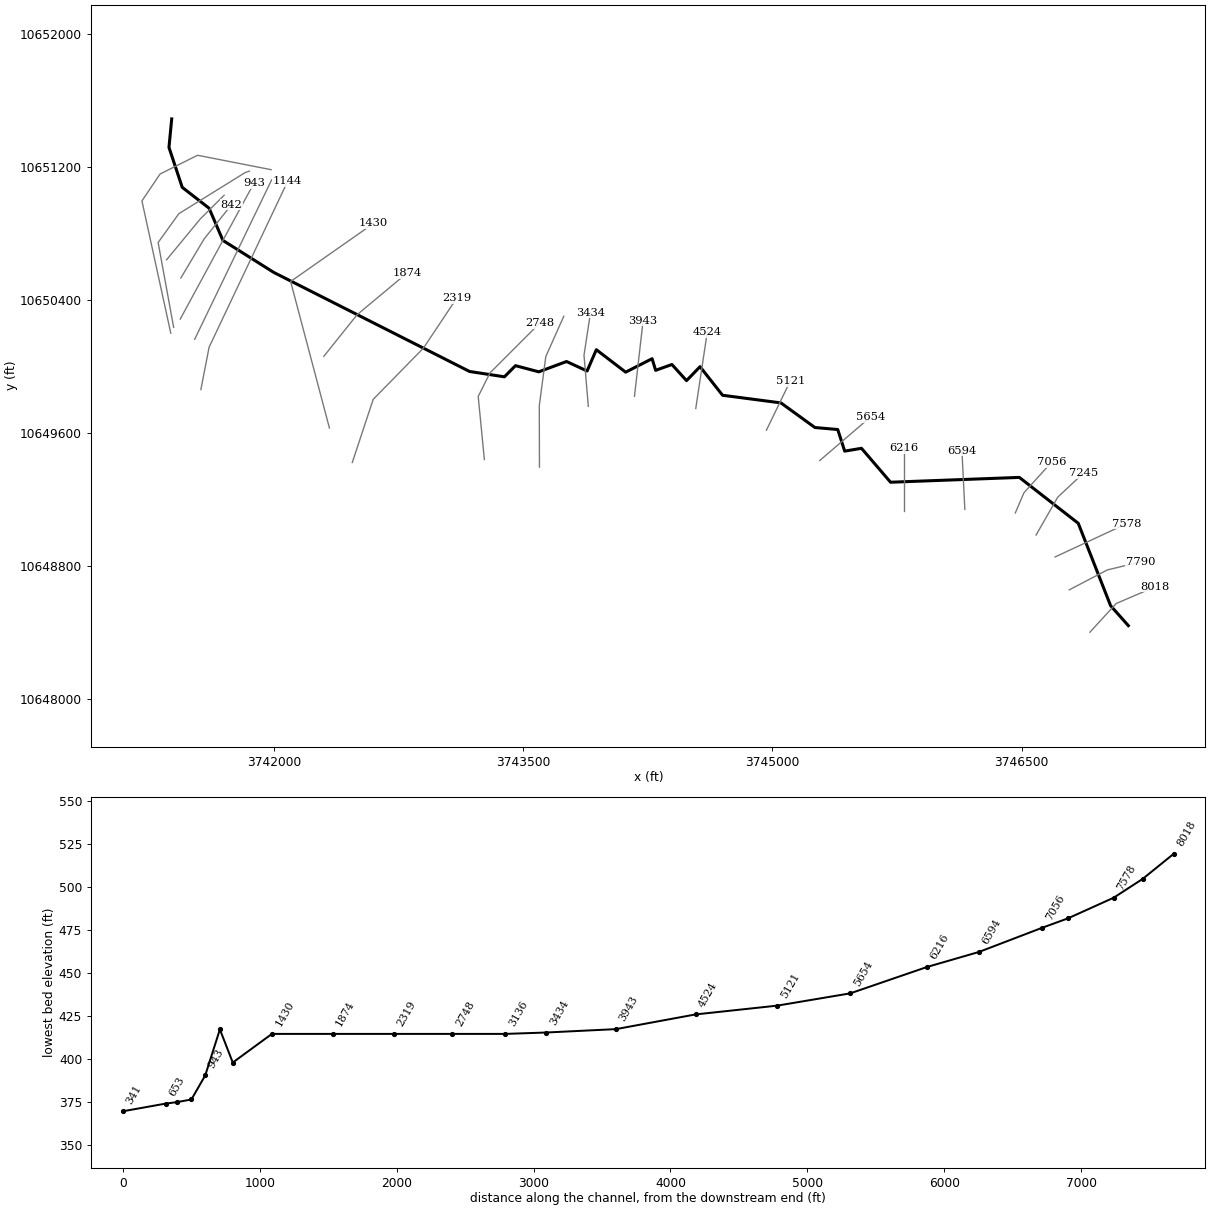
--- UNT 152 IN BOCR.prj (project) ---

Proj Title=UNT 152 IN BOCR Base Level Engineering
Current Plan=p01
Default Exp/Contr=0.3,0.1
English Units
Geom File=g01
Flow File=f01
Plan File=p01
Y Axis Title=Elevation
X Axis Title(PF)=Main Channel Distance
X Axis Title(XS)=Station
BEGIN DESCRIPTION:
UNT 152 IN BOCR
END DESCRIPTION:
DSS Export Rating Curves= 0
DSS Export Rating Curve Sorted= 0
DSS Export Volume Flow Curves= 0
DXF OffsetX= 0
DXF OffsetY= 0
DXF ScaleX= 1
DXF ScaleY= 10

--- UNT 152 IN BOCR.p01 (plan) ---

Plan Title=Multiple Run
Short Identifier=Multiple
Geom File=g01
Flow File=f01
Subcritical Flow
K Sum by GR= 0
Std Step Tol= 0.01
Critical Tol= 0.01
Num of Std Step Trials= 20
Max Error Tol= 0.3
Flow Tol Ratio= 0.001
Split Flow NTrial= 30
Split Flow Tol= 0.02
Split Flow Ratio= 0.02
Log Output Level= 0
Friction Slope Method= 1
Unsteady Friction Slope Method= 2
Unsteady Bridges Friction Slope Method= 1
Parabolic Critical Depth
Global Vel Dist=  1 , 1 , 1
Global Log Level= 0
CheckData=True
Encroach Param= -1, 0, 0, 0
BEGIN DESCRIPTION:
Multiple Run
END DESCRIPTION:

--- UNT 152 IN BOCR.f01 (steady flow) ---

Flow Title=Multiple
Program Version=4.10
Number of Profiles= 7
Profile Names=10-year,25-year,50-year,1pct_min,100-year,1pct_plu,500-year
River Rch & RM=UNT 152 IN BOCR,Reach-1         ,8018
     602     827    1017     922    1247    1686    1877
Boundary for River Rch & Prof#=UNT 152 IN BOCR,Reach-1         , 1
Up Type= 0
Dn Type= 3
Dn Slope=0.015
Boundary for River Rch & Prof#=UNT 152 IN BOCR,Reach-1         , 2
Up Type= 0
Dn Type= 3
Dn Slope=0.015
Boundary for River Rch & Prof#=UNT 152 IN BOCR,Reach-1         , 3
Up Type= 0
Dn Type= 3
Dn Slope=0.015
Boundary for River Rch & Prof#=UNT 152 IN BOCR,Reach-1         , 4
Up Type= 0
Dn Type= 3
Dn Slope=0.015
Boundary for River Rch & Prof#=UNT 152 IN BOCR,Reach-1         , 5
Up Type= 0
Dn Type= 3
Dn Slope=0.015
Boundary for River Rch & Prof#=UNT 152 IN BOCR,Reach-1         , 6
Up Type= 0
Dn Type= 3
Dn Slope=0.015
Boundary for River Rch & Prof#=UNT 152 IN BOCR,Reach-1         , 7
Up Type= 0
Dn Type= 3
Dn Slope=0.015
DSS Import GetInterval= 0
DSS Import GetPeak= 0
DSS Import FillOption= 0

--- UNT 152 IN BOCR.g01 (geometry) ---

Geom Title=Existing Conditions
Program Version=4.10

River Reach=UNT 152 IN BOCR ,Reach-1
Reach XY= 30
      3747142.86     10648440.47      3747035.92     10648560.61
      3746841.25       10649056.      3746486.75       10649332.
      3745711.25       10649303.      3745536.25       10649507.
      3745435.25       10649490.      3745393.25       10649620.
        3745256.       10649632.       3745051.5       10649780.
        3744700.       10649826.      3744564.25       10649998.
        3744483.       10649914.        3744395.       10650011.
        3744297.       10649976.      3744275.75       10650046.
       3744116.5       10649965.        3743940.       10650100.
       3743884.5       10649972.       3743760.5       10650029.
      3743593.75       10649967.      3743453.25       10650004.
      3743386.75       10649937.        3743177.       10649969.
      3741997.75       10650565.      3741691.94     10650757.36
      3741608.75       10650951.       3741447.1     10651076.47
      3741367.24     10651316.82      3741383.75       10651488.

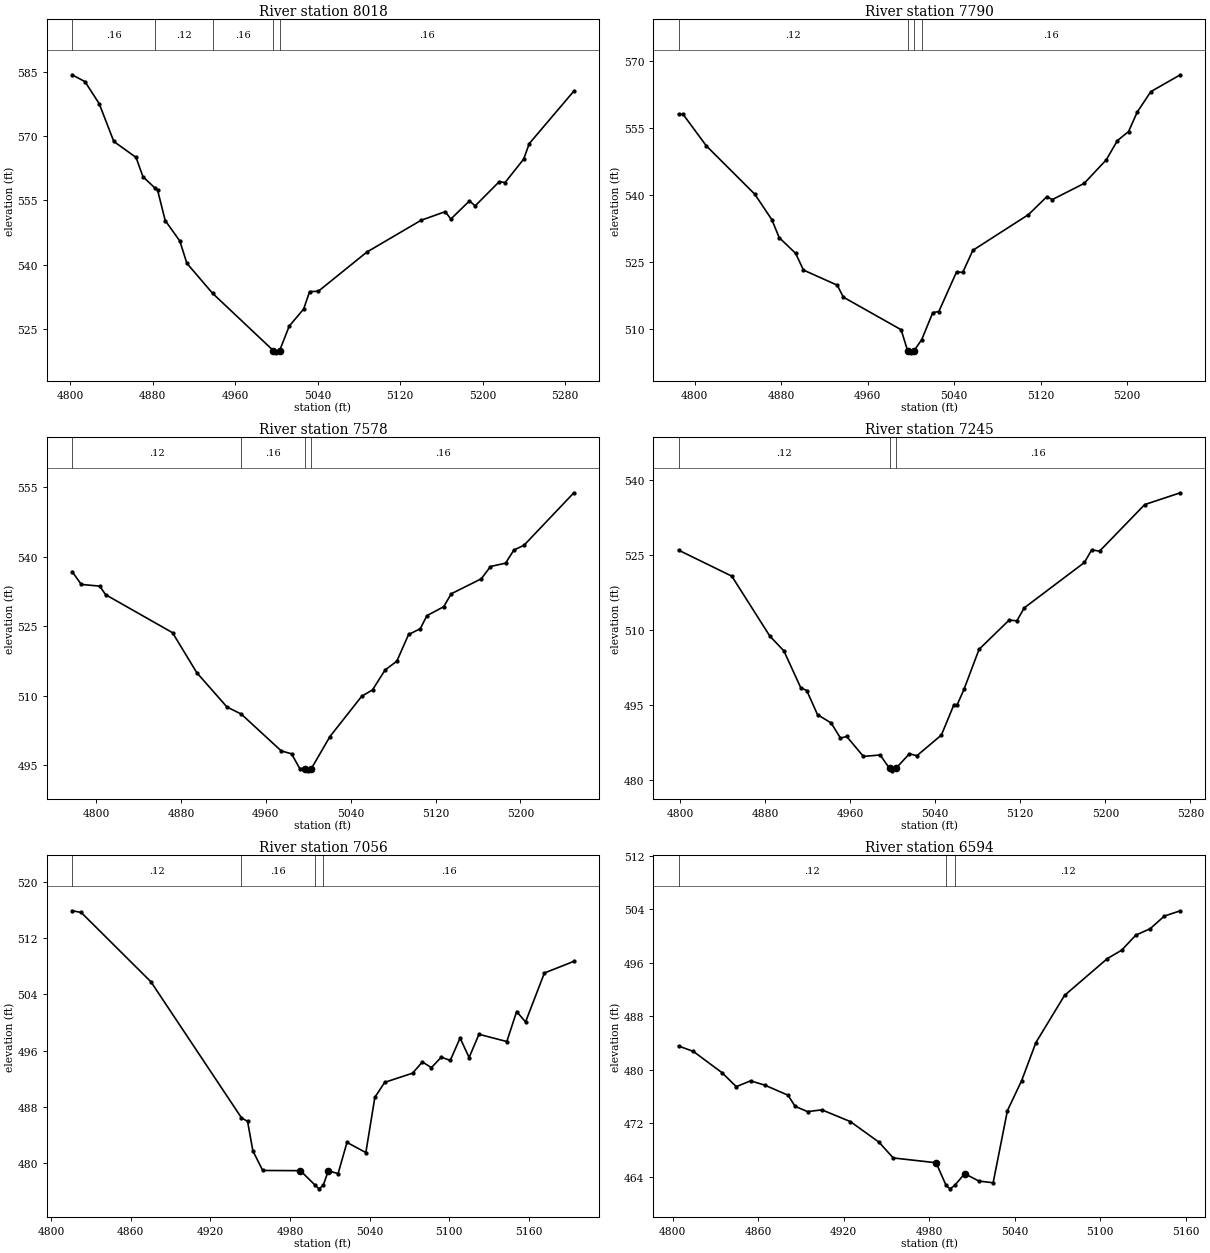
Type RM Length L Ch R = 1 ,8018    ,228,228,228
BEGIN DESCRIPTION:
UNT 152 IN BOCR 16.0
END DESCRIPTION:
XS GIS Cut Line= 3
      3746911.24     10648400.99      3747069.67     10648573.53
      3747301.88     10648673.36
#Sta/Elev= 30
  4801.6  584.35  4814.1  582.75  4827.9  577.62  4842.1  568.78  4863.7  565.05
  4870.4  560.54  4881.9  557.94  4884.6   557.4    4892  550.32  4906.2  545.52
    4913  540.34  4937.9  533.34    4997  519.92  4999.8  519.42    5003  519.92
  5012.3  525.64  5026.4  529.67  5032.1  533.71  5040.6   533.8  5087.7  542.95
  5140.2  550.36  5163.8  552.39  5169.2  550.66  5187.3   554.9  5192.8  553.73
  5216.3  559.42  5221.8  559.18  5239.9  564.66  5245.3  568.28  5288.6  580.54
#Mann= 5 ,-1 , 0
  4801.6     .16       0  4881.9     .12       0  4937.9     .16       0
    4997     .07       0    5003     .16       0
Bank Sta=4997,5003
XS Rating Curve= 0 ,0
Exp/Cntr=0.3,0.1

Type RM Length L Ch R = 1 ,7790    ,212,212,212
BEGIN DESCRIPTION:
Mapping XS a4e44f0c
END DESCRIPTION:
XS GIS Cut Line= 3
      3746787.12     10648655.78      3747016.29     10648775.57
      3747216.16     10648823.82
#Sta/Elev= 30
  4785.1  558.17  4789.3  558.17  4810.8   551.1  4855.6  540.28  4871.4  534.57
  4878.2  530.55  4893.4  527.02  4900.7  523.27  4931.9  519.89  4937.6   517.2
    4991  509.91    4997  505.23  4999.8  504.73    5003  505.23    5010  507.65
  5020.3  513.74  5025.9  513.99  5042.3  522.86    5048  522.75  5057.4   527.7
  5108.8  535.69  5125.8  539.71  5130.9  539.06  5160.3  542.68  5180.8  547.97
  5191.1  552.28  5201.4   554.3  5209.5  558.69    5222  563.24  5249.3  567.02
#Mann= 4 ,-1 , 0
  4785.1     .12       0    4997     .07       0    5003     .12       0
    5010     .16       0
Bank Sta=4997,5003
XS Rating Curve= 0 ,0
Exp/Cntr=0.3,0.1

Type RM Length L Ch R = 1 ,7578    ,333,333,333
BEGIN DESCRIPTION:
Mapping XS e8862894
END DESCRIPTION:
XS GIS Cut Line= 2
      3746702.04     10648853.69      3747130.85     10649053.34
#Sta/Elev= 30
  4777.4  536.82  4786.1  534.03  4803.5  533.67    4809  531.82  4872.1  523.61
    4895  514.96  4923.4  507.56  4936.9  506.03  4974.6  498.07  4984.3  497.45
    4992  494.27    4997  494.27  4999.8  493.77    5003  494.27  5020.4  501.15
  5050.5   509.9  5060.6  511.25  5072.5  515.57  5083.5  517.44  5094.6  523.22
  5105.6  524.46  5111.9  527.29  5127.7  529.22  5134.8  532.01  5163.2  535.26
  5171.8   537.9    5186  538.63  5193.9  541.47  5203.4  542.49  5250.4  553.83
#Mann= 4 ,-1 , 0
  4777.4     .12       0  4936.9     .16       0    4997     .07       0
    5003     .16       0
Bank Sta=4997,5003
XS Rating Curve= 0 ,0
Exp/Cntr=0.3,0.1

Type RM Length L Ch R = 1 ,7245    ,189,189,189
BEGIN DESCRIPTION:
Mapping XS f381e30d
END DESCRIPTION:
XS GIS Cut Line= 3
      3746587.45     10648985.62      3746717.68     10649213.07
      3746871.11     10649356.17
#Sta/Elev= 30
  4798.6  525.89  4848.7  520.69  4884.5   508.7  4897.7  505.75  4913.5  498.41
  4919.2  497.83  4929.3  493.01  4942.1  491.36  4950.9  488.33  4956.7  488.66
  4972.5  484.67  4988.2  484.96    4997  482.29  4999.8  481.79    5003  482.29
  5015.7  485.19  5022.8  484.82  5045.8  488.94  5057.6  495.02  5060.7  495.02
    5067  498.05  5081.2  506.06  5109.5  511.91  5116.8  511.77  5123.7  514.35
  5180.3  523.42  5187.2  525.97  5194.5  525.67    5237  534.99  5270.5  537.35
#Mann= 3 ,-1 , 0
  4798.6     .12       0    4997     .07       0    5003     .16       0
Bank Sta=4997,5003
XS Rating Curve= 0 ,0
Exp/Cntr=0.3,0.1

Type RM Length L Ch R = 1 ,7056    ,462,462,462
BEGIN DESCRIPTION:
UNT 152 IN BOCR 15.0
END DESCRIPTION:
XS GIS Cut Line= 3
      3746462.28     10649118.06      3746514.36     10649239.57
      3746679.27     10649421.84
#Sta/Elev= 30
  4815.8  515.93  4822.6   515.7  4875.2  505.81  4943.4  486.42    4948  485.91
    4952  481.71  4959.4  478.91  4987.8  478.88    4999  476.79  5001.8  476.29
    5005  476.79  5008.8  478.85  5016.2  478.47  5022.9  482.91  5037.1  481.46
  5043.9  489.34  5051.3  491.47  5072.3  492.78  5079.7  494.38  5086.5  493.57
  5093.9  495.06  5100.7   494.6  5108.1  497.79  5114.9  495.01  5122.3  498.32
  5143.3  497.29  5150.7  501.57  5157.4  500.08  5171.6  507.06  5193.8  508.72
#Mann= 4 ,-1 , 0
  4815.8     .12       0  4943.4     .16       0    4999     .07       0
    5005     .16       0
Bank Sta=4987.8,5008.8
XS Rating Curve= 0 ,0
Exp/Cntr=0.3,0.1

Type RM Length L Ch R = 1 ,6594    ,378,378,378
BEGIN DESCRIPTION:
UNT 152 IN BOCR 14.0
END DESCRIPTION:
XS GIS Cut Line= 2
      3746158.46     10649139.75       3746141.1     10649491.33
#Sta/Elev= 30
  4804.2  483.57  4814.6  482.76  4834.7  479.58  4844.7  477.49  4854.7  478.36
  4864.7  477.72    4881  476.21    4886  474.54  4894.7  473.76  4904.8  474.02
  4924.8  472.26  4944.8  469.19  4954.8  466.83  4984.9  466.11  4991.9  462.71
  4994.6  462.21  4997.9  462.71  5004.9  464.48  5014.9  463.37  5024.9  463.12
  5034.9   473.9  5044.9   478.4  5054.9  484.09    5075  491.14    5105  496.64
    5115  497.89    5125  500.15    5135   501.1    5145     503  5156.2  503.79
#Mann= 3 ,-1 , 0
  4804.2     .12       0  4991.9     .07       0  4997.9     .12       0
Bank Sta=4984.9,5004.9
XS Rating Curve= 0 ,0
Exp/Cntr=0.3,0.1

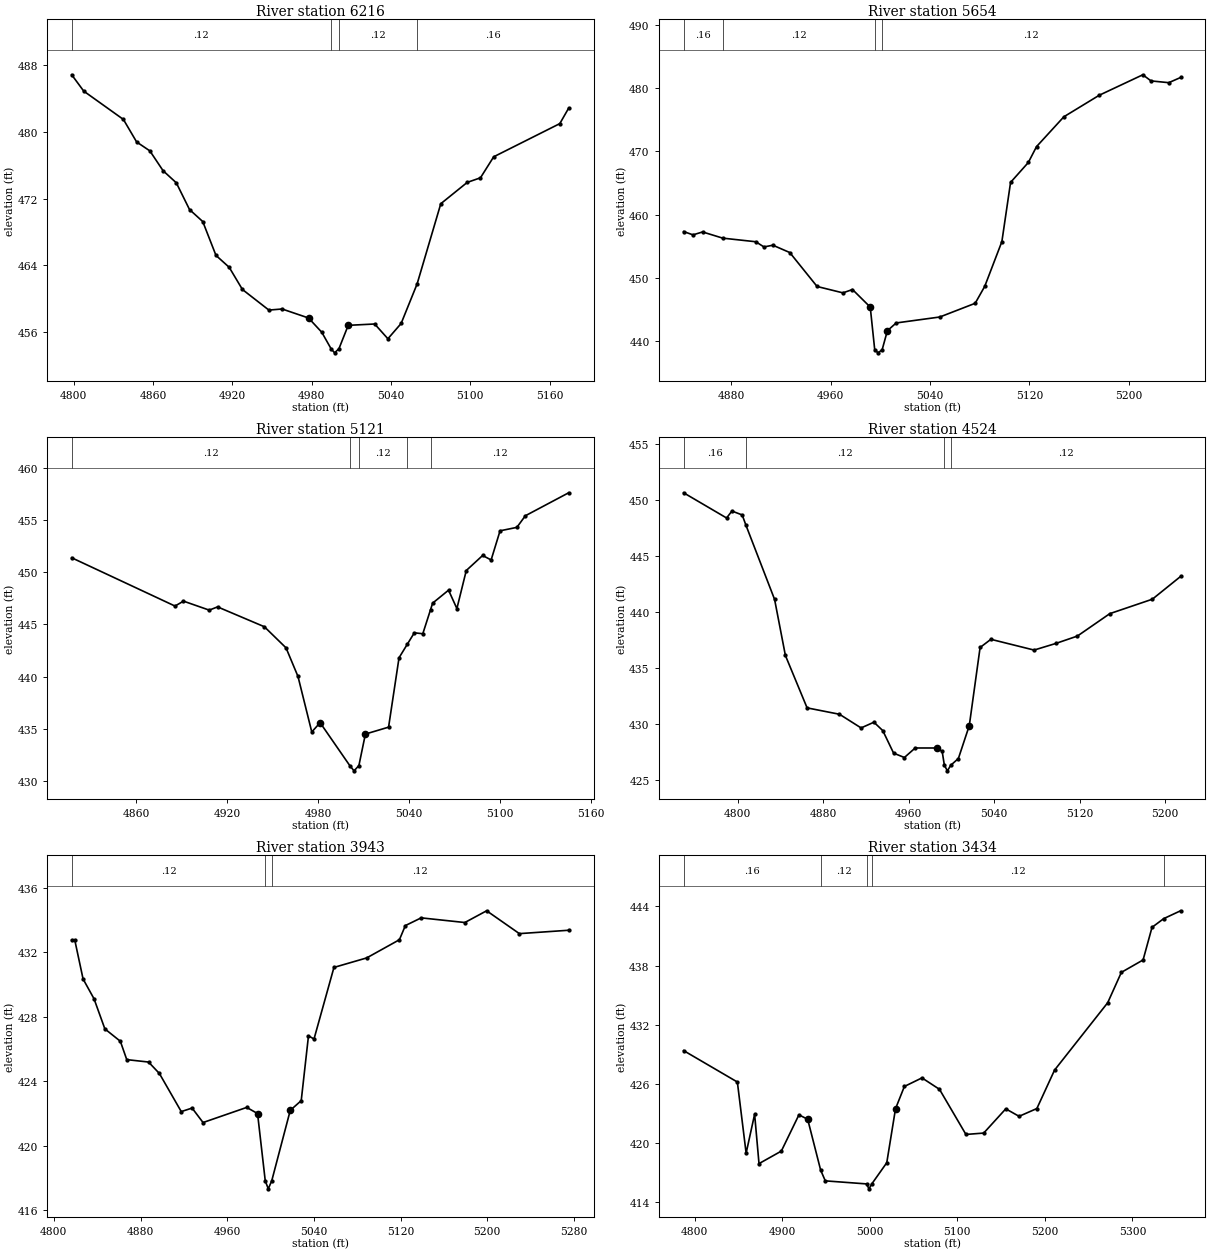
Type RM Length L Ch R = 1 ,6216    ,562,562,562
BEGIN DESCRIPTION:
UNT 152 IN BOCR 13.0
END DESCRIPTION:
XS GIS Cut Line= 2
      3745793.87      10649131.1      3745793.87      10649506.9
#Sta/Elev= 30
  4798.6  486.86  4807.7   484.9  4837.7   481.5  4847.7   478.8  4857.7  477.73
  4867.7  475.35  4877.7   473.9  4887.7  470.69  4897.7  469.25  4907.7  465.19
  4917.7  463.76  4927.7   461.1  4947.7  458.63  4957.7  458.76  4977.7  457.68
  4987.7  455.97  4994.7     454  4997.4   453.5  5000.7     454  5007.7   456.8
  5027.7  456.96  5037.7  455.19  5047.7  457.02  5059.8  461.77  5077.7  471.39
  5097.7  473.95  5107.7   474.5  5117.7  477.02  5167.7     481  5174.4  482.86
#Mann= 4 ,-1 , 0
  4798.6     .12       0  4994.7     .07       0  5000.7     .12       0
  5059.8     .16       0
Bank Sta=4977.7,5007.7
XS Rating Curve= 0 ,0
Exp/Cntr=0.3,0.1

Type RM Length L Ch R = 1 ,5654    ,533,533,533
BEGIN DESCRIPTION:
UNT 152 IN BOCR 12.0
END DESCRIPTION:
XS GIS Cut Line= 2
      3745285.02     10649433.49      3745588.88     10649693.94
#Sta/Elev= 30
  4841.6  457.31  4849.2  456.79  4856.9  457.25  4873.1  456.27  4899.7   455.7
  4906.3  454.88  4913.5  455.15  4927.1  453.99  4949.1  448.62  4969.9  447.61
  4977.6  448.14  4991.9  445.36  4995.5  438.62  4998.2  438.12  5001.5  438.62
  5005.7  441.62  5012.8  442.85  5047.9  443.79  5076.4  445.96  5084.1  448.64
  5097.9  455.72  5104.9  465.09  5119.2  468.24  5125.8  470.75  5147.8  475.47
  5176.3  478.88  5211.4  482.12    5218  481.15  5232.3  480.87  5241.8  481.69
#Mann= 4 ,-1 , 0
  4841.6     .16       0  4873.1     .12       0  4995.5     .07       0
  5001.5     .12       0
Bank Sta=4991.9,5005.7
XS Rating Curve= 0 ,0
Exp/Cntr=0.3,0.1

Type RM Length L Ch R = 1 ,5121    ,597,597,597
BEGIN DESCRIPTION:
UNT 152 IN BOCR 11.0
END DESCRIPTION:
XS GIS Cut Line= 2
      3744963.87     10649615.79      3745107.11     10649910.96
#Sta/Elev= 30
  4817.4  451.37  4885.6  446.75  4891.2  447.22  4908.2  446.36  4913.7  446.67
  4944.6  444.77  4958.9  442.75  4966.8  440.01  4975.9   434.7  4981.4  435.59
    5001  431.48  5003.8  430.98    5007  431.48  5011.3   434.5  5026.6  435.16
  5033.5   441.8  5038.9  443.08  5043.6  444.19  5049.2   444.1  5054.3   446.4
  5055.7  447.03  5066.2  448.27  5071.7  446.51  5077.9  450.15  5088.7  451.59
  5094.3  451.16  5100.2  453.95  5111.3  454.28  5116.9  455.39  5145.5  457.59
#Mann= 5 ,-1 , 0
  4817.4     .12       0    5001     .07       0    5007     .12       0
  5038.9     .16       0  5054.3     .12       0
Bank Sta=4981.4,5011.3
XS Rating Curve= 0 ,0
Exp/Cntr=0.3,0.1

Type RM Length L Ch R = 1 ,4524    ,581,581,581
BEGIN DESCRIPTION:
Mapping XS 01520737
END DESCRIPTION:
XS GIS Cut Line= 2
      3744538.53     10649746.02       3744607.9     10650205.61
#Sta/Elev= 30
  4749.5  450.68  4789.7  448.43  4794.7  449.05  4804.3   448.7  4807.9  447.76
  4834.6  441.16  4844.7  436.16    4865  431.48  4895.3  430.91  4915.5  429.69
  4927.5   430.2  4935.8  429.45  4945.9  427.44    4956  427.05  4966.1   427.9
  4986.2   427.9  4991.3  427.61  4993.4  426.36  4996.2  425.86  4999.4  426.36
  5006.5  426.96  5016.7   429.9  5026.8  436.87  5036.9   437.6  5077.3  436.64
  5097.6  437.23  5117.8  437.89  5148.1  439.89  5187.9  441.18  5214.3  443.21
#Mann= 4 ,-1 , 0
  4749.5     .16       0  4807.9     .12       0  4993.4     .07       0
  4999.4     .12       0
Bank Sta=4986.2,5016.7
XS Rating Curve= 0 ,0
Exp/Cntr=0.3,0.1

Type RM Length L Ch R = 1 ,3943    ,509,509,509
BEGIN DESCRIPTION:
Mapping XS 6b9d18eb
END DESCRIPTION:
XS GIS Cut Line= 2
       3744169.6     10649819.76      3744221.67      10650275.4
#Sta/Elev= 30
  4816.5  432.78  4819.3  432.78    4827  430.35  4837.1  429.12  4847.1  427.25
  4861.4  426.48  4867.3  425.34  4887.4  425.19  4897.4  424.48  4917.6  422.11
  4927.6  422.33  4937.7  421.43    4978  422.37    4988  421.99  4995.1  417.81
  4997.9  417.31  5001.1  417.81  5018.2  422.19  5028.3  422.79    5035  426.82
  5040.1  426.62  5058.5  431.07  5088.7  431.66  5118.9  432.79  5124.4  433.67
    5139  434.15  5179.3  433.86  5199.4  434.59  5229.6  433.17  5275.1  433.38
#Mann= 3 ,-1 , 0
  4816.5     .12       0  4995.1     .07       0  5001.1     .12       0
Bank Sta=4988,5018.2
XS Rating Curve= 0 ,0
Exp/Cntr=0.3,0.1

Type RM Length L Ch R = 1 ,3434    ,298,298,298
BEGIN DESCRIPTION:
Mapping XS f0868e4a
END DESCRIPTION:
XS GIS Cut Line= 3
      3743891.83       10649759.      3743865.79      10650067.2
      3743904.72     10650322.45
#Sta/Elev= 30
  4787.4  429.37  4848.8  426.18  4858.8  418.96  4868.5  422.91  4873.5   417.9
    4899  419.17  4919.1  422.85  4929.1   422.4  4943.9  417.24  4949.2  416.15
  4996.3  415.84  4999.1  415.34  5002.3  415.84  5019.4  417.99  5029.4  423.47
  5039.5  425.73  5059.6   426.6  5079.6  425.44  5109.8  420.86  5130.1     421
  5155.3  423.46  5170.5   422.7  5190.8  423.49    5211  427.39  5271.7  434.23
  5287.3  437.31  5312.1  438.57  5322.3  441.88  5335.6  442.76  5354.9  443.56
#Mann= 5 ,-1 , 0
  4787.4     .16       0  4943.9     .12       0  4996.3     .07       0
  5002.3     .12       0  5335.6     .16       0
Bank Sta=4929.1,5029.4
XS Rating Curve= 0 ,0
Exp/Cntr=0.3,0.1

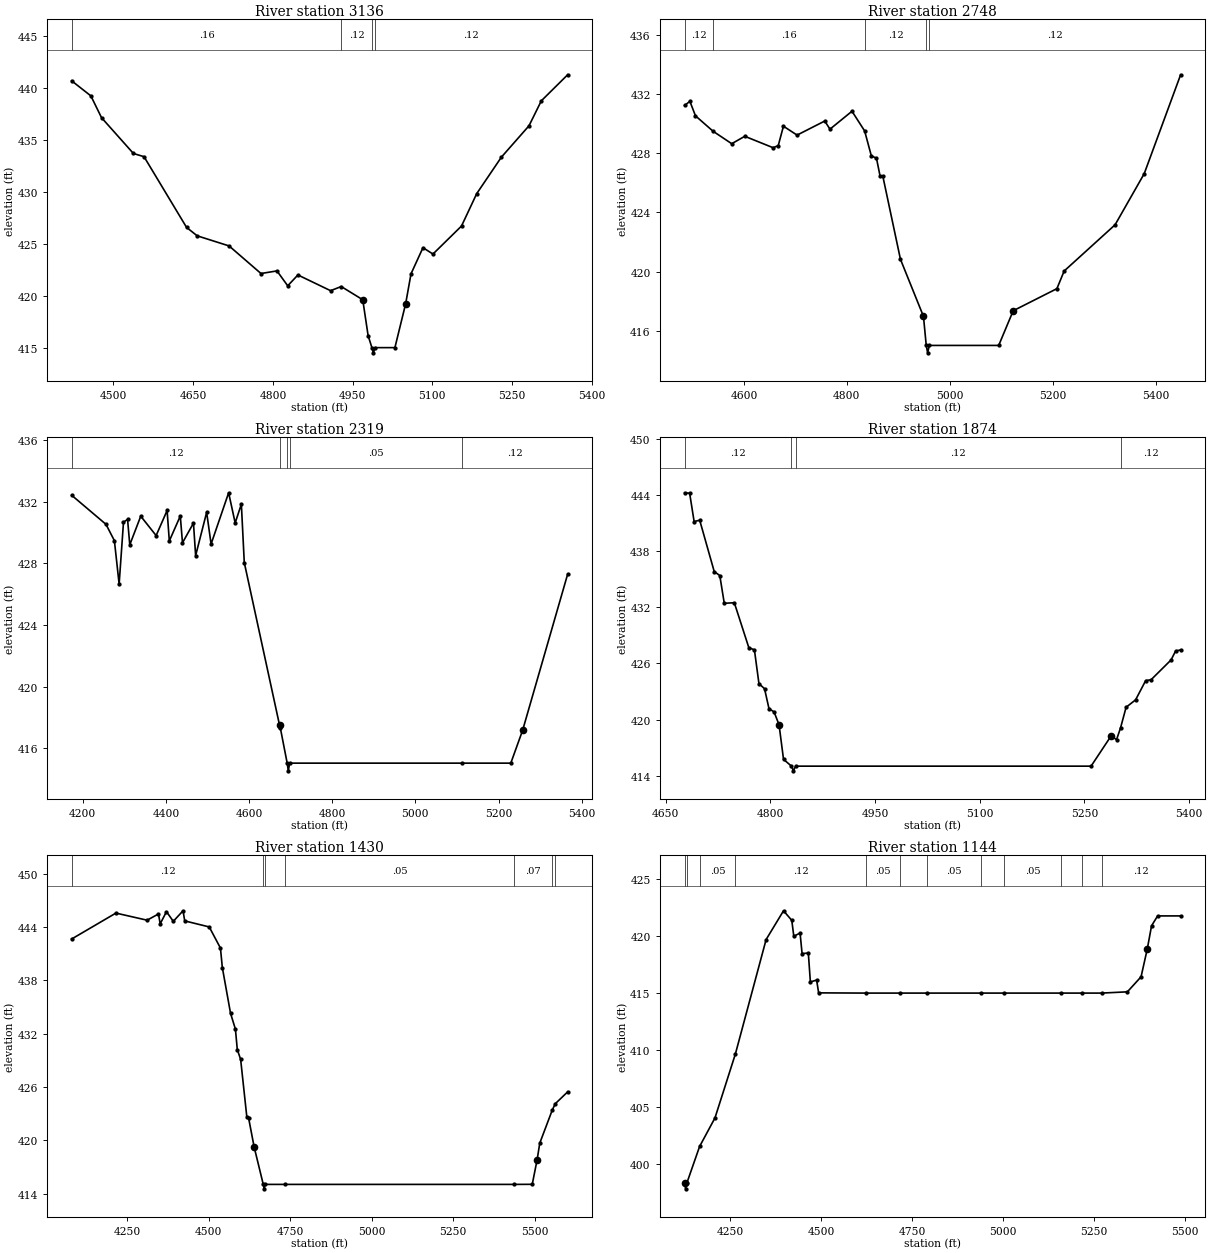
Type RM Length L Ch R = 1 ,3136    ,388,388,388
BEGIN DESCRIPTION:
Mapping XS 7ef010be
END DESCRIPTION:
XS GIS Cut Line= 4
      3743597.59     10649394.03      3743596.69     10649763.38
      3743635.75     10650058.52      3743744.24     10650301.54
#Sta/Elev= 30
  4421.4  440.66  4457.6  439.21  4477.6  437.12  4537.6  433.68  4557.6  433.37
  4637.6  426.58  4657.6  425.77  4717.6   424.8  4777.6  422.15  4807.7   422.4
  4827.9  420.97  4847.1  422.01  4908.6   420.5  4928.6   420.9  4969.1  419.63
  4979.2  416.18  4986.3  415.03    4989  414.53  4992.3  415.03  5029.6  415.03
  5049.8  419.24  5059.9  422.12  5082.4  424.63  5101.2  424.02  5154.9  426.71
  5183.6  429.83    5230  433.33  5281.9  436.34  5305.1  438.74  5354.6  441.24
#Mann= 4 ,-1 , 0
  4421.4     .16       0  4928.6     .12       0  4986.3     .07       0
  4992.3     .12       0
Bank Sta=4969.1,5049.8
XS Rating Curve= 0 ,0
Exp/Cntr=0.3,0.1

Type RM Length L Ch R = 1 ,2748    ,429,429,429
BEGIN DESCRIPTION:
UNT 152 IN BOCR 6.0
END DESCRIPTION:
XS GIS Cut Line= 4
        3743266.     10649439.14      3743228.91      10649818.8
      3743299.61     10649960.19       3743599.6     10650260.18
#Sta/Elev= 30
  4484.8  431.22    4495   431.5  4505.9  430.52  4540.1  429.48  4576.3  428.64
  4601.7  429.14  4656.7  428.37  4666.7  428.51  4676.8  429.82  4703.3  429.22
  4757.1  430.17  4767.2  429.62    4810  430.83  4834.6   429.5  4847.6  427.82
  4857.6  427.66  4864.5  426.47  4869.8  426.47  4904.2  420.84  4948.9  416.99
  4954.3  415.03    4957  414.53  4960.3  415.03  5095.1  415.03  5123.3  417.37
  5208.2  418.86  5222.3  420.05  5321.3  423.17  5377.9  426.62  5448.6  433.29
#Mann= 5 ,-1 , 0
  4484.8     .12       0  4540.1     .16       0  4834.6     .12       0
  4954.3     .07       0  4960.3     .12       0
Bank Sta=4948.9,5123.3
XS Rating Curve= 0 ,0
Exp/Cntr=0.3,0.1

Type RM Length L Ch R = 1 ,2319    ,445,445,445
BEGIN DESCRIPTION:
UNT 152 IN BOCR 5.0
END DESCRIPTION:
XS GIS Cut Line= 4
      3742470.86     10649421.79      3742596.65     10649801.25
      3742899.61     10650110.19       3743099.6     10650410.18
#Sta/Elev= 30
  4173.3  432.43  4255.9  430.54  4276.1  429.48  4287.5  426.66    4298  430.68
  4307.8  430.86  4313.1  429.21  4339.5  431.07  4376.5  429.81  4402.9  431.44
  4408.2  429.46  4434.6  431.08  4439.9  429.34  4466.3  430.62  4471.5  428.51
    4498  431.32  4508.7  429.26  4550.9  432.59  4566.6  430.63  4581.5  431.85
  4588.5  428.06  4673.4  417.49  4675.3  417.31  4691.7  415.03  4694.4  414.53
  4697.7  415.03  5113.4  415.03  5229.6  415.03  5258.1  417.17  5366.3   427.3
#Mann= 5 ,-1 , 0
  4173.3     .12       0  4675.3     .05       0  4691.7    .033       0
  4697.7     .05       0  5113.4     .12       0
Bank Sta=4673.4,5258.1
XS Rating Curve= 0 ,0
Exp/Cntr=0.3,0.1

Type RM Length L Ch R = 1 ,1874    ,444,444,444
BEGIN DESCRIPTION:
UNT 152 IN BOCR 4.0
END DESCRIPTION:
XS GIS Cut Line= 3
      3742299.61     10650060.19      3742499.61     10650310.19
      3742799.63     10650560.21
#Sta/Elev= 30
  4677.1  444.22  4684.3  444.17  4690.7  441.15  4698.7  441.29  4719.5  435.81
  4727.5  435.38  4733.9  432.42  4748.3  432.48  4769.1  427.68  4777.1  427.45
  4783.6  423.84  4791.6   423.3    4798  421.16  4805.2  420.83  4812.4  419.45
  4818.8  415.76  4830.2  415.03  4832.9  414.53  4836.2  415.03  5259.5  415.03
  5288.2  418.26    5296  417.86  5301.7  419.11  5309.7  421.32  5323.3  422.11
  5337.7  424.16  5345.5  424.26  5374.1  426.37  5380.6  427.32  5387.8  427.44
#Mann= 4 ,-1 , 0
  4677.1     .12       0  4830.2    .033       0  4836.2     .12       0
  5301.7     .12       0
Bank Sta=4812.4,5288.2
XS Rating Curve= 0 ,0
Exp/Cntr=0.3,0.1

Type RM Length L Ch R = 1 ,1430    ,286,286,286
BEGIN DESCRIPTION:
UNT 152 IN BOCR 3.0
END DESCRIPTION:
XS GIS Cut Line= 3
      3742333.28     10649628.88      3742099.61     10650510.19
      3742599.62      10650860.2
#Sta/Elev= 30
  4079.4  442.67  4215.2  445.59  4310.9  444.79  4345.9  445.49  4351.1  444.38
  4370.4  445.75  4391.3  444.66  4421.2  445.85  4426.4  444.71  4501.6  444.03
    4536  441.65  4541.8  439.46    4567   434.3    4582  432.51  4587.7  430.22
    4598  429.11    4617  422.62  4622.2  422.55  4639.4  419.25  4667.4  415.03
  4670.2  414.53  4673.4  415.03  4735.3  415.03  5436.3  415.03  5492.9  415.04
  5507.8   417.8    5516  419.68  5553.9  423.36  5563.3  424.11  5601.5  425.45
#Mann= 7 ,-1 , 0
  4079.4     .12       0  4667.4    .033       0  4673.4     .12       0
  4735.3     .05       0  5436.3     .07       0  5553.9     .12       0
  5563.3     .16       0
Bank Sta=4639.4,5507.8
XS Rating Curve= 0 ,0
Exp/Cntr=0.3,0.1

Type RM Length L Ch R = 1 ,1144    ,94,94,94
BEGIN DESCRIPTION:
Mapping XS 4102d351
END DESCRIPTION:
XS GIS Cut Line= 3
      3741559.26     10649860.32      3741608.84     10650114.94
      3742081.63     10651112.36
#Sta/Elev= 30
  4124.1  398.36  4126.9  397.86  4130.1  398.36  4165.3  401.58  4207.5  404.08
  4263.7   409.7  4348.1  419.73  4395.9  422.25  4418.6  421.41  4424.2  420.01
  4441.4   420.3  4446.9   418.5  4464.1  418.54  4469.7  416.01  4486.9  416.17
  4492.4  415.05  4622.6  415.03  4717.4  415.03  4789.2  415.03  4938.5  415.03
  5002.9  415.03  5159.6  415.03  5216.6  415.03  5270.1  415.03    5341  415.14
  5378.6  416.46  5395.8  418.92  5407.4  420.93  5424.1   421.8  5487.3   421.8
#Mann= 12 ,-1 , 0
  4124.1     .07       0  4130.1     .12       0  4165.3     .05       0
  4263.7     .12       0  4622.6     .05       0  4717.4     .07       0
  4789.2     .05       0  4938.5     .07       0  5002.9     .05       0
  5159.6     .07       0  5216.6     .05       0  5270.1     .12       0
Bank Sta=4124.1,5395.8
XS Rating Curve= 0 ,0
Exp/Cntr=0.3,0.1

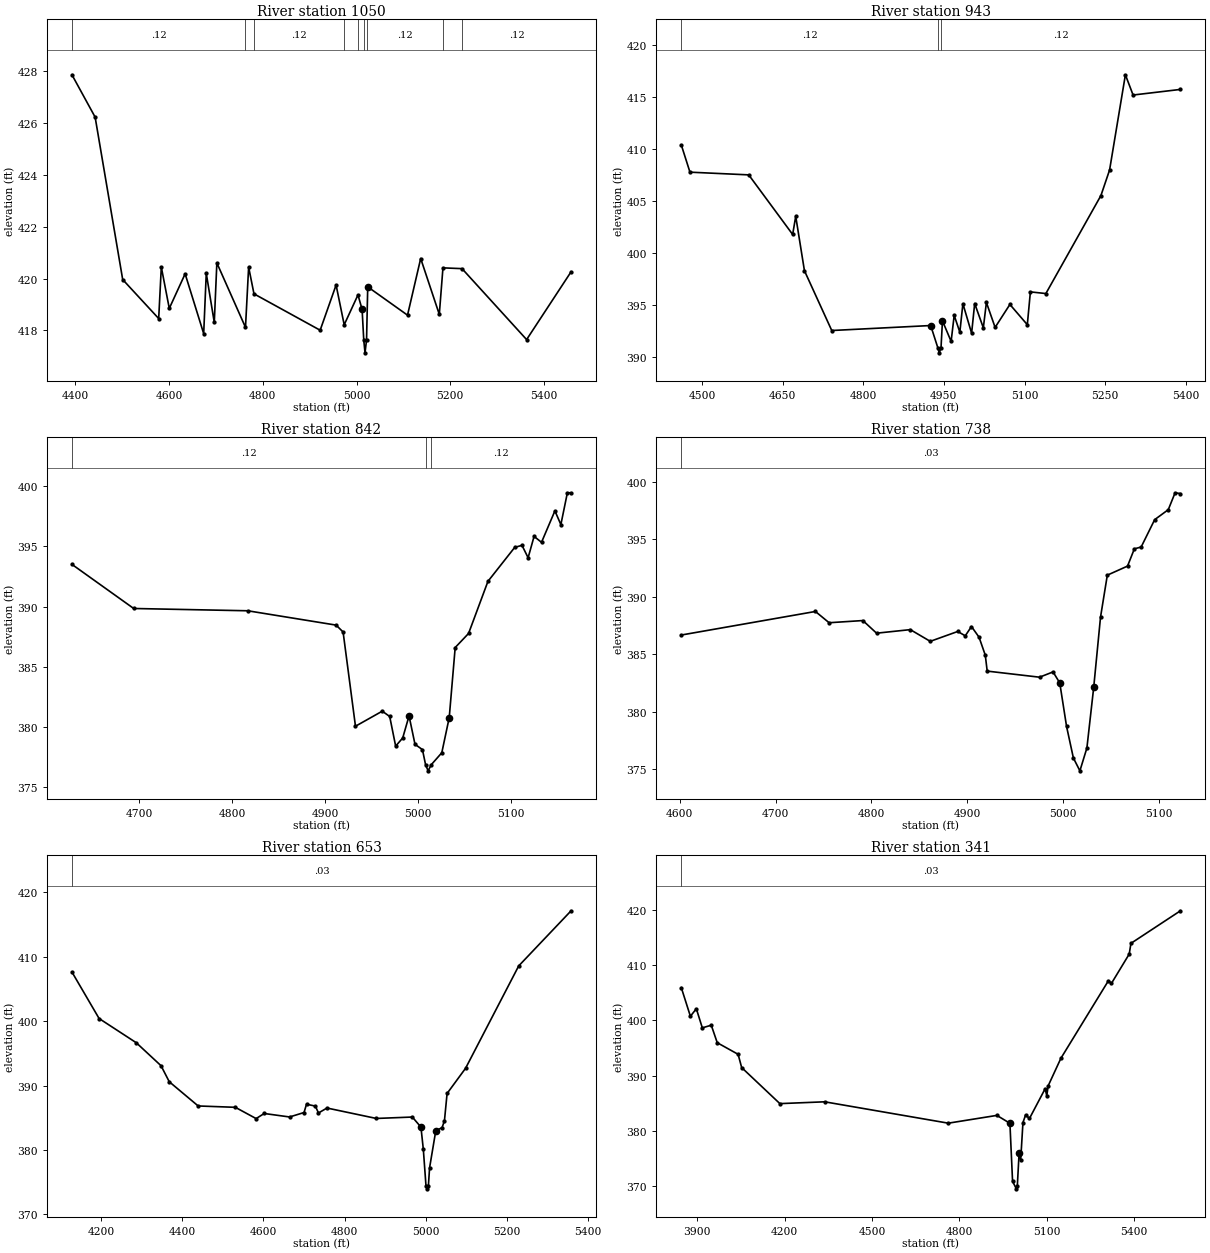
Type RM Length L Ch R = 1 ,1050    ,107,107,107
BEGIN DESCRIPTION:
UNT 152 IN BOCR 2.0
END DESCRIPTION:
XS GIS Cut Line= 2
      3741522.05     10650162.71      3741985.39     10651121.64
#Sta/Elev= 30
  4392.7  427.84  4442.2  426.21    4501  419.96  4577.8  418.46  4583.4  420.44
  4600.4  418.85  4634.2  420.18  4673.8  417.88  4679.3   420.2  4696.4  418.31
  4701.9   420.6    4763  418.12  4769.7  420.44  4781.1  419.41  4922.3  418.01
  4956.3  419.75  4973.6  418.22    5003  419.37  5011.8  418.81  5015.3  417.64
    5018  417.14  5021.3  417.64  5023.8  419.68  5108.7  418.59  5136.8  420.77
  5176.5  418.62  5184.3  420.41    5225  420.38  5362.8  417.65  5457.7  420.26
#Mann= 9 ,-1 , 0
  4392.7     .12       0    4763     .07       0  4781.1     .12       0
  4973.6     .07       0    5003     .12       0  5015.3     .07       0
  5021.3     .12       0  5184.3     .07       0    5225     .12       0
Bank Sta=5011.8,5023.8
XS Rating Curve= 0 ,0
Exp/Cntr=0.3,0.1

Type RM Length L Ch R = 1 ,943     ,101,101,101
BEGIN DESCRIPTION:
Mapping XS 277cae4b
END DESCRIPTION:
XS GIS Cut Line= 2
      3741435.23     10650284.21      3741877.92     10651100.15
#Sta/Elev= 30
  4461.7  410.42  4477.8   407.8  4587.1  407.54  4668.8   401.8  4674.5  403.55
  4690.7  398.31  4741.5  392.55  4925.5  393.03  4938.7   390.9  4941.4   390.4
  4944.7   390.9  4947.4  393.48  4963.5   391.5  4969.2  394.01  4979.7  392.39
  4985.4  395.13  5001.6  392.29  5007.3  395.15  5023.4  392.81  5029.1  395.25
  5045.3  392.85  5072.8  395.06  5105.2  393.11  5110.9  396.27  5139.7  396.11
  5242.1  405.55  5258.2  408.01  5287.6  417.18  5301.9  415.23    5390  415.77
#Mann= 3 ,-1 , 0
  4461.7     .12       0  4938.7     .07       0  4944.7     .12       0
Bank Sta=4925.5,4947.4
XS Rating Curve= 0 ,0
Exp/Cntr=0.3,0.1

Type RM Length L Ch R = 1 ,842     ,104,104,104
BEGIN DESCRIPTION:
Mapping XS 672ae9e4
END DESCRIPTION:
XS GIS Cut Line= 3
      3741438.73     10650531.22      3741579.36     10650766.92
      3741743.43     10650971.36
#Sta/Elev= 30
    4628   393.5  4694.4  389.84    4817  389.65    4912  388.46  4919.5  387.89
  4932.8  380.07  4961.6  381.32  4969.6  380.88    4976  378.42  4983.6   379.1
  4990.4  380.93  4996.8  378.57  5004.8  378.13  5008.2  376.87  5010.9  376.37
  5014.2  376.87  5025.6  377.87  5033.6  380.79    5040   386.6  5054.4  387.77
  5075.2  392.09    5104  394.91  5111.8  395.08  5118.4  394.05  5124.8  395.82
  5132.8  395.33  5147.2  397.94  5153.6   396.8  5160.6  399.44  5164.6  399.44
#Mann= 3 ,-1 , 0
    4628     .12       0  5008.2     .07       0  5014.2     .12       0
Bank Sta=4990.4,5033.6
XS Rating Curve= 0 ,0
Exp/Cntr=0.3,0.1

Type RM Length L Ch R = 1 ,738     ,85,85,85
BEGIN DESCRIPTION:
Mapping XS 7490affa
END DESCRIPTION:
XS GIS Cut Line= 3
       3741352.8     10650640.62      3741555.93     10650886.72
      3741699.13     10651028.62
#Sta/Elev= 30
  4601.6  386.67  4741.5  388.72  4755.8  387.74    4791  387.93  4805.3  386.83
  4840.5  387.14  4861.3  386.12    4890  386.98  4897.8   386.6  4904.3  387.41
  4912.2  386.48  4918.7  384.92  4920.7  383.53  4975.3     383  4989.4  383.46
  4996.4   382.5  5003.5  378.71  5010.6  375.97  5017.4  374.85  5024.7  376.84
  5031.8  382.11  5038.9  388.22    5046  391.88  5067.1  392.67  5074.2  394.17
  5081.3  394.33  5095.4  396.71  5109.6  397.58  5116.7  399.05  5122.3  398.98
#Mann= 1 ,-1 , 0
  4601.6     .03       0
Bank Sta=4996.4,5031.8
XS Rating Curve= 0 ,0
Exp/Cntr=0.3,0.1

Type RM Length L Ch R = 1 ,653     ,312,312,312
BEGIN DESCRIPTION:
Mapping XS 5045db57
END DESCRIPTION:
XS GIS Cut Line= 5
      3741395.48      10650234.4      3741302.04     10650744.62
      3741426.55      10650917.9      3741825.86     10651165.29
      3741851.94     10651173.99
#Sta/Elev= 30
  4128.7  407.63  4195.6  400.41  4287.1  396.65  4348.1  393.08  4368.4  390.59
  4439.6  386.83  4531.1  386.62  4582.3  384.87  4602.2  385.66  4664.7  385.12
  4700.3  385.81  4706.4   387.1  4728.1  386.81  4735.9  385.74  4756.8  386.51
  4878.3  384.89    4967  385.11  4988.2  383.55  4994.1  380.09  5000.6  374.46
  5003.3  373.96  5006.6  374.46  5009.5  377.23  5024.8     383  5040.2  383.46
  5046.1  384.53  5052.6  388.77  5098.1  392.68    5229  408.58    5358  417.14
#Mann= 1 ,-1 , 0
  4128.7     .03       0
Bank Sta=4988.2,5024.8
XS Rating Curve= 0 ,0
Exp/Cntr=0.3,0.1

Type RM Length L Ch R = 1 ,341     ,0,0,0
BEGIN DESCRIPTION:
UNT 152 IN BOCR 1.0
END DESCRIPTION:
XS GIS Cut Line= 5
       3741378.1     10650199.75       3741204.5     10650994.86
       3741313.7     10651156.61       3741539.4     10651269.46
      3741982.13     10651182.65
#Sta/Elev= 30
  3845.9  405.93  3877.1  400.75  3897.5  402.11    3918  398.65  3948.7  399.13
  3969.2  395.96  4040.8  393.86    4053  391.46  4184.1  384.93  4337.7  385.26
  4761.9  381.39  4928.6   382.8  4973.3  381.37  4982.4  370.86  4995.4   369.5
  4998.7     370  5004.8  375.97  5010.3  374.74    5018  381.49  5027.1  382.89
  5040.4  382.24  5094.2  387.63  5099.8  386.35  5104.6  388.16  5148.2  393.14
  5311.3  407.19  5321.5  406.69  5382.6  412.01  5388.5  413.95  5558.4  419.85
#Mann= 1 ,-1 , 0
  3845.9     .03       0
Bank Sta=4973.3,5004.8
XS Rating Curve= 0 ,0
Exp/Cntr=0.3,0.1

Chan Stop Cuts=-1
Use User Specified Reach Order=0
Composite Channel Slope=5