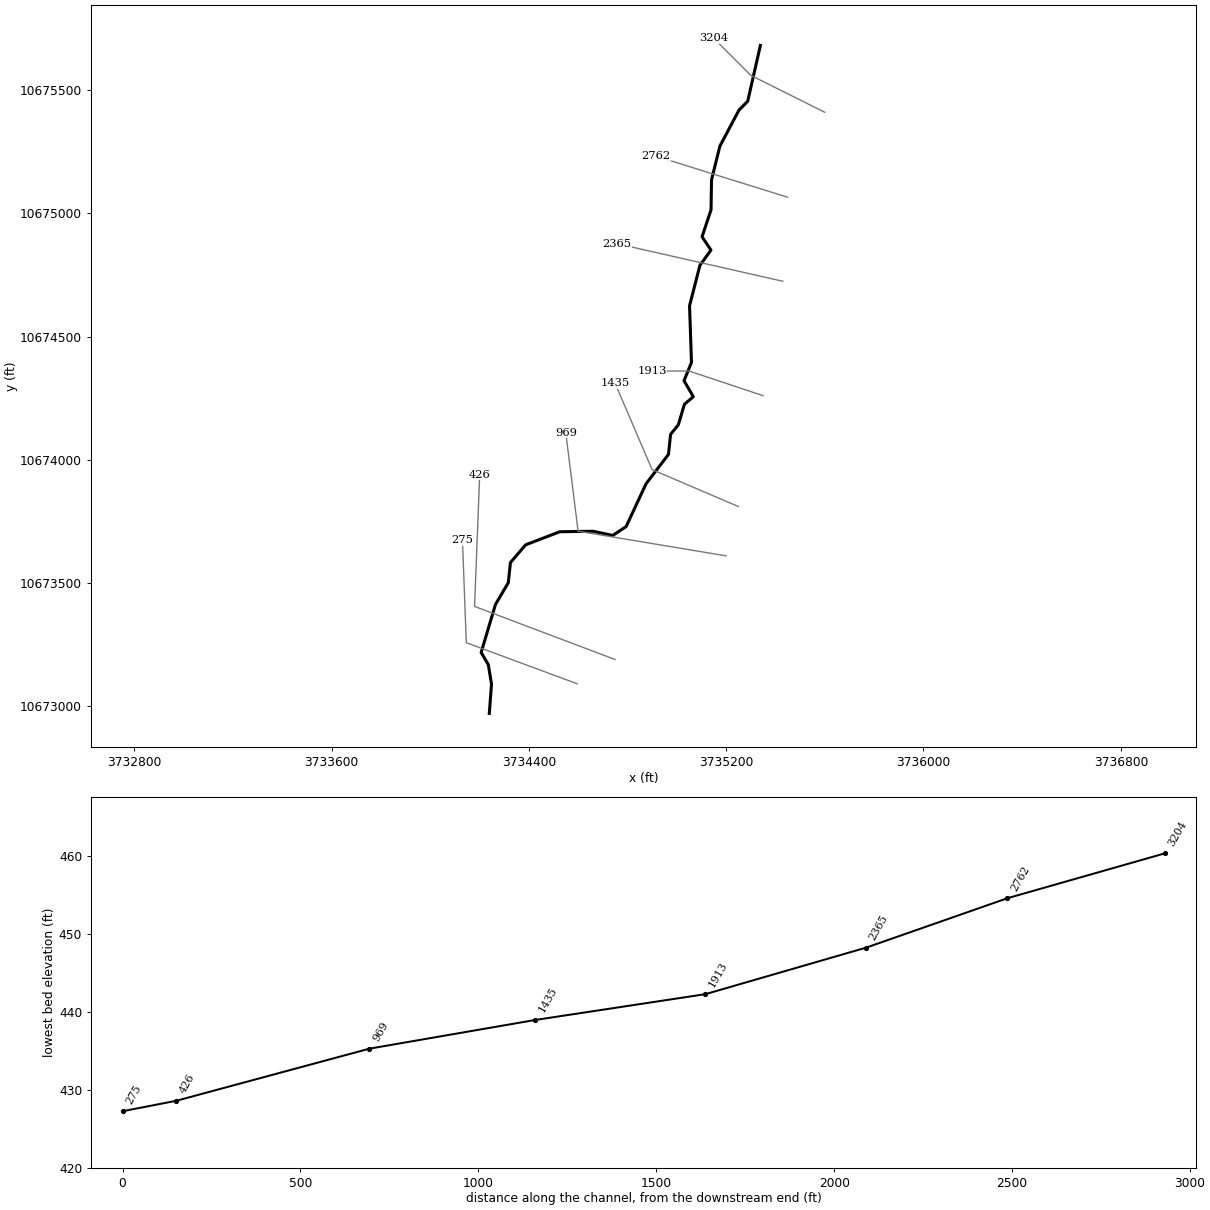
--- UNT 154 IN BOCR.prj (project) ---

Proj Title=UNT 154 IN BOCR Base Level Engineering
Current Plan=p01
Default Exp/Contr=0.3,0.1
English Units
Geom File=g01
Flow File=f01
Plan File=p01
Y Axis Title=Elevation
X Axis Title(PF)=Main Channel Distance
X Axis Title(XS)=Station
BEGIN DESCRIPTION:
UNT 154 IN BOCR
END DESCRIPTION:
DSS Export Rating Curves= 0
DSS Export Rating Curve Sorted= 0
DSS Export Volume Flow Curves= 0
DXF OffsetX= 0
DXF OffsetY= 0
DXF ScaleX= 1
DXF ScaleY= 10

--- UNT 154 IN BOCR.p01 (plan) ---

Plan Title=Multiple Run
Short Identifier=Multiple
Geom File=g01
Flow File=f01
Subcritical Flow
K Sum by GR= 0
Std Step Tol= 0.01
Critical Tol= 0.01
Num of Std Step Trials= 20
Max Error Tol= 0.3
Flow Tol Ratio= 0.001
Split Flow NTrial= 30
Split Flow Tol= 0.02
Split Flow Ratio= 0.02
Log Output Level= 0
Friction Slope Method= 1
Unsteady Friction Slope Method= 2
Unsteady Bridges Friction Slope Method= 1
Parabolic Critical Depth
Global Vel Dist=  1 , 1 , 1
Global Log Level= 0
CheckData=True
Encroach Param= -1, 0, 0, 0
BEGIN DESCRIPTION:
Multiple Run
END DESCRIPTION:

--- UNT 154 IN BOCR.f01 (steady flow) ---

Flow Title=Multiple
Program Version=4.10
Number of Profiles= 7
Profile Names=10-year,25-year,50-year,1pct_min,100-year,1pct_plu,500-year
River Rch & RM=UNT 154 IN BOCR,Reach-1         ,3204
     781    1086    1346    1227    1659    2244    2531
Boundary for River Rch & Prof#=UNT 154 IN BOCR,Reach-1         , 1
Up Type= 0
Dn Type= 3
Dn Slope=0.009
Boundary for River Rch & Prof#=UNT 154 IN BOCR,Reach-1         , 2
Up Type= 0
Dn Type= 3
Dn Slope=0.009
Boundary for River Rch & Prof#=UNT 154 IN BOCR,Reach-1         , 3
Up Type= 0
Dn Type= 3
Dn Slope=0.009
Boundary for River Rch & Prof#=UNT 154 IN BOCR,Reach-1         , 4
Up Type= 0
Dn Type= 3
Dn Slope=0.009
Boundary for River Rch & Prof#=UNT 154 IN BOCR,Reach-1         , 5
Up Type= 0
Dn Type= 3
Dn Slope=0.009
Boundary for River Rch & Prof#=UNT 154 IN BOCR,Reach-1         , 6
Up Type= 0
Dn Type= 3
Dn Slope=0.009
Boundary for River Rch & Prof#=UNT 154 IN BOCR,Reach-1         , 7
Up Type= 0
Dn Type= 3
Dn Slope=0.009
DSS Import GetInterval= 0
DSS Import GetPeak= 0
DSS Import FillOption= 0

--- UNT 154 IN BOCR.g01 (geometry) ---

Geom Title=Existing Conditions
Program Version=4.10

River Reach=UNT 154 IN BOCR ,Reach-1
Reach XY= 30
      3735338.71     10675681.46      3735287.25       10675455.
        3735252.       10675419.       3735174.5       10675273.
       3735140.5       10675136.      3735138.61     10675014.75
      3735102.25       10674905.      3735138.25       10674851.
       3735093.5       10674789.       3735051.5       10674625.
      3735059.25       10674395.        3735029.       10674321.
      3735066.75       10674256.       3735030.5       10674225.
        3735006.       10674142.       3734974.5       10674103.
        3734966.       10674022.      3734875.25       10673903.
      3734794.25       10673729.      3734740.31     10673693.13
        3734660.       10673710.       3734525.5       10673708.
        3734387.       10673655.      3734325.25       10673583.
       3734316.5       10673501.       3734264.5       10673413.
       3734206.5       10673218.       3734235.5       10673169.
       3734248.5       10673090.       3734239.5       10672971.

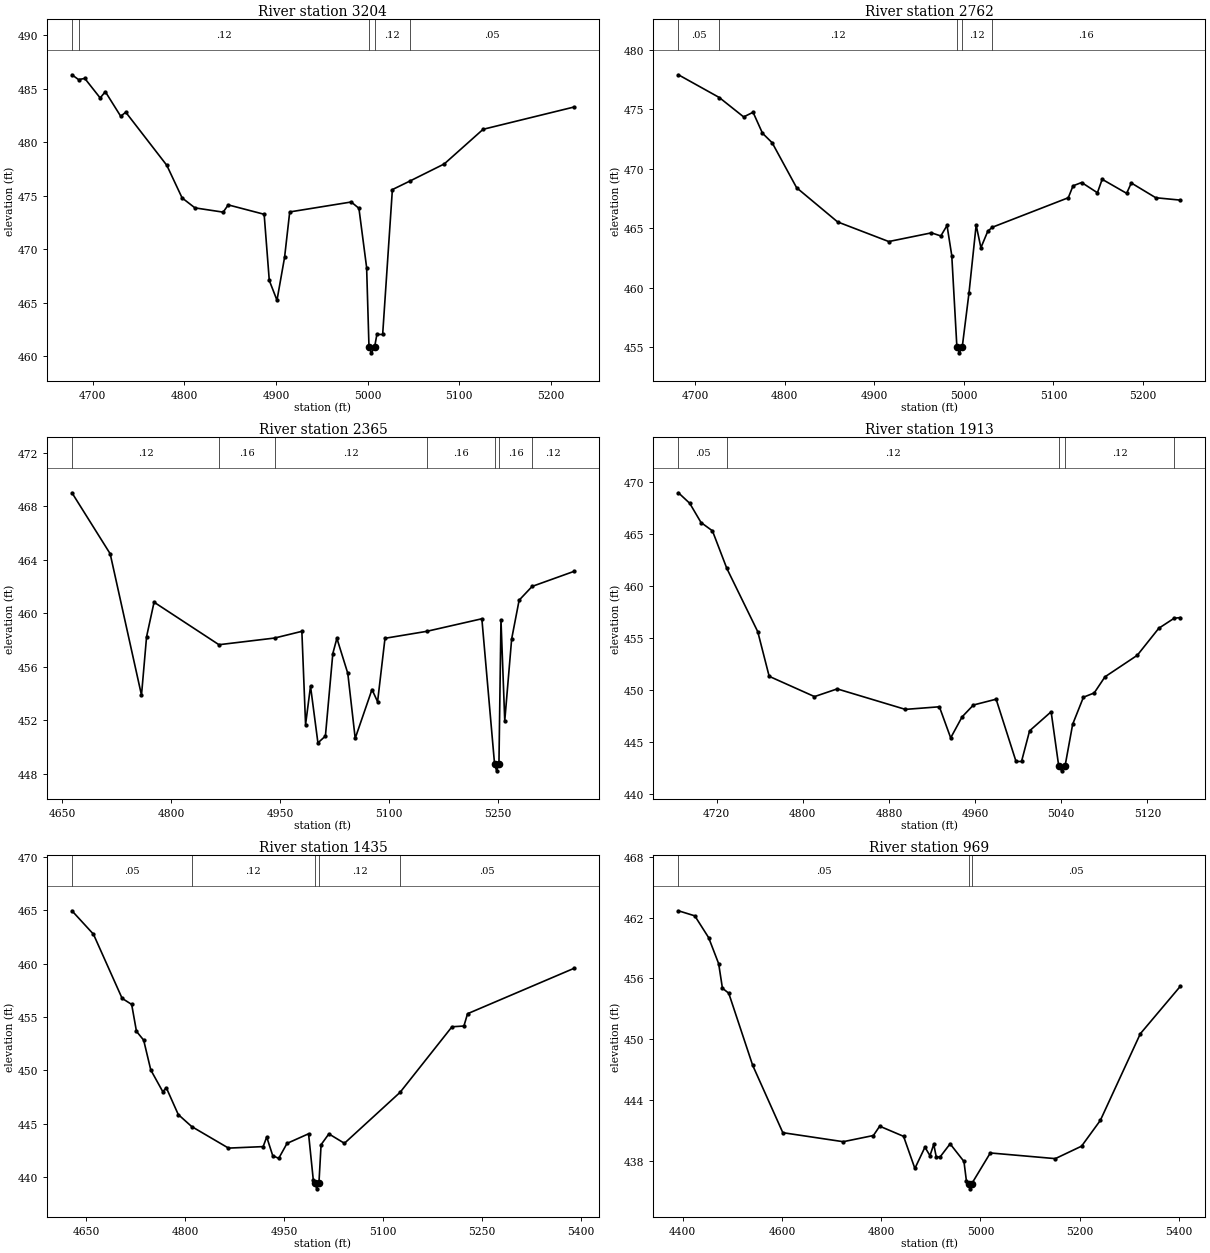
Type RM Length L Ch R = 1 ,3204    ,442,442,442
BEGIN DESCRIPTION:
UNT 154 IN BOCR 7.0
END DESCRIPTION:
XS GIS Cut Line= 3
      3735599.65     10675410.17      3735299.61     10675560.19
       3735149.6      10675710.2
#Sta/Elev= 30
  4677.4  486.31  4684.6  485.86  4691.4  485.97  4708.2  484.14  4713.8  484.73
  4730.6  482.43  4736.1  482.81  4780.9  477.84  4797.6  474.79  4811.6  473.86
  4842.4  473.46  4847.9  474.14  4887.1  473.26  4892.7  467.07  4901.1  465.22
  4909.4  469.24    4915  473.48  4982.1  474.41  4990.5  473.82  4998.9  468.28
  5001.5   460.8  5004.2   460.3  5007.5   460.8  5010.1  462.02  5016.4  462.02
    5027  475.57  5045.9  476.36  5083.6  477.97    5126  481.21    5225  483.29
#Mann= 5 ,-1 , 0
  4677.4     .16       0  4684.6     .12       0  5001.5     .07       0
  5007.5     .12       0  5045.9     .05       0
Bank Sta=5001.5,5007.5
XS Rating Curve= 0 ,0
Exp/Cntr=0.3,0.1

Type RM Length L Ch R = 1 ,2762    ,397,397,397
BEGIN DESCRIPTION:
UNT 154 IN BOCR 6.0
END DESCRIPTION:
XS GIS Cut Line= 2
      3735449.14     10675065.49       3734914.5     10675232.13
#Sta/Elev= 30
  4681.6  477.91  4727.2     476  4754.4  474.37  4764.9  474.76  4775.4     473
  4786.2   472.2  4813.5  468.42  4859.2  465.55  4916.3   463.9  4963.9  464.63
  4974.4  464.37  4981.3  465.25  4986.6  462.72  4992.3  455.05  4995.1  454.55
  4998.3  455.05  5005.8  459.57  5013.8  465.28  5019.1  463.38  5026.8  464.77
  5031.8   465.1  5116.6  467.58  5121.9  468.58  5131.5  468.86  5149.1     468
  5154.4  469.13  5181.7  467.95  5186.9  468.82  5214.2  467.58  5241.6  467.38
#Mann= 5 ,-1 , 0
  4681.6     .05       0  4727.2     .12       0  4992.3     .07       0
  4998.3     .12       0  5031.8     .16       0
Bank Sta=4992.3,4998.3
XS Rating Curve= 0 ,0
Exp/Cntr=0.3,0.1

Type RM Length L Ch R = 1 ,2365    ,452,452,452
BEGIN DESCRIPTION:
UNT 154 IN BOCR 5.0
END DESCRIPTION:
XS GIS Cut Line= 2
      3735429.76     10674724.45      3734756.17     10674877.22
#Sta/Elev= 30
  4663.8     469  4716.4  464.44  4759.5  453.87  4766.5  458.24  4776.8  460.82
  4866.1  457.64  4942.8  458.14  4980.2  458.64  4985.3  451.67  4992.1  454.54
  5002.3   450.3  5012.6  450.81  5022.8  456.98  5028.4  458.12  5043.4   455.5
  5053.6  450.64  5076.7  454.29  5084.4  453.38  5094.6  458.12    5152  458.64
  5227.9  459.58  5245.4  448.71  5248.2  448.21  5251.4  448.71  5254.2  459.51
  5259.4  451.95  5268.9  458.07  5279.2  460.97  5297.1     462  5354.5  463.12
#Mann= 7 ,-1 , 0
  4663.8     .12       0  4866.1     .16       0  4942.8     .12       0
    5152     .16       0  5245.4     .07       0  5251.4     .16       0
  5297.1     .12       0
Bank Sta=5245.4,5251.4
XS Rating Curve= 0 ,0
Exp/Cntr=0.3,0.1

Type RM Length L Ch R = 1 ,1913    ,478,478,478
BEGIN DESCRIPTION:
UNT 154 IN BOCR 4.0
END DESCRIPTION:
XS GIS Cut Line= 3
      3735349.57      10674260.2      3735049.61     10674360.19
      3734899.59     10674360.19
#Sta/Elev= 30
  4684.4  468.98  4694.9  467.97  4705.4  466.12    4716  465.32  4729.4   461.7
  4758.1  455.62  4768.7  451.33  4810.8  449.38  4831.9  450.12  4895.2  448.15
  4926.8   448.4  4937.3  445.41  4947.9  447.43  4958.4  448.57  4979.5  449.13
    4998  443.14  5003.1  443.14  5010.6  446.09  5030.6  447.92  5037.6  442.74
  5040.3  442.24  5043.6  442.74  5050.6  446.72  5060.6  449.32  5070.6  449.73
  5080.6  451.28  5110.6  453.35  5130.6  455.95  5144.8  456.91  5150.6  456.98
#Mann= 5 ,-1 , 0
  4684.4     .05       0  4729.4     .12       0  5037.6     .07       0
  5043.6     .12       0  5144.8     .05       0
Bank Sta=5037.6,5043.6
XS Rating Curve= 0 ,0
Exp/Cntr=0.3,0.1

Type RM Length L Ch R = 1 ,1435    ,466,466,466
BEGIN DESCRIPTION:
UNT 154 IN BOCR 3.0
END DESCRIPTION:
XS GIS Cut Line= 3
      3735249.57     10673810.21      3734899.61     10673960.19
      3734749.62     10674310.16
#Sta/Elev= 30
  4628.2  464.94  4660.8  462.75  4704.3  456.75  4718.8  456.18  4726.1  453.66
    4737  452.84  4747.8  450.05    4766  448.02  4771.4  448.38  4789.5  445.88
  4809.8  444.76  4865.7  442.74  4918.3  442.88  4923.7  443.78  4932.8  442.04
  4941.9  441.78  4954.5  443.18  4987.2  444.08  4994.4  439.74  4996.9  439.43
  4999.6  438.93  5002.9  439.43  5006.2  443.06    5018  444.07  5041.6  443.19
  5126.1  447.96  5204.8  454.09  5222.9  454.16  5228.4  455.31  5389.7  459.55
#Mann= 5 ,-1 , 0
  4628.2     .05       0  4809.8     .12       0  4996.9     .07       0
  5002.9     .12       0  5126.1     .05       0
Bank Sta=4996.9,5002.9
XS Rating Curve= 0 ,0
Exp/Cntr=0.3,0.1

Type RM Length L Ch R = 1 ,969     ,543,543,543
BEGIN DESCRIPTION:
UNT 154 IN BOCR 2.0
END DESCRIPTION:
XS GIS Cut Line= 3
      3735199.65     10673610.18      3734599.61     10673710.19
      3734549.61     10674110.16
#Sta/Elev= 30
  4391.3  462.68  4424.3  462.18  4452.2  460.03  4472.4  457.46    4480  455.04
  4492.7  454.55  4540.9  447.44  4601.7  440.79  4723.4   439.9  4784.2  440.51
  4796.9  441.43    4845  440.43  4867.8  437.26  4888.1  439.36  4898.2  438.52
  4905.8  439.64  4910.9   438.4  4918.5  438.39  4938.8  439.69  4966.7  437.95
  4971.7  436.01  4976.3  435.75  4979.1  435.25  4982.3  435.75  5019.8  438.79
  5150.8  438.23  5203.7  439.46  5241.5     442  5322.1  450.55  5402.7  455.23
#Mann= 3 ,-1 , 0
  4391.3     .05       0  4976.3     .03       0  4982.3     .05       0
Bank Sta=4976.3,4982.3
XS Rating Curve= 0 ,0
Exp/Cntr=0.3,0.1

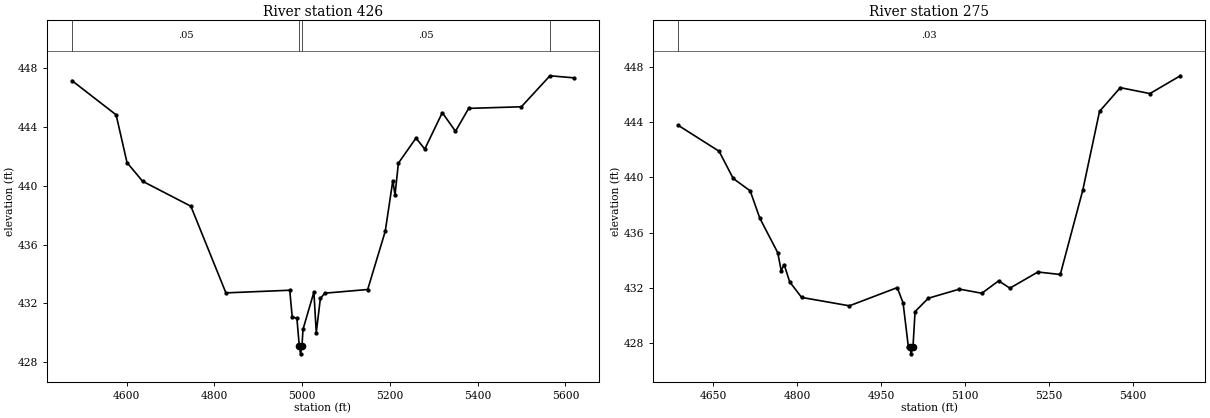
Type RM Length L Ch R = 1 ,426     ,151,151,151
BEGIN DESCRIPTION:
UNT 154 IN BOCR 1.0
END DESCRIPTION:
XS GIS Cut Line= 3
      3734749.18     10673189.73      3734179.75       10673405.
      3734200.58     10673939.74
#Sta/Elev= 30
  4475.4  447.16  4576.1  444.83  4600.9  441.58  4636.4  440.31  4746.4  438.61
  4826.3  432.71  4971.8  432.89  4977.4  431.07  4988.1  430.98  4993.6  429.06
  4996.4  428.56  4999.6  429.06    5002  430.23  5026.8  432.76  5032.2  430.01
  5041.6  432.33  5051.6  432.69  5149.4  432.94  5189.4   436.9  5206.7  440.35
  5211.7  439.38  5219.4  441.54  5259.5  443.25  5279.5   442.5  5319.5  444.98
  5349.5  443.71  5379.6  445.27  5499.7  445.38  5564.8  447.49  5619.3  447.35
#Mann= 4 ,-1 , 0
  4475.4     .05       0  4993.6     .03       0  4999.6     .05       0
  5564.8     .16       0
Bank Sta=4993.6,4999.6
XS Rating Curve= 0 ,0
Exp/Cntr=0.3,0.1

Type RM Length L Ch R = 1 ,275     ,0,0,0
BEGIN DESCRIPTION:
Mapping XS b49c0866
END DESCRIPTION:
XS GIS Cut Line= 3
      3734595.93     10673091.08      3734146.29     10673257.74
      3734130.67     10673674.41
#Sta/Elev= 30
  4587.9  443.77  4660.6   441.9  4685.7  439.93  4716.1  439.03  4733.3  437.05
  4765.3  434.55  4771.5  433.25  4776.8  433.69  4786.6  432.44  4807.9  431.31
  4893.3   430.7  4978.8  432.02  4989.2  430.91  4998.6  427.73  5000.9  427.72
  5003.6  427.22  5006.9  427.72  5010.6  430.28  5034.3  431.25  5089.9  431.91
  5129.9  431.61  5159.9  432.51    5180  431.98    5230  433.15    5270  432.97
  5310.1  439.07  5340.1  444.79  5377.2  446.51  5430.1  446.08  5484.4  447.37
#Mann= 1 ,-1 , 0
  4587.9     .03       0
Bank Sta=5000.9,5006.9
XS Rating Curve= 0 ,0
Exp/Cntr=0.3,0.1

Chan Stop Cuts=-1
Use User Specified Reach Order=0
Composite Channel Slope=5