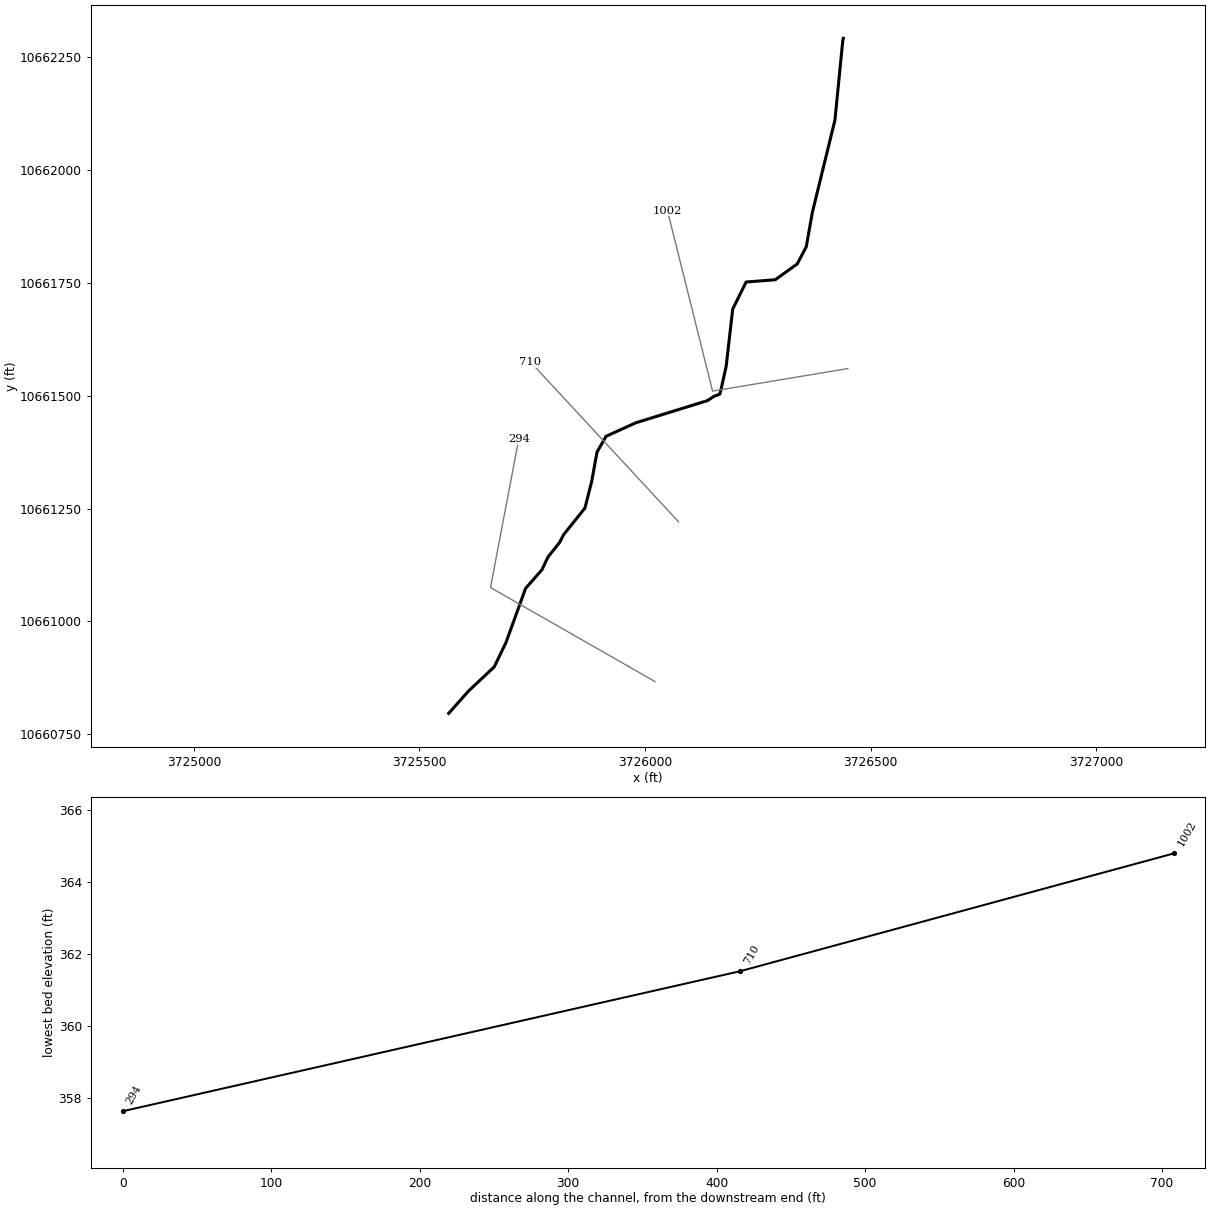
--- UNT 158 IN BOCR.prj (project) ---

Proj Title=UNT 158 IN BOCR Base Level Engineering
Current Plan=p01
Default Exp/Contr=0.3,0.1
English Units
Geom File=g01
Flow File=f01
Plan File=p01
Y Axis Title=Elevation
X Axis Title(PF)=Main Channel Distance
X Axis Title(XS)=Station
BEGIN DESCRIPTION:
UNT 158 IN BOCR
END DESCRIPTION:
DSS Export Rating Curves= 0
DSS Export Rating Curve Sorted= 0
DSS Export Volume Flow Curves= 0
DXF OffsetX= 0
DXF OffsetY= 0
DXF ScaleX= 1
DXF ScaleY= 10

--- UNT 158 IN BOCR.p01 (plan) ---

Plan Title=Multiple Run
Short Identifier=Multiple
Geom File=g01
Flow File=f01
Subcritical Flow
K Sum by GR= 0
Std Step Tol= 0.01
Critical Tol= 0.01
Num of Std Step Trials= 20
Max Error Tol= 0.3
Flow Tol Ratio= 0.001
Split Flow NTrial= 30
Split Flow Tol= 0.02
Split Flow Ratio= 0.02
Log Output Level= 0
Friction Slope Method= 1
Unsteady Friction Slope Method= 2
Unsteady Bridges Friction Slope Method= 1
Parabolic Critical Depth
Global Vel Dist=  1 , 1 , 1
Global Log Level= 0
CheckData=True
Encroach Param= -1, 0, 0, 0
BEGIN DESCRIPTION:
Multiple Run
END DESCRIPTION:

--- UNT 158 IN BOCR.f01 (steady flow) ---

Flow Title=Multiple
Program Version=4.10
Number of Profiles= 7
Profile Names=10-year,25-year,50-year,1pct_min,100-year,1pct_plu,500-year
River Rch & RM=UNT 158 IN BOCR,Reach-1         ,1002
     175     220     254     216     293     396     390
Boundary for River Rch & Prof#=UNT 158 IN BOCR,Reach-1         , 1
Up Type= 0
Dn Type= 3
Dn Slope=0.009
Boundary for River Rch & Prof#=UNT 158 IN BOCR,Reach-1         , 2
Up Type= 0
Dn Type= 3
Dn Slope=0.009
Boundary for River Rch & Prof#=UNT 158 IN BOCR,Reach-1         , 3
Up Type= 0
Dn Type= 3
Dn Slope=0.009
Boundary for River Rch & Prof#=UNT 158 IN BOCR,Reach-1         , 4
Up Type= 0
Dn Type= 3
Dn Slope=0.009
Boundary for River Rch & Prof#=UNT 158 IN BOCR,Reach-1         , 5
Up Type= 0
Dn Type= 3
Dn Slope=0.009
Boundary for River Rch & Prof#=UNT 158 IN BOCR,Reach-1         , 6
Up Type= 0
Dn Type= 3
Dn Slope=0.009
Boundary for River Rch & Prof#=UNT 158 IN BOCR,Reach-1         , 7
Up Type= 0
Dn Type= 3
Dn Slope=0.009
DSS Import GetInterval= 0
DSS Import GetPeak= 0
DSS Import FillOption= 0

--- UNT 158 IN BOCR.g01 (geometry) ---

Geom Title=Existing Conditions
Program Version=4.10

River Reach=UNT 158 IN BOCR ,Reach-1
Reach XY= 28
      3726439.28     10662292.01      3726437.96     10662284.62
      3726420.79     10662110.68      3726370.85     10661906.63
      3726357.25       10661830.      3726337.25       10661792.
       3726288.5       10661757.        3726224.       10661752.
      3726194.25       10661692.      3726179.75       10661565.
        3726167.       10661508.      3726165.81     10661503.44
      3726153.21     10661498.96        3726138.       10661489.
       3725979.5       10661440.       3725913.5       10661410.
       3725893.5       10661375.      3725881.75       10661310.
      3725866.75       10661251.       3725819.5       10661192.
      3725810.75       10661175.      3725785.25       10661143.
      3725771.25       10661114.      3725735.25       10661073.
      3725691.75       10660953.      3725665.75       10660899.
      3725609.25       10660846.      3725564.75       10660796.

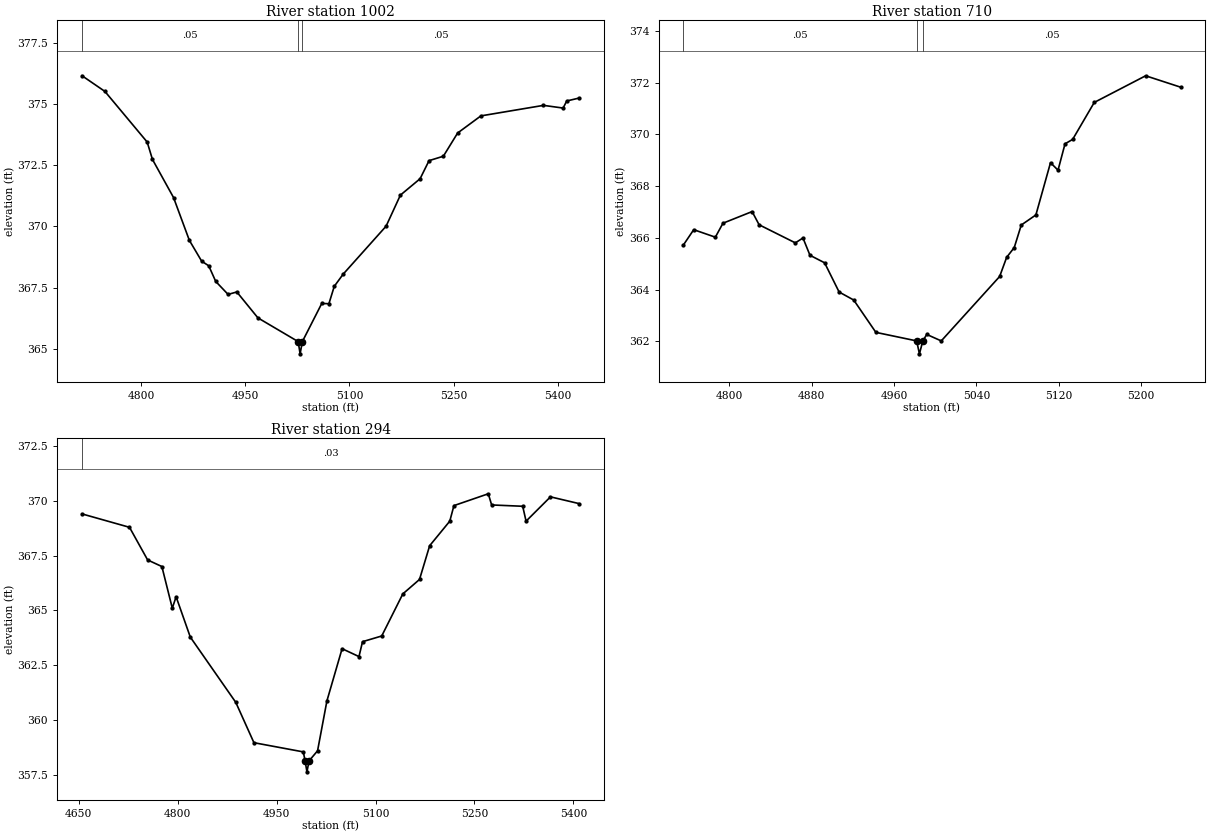
Type RM Length L Ch R = 1 ,1002    ,292,292,292
BEGIN DESCRIPTION:
UNT 158 IN BOCR 2.0
END DESCRIPTION:
XS GIS Cut Line= 3
       3726449.6     10661560.19      3726149.61     10661510.19
      3726049.62     10661910.15
#Sta/Elev= 30
  4714.7  376.16  4747.6  375.52  4808.5  373.45  4816.1  372.74  4846.5  371.18
  4869.3  369.43    4887  368.58  4897.2  368.39  4907.3  367.75  4925.1  367.22
  4937.7  367.32  4968.1  366.26  5026.1  365.29  5028.9  364.79  5032.1  365.29
  5060.1  366.85  5070.4  366.84  5078.1  367.55    5091  368.05  5152.8  370.01
  5173.4  371.28  5201.8  371.95  5214.7  372.69  5235.3  372.87  5255.9  373.82
  5289.4  374.52  5379.6  374.95  5407.9  374.84  5413.1  375.13  5431.1  375.25
#Mann= 3 ,-1 , 0
  4714.7     .05       0  5026.1     .03       0  5032.1     .05       0
Bank Sta=5026.1,5032.1
XS Rating Curve= 0 ,0
Exp/Cntr=0.3,0.1

Type RM Length L Ch R = 1 ,710     ,416,416,416
BEGIN DESCRIPTION:
Mapping XS 4371a97f
END DESCRIPTION:
XS GIS Cut Line= 2
       3726074.1      10661220.7      3725745.97     10661574.86
#Sta/Elev= 30
  4755.4  365.73  4765.4  366.32  4786.4  366.03  4793.8  366.57  4822.1  367.02
  4828.9  366.51  4864.1  365.81  4871.5     366  4878.3  365.33  4892.5  365.04
  4906.6  363.91  4920.8   363.6  4942.3  362.35  4981.9  362.02  4984.6  361.52
  4987.9  362.02  4991.7  362.27  5005.8  362.02  5062.5  364.51  5069.3  365.25
  5076.7  365.63  5083.5   366.5  5097.7  366.89  5111.9  368.91  5119.2  368.62
    5126  369.64  5133.4  369.81  5154.4  371.24  5204.3  372.27  5238.2  371.83
#Mann= 3 ,-1 , 0
  4755.4     .05       0  4981.9     .03       0  4987.9     .05       0
Bank Sta=4981.9,4987.9
XS Rating Curve= 0 ,0
Exp/Cntr=0.3,0.1

Type RM Length L Ch R = 1 ,294     ,0,0,0
BEGIN DESCRIPTION:
UNT 158 IN BOCR 1.0
END DESCRIPTION:
XS GIS Cut Line= 3
        3726022.     10660866.53      3725657.45     10661074.84
      3725719.96     10661402.98
#Sta/Elev= 30
    4655   369.4  4726.9  368.79  4754.4   367.3    4776     367  4791.8   365.1
  4797.6  365.62  4819.1  363.78  4888.1   360.8  4915.6  358.96  4990.5  358.54
  4993.2  358.13    4996  357.63  4999.2  358.13  5012.1  358.59  5026.3  360.87
  5049.3  363.25  5074.9  362.89  5080.3  363.57  5109.4  363.83  5141.4  365.75
  5166.7  366.41  5182.1  367.95  5212.6  369.07  5218.9  369.78    5271  370.32
  5276.1  369.81  5323.2  369.75  5328.3  369.07  5365.3  370.18  5408.9  369.87
#Mann= 1 ,-1 , 0
    4655     .03       0
Bank Sta=4993.2,4999.2
XS Rating Curve= 0 ,0
Exp/Cntr=0.3,0.1

Chan Stop Cuts=-1
Use User Specified Reach Order=0
Composite Channel Slope=5