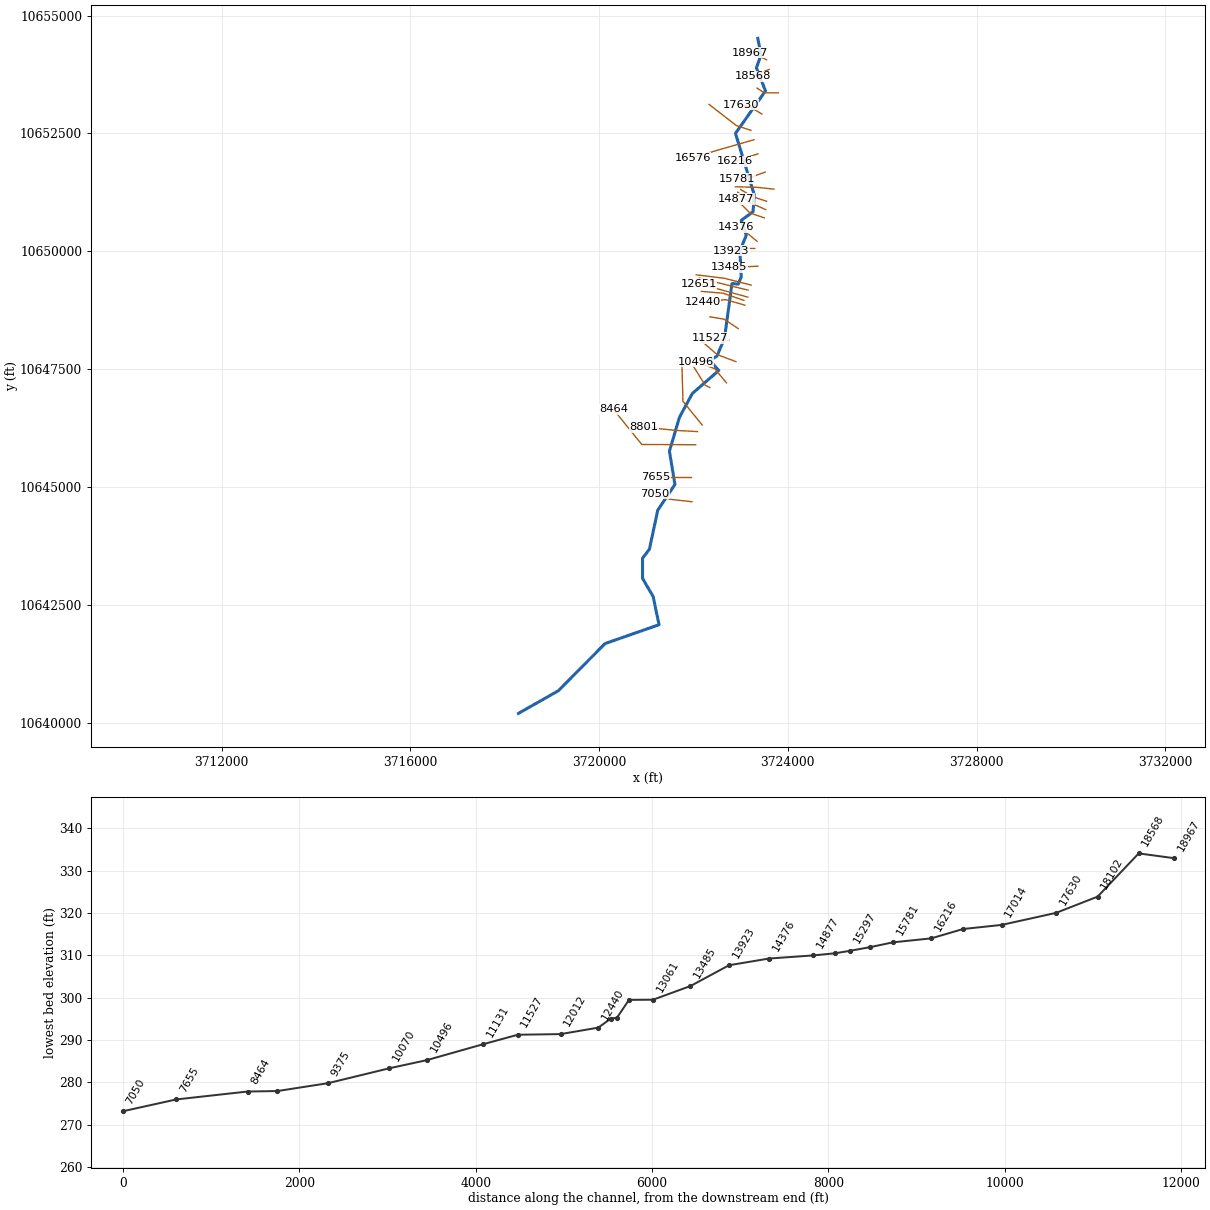
--- UNT 159 IN BOCR.prj (project) ---

Proj Title=UNT 159 IN BOCR Base Level Engineering
Current Plan=p01
Default Exp/Contr=0.3,0.1
English Units
Geom File=g01
Flow File=f01
Plan File=p01
Y Axis Title=Elevation
X Axis Title(PF)=Main Channel Distance
X Axis Title(XS)=Station
BEGIN DESCRIPTION:
UNT 159 IN BOCR
END DESCRIPTION:
DSS Export Rating Curves= 0
DSS Export Rating Curve Sorted= 0
DSS Export Volume Flow Curves= 0
DXF OffsetX= 0
DXF OffsetY= 0
DXF ScaleX= 1
DXF ScaleY= 10

--- UNT 159 IN BOCR.p01 (plan) ---

Plan Title=Multiple Run
Short Identifier=Multiple
Geom File=g01
Flow File=f01
Subcritical Flow
K Sum by GR= 0
Std Step Tol= 0.01
Critical Tol= 0.01
Num of Std Step Trials= 20
Max Error Tol= 0.3
Flow Tol Ratio= 0.001
Split Flow NTrial= 30
Split Flow Tol= 0.02
Split Flow Ratio= 0.02
Log Output Level= 0
Friction Slope Method= 1
Unsteady Friction Slope Method= 2
Unsteady Bridges Friction Slope Method= 1
Parabolic Critical Depth
Global Vel Dist=  1 , 1 , 1
Global Log Level= 0
CheckData=True
Encroach Param= -1, 0, 0, 0
BEGIN DESCRIPTION:
Multiple Run
END DESCRIPTION:

--- UNT 159 IN BOCR.f01 (steady flow) ---

Flow Title=Multiple
Program Version=4.10
Number of Profiles= 7
Profile Names=10-year,25-year,50-year,1pct_min,100-year,1pct_plu,500-year
River Rch & RM=UNT 159 IN BOCR,Reach-1         ,18967
     379     495     587     512     692     936     966
River Rch & RM=UNT 159 IN BOCR,Reach-1         ,13485
     472     624     747     657     888    1201    1260
River Rch & RM=UNT 159 IN BOCR,Reach-1         ,11527
     472     624     747     657     888    1201    1260
River Rch & RM=UNT 159 IN BOCR,Reach-1         ,8801
     872    1188    1450    1297    1754    2372    2577
River Rch & RM=UNT 159 IN BOCR,Reach-1         ,8464
     872    1188    1450    1297    1754    2372    2577
Boundary for River Rch & Prof#=UNT 159 IN BOCR,Reach-1         , 1
Up Type= 0
Dn Type= 3
Dn Slope=0.005
Boundary for River Rch & Prof#=UNT 159 IN BOCR,Reach-1         , 2
Up Type= 0
Dn Type= 3
Dn Slope=0.005
Boundary for River Rch & Prof#=UNT 159 IN BOCR,Reach-1         , 3
Up Type= 0
Dn Type= 3
Dn Slope=0.005
Boundary for River Rch & Prof#=UNT 159 IN BOCR,Reach-1         , 4
Up Type= 0
Dn Type= 3
Dn Slope=0.005
Boundary for River Rch & Prof#=UNT 159 IN BOCR,Reach-1         , 5
Up Type= 0
Dn Type= 3
Dn Slope=0.005
Boundary for River Rch & Prof#=UNT 159 IN BOCR,Reach-1         , 6
Up Type= 0
Dn Type= 3
Dn Slope=0.005
Boundary for River Rch & Prof#=UNT 159 IN BOCR,Reach-1         , 7
Up Type= 0
Dn Type= 3
Dn Slope=0.005
DSS Import GetInterval= 0
DSS Import GetPeak= 0
DSS Import FillOption= 0

--- UNT 159 IN BOCR.g01 (geometry) ---

Geom Title=Existing Conditions
Program Version=4.10

River Reach=UNT 159 IN BOCR ,Reach-1
Reach XY= 30
       3723364.3     10654515.76        3723430.       10654165.
      3723335.56     10653888.76        3723527.       10653401.
      3722890.75       10652500.       3723288.5       10651200.
       3723263.5       10650839.       3723012.5       10650655.
        3723120.       10650340.      3722985.25       10650011.
      3723012.25       10649455.       3722950.5       10649304.
      3722816.75       10649317.      3722657.75       10648156.
        3722498.       10647776.       3722343.5       10647688.
       3722536.5       10647472.      3721975.25       10646983.
      3721703.25       10646479.      3721490.75       10645761.
       3721607.5       10645055.       3721243.5       10644508.
       3721066.5       10643681.       3720920.5       10643490.
      3720922.25       10643061.      3721145.75       10642679.
      3721270.75       10642081.       3720126.5       10641681.
      3719135.25       10640679.        3718292.       10640201.

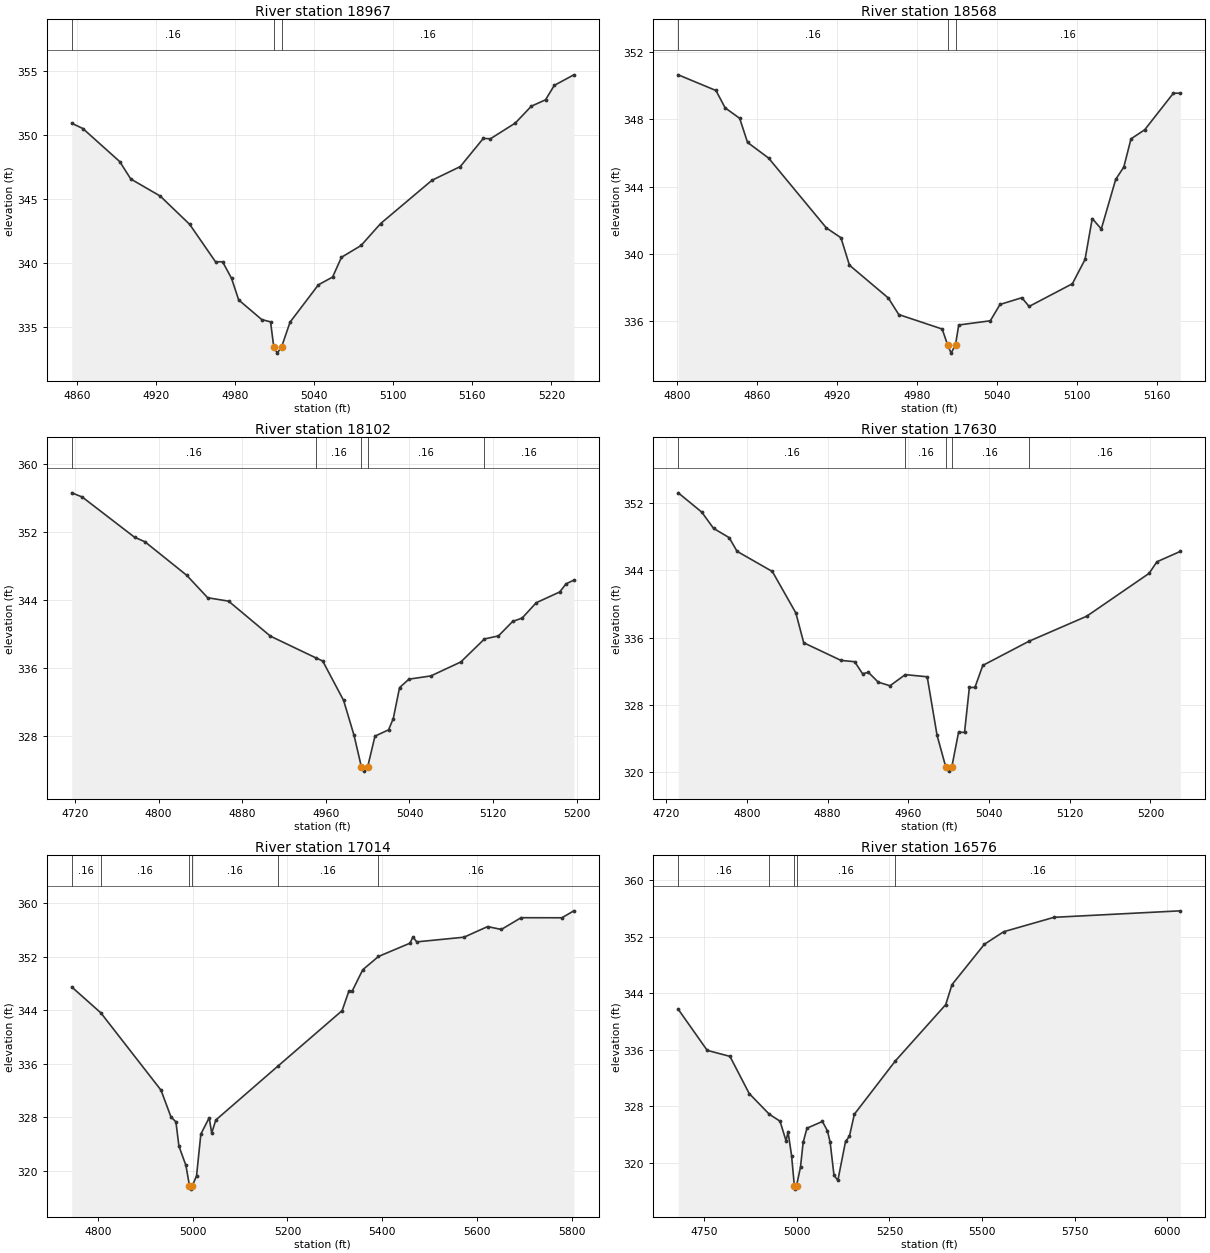
Type RM Length L Ch R = 1 ,18967   ,399,399,399
BEGIN DESCRIPTION:
UNT 159 IN BOCR 22.0
END DESCRIPTION:
XS GIS Cut Line= 3
      3723549.65     10654060.17      3723449.61     10654110.19
      3723199.62     10654210.18
#Sta/Elev= 30
  4855.9  350.93  4864.3  350.52  4892.3  347.94  4900.7  346.58    4923  345.25
  4945.4  343.04    4965  340.12  4970.4  340.12  4977.2  338.82  4982.6  337.14
  5000.1  335.61  5006.8  335.43  5009.2  333.49  5011.9  332.99  5015.2  333.49
  5021.6  335.41  5043.1  338.32  5053.9  338.93  5060.6  340.47  5075.5  341.39
  5090.3   343.1  5129.3  346.48  5150.8  347.55  5168.3  349.75  5173.7  349.72
  5192.6  350.95  5204.7  352.26  5215.5  352.76  5222.2  353.89    5237  354.71
#Mann= 3 ,-1 , 0
  4855.9     .16       0  5009.2     .16       0  5015.2     .16       0
Bank Sta=5009.2,5015.2
XS Rating Curve= 0 ,0
Exp/Cntr=0.3,0.1

Type RM Length L Ch R = 1 ,18568   ,466,466,466
BEGIN DESCRIPTION:
UNT 159 IN BOCR 21.0
END DESCRIPTION:
XS GIS Cut Line= 2
      3723602.04     10653855.63      3723254.97     10653708.94
#Sta/Elev= 30
  4800.9  350.63  4829.2   349.7  4836.1  348.67    4847  348.05  4852.9  346.62
  4868.7  345.69  4912.1  341.54    4923  340.96  4929.4  339.33  4958.6  337.38
  4966.4   336.4    4999  335.54    5003  334.61  5005.7  334.11    5009  334.61
  5011.4  335.78  5035.1  336.03  5042.4     337  5058.8   337.4  5064.2  336.88
  5096.7  338.23  5106.2  339.67  5111.6   342.1  5118.4  341.48  5129.2  344.42
  5135.3  345.16  5140.7  346.83    5151  347.37  5172.5  349.54  5177.7  349.54
#Mann= 3 ,-1 , 0
  4800.9     .16       0    5003     .16       0    5009     .16       0
Bank Sta=5003,5009
XS Rating Curve= 0 ,0
Exp/Cntr=0.3,0.1

Type RM Length L Ch R = 1 ,18102   ,472,472,472
BEGIN DESCRIPTION:
UNT 159 IN BOCR 20.0
END DESCRIPTION:
XS GIS Cut Line= 3
      3723799.57     10653360.19      3723499.61     10653360.19
      3723349.64     10653460.17
#Sta/Elev= 30
    4717  356.57    4727  356.08    4777  351.36    4787  350.82    4827  346.88
    4847  344.25    4867  343.85    4907  339.74  4950.3   337.2    4957  336.82
    4977  332.19    4987  328.08    4994  324.39  4996.7  323.89    5000  324.39
    5007     328    5020  328.74  5024.5  330.06  5030.5   333.7  5039.5  334.69
  5060.5  335.07  5089.1  336.71  5111.7  339.41  5125.1  339.77  5138.7  341.47
  5147.7  341.86  5161.2  343.66  5183.7  344.93  5189.7  345.88  5197.2  346.32
#Mann= 5 ,-1 , 0
    4717     .16       0  4950.3     .16       0    4994     .16       0
    5000     .16       0  5111.7     .16       0
Bank Sta=4994,5000
XS Rating Curve= 0 ,0
Exp/Cntr=0.3,0.1

Type RM Length L Ch R = 1 ,17630   ,616,616,616
BEGIN DESCRIPTION:
UNT 159 IN BOCR 19.0
END DESCRIPTION:
XS GIS Cut Line= 3
      3723449.61     10652910.19      3723199.61     10653060.19
      3722999.61     10653110.19
#Sta/Elev= 30
  4731.9  353.27  4755.2  350.97  4766.9  349.03  4782.4  347.92  4790.2  346.29
  4825.2  343.88  4848.5  338.93  4856.3  335.37  4893.2  333.27  4906.8  333.11
  4914.6  331.68  4920.4  331.84  4930.2  330.67  4941.8  330.24    4957  331.57
  4978.7  331.31  4988.5  324.31  4997.1  320.55  4999.9  320.05  5003.1  320.55
  5009.8   324.7  5015.7  324.67  5020.5  330.04    5026  330.04  5033.8  332.67
  5079.2  335.53  5136.8  338.54  5198.7  343.66  5206.4  345.04  5229.6  346.28
#Mann= 5 ,-1 , 0
  4731.9     .16       0    4957     .16       0  4997.1     .16       0
  5003.1     .16       0  5079.2     .16       0
Bank Sta=4997.1,5003.1
XS Rating Curve= 0 ,0
Exp/Cntr=0.3,0.1

Type RM Length L Ch R = 1 ,17014   ,438,438,438
BEGIN DESCRIPTION:
UNT 159 IN BOCR 18.0
END DESCRIPTION:
XS GIS Cut Line= 3
      3723218.65     10652565.25      3722910.49     10652665.07
      3722329.71     10653115.83
#Sta/Elev= 30
    4745  347.49  4806.4  343.61  4933.2  332.04  4954.2  328.03  4964.7  327.29
    4971  323.66  4985.8  320.76  4993.3  317.71    4996  317.21  4999.3  317.71
  5008.2   319.2  5017.3  325.46  5034.9   327.9  5040.2  325.61  5048.8  327.56
  5179.4  335.61  5315.3  343.95  5329.8  346.93  5336.1  346.82  5358.8  350.07
  5391.9  352.06  5458.3  354.05  5464.7  354.98  5472.8  354.25  5572.4  354.95
  5622.2  356.54  5651.1  356.11  5692.8  357.87  5778.9  357.86  5804.1   358.9
#Mann= 6 ,-1 , 0
    4745     .16       0  4806.4     .16       0  4993.3     .16       0
  4999.3     .16       0  5179.4     .16       0  5391.9     .16       0
Bank Sta=4993.3,4999.3
XS Rating Curve= 0 ,0
Exp/Cntr=0.3,0.1

Type RM Length L Ch R = 1 ,16576   ,360,360,360
BEGIN DESCRIPTION:
UNT 159 IN BOCR 17.0
END DESCRIPTION:
XS GIS Cut Line= 3
      3723283.79     10652365.61      3722571.95      10652161.6
      3721983.12     10651984.09
#Sta/Elev= 30
  4679.9  341.74  4758.1  335.91  4819.5  335.06  4871.5  329.79  4925.7  326.86
  4954.7  325.87  4971.1  323.07  4976.3  324.39  4985.9  320.99  4993.3  316.74
  4996.1  316.24  4999.3  316.74    5010  319.37  5017.1  322.87  5027.5  324.88
  5069.1  325.83  5082.7  324.51    5090  322.89  5100.4  318.21  5110.8  317.47
  5131.6     323    5142  323.72  5155.4  326.86    5266  334.41    5402  342.39
    5419  345.23  5506.4  350.95  5558.6  352.73  5694.4  354.77  6035.4  355.69
#Mann= 5 ,-1 , 0
  4679.9     .16       0  4925.7     .16       0  4993.3     .16       0
  4999.3     .16       0    5266     .16       0
Bank Sta=4993.3,4999.3
XS Rating Curve= 0 ,0
Exp/Cntr=0.3,0.1

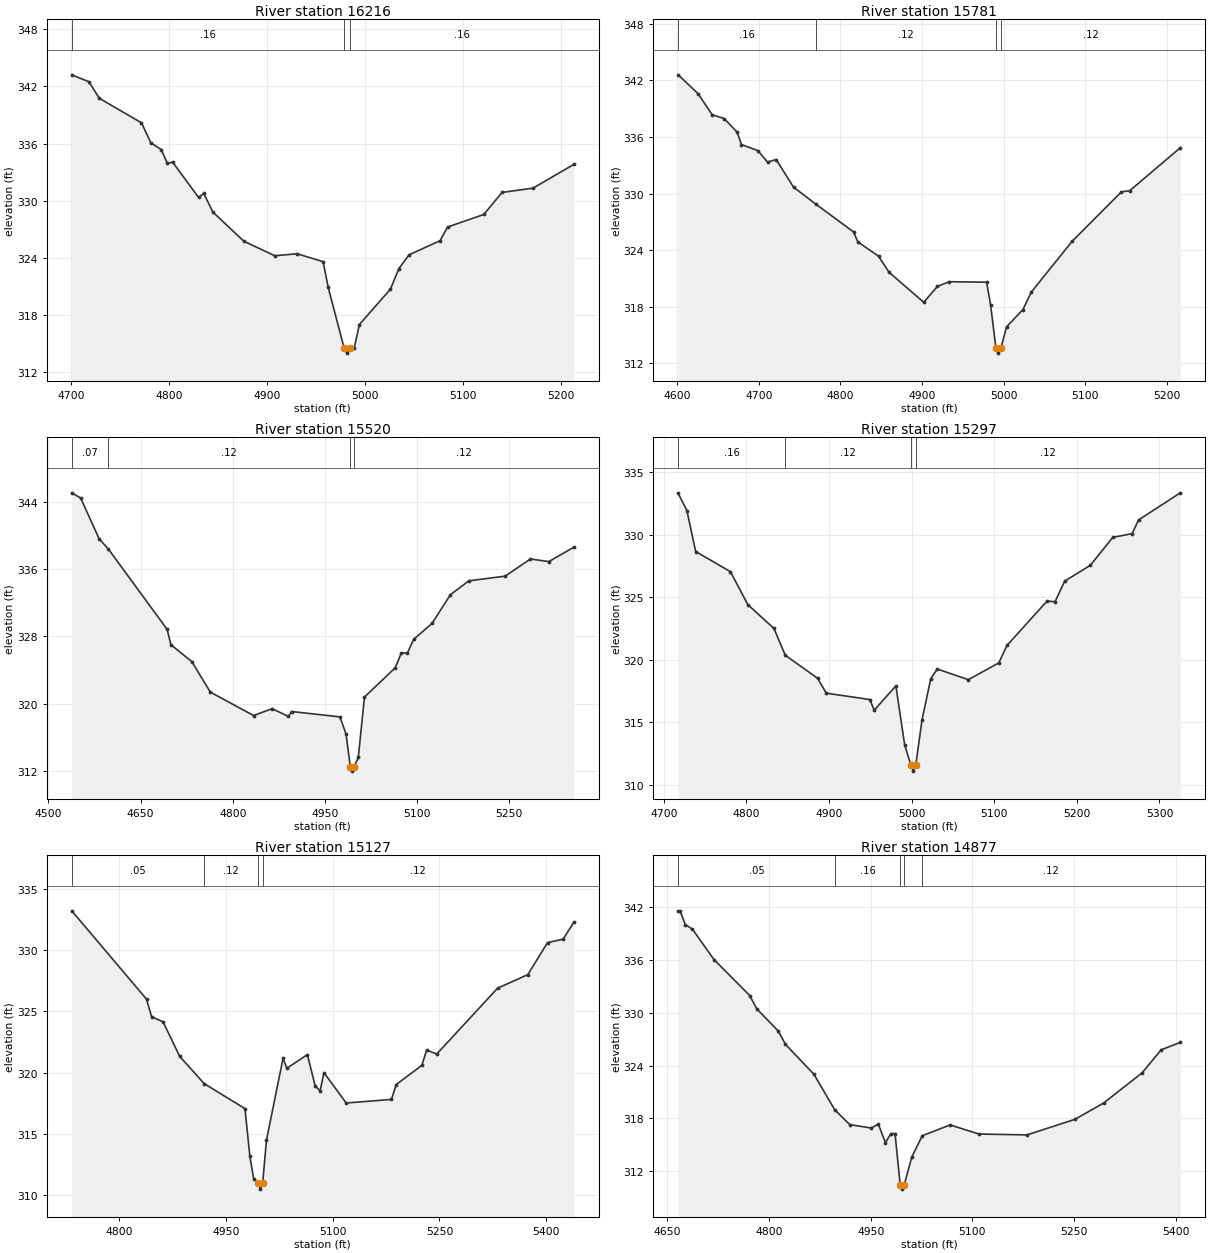
Type RM Length L Ch R = 1 ,16216   ,435,435,435
BEGIN DESCRIPTION:
UNT 159 IN BOCR 16.0
END DESCRIPTION:
XS GIS Cut Line= 2
      3723366.25     10652066.13      3722880.09     10651905.52
#Sta/Elev= 30
  4701.1  343.21  4718.6  342.48  4729.2  340.75  4772.2  338.18  4781.8  336.07
  4792.3  335.38  4798.7  333.92  4803.9  334.06  4830.4  330.36  4835.7  330.77
    4845  328.82  4876.6  325.76  4908.2  324.24  4930.9  324.45  4957.4  323.62
  4962.6  320.92  4978.9  314.53  4981.7  314.03  4984.9  314.53  4989.1  314.54
  4994.4  317.03  5026.1  320.74  5034.6  322.88  5045.1  324.34  5076.7  325.82
  5084.3  327.25  5121.3  328.57  5139.9  330.88  5171.5  331.33  5213.1  333.82
#Mann= 3 ,-1 , 0
  4701.1     .16       0  4978.9     .16       0  4984.9     .16       0
Bank Sta=4978.9,4984.9
XS Rating Curve= 0 ,0
Exp/Cntr=0.3,0.1

Type RM Length L Ch R = 1 ,15781   ,261,261,261
BEGIN DESCRIPTION:
UNT 159 IN BOCR 15.0
END DESCRIPTION:
XS GIS Cut Line= 3
      3723522.44     10651679.82      3723222.99     10651571.32
      3722927.85     10651540.94
#Sta/Elev= 30
  4601.3  342.59  4625.6  340.59  4642.9  338.36  4657.5  337.96  4673.5  336.51
  4678.8   335.2  4698.8  334.56  4710.7  333.34  4721.3  333.61  4742.6  330.68
  4770.1  328.87  4816.1  325.94  4821.4  324.88  4846.7  323.37  4859.6  321.66
  4902.1  318.48  4918.9  320.16  4933.3  320.66  4979.1  320.61  4984.1  318.18
  4990.6  313.59  4993.3  313.09  4996.6  313.59  5003.6  315.88  5023.7  317.71
  5033.8  319.55    5084  324.95  5144.4  330.19  5154.4   330.3  5216.5  334.86
#Mann= 4 ,-1 , 0
  4601.3     .16       0  4770.1     .12       0  4990.6     .07       0
  4996.6     .12       0
Bank Sta=4990.6,4996.6
XS Rating Curve= 0 ,0
Exp/Cntr=0.3,0.1

Type RM Length L Ch R = 1 ,15520   ,223,223,223
BEGIN DESCRIPTION:
Mapping XS bec87f85
END DESCRIPTION:
XS GIS Cut Line= 3
      3723703.94     10651318.25      3723331.58     10651357.31
      3722888.91     10651367.72
#Sta/Elev= 30
  4537.9  345.13  4552.3  344.51  4582.5  339.64  4597.4  338.43  4693.1  328.85
  4699.2  327.02  4733.3     325  4763.5  321.36  4833.8  318.57    4864  319.39
  4890.6  318.46  4895.6  319.05  4974.3  318.41  4984.3  316.38  4991.3  312.44
    4994  311.94  4997.3  312.44  5004.3  313.59  5014.3  320.77  5064.3  324.26
  5074.3  326.02  5084.3  326.04  5094.3  327.65  5124.3  329.56  5154.3  332.99
  5184.3  334.64  5243.3  335.19  5284.4  337.24  5314.4  336.93  5355.1  338.65
#Mann= 4 ,-1 , 0
  4537.9     .07       0  4597.4     .12       0  4991.3     .07       0
  4997.3     .12       0
Bank Sta=4991.3,4997.3
XS Rating Curve= 0 ,0
Exp/Cntr=0.3,0.1

Type RM Length L Ch R = 1 ,15297   ,170,170,170
BEGIN DESCRIPTION:
UNT 159 IN BOCR 14.0
END DESCRIPTION:
XS GIS Cut Line= 3
      3723549.61     10651060.19      3723249.61     10651160.19
      3722999.59      10651310.2
#Sta/Elev= 30
  4717.4  333.29  4727.9  331.92  4738.5  328.65  4780.6  327.04  4801.7   324.4
  4833.3   322.5    4847  320.36  4886.1  318.52  4896.6  317.33  4949.3  316.82
  4954.6  315.97  4980.9  317.91  4991.5   313.2    4999   311.6  5001.8   311.1
    5005   311.6  5012.5  315.19  5023.1  318.49    5031  319.26  5068.6  318.41
  5105.5  319.75  5115.3  321.14  5163.9  324.69  5173.6  324.64  5185.2  326.28
  5216.3  327.55  5243.5  329.78  5266.9  330.08  5274.6  331.17  5325.2  333.34
#Mann= 4 ,-1 , 0
  4717.4     .16       0    4847     .12       0    4999     .07       0
    5005     .12       0
Bank Sta=4999,5005
XS Rating Curve= 0 ,0
Exp/Cntr=0.3,0.1

Type RM Length L Ch R = 1 ,15127   ,250,250,250
BEGIN DESCRIPTION:
Mapping XS 9d7961ab
END DESCRIPTION:
XS GIS Cut Line= 3
      3723532.11     10650883.34      3723190.96     10651034.39
      3722940.95     10651253.15
#Sta/Elev= 30
  4733.5  333.19  4838.5  325.99  4845.6  324.57  4861.8  324.14  4885.1  321.33
  4919.5  319.11  4976.8  317.07  4983.7  313.17  4989.2   311.3  4995.7  311.01
  4998.5  310.51  5001.7  311.01    5007   314.5  5030.3  321.17  5035.7  320.36
  5064.5  321.47  5075.3  318.95  5082.3  318.51  5087.8     320    5119  317.53
  5182.6  317.82  5189.2  319.03  5225.3   320.6    5232  321.84  5246.2  321.52
  5331.6  326.88  5374.1  327.99  5401.9   330.6  5423.7  330.88  5438.8  332.26
#Mann= 4 ,-1 , 0
  4733.5     .05       0  4919.5     .12       0  4995.7     .07       0
  5001.7     .12       0
Bank Sta=4995.7,5001.7
XS Rating Curve= 0 ,0
Exp/Cntr=0.3,0.1

Type RM Length L Ch R = 1 ,14877   ,501,501,501
BEGIN DESCRIPTION:
UNT 159 IN BOCR 13.0
END DESCRIPTION:
XS GIS Cut Line= 3
      3723499.57      10650710.2      3723199.61     10650810.19
      3722899.64     10651110.16
#Sta/Elev= 30
  4666.2  341.52  4668.8  341.52  4676.7  339.95  4687.2  339.44  4718.9     336
  4771.6  331.93  4782.1  330.41  4813.7  327.91  4824.3   326.4  4866.4     323
  4896.9     319  4919.1  317.31  4950.8  316.92  4961.3  317.35  4971.8  315.26
  4979.7  316.28  4985.9  316.28  4993.5   310.5  4996.3     310  4999.5   310.5
  5010.7  313.66  5026.1  316.05  5067.2  317.27  5109.7  316.24  5180.4  316.14
  5251.1   317.9  5293.5  319.75  5350.1  323.16  5378.4  325.78  5406.6  326.62
#Mann= 5 ,-1 , 0
  4666.2     .05       0  4896.9     .16       0  4993.5     .07       0
  4999.5     .16       0  5026.1     .12       0
Bank Sta=4993.5,4999.5
XS Rating Curve= 0 ,0
Exp/Cntr=0.3,0.1

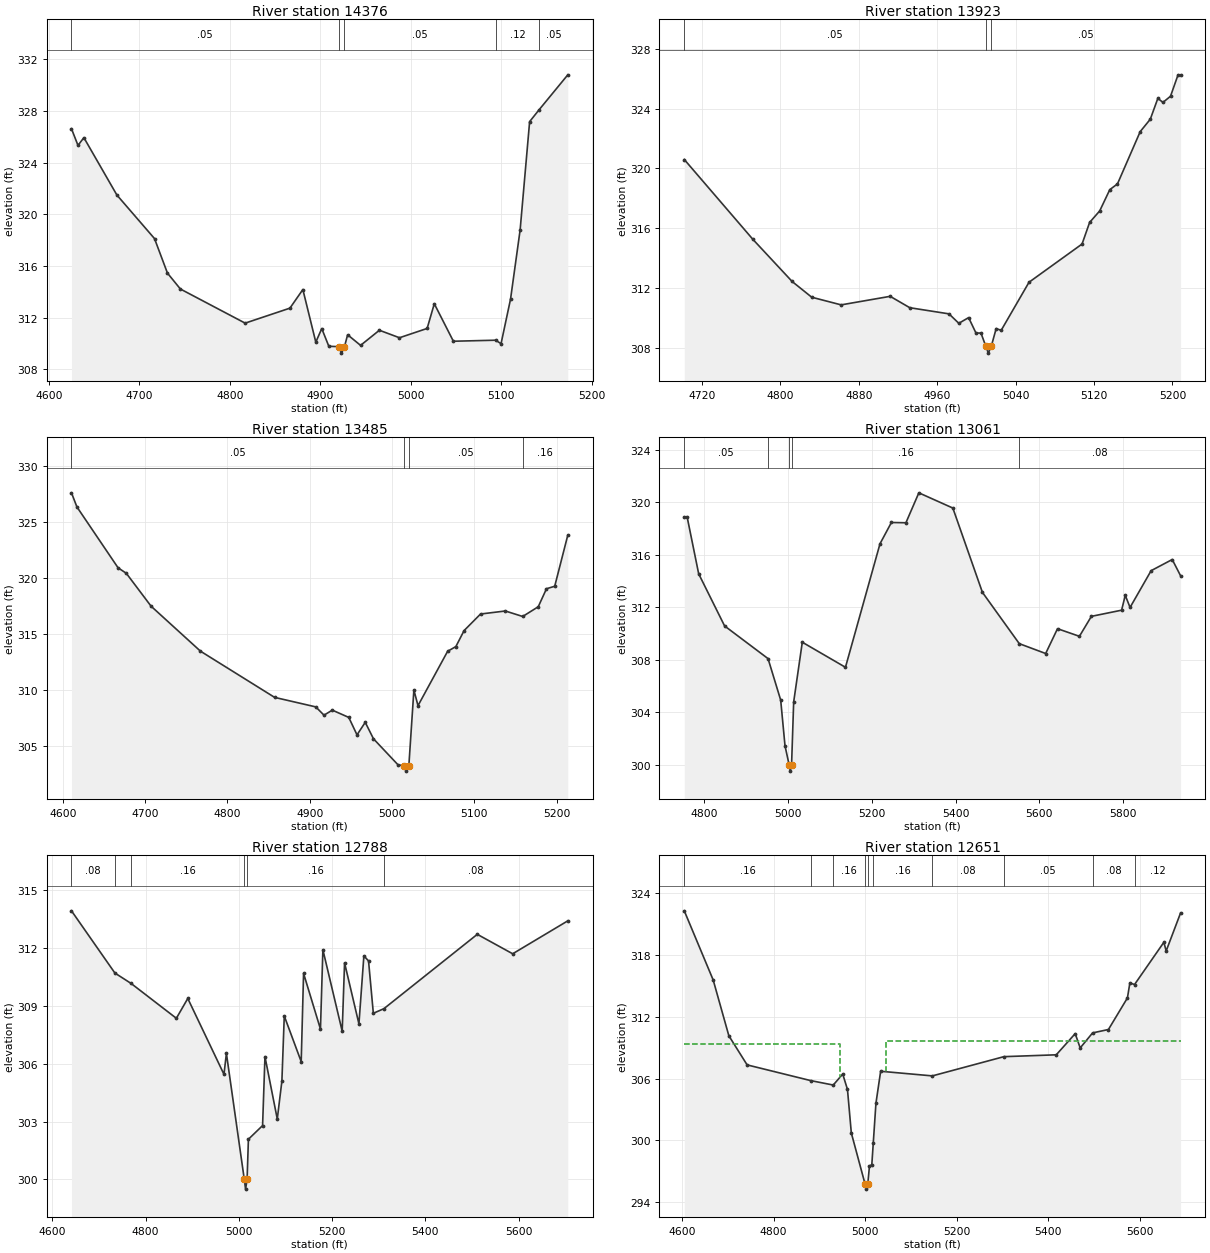
Type RM Length L Ch R = 1 ,14376   ,453,453,453
BEGIN DESCRIPTION:
UNT 159 IN BOCR 12.0
END DESCRIPTION:
XS GIS Cut Line= 3
      3723349.64     10650210.16      3723049.61     10650460.19
      3722899.57      10650510.2
#Sta/Elev= 30
    4625  326.62  4632.2  325.33  4638.7  325.93  4675.2  321.49  4716.8  318.12
  4731.1  315.45  4745.4  314.22    4817  311.58  4866.5  312.74  4880.8  314.18
  4895.1  310.11  4901.7  311.16  4909.5  309.79  4920.8  309.76  4923.5  309.26
  4926.8  309.76  4930.3  310.68  4944.6  309.86  4965.4  311.03  4987.6  310.45
  5018.2  311.17  5026.1  313.08  5047.2  310.18  5093.9  310.26  5099.9  309.99
  5110.4  313.44    5121  318.79  5131.5  327.17    5142  328.09  5173.7  330.79
#Mann= 5 ,-1 , 0
    4625     .05       0  4920.8     .03       0  4926.8     .05       0
  5093.9     .12       0    5142     .05       0
Bank Sta=4920.8,4926.8
XS Rating Curve= 0 ,0
Exp/Cntr=0.3,0.1

Type RM Length L Ch R = 1 ,13923   ,438,438,438
BEGIN DESCRIPTION:
UNT 159 IN BOCR 11.0
END DESCRIPTION:
XS GIS Cut Line= 3
      3723299.65     10650060.19      3722999.61     10650060.19
       3722799.6     10650010.19
#Sta/Elev= 30
  4702.1   320.6  4772.1  315.27  4812.1  312.46  4832.1  311.41  4862.1   310.9
  4912.1  311.47  4932.1  310.71  4972.1   310.3  4982.1  309.67  4992.1  310.05
  4999.6  309.02  5004.7  309.02  5009.4  308.18  5012.2  307.68  5015.4  308.18
  5020.2  309.32  5025.3   309.2  5053.7  312.41  5107.8  314.96  5115.5   316.4
  5125.8  317.17  5136.1  318.59  5143.9  318.97  5167.1  322.46  5177.4  323.29
  5185.1  324.68  5190.3  324.41    5198  324.82  5205.7  326.25  5208.3  326.25
#Mann= 3 ,-1 , 0
  4702.1     .05       0  5009.4    .035       0  5015.4     .05       0
Bank Sta=5009.4,5015.4
XS Rating Curve= 0 ,0
Exp/Cntr=0.3,0.1

Type RM Length L Ch R = 1 ,13485   ,424,424,424
BEGIN DESCRIPTION:
Mapping XS 2a85a99d
END DESCRIPTION:
XS GIS Cut Line= 2
      3723366.17      10649683.3      3722763.73      10649657.3
#Sta/Elev= 30
  4610.6  327.63  4617.2  326.37  4667.2  320.93  4677.2  320.44  4707.3   317.5
  4767.3  313.48  4857.4  309.35  4907.4   308.5  4917.4  307.76  4927.5  308.21
  4947.5  307.56  4957.5     306  4967.5  307.12  4977.5  305.65  5007.5  303.31
  5014.5  303.26  5017.3  302.76  5020.5  303.26  5026.6  310.01  5031.6  308.61
  5067.6  313.47  5077.6  313.89  5087.6  315.32  5107.6   316.8  5137.7  317.07
  5158.8  316.58  5177.7  317.45  5187.7  319.06  5197.7  319.28  5213.6  323.85
#Mann= 4 ,-1 , 0
  4610.6     .05       0  5014.5     .03       0  5020.5     .05       0
  5158.8     .16       0
Bank Sta=5014.5,5020.5
XS Rating Curve= 0 ,0
Exp/Cntr=0.3,0.1

Type RM Length L Ch R = 1 ,13061   ,273,273,273
BEGIN DESCRIPTION:
Mapping XS 5e660460
END DESCRIPTION:
XS GIS Cut Line= 3
      3723222.97       10649284.      3722654.42     10649427.23
      3722059.79     10649501.01
#Sta/Elev= 30
  4752.1  318.89  4758.8  318.91  4786.5  314.56  4848.4  310.59  4952.2   308.1
  4982.4  304.94  4992.7  301.46  5002.4  300.03  5005.1  299.53  5008.4  300.03
  5013.4   304.8    5034  309.35  5137.1  307.44  5219.6  316.85  5246.8  318.47
  5281.5  318.45  5312.4  320.73  5393.6  319.57  5464.2  313.15  5552.3  309.24
  5615.3  308.49  5643.6  310.38  5695.9   309.8  5724.5  311.32  5796.7  311.79
  5805.4  312.92  5816.9     312  5867.2   314.8  5917.6  315.65  5937.6  314.41
#Mann= 5 ,-1 , 0
  4752.1     .05       0  4952.2     .16       0  5002.4     .07       0
  5008.4     .16       0  5552.3     .08       0
Bank Sta=5002.4,5008.4
XS Rating Curve= 0 ,0
Exp/Cntr=0.3,0.1

Type RM Length L Ch R = 1 ,12788   ,137,137,137
BEGIN DESCRIPTION:
Mapping XS 4189e2e5
END DESCRIPTION:
XS GIS Cut Line= 2
      3723157.91     10649175.49      3722124.88     10649431.57
#Sta/Elev= 30
  4641.1  313.94  4734.2  310.71  4768.9  310.17    4866  308.36  4890.5  309.39
  4968.1  305.45  4973.3  306.54  5011.7  299.99  5014.4  299.49  5017.7  299.99
  5020.5  302.08  5050.9  302.79    5056  306.37  5082.4  303.13  5092.3   305.1
  5097.4  308.48  5133.7  306.11  5138.8  310.69    5175   307.8  5180.2  311.92
  5221.6  307.69  5226.7  311.24  5257.5  308.07  5268.1   311.6  5278.1  311.34
  5288.4  308.62  5311.1  308.86  5511.3  312.72  5587.2  311.71  5705.4  313.42
#Mann= 6 ,-1 , 0
  4641.1     .08       0  4734.2     .05       0  4768.9     .16       0
  5011.7     .07       0  5017.7     .16       0  5311.1     .08       0
Bank Sta=5011.7,5017.7
XS Rating Curve= 0 ,0
Exp/Cntr=0.3,0.1

Type RM Length L Ch R = 1 ,12651   ,68,68,68
BEGIN DESCRIPTION:
UNT 159 IN BOCR 9.0
END DESCRIPTION:
XS GIS Cut Line= 2
      3723153.51     10649027.93      3722107.52     10649314.38
#Sta/Elev= 30
  4604.9  322.31  4668.1  315.58  4702.3  310.16  4742.2  307.33  4881.4   305.8
  4930.4  305.37  4951.1  306.44  4961.5  304.94  4969.9  300.71  4999.9  295.75
  5002.7  295.25  5005.9  295.75  5009.5  297.48  5014.7  297.64  5017.9  299.76
  5023.7   303.6    5034  306.71  5146.9  306.26  5303.3  308.13  5417.7  308.31
  5459.1  310.37    5470  308.98  5497.1  310.44  5531.7  310.77  5573.2  313.84
  5578.6  315.31  5588.7  315.14  5652.8  319.25  5657.9  318.41  5689.4  322.11
#Mann= 10 ,-1 , 0
  4604.9     .16       0  4881.4     .05       0  4930.4     .16       0
  4999.9     .07       0  5005.9     .08       0  5017.9     .16       0
  5146.9     .08       0  5303.3     .05       0  5497.1     .08       0
  5588.7     .12       0
#XS Ineff= 2 , 0
         4944.32  309.38 5046.59          309.64
Permanent Ineff=
       F       F
Bank Sta=4999.9,5005.9
XS Rating Curve= 0 ,0
Exp/Cntr=0.3,0.1

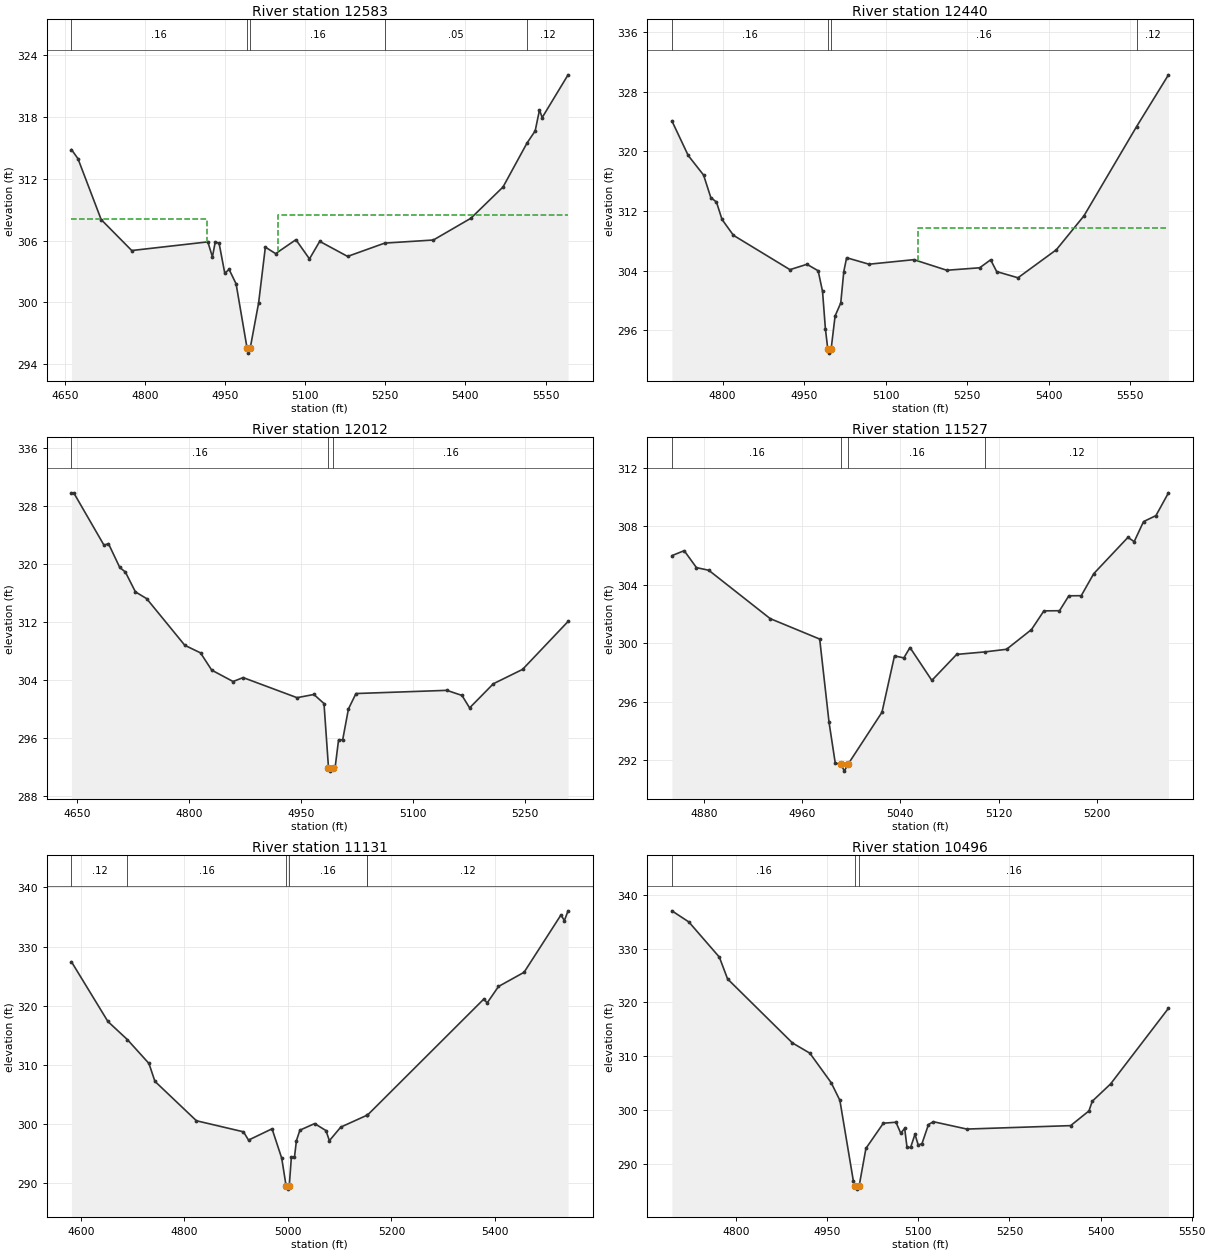
Type RM Length L Ch R = 1 ,12583   ,143,143,143
BEGIN DESCRIPTION:
Mapping XS 5f3945b2
END DESCRIPTION:
XS GIS Cut Line= 3
      3723071.08     10648958.48      3722628.37     10649110.39
      3722168.28     10649149.45
#Sta/Elev= 30
  4662.4  314.82  4674.5  313.94    4718  308.03  4775.2  305.03  4917.7  305.87
  4926.3  304.41  4931.6  305.87  4938.8  305.73  4949.4  302.83  4957.5   303.2
  4970.6   301.8  4991.1  295.58  4993.8  295.08  4997.1  295.58  5012.8  299.96
  5025.4  305.36  5044.6  304.73  5082.6  306.08    5108  304.22  5127.2  305.92
  5179.4  304.46  5248.9  305.75    5340  306.05  5410.2  308.16  5470.4  311.19
  5515.4  315.46  5530.6  316.63  5538.7  318.66  5543.8  317.93  5592.2  322.07
#Mann= 5 ,-1 , 0
  4662.4     .16       0  4991.1     .07       0  4997.1     .16       0
  5248.9     .05       0  5515.4     .12       0
#XS Ineff= 2 , 0
       0 4916.48  308.07    5050       0  308.52
Permanent Ineff=
       F       F
Bank Sta=4991.1,4997.1
XS Rating Curve= 0 ,0
Exp/Cntr=0.3,0.1

Type RM Length L Ch R = 1 ,12440   ,428,428,428
BEGIN DESCRIPTION:
UNT 159 IN BOCR 8.0
END DESCRIPTION:
XS GIS Cut Line= 3
      3723088.49     10648858.64      3722676.12     10648975.84
      3722194.93     10648915.15
#Sta/Elev= 30
  4706.7  324.09  4736.7  319.45    4765  316.82  4778.3   313.8  4788.7   313.2
  4798.9  310.87  4819.9  308.74  4923.9  304.13  4955.2  304.85  4975.8  303.98
  4983.9   301.2  4989.1  296.23  4993.6  293.43  4996.4  292.93  4999.6  293.43
    5007  297.92  5017.4  299.66    5023  303.88  5028.2  305.73  5069.4  304.86
    5152  305.47  5212.5  304.05    5273  304.38  5293.2  305.45  5304.3  303.87
  5343.5  303.04  5414.1   306.8  5464.9  311.35  5561.6  323.31  5620.4  330.27
#Mann= 4 ,-1 , 0
  4706.7     .16       0  4993.6     .07       0  4999.6     .16       0
  5561.6     .12       0
#XS Ineff= 2 , 0
       0                    5160       0  309.71
Permanent Ineff=
       F       F
Bank Sta=4993.6,4999.6
XS Rating Curve= 0 ,0
Exp/Cntr=0.3,0.1

Type RM Length L Ch R = 1 ,12012   ,485,485,485
BEGIN DESCRIPTION:
UNT 159 IN BOCR 7.0
END DESCRIPTION:
XS GIS Cut Line= 3
      3722949.58     10648360.21      3722649.61     10648560.19
      3722349.56      10648610.2
#Sta/Elev= 30
  4642.9  329.78  4645.9  329.78  4686.4  322.56  4692.4  322.77  4707.5  319.49
    4715  318.86  4728.5  316.12  4743.5  315.19  4794.6  308.75  4815.6  307.71
  4830.6  305.33  4859.2  303.76  4872.7   304.3  4944.8  301.53  4967.4  301.97
  4980.9  300.72  4986.9   291.9  4989.6   291.4  4992.9   291.9  4995.9     292
  5000.4  295.71  5005.9  295.71  5013.6  299.97  5023.7   302.1  5145.3  302.54
  5165.6  301.84  5175.8  300.12  5207.6  303.45  5246.7  305.43  5307.6  312.04
#Mann= 3 ,-1 , 0
  4642.9     .16       0  4986.9     .07       0  4992.9     .16       0
Bank Sta=4986.9,4992.9
XS Rating Curve= 0 ,0
Exp/Cntr=0.3,0.1

Type RM Length L Ch R = 1 ,11527   ,396,396,396
BEGIN DESCRIPTION:
UNT 159 IN BOCR 6.0
END DESCRIPTION:
XS GIS Cut Line= 3
      3722749.66     10648110.19      3722649.61     10648110.19
      3722349.59     10648160.19
#Sta/Elev= 30
  4854.1     306  4864.1  306.34  4874.1  305.18  4884.1     305  4934.1  301.69
  4974.4  300.29    4982   294.6  4987.1  291.78  4991.7  291.75  4994.4  291.25
  4997.7  291.75  5025.1  295.28  5035.3  299.14  5042.9     299  5047.9  299.71
  5065.7  297.46  5085.9  299.24  5108.7  299.41  5126.5  299.59  5146.8  300.94
  5156.9  302.22  5169.6  302.23  5177.2  303.25  5187.3  303.26  5197.5  304.77
  5225.3  307.25  5230.4  306.96    5238  308.33  5248.1  308.74  5258.3   310.3
#Mann= 4 ,-1 , 0
  4854.1     .16       0  4991.7     .07       0  4997.7     .16       0
  5108.7     .12       0
Bank Sta=4991.7,4997.7
XS Rating Curve= 0 ,0
Exp/Cntr=0.3,0.1

Type RM Length L Ch R = 1 ,11131   ,635,635,635
BEGIN DESCRIPTION:
UNT 159 IN BOCR 5.0
END DESCRIPTION:
XS GIS Cut Line= 3
      3722899.62     10647660.18      3722499.61     10647810.19
      3722099.62     10648160.17
#Sta/Elev= 30
  4582.2  327.42  4652.5  317.33  4690.1  314.27  4731.7  310.24  4743.3  307.21
  4823.4  300.55  4914.2  298.68    4924  297.28  4969.4  299.19  4988.1  294.21
  4996.6  289.49  4999.4  288.99  5002.6  289.49  5006.7   294.4  5012.7   294.4
  5016.5   297.2  5023.2  298.96  5051.6  300.07  5073.5  298.89  5080.1  297.18
    5102  299.47  5153.1   301.5  5153.6   301.5  5378.1  321.11  5384.8  320.48
  5406.6  323.25    5456  325.65  5527.2  335.34  5533.8  334.39  5540.9  336.04
#Mann= 6 ,-1 , 0
  4582.2     .12       0  4690.1     .16       0  4996.6     .07       0
  5002.6     .16       0  5153.1     .05       0  5153.6     .12       0
Bank Sta=4996.6,5002.6
XS Rating Curve= 0 ,0
Exp/Cntr=0.3,0.1

Type RM Length L Ch R = 1 ,10496   ,426,426,426
BEGIN DESCRIPTION:
UNT 159 IN BOCR 4.0
END DESCRIPTION:
XS GIS Cut Line= 3
      3722699.58     10647210.22      3722449.61     10647510.19
      3722049.58      10647660.2
#Sta/Elev= 30
  4694.1  337.05    4722  334.98  4772.2  328.44  4785.8  324.37  4892.6  312.46
  4921.2  310.56  4956.3  305.08  4970.7  301.78  4992.8  286.84  4996.3  285.75
  4999.1  285.25  5002.3  285.75  5013.6  292.83  5042.3  297.52  5063.1   297.7
  5070.9  295.67  5077.4  296.55  5081.3  293.01  5087.2  293.01  5094.4  295.47
  5099.7  293.45  5105.9  293.72  5116.6  297.27  5124.6   297.8  5179.8  296.43
  5350.7  297.07  5380.9  299.81  5386.3  301.61  5416.5  304.83  5511.8  318.91
#Mann= 3 ,-1 , 0
  4694.1     .16       0  4996.3     .07       0  5002.3     .16       0
Bank Sta=4996.3,5002.3
XS Rating Curve= 0 ,0
Exp/Cntr=0.3,0.1

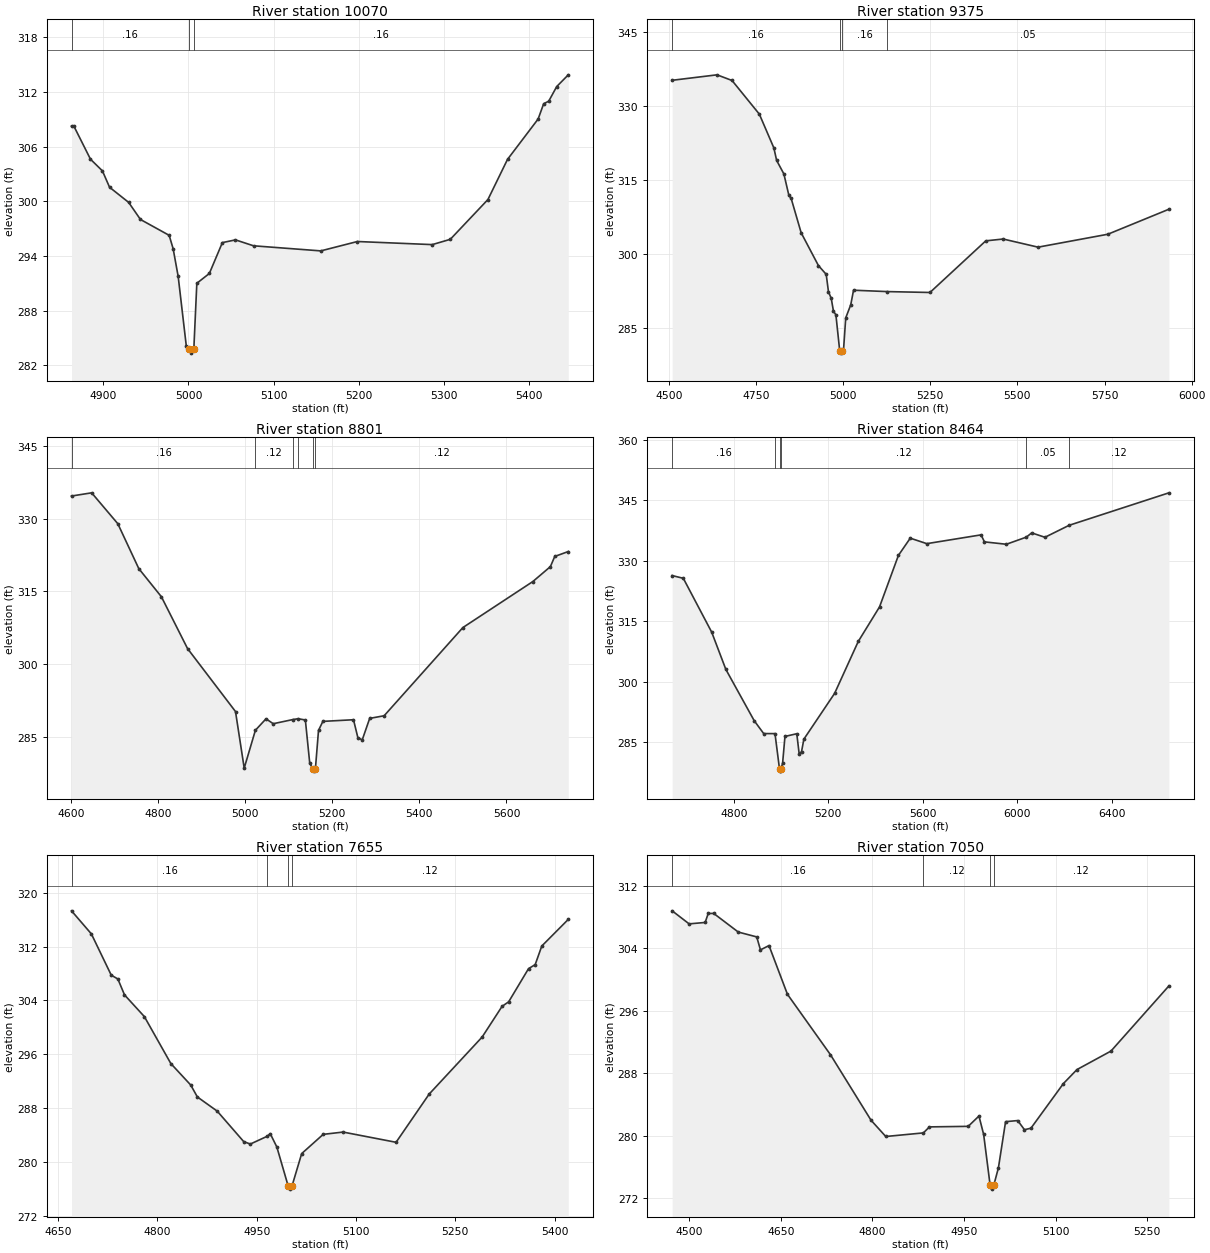
Type RM Length L Ch R = 1 ,10070   ,695,695,695
BEGIN DESCRIPTION:
UNT 159 IN BOCR 3.0
END DESCRIPTION:
XS GIS Cut Line= 3
      3722349.59      10647110.2      3722249.61     10647160.19
       3721999.6     10647560.21
#Sta/Elev= 30
  4862.6  308.25  4865.4  308.25  4884.9  304.62  4898.9  303.34  4907.3  301.54
  4929.7  299.88  4943.6     298  4977.3  296.26    4982  294.78  4987.9  291.74
  4997.4  284.13  5000.3  283.82    5003  283.32  5006.3  283.82  5009.8  290.99
  5024.5  292.07  5039.8  295.46  5055.2  295.76  5076.4  295.11  5155.4  294.55
  5198.4  295.58  5286.3  295.24  5307.5  295.82  5351.7  300.19  5374.7   304.6
  5410.7  309.04  5417.2  310.72  5423.1  310.99  5432.5   312.6  5446.1  313.89
#Mann= 3 ,-1 , 0
  4862.6     .16       0  5000.3     .07       0  5006.3     .16       0
Bank Sta=5000.3,5006.3
XS Rating Curve= 0 ,0
Exp/Cntr=0.3,0.1

Type RM Length L Ch R = 1 ,9375    ,574,574,574
BEGIN DESCRIPTION:
UNT 159 IN BOCR 2.0
END DESCRIPTION:
XS GIS Cut Line= 3
      3722185.64     10646315.27      3721777.68     10646818.72
      3721755.98     10647595.43
#Sta/Elev= 30
  4509.8  335.18  4638.5  336.29  4681.6  335.14  4759.9  328.31  4801.5  321.46
  4809.5  318.92  4830.3  316.17  4844.7   311.8  4851.1  311.22  4879.9  304.22
  4929.4  297.57  4951.7  295.79  4958.2  292.25  4966.1  290.92  4972.6  288.29
  4979.5  287.58  4990.4   280.3  4993.1   279.8  4996.4   280.3  5001.3  280.35
  5007.7  286.95  5022.1  289.61  5030.1  292.57  5127.2  292.29  5249.3  292.11
  5409.4  302.59  5459.4  302.96  5559.4  301.31  5759.5  303.93  5934.8  309.01
#Mann= 4 ,-1 , 0
  4509.8     .16       0  4990.4     .07       0  4996.4     .16       0
  5127.2     .05       0
Bank Sta=4990.4,4996.4
XS Rating Curve= 0 ,0
Exp/Cntr=0.3,0.1

Type RM Length L Ch R = 1 ,8801    ,337,337,337
BEGIN DESCRIPTION:
UNT 159 IN BOCR 1.0
END DESCRIPTION:
XS GIS Cut Line= 3
      3722085.81     10646176.36      3721621.43      10646202.4
      3720948.72     10646271.84
#Sta/Elev= 30
  4600.7  334.68    4647  335.34  4707.1  328.97  4755.3  319.71  4807.2  313.91
  4867.3  303.22  4977.5  290.23  4997.5  278.56  5023.2  286.37  5047.6  288.73
  5064.2  287.72  5108.5  288.56  5121.1  288.75    5138  288.49  5148.1  279.55
  5155.1  278.44  5157.9  277.94  5161.1  278.44  5168.2  286.33  5178.2   288.2
  5248.6  288.54  5258.7  284.82  5268.7  284.39  5285.8  288.82    5319  289.36
  5499.9  307.55  5660.8  317.05    5701  320.12    5711  322.22  5742.1  323.23
#Mann= 6 ,-1 , 0
  4600.7     .16       0  5023.2     .12       0  5108.5     .16       0
  5121.1     .12       0  5155.1     .07       0  5161.1     .12       0
Bank Sta=5155.1,5161.1
XS Rating Curve= 0 ,0
Exp/Cntr=0.3,0.1

Type RM Length L Ch R = 1 ,8464    ,809,809,809
BEGIN DESCRIPTION:
UNT 199 IN BOCR 8.0
END DESCRIPTION:
XS GIS Cut Line= 3
      3722046.82     10645898.58      3720905.28     10645902.92
      3720301.97     10646649.47
#Sta/Elev= 30
  4539.5  326.31  4586.7  325.63  4706.7  312.29  4766.7  303.04  4886.7  290.32
  4926.7  287.14  4974.5  287.13  4993.7  278.33  4996.5  277.83  4999.7  278.33
  5006.7  279.77  5016.7  286.43  5066.7   287.1  5076.7  282.16  5086.7  282.63
  5096.7  285.76  5226.7   297.1  5326.7  309.97  5416.7  318.54  5496.7  331.32
  5546.7  335.58  5616.7  334.22  5846.2   336.4  5860.5  334.66  5953.3  334.07
  6037.8  335.84  6060.4  336.89  6116.4   335.8  6218.8  338.77  6640.9  346.82
#Mann= 6 ,-1 , 0
  4539.5     .16       0  4974.5     .12       0  4993.7     .07       0
  4999.7     .12       0  6037.8     .05       0  6218.8     .12       0
Bank Sta=4993.7,4999.7
XS Rating Curve= 0 ,0
Exp/Cntr=0.3,0.1

Type RM Length L Ch R = 1 ,7655    ,605,605,605
BEGIN DESCRIPTION:
UNT 199 IN BOCR 7.0
END DESCRIPTION:
XS GIS Cut Line= 3
      3721949.61     10645210.19      3721599.61     10645210.19
      3721199.61     10645210.19
#Sta/Elev= 30
  4670.5  317.32  4700.5  313.89  4730.5  307.76  4740.5  307.19  4750.5  304.83
  4780.5   301.6  4820.5  294.62  4850.5  291.43  4860.5  289.66  4890.5  287.55
  4930.5  283.02  4940.5  282.66  4966.3  283.83  4970.5  284.21  4980.5  282.22
  4997.5  276.46  5000.2  275.96  5003.5  276.46    5018  281.24  5050.5   284.1
  5080.5  284.44  5160.5  282.92  5210.5  290.09  5290.5  298.57  5320.5  303.12
  5330.5   303.8  5360.5  308.73  5370.5  309.32  5380.5  312.09  5420.5  316.05
#Mann= 4 ,-1 , 0
  4670.5     .16       0  4966.3     .12       0  4997.5     .07       0
  5003.5     .12       0
Bank Sta=4997.5,5003.5
XS Rating Curve= 0 ,0
Exp/Cntr=0.3,0.1

Type RM Length L Ch R = 1 ,7050    ,357,357,357
BEGIN DESCRIPTION:
UNT 199 IN BOCR 6.0
END DESCRIPTION:
XS GIS Cut Line= 3
      3721967.23      10644689.1      3721498.49     10644741.19
      3721177.32     10644858.37
#Sta/Elev= 30
    4472  308.81  4499.8  307.14    4526  307.32  4531.1  308.47    4540  308.48
  4580.3  306.09  4610.5  305.47  4616.6  303.81  4630.6  304.36  4660.8  298.12
  4731.2  290.39  4797.7  281.99  4821.8  279.91  4883.4  280.37  4893.3  281.14
  4956.8  281.21  4974.4  282.53  4982.1  280.17  4992.7  273.67  4995.4  273.17
  4998.7  273.67  5006.3  275.91    5018  281.81  5037.9  281.95  5048.9  280.78
  5059.5  280.97  5112.7  286.69  5134.9  288.48  5190.6  290.85  5285.5   299.2
#Mann= 4 ,-1 , 0
    4472     .16       0  4883.4     .12       0  4992.7     .07       0
  4998.7     .12       0
Bank Sta=4992.7,4998.7
XS Rating Curve= 0 ,0
Exp/Cntr=0.3,0.1