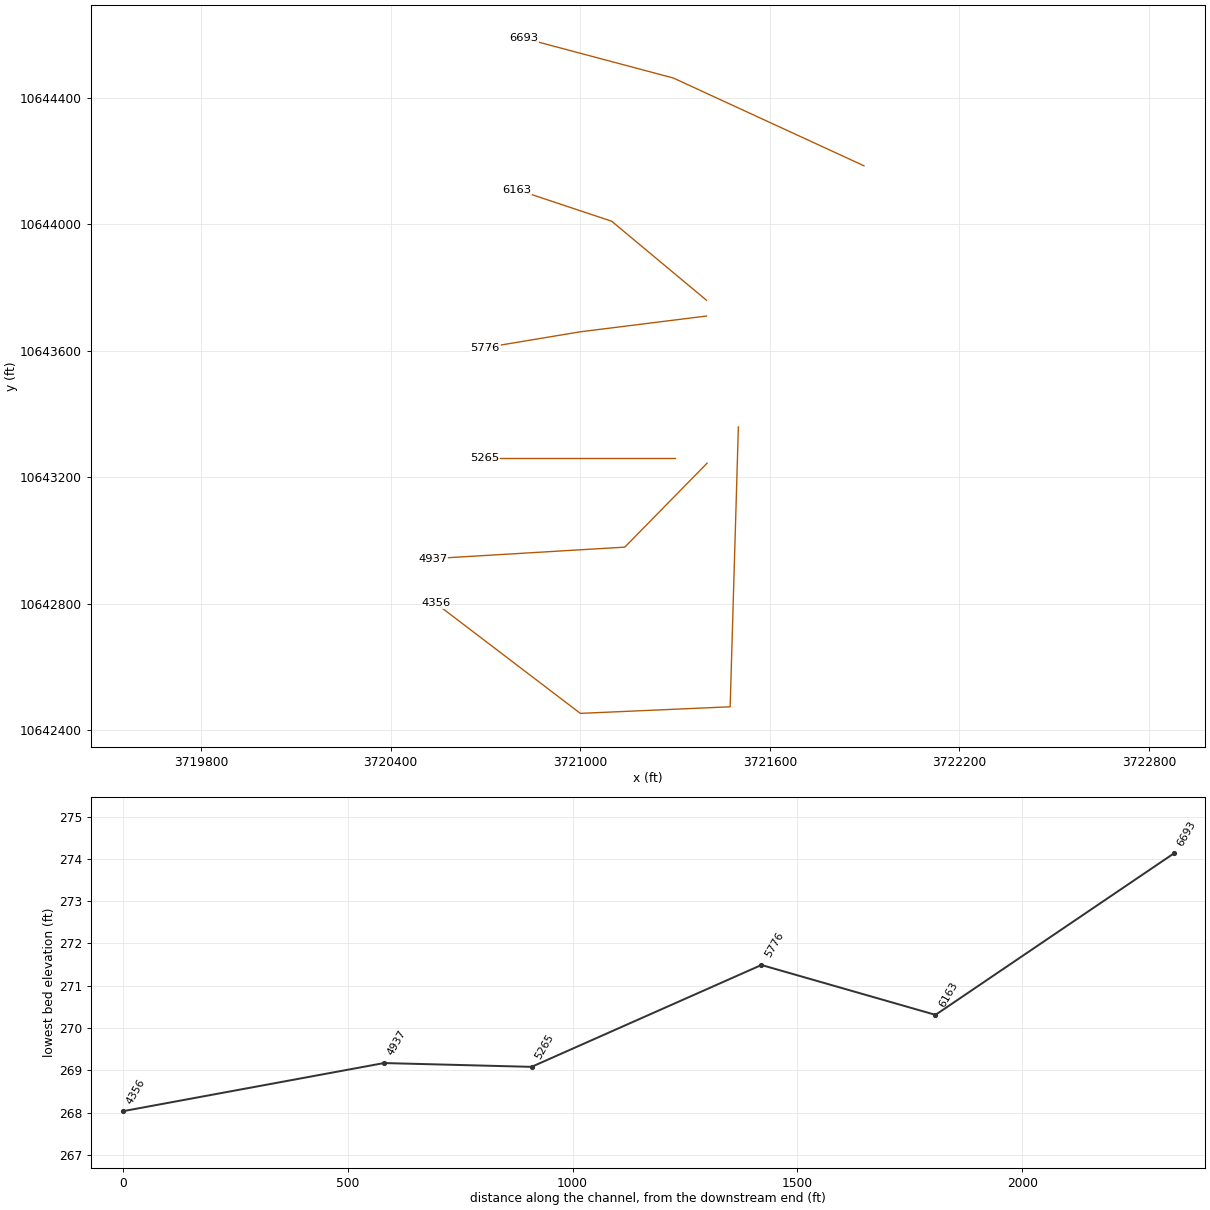
HEC-RAS study UNT 159 IN BOCR.prj: UNT 159 IN BOCR Base Level Engineering

--- UNT 159 IN BOCR.g01 (geometry) --- (continued)

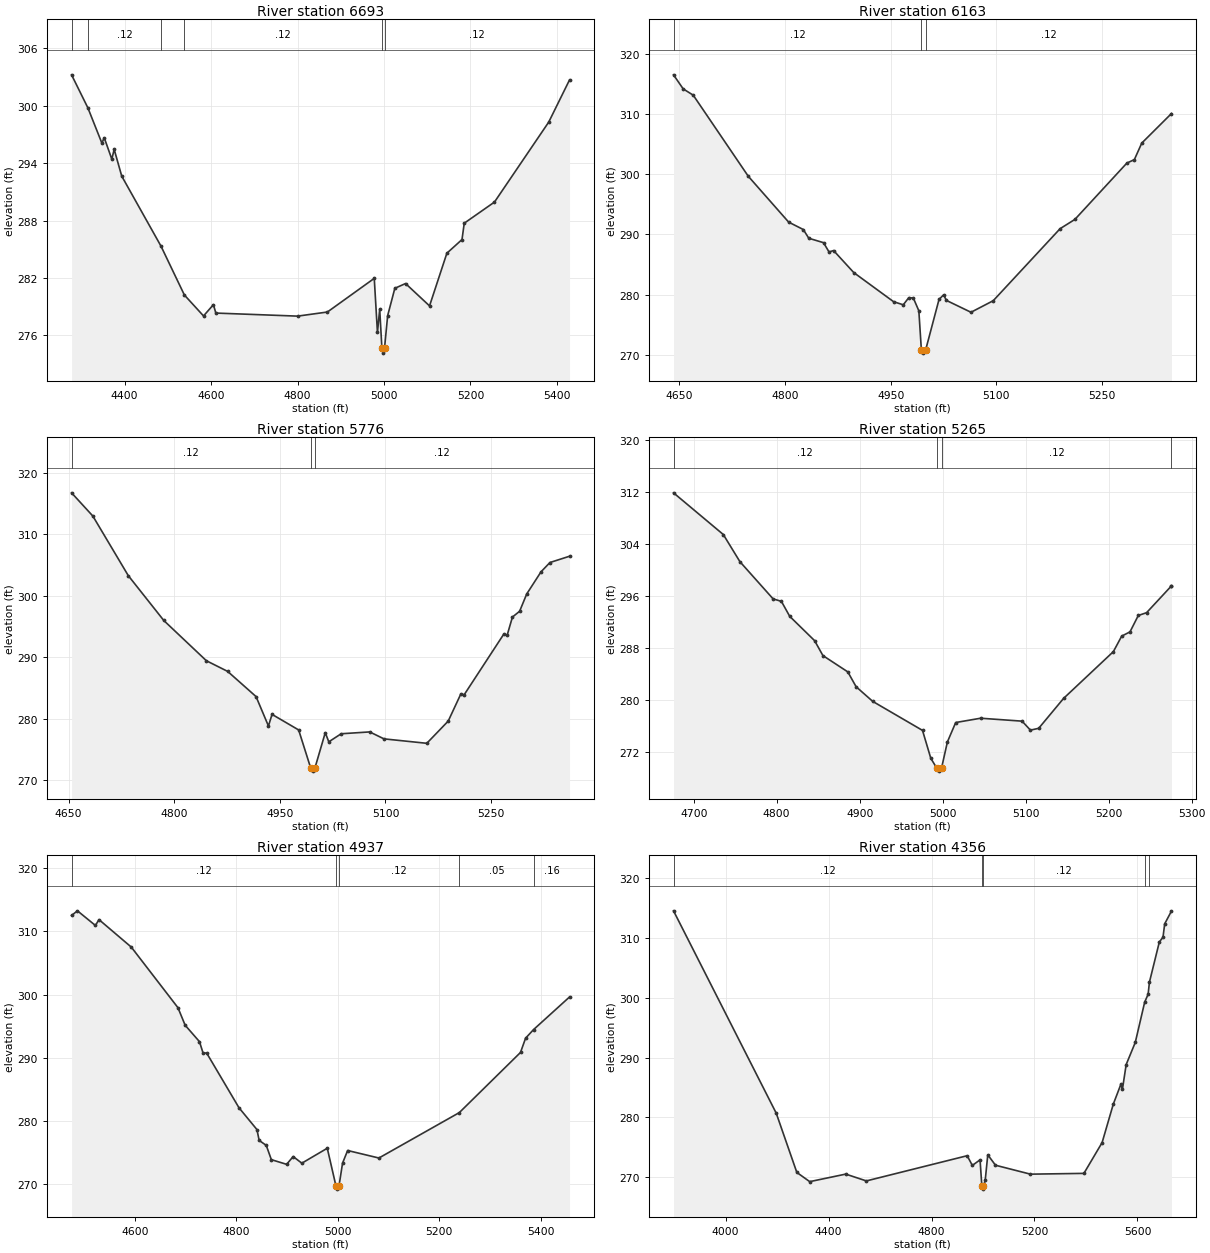
Type RM Length L Ch R = 1 ,6693    ,530,530,530
BEGIN DESCRIPTION:
UNT 199 IN BOCR 5.0
END DESCRIPTION:
XS GIS Cut Line= 3
      3721897.81     10644185.62       3721294.5     10644463.41
      3720822.99     10644588.85
#Sta/Elev= 30
  4277.1  303.24  4314.9  299.78  4347.2   296.1  4352.7  296.66  4370.2  294.42
  4375.7  295.44  4393.2  292.64    4484  285.32  4538.1  280.21  4582.4  278.02
  4605.3   279.2  4610.9  278.32  4800.1     278    4869  278.43  4977.4  281.95
  4984.8  276.29    4990  278.72  4995.1  274.63  4997.8  274.13  5001.1  274.63
  5008.4  278.05    5025  280.91  5049.8  281.41  5105.3  279.07  5145.4  284.58
  5180.4  286.01  5185.6  287.72  5255.5  289.93  5381.1   298.3  5429.2  302.71
#Mann= 6 ,-1 , 0
  4277.1      .1       0  4314.9     .12       0    4484     .16       0
  4538.1     .12       0  4995.1     .07       0  5001.1     .12       0
Bank Sta=4995.1,5001.1
XS Rating Curve= 0 ,0
Exp/Cntr=0.3,0.1

Type RM Length L Ch R = 1 ,6163    ,387,387,387
BEGIN DESCRIPTION:
UNT 199 IN BOCR 4.0
END DESCRIPTION:
XS GIS Cut Line= 3
      3721399.64     10643760.16      3721099.61     10644010.19
      3720799.59     10644110.19
#Sta/Elev= 30
  4641.7  316.49  4655.4  314.16  4669.7  313.11  4747.8  299.66  4805.1  292.05
  4825.9  290.82  4833.7  289.37  4854.6  288.64  4862.4   287.1  4868.9  287.33
  4897.5  283.68  4954.1  278.84  4967.8  278.33  4975.6  279.51  4982.1  279.45
  4989.9  277.33  4993.5  270.81  4996.2  270.31  4999.5  270.81  5018.6  279.24
  5025.1  279.98    5029  279.06  5063.9  277.09  5095.5  279.01  5190.4  290.96
  5211.4   292.5  5285.2  301.85  5295.8  302.42  5306.3  305.16  5348.5  310.07
#Mann= 3 ,-1 , 0
  4641.7     .12       0  4993.5     .07       0  4999.5     .12       0
Bank Sta=4993.5,4999.5
XS Rating Curve= 0 ,0
Exp/Cntr=0.3,0.1

Type RM Length L Ch R = 1 ,5776    ,511,511,511
BEGIN DESCRIPTION:
UNT 199 IN BOCR 3.0
END DESCRIPTION:
XS GIS Cut Line= 3
       3721399.6     10643710.19      3720999.61     10643660.19
      3720699.65     10643610.19
#Sta/Elev= 30
  4654.2   316.7  4684.4  312.93  4734.8  303.24  4785.2  295.96  4845.7  289.42
  4875.9  287.69  4916.2   283.6  4933.8  278.82  4938.9  280.71  4976.7  278.18
  4993.8  271.99  4996.6  271.49  4999.8  271.99  5014.5  277.74  5019.5  276.25
  5037.1  277.56  5077.6  277.86  5097.9  276.73  5158.7  276.01  5189.1  279.62
  5206.8  283.97  5211.9  283.92  5267.7  293.69  5272.7  293.53  5280.3  296.52
  5290.5  297.46  5300.6  300.27  5320.9  303.87  5333.6  305.38  5361.4   306.4
#Mann= 3 ,-1 , 0
  4654.2     .12       0  4993.8     .07       0  4999.8     .12       0
Bank Sta=4993.8,4999.8
XS Rating Curve= 0 ,0
Exp/Cntr=0.3,0.1

Type RM Length L Ch R = 1 ,5265    ,328,328,328
BEGIN DESCRIPTION:
UNT 199 IN BOCR 2.0
END DESCRIPTION:
XS GIS Cut Line= 3
       3721299.6     10643260.19      3720949.61     10643260.19
       3720699.6     10643260.19
#Sta/Elev= 30
  4675.7  311.85  4735.7  305.44  4755.7  301.27  4795.7  295.55  4805.7  295.17
  4815.7  292.87  4845.7  289.13  4855.7  286.84  4885.7  284.33  4895.7  282.05
  4915.7   279.8  4975.7  275.34  4985.7  271.05  4992.7  269.58  4995.4  269.08
  4998.7  269.58  5005.7  273.57  5015.7  276.55  5045.7  277.21  5095.7  276.76
  5105.7  275.38  5115.7  275.66  5145.7  280.26  5205.7  287.45  5215.7  289.83
  5225.7  290.48  5235.7     293  5245.7  293.43  5275.6  297.54  5275.7  297.54
#Mann= 4 ,-1 , 0
  4675.7     .12       0  4992.7     .07       0  4998.7     .12       0
  5275.6     .05       0
Bank Sta=4992.7,4998.7
XS Rating Curve= 0 ,0
Exp/Cntr=0.3,0.1

Type RM Length L Ch R = 1 ,4937    ,581,581,581
BEGIN DESCRIPTION:
Mapping XS 7892a486
END DESCRIPTION:
XS GIS Cut Line= 3
      3721401.63     10643244.58      3721141.18     10642978.92
       3720533.2     10642942.54
#Sta/Elev= 30
  4475.6  312.54  4487.2  313.27  4522.6  310.95  4529.6  311.88  4593.3  307.52
  4685.2  297.92  4699.4  295.14  4727.6  292.54  4734.6  290.76  4741.8  290.73
  4805.4  282.07  4840.8  278.61  4845.2  276.89  4859.2   276.1  4869.2  273.84
  4899.3   273.1  4912.2  274.33  4929.3  273.28  4979.4  275.65  4996.5  269.67
  4999.2  269.17  5002.5  269.67  5009.5  273.29  5019.5  275.29  5081.1   274.1
  5239.6   281.3  5360.1  290.83  5370.1  293.09  5385.8  294.45  5456.7  299.62
#Mann= 5 ,-1 , 0
  4475.6     .12       0  4996.5     .07       0  5002.5     .12       0
  5239.6     .05       0  5385.8     .16       0
Bank Sta=4996.5,5002.5
XS Rating Curve= 0 ,0
Exp/Cntr=0.3,0.1

Type RM Length L Ch R = 1 ,4356    ,0,0,0
BEGIN DESCRIPTION:
UNT 199 IN BOCR 1.0
END DESCRIPTION:
XS GIS Cut Line= 4
      3721500.55     10643359.11      3721474.51     10642473.71
      3721000.55     10642452.88      3720543.38     10642800.95
#Sta/Elev= 30
  3797.5  314.51  4196.6  280.71  4276.6  270.82  4326.7  269.28  4466.7  270.54
  4546.7   269.4  4938.4  273.61  4958.5  271.99  4988.5  272.92  4995.5  268.53
  4998.2  268.03  5001.5  268.53  5008.5  269.48  5018.5  273.76  5048.5  272.02
  5184.2  270.53    5392  270.66  5462.7   275.8  5506.3  282.24  5535.4  285.51
  5541.7  284.71  5556.2  288.83  5591.6  292.53  5628.2  299.27  5641.5  300.57
  5646.6   302.6  5685.1  309.31  5699.3   310.1  5705.9  312.34  5732.3  314.48
#Mann= 5 ,-1 , 0
  3797.5     .12       0  4995.5     .07       0  5001.5     .12       0
  5628.2     .16       0  5646.6     .12       0
Bank Sta=4995.5,5001.5
XS Rating Curve= 0 ,0
Exp/Cntr=0.3,0.1

Chan Stop Cuts=-1
Use User Specified Reach Order=0
Composite Channel Slope=5