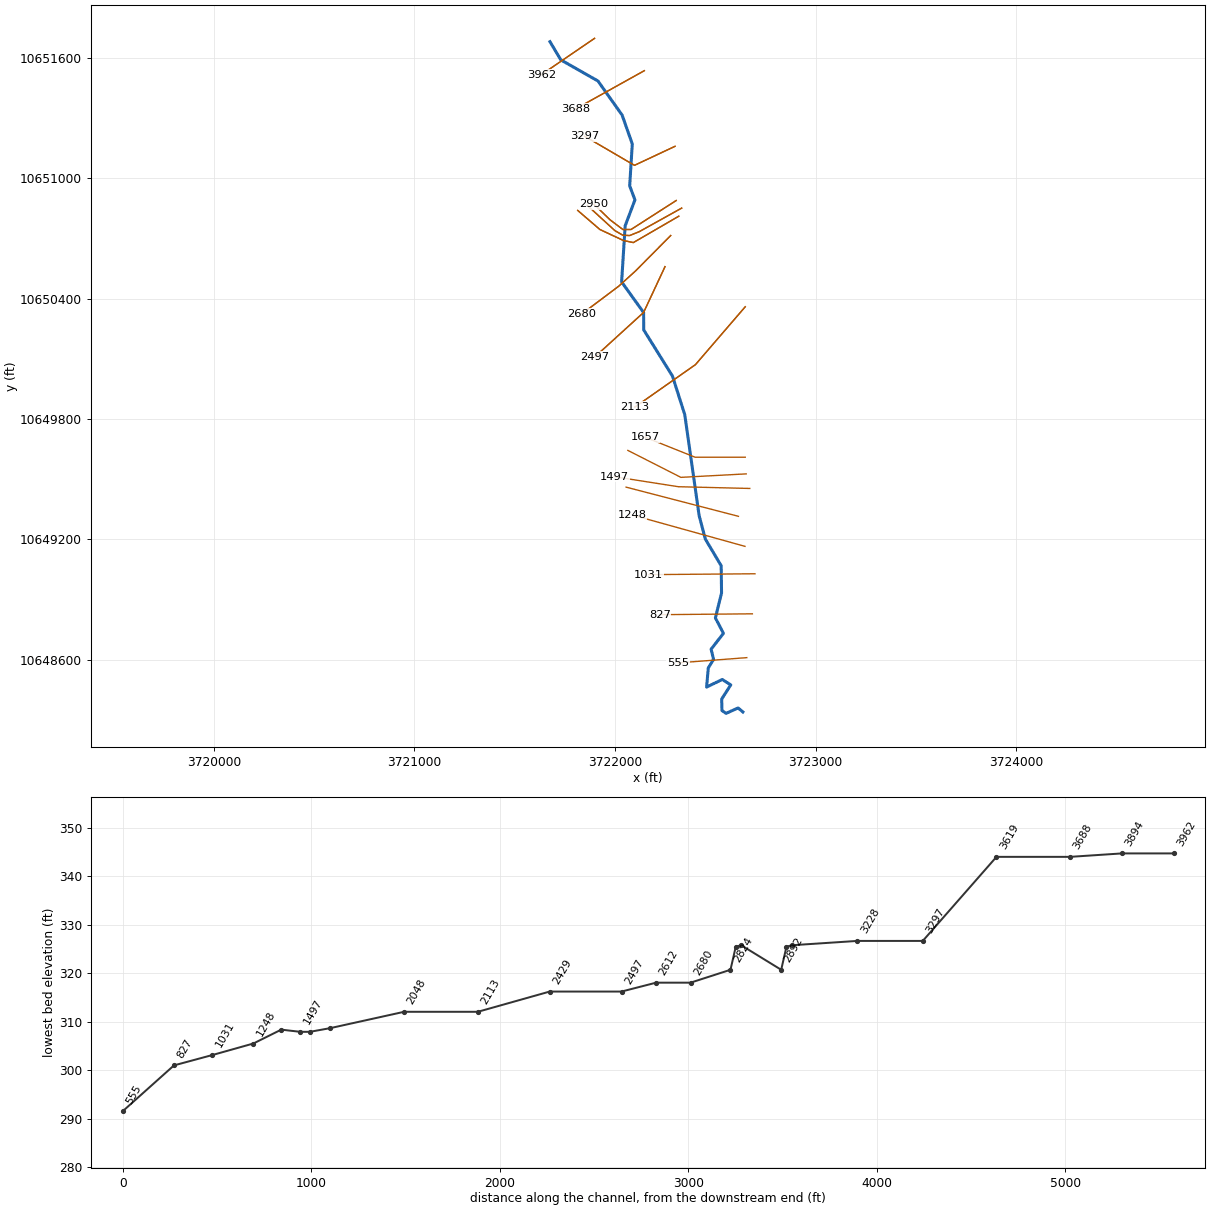
--- UNT 160 IN BOCR.prj (project) ---

Proj Title=UNT 160 IN BOCR Base Level Engineering
Current Plan=p01
Default Exp/Contr=0.3,0.1
English Units
Geom File=g01
Flow File=f01
Plan File=p01
Y Axis Title=Elevation
X Axis Title(PF)=Main Channel Distance
X Axis Title(XS)=Station
BEGIN DESCRIPTION:
UNT 160 IN BOCR
END DESCRIPTION:
DSS Export Rating Curves= 0
DSS Export Rating Curve Sorted= 0
DSS Export Volume Flow Curves= 0
DXF OffsetX= 0
DXF OffsetY= 0
DXF ScaleX= 1
DXF ScaleY= 10

--- UNT 160 IN BOCR.p01 (plan) ---

Plan Title=Multiple Run
Short Identifier=Multiple
Geom File=g01
Flow File=f01
Subcritical Flow
K Sum by GR= 0
Std Step Tol= 0.01
Critical Tol= 0.01
Num of Std Step Trials= 20
Max Error Tol= 0.3
Flow Tol Ratio= 0.001
Split Flow NTrial= 30
Split Flow Tol= 0.02
Split Flow Ratio= 0.02
Log Output Level= 0
Friction Slope Method= 1
Unsteady Friction Slope Method= 2
Unsteady Bridges Friction Slope Method= 1
Parabolic Critical Depth
Global Vel Dist=  1 , 1 , 1
Global Log Level= 0
CheckData=True
Encroach Param= -1, 0, 0, 0
BEGIN DESCRIPTION:
Multiple Run
END DESCRIPTION:

--- UNT 160 IN BOCR.f01 (steady flow) ---

Flow Title=Multiple
Program Version=4.10
Number of Profiles= 7
Profile Names=10-year,25-year,50-year,1pct_min,100-year,1pct_plu,500-year
River Rch & RM=UNT 160 IN BOCR,Reach-1         ,3962
     117     141     159     133     180     243     228
Boundary for River Rch & Prof#=UNT 160 IN BOCR,Reach-1         , 1
Up Type= 0
Dn Type= 3
Dn Slope=0.005
Boundary for River Rch & Prof#=UNT 160 IN BOCR,Reach-1         , 2
Up Type= 0
Dn Type= 3
Dn Slope=0.005
Boundary for River Rch & Prof#=UNT 160 IN BOCR,Reach-1         , 3
Up Type= 0
Dn Type= 3
Dn Slope=0.005
Boundary for River Rch & Prof#=UNT 160 IN BOCR,Reach-1         , 4
Up Type= 0
Dn Type= 3
Dn Slope=0.005
Boundary for River Rch & Prof#=UNT 160 IN BOCR,Reach-1         , 5
Up Type= 0
Dn Type= 3
Dn Slope=0.005
Boundary for River Rch & Prof#=UNT 160 IN BOCR,Reach-1         , 6
Up Type= 0
Dn Type= 3
Dn Slope=0.005
Boundary for River Rch & Prof#=UNT 160 IN BOCR,Reach-1         , 7
Up Type= 0
Dn Type= 3
Dn Slope=0.005
DSS Import GetInterval= 0
DSS Import GetPeak= 0
DSS Import FillOption= 0

--- UNT 160 IN BOCR.g01 (geometry) ---

Geom Title=Existing Conditions
Program Version=4.10

River Reach=UNT 160 IN BOCR ,Reach-1
Reach XY= 30
        3721676.       10651682.      3721730.25       10651591.
      3721915.25       10651486.      3722035.75       10651316.
       3722086.5       10651172.       3722073.5       10650963.
      3722099.75       10650893.        3722051.       10650764.
      3722033.25       10650484.      3722142.99     10650331.55
      3722143.58     10650244.78      3722286.81     10650014.74
      3722348.25       10649822.       3722419.5       10649320.
      3722450.75       10649202.      3722529.75       10649069.
       3722531.5       10648933.      3722500.75       10648809.
        3722541.       10648732.       3722479.5       10648653.
      3722491.75       10648602.       3722465.5       10648560.
        3722457.       10648464.        3722535.       10648502.
       3722577.5       10648475.        3722532.       10648404.
      3722533.75       10648347.        3722554.       10648333.
        3722614.       10648360.        3722638.       10648340.

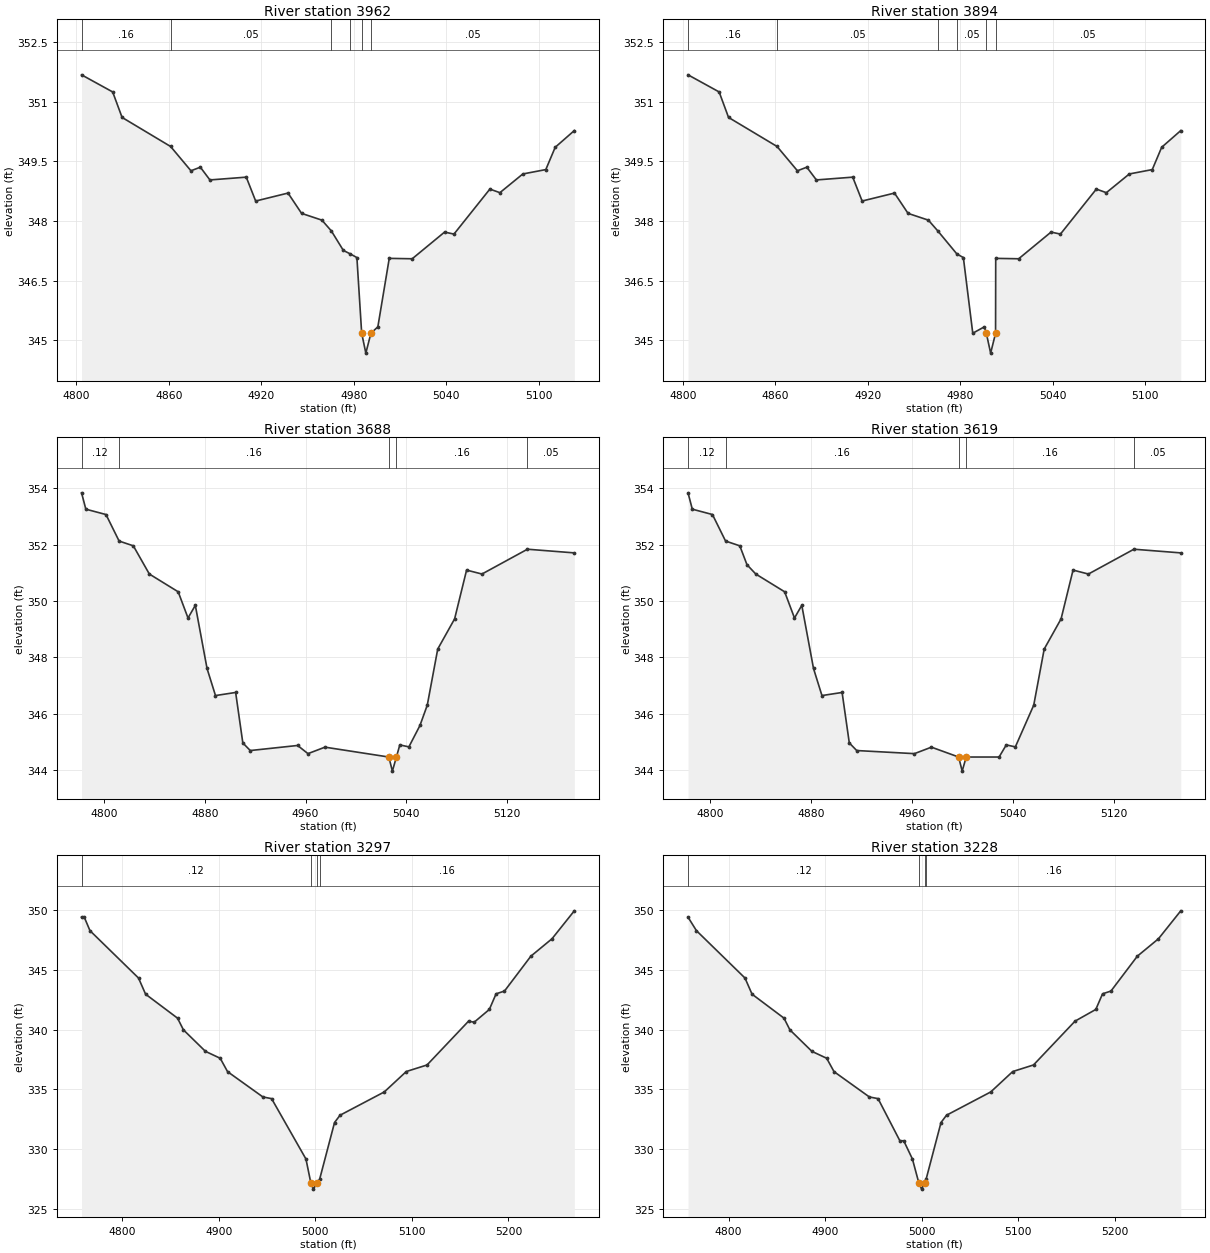
Type RM Length L Ch R = 1 ,3962    ,275,275,275
BEGIN DESCRIPTION:
UNT 160 IN BOCR 8.0
END DESCRIPTION:
XS GIS Cut Line= 2
      3721898.44     10651698.56      3721634.34     10651518.21
#Sta/Elev= 30
  4803.4  351.67  4823.6  351.24  4829.7   350.6  4861.2  349.87  4874.4  349.26
  4880.5  349.35  4886.7  349.03  4910.3   349.1  4916.4   348.5  4937.4   348.7
  4946.2  348.19  4959.4  348.02  4965.5  347.75  4973.3  347.26  4977.9  347.17
  4982.1  347.08  4985.2  345.18  4987.9  344.68  4991.2  345.18  4995.7  345.34
  5003.1  347.06    5018  347.05    5039  347.72  5045.1  347.67  5068.4   348.8
  5074.9  348.71  5089.8  349.18  5104.7  349.29  5110.8  349.85  5123.2  350.27
#Mann= 6 ,-1 , 0
  4803.4     .16       0  4861.2     .05       0  4965.5     .16       0
  4977.9     .05       0  4985.2     .03       0  4991.2     .05       0
Bank Sta=4985.2,4991.2
XS Rating Curve= 0 ,0
Exp/Cntr=0.3,0.1

Type RM Length L Ch R = 1 ,3894    ,275,275,275
BEGIN DESCRIPTION:
UNT 160 IN BOCR 8.0
END DESCRIPTION:
XS GIS Cut Line= 2
      3721898.44     10651698.56      3721634.34     10651518.21
#Sta/Elev= 30
  4803.4  351.67  4823.6  351.24  4829.7   350.6  4861.2  349.87  4874.4  349.26
  4880.5  349.35  4886.7  349.03  4910.3   349.1  4916.4   348.5  4937.4   348.7
  4946.2  348.19  4959.4  348.02  4965.5  347.75  4977.9  347.17  4982.1  347.08
  4988.2  345.18  4995.7  345.34    4997  345.18  4999.8  344.68    5003  345.18
  5003.1  347.06    5018  347.05    5039  347.72  5045.1  347.67  5068.4   348.8
  5074.9  348.71  5089.8  349.18  5104.7  349.29  5110.8  349.85  5123.2  350.27
#Mann= 6 ,-1 , 0
  4803.4     .16       0  4861.2     .05       0  4965.5     .16       0
  4977.9     .05       0    4997     .03       0    5003     .05       0
Bank Sta=4997,5003
XS Rating Curve= 0 ,0
Exp/Cntr=0.3,0.1

Type RM Length L Ch R = 1 ,3688    ,391,391,391
BEGIN DESCRIPTION:
UNT 160 IN BOCR 7.0
END DESCRIPTION:
XS GIS Cut Line= 2
      3722146.62     10651537.35      3721804.89     10651347.14
#Sta/Elev= 30
  4782.2  353.84  4785.6  353.26  4801.6  353.07    4812  352.13  4823.3  351.96
    4836  350.96  4858.9  350.33  4866.7   349.4  4872.5  349.85  4881.8  347.61
  4888.5  346.65  4904.5  346.76  4910.2  344.97  4916.1   344.7  4953.7  344.88
  4961.9  344.59  4975.4  344.82  5026.1  344.47  5028.9  343.97  5032.1  344.47
  5034.8   344.9    5042  344.83  5050.8  345.59  5056.6  346.31  5064.9   348.3
  5078.3  349.37  5087.8   351.1    5100  350.96  5136.1  351.84  5173.3  351.71
#Mann= 5 ,-1 , 0
  4782.2     .12       0    4812     .16       0  5026.1     .07       0
  5032.1     .16       0  5136.1     .05       0
Bank Sta=5026.1,5032.1
XS Rating Curve= 0 ,0
Exp/Cntr=0.3,0.1

Type RM Length L Ch R = 1 ,3619    ,391,391,391
BEGIN DESCRIPTION:
UNT 160 IN BOCR 7.0
END DESCRIPTION:
XS GIS Cut Line= 2
      3722146.62     10651537.35      3721804.89     10651347.14
#Sta/Elev= 30
  4782.2  353.84  4785.6  353.26  4801.6  353.07    4812  352.13  4823.3  351.96
    4829  351.29    4836  350.96  4858.9  350.33  4866.7   349.4  4872.5  349.85
  4881.8  347.61  4888.5  346.65  4904.5  346.76  4910.2  344.97  4916.1   344.7
  4961.9  344.59  4975.4  344.82    4997  344.47  4999.8  343.97    5003  344.47
  5029.1  344.47  5034.8   344.9    5042  344.83  5056.6  346.31  5064.9   348.3
  5078.3  349.37  5087.8   351.1    5100  350.96  5136.1  351.84  5173.3  351.71
#Mann= 5 ,-1 , 0
  4782.2     .12       0    4812     .16       0    4997     .07       0
    5003     .16       0  5136.1     .05       0
Bank Sta=4997,5003
XS Rating Curve= 0 ,0
Exp/Cntr=0.3,0.1

Type RM Length L Ch R = 1 ,3297    ,347,347,347
BEGIN DESCRIPTION:
UNT 160 IN BOCR 6.0
END DESCRIPTION:
XS GIS Cut Line= 3
      3722299.65     10651160.21      3722097.39     10651065.41
      3721849.65     10651210.16
#Sta/Elev= 30
  4757.9  349.42  4760.7  349.42  4766.6  348.29  4816.9  344.32  4824.2  342.97
  4857.3  340.96  4863.4  339.98  4886.2  338.18  4901.5   337.6  4909.1  336.48
  4945.7  334.36  4954.7  334.22  4990.3  329.16  4995.4  327.14  4998.1  326.64
  5001.4  327.14  5004.4  327.45  5019.9  332.22  5025.6  332.83  5071.4  334.78
  5094.2  336.49  5115.7  337.04  5158.7  340.71  5164.5  340.62  5180.2  341.69
  5187.2     343  5195.9  343.23  5223.2  346.15  5245.1  347.61  5268.2  349.95
#Mann= 4 ,-1 , 0
  4757.9     .12       0  4995.4     .07       0  5001.4     .12       0
  5004.4     .16       0
Bank Sta=4995.4,5001.4
XS Rating Curve= 0 ,0
Exp/Cntr=0.3,0.1

Type RM Length L Ch R = 1 ,3228    ,347,347,347
BEGIN DESCRIPTION:
UNT 160 IN BOCR 6.0
END DESCRIPTION:
XS GIS Cut Line= 3
      3722299.65     10651160.21      3722097.39     10651065.41
      3721849.65     10651210.16
#Sta/Elev= 30
  4757.9  349.42  4766.6  348.29  4816.9  344.32  4824.2  342.97  4857.3  340.96
  4863.4  339.98  4886.2  338.18  4901.5   337.6  4909.1  336.48  4945.7  334.36
  4954.7  334.22  4977.3  330.69  4981.3  330.69  4990.3  329.16    4997  327.14
  4999.8  326.64    5003  327.14  5004.4  327.45  5019.9  332.22  5025.6  332.83
  5071.4  334.78  5094.2  336.49  5115.7  337.04  5158.7  340.71  5180.2  341.69
  5187.2     343  5195.9  343.23  5223.2  346.15  5245.1  347.61  5268.2  349.95
#Mann= 4 ,-1 , 0
  4757.9     .12       0    4997     .07       0    5003     .12       0
  5004.4     .16       0
Bank Sta=4997,5003
XS Rating Curve= 0 ,0
Exp/Cntr=0.3,0.1

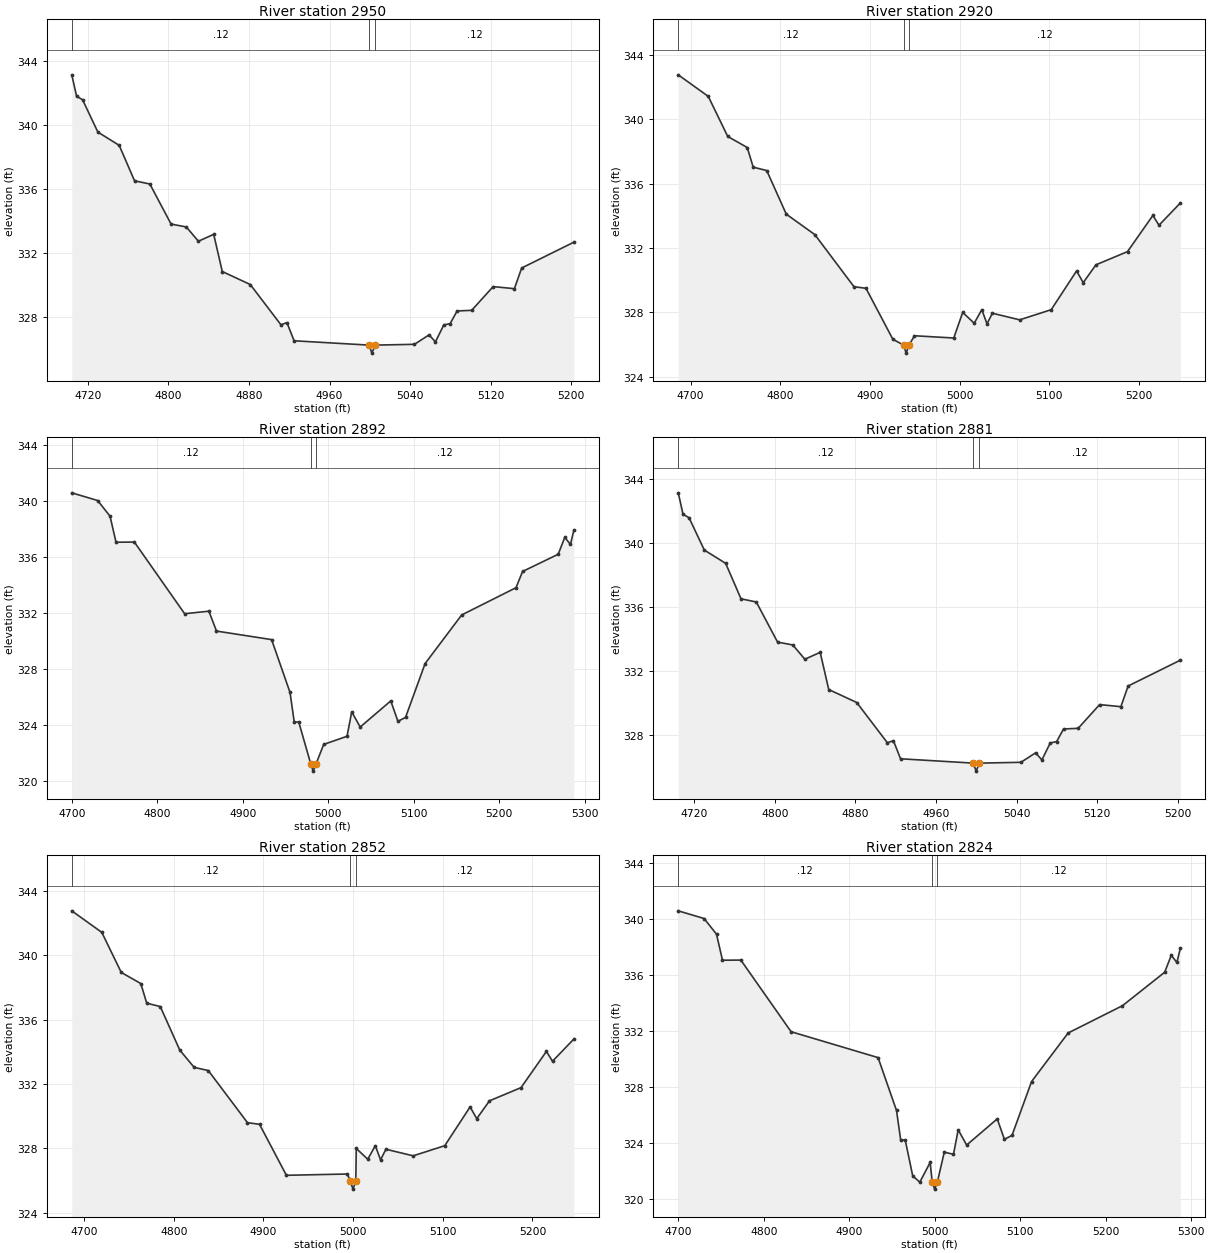
Type RM Length L Ch R = 1 ,2950    ,29,29,29
BEGIN DESCRIPTION:
Mapping XS 85c91712
END DESCRIPTION:
XS GIS Cut Line= 5
      3722305.34     10650889.88      3722080.09     10650745.35
      3722039.72     10650745.35      3721975.92     10650793.53
      3721896.52     10650870.33
#Sta/Elev= 30
  4704.1  343.11  4708.9  341.77  4714.8  341.56    4730  339.54  4751.2  338.71
  4766.4   336.5  4781.6   336.3  4802.7   333.8  4817.8  333.62  4829.8  332.73
    4845  333.16  4853.5  330.84  4881.3  330.03  4911.7  327.52  4917.7  327.65
  4924.8  326.52  4999.2  326.25    5002  325.75  5005.2  326.25  5044.3   326.3
  5058.8  326.89  5065.1  326.45  5073.4  327.51  5079.7  327.59  5086.6  328.38
  5101.1  328.42  5122.4   329.9  5143.5  329.77  5150.7  331.06  5202.5  332.67
#Mann= 3 ,-1 , 0
  4704.1     .12       0  4999.2     .07       0  5005.2     .12       0
Bank Sta=4999.2,5005.2
XS Rating Curve= 0 ,0
Exp/Cntr=0.3,0.1

Type RM Length L Ch R = 1 ,2920    ,28,28,28
BEGIN DESCRIPTION:
Mapping XS 6488d4a6
END DESCRIPTION:
XS GIS Cut Line= 6
       3722332.7     10650852.13      3722121.76     10650734.94
      3722073.58     10650715.41      3722039.72     10650716.71
      3721999.36     10650740.15      3721862.03     10650865.81
#Sta/Elev= 30
  4686.2  342.76  4719.7  341.42  4741.4  338.93  4763.2  338.24  4769.8  337.02
  4784.9  336.81  4806.7   334.1  4838.5  332.83  4882.2  329.59  4895.6  329.49
  4925.6  326.32  4937.6  325.96  4940.4  325.46  4943.6  325.96  4949.7  326.54
  4993.5   326.4  5003.5  327.99  5016.3  327.32  5024.8  328.16  5030.6  327.28
  5036.6  327.94    5067  327.53  5102.2  328.16  5130.5  330.57  5137.9  329.84
  5152.1  330.95  5187.3  331.77  5215.6  334.02  5222.4  333.41  5246.2  334.79
#Mann= 3 ,-1 , 0
  4686.2     .12       0  4937.6     .07       0  4943.6     .12       0
Bank Sta=4937.6,4943.6
XS Rating Curve= 0 ,0
Exp/Cntr=0.3,0.1

Type RM Length L Ch R = 1 ,2892    ,212,212,212
BEGIN DESCRIPTION:
Mapping XS 52f120c9
END DESCRIPTION:
XS GIS Cut Line= 5
      3722318.39     10650811.77      3722091.81     10650680.25
      3722042.33     10650690.67      3721925.14     10650745.35
      3721814.51     10650840.37
#Sta/Elev= 30
  4699.7  340.58    4730  340.03  4744.5  338.91  4751.5  337.05    4773  337.06
  4831.8  331.94  4860.2  332.12  4869.1   330.7  4933.6  330.09  4955.2  326.31
  4960.1   324.2  4965.4   324.2  4979.5  321.19  4982.2  320.69  4985.5  321.19
  4994.6   322.6  5021.9  323.18  5027.4  324.93  5037.3  323.84  5073.1  325.71
  5081.5  324.25  5090.4  324.53  5113.3  328.38  5156.1  331.85  5219.7   333.8
  5227.4  334.96  5269.1  336.19  5276.8   337.4  5283.4  336.89  5287.4   337.9
#Mann= 3 ,-1 , 0
  4699.7     .12       0  4979.5     .07       0  4985.5     .12       0
Bank Sta=4979.5,4985.5
XS Rating Curve= 0 ,0
Exp/Cntr=0.3,0.1

Type RM Length L Ch R = 1 ,2881    ,29,29,29
BEGIN DESCRIPTION:
Mapping XS 85c91712
END DESCRIPTION:
XS GIS Cut Line= 5
      3722305.34     10650889.88      3722080.09     10650745.35
      3722039.72     10650745.35      3721975.92     10650793.53
      3721896.52     10650870.33
#Sta/Elev= 30
  4704.1  343.11  4708.9  341.77  4714.8  341.56    4730  339.54  4751.2  338.71
  4766.4   336.5  4781.6   336.3  4802.7   333.8  4817.8  333.62  4829.8  332.73
    4845  333.16  4853.5  330.84  4881.3  330.03  4911.7  327.52  4917.7  327.65
  4924.8  326.52    4997  326.25  4999.8  325.75    5003  326.25  5044.3   326.3
  5058.8  326.89  5065.1  326.45  5073.4  327.51  5079.7  327.59  5086.6  328.38
  5101.1  328.42  5122.4   329.9  5143.5  329.77  5150.7  331.06  5202.5  332.67
#Mann= 3 ,-1 , 0
  4704.1     .12       0    4997     .07       0    5003     .12       0
Bank Sta=4997,5003
XS Rating Curve= 0 ,0
Exp/Cntr=0.3,0.1

Type RM Length L Ch R = 1 ,2852    ,28,28,28
BEGIN DESCRIPTION:
Mapping XS 6488d4a6
END DESCRIPTION:
XS GIS Cut Line= 6
       3722332.7     10650852.13      3722121.76     10650734.94
      3722073.58     10650715.41      3722039.72     10650716.71
      3721999.36     10650740.15      3721862.03     10650865.81
#Sta/Elev= 30
  4686.2  342.76  4719.7  341.42  4741.4  338.93  4763.2  338.24  4769.8  337.02
  4784.9  336.81  4806.7   334.1  4822.7  333.03  4838.5  332.83  4882.2  329.59
  4895.6  329.49  4925.6  326.32  4993.5   326.4    4997  325.96  4999.8  325.46
    5003  325.96  5003.5  327.99  5016.3  327.32  5024.8  328.16  5030.6  327.28
  5036.6  327.94    5067  327.53  5102.2  328.16  5130.5  330.57  5137.9  329.84
  5152.1  330.95  5187.3  331.77  5215.6  334.02  5222.4  333.41  5246.2  334.79
#Mann= 3 ,-1 , 0
  4686.2     .12       0    4997     .07       0    5003     .12       0
Bank Sta=4997,5003
XS Rating Curve= 0 ,0
Exp/Cntr=0.3,0.1

Type RM Length L Ch R = 1 ,2824    ,212,212,212
BEGIN DESCRIPTION:
Mapping XS 52f120c9
END DESCRIPTION:
XS GIS Cut Line= 5
      3722318.39     10650811.77      3722091.81     10650680.25
      3722042.33     10650690.67      3721925.14     10650745.35
      3721814.51     10650840.37
#Sta/Elev= 30
  4699.7  340.58    4730  340.03  4744.5  338.91  4751.5  337.05    4773  337.06
  4831.8  331.94  4933.6  330.09  4955.2  326.31  4960.1   324.2  4965.4   324.2
  4974.2  321.63  4982.5  321.19  4994.6   322.6    4997  321.19  4999.8  320.69
    5003  321.19  5011.1  323.33  5021.9  323.18  5027.4  324.93  5037.3  323.84
  5073.1  325.71  5081.5  324.25  5090.4  324.53  5113.3  328.38  5156.1  331.85
  5219.7   333.8  5269.1  336.19  5276.8   337.4  5283.4  336.89  5287.4   337.9
#Mann= 3 ,-1 , 0
  4699.7     .12       0    4997     .07       0    5003     .12       0
Bank Sta=4997,5003
XS Rating Curve= 0 ,0
Exp/Cntr=0.3,0.1

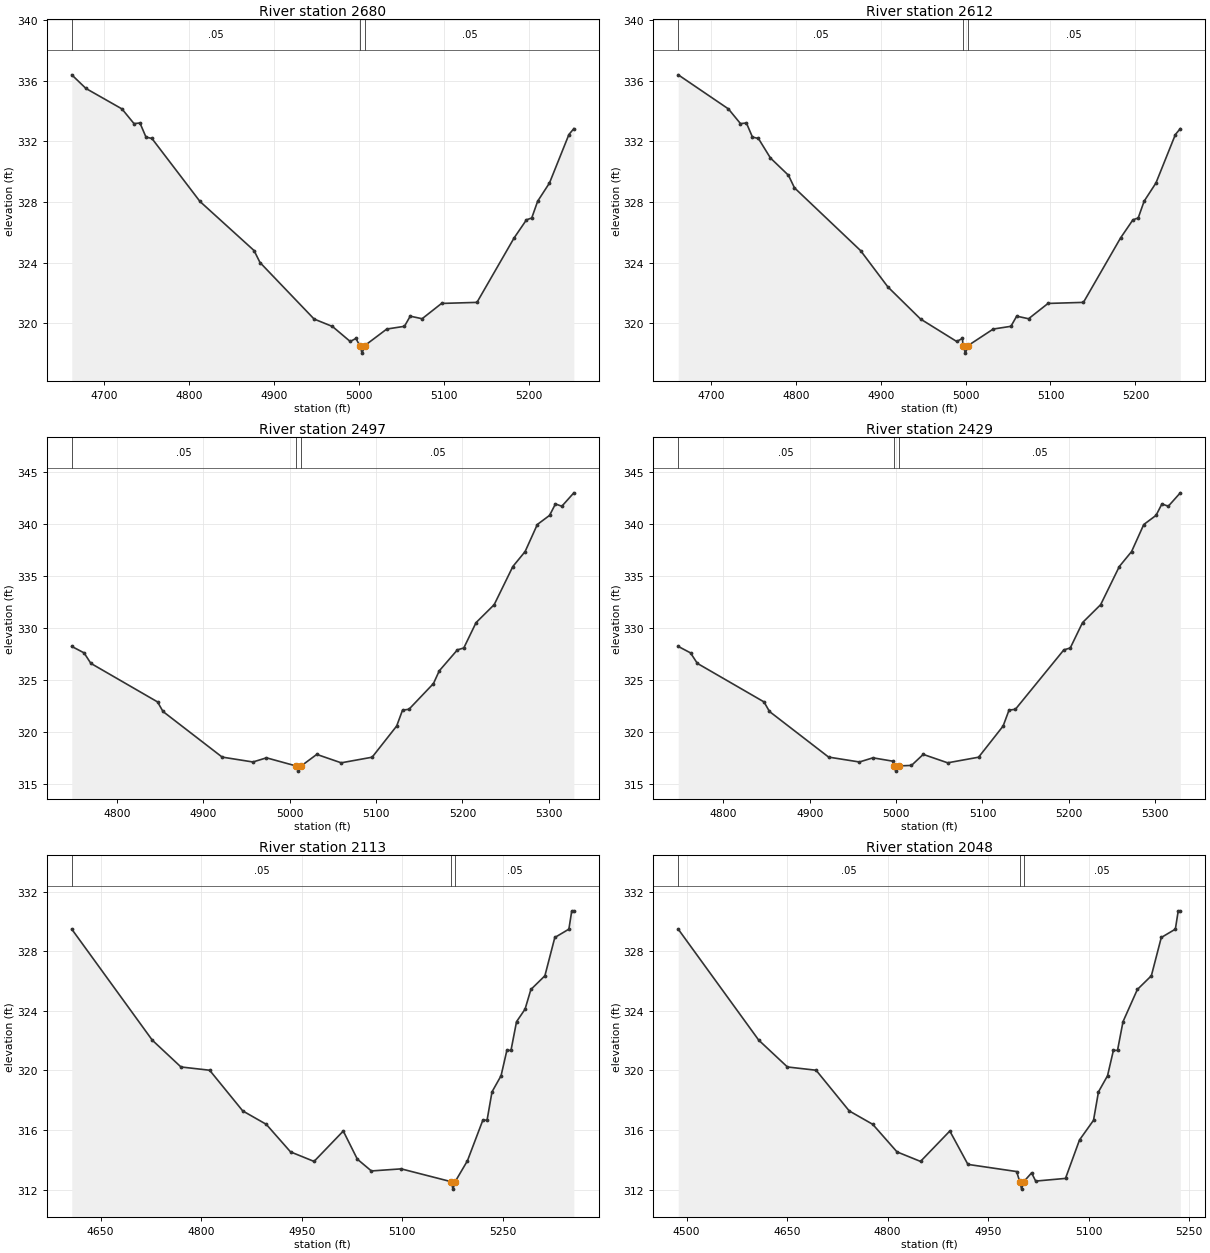
Type RM Length L Ch R = 1 ,2680    ,183,183,183
BEGIN DESCRIPTION:
Mapping XS ed4e1784
END DESCRIPTION:
XS GIS Cut Line= 4
      3722277.99     10650715.39      3722103.53     10650539.63
      3722018.89      10650462.8      3721835.57     10650324.99
#Sta/Elev= 30
  4661.6   336.4  4678.3   335.5  4720.7  334.15  4734.9  333.18  4741.9  333.22
    4749  332.29    4756   332.2  4812.6  328.04  4876.3   324.8  4883.3  324.01
    4947  320.28  4968.6  319.79  4989.5   318.8  4996.3     319  5000.7  318.53
  5003.5  318.03  5006.7  318.53  5032.6  319.62  5053.4   319.8  5060.2  320.47
  5074.2   320.3  5097.1  321.31  5138.8  321.38  5182.5  325.63  5197.1  326.83
  5203.3  326.95  5210.3  328.06  5224.2  329.26  5247.1  332.46  5252.9  332.85
#Mann= 3 ,-1 , 0
  4661.6     .05       0  5000.7    .035       0  5006.7     .05       0
Bank Sta=5000.7,5006.7
XS Rating Curve= 0 ,0
Exp/Cntr=0.3,0.1

Type RM Length L Ch R = 1 ,2612    ,183,183,183
BEGIN DESCRIPTION:
Mapping XS ed4e1784
END DESCRIPTION:
XS GIS Cut Line= 4
      3722277.99     10650715.39      3722103.53     10650539.63
      3722018.89      10650462.8      3721835.57     10650324.99
#Sta/Elev= 30
  4661.6   336.4  4720.7  334.15  4734.9  333.18  4741.9  333.22    4749  332.29
    4756   332.2  4770.2  330.91  4791.4  329.77  4798.5  328.94  4876.3   324.8
  4908.5   322.4    4947  320.28  4989.5   318.8  4996.3     319    4997  318.53
  4999.8  318.03    5003  318.53  5032.6  319.62  5053.4   319.8  5060.2  320.47
  5074.2   320.3  5097.1  321.31  5138.8  321.38  5182.5  325.63  5197.1  326.83
  5203.3  326.95  5210.3  328.06  5224.2  329.26  5247.1  332.46  5252.9  332.85
#Mann= 3 ,-1 , 0
  4661.6     .05       0    4997    .035       0    5003     .05       0
Bank Sta=4997,5003
XS Rating Curve= 0 ,0
Exp/Cntr=0.3,0.1

Type RM Length L Ch R = 1 ,2497    ,381,381,381
BEGIN DESCRIPTION:
UNT 160 IN BOCR 4.0
END DESCRIPTION:
XS GIS Cut Line= 3
      3722249.61      10650560.2      3722142.96     10650331.91
       3721899.6     10650110.18
#Sta/Elev= 30
  4747.8   328.2    4762  327.58  4769.9  326.57  4847.1  322.86  4853.4  321.94
  4921.9  317.55  4957.5  317.08  4973.2  317.48  5007.4   316.7  5010.2   316.2
  5013.4   316.7  5031.4  317.81  5059.7     317  5095.5  317.54  5123.9  320.54
  5130.7  322.07  5138.1  322.15  5166.5  324.63  5173.2  325.85  5194.2  327.87
  5201.6  328.05  5215.8  330.49  5236.8  332.22  5258.4  335.89  5272.6  337.33
  5286.7  339.93  5300.9  340.81  5307.7  341.91  5315.1  341.69    5329  342.98
#Mann= 3 ,-1 , 0
  4747.8     .05       0  5007.4     .03       0  5013.4     .05       0
Bank Sta=5007.4,5013.4
XS Rating Curve= 0 ,0
Exp/Cntr=0.3,0.1

Type RM Length L Ch R = 1 ,2429    ,381,381,381
BEGIN DESCRIPTION:
UNT 160 IN BOCR 4.0
END DESCRIPTION:
XS GIS Cut Line= 3
      3722249.61      10650560.2      3722142.96     10650331.91
       3721899.6     10650110.18
#Sta/Elev= 30
  4747.8   328.2    4762  327.58  4769.9  326.57  4847.1  322.86  4853.4  321.94
  4921.9  317.55  4957.5  317.08  4973.2  317.48    4996  317.16    4997   316.7
  4999.8   316.2    5003   316.7  5017.8  316.75  5031.4  317.81  5059.7     317
  5095.5  317.54  5123.9  320.54  5130.7  322.07  5138.1  322.15  5194.2  327.87
  5201.6  328.05  5215.8  330.49  5236.8  332.22  5258.4  335.89  5272.6  337.33
  5286.7  339.93  5300.9  340.81  5307.7  341.91  5315.1  341.69    5329  342.98
#Mann= 3 ,-1 , 0
  4747.8     .05       0    4997     .03       0    5003     .05       0
Bank Sta=4997,5003
XS Rating Curve= 0 ,0
Exp/Cntr=0.3,0.1

Type RM Length L Ch R = 1 ,2113    ,391,391,391
BEGIN DESCRIPTION:
UNT 160 IN BOCR 3.0
END DESCRIPTION:
XS GIS Cut Line= 3
      3722649.58     10650360.15      3722401.21     10650071.49
      3722099.58     10649860.17
#Sta/Elev= 30
    4607  329.48  4727.1  322.03  4769.9  320.23  4812.7  320.01  4862.1  317.28
  4897.2  316.38  4933.4  314.53  4968.5  313.89  5012.1  315.93  5033.1  314.04
    5054  313.25  5098.5  313.39    5173  312.53  5175.8  312.03    5179  312.53
  5197.3  313.93  5220.5  316.68  5226.6  316.65    5234  318.56  5247.5  319.64
  5256.2  321.35  5262.3  321.34  5270.6  323.27  5283.3  324.11    5292  325.43
  5312.9  326.35  5327.7  328.92  5348.7  329.48    5353  330.71  5356.1  330.71
#Mann= 3 ,-1 , 0
    4607     .05       0    5173     .03       0    5179     .05       0
Bank Sta=5173,5179
XS Rating Curve= 0 ,0
Exp/Cntr=0.3,0.1

Type RM Length L Ch R = 1 ,2048    ,391,391,391
BEGIN DESCRIPTION:
UNT 160 IN BOCR 3.0
END DESCRIPTION:
XS GIS Cut Line= 3
      3722649.59     10650360.16      3722401.21     10650071.49
      3722099.59     10649860.17
#Sta/Elev= 30
  4487.5  329.48  4607.6  322.03  4650.4  320.23  4693.2  320.01  4742.6  317.28
  4777.7  316.38  4813.9  314.53    4849  313.89  4892.7  315.93  4919.7  313.69
  4992.4  313.21    4997  312.53  4999.8  312.03    5003  312.53  5014.7  313.12
  5020.8  312.57  5065.3  312.75  5086.2  315.33  5107.1  316.65  5114.5  318.56
    5128  319.64  5136.8  321.35  5142.9  321.34  5151.1  323.27  5172.5  325.43
  5193.4  326.35  5208.2  328.92  5229.2  329.48  5233.5  330.71  5236.6  330.71
#Mann= 3 ,-1 , 0
  4487.5     .05       0    4997     .03       0    5003     .05       0
Bank Sta=4997,5003
XS Rating Curve= 0 ,0
Exp/Cntr=0.3,0.1

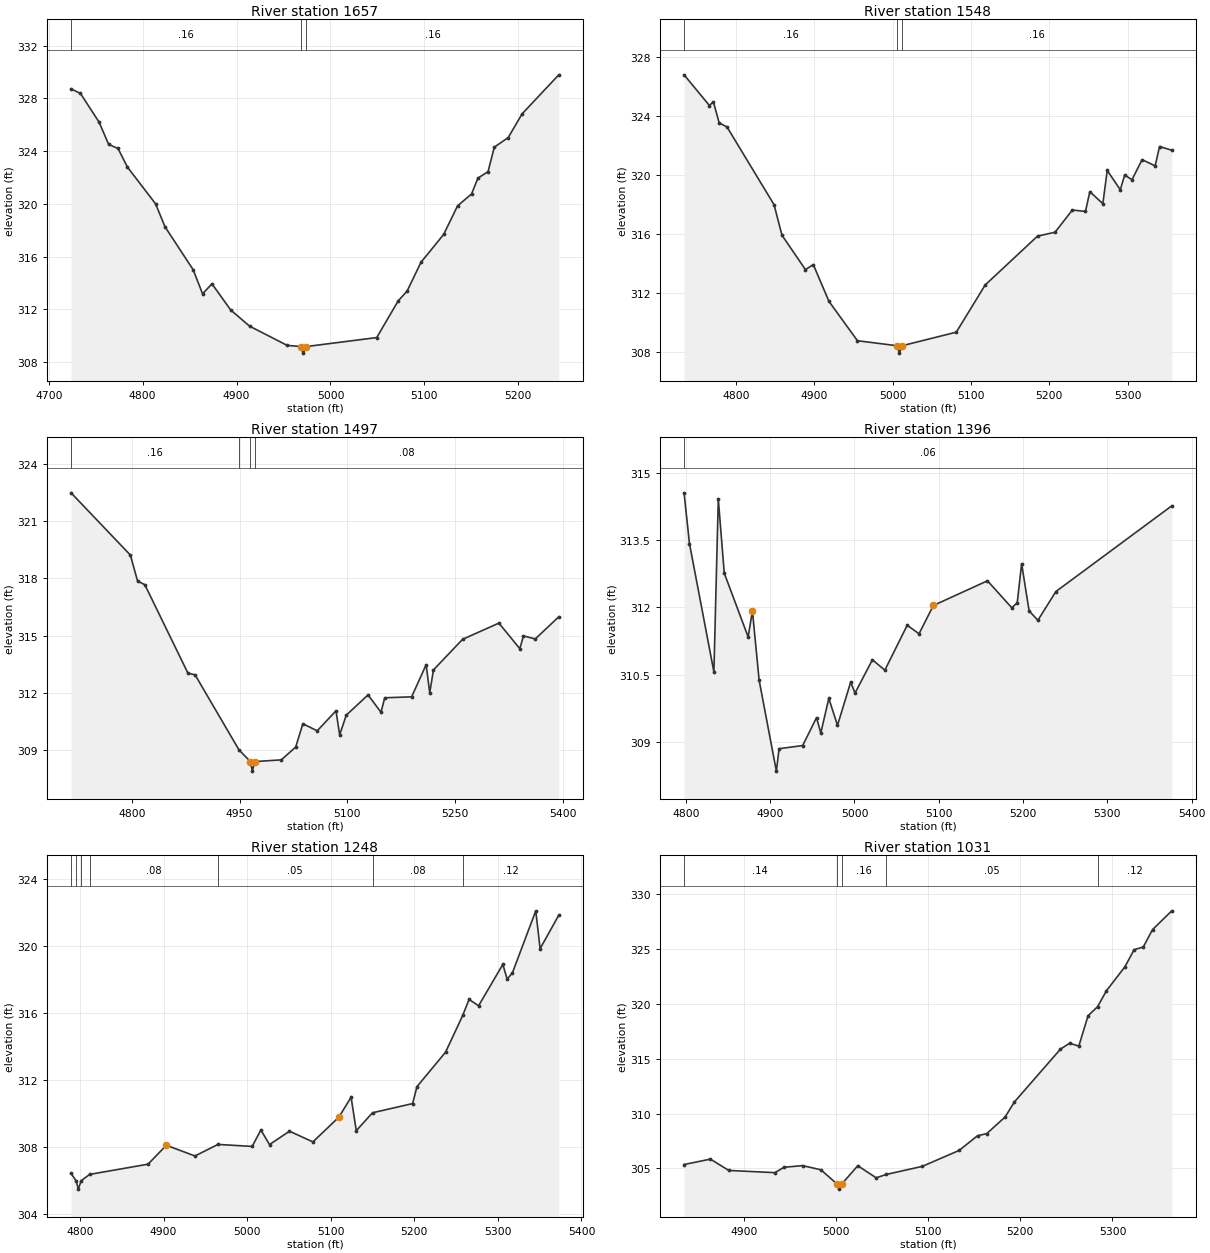
Type RM Length L Ch R = 1 ,1657    ,109,109,109
BEGIN DESCRIPTION:
UNT 160 IN BOCR 2.0
END DESCRIPTION:
XS GIS Cut Line= 3
       3722649.6     10649610.19      3722399.61     10649610.19
      3722149.66     10649710.17
#Sta/Elev= 30
  4723.8  328.72  4733.8  328.38  4753.8  326.18  4763.8  324.51  4773.8   324.2
  4783.8  322.79  4813.8     320  4823.8  318.26  4853.8     315  4863.8  313.17
  4873.8  313.93  4893.8  311.94  4913.8  310.72  4953.8  309.26  4968.3  309.17
    4971  308.67  4974.3  309.17  5049.2  309.85  5072.1  312.64  5081.5  313.37
  5096.3  315.56  5120.5  317.68  5135.3  319.85  5150.2  320.75  5156.9  321.95
  5167.7  322.44  5174.4   324.3  5189.2  325.03    5204  326.83    5243  329.79
#Mann= 3 ,-1 , 0
  4723.8     .16       0  4968.3     .03       0  4974.3     .16       0
Bank Sta=4968.3,4974.3
XS Rating Curve= 0 ,0
Exp/Cntr=0.3,0.1

Type RM Length L Ch R = 1 ,1548    ,51,51,51
BEGIN DESCRIPTION:
UNT 160 IN BOCR 1.0
END DESCRIPTION:
XS GIS Cut Line= 3
      3722654.39     10649527.05       3722328.9     10649509.69
      3722064.36     10649644.13
#Sta/Elev= 30
  4733.8  326.76  4766.2  324.68  4771.2  324.94  4778.6  323.51  4788.7  323.22
  4848.7  317.96  4858.8  315.89  4888.8  313.56  4898.8   313.9  4918.8  311.41
  4955.2  308.74    5006   308.4  5008.7   307.9    5012   308.4  5081.4  309.32
  5118.3  312.52  5185.1  315.83  5207.4  316.09  5229.6   317.6  5246.3   317.5
  5251.9  318.84  5268.5  318.03  5274.1  320.28  5290.8  318.97  5296.4  319.97
  5305.7  319.65  5318.6  321.01  5335.3  320.59  5340.9   321.9  5356.5  321.65
#Mann= 3 ,-1 , 0
  4733.8     .16       0    5006     .03       0    5012     .16       0
Bank Sta=5006,5012
XS Rating Curve= 0 ,0
Exp/Cntr=0.3,0.1

Type RM Length L Ch R = 1 ,1497    ,101,101,101
BEGIN DESCRIPTION:
Mapping XS f268f5f4
END DESCRIPTION:
XS GIS Cut Line= 3
      3722672.23     10649454.38      3722316.28     10649463.06
      3721997.32     10649512.97
#Sta/Elev= 30
  4715.5  322.47  4798.1  319.21  4808.1  317.85  4818.2  317.66  4878.2  313.03
  4888.2  312.94  4949.3  309.01  4965.2   308.4  4967.9   307.9  4971.2   308.4
  5008.2  308.49  5028.2  309.16  5038.2  310.38  5058.2  310.01  5084.3  311.06
  5089.4   309.8  5098.6  310.83  5128.9  311.89    5147  310.98  5152.1  311.74
  5189.6  311.79  5209.8  313.47  5214.8     312    5220   313.2  5260.5   314.8
  5311.1  315.65  5340.2  314.31  5345.3  314.98  5361.7  314.82  5394.4  315.98
#Mann= 4 ,-1 , 0
  4715.5     .16       0  4949.3     .08       0  4965.2     .07       0
  4971.2     .08       0
Bank Sta=4965.2,4971.2
XS Rating Curve= 0 ,0
Exp/Cntr=0.3,0.1

Type RM Length L Ch R = 1 ,1396    ,148,148,148
BEGIN DESCRIPTION:
Mapping XS 5457957b
END DESCRIPTION:
XS GIS Cut Line= 2
      3722615.79     10649315.49      3722055.86     10649460.89
#Sta/Elev= 30
  4797.9  314.55  4804.3  313.42  4833.3  310.56  4838.5  314.41  4845.6  312.76
  4873.9  311.34    4879  311.92  4886.9  310.38  4907.4  308.35  4910.6  308.85
  4938.6  308.92    4955  309.54  4960.1   309.2  4969.6  309.97  4979.9  309.37
  4995.5  310.33  5000.7  310.09  5021.3  310.83  5036.1   310.6  5062.6   311.6
  5076.6  311.41  5093.6  312.04  5157.8  312.59  5186.6  311.99  5193.1   312.1
  5198.3  312.97  5207.2  311.92  5217.6  311.71  5238.9  312.35  5376.4  314.26
#Mann= 1 ,-1 , 0
  4797.9     .06       0
Bank Sta=4879,5093.6
XS Rating Curve= 0 ,0
Exp/Cntr=0.3,0.1

Type RM Length L Ch R = 1 ,1248    ,217,217,217
BEGIN DESCRIPTION:
Mapping XS b0fee335
END DESCRIPTION:
XS GIS Cut Line= 2
      3722648.32     10649165.75      3722086.23     10649322.01
#Sta/Elev= 30
  4789.4  306.43  4795.4  305.99  4798.2  305.49  4801.4  305.99  4811.7  306.37
  4881.5  306.98  4903.4  308.11  4937.6  307.47  4965.2  308.16    5006  308.04
  5016.5  309.02  5026.8  308.15  5050.7  308.95  5078.7  308.31  5109.8  309.79
  5124.4  310.98  5130.6  308.98    5150  310.05    5198   310.6  5203.2  311.61
  5237.4  313.67  5257.9  315.86  5265.5  316.82  5276.9  316.44  5305.9  318.91
  5311.1  318.03  5317.4  318.41  5345.3  322.11  5350.5  319.85  5372.8  321.85
#Mann= 7 ,-1 , 0
  4789.4     .16       0  4795.4     .03       0  4801.4     .16       0
  4811.7     .08       0  4965.2     .05       0    5150     .08       0
  5257.9     .12       0
Bank Sta=4903.4,5109.8
XS Rating Curve= 0 ,0
Exp/Cntr=0.3,0.1

Type RM Length L Ch R = 1 ,1031    ,204,204,204
BEGIN DESCRIPTION:
Mapping XS 57705ee1
END DESCRIPTION:
XS GIS Cut Line= 2
      3722698.23     10649029.04      3722168.75      10649024.7
#Sta/Elev= 30
  4834.9  305.36  4863.5  305.85  4883.5  304.82  4933.5  304.62  4943.5  305.11
  4963.5  305.26  4983.5  304.88  5000.5  303.62  5003.3  303.12  5006.5  303.62
  5023.5  305.25  5043.5  304.15  5054.6  304.46  5093.5  305.19  5133.5  306.64
  5153.5  307.98  5163.5  308.17  5183.5  309.69  5193.5  311.05  5243.5  315.86
  5253.5   316.4  5263.5  316.14  5273.5   318.9  5283.8  319.72  5293.5  321.18
  5313.5  323.35  5323.5  324.91  5333.5  325.16  5343.5  326.74  5364.4  328.45
#Mann= 5 ,-1 , 0
  4834.9     .14       0  5000.5     .07       0  5006.5     .16       0
  5054.6     .05       0  5283.8     .12       0
Bank Sta=5000.5,5006.5
XS Rating Curve= 0 ,0
Exp/Cntr=0.3,0.1

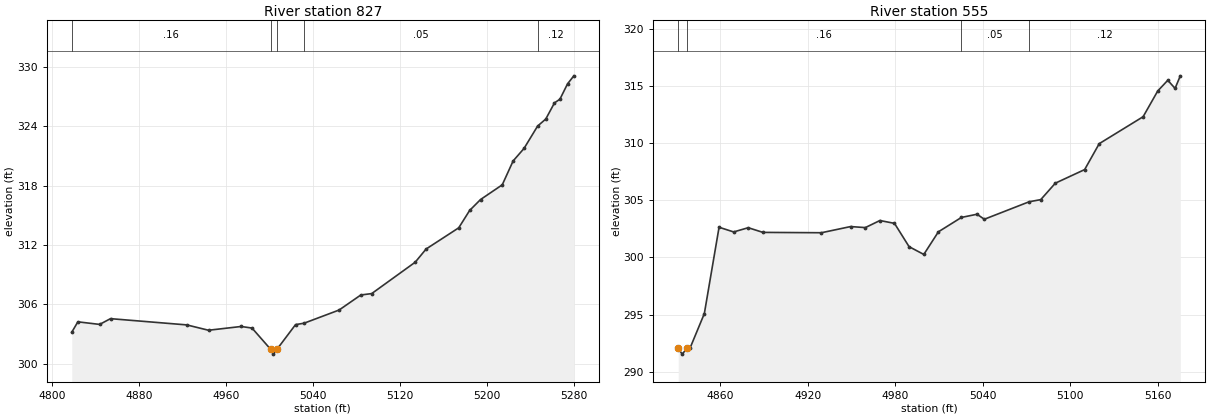
Type RM Length L Ch R = 1 ,827     ,272,272,272
BEGIN DESCRIPTION:
Mapping XS 21bde201
END DESCRIPTION:
XS GIS Cut Line= 2
      3722685.26     10648829.38      3722223.78     10648825.05
#Sta/Elev= 30
  4818.3  303.19  4823.9  304.24  4843.9  303.98  4853.9  304.56    4924  303.93
    4944  303.39    4974  303.77    4984  303.61    5001  301.48  5003.7  300.98
    5007  301.48    5024  303.96  5031.8   304.1    5064  305.43    5084  306.95
    5094  307.09    5134  310.26    5144  311.59    5174  313.73    5184  315.48
    5194  316.58    5214  318.07    5224  320.48    5234  321.74  5246.5     324
    5254  324.71    5262  326.34    5267  326.71    5274  328.26  5279.8  329.07
#Mann= 5 ,-1 , 0
  4818.3     .16       0    5001     .07       0    5007     .16       0
  5031.8     .05       0  5246.5     .12       0
Bank Sta=5001,5007
XS Rating Curve= 0 ,0
Exp/Cntr=0.3,0.1

Type RM Length L Ch R = 1 ,555     ,0,0,0
BEGIN DESCRIPTION:
Mapping XS 1434b752
END DESCRIPTION:
XS GIS Cut Line= 2
      3722657.49     10648610.91      3722314.19     10648584.67
#Sta/Elev= 30
  4831.3  292.03    4834  291.53  4837.3  292.03  4839.3  292.03  4849.2  295.08
  4859.3  302.64  4869.3  302.23  4879.3   302.6  4889.4  302.19  4929.5  302.16
  4949.5   302.7  4959.6  302.61  4969.6  303.23  4979.6  302.98  4989.6  300.94
  4999.7  300.26  5009.7  302.24  5025.5   303.5  5036.2  303.78  5041.2  303.34
  5071.9  304.87  5079.9  305.06  5089.9   306.5    5110  307.69    5120  309.96
  5150.1  312.32  5160.1  314.57    5167  315.51    5172   314.8  5175.6   315.9
#Mann= 4 ,-1 , 0
  4831.3     .07       0  4837.3     .16       0  5025.5     .05       0
  5071.9     .12       0
Bank Sta=4831.3,4837.3
XS Rating Curve= 0 ,0
Exp/Cntr=0.3,0.1

Chan Stop Cuts=-1
Use User Specified Reach Order=0
Composite Channel Slope=5