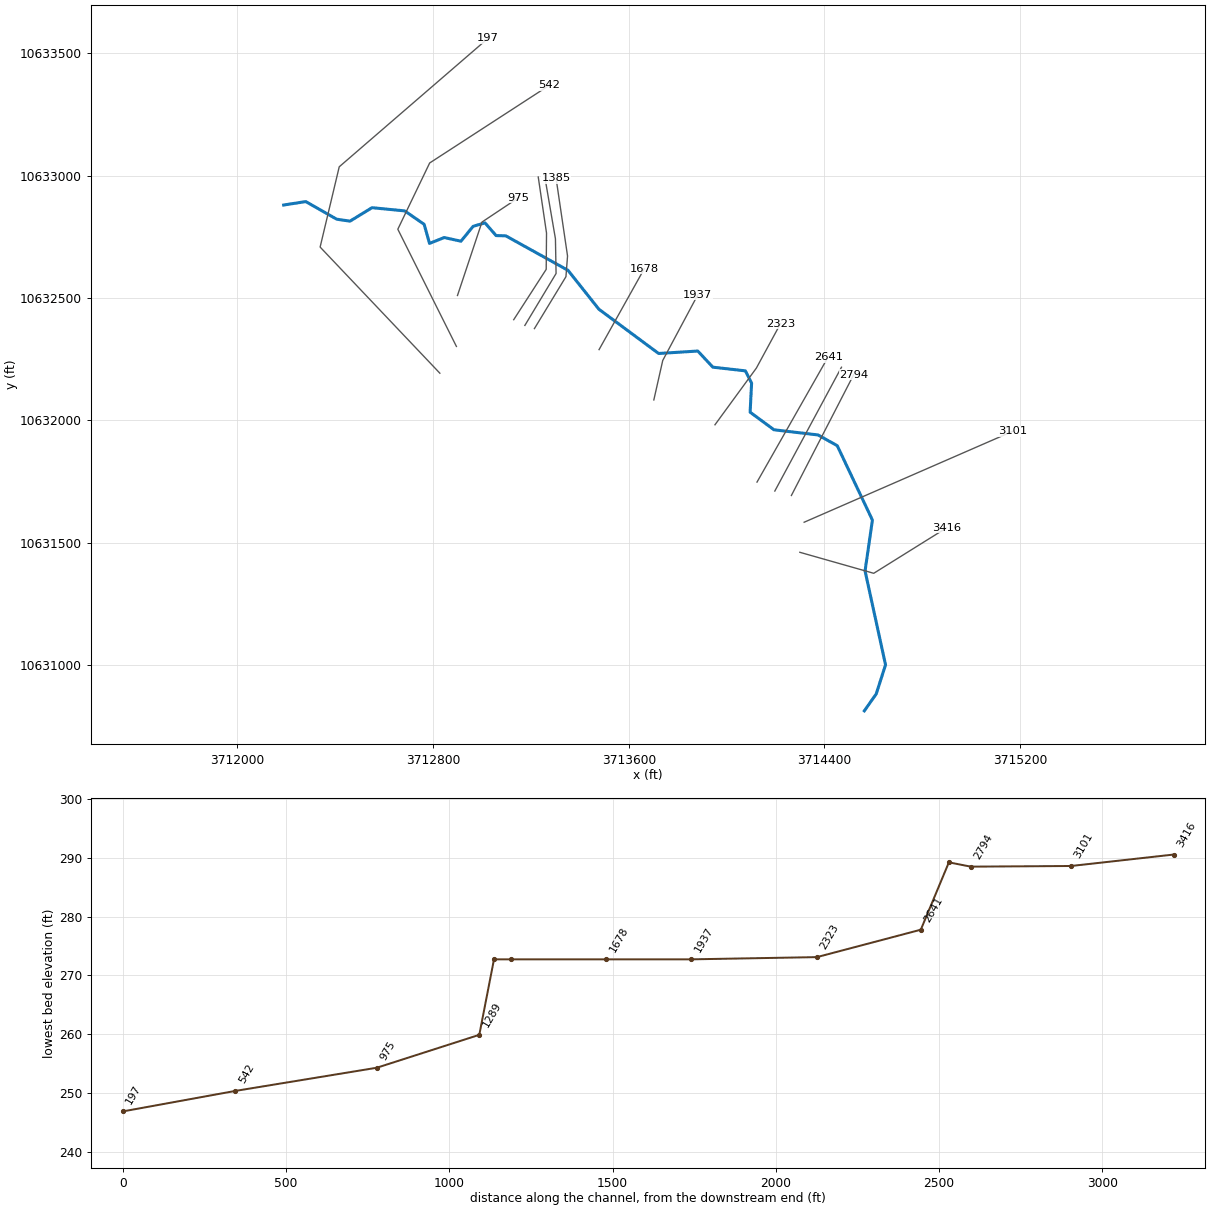
--- UNT 162 IN BOCR.prj (project) ---

Proj Title=UNT 162 IN BOCR Base Level Engineering
Current Plan=p01
Default Exp/Contr=0.3,0.1
English Units
Geom File=g01
Flow File=f01
Plan File=p01
Y Axis Title=Elevation
X Axis Title(PF)=Main Channel Distance
X Axis Title(XS)=Station
BEGIN DESCRIPTION:
UNT 162 IN BOCR
END DESCRIPTION:
DSS Export Rating Curves= 0
DSS Export Rating Curve Sorted= 0
DSS Export Volume Flow Curves= 0
DXF OffsetX= 0
DXF OffsetY= 0
DXF ScaleX= 1
DXF ScaleY= 10

--- UNT 162 IN BOCR.p01 (plan) ---

Plan Title=Multiple Run
Short Identifier=Multiple
Geom File=g01
Flow File=f01
Subcritical Flow
K Sum by GR= 0
Std Step Tol= 0.01
Critical Tol= 0.01
Num of Std Step Trials= 20
Max Error Tol= 0.3
Flow Tol Ratio= 0.001
Split Flow NTrial= 30
Split Flow Tol= 0.02
Split Flow Ratio= 0.02
Log Output Level= 0
Friction Slope Method= 1
Unsteady Friction Slope Method= 2
Unsteady Bridges Friction Slope Method= 1
Parabolic Critical Depth
Global Vel Dist=  1 , 1 , 1
Global Log Level= 0
CheckData=True
Encroach Param= -1, 0, 0, 0
BEGIN DESCRIPTION:
Multiple Run
END DESCRIPTION:

--- UNT 162 IN BOCR.f01 (steady flow) ---

Flow Title=Multiple
Program Version=4.10
Number of Profiles= 7
Profile Names=10-year,25-year,50-year,1pct_min,100-year,1pct_plu,500-year
River Rch & RM=UNT 162 IN BOCR,Reach-1         ,3416
      91     108     121     100     135     183     168
River Rch & RM=UNT 162 IN BOCR,Reach-1         ,1385
     152     188     215     182     246     332     321
River Rch & RM=UNT 162 IN BOCR,Reach-1         ,975
     152     188     215     182     246     332     321
Boundary for River Rch & Prof#=UNT 162 IN BOCR,Reach-1         , 1
Up Type= 0
Dn Type= 3
Dn Slope=0.005
Boundary for River Rch & Prof#=UNT 162 IN BOCR,Reach-1         , 2
Up Type= 0
Dn Type= 3
Dn Slope=0.005
Boundary for River Rch & Prof#=UNT 162 IN BOCR,Reach-1         , 3
Up Type= 0
Dn Type= 3
Dn Slope=0.005
Boundary for River Rch & Prof#=UNT 162 IN BOCR,Reach-1         , 4
Up Type= 0
Dn Type= 3
Dn Slope=0.005
Boundary for River Rch & Prof#=UNT 162 IN BOCR,Reach-1         , 5
Up Type= 0
Dn Type= 3
Dn Slope=0.005
Boundary for River Rch & Prof#=UNT 162 IN BOCR,Reach-1         , 6
Up Type= 0
Dn Type= 3
Dn Slope=0.005
Boundary for River Rch & Prof#=UNT 162 IN BOCR,Reach-1         , 7
Up Type= 0
Dn Type= 3
Dn Slope=0.005
DSS Import GetInterval= 0
DSS Import GetPeak= 0
DSS Import FillOption= 0

--- UNT 162 IN BOCR.g01 (geometry) ---

Geom Title=Existing Conditions

River Reach=UNT 162 IN BOCR,Reach-1
Reach XY= 30
      3714563.25     10630812.00      3714611.75     10630881.00
      3714650.00     10631000.00      3714566.25     10631384.00
      3714596.25     10631592.00      3714452.50     10631896.00
      3714373.75     10631940.00      3714194.00     10631961.00
      3714096.25     10632033.00      3714102.25     10632152.00
      3714076.75     10632202.00      3713943.75     10632217.00
      3713882.25     10632283.00      3713722.00     10632273.00
      3713477.75     10632454.00      3713351.50     10632613.00
      3713097.00     10632754.00      3713057.50     10632755.00
      3713012.00     10632807.00      3712963.75     10632793.00
      3712913.75     10632732.00      3712845.25     10632747.00
      3712785.25     10632723.00      3712763.25     10632801.00
      3712683.75     10632856.00      3712550.00     10632869.00
      3712460.00     10632814.00      3712405.75     10632822.00
      3712279.25     10632894.00      3712188.75     10632880.00

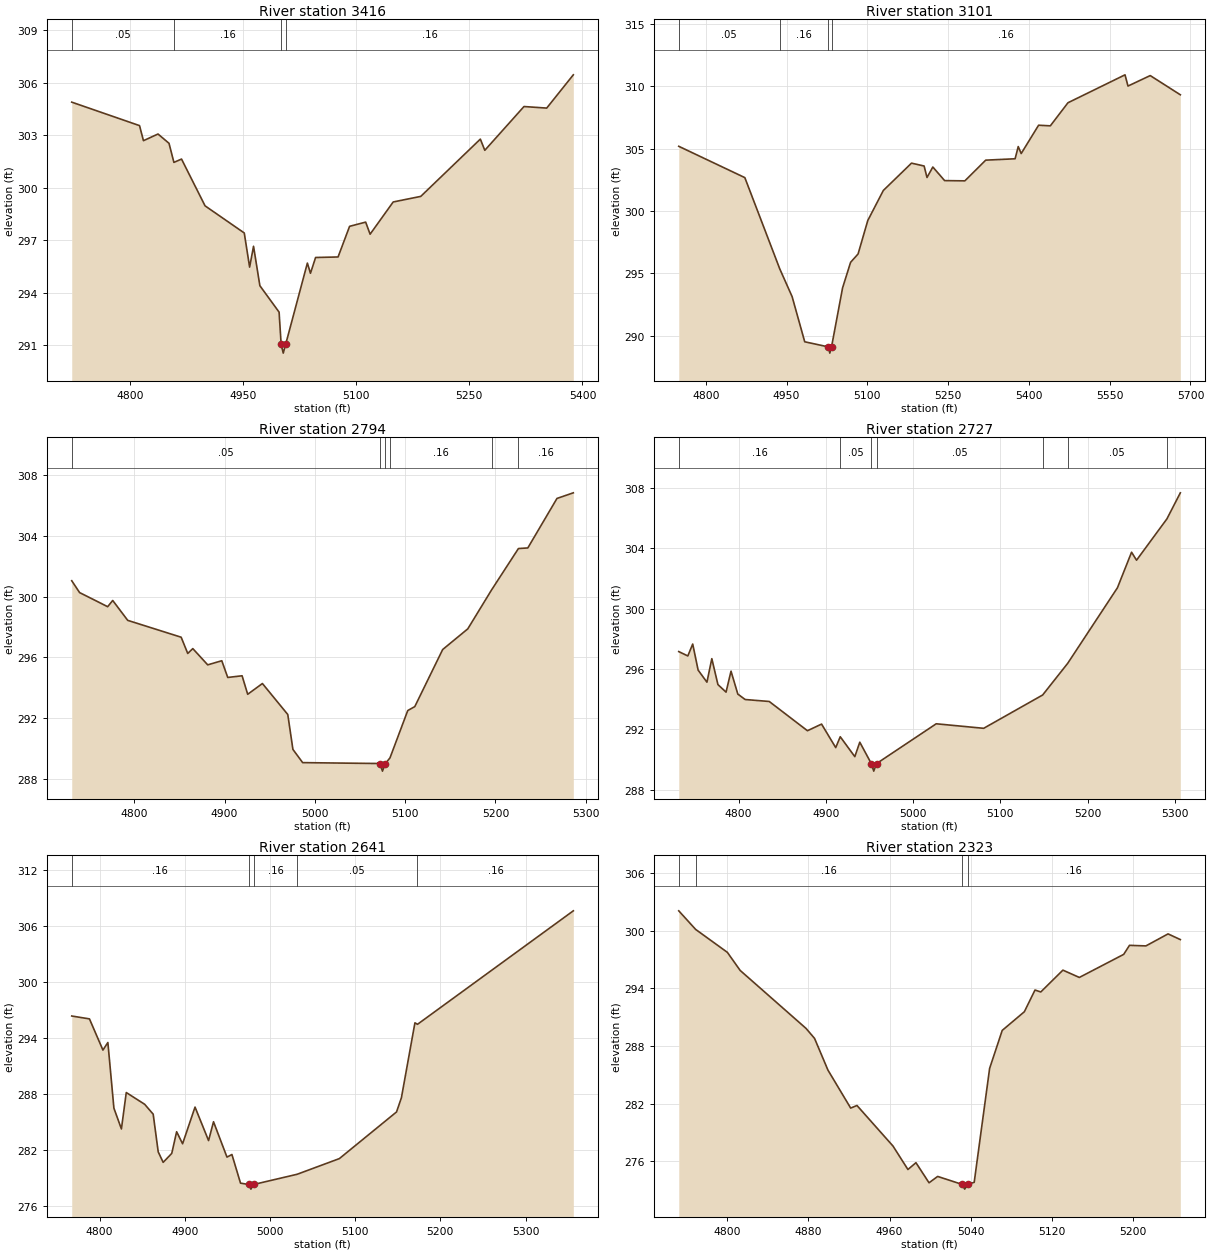
Type RM Length L Ch R = 1,3416,315,315,315
BEGIN DESCRIPTION:
UNT 162 IN BOCR 8.0
END DESCRIPTION:
XS GIS Cut Line= 3
      3714299.57     10631460.20      3714601.69     10631374.33
      3714899.59     10631560.17
#Sta/Elev= 30
  4722.7  304.89  4812.6  303.55  4817.8  302.69  4837.1  303.07  4851.7  302.54
  4858.2  301.45  4868.3  301.64  4899.5  298.97  4951.5  297.42  4958.6  295.47
  4963.8  296.66  4972.2  294.41  4997.7  292.90  5000.4  291.06  5003.2  290.56
  5006.4  291.06  5035.2  295.70  5039.3  295.12  5046.1  296.02  5075.9  296.05
  5091.2  297.80  5112.5  298.04  5118.4  297.35  5149.0  299.19  5185.6  299.51
  5264.6  302.78  5270.5  302.14  5322.5  304.64  5352.6  304.55  5387.9  306.45
#Mann=4,-1,0
  4722.7    0.05       0  4858.2    0.16       0  5000.4    0.07       0
  5006.4    0.16       0
Bank Sta=5000.4,5006.4
Exp/Cntr=0.3,0.1

Type RM Length L Ch R = 1,3101,307,307,307
BEGIN DESCRIPTION:
UNT 162 IN BOCR 7.0
END DESCRIPTION:
XS GIS Cut Line= 2
      3714317.09     10631583.07      3715170.88     10631955.30
#Sta/Elev= 30
  4749.8  305.19  4872.5  302.68  4937.3  295.37  4960.3  293.14  4983.7  289.52
  5027.5  289.11  5030.3  288.61  5033.5  289.11  5054.0  293.84  5068.9  295.89
  5082.8  296.56  5100.8  299.24  5129.7  301.65  5182.0  303.84  5205.4  303.61
  5210.8  302.69  5221.6  303.53  5243.5  302.44  5281.1  302.42  5319.8  304.08
  5374.4  304.19  5380.2  305.17  5385.7  304.61  5418.0  306.88  5439.8  306.83
  5472.5  308.68  5578.5  310.92  5584.0  310.02  5625.3  310.86  5681.2  309.32
#Mann=4,-1,0
  4749.8    0.05       0  4937.3    0.16       0  5027.5    0.07       0
  5033.5    0.16       0
Bank Sta=5027.5,5033.5
Exp/Cntr=0.3,0.1

Type RM Length L Ch R = 1,2794,67,67,67
BEGIN DESCRIPTION:
Mapping XS b5998edc
END DESCRIPTION:
XS GIS Cut Line= 2
      3714264.98     10631692.46      3714519.67     10632186.25
#Sta/Elev= 30
  4730.7  301.04  4739.4  300.26  4770.5  299.33  4776.1  299.74  4792.7  298.43
  4851.9  297.32  4859.2  296.25  4864.8  296.57  4881.3  295.50  4896.9  295.77
  4903.5  294.67  4919.4  294.78  4925.6  293.56  4941.9  294.27  4970.0  292.23
  4975.7  289.93  4986.5  289.06  5072.1  289.00  5074.9  288.50  5078.1  289.00
  5083.2  289.37  5102.9  292.49  5110.7  292.75  5141.6  296.51  5169.4  297.87
  5195.8  300.44  5225.5  303.16  5235.9  303.20  5268.2  306.46  5286.3  306.83
#Mann=6,-1,0
  4730.7    0.05       0  5072.1    0.03       0  5078.1    0.05       0
  5083.2    0.16       0  5195.8    0.05       0  5225.5    0.16       0
Bank Sta=5072.1,5078.1
Exp/Cntr=0.3,0.1

Type RM Length L Ch R = 1,2727,86,86,86
BEGIN DESCRIPTION:
Mapping XS 430b23ba
END DESCRIPTION:
XS GIS Cut Line= 2
      3714197.24     10631710.62      3714469.80     10632216.81
#Sta/Elev= 30
  4731.5  297.16  4741.9  296.87  4747.5  297.66  4753.7  295.93  4763.8  295.13
  4769.4  296.69  4776.4  294.97  4785.7  294.47  4791.4  295.86  4799.2  294.34
  4807.6  293.98  4835.2  293.85  4879.0  291.91  4895.2  292.35  4911.4  290.79
  4916.6  291.51  4933.3  290.19  4939.0  291.15  4952.2  289.73  4955.0  289.23
  4958.2  289.73  5026.6  292.37  5081.0  292.07  5148.6  294.28  5177.3  296.38
  5234.3  301.39  5250.5  303.75  5256.2  303.22  5291.0  305.96  5306.4  307.69
#Mann=7,-1,0
  4731.5    0.16       0  4916.6    0.05       0  4952.2    0.03       0
  4958.2    0.05       0  5148.6    0.16       0  5177.3    0.05       0
  5291.0    0.16       0
Bank Sta=4952.2,4958.2
Exp/Cntr=0.3,0.1

Type RM Length L Ch R = 1,2641,318,318,318
BEGIN DESCRIPTION:
UNT 162 IN BOCR 6.0
END DESCRIPTION:
XS GIS Cut Line= 2
      3714124.34     10631747.12      3714415.30     10632258.89
#Sta/Elev= 30
  4767.4  296.32  4788.2  296.01  4804.0  292.67  4809.8  293.48  4816.9  286.44
  4825.7  284.22  4831.4  288.12  4853.0  286.86  4863.0  285.80  4868.9  281.76
  4874.7  280.64  4884.8  281.60  4890.5  283.92  4897.5  282.63  4912.1  286.56
  4928.0  282.97  4933.8  284.99  4949.6  281.20  4955.4  281.48  4965.5  278.41
  4975.0  278.27  4977.7  277.77  4981.0  278.27  5031.9  279.36  5081.5  281.04
  5148.6  286.04  5154.3  287.55  5170.2  295.59  5173.2  295.43  5356.1  307.59
#Mann=5,-1,0
  4767.4    0.16       0  4975.0    0.07       0  4981.0    0.16       0
  5031.9    0.05       0  5173.2    0.16       0
Bank Sta=4975,4981
Exp/Cntr=0.3,0.1

Type RM Length L Ch R = 1,2323,386,386,386
BEGIN DESCRIPTION:
UNT 162 IN BOCR 5.0
END DESCRIPTION:
XS GIS Cut Line= 3
      3713952.47     10631981.50      3714121.74     10632213.26
      3714220.59     10632395.36
#Sta/Elev= 30
  4752.3  302.06  4768.9  300.13  4800.2  297.74  4812.8  295.86  4877.7  289.83
  4886.1  288.79  4899.3  285.49  4921.7  281.54  4927.9  281.81  4963.4  277.59
  4978.1  275.15  4986.0  275.86  4998.9  273.77  5007.4  274.43  5031.3  273.61
  5034.0  273.11  5037.3  273.61  5043.4  273.82  5058.6  285.67  5071.0  289.62
  5092.8  291.56  5103.3  293.82  5109.0  293.62  5130.8  295.89  5147.0  295.13
  5190.7  297.53  5196.4  298.47  5212.6  298.41  5234.4  299.66  5246.5  299.07
#Mann=4,-1,0
  4752.3    0.05       0  4768.9    0.16       0  5031.3    0.07       0
  5037.3    0.16       0
Bank Sta=5031.3,5037.3
Exp/Cntr=0.3,0.1

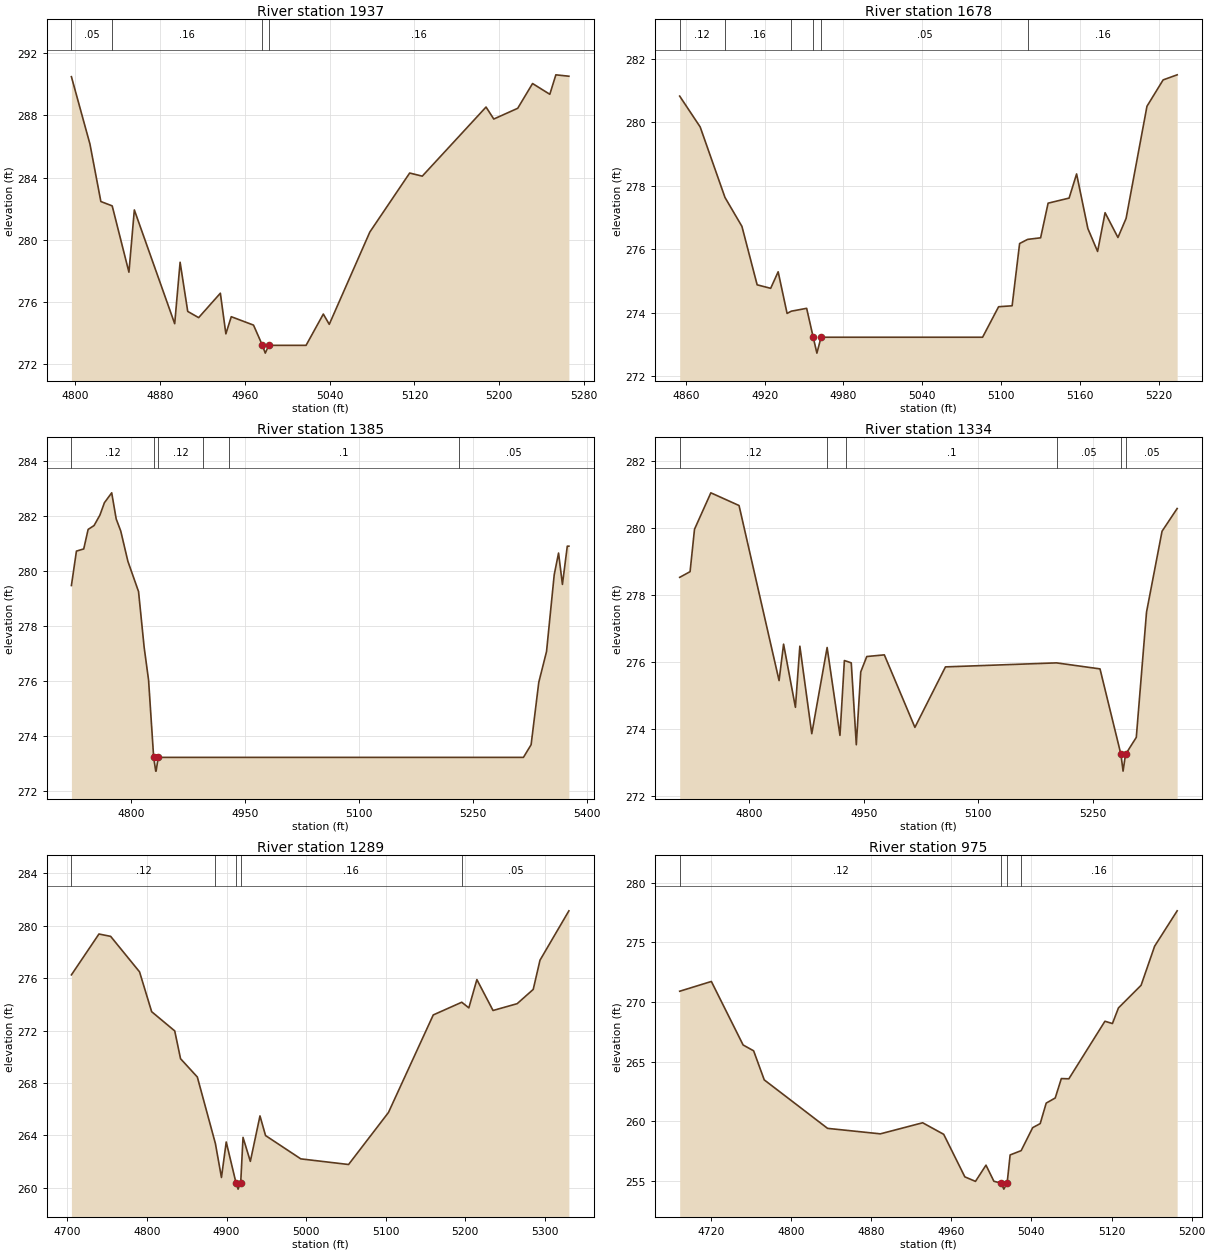
Type RM Length L Ch R = 1,1937,259,259,259
BEGIN DESCRIPTION:
UNT 162 IN BOCR 4.0
END DESCRIPTION:
XS GIS Cut Line= 3
      3713702.47     10632083.08      3713738.92     10632244.51
      3713882.17     10632512.76
#Sta/Elev= 30
  4796.2  290.49  4813.7  286.16  4824.0  282.47  4834.7  282.19  4850.5  277.93
  4855.6  281.93  4893.7  274.62  4898.8  278.57  4906.0  275.41  4916.3  275.01
  4936.8  276.58  4942.0  273.97  4947.1  275.07  4968.1  274.53  4976.5  273.23
  4979.2  272.73  4982.5  273.23  5017.7  273.23  5034.0  275.24  5039.6  274.58
  5077.9  280.51  5115.5  284.30  5127.4  284.10  5187.6  288.54  5194.9  287.77
  5217.5  288.46  5231.5  290.05  5247.8  289.36  5253.5  290.61  5265.8  290.52
#Mann=4,-1,0
  4796.2    0.05       0  4834.7    0.16       0  4976.5    0.07       0
  4982.5    0.16       0
Bank Sta=4976.5,4982.5
Exp/Cntr=0.3,0.1

Type RM Length L Ch R = 1,1678,293,293,293
BEGIN DESCRIPTION:
Mapping XS 1d7fa806
END DESCRIPTION:
XS GIS Cut Line= 2
      3713478.52     10632288.80      3713663.41     10632619.53
#Sta/Elev= 30
  4855.3  280.82  4870.9  279.85  4889.8  277.63  4902.7  276.72  4914.3  274.88
  4924.6  274.77  4930.3  275.29  4937.1  273.98  4940.3  274.05  4952.0  274.14
  4957.0  273.23  4959.8  272.73  4963.0  273.23  5086.0  273.23  5098.2  274.19
  5108.5  274.22  5114.2  276.18  5120.3  276.31  5130.2  276.36  5135.9  277.45
  5151.9  277.61  5157.6  278.37  5166.2  276.65  5173.6  275.93  5179.3  277.15
  5189.1  276.37  5195.3  276.97  5211.2  280.50  5223.5  281.33  5234.2  281.49
#Mann=6,-1,0
  4855.3    0.12       0  4889.8    0.16       0  4940.3    0.05       0
  4957.0   0.033       0  4963.0    0.05       0  5120.3    0.16       0
Bank Sta=4957,4963
Exp/Cntr=0.3,0.1

Type RM Length L Ch R = 1,1385,51,51,51
BEGIN DESCRIPTION:
UNT 162 IN BOCR 3.0
END DESCRIPTION:
XS GIS Cut Line= 4
      3713214.17     10632374.69      3713343.09     10632586.96
      3713349.60     10632671.60      3713302.72     10632989.32
#Sta/Elev= 30
  4721.8  279.48  4728.4  280.73  4738.0  280.81  4743.8  281.52  4751.6  281.66
  4759.3  282.04  4765.2  282.49  4774.8  282.85  4780.7  281.90  4786.7  281.46
  4796.1  280.36  4810.1  279.26  4817.5  277.23  4823.3  276.04  4830.0  273.23
  4832.7  272.73  4833.2  272.73  4836.0  273.23  4894.8  273.23  4928.6  273.23
  5231.0  273.23  5316.4  273.23  5326.5  273.69  5336.6  275.96  5346.8  277.08
  5356.9  279.87  5362.6  280.66  5367.7  279.52  5374.1  280.91  5376.2  280.91
#Mann=6,-1,0
  4721.8    0.12       0  4830.0    0.07       0  4836.0    0.12       0
  4894.8    0.05       0  4928.6     0.1       0  5231.0    0.05       0
Bank Sta=4830,4836
Exp/Cntr=0.3,0.1

Type RM Length L Ch R = 1,1334,45,45,45
BEGIN DESCRIPTION:
Mapping XS 8bd82cd8
END DESCRIPTION:
XS GIS Cut Line= 4
      3713175.12     10632387.73      3713302.73     10632599.98
      3713300.12     10632741.91      3713255.85     10632999.73
#Sta/Elev= 30
  4709.2  278.53  4722.8  278.70  4728.6  279.97  4750.0  281.06  4786.9  280.68
  4839.3  275.44  4845.2  276.53  4860.7  274.64  4866.5  276.47  4882.1  273.85
  4902.2  276.43  4919.0  273.80  4924.8  276.04  4927.5  276.02  4933.8  275.97
  4940.4  273.52  4946.2  275.70  4954.1  276.16  4977.1  276.21  5017.1  274.04
  5057.1  275.85  5202.5  275.97  5259.4  275.79  5286.8  273.23  5289.6  272.73
  5292.8  273.23  5306.9  273.74  5320.3  277.49  5340.6  279.91  5360.4  280.59
#Mann=6,-1,0
  4709.2    0.12       0  4902.2    0.16       0  4927.5     0.1       0
  5202.5    0.05       0  5286.8    0.07       0  5292.8    0.05       0
Bank Sta=5286.8,5292.8
Exp/Cntr=0.3,0.1

Type RM Length L Ch R = 1,1289,314,314,314
BEGIN DESCRIPTION:
Mapping XS 8bb22a9a
END DESCRIPTION:
XS GIS Cut Line= 4
      3713129.53     10632411.15      3713262.36     10632616.91
      3713263.66     10632765.35      3713229.81     10632994.50
#Sta/Elev= 30
  4705.1  276.25  4739.7  279.37  4754.4  279.19  4790.7  276.48  4805.9  273.44
  4834.9  271.97  4842.2  269.85  4863.3  268.45  4886.0  263.37  4893.6  260.78
  4899.6  263.49  4911.8  260.39  4914.5  259.89  4917.8  260.39  4920.7  263.84
  4929.9  262.01  4942.0  265.48  4949.0  263.98  4993.3  262.20  5053.3  261.77
  5103.4  265.74  5159.7  273.19  5195.5  274.16  5204.4  273.73  5214.5  275.89
  5234.8  273.53  5265.1  274.05  5285.3  275.14  5293.8  277.37  5330.1  281.14
#Mann=5,-1,0
  4705.1    0.12       0  4886.0    0.16       0  4911.8    0.07       0
  4917.8    0.16       0  5195.5    0.05       0
Bank Sta=4911.8,4917.8
Exp/Cntr=0.3,0.1

Type RM Length L Ch R = 1,975,433,433,433
BEGIN DESCRIPTION:
UNT 162 IN BOCR 2.0
END DESCRIPTION:
XS GIS Cut Line= 3
      3712899.60     10632510.17      3712999.61     10632810.19
      3713149.58     10632910.17
#Sta/Elev= 30
  4689.0  270.90  4720.6  271.72  4752.3  266.39  4762.8  265.90  4773.4  263.46
  4836.6  259.39  4889.3  258.93  4931.5  259.86  4952.5  258.89  4973.6  255.32
  4984.2  254.94  4994.7  256.30  5002.6  254.95  5009.8  254.79  5012.5  254.29
  5015.8  254.79  5018.8  257.16  5029.8  257.52  5041.3  259.45  5048.8  259.79
  5054.8  261.51  5063.8  261.94  5069.9  263.57  5077.4  263.55  5113.4  268.38
  5120.9  268.19  5126.9  269.50  5149.5  271.40  5163.0  274.68  5185.5  277.65
#Mann=4,-1,0
  4689.0    0.12       0  5009.8    0.07       0  5015.8    0.12       0
  5029.8    0.16       0
Bank Sta=5009.8,5015.8
Exp/Cntr=0.3,0.1

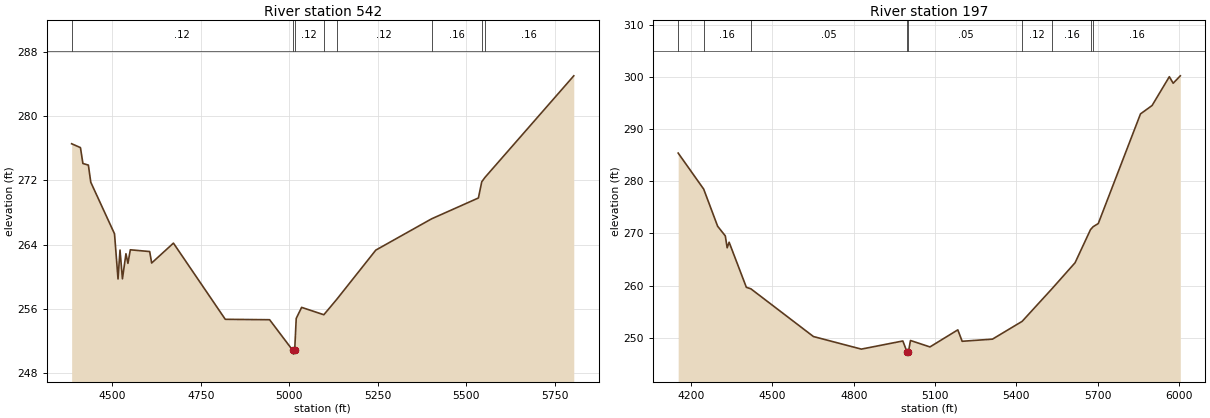
Type RM Length L Ch R = 1,542,345,345,345
BEGIN DESCRIPTION:
Mapping XS 292cbfca
END DESCRIPTION:
XS GIS Cut Line= 4
      3712895.19     10632301.77      3712655.59     10632780.97
      3712785.80     10633051.80      3713274.96     10633369.24
#Sta/Elev= 30
  4384.6  276.58  4409.5  276.10  4416.4  274.12  4431.9  273.92  4438.7  271.78
  4505.8  265.35  4515.7  259.72  4521.3  263.33  4528.2  259.74  4538.1  262.87
  4543.7  261.67  4550.5  263.36  4605.2  263.14  4610.8  261.71  4672.3  264.19
  4818.9  254.69  4944.2  254.64  5009.1  250.85  5011.9  250.35  5015.1  250.85
  5019.4  254.80  5034.7  256.18  5097.5  255.26  5133.8  257.17  5244.4  263.32
  5402.1  267.22  5534.4  269.82  5543.9  271.84  5552.9  272.38  5804.0  285.05
#Mann=8,-1,0
  4384.6    0.12       0  5009.1    0.07       0  5015.1    0.12       0
  5097.5    0.05       0  5133.8    0.12       0  5402.1    0.16       0
  5543.9    0.12       0  5552.9    0.16       0
Bank Sta=5009.1,5015.1
Exp/Cntr=0.3,0.1

Type RM Length L Ch R = 1,197,0,0,0
BEGIN DESCRIPTION:
UNT 162 IN BOCR 1.0
END DESCRIPTION:
XS GIS Cut Line= 4
      3712827.49     10632192.40      3712337.88     10632708.05
      3712416.01     10633036.18      3713025.02     10633561.91
#Sta/Elev= 30
  4152.1  285.38  4246.2  278.48  4297.7  271.37  4326.0  269.51  4332.9  267.23
  4340.1  268.30  4403.7  259.66  4420.5  259.37  4651.2  250.23  4828.0  247.82
  4981.1  249.38  4996.0  247.36  4998.7  246.86  5002.0  247.36  5009.3  249.47
  5081.2  248.24  5184.0  251.51  5200.0  249.32  5311.8  249.73  5421.4  253.14
  5533.1  259.48  5616.7  264.37  5673.6  270.71  5683.3  271.27  5702.3  271.88
  5858.1  292.89  5900.8  294.49  5964.5  300.01  5978.7  298.76  6005.0  300.18
#Mann=9,-1,0
  4152.1    0.12       0  4246.2    0.16       0  4420.5    0.05       0
  4996.0    0.03       0  5002.0    0.05       0  5421.4    0.12       0
  5533.1    0.16       0  5673.6    0.12       0  5683.3    0.16       0
Bank Sta=4996,5002
Exp/Cntr=0.3,0.1

Chan Stop Cuts=-1