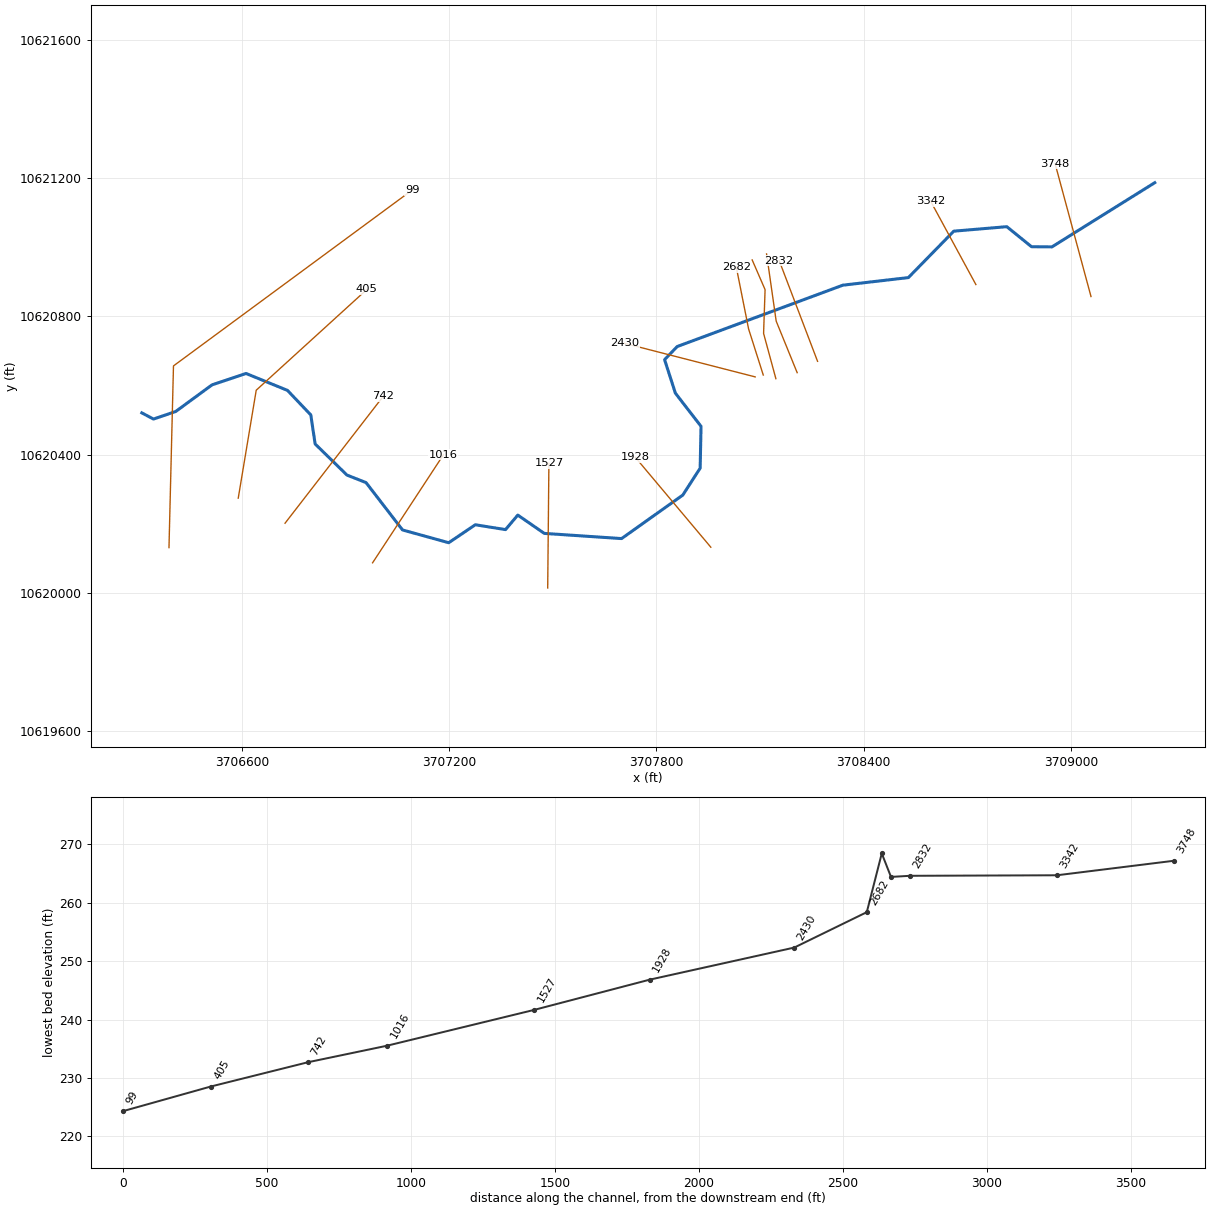
--- UNT 163 IN BOCR.prj (project) ---

Proj Title=UNT 163 IN BOCR Base Level Engineering
Current Plan=p01
Default Exp/Contr=0.3,0.1
English Units
Geom File=g01
Flow File=f01
Plan File=p01
Y Axis Title=Elevation
X Axis Title(PF)=Main Channel Distance
X Axis Title(XS)=Station
BEGIN DESCRIPTION:
UNT 163 IN BOCR
END DESCRIPTION:
DSS Export Rating Curves= 0
DSS Export Rating Curve Sorted= 0
DSS Export Volume Flow Curves= 0
DXF OffsetX= 0
DXF OffsetY= 0
DXF ScaleX= 1
DXF ScaleY= 10

--- UNT 163 IN BOCR.p01 (plan) ---

Plan Title=Multiple Run
Short Identifier=Multiple
Geom File=g01
Flow File=f01
Subcritical Flow
K Sum by GR= 0
Std Step Tol= 0.01
Critical Tol= 0.01
Num of Std Step Trials= 20
Max Error Tol= 0.3
Flow Tol Ratio= 0.001
Split Flow NTrial= 30
Split Flow Tol= 0.02
Split Flow Ratio= 0.02
Log Output Level= 0
Friction Slope Method= 1
Unsteady Friction Slope Method= 2
Unsteady Bridges Friction Slope Method= 1
Parabolic Critical Depth
Global Vel Dist=  1 , 1 , 1
Global Log Level= 0
CheckData=True
Encroach Param= -1, 0, 0, 0
BEGIN DESCRIPTION:
Multiple Run
END DESCRIPTION:

--- UNT 163 IN BOCR.f01 (steady flow) ---

Flow Title=Multiple
Program Version=4.10
Number of Profiles= 7
Profile Names=10-year,25-year,50-year,1pct_min,100-year,1pct_plu,500-year
River Rch & RM=UNT 163 IN BOCR,Reach-1         ,3748
     243     309     359     307     416     562     559
Boundary for River Rch & Prof#=UNT 163 IN BOCR,Reach-1         , 1
Up Type= 0
Dn Type= 3
Dn Slope=0.01
Boundary for River Rch & Prof#=UNT 163 IN BOCR,Reach-1         , 2
Up Type= 0
Dn Type= 3
Dn Slope=0.01
Boundary for River Rch & Prof#=UNT 163 IN BOCR,Reach-1         , 3
Up Type= 0
Dn Type= 3
Dn Slope=0.01
Boundary for River Rch & Prof#=UNT 163 IN BOCR,Reach-1         , 4
Up Type= 0
Dn Type= 3
Dn Slope=0.01
Boundary for River Rch & Prof#=UNT 163 IN BOCR,Reach-1         , 5
Up Type= 0
Dn Type= 3
Dn Slope=0.01
Boundary for River Rch & Prof#=UNT 163 IN BOCR,Reach-1         , 6
Up Type= 0
Dn Type= 3
Dn Slope=0.01
Boundary for River Rch & Prof#=UNT 163 IN BOCR,Reach-1         , 7
Up Type= 0
Dn Type= 3
Dn Slope=0.01
DSS Import GetInterval= 0
DSS Import GetPeak= 0
DSS Import FillOption= 0

--- UNT 163 IN BOCR.g01 (geometry) ---

Geom Title=Existing Conditions
Program Version=4.10

River Reach=UNT 163 IN BOCR ,Reach-1
Reach XY= 30
      3709242.87      10621187.3      3708945.18     10621001.48
        3708886.       10621002.       3708814.5       10621060.
        3708661.       10621047.      3708529.55     10620912.59
      3708339.74     10620890.61      3707860.25       10620713.
      3707823.75       10620675.        3707855.       10620578.
      3707929.25       10620482.      3707926.75       10620361.
       3707876.5       10620283.      3707699.25       10620157.
       3707475.5       10620172.      3707398.75       10620225.
      3707363.25       10620183.      3707275.75       10620197.
      3707198.75       10620145.        3707065.       10620182.
       3706959.5       10620319.        3706904.       10620341.
        3706812.       10620431.       3706799.5       10620515.
        3706732.       10620586.        3706612.       10620635.
       3706513.5       10620602.       3706408.5       10620525.
        3706344.       10620503.      3706310.25       10620521.

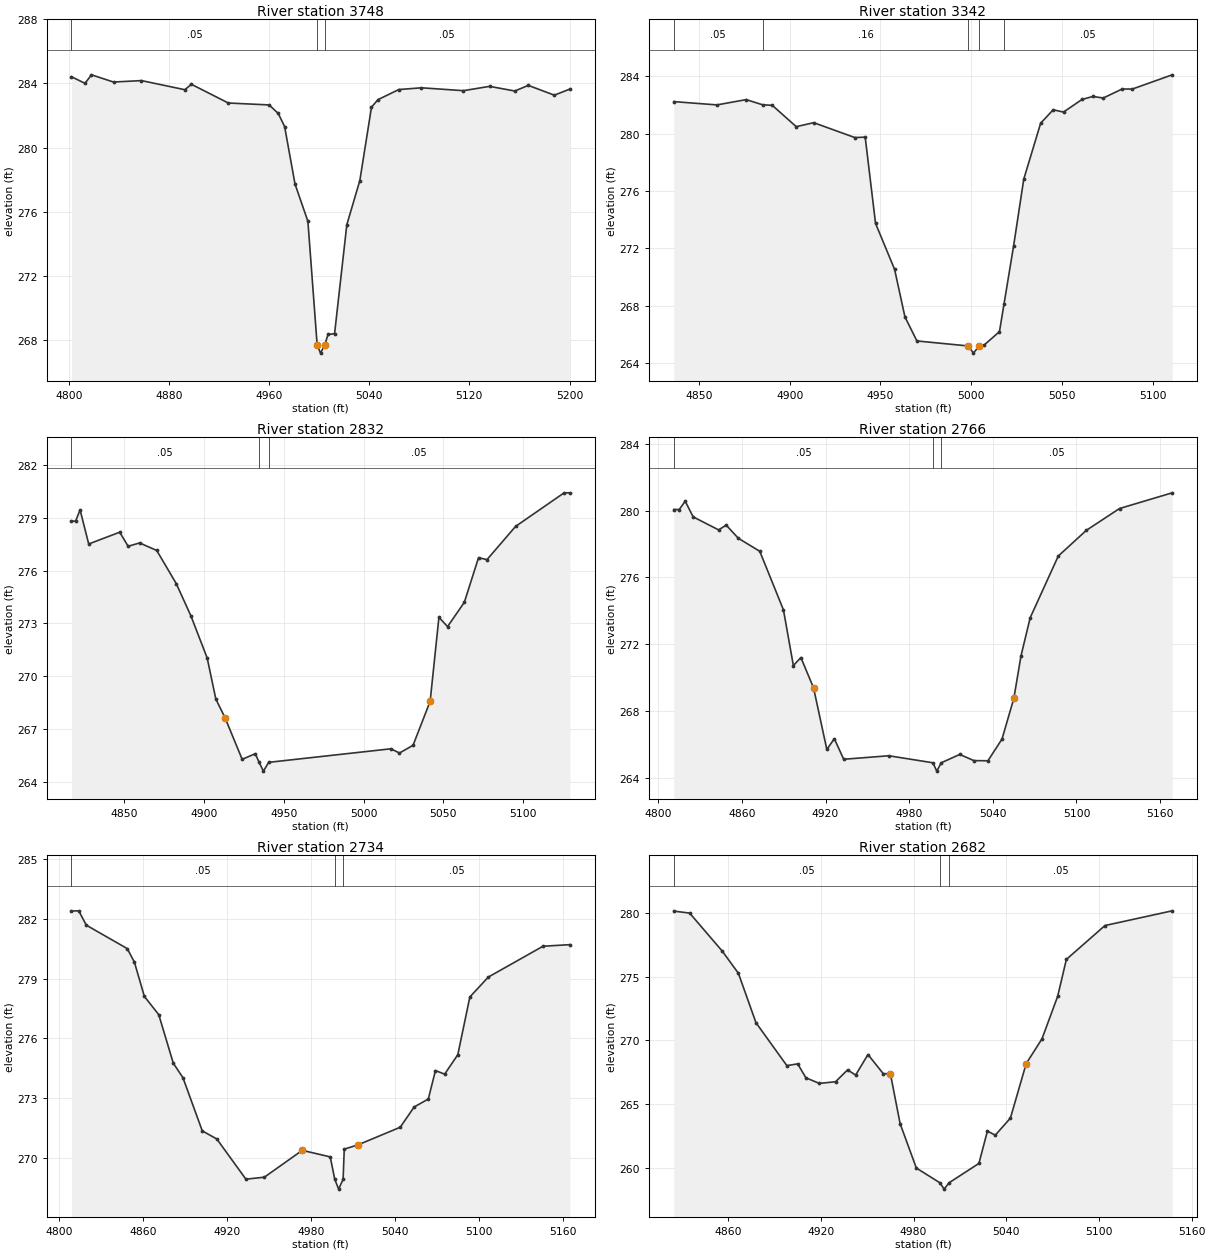
Type RM Length L Ch R = 1 ,3748    ,406,406,406
BEGIN DESCRIPTION:
UNT 163 IN BOCR 8.0
END DESCRIPTION:
XS GIS Cut Line= 2
      3709058.26     10620857.79      3708954.36      10621242.2
#Sta/Elev= 30
  4802.1  284.42  4812.9  284.01  4818.1  284.54  4835.7  284.09    4858  284.18
  4892.7  283.61  4897.9  283.95  4927.4  282.78    4960  282.66  4967.3  282.13
  4972.4  281.31  4980.7  277.72    4991  275.39  4998.4  267.66  5001.1  267.16
  5004.4  267.66  5007.1  268.33  5012.3  268.37  5022.1  275.18  5032.5  277.94
  5041.8  282.52    5047  282.99  5063.6  283.62  5081.7  283.73  5115.3  283.55
  5136.1  283.82  5156.3  283.53  5167.1  283.88  5187.9  283.27  5200.3  283.65
#Mann= 3 ,-1 , 0
  4802.1     .05       0  4998.4     .03       0  5004.4     .05       0
Bank Sta=4998.4,5004.4
XS Rating Curve= 0 ,0
Exp/Cntr=0.3,0.1

Type RM Length L Ch R = 1 ,3342    ,510,510,510
BEGIN DESCRIPTION:
UNT 163 IN BOCR 7.0
END DESCRIPTION:
XS GIS Cut Line= 2
      3708724.94     10620892.45      3708593.89     10621133.88
#Sta/Elev= 30
  4836.1  282.24  4859.9  282.01    4876  282.38    4885  282.02  4890.4  281.98
  4903.6  280.49  4913.2  280.77  4935.9  279.73  4941.6  279.76  4947.3  273.74
  4957.8  270.53  4963.5  267.21  4970.1  265.53  4998.5  265.18  5001.2  264.68
  5004.5  265.18  5007.2  265.25  5015.6  266.18  5018.1   268.1  5023.4  272.17
    5029  276.83  5038.3  280.73  5045.2  281.67  5050.9  281.51  5061.1  282.39
  5067.1   282.6  5072.8  282.49  5083.2  283.12  5088.9  283.12  5110.8  284.11
#Mann= 5 ,-1 , 0
  4836.1     .05       0    4885     .16       0  4998.5     .07       0
  5004.5     .16       0  5018.1     .05       0
Bank Sta=4998.5,5004.5
XS Rating Curve= 0 ,0
Exp/Cntr=0.3,0.1

Type RM Length L Ch R = 1 ,2832    ,66,66,66
BEGIN DESCRIPTION:
UNT 163 IN BOCR 6.0
END DESCRIPTION:
XS GIS Cut Line= 2
      3708266.59     10620670.27      3708155.49     10620961.92
#Sta/Elev= 30
  4817.1  278.81  4819.7  278.81  4822.5  279.45  4827.9  277.51  4847.3  278.18
  4852.6  277.38  4859.8  277.57  4870.5  277.14  4882.7  275.26  4891.9  273.42
  4902.1  271.02  4907.5  268.69  4913.3  267.62    4924  265.26  4932.2  265.58
  4934.6  265.09  4937.3  264.59  4940.6  265.09  5017.1  265.86  5022.5  265.62
    5031  266.06  5041.7  268.56  5047.2  273.34  5052.6  272.81  5063.1  274.19
    5072  276.73  5077.3  276.62  5095.2  278.51  5125.6  280.42  5129.2  280.42
#Mann= 3 ,-1 , 0
  4817.1     .05       0  4934.6     .03       0  4940.6     .05       0
Bank Sta=4913.3,5041.7
XS Rating Curve= 0 ,0
Exp/Cntr=0.3,0.1

Type RM Length L Ch R = 1 ,2766    ,32,32,32
BEGIN DESCRIPTION:
Mapping XS 43732615
END DESCRIPTION:
XS GIS Cut Line= 3
      3708207.57     10620637.31      3708146.81     10620786.61
      3708119.03     10620981.04
#Sta/Elev= 30
  4811.1  280.06    4815  280.06  4819.3  280.56    4825  279.62  4843.3  278.84
  4848.7  279.13  4857.4  278.34  4872.8  277.56  4889.8  274.05  4896.9  270.72
  4902.3   271.2  4911.4  269.38  4920.9   265.7  4926.3  266.34    4933  265.11
  4965.4  265.32    4997   264.9  4999.8   264.4    5003   264.9  5016.3   265.4
  5026.4  265.03  5036.5  265.02  5046.6  266.32  5055.1  268.76  5060.2  271.29
  5066.8  273.58    5087  277.28  5107.2  278.82  5130.9  280.12  5168.7  281.06
#Mann= 3 ,-1 , 0
  4811.1     .05       0    4997     .03       0    5003     .05       0
Bank Sta=4911.4,5055.1
XS Rating Curve= 0 ,0
Exp/Cntr=0.3,0.1

Type RM Length L Ch R = 1 ,2734    ,52,52,52
BEGIN DESCRIPTION:
Mapping XS 08780bfb
END DESCRIPTION:
XS GIS Cut Line= 4
      3708145.93     10620619.95      3708110.35     10620751.02
      3708114.69     10620877.75      3708077.37     10620963.68
#Sta/Elev= 30
  4808.8   282.4    4814  282.41  4819.4  281.69  4848.7  280.51  4853.8  279.83
  4860.9  278.11  4871.2  277.19  4881.6  274.75  4888.5  274.02  4902.3  271.35
  4912.7  270.94  4933.5  268.92  4946.7  269.02  4973.8  270.37  4993.8  270.04
    4997  268.92  4999.8  268.42    5003  268.92  5003.8  270.43  5013.8  270.65
  5043.8  271.53  5053.8  272.55  5063.9  272.95    5069  274.38  5075.6   274.2
    5085  275.18  5093.6  278.08  5106.8  279.08  5145.9  280.63  5165.1  280.71
#Mann= 3 ,-1 , 0
  4808.8     .05       0    4997     .03       0    5003     .05       0
Bank Sta=4973.8,5013.8
XS Rating Curve= 0 ,0
Exp/Cntr=0.3,0.1

Type RM Length L Ch R = 1 ,2682    ,252,252,252
BEGIN DESCRIPTION:
Mapping XS 822d343f
END DESCRIPTION:
XS GIS Cut Line= 3
      3708109.46      10620630.4      3708066.94     10620764.04
      3708031.35     10620942.89
#Sta/Elev= 30
  4824.8  280.12  4835.1  279.96  4856.1     277  4866.6  275.26    4878  271.39
    4898  268.03    4905  268.17  4910.3  267.08    4919  266.64  4929.5  266.77
  4937.3   267.7  4942.5  267.29  4950.5   268.9  4960.4   267.4    4965   267.4
  4971.3  263.49  4981.8  260.02    4997  258.87  4999.8  258.37    5003  258.87
  5022.3  260.38  5027.8  262.91  5032.9  262.59  5042.7  263.93  5052.9  268.19
  5063.1  270.12  5073.3  273.46  5078.9  276.34  5103.9  278.99  5147.4  280.14
#Mann= 3 ,-1 , 0
  4824.8     .05       0    4997     .03       0    5003     .05       0
Bank Sta=4965,5052.9
XS Rating Curve= 0 ,0
Exp/Cntr=0.3,0.1

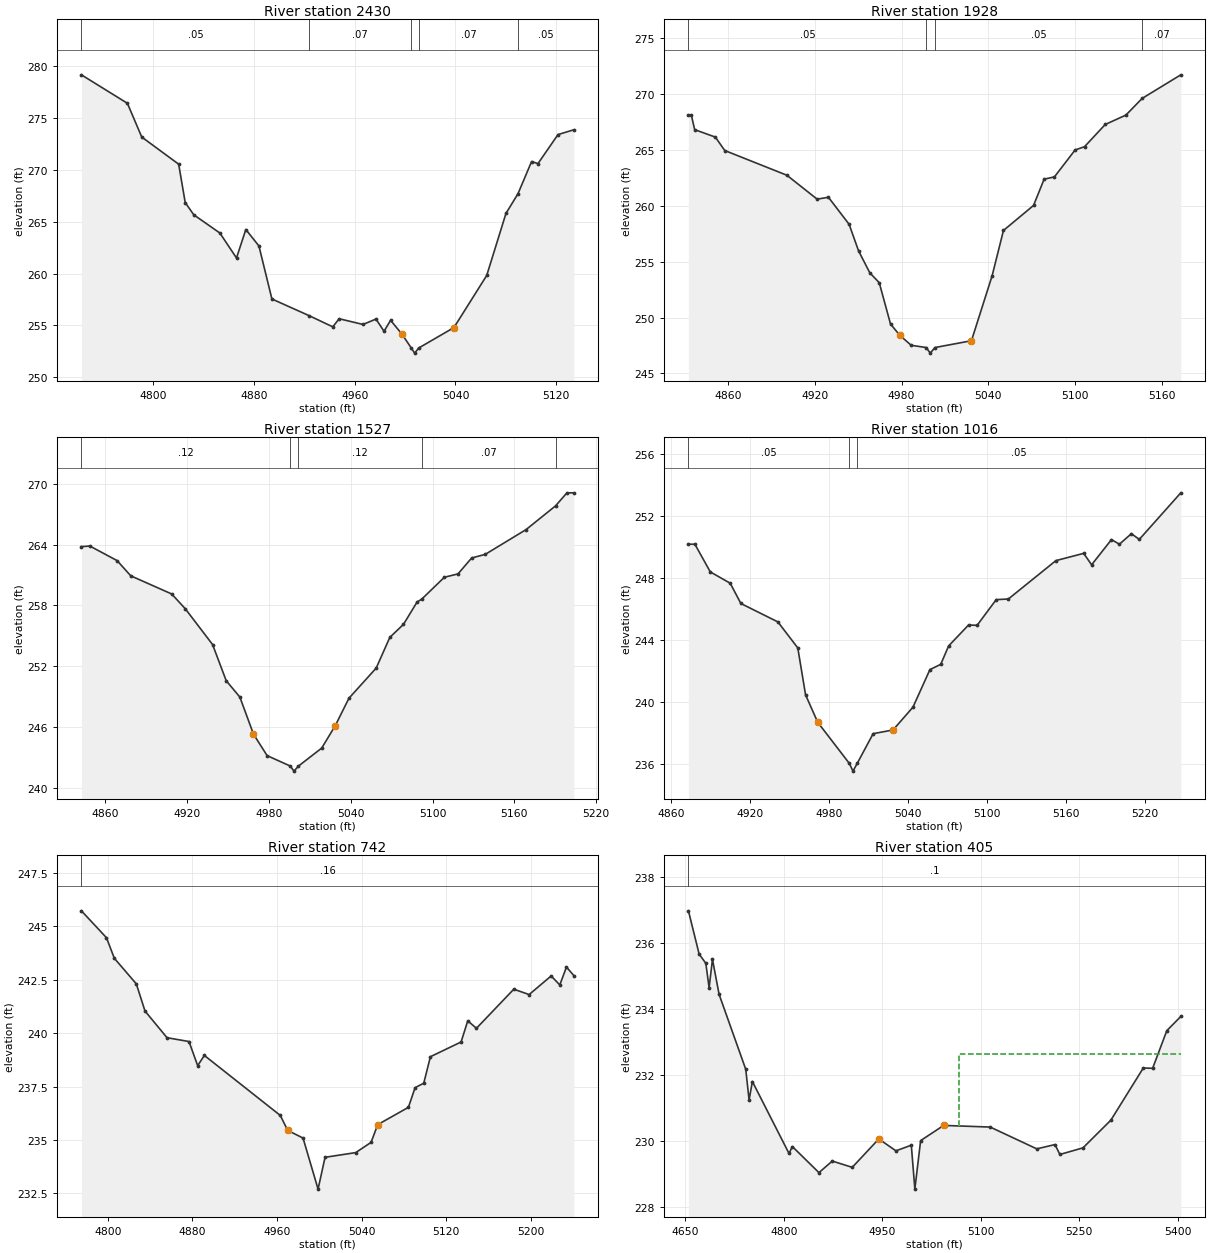
Type RM Length L Ch R = 1 ,2430    ,502,502,502
BEGIN DESCRIPTION:
UNT 163 IN BOCR 5.0
END DESCRIPTION:
XS GIS Cut Line= 2
      3708086.05     10620625.11      3707707.53     10620722.34
#Sta/Elev= 30
  4743.1  279.19  4779.6  276.44    4791  273.18  4820.3  270.56  4825.5  266.85
  4832.3  265.67    4853  263.91  4866.2   261.5  4873.6  264.25    4884  262.66
  4894.3  257.54    4924  255.92  4942.6  254.85  4947.7  255.63  4966.6  255.08
  4976.9   255.6  4983.3  254.42  4988.5  255.48  4997.5  254.15  5004.9  252.81
  5007.6  252.31  5010.9  252.81  5038.8  254.78  5064.8  259.81  5080.1  265.81
  5089.6   267.7  5100.4  270.81  5105.5  270.62  5121.4  273.42  5133.9  273.88
#Mann= 5 ,-1 , 0
  4743.1     .05       0    4924     .07       0  5004.9     .07       0
  5010.9     .07       0  5089.6     .05       0
Bank Sta=4997.5,5038.8
XS Rating Curve= 0 ,0
Exp/Cntr=0.3,0.1

Type RM Length L Ch R = 1 ,1928    ,401,401,401
BEGIN DESCRIPTION:
UNT 163 IN BOCR 4.0
END DESCRIPTION:
XS GIS Cut Line= 2
      3707957.54     10620132.09      3707738.79     10620392.51
#Sta/Elev= 30
  4832.8  268.11  4834.8  268.11  4837.1  266.81  4851.4  266.14  4857.9  264.94
  4900.8  262.73  4921.7  260.59  4929.5  260.76  4943.8  258.34  4950.3  255.97
  4958.1     254  4964.6  253.12  4972.4  249.42  4978.9   248.4  4986.7  247.52
  4997.1  247.32  4999.8  246.82  5003.1  247.32  5028.3  247.93  5042.6  253.75
  5050.4  257.79  5071.2  260.03  5078.5  262.38  5085.6  262.58  5099.9  264.99
  5106.4  265.28  5120.7  267.27    5135  268.11  5146.2   269.6  5172.9  271.71
#Mann= 4 ,-1 , 0
  4832.8     .05       0  4997.1     .03       0  5003.1     .05       0
  5146.2     .07       0
Bank Sta=4978.9,5028.3
XS Rating Curve= 0 ,0
Exp/Cntr=0.3,0.1

Type RM Length L Ch R = 1 ,1527    ,511,511,511
BEGIN DESCRIPTION:
UNT 163 IN BOCR 3.0
END DESCRIPTION:
XS GIS Cut Line= 2
      3707485.35     10620014.02      3707488.82     10620375.11
#Sta/Elev= 30
  4842.5   263.8  4848.7  263.86  4868.7  262.42  4878.7  260.92  4908.7  259.13
  4918.7  257.67  4938.7  254.14  4948.7  250.57  4958.7  248.96  4968.7   245.3
  4978.7  243.18  4995.7  242.15  4998.4  241.65  5001.7  242.15  5018.7  243.92
  5028.7  246.14  5038.7  248.84  5058.7  251.82  5068.7  254.85  5078.7  256.13
  5088.7  258.34  5092.1  258.62  5108.7  260.78  5118.7  261.11  5128.7  262.68
  5138.7  263.04  5168.7  265.49  5190.2  267.82  5198.6  269.11  5203.6  269.11
#Mann= 5 ,-1 , 0
  4842.5     .12       0  4995.7     .07       0  5001.7     .12       0
  5092.1     .07       0  5190.2     .05       0
Bank Sta=4968.7,5028.7
XS Rating Curve= 0 ,0
Exp/Cntr=0.3,0.1

Type RM Length L Ch R = 1 ,1016    ,274,274,274
BEGIN DESCRIPTION:
UNT 163 IN BOCR 2.0
END DESCRIPTION:
XS GIS Cut Line= 2
      3706978.41     10620086.92      3707183.29     10620399.45
#Sta/Elev= 30
  4873.4  250.18  4878.3  250.18    4890  248.39  4905.1  247.66  4913.2  246.35
  4941.3  245.16  4956.4  243.48  4962.3  240.45  4971.5  238.68  4995.5  236.02
  4998.3  235.52  5001.5  236.02  5013.6  237.94  5028.7  238.18  5043.8  239.65
  5056.7  242.08  5064.9  242.42  5070.9  243.61    5086  244.96  5092.5  244.94
    5107   246.6  5116.2  246.64  5152.3  249.12  5173.4  249.59  5179.4  248.85
  5194.5  250.48  5200.5  250.18  5209.6  250.86  5215.6  250.49  5247.1   253.5
#Mann= 3 ,-1 , 0
  4873.4     .05       0  4995.5     .03       0  5001.5     .05       0
Bank Sta=4971.5,5028.7
XS Rating Curve= 0 ,0
Exp/Cntr=0.3,0.1

Type RM Length L Ch R = 1 ,742     ,337,337,337
BEGIN DESCRIPTION:
Mapping XS 38690341
END DESCRIPTION:
XS GIS Cut Line= 2
      3706724.91     10620201.47      3707009.68     10620569.58
#Sta/Elev= 30
  4775.1  245.73  4798.8  244.47  4806.2  243.51    4827  242.31  4835.2  241.04
    4856  239.79  4876.8  239.61    4885  238.48  4891.3  238.96  4963.1  236.15
  4970.1  235.45  4984.6  235.09  4998.8   232.7  5005.4  234.19  5034.4  234.41
  5048.9  234.89  5055.2  235.72  5084.2  236.53  5090.5  237.45  5098.7  237.66
    5105   238.9    5134  239.59  5140.3  240.58  5148.5  240.23  5183.8  242.06
  5198.3  241.81  5219.1  242.68  5227.3  242.26  5233.6   243.1  5240.5   242.7
#Mann= 1 ,-1 , 0
  4775.1     .16       0
Bank Sta=4970.1,5055.2
XS Rating Curve= 0 ,0
Exp/Cntr=0.3,0.1

Type RM Length L Ch R = 1 ,405     ,306,306,306
BEGIN DESCRIPTION:
Mapping XS 5f913e62
END DESCRIPTION:
XS GIS Cut Line= 3
      3706589.42      10620274.1      3706641.51     10620586.59
      3706961.81     10620878.25
#Sta/Elev= 30
  4654.9  236.98  4671.2  235.67  4681.4  235.39  4686.4  234.65  4691.5  235.51
  4701.6  234.45  4742.2  232.18  4747.3  231.25  4752.3  231.81  4808.1  229.63
  4813.2  229.84  4853.7  229.05    4874   229.4  4904.4  229.21  4944.9  230.07
    4971  229.71  4994.4  229.88  4999.8  228.55  5008.6  230.02  5043.7  230.48
  5114.6  230.43  5185.5  229.77  5213.3   229.9  5220.7   229.6  5255.9   229.8
  5298.4  230.64  5347.8  232.22    5362  232.21  5383.6  233.35  5404.9  233.78
#Mann= 1 ,-1 , 0
  4654.9      .1       0
#XS Ineff= 2 , 0
                         5067.14          232.64
Permanent Ineff=
       F       F
Bank Sta=4944.9,5043.7
XS Rating Curve= 0 ,0
Exp/Cntr=0.3,0.1

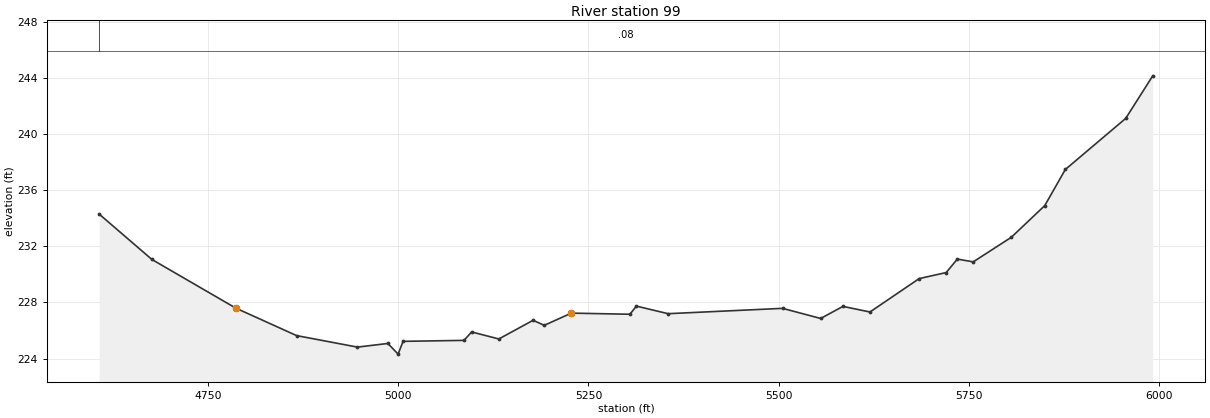
Type RM Length L Ch R = 1 ,99      ,0,0,0
BEGIN DESCRIPTION:
UNT 163 IN BOCR 1.0
END DESCRIPTION:
XS GIS Cut Line= 3
       3706388.9     10620130.88      3706401.92      10620656.9
      3707093.16     10621166.23
#Sta/Elev= 30
  4606.9  234.29  4676.2  231.06  4786.3   227.6  4866.3  225.64  4946.3  224.82
  4986.3  225.08  4999.8  224.32  5006.3  225.23  5086.4   225.3  5096.4   225.9
  5132.2   225.4  5177.2  226.73  5191.9  226.37  5227.4  227.24  5304.5  227.16
    5313  227.74  5354.7   227.2  5505.1  227.58  5555.2  226.86  5584.5  227.72
    5620  227.32  5684.7   229.7  5720.2  230.13  5734.9  231.09  5755.7  230.89
  5805.8  232.64  5849.8   234.9  5876.8  237.47  5956.2  241.11  5991.7  244.14
#Mann= 1 ,-1 , 0
  4606.9     .08       0
Bank Sta=4786.3,5227.4
XS Rating Curve= 0 ,0
Exp/Cntr=0.3,0.1

Chan Stop Cuts=-1
Use User Specified Reach Order=0
Composite Channel Slope=5