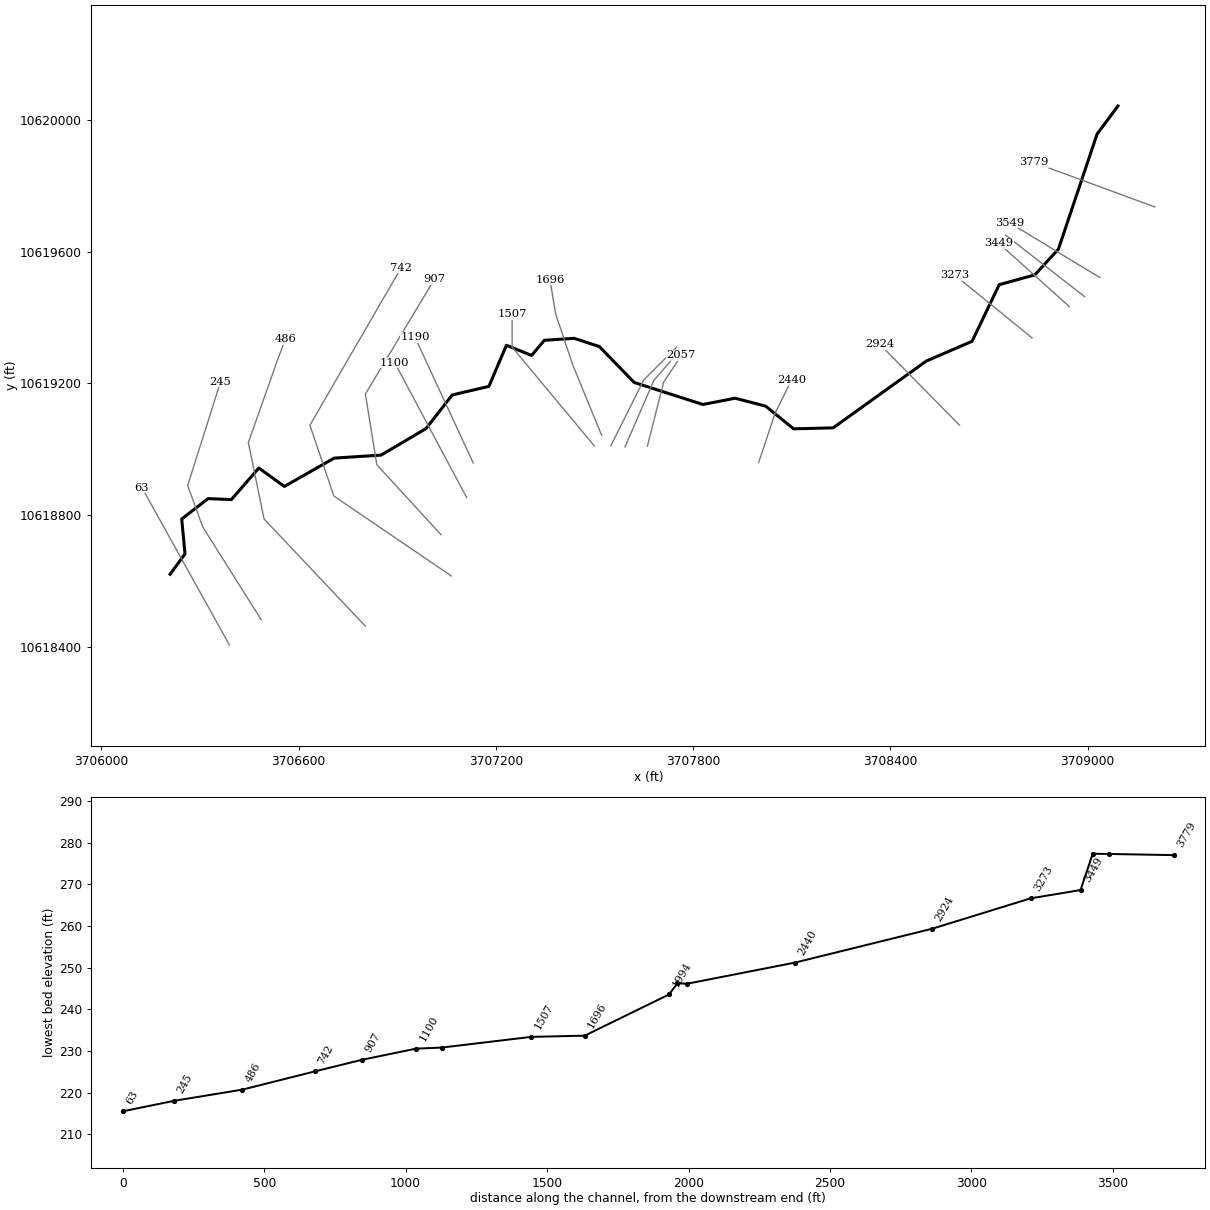
--- UNT 164 IN BOCR.prj (project) ---

Proj Title=UNT 164 IN BOCR Base Level Engineering
Current Plan=p01
Default Exp/Contr=0.3,0.1
English Units
Geom File=g01
Flow File=f01
Plan File=p01
Y Axis Title=Elevation
X Axis Title(PF)=Main Channel Distance
X Axis Title(XS)=Station
BEGIN DESCRIPTION:
UNT 164 IN BOCR
END DESCRIPTION:
DSS Export Rating Curves= 0
DSS Export Rating Curve Sorted= 0
DSS Export Volume Flow Curves= 0
DXF OffsetX= 0
DXF OffsetY= 0
DXF ScaleX= 1
DXF ScaleY= 10

--- UNT 164 IN BOCR.p01 (plan) ---

Plan Title=Multiple Run
Short Identifier=Multiple
Geom File=g01
Flow File=f01
Subcritical Flow
K Sum by GR= 0
Std Step Tol= 0.01
Critical Tol= 0.01
Num of Std Step Trials= 20
Max Error Tol= 0.3
Flow Tol Ratio= 0.001
Split Flow NTrial= 30
Split Flow Tol= 0.02
Split Flow Ratio= 0.02
Log Output Level= 0
Friction Slope Method= 1
Unsteady Friction Slope Method= 2
Unsteady Bridges Friction Slope Method= 1
Parabolic Critical Depth
Global Vel Dist=  1 , 1 , 1
Global Log Level= 0
CheckData=True
Encroach Param= -1, 0, 0, 0
BEGIN DESCRIPTION:
Multiple Run
END DESCRIPTION:

--- UNT 164 IN BOCR.f01 (steady flow) ---

Flow Title=Multiple
Number of Profiles=7
Profile Names=10-year,25-year,50-year,1pct_min,100-year,1pct_plu,500-year
River Rch & RM= UNT 164 IN BOCR,Reach-1,3779
     118     143     161     135     182     247     233
Boundary for River Rch & Prof#=UNT 164 IN BOCR,Reach-1,1
Up Type=0
Dn Type=3
Dn Slope=0.005
Boundary for River Rch & Prof#=UNT 164 IN BOCR,Reach-1,2
Up Type=0
Dn Type=3
Dn Slope=0.005
Boundary for River Rch & Prof#=UNT 164 IN BOCR,Reach-1,3
Up Type=0
Dn Type=3
Dn Slope=0.005
Boundary for River Rch & Prof#=UNT 164 IN BOCR,Reach-1,4
Up Type=0
Dn Type=3
Dn Slope=0.005
Boundary for River Rch & Prof#=UNT 164 IN BOCR,Reach-1,5
Up Type=0
Dn Type=3
Dn Slope=0.005
Boundary for River Rch & Prof#=UNT 164 IN BOCR,Reach-1,6
Up Type=0
Dn Type=3
Dn Slope=0.005
Boundary for River Rch & Prof#=UNT 164 IN BOCR,Reach-1,7
Up Type=0
Dn Type=3
Dn Slope=0.005

--- UNT 164 IN BOCR.g01 (geometry) ---

Geom Title=Existing Conditions
Program Version=4.10

River Reach=UNT 164 IN BOCR ,Reach-1
Reach XY= 30
      3709092.22     10620043.21      3709028.77     10619957.94
        3708911.       10619608.       3708839.5       10619530.
        3708731.       10619500.       3708648.5       10619328.
      3708509.25       10619268.        3708226.       10619065.
      3708105.75       10619062.      3708020.75       10619131.
      3707927.75       10619155.      3707829.75       10619136.
      3707620.75       10619203.        3707515.       10619312.
       3707438.5       10619337.      3707347.75       10619331.
      3707308.75       10619285.      3707232.25       10619316.
        3707179.       10619191.       3707067.5       10619165.
        3706988.       10619063.      3706851.14     10618982.16
      3706708.51     10618973.07        3706557.       10618887.
      3706479.25       10618943.      3706395.75       10618847.
      3706324.75       10618850.      3706244.75       10618788.
      3706254.75       10618682.       3706209.5       10618620.

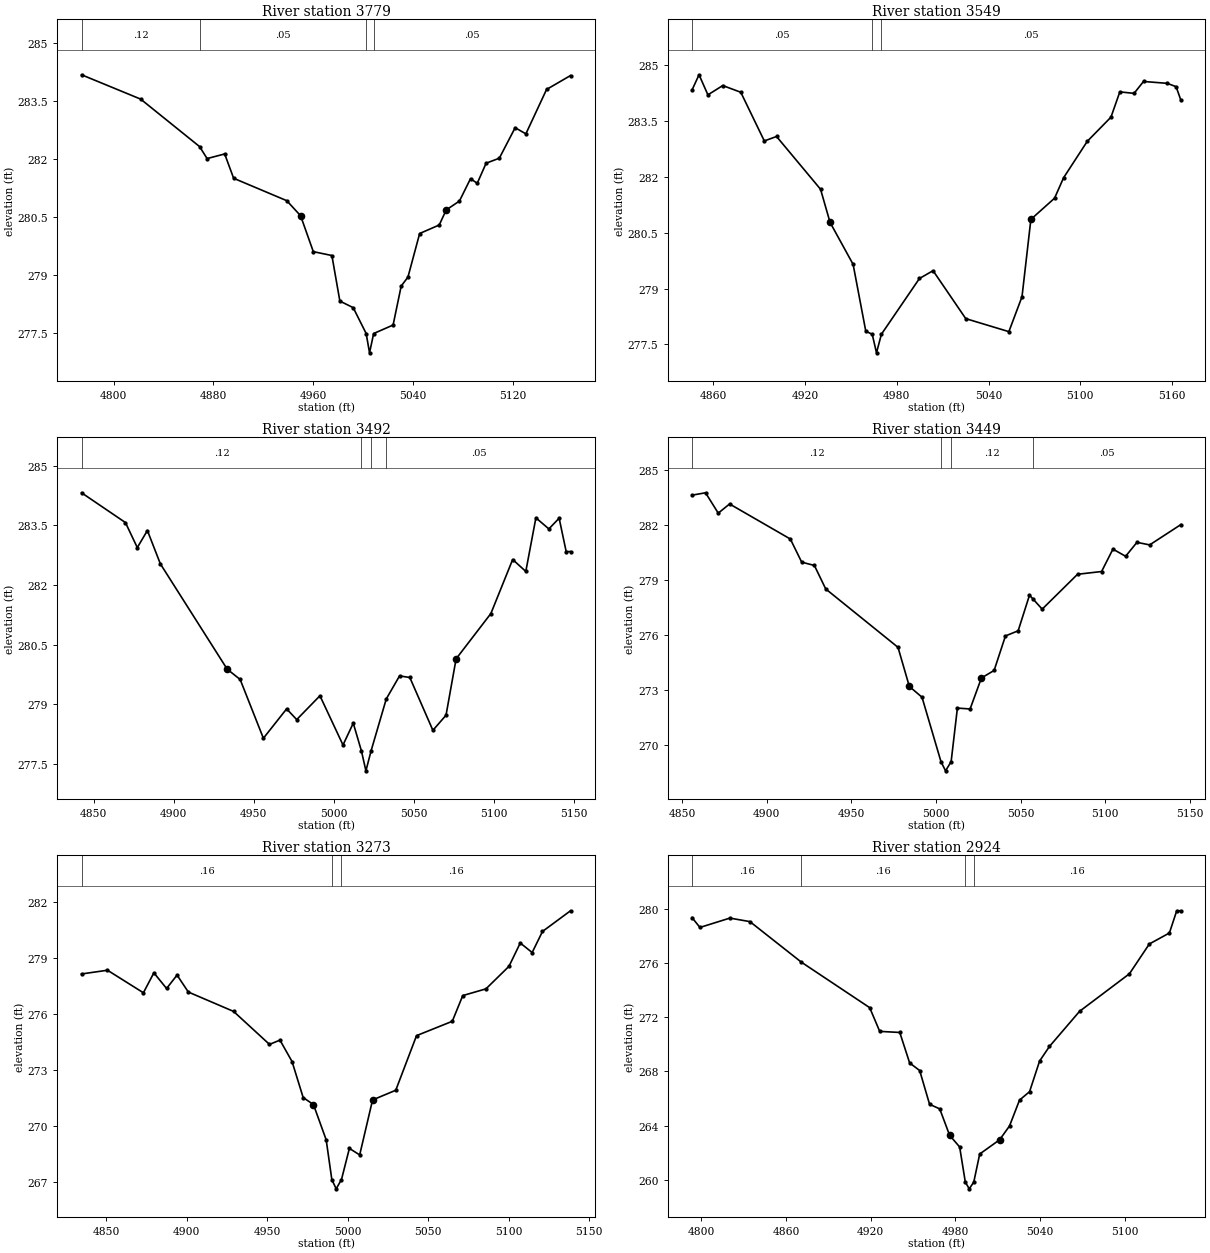
Type RM Length L Ch R = 1 ,3779    ,230,230,230
BEGIN DESCRIPTION:
UNT 164 IN BOCR 7.0
END DESCRIPTION:
XS GIS Cut Line= 2
      3709204.11     10619736.22      3708836.03     10619871.64
#Sta/Elev= 30
  4774.2  284.19  4821.6  283.56  4868.9  282.33  4874.9  282.02    4889  282.14
  4896.2  281.51  4938.8  280.93  4949.9  280.54  4960.1  279.61    4975  279.51
  4981.4  278.33  4992.1  278.16  5002.5  277.49  5005.2  276.99  5008.5  277.49
  5024.1  277.71  5030.6  278.72    5036  278.95  5045.4  280.08  5061.1   280.3
  5066.7  280.69  5077.3  280.92  5086.2   281.5  5091.6  281.38  5098.7   281.9
  5109.3  282.03    5122  282.82  5130.6  282.66  5147.2  283.81  5166.4  284.17
#Mann= 4 ,-1 , 0
  4774.2     .12       0  4868.9     .05       0  5002.5     .03       0
  5008.5     .05       0
Bank Sta=4949.9,5066.7
XS Rating Curve= 0 ,0
Exp/Cntr=0.3,0.1

Type RM Length L Ch R = 1 ,3549    ,57,57,57
BEGIN DESCRIPTION:
Mapping XS 28f5e619
END DESCRIPTION:
XS GIS Cut Line= 2
      3709036.86     10619521.79      3708763.35     10619687.71
#Sta/Elev= 30
    4846  284.34  4850.6  284.75  4856.4  284.21  4866.1  284.46  4877.9  284.28
  4893.3  282.97  4901.3  283.09  4930.1  281.67  4936.3  280.78  4951.4  279.65
  4959.7  277.85  4963.9  277.77  4966.7  277.27  4969.9  277.77  4994.8  279.27
  5003.7  279.48  5025.1  278.19  5053.3  277.84  5061.9  278.78  5067.7  280.86
  5083.2  281.43  5089.1  281.98  5104.6  282.96  5120.1  283.61  5125.9  284.29
  5135.2  284.25  5141.4  284.57  5156.9  284.52  5162.7  284.43  5165.9  284.06
#Mann= 3 ,-1 , 0
    4846     .05       0  4963.9     .03       0  4969.9     .05       0
Bank Sta=4936.3,5067.7
XS Rating Curve= 0 ,0
Exp/Cntr=0.3,0.1

Type RM Length L Ch R = 1 ,3492    ,43,43,43
BEGIN DESCRIPTION:
Mapping XS e2828e7b
END DESCRIPTION:
XS GIS Cut Line= 2
      3708991.25     10619463.22      3708750.41     10619650.68
#Sta/Elev= 30
  4842.5  284.32  4869.9  283.57  4877.3  282.94  4883.6  283.37  4891.7  282.53
  4933.4  279.88  4941.5  279.62    4956  278.14  4970.5  278.88  4976.8  278.61
  4991.3  279.21  5005.7  277.97  5012.1  278.52  5017.2  277.82    5020  277.32
  5023.2  277.82  5032.7  279.13    5041  279.71  5047.4  279.67  5061.8  278.34
    5070  278.72  5076.3  280.14    5098  281.28  5111.6  282.64  5119.8  282.34
  5126.1  283.69  5134.2  283.41  5140.6  283.68    5145  282.84  5147.7  282.84
#Mann= 4 ,-1 , 0
  4842.5     .12       0  5017.2     .07       0  5023.2     .12       0
  5032.7     .05       0
Bank Sta=4933.4,5076.3
XS Rating Curve= 0 ,0
Exp/Cntr=0.3,0.1

Type RM Length L Ch R = 1 ,3449    ,176,176,176
BEGIN DESCRIPTION:
Mapping XS a2c34d68
END DESCRIPTION:
XS GIS Cut Line= 2
      3708944.39     10619433.26       3708729.4     10619626.24
#Sta/Elev= 30
  4855.9  283.63  4863.9  283.76  4871.4  282.65  4878.1  283.15    4914  281.24
  4920.7  279.98  4928.2   279.8  4934.9  278.52  4977.6  275.34  4984.3  273.21
  4991.8  272.62    5003  269.11  5005.7  268.61    5009  269.11  5012.7  272.03
  5020.2  271.98  5026.9  273.67  5034.4  274.08  5041.1  275.96  5048.6  276.24
  5055.3  278.18  5057.2  277.99  5062.8  277.42  5083.7  279.32  5097.9  279.47
  5104.6  280.69  5112.1   280.3  5118.8  281.06  5126.3  280.92  5144.8  282.03
#Mann= 4 ,-1 , 0
  4855.9     .12       0    5003     .07       0    5009     .12       0
  5057.2     .05       0
Bank Sta=4984.3,5026.9
XS Rating Curve= 0 ,0
Exp/Cntr=0.3,0.1

Type RM Length L Ch R = 1 ,3273    ,349,349,349
BEGIN DESCRIPTION:
UNT 164 IN BOCR 6.0
END DESCRIPTION:
XS GIS Cut Line= 2
      3708831.09     10619338.22      3708595.43     10619529.62
#Sta/Elev= 30
  4834.8  278.16  4850.9  278.36  4873.2  277.15  4879.7  278.22  4887.6  277.38
  4894.1   278.1  4901.1  277.19  4929.2  276.15  4951.5  274.38    4958  274.61
  4965.5  273.46  4972.4  271.53  4978.8  271.15  4986.7  269.26  4990.2  267.13
  4992.9  266.63  4996.2  267.13  5001.1   268.8  5007.5  268.45  5015.5   271.4
  5029.9  271.92  5042.8  274.85    5065  275.62  5071.5     277  5085.9  277.36
  5100.2  278.57  5107.2  279.82  5114.6  279.31    5121  280.44  5138.4  281.55
#Mann= 3 ,-1 , 0
  4834.8     .16       0  4990.2     .16       0  4996.2     .16       0
Bank Sta=4978.8,5015.5
XS Rating Curve= 0 ,0
Exp/Cntr=0.3,0.1

Type RM Length L Ch R = 1 ,2924    ,484,484,484
BEGIN DESCRIPTION:
UNT 164 IN BOCR 5.0
END DESCRIPTION:
XS GIS Cut Line= 2
      3708610.38       10619073.      3708367.32     10619319.53
#Sta/Elev= 30
  4793.5  279.35  4799.1  278.62  4820.3  279.31  4834.5  279.05  4870.9  276.06
  4919.3   272.7  4926.4  270.95  4940.6  270.87  4947.6  268.62  4954.7  268.06
  4961.7  265.57  4968.9  265.23  4975.9  263.28    4983  262.42    4987  259.83
  4989.8  259.33    4993  259.83  4997.2   261.9  5011.3  262.95  5018.3  263.97
  5025.4  265.88  5032.5   266.5  5039.6  268.76  5046.6  269.84  5067.9  272.43
  5103.2   275.2  5117.3   277.4  5131.5  278.21  5136.7  279.85  5139.7  279.85
#Mann= 4 ,-1 , 0
  4793.5     .16       0  4870.9     .16       0    4987     .16       0
    4993     .16       0
Bank Sta=4975.9,5011.3
XS Rating Curve= 0 ,0
Exp/Cntr=0.3,0.1

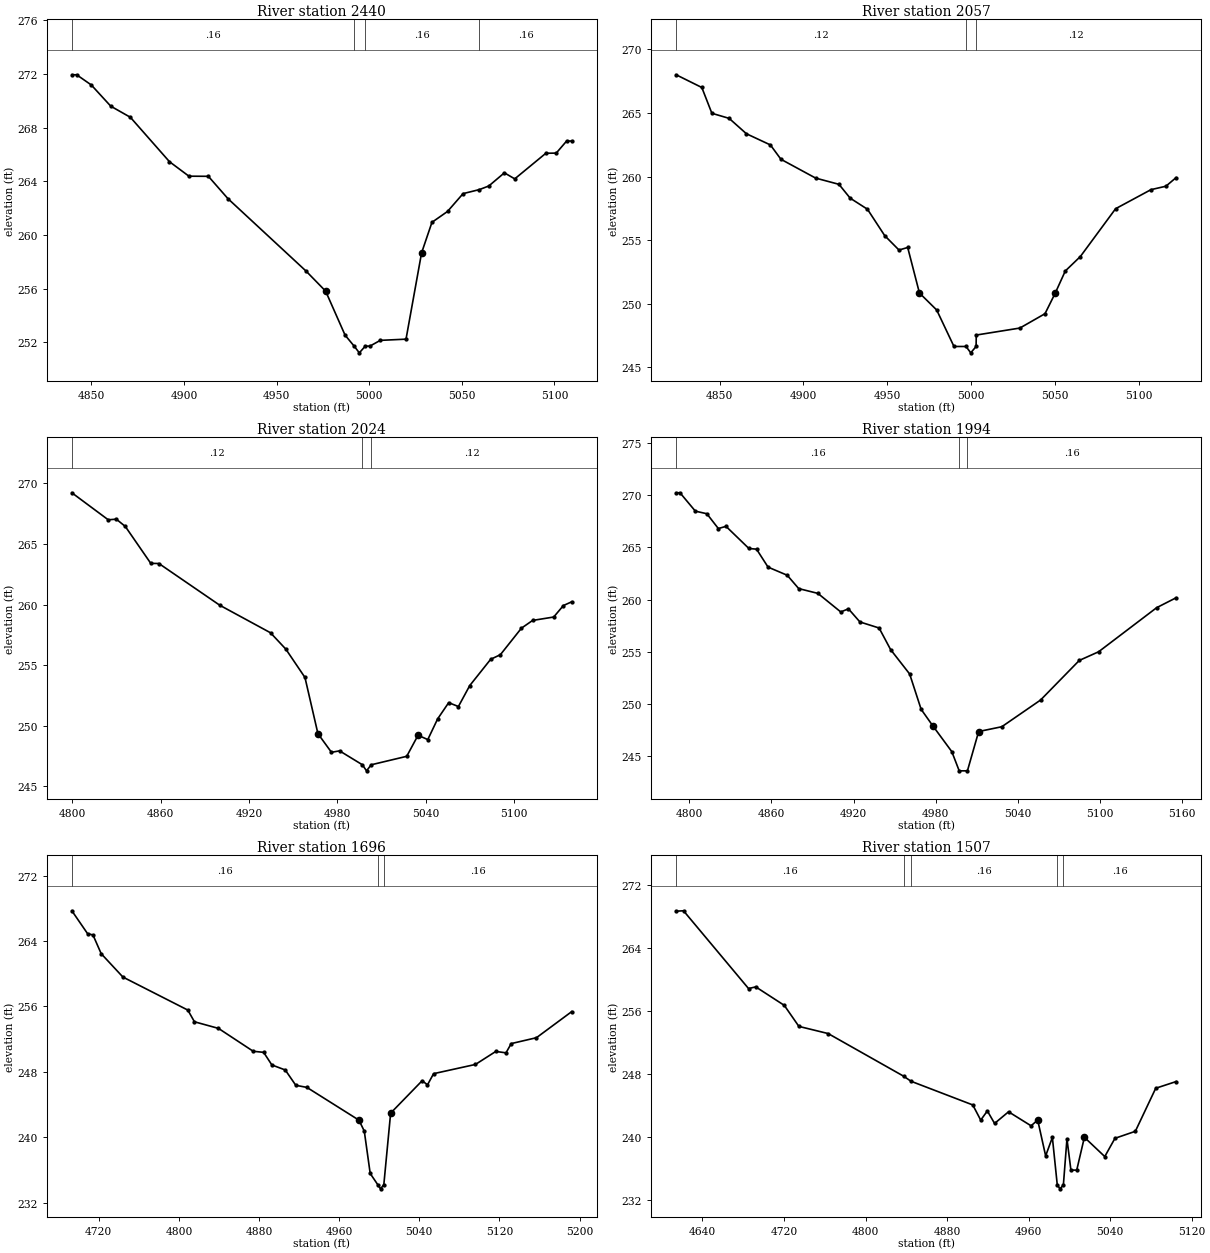
Type RM Length L Ch R = 1 ,2440    ,383,383,383
BEGIN DESCRIPTION:
UNT 164 IN BOCR 4.0
END DESCRIPTION:
XS GIS Cut Line= 3
      3707999.62     10618960.23      3708049.61     10619110.19
      3708099.62     10619210.22
#Sta/Elev= 30
  4839.5  271.95  4842.1  271.95    4850  271.19  4860.5  269.61  4871.1  268.78
  4892.2  265.47  4902.7  264.39  4913.2  264.38  4923.8  262.71  4965.9  257.32
  4976.5  255.82    4987  252.54  4991.9  251.72  4994.7  251.22  4997.9  251.72
  5000.4  251.72    5006  252.15  5019.9  252.24  5028.3  258.67  5033.9  260.95
  5042.3  261.76  5050.7  263.09  5059.5  263.39  5064.6  263.66    5073  264.64
  5078.6  264.19  5095.4   266.1    5101  266.11  5106.6  267.01  5109.4  267.01
#Mann= 4 ,-1 , 0
  4839.5     .16       0  4991.9     .16       0  4997.9     .16       0
  5059.5     .16       0
Bank Sta=4976.5,5028.3
XS Rating Curve= 0 ,0
Exp/Cntr=0.3,0.1

Type RM Length L Ch R = 1 ,2057    ,33,33,33
BEGIN DESCRIPTION:
Mapping XS 2aaf050b
END DESCRIPTION:
XS GIS Cut Line= 3
      3707661.02     10619009.59      3707710.49       10619204.
      3707764.53     10619285.27
#Sta/Elev= 30
  4824.1  268.01  4839.4  267.01  4845.4  264.98  4855.7  264.58    4866  263.37
  4880.3  262.49  4886.6  261.36  4907.3  259.88  4921.2  259.39  4927.9   258.3
  4938.2  257.43  4948.5  255.35    4957  254.22  4962.2  254.42  4969.2  250.84
  4979.5   249.5  4989.8  246.63    4997  246.63  4999.8  246.13    5003  246.63
  5003.1  247.53  5029.1  248.08  5044.1  249.21  5050.2  250.83  5056.2  252.57
  5065.2  253.71  5086.2  257.47  5107.3  258.97  5116.2  259.24  5122.3  259.92
#Mann= 3 ,-1 , 0
  4824.1     .12       0    4997     .07       0    5003     .12       0
Bank Sta=4969.2,5050.2
XS Rating Curve= 0 ,0
Exp/Cntr=0.3,0.1

Type RM Length L Ch R = 1 ,2024    ,30,30,30
BEGIN DESCRIPTION:
Mapping XS 9185e169
END DESCRIPTION:
XS GIS Cut Line= 3
      3707592.86     10619006.92      3707680.54     10619208.77
       3707758.7     10619299.08
#Sta/Elev= 30
  4799.7  269.23  4824.4     267  4829.9  267.05    4836  266.45  4853.3   263.4
  4858.8  263.39  4900.2  259.94  4934.6  257.67    4945  256.32    4958  253.98
  4966.8  249.34    4976   247.8  4981.5  247.92    4997  246.77  4999.8  246.27
    5003  246.77  5027.1  247.47  5034.8  249.21  5041.4  248.85  5048.1  250.56
  5055.6   251.9  5062.2  251.58  5069.9  253.31  5084.1  255.48  5090.7  255.86
    5105  258.05  5112.6  258.69  5126.9  258.97  5133.5  259.92  5139.2  260.23
#Mann= 3 ,-1 , 0
  4799.7     .12       0    4997     .07       0    5003     .12       0
Bank Sta=4966.8,5034.8
XS Rating Curve= 0 ,0
Exp/Cntr=0.3,0.1

Type RM Length L Ch R = 1 ,1994    ,298,298,298
BEGIN DESCRIPTION:
UNT 164 IN BOCR 3.0
END DESCRIPTION:
XS GIS Cut Line= 3
      3707549.59     10619010.15      3707649.61     10619210.19
      3707749.63     10619310.21
#Sta/Elev= 30
  4790.4  270.24  4793.2  270.24  4804.4  268.48  4812.8  268.23  4821.2  266.81
  4826.8  267.02  4843.5   264.9  4849.1  264.83  4857.5  263.11  4871.5  262.33
  4879.9  261.05  4893.9  260.59  4910.6  258.81  4916.2  259.11  4924.6  257.85
  4938.6  257.27    4947   255.2  4960.9  252.86  4969.3  249.47  4977.7  247.91
  4991.7  245.41  4997.1  243.57  5003.1  243.57  5011.3  247.34  5028.2   247.8
  5056.5  250.36  5084.8  254.16  5098.9  254.99  5141.3  259.22  5155.5  260.17
#Mann= 3 ,-1 , 0
  4790.4     .16       0  4997.1     .16       0  5003.1     .16       0
Bank Sta=4977.7,5011.3
XS Rating Curve= 0 ,0
Exp/Cntr=0.3,0.1

Type RM Length L Ch R = 1 ,1696    ,189,189,189
BEGIN DESCRIPTION:
Mapping XS 3cae9161
END DESCRIPTION:
XS GIS Cut Line= 4
      3707521.57     10619043.05      3707434.35     10619255.25
      3707382.27     10619410.19      3707364.58     10619515.02
#Sta/Elev= 30
  4693.1  267.71  4708.8  264.91  4714.2  264.75  4722.4  262.46  4744.1   259.6
  4808.9  255.56  4815.5  254.13  4839.5  253.32  4874.2  250.52  4884.6  250.39
  4892.8  248.85  4906.2  248.23  4916.7  246.36  4927.8   246.1  4979.8  242.09
  4985.1  240.75    4991  235.57  4998.6  234.19  5001.3  233.69  5004.6  234.19
  5011.4  242.95  5042.9  246.92  5048.2  246.41  5054.3  247.78  5096.1  248.91
  5116.4   250.5  5126.6  250.33  5131.8  251.46    5157  252.18  5192.3  255.38
#Mann= 3 ,-1 , 0
  4693.1     .16       0  4998.6     .16       0  5004.6     .16       0
Bank Sta=4979.8,5011.4
XS Rating Curve= 0 ,0
Exp/Cntr=0.3,0.1

Type RM Length L Ch R = 1 ,1507    ,317,317,317
BEGIN DESCRIPTION:
UNT 164 IN BOCR 2.0
END DESCRIPTION:
XS GIS Cut Line= 3
      3707499.62     10619010.17      3707249.61     10619310.19
      3707249.61     10619410.16
#Sta/Elev= 30
  4614.2  268.68  4621.4  268.73  4685.2  258.85  4692.3  259.06  4720.3  256.71
  4734.6  254.04  4763.3  253.13  4837.4  247.71  4844.6  247.07  4905.2  244.06
    4913  242.13  4919.5   243.3  4926.6  241.71  4940.3  243.19  4962.4  241.41
  4968.9  242.14  4976.7  237.59  4983.3  239.93  4988.1   233.9  4990.8   233.4
  4994.1   233.9  4997.6  239.74  5001.5  235.78  5007.2  235.78  5014.7  239.95
  5034.7   237.5  5044.7  239.82  5064.7  240.71  5084.7  246.18  5104.7  247.03
#Mann= 5 ,-1 , 0
  4614.2     .16       0  4837.4     .16       0  4844.6     .16       0
  4988.1     .16       0  4994.1     .16       0
Bank Sta=4968.9,5014.7
XS Rating Curve= 0 ,0
Exp/Cntr=0.3,0.1

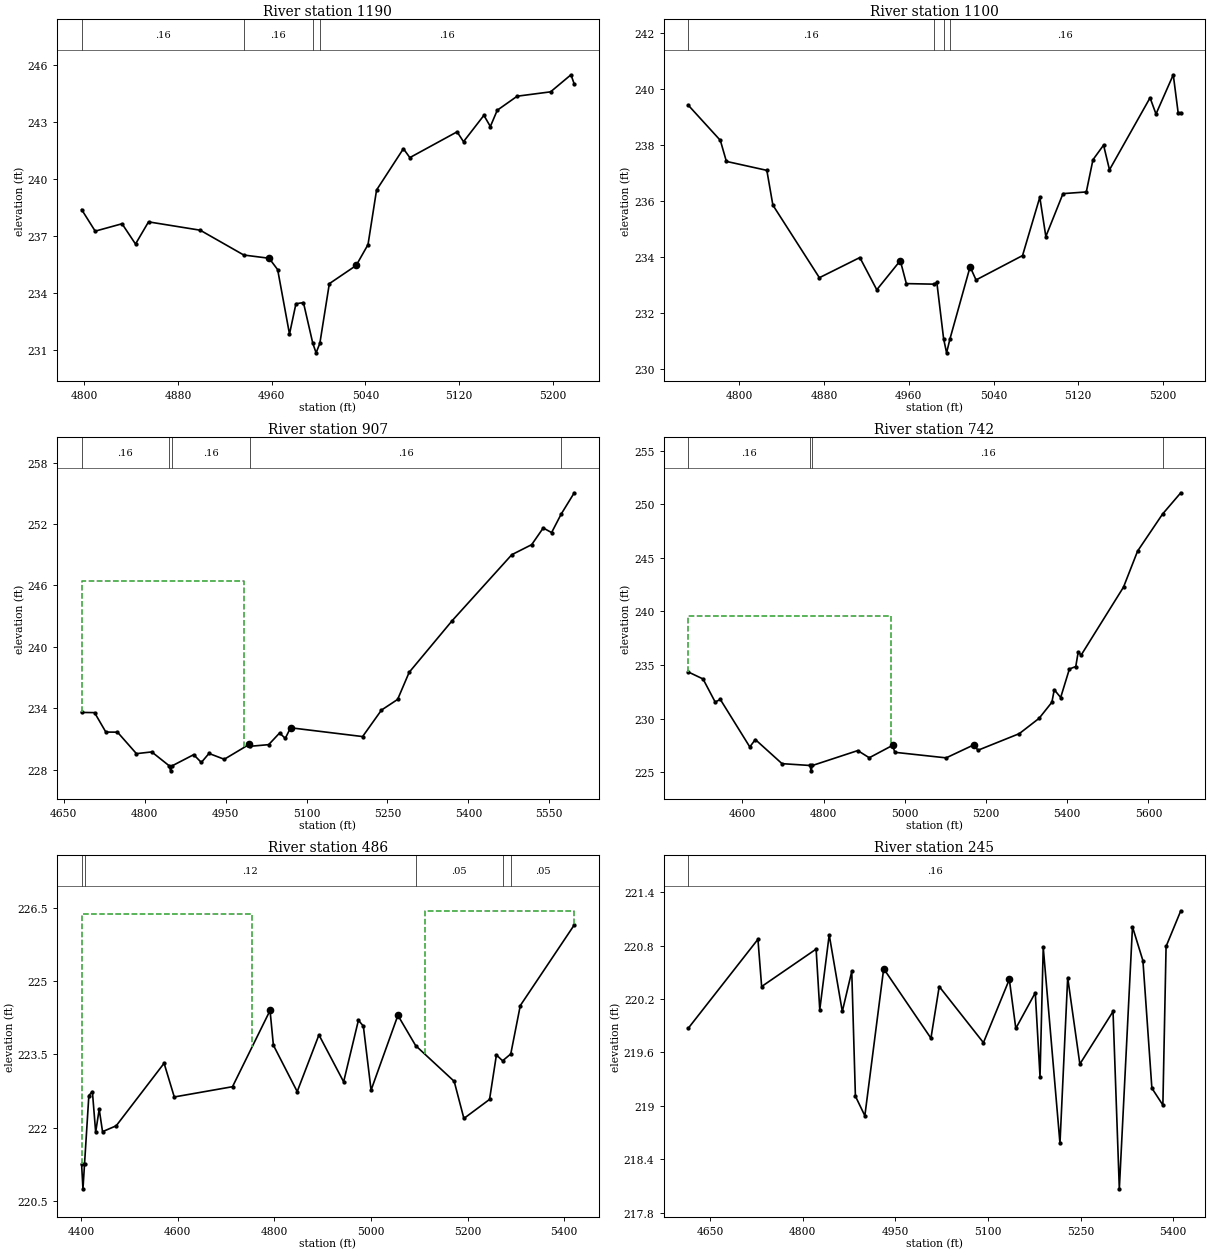
Type RM Length L Ch R = 1 ,1190    ,90,90,90
BEGIN DESCRIPTION:
Mapping XS 4f0a06c0
END DESCRIPTION:
XS GIS Cut Line= 2
      3707131.19     10618958.42      3706954.36     10619339.82
#Sta/Elev= 30
  4797.8  238.39  4809.4  237.25  4832.3  237.64  4843.8  236.57  4854.9  237.74
    4899   237.3  4936.2  235.99  4957.8  235.82  4965.1  235.22  4975.2  231.82
  4980.7  233.42  4987.1  233.48  4995.1  231.33  4997.9  230.83  5001.1  231.33
  5009.2  234.48  5032.1  235.44  5042.2  236.54  5049.5  239.42  5072.4   241.6
  5077.9  241.13  5118.2  242.49  5123.7  241.97  5141.1  243.36  5146.6  242.77
  5152.5  243.63  5169.5  244.37    5198   244.6  5215.4   245.5  5218.2  245.01
#Mann= 4 ,-1 , 0
  4797.8     .16       0  4936.2     .16       0  4995.1     .16       0
  5001.1     .16       0
Bank Sta=4957.8,5032.1
XS Rating Curve= 0 ,0
Exp/Cntr=0.3,0.1

Type RM Length L Ch R = 1 ,1100    ,193,193,193
BEGIN DESCRIPTION:
Mapping XS 4f3d487a
END DESCRIPTION:
XS GIS Cut Line= 2
      3707111.49     10618853.13      3706892.28     10619263.33
#Sta/Elev= 30
  4751.7  239.42  4782.1  238.16  4787.8  237.41    4826  237.09  4831.7  235.85
  4875.6  233.26  4913.8  233.98  4929.8  232.83    4952  233.87  4957.7  233.05
  4983.8  233.03  4986.5  233.09  4992.9  231.08  4995.7  230.58  4998.9  231.08
  5017.9  233.65  5023.5  233.18  5067.4  234.05  5083.7  236.13  5089.4  234.73
  5105.6  236.26  5127.6  236.32  5133.9  237.47  5143.9  237.99  5149.5  237.11
  5187.8  239.68  5193.4   239.1  5209.7   240.5  5214.3  239.15  5216.8  239.15
#Mann= 4 ,-1 , 0
  4751.7     .16       0  4983.8     .16       0  4992.9     .16       0
  4998.9     .16       0
Bank Sta=4952,5017.9
XS Rating Curve= 0 ,0
Exp/Cntr=0.3,0.1

Type RM Length L Ch R = 1 ,907     ,165,165,165
BEGIN DESCRIPTION:
Mapping XS 5c1e6f78
END DESCRIPTION:
XS GIS Cut Line= 4
      3707033.35     10618740.31      3706838.04     10618952.99
      3706803.32     10619167.83      3707013.21     10619516.21
#Sta/Elev= 30
  4683.1  233.59  4707.1  233.57    4728  231.67  4749.6  231.66  4784.7  229.56
  4813.1  229.73  4845.3  228.38    4848  227.88  4851.3  228.38  4890.8  229.46
    4905   228.7  4919.2  229.58  4947.5  229.01  4993.8  230.47  4995.5  230.28
  5029.8  230.44  5050.1  231.58  5060.6  231.05  5070.3  232.09  5203.9  231.23
  5238.9  233.82  5268.8  234.86  5290.2  237.51  5369.8  242.55  5480.5  249.01
  5517.3  249.99  5538.7  251.62  5554.2  251.17    5572  252.98  5596.2  255.06
#Mann= 5 ,-1 , 0
  4683.1     .16       0  4845.3     .16       0  4851.3     .16       0
  4995.5     .16       0    5572     .16       0
#XS Ineff= 2 , 0
         4984.71   246.4
Permanent Ineff=
       F       F
Bank Sta=4993.8,5070.3
XS Rating Curve= 0 ,0
Exp/Cntr=0.3,0.1

Type RM Length L Ch R = 1 ,742     ,256,256,256
BEGIN DESCRIPTION:
UNT 164 IN BOCR 1.0
END DESCRIPTION:
XS GIS Cut Line= 4
      3707065.22     10618614.69      3706707.57     10618857.75
      3706634.66     10619073.03      3706912.45     10619552.22
#Sta/Elev= 30
  4466.2  234.35  4502.9  233.69  4532.8  231.54  4545.5  231.78  4618.1  227.35
  4631.7  228.04  4697.5  225.79  4766.4  225.62  4769.1  225.12  4772.4  225.62
  4884.1  227.01  4912.4  226.34    4970   227.5  4975.3  226.85  5101.8  226.33
  5170.2  227.55  5180.1  227.04    5282  228.59  5330.8  230.02  5362.3  231.52
  5368.1  232.69  5383.9  231.96  5405.4  234.62  5421.1  234.85  5426.9  236.16
  5434.7  235.94  5538.7  242.26  5573.4  245.62    5635  249.08  5679.8  251.06
#Mann= 4 ,-1 , 0
  4466.2     .16       0  4766.4     .16       0  4772.4     .16       0
    5635     .16       0
#XS Ineff= 2 , 0
         4965.57  239.53
Permanent Ineff=
       F       F
Bank Sta=4970,5170.2
XS Rating Curve= 0 ,0
Exp/Cntr=0.3,0.1

Type RM Length L Ch R = 1 ,486     ,241,241,241
BEGIN DESCRIPTION:
Mapping XS bc5f33d1
END DESCRIPTION:
XS GIS Cut Line= 5
      3706803.22     10618462.52      3706495.16     10618788.06
      3706447.41     10619020.26      3706536.39       10619272.
      3706560.27     10619334.97
#Sta/Elev= 30
  4401.2  221.25    4404  220.75  4407.2  221.25  4416.2  222.66  4423.5  222.74
  4430.3  221.91  4437.6  222.38  4444.5  221.92  4472.8  222.04  4571.9  223.32
    4593  222.63  4713.5  222.84  4791.2   224.4  4798.1  223.69  4847.4  222.74
  4892.4   223.9  4943.5  222.94  4974.1   224.2  4984.3  224.08  5000.3  222.77
  5055.8   224.3  5092.6  223.68  5172.3  222.95  5192.4  222.19  5245.5  222.58
  5259.7  223.49  5272.5  223.37  5289.4  223.51  5309.1   224.5  5420.8  226.15
#Mann= 5 ,-1 , 0
  4401.2     .07       0  4407.2     .12       0  5092.6     .05       0
  5272.5     .12       0  5289.4     .05       0
#XS Ineff= 2 , 0
         4754.12  226.38 5111.11          226.44
Permanent Ineff=
       F       F
Bank Sta=4791.2,5055.8
XS Rating Curve= 0 ,0
Exp/Cntr=0.3,0.1

Type RM Length L Ch R = 1 ,245     ,182,182,182
BEGIN DESCRIPTION:
Mapping XS 731363f8
END DESCRIPTION:
XS GIS Cut Line= 4
      3706486.49     10618482.05      3706308.52     10618764.19
      3706262.95     10618890.05      3706362.79     10619204.76
#Sta/Elev= 30
  4614.6  219.87  4727.6  220.87  4733.6  220.34  4821.8  220.76  4827.7  220.08
    4843  220.92  4864.2  220.06  4879.5  220.51  4885.4  219.11  4900.7  218.89
  4931.2  220.54  5007.7  219.76  5021.1  220.34  5092.7  219.71  5134.6  220.42
  5145.1  219.87  5176.6  220.27  5184.3  219.33  5189.5  220.78  5216.6  218.58
  5229.1  220.44  5248.8  219.47  5302.5  220.06  5312.7  218.07    5334  221.01
  5350.9  220.63  5365.4   219.2  5383.2  219.01  5388.4  220.79  5412.2  221.19
#Mann= 1 ,-1 , 0
  4614.6     .16       0
Bank Sta=4931.2,5134.6
XS Rating Curve= 0 ,0
Exp/Cntr=0.3,0.1

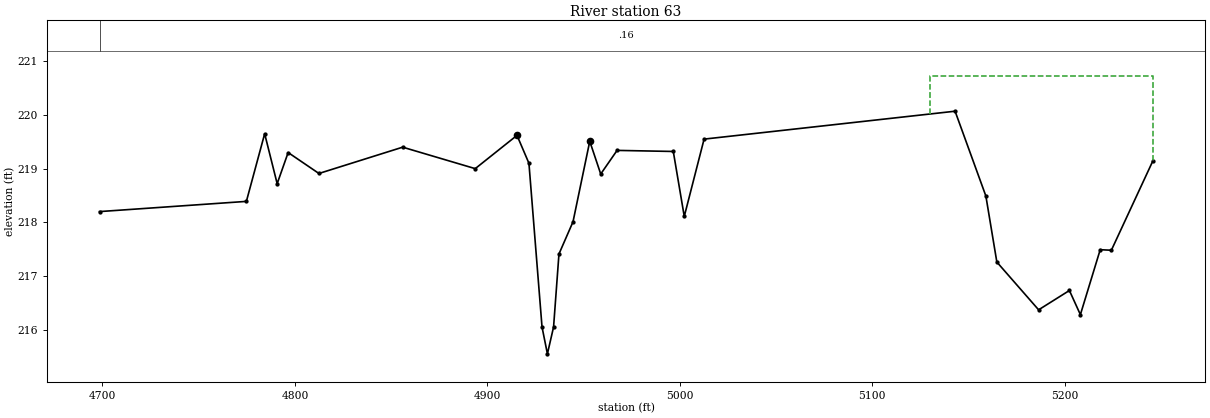
Type RM Length L Ch R = 1 ,63      ,0,0,0
BEGIN DESCRIPTION:
Mapping XS 33fa06f8
END DESCRIPTION:
XS GIS Cut Line= 2
      3706389.87     10618405.21      3706123.76     10618883.35
#Sta/Elev= 30
  4698.5   218.2  4774.8  218.39  4784.3  219.65  4790.8  218.72  4796.5   219.3
  4812.5  218.91    4856   219.4  4893.7     219  4915.4  219.62  4921.6   219.1
  4928.4  216.05  4931.2  215.55  4934.4  216.05  4937.2  217.41  4944.5  218.01
  4953.2  219.51  4958.9   218.9  4967.4  219.34  4996.6  219.32  5002.3  218.11
  5012.6  219.55    5143  220.07    5159  218.49  5164.7  217.26  5186.4  216.37
  5202.4  216.73  5208.1  216.28  5218.4  217.49  5224.2  217.48  5245.7  219.14
#Mann= 1 ,-1 , 0
  4698.5     .16       0
#XS Ineff= 2 , 0
                         5129.77          220.73
Permanent Ineff=
       F       F
Bank Sta=4915.4,4953.2
XS Rating Curve= 0 ,0
Exp/Cntr=0.3,0.1

Chan Stop Cuts=-1
Use User Specified Reach Order=0
Composite Channel Slope=5