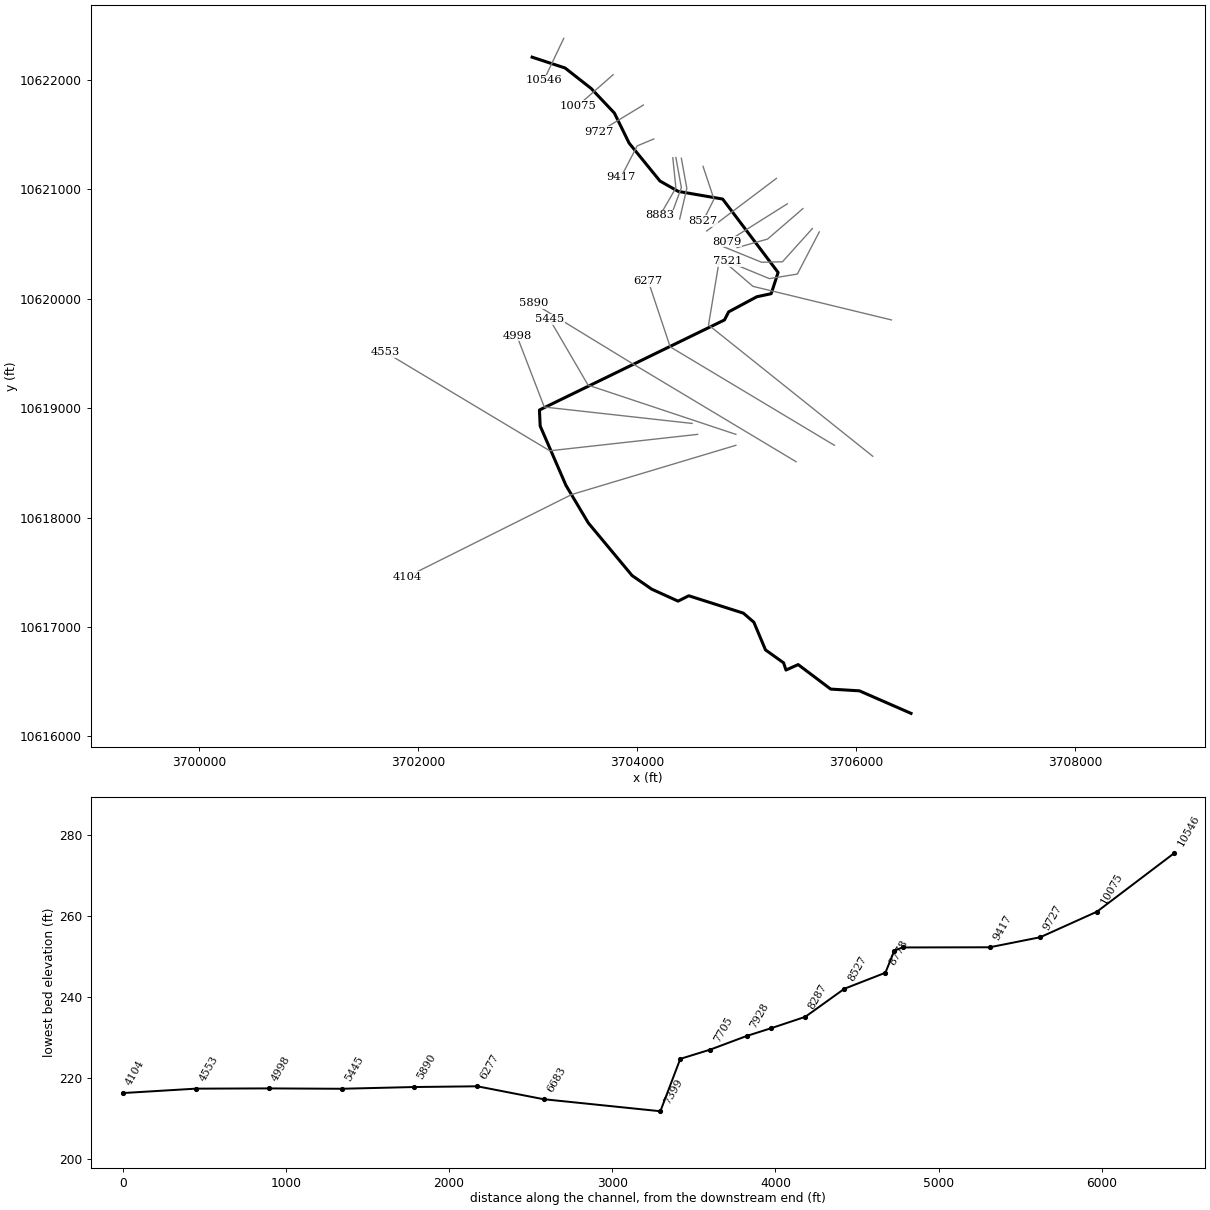
--- UNT 165 IN BOCR.prj (project) ---

Proj Title=UNT 165 IN BOCR Base Level Engineering
Current Plan=p01
Default Exp/Contr=0.3,0.1
English Units
Geom File=g01
Flow File=f01
Plan File=p01
Y Axis Title=Elevation
X Axis Title(PF)=Main Channel Distance
X Axis Title(XS)=Station
BEGIN DESCRIPTION:
UNT 165 IN BOCR
END DESCRIPTION:
DSS Export Rating Curves= 0
DSS Export Rating Curve Sorted= 0
DSS Export Volume Flow Curves= 0
DXF OffsetX= 0
DXF OffsetY= 0
DXF ScaleX= 1
DXF ScaleY= 10

--- UNT 165 IN BOCR.p01 (plan) ---

Plan Title=Multiple Run
Short Identifier=Multiple
Geom File=g01
Flow File=f01
Subcritical Flow
K Sum by GR= 0
Std Step Tol= 0.01
Critical Tol= 0.01
Num of Std Step Trials= 20
Max Error Tol= 0.3
Flow Tol Ratio= 0.001
Split Flow NTrial= 30
Split Flow Tol= 0.02
Split Flow Ratio= 0.02
Log Output Level= 0
Friction Slope Method= 1
Unsteady Friction Slope Method= 2
Unsteady Bridges Friction Slope Method= 1
Parabolic Critical Depth
Global Vel Dist=  1 , 1 , 1
Global Log Level= 0
CheckData=True
Encroach Param= -1, 0, 0, 0
BEGIN DESCRIPTION:
Multiple Run
END DESCRIPTION:

--- UNT 165 IN BOCR.f01 (steady flow) ---

Flow Title=Multiple
Number of Profiles=7
Profile Names=10-year,25-year,50-year,1pct_min,100-year,1pct_plu,500-year
River Rch & RM= UNT 165 IN BOCR,Reach-1,10546
     395     501     582     495     669     905     889
Boundary for River Rch & Prof#=UNT 165 IN BOCR,Reach-1,1
Up Type=0
Dn Type=3
Dn Slope=0.005
Boundary for River Rch & Prof#=UNT 165 IN BOCR,Reach-1,2
Up Type=0
Dn Type=3
Dn Slope=0.005
Boundary for River Rch & Prof#=UNT 165 IN BOCR,Reach-1,3
Up Type=0
Dn Type=3
Dn Slope=0.005
Boundary for River Rch & Prof#=UNT 165 IN BOCR,Reach-1,4
Up Type=0
Dn Type=3
Dn Slope=0.005
Boundary for River Rch & Prof#=UNT 165 IN BOCR,Reach-1,5
Up Type=0
Dn Type=3
Dn Slope=0.005
Boundary for River Rch & Prof#=UNT 165 IN BOCR,Reach-1,6
Up Type=0
Dn Type=3
Dn Slope=0.005
Boundary for River Rch & Prof#=UNT 165 IN BOCR,Reach-1,7
Up Type=0
Dn Type=3
Dn Slope=0.005

--- UNT 165 IN BOCR.g01 (geometry) ---

Geom Title=Existing Conditions
Program Version=4.10

River Reach=UNT 165 IN BOCR ,Reach-1
Reach XY= 30
      3703038.25       10622208.       3703339.5       10622109.
       3703577.5       10621922.        3703790.       10621697.
        3703924.       10621423.        3704206.       10621076.
      3704373.25       10620981.        3704779.       10620911.
      3705285.25       10620240.      3705222.25       10620046.
      3705090.75       10620018.       3704833.5       10619880.
       3704795.5       10619806.       3703105.5       10618983.
        3703112.       10618837.       3703347.5       10618294.
      3703552.25       10617950.      3703951.25       10617470.
      3704131.25       10617345.       3704371.5       10617236.
      3704469.25       10617285.      3704968.25       10617126.
        3705064.       10617043.      3705170.25       10616790.
       3705335.5       10616672.      3705357.25       10616606.
       3705468.5       10616656.       3705765.5       10616432.
        3706028.       10616416.       3706499.5       10616210.

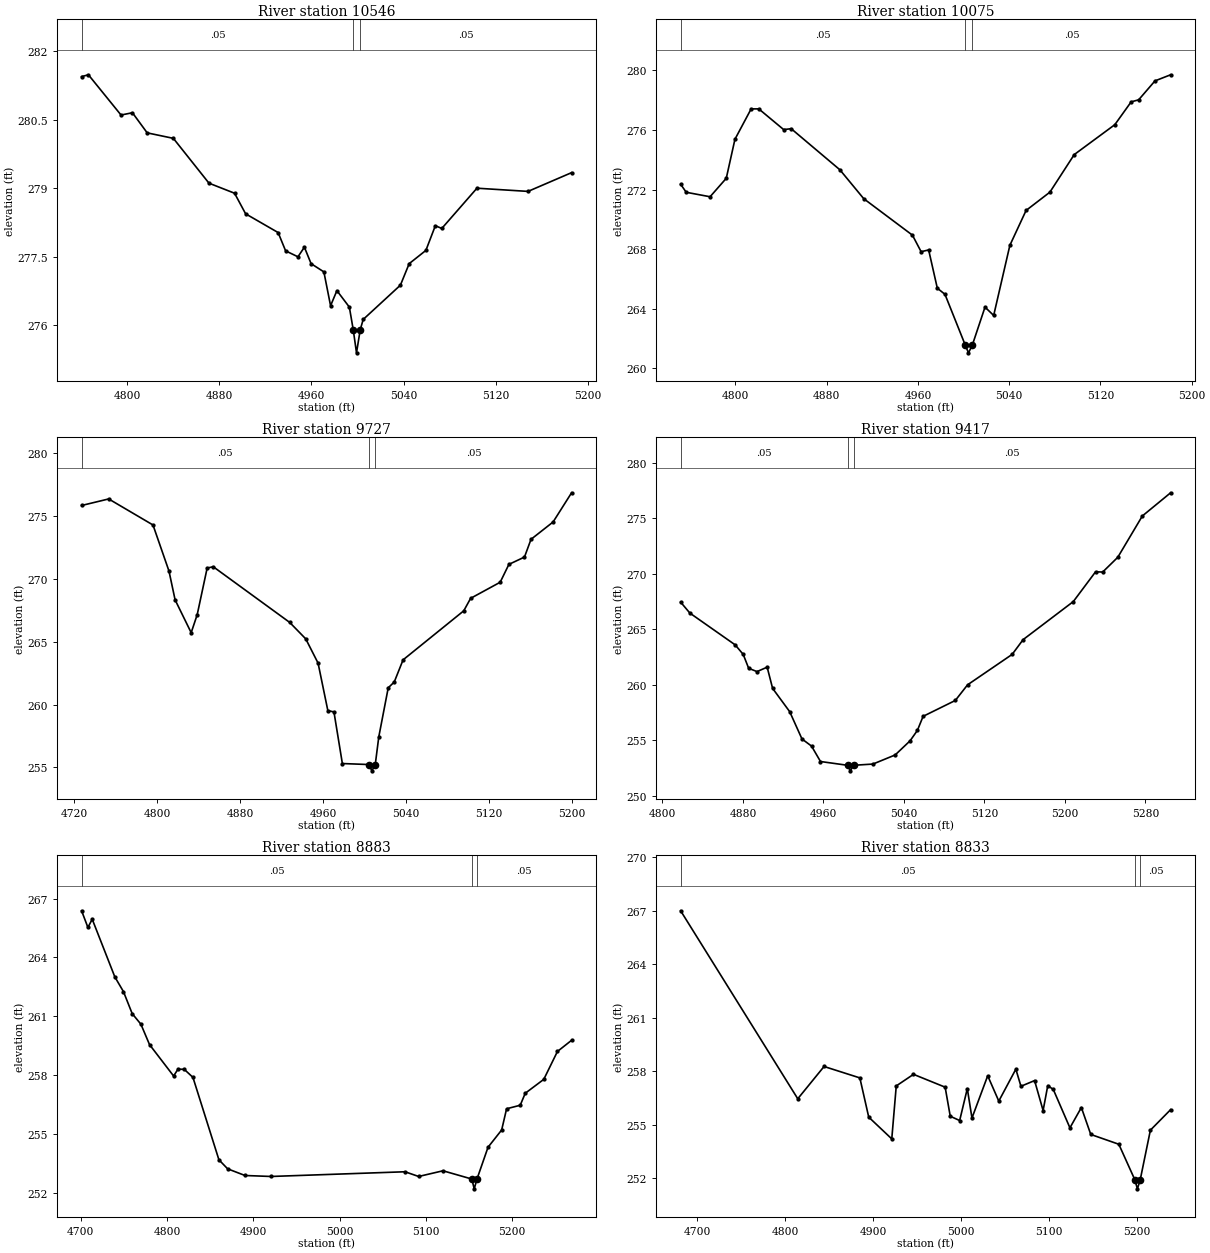
Type RM Length L Ch R = 1 ,10546   ,471,471,471
BEGIN DESCRIPTION:
UNT 165 IN BOCR 15.0
END DESCRIPTION:
XS GIS Cut Line= 2
      3703327.35     10622380.06      3703145.09     10621996.01
#Sta/Elev= 30
  4760.6  281.44  4766.5  281.48  4794.8   280.6  4804.7  280.65  4817.5  280.21
  4840.2  280.09  4871.1  279.11  4893.3  278.89  4902.9  278.44  4931.1  278.03
  4937.6  277.63  4948.3   277.5  4953.9  277.71  4959.7  277.35  4970.8  277.17
  4976.6  276.43  4982.1  276.76  4992.9   276.4  4996.3   275.9  4999.1   275.4
  5002.3   275.9  5004.9  276.13  5037.2  276.88  5044.8  277.35  5059.3  277.64
  5067.5  278.18  5073.1  278.12  5103.6     279  5147.9  278.93  5185.7  279.34
#Mann= 3 ,-1 , 0
  4760.6     .05       0  4996.3     .03       0  5002.3     .05       0
Bank Sta=4996.3,5002.3
XS Rating Curve= 0 ,0
Exp/Cntr=0.3,0.1

Type RM Length L Ch R = 1 ,10075   ,348,348,348
BEGIN DESCRIPTION:
UNT 165 IN BOCR 14.0
END DESCRIPTION:
XS GIS Cut Line= 2
      3703778.74     10622048.04      3703456.18     10621764.45
#Sta/Elev= 30
    4752  272.36  4756.9  271.82  4777.8  271.52    4792  272.76  4799.6  275.38
  4813.8  277.42  4820.5  277.42  4842.3  276.03  4848.9  276.09  4891.6  273.33
  4912.5  271.39  4955.2  268.94  4962.8  267.83  4969.4  267.95    4977  265.38
  4983.7  264.97  5001.6  261.54  5004.3  261.04  5007.6  261.54  5018.8  264.11
  5026.4  263.55  5040.6  268.26  5054.8   270.6  5075.7  271.83    5097  274.35
  5132.6  276.36  5146.9  277.89  5153.5  278.03  5167.8   279.3  5181.5  279.71
#Mann= 3 ,-1 , 0
    4752     .05       0  5001.6     .03       0  5007.6     .05       0
Bank Sta=5001.6,5007.6
XS Rating Curve= 0 ,0
Exp/Cntr=0.3,0.1

Type RM Length L Ch R = 1 ,9727    ,310,310,310
BEGIN DESCRIPTION:
UNT 165 IN BOCR 13.0
END DESCRIPTION:
XS GIS Cut Line= 2
      3704054.37     10621770.28      3703650.81     10621525.11
#Sta/Elev= 30
  4727.3  275.82  4753.4  276.34  4796.1  274.27  4811.5  270.61  4817.4  268.32
  4832.9  265.71  4838.7  267.14  4848.3  270.85  4854.2  270.95  4927.8  266.53
  4943.3  265.22  4955.2  263.29  4964.6  259.52  4970.5  259.41  4978.6  255.31
  5004.3  255.23    5007  254.73  5010.3  255.23  5013.7  257.43  5022.8  261.33
  5028.6  261.79  5037.1  263.55  5095.6  267.45  5102.2  268.44  5130.7  269.72
  5139.1  271.14  5154.1  271.72  5160.4  273.13  5181.7  274.51  5199.5  276.83
#Mann= 3 ,-1 , 0
  4727.3     .05       0  5004.3     .03       0  5010.3     .05       0
Bank Sta=5004.3,5010.3
XS Rating Curve= 0 ,0
Exp/Cntr=0.3,0.1

Type RM Length L Ch R = 1 ,9417    ,534,534,534
BEGIN DESCRIPTION:
UNT 165 IN BOCR 12.0
END DESCRIPTION:
XS GIS Cut Line= 3
       3704149.6     10621460.18      3703998.13     10621396.85
      3703849.62     10621110.21
#Sta/Elev= 30
  4818.1  267.45  4827.3  266.46  4872.3   263.6  4880.3  262.74  4885.7  261.49
    4894  261.19  4904.1  261.59  4909.5  259.68  4926.5  257.58  4938.7  255.12
  4948.2  254.48  4957.1  253.09    4984  252.75  4986.8  252.25    4990  252.75
  5009.2  252.86  5031.3  253.68  5046.1  254.95  5053.4  255.89  5059.1  257.16
  5091.1  258.59  5103.3     260  5147.6  262.74  5158.5  264.07  5208.4   267.5
  5230.5  270.18  5237.6  270.16  5252.6  271.49    5277  275.21  5305.1   277.3
#Mann= 3 ,-1 , 0
  4818.1     .05       0    4984     .03       0    4990     .05       0
Bank Sta=4984,4990
XS Rating Curve= 0 ,0
Exp/Cntr=0.3,0.1

Type RM Length L Ch R = 1 ,8883    ,50,50,50
BEGIN DESCRIPTION:
UNT 165 IN BOCR 11.0
END DESCRIPTION:
XS GIS Cut Line= 3
      3704323.47     10621288.48      3704351.68      10621012.9
      3704206.29     10620761.19
#Sta/Elev= 30
    4701  266.38  4708.3  265.53  4713.3  265.95  4739.5  263.01  4749.5  262.26
  4759.6  261.14  4769.7   260.6  4779.7  259.56  4807.6  257.96  4812.7  258.31
  4819.9   258.3    4830  257.89  4860.1  253.69  4870.2  253.23  4890.3  252.89
  4920.4  252.84  5075.7  253.08  5091.5  252.84  5119.7  253.13  5153.1  252.71
  5155.9  252.21  5159.1  252.71  5171.9  254.33  5187.7  255.21  5193.4  256.29
  5209.2  256.47    5215  257.08  5236.5  257.79  5252.3  259.21  5268.7  259.78
#Mann= 3 ,-1 , 0
    4701     .05       0  5153.1     .03       0  5159.1     .05       0
Bank Sta=5153.1,5159.1
XS Rating Curve= 0 ,0
Exp/Cntr=0.3,0.1

Type RM Length L Ch R = 1 ,8833    ,55,55,55
BEGIN DESCRIPTION:
Mapping XS ef054952
END DESCRIPTION:
XS GIS Cut Line= 3
      3704351.67      10621290.7      3704401.59     10621015.07
       3704306.2     10620754.92
#Sta/Elev= 30
    4681     267  4814.2  256.46  4844.1  258.27  4884.8  257.63  4894.9  255.43
  4921.1  254.21  4926.2  257.18  4945.8  257.83  4981.8  257.11  4987.6  255.48
  4998.3  255.24    5007  257.03  5012.3  255.38  5030.2  257.75  5042.8  256.33
  5062.2  258.12    5068  257.16  5083.5  257.48  5093.2   255.8  5098.5   257.2
  5104.8  256.98  5123.7  254.83  5136.7  255.97  5147.4  254.46  5179.3  253.91
  5197.6  251.91  5200.4  251.41  5203.6  251.91  5215.2   254.7  5238.2  255.85
#Mann= 3 ,-1 , 0
    4681     .05       0  5197.6     .03       0  5203.6     .05       0
Bank Sta=5197.6,5203.6
XS Rating Curve= 0 ,0
Exp/Cntr=0.3,0.1

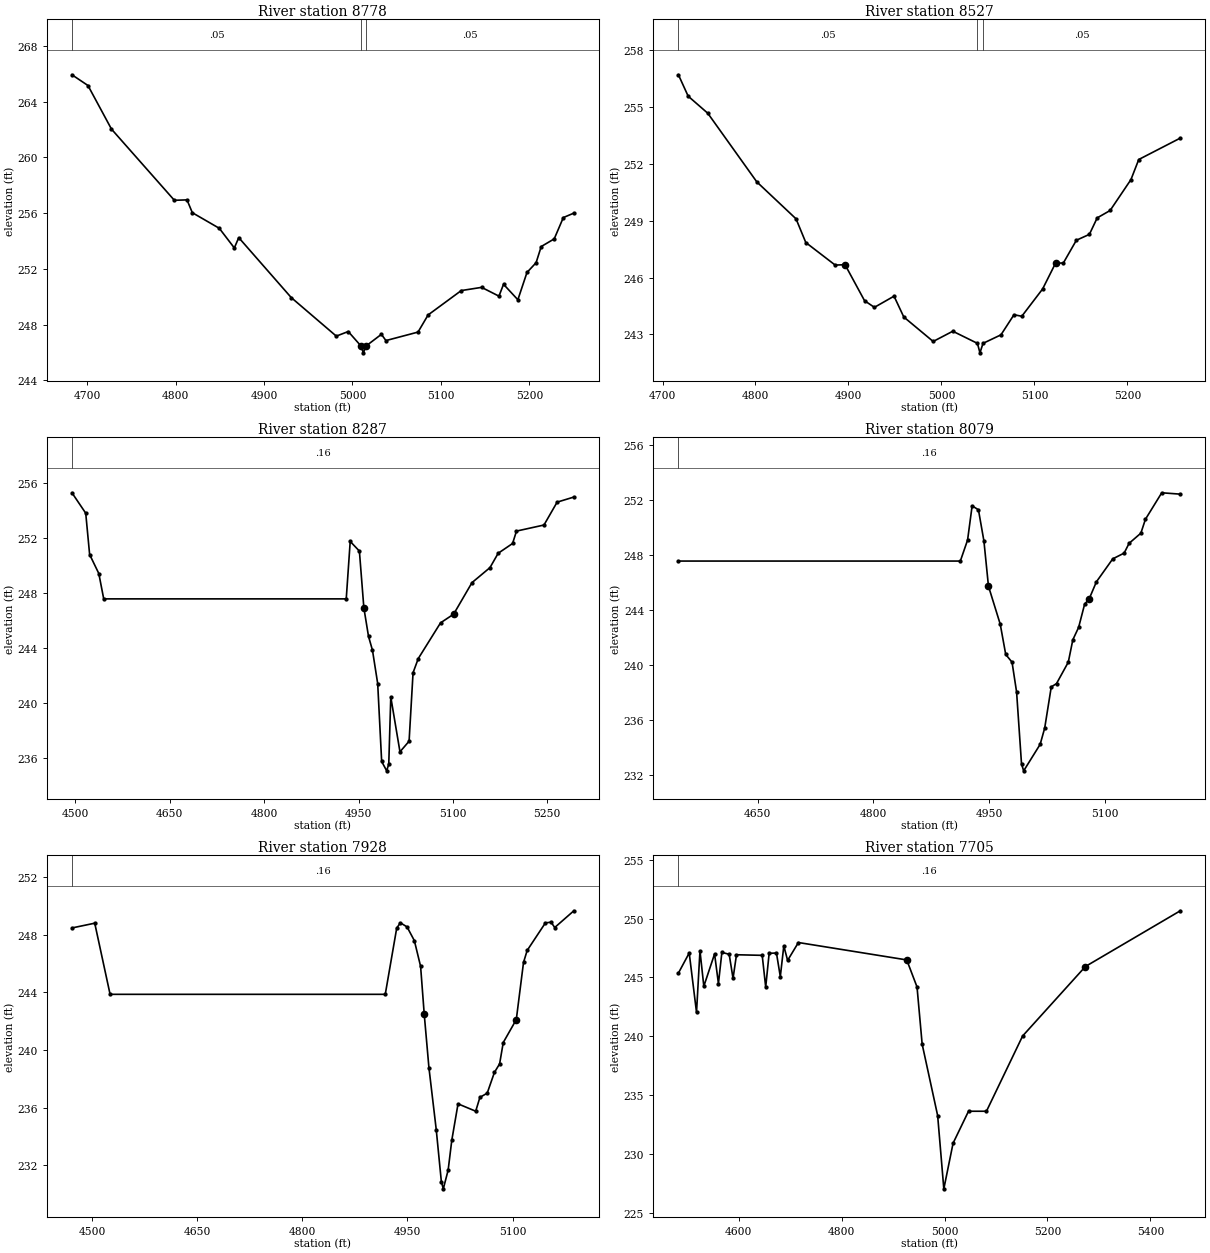
Type RM Length L Ch R = 1 ,8778    ,251,251,251
BEGIN DESCRIPTION:
Mapping XS f180b8eb
END DESCRIPTION:
XS GIS Cut Line= 3
       3704401.6     10621284.13       3704451.5     10621008.56
      3704386.39     10620728.58
#Sta/Elev= 30
  4682.8  265.93  4700.9  265.16  4727.5  262.03  4798.6  256.92  4812.9  256.95
  4818.9  256.03  4849.4  254.91  4866.4   253.5  4871.4  254.24  4930.7  249.94
  4981.7  247.17  4995.2   247.5  5009.5  246.47  5012.3  245.97  5015.5  246.47
  5032.7   247.3  5037.8  246.85  5074.1  247.46  5085.5  248.69    5123  250.44
    5146  250.67  5165.6  250.04  5170.8  250.89    5187  249.78  5197.3  251.74
  5207.6  252.44  5213.4   253.6  5228.1  254.15  5238.4  255.68  5250.3     256
#Mann= 3 ,-1 , 0
  4682.8     .05       0  5009.5     .03       0  5015.5     .05       0
Bank Sta=5009.5,5015.5
XS Rating Curve= 0 ,0
Exp/Cntr=0.3,0.1

Type RM Length L Ch R = 1 ,8527    ,240,240,240
BEGIN DESCRIPTION:
UNT 165 IN BOCR 10.0
END DESCRIPTION:
XS GIS Cut Line= 3
      3704599.62     10621210.16      3704699.61     10620910.19
      3704599.61     10620710.19
#Sta/Elev= 30
  4717.1   256.7  4727.6  255.57  4748.7  254.67  4801.4  251.05  4843.6   249.1
  4854.1  247.85  4885.7  246.66  4896.3  246.68  4917.3  244.78  4927.9  244.43
    4949  245.02  4959.5  243.92  4991.1  242.63  5012.2  243.17  5038.7  242.53
  5041.4  242.03  5044.7  242.53    5064  242.98    5078  244.04  5086.4  243.96
  5108.8   245.4  5122.7  246.76  5131.1  246.77  5145.1  247.97  5159.1  248.28
  5167.5  249.15  5181.4  249.54  5203.8  251.17  5212.2  252.23  5256.9  253.36
#Mann= 3 ,-1 , 0
  4717.1     .05       0  5038.7     .03       0  5044.7     .05       0
Bank Sta=4896.3,5122.7
XS Rating Curve= 0 ,0
Exp/Cntr=0.3,0.1

Type RM Length L Ch R = 1 ,8287    ,208,208,208
BEGIN DESCRIPTION:
Mapping XS 7c132197
END DESCRIPTION:
XS GIS Cut Line= 2
      3705269.92     10621099.96      3704633.25      10620619.2
#Sta/Elev= 30
  4494.5  255.28  4516.4   253.8  4522.6   250.8  4537.2  249.42    4545  247.58
  4930.5  247.58  4936.8  251.75  4951.4  251.05  4958.5  246.93  4965.9  244.86
  4972.2  243.85  4980.5  241.43  4986.8  235.78  4994.8   235.1  4998.1   235.6
  5001.3  240.46  5015.9  236.48  5030.4  237.25  5036.7  242.22    5045  243.25
  5080.4  245.84  5101.2  246.47  5130.4  248.76    5159  249.85    5172  250.89
  5194.9   251.6  5201.1   252.5  5244.8  252.94  5265.7   254.6  5292.3  254.97
#Mann= 1 ,-1 , 0
  4494.5     .16       0
Bank Sta=4958.5,5101.2
XS Rating Curve= 0 ,0
Exp/Cntr=0.3,0.1

Type RM Length L Ch R = 1 ,8079    ,151,151,151
BEGIN DESCRIPTION:
UNT 165 IN BOCR 9.0
END DESCRIPTION:
XS GIS Cut Line= 2
      3705369.06     10620867.19       3704817.9     10620520.01
#Sta/Elev= 30
  4546.9  247.58  4912.8  247.58  4922.2  249.11  4928.1   251.6  4936.3  251.31
  4943.4  249.04  4949.3  245.75  4964.6  242.98  4971.7  240.78  4979.9  240.22
  4985.8  238.05  4992.2  232.81    4995  232.31  5016.4  234.24  5022.3  235.43
  5030.8  238.42  5037.6  238.66  5052.9  240.22  5058.8  241.85  5066.3  242.75
  5074.1  244.44    5080  244.83  5089.4  246.07  5110.6  247.74  5125.4  248.16
  5131.8  248.87  5147.1  249.61    5153  250.62  5174.2  252.55  5198.3  252.45
#Mann= 1 ,-1 , 0
  4546.9     .16       0
Bank Sta=4949.3,5080
XS Rating Curve= 0 ,0
Exp/Cntr=0.3,0.1

Type RM Length L Ch R = 1 ,7928    ,223,223,223
BEGIN DESCRIPTION:
Mapping XS e842da02
END DESCRIPTION:
XS GIS Cut Line= 3
      3705512.12     10620823.93      3705189.23      10620545.3
      3704910.56     10620467.17
#Sta/Elev= 30
  4471.4  248.46  4503.9  248.79  4525.8  243.86  4918.3  243.86  4934.6  248.44
  4939.8  248.82  4949.4  248.53  4959.8  247.58  4968.7   245.8  4973.9  242.47
  4980.6  238.77    4991  234.49  4998.3  230.88  5001.1  230.38    5008  231.68
  5013.2  233.75  5022.1  236.27  5047.3  235.76  5053.3  236.72  5063.7  237.01
    5074  238.45  5081.4  239.04  5086.6  240.52  5105.2  242.11  5115.5  246.07
  5120.7   246.9  5146.7  248.81  5154.8  248.86    5160  248.49  5187.3  249.65
#Mann= 1 ,-1 , 0
  4471.4     .16       0
Bank Sta=4973.9,5105.2
XS Rating Curve= 0 ,0
Exp/Cntr=0.3,0.1

Type RM Length L Ch R = 1 ,7705    ,184,184,184
BEGIN DESCRIPTION:
UNT 165 IN BOCR 8.0
END DESCRIPTION:
XS GIS Cut Line= 4
      3705598.23     10620641.25      3705324.79     10620337.43
      3705134.71     10620333.36      3704785.64     10620475.57
#Sta/Elev= 30
  4482.5  245.37  4503.5  247.08  4517.7  242.03  4524.4  247.27  4531.9  244.25
  4552.8     247  4560.3  244.48    4567  247.13  4581.2  246.97  4588.7  244.92
  4595.4  246.93  4645.4  246.88  4652.2  244.18  4658.9  247.05  4673.1  247.08
  4680.6  245.07  4687.4  247.68  4694.8  246.45  4715.8  247.97  4926.4  246.49
  4946.4  244.19  4956.4  239.32  4986.5  233.25  4998.5  227.02  5016.5   230.9
  5046.5  233.62  5081.4  233.62  5151.7  240.02  5273.8  245.93  5458.3  250.67
#Mann= 1 ,-1 , 0
  4482.5     .16       0
Bank Sta=4926.4,5273.8
XS Rating Curve= 0 ,0
Exp/Cntr=0.3,0.1

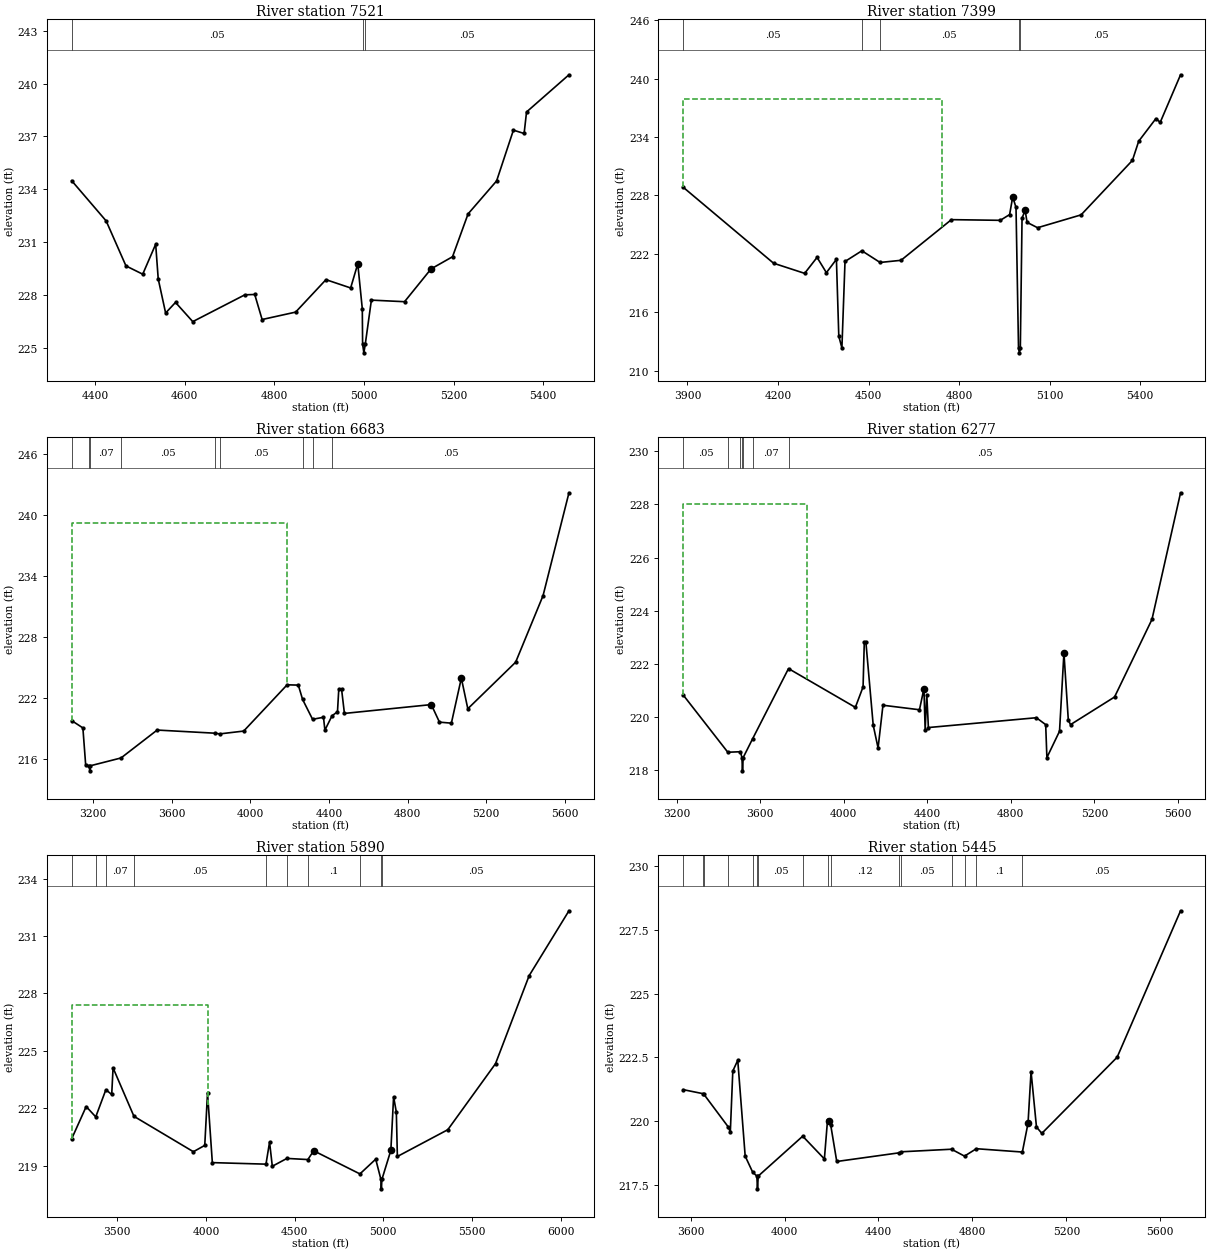
Type RM Length L Ch R = 1 ,7521    ,122,122,122
BEGIN DESCRIPTION:
Mapping XS 39040e53
END DESCRIPTION:
XS GIS Cut Line= 4
      3705661.47     10620610.81      3705460.95     10620225.41
      3705205.75     10620183.74      3704820.33     10620342.59
#Sta/Elev= 30
  4347.7  234.49  4424.6  232.21  4468.8  229.66  4506.2  229.19  4535.1  230.89
  4540.8  228.92  4557.3  226.99  4579.4  227.59  4617.9   226.5  4734.1  228.02
  4756.2  228.04  4772.7  226.62  4847.5  227.04  4915.2  228.88  4970.3  228.41
  4986.2  229.78  4996.3  227.23    4997  225.23  4999.8  224.73    5003  225.23
  5016.6  227.72  5090.6  227.63  5149.8  229.49  5197.7  230.18  5232.4  232.61
  5296.1  234.48  5333.6  237.36  5357.5  237.17  5362.9  238.39  5457.6   240.5
#Mann= 3 ,-1 , 0
  4347.7     .05       0    4997     .03       0    5003     .05       0
Bank Sta=4986.2,5149.8
XS Rating Curve= 0 ,0
Exp/Cntr=0.3,0.1

Type RM Length L Ch R = 1 ,7399    ,716,716,716
BEGIN DESCRIPTION:
Mapping XS f1ff5034
END DESCRIPTION:
XS GIS Cut Line= 3
      3706320.28     10619806.15       3705054.7     10620113.43
      3704793.12     10620338.75
#Sta/Elev= 30
  3886.3  228.83  4185.4  221.03  4288.3  219.99  4329.5  221.63  4360.4  220.06
  4393.6  221.43  4401.5  213.54  4411.8  212.32  4422.1  221.21    4478  222.31
  4538.3  221.11  4607.6  221.33  4774.7  225.51  4936.6  225.44  4967.5  226.03
  4977.8  227.85  4988.7  226.76    4997  212.32  4999.8  211.82    5003  212.32
  5008.7  225.67    5019  226.47  5025.3  225.23  5060.1  224.68  5204.3     226
  5374.4   231.6  5395.2  233.57  5452.3   235.9  5466.5  235.51  5533.9   240.4
#Mann= 5 ,-1 , 0
  3886.3     .05       0    4478      .1       0  4538.3     .05       0
    4997     .03       0    5003     .05       0
#XS Ineff= 2 , 0
         4741.94  237.95
Permanent Ineff=
       F       F
Bank Sta=4977.8,5019
XS Rating Curve= 0 ,0
Exp/Cntr=0.3,0.1

Type RM Length L Ch R = 1 ,6683    ,406,406,406
BEGIN DESCRIPTION:
UNT 165 IN BOCR 7.0
END DESCRIPTION:
XS GIS Cut Line= 3
       3706149.6      10618560.2      3704649.61     10619760.19
      3704749.61     10620360.19
#Sta/Elev= 30
  3091.4  219.74  3148.2  219.02  3162.6  215.32  3180.4  215.29  3183.2  214.79
  3186.4  215.29  3342.2  216.06    3526  218.81  3820.3   218.5  3843.8  218.43
  3966.2  218.71  4187.1  223.27    4244  223.24  4265.7  221.83  4316.5  219.87
    4372  220.07  4379.2   218.8  4415.5  220.22  4443.2  220.61  4449.7  222.81
  4464.1  222.82  4478.5  220.45  4920.3  221.32  4961.9  219.59  5022.5  219.49
  5073.2  223.93  5106.1  220.91  5349.4   225.5  5488.8  232.06  5620.6   242.2
#Mann= 9 ,-1 , 0
  3091.4     .07       0  3180.4     .03       0  3186.4     .07       0
  3342.2     .05       0  3820.3     .07       0  3843.8     .05       0
  4265.7      .1       0  4316.5     .07       0  4415.5     .05       0
#XS Ineff= 2 , 0
         4188.07  239.26
Permanent Ineff=
       F       F
Bank Sta=4920.3,5073.2
XS Rating Curve= 0 ,0
Exp/Cntr=0.3,0.1

Type RM Length L Ch R = 1 ,6277    ,387,387,387
BEGIN DESCRIPTION:
UNT 165 IN BOCR 6.0
END DESCRIPTION:
XS GIS Cut Line= 3
       3705799.6      10618660.2      3704299.61     10619560.19
      3704099.62     10620160.16
#Sta/Elev= 30
  3231.3  220.82  3444.5  218.67    3505  218.69  3512.1  218.47  3514.8  217.97
  3518.1  218.47  3562.8  219.17  3735.2  221.82  4055.4  220.36  4092.3  221.13
  4098.2  222.82  4105.9  222.81  4140.9  219.69  4164.2  218.83  4187.6  220.44
  4362.5  220.27  4383.9  221.07  4389.7  219.52  4397.5  220.84  4405.2   219.6
  4922.3  219.97    4967  219.71  4972.8  218.47  5033.3  219.46  5054.4  222.41
  5075.4  219.88    5086  219.71  5296.8  220.75    5476  223.67    5613  228.44
#Mann= 7 ,-1 , 0
  3231.3     .05       0  3444.5     .07       0    3505     .05       0
  3512.1    .035       0  3518.1     .05       0  3562.8     .07       0
  3735.2     .05       0
#XS Ineff= 2 , 0
         3821.59     228
Permanent Ineff=
       F       F
Bank Sta=4383.9,5054.4
XS Rating Curve= 0 ,0
Exp/Cntr=0.3,0.1

Type RM Length L Ch R = 1 ,5890    ,445,445,445
BEGIN DESCRIPTION:
UNT 165 IN BOCR 5.0
END DESCRIPTION:
XS GIS Cut Line= 3
       3705449.6     10618510.19      3703949.61     10619410.19
      3703049.63     10619960.18
#Sta/Elev= 30
  3243.1  220.41  3324.7  222.09  3378.6  221.55  3435.7  222.97  3468.6  222.72
  3476.3  224.11    3594  221.58  3929.2  219.73  3993.3  220.06  4008.9   222.8
  4036.1  219.16  4338.6  219.08  4358.7  220.23  4374.3  218.97  4456.7  219.38
  4574.8  219.32  4607.5  219.78  4868.3  218.57  4957.4  219.34  4986.5  218.29
  4989.2  217.79  4992.5  218.29  5042.7   219.8  5058.2   222.6  5073.6   221.8
  5079.5  219.48  5363.9  220.88  5632.9  224.33  5822.6  228.93  6047.1  232.32
#Mann= 10 ,-1 , 0
  3243.1     .05       0  3378.6     .12       0  3435.7     .07       0
    3594     .05       0  4338.6     .07       0  4456.7     .12       0
  4574.8      .1       0  4868.3     .05       0  4986.5    .035       0
  4992.5     .05       0
#XS Ineff= 2 , 0
          4014.2   227.4
Permanent Ineff=
       F       F
Bank Sta=4607.5,5042.7
XS Rating Curve= 0 ,0
Exp/Cntr=0.3,0.1

Type RM Length L Ch R = 1 ,5445    ,447,447,447
BEGIN DESCRIPTION:
UNT 165 IN BOCR 4.0
END DESCRIPTION:
XS GIS Cut Line= 3
      3704899.57      10618760.2      3703549.61     10619210.19
      3703199.61     10619810.18
#Sta/Elev= 30
  3568.9  221.24  3654.8  221.08  3654.9  221.08  3760.5  219.78  3769.1  219.58
  3779.7  221.97  3800.8  222.39  3832.4  218.64  3864.4  218.01  3882.1  217.86
  3884.8  217.36  3888.1  217.86  4077.4  219.42  4169.7  218.53    4183  220.04
  4190.8  220.03  4196.6  219.86  4222.4  218.43  4488.5  218.77  4498.1  218.81
  4711.2  218.91  4766.4  218.64  4816.8  218.93  5012.8   218.8    5037  219.93
  5049.8  221.95  5072.9  219.78  5095.7  219.53  5416.5  222.51  5686.5  228.24
#Mann= 16 ,-1 , 0
  3568.9     .07       0  3654.8     .12       0  3654.9     .05       0
  3760.5     .12       0  3864.4     .05       0  3882.1     .07       0
  3888.1     .05       0  4077.4     .12       0    4183     .05       0
  4196.6     .12       0  4488.5      .1       0  4498.1     .05       0
  4711.2      .1       0  4766.4     .05       0  4816.8      .1       0
  5012.8     .05       0
Bank Sta=4190.8,5037
XS Rating Curve= 0 ,0
Exp/Cntr=0.3,0.1

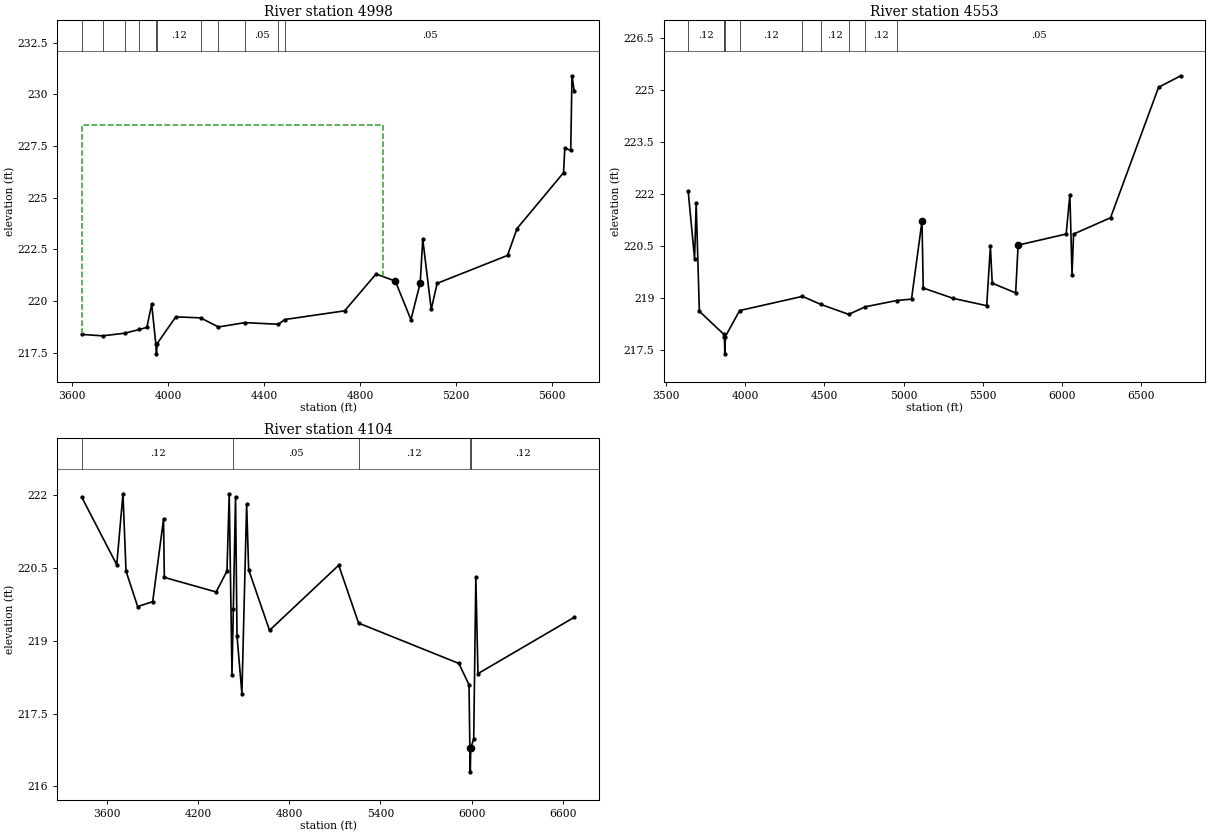
Type RM Length L Ch R = 1 ,4998    ,445,445,445
BEGIN DESCRIPTION:
UNT 165 IN BOCR 3.0
END DESCRIPTION:
XS GIS Cut Line= 3
      3704499.65     10618860.18      3703149.61     10619010.19
       3702899.6     10619660.22
#Sta/Elev= 30
  3639.3  218.39  3726.4  218.32  3820.2  218.45  3879.8  218.63    3911  218.73
  3931.1  219.85  3948.2  217.95    3951  217.45  3954.2  217.95  4031.7  219.24
  4134.9  219.19  4209.6  218.75    4320  218.96  4459.6  218.88  4486.2  219.11
    4736  219.53  4866.8  221.31  4947.3  220.97  5012.6   219.1  5051.2  220.88
  5061.9  222.99  5097.3   219.6  5121.9  220.86  5415.5  222.21  5455.1  223.51
  5649.1  226.21  5654.4   227.4  5679.1  227.29  5684.4   230.9  5694.1  230.14
#Mann= 11 ,-1 , 0
  3639.3     .05       0  3726.4     .12       0  3820.2     .05       0
  3879.8     .12       0  3948.2     .03       0  3954.2     .12       0
  4134.9     .05       0  4209.6     .12       0    4320     .05       0
  4459.6     .07       0  4486.2     .05       0
#XS Ineff= 2 , 0
         4897.73  228.52
Permanent Ineff=
       F       F
Bank Sta=4947.3,5051.2
XS Rating Curve= 0 ,0
Exp/Cntr=0.3,0.1

Type RM Length L Ch R = 1 ,4553    ,449,449,449
BEGIN DESCRIPTION:
UNT 165 IN BOCR 2.0
END DESCRIPTION:
XS GIS Cut Line= 3
      3704549.56     10618760.18      3703199.61     10618610.19
      3701699.65     10619510.17
#Sta/Elev= 30
  3640.8  222.08    3681  220.14  3691.1  221.74  3711.2  218.62  3866.3  217.95
  3869.2  217.89  3871.9  217.39  3875.2  217.89  3965.4  218.64  4361.8  219.05
  4476.2  218.82    4653  218.53  4758.8  218.75  4956.4  218.93  5049.6  218.97
  5115.7  221.22  5123.5  219.29  5313.9  218.99  5523.8  218.78  5547.2  220.49
  5558.8  219.43  5706.5  219.15  5722.1  220.53  6025.3  220.85  6048.6  221.99
  6062.2  219.68    6072  220.85  6305.2  221.32  6608.4  225.09  6748.3  225.42
#Mann= 10 ,-1 , 0
  3640.8     .12       0  3866.3     .05       0  3869.2     .03       0
  3875.2     .05       0  3965.4     .12       0  4361.8     .05       0
  4476.2     .12       0    4653     .05       0  4758.8     .12       0
  4956.4     .05       0
Bank Sta=5115.7,5722.1
XS Rating Curve= 0 ,0
Exp/Cntr=0.3,0.1

Type RM Length L Ch R = 1 ,4104    ,0,0,0
BEGIN DESCRIPTION:
UNT 165 IN BOCR 1.0
END DESCRIPTION:
XS GIS Cut Line= 3
      3704899.64      10618660.2      3703399.61     10618210.19
      3701899.63      10617460.2
#Sta/Elev= 30
  3433.1  221.95  3663.7  220.56  3704.6  222.02  3724.6  220.43  3801.2   219.7
  3900.3   219.8  3971.7   221.5  3976.9   220.3  4317.9     220  4389.3  220.43
  4404.1  222.01  4422.3   218.3  4431.1  219.65  4445.8  221.96  4455.4   219.1
  4487.6  217.91  4518.9   221.8    4532  220.46  4669.4  219.21    5125  220.55
  5255.8  219.36    5916  218.53    5983  218.09  5988.4   216.8  5991.2   216.3
  5994.4   216.8  6013.8  216.97  6027.8  220.31  6041.7  218.32  6676.2  219.48
#Mann= 5 ,-1 , 0
  3433.1     .12       0  4431.1     .05       0  5255.8     .12       0
  5988.4     .03       0  5994.4     .12       0
Bank Sta=5988.4,5994.4
XS Rating Curve= 0 ,0
Exp/Cntr=0.3,0.1

Chan Stop Cuts=-1
Use User Specified Reach Order=0
Composite Channel Slope=5