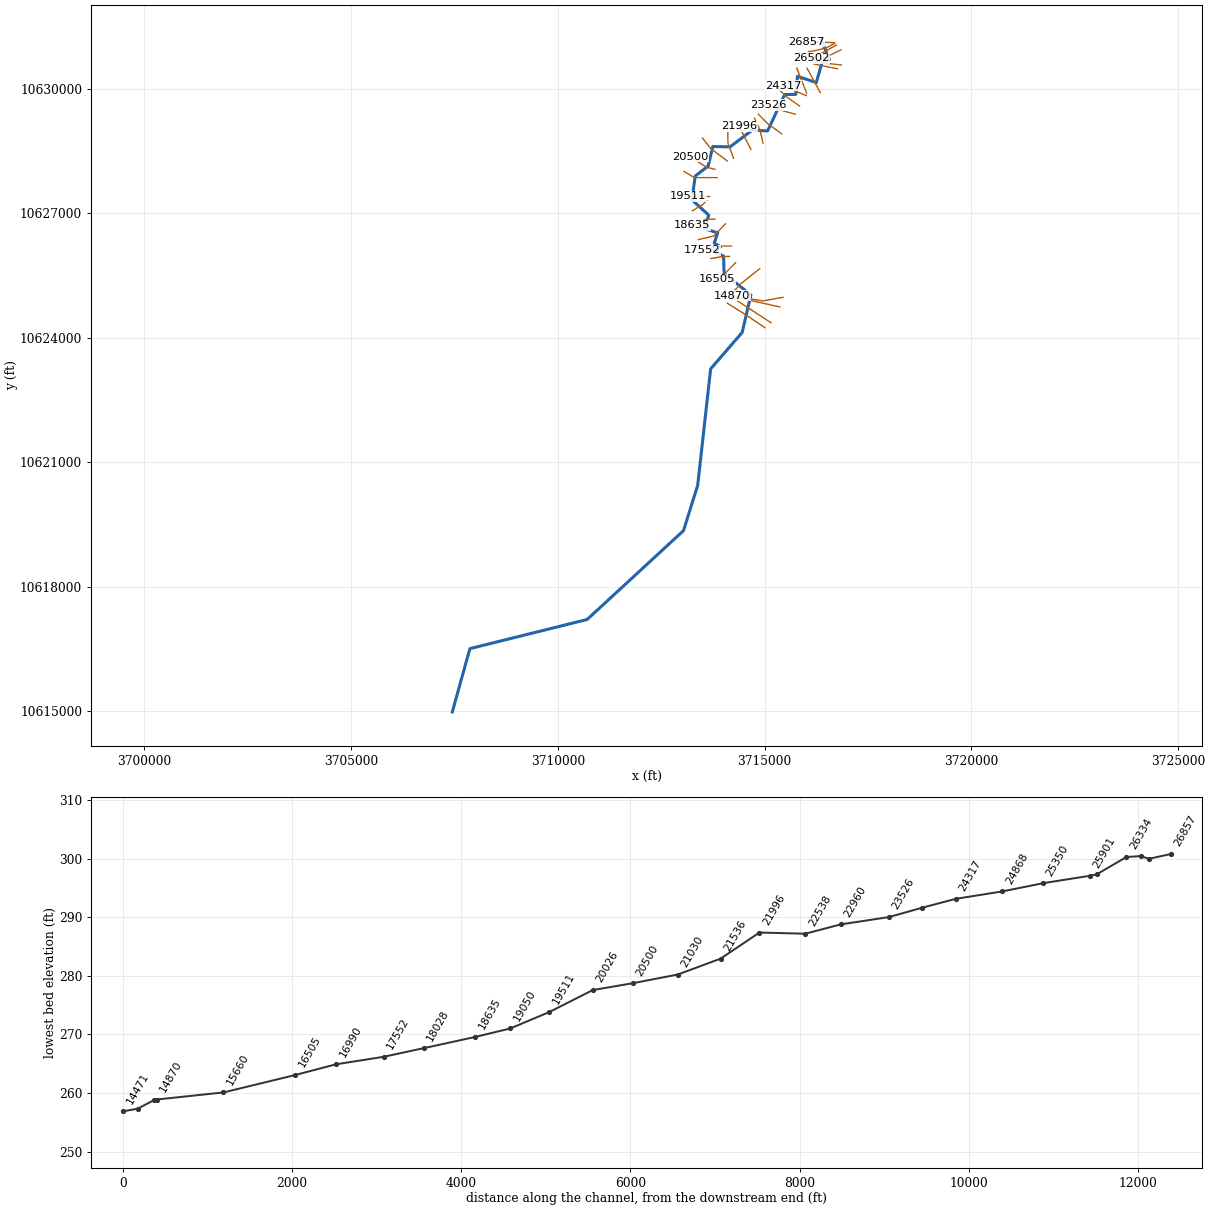
--- UNT 166 IN BOCR.prj (project) ---

Proj Title=UNT 166 IN BOCR Base Level Engineering
Current Plan=p01
Default Exp/Contr=0.3,0.1
English Units
Geom File=g01
Flow File=f01
Plan File=p01
Y Axis Title=Elevation
X Axis Title(PF)=Main Channel Distance
X Axis Title(XS)=Station
BEGIN DESCRIPTION:
UNT 166 IN BOCR
END DESCRIPTION:
DSS Export Rating Curves= 0
DSS Export Rating Curve Sorted= 0
DSS Export Volume Flow Curves= 0
DXF OffsetX= 0
DXF OffsetY= 0
DXF ScaleX= 1
DXF ScaleY= 10

--- UNT 166 IN BOCR.p01 (plan) ---

Plan Title=Multiple Run
Short Identifier=Multiple
Geom File=g01
Flow File=f01
Subcritical Flow
K Sum by GR= 0
Std Step Tol= 0.01
Critical Tol= 0.01
Num of Std Step Trials= 20
Max Error Tol= 0.3
Flow Tol Ratio= 0.001
Split Flow NTrial= 30
Split Flow Tol= 0.02
Split Flow Ratio= 0.02
Log Output Level= 0
Friction Slope Method= 1
Unsteady Friction Slope Method= 2
Unsteady Bridges Friction Slope Method= 1
Parabolic Critical Depth
Global Vel Dist=  1 , 1 , 1
Global Log Level= 0
CheckData=True
Encroach Param= -1, 0, 0, 0
BEGIN DESCRIPTION:
Multiple Run
END DESCRIPTION:

--- UNT 166 IN BOCR.f01 (steady flow) ---

Flow Title=Multiple
Number of Profiles=7
Profile Names=10-year,25-year,50-year,1pct_min,100-year,1pct_plu,500-year
River Rch & RM= UNT 166 IN BOCR,Reach-1,26857
     359     462     542     467     632     855     863
River Rch & RM= UNT 166 IN BOCR,Reach-1,25982
     580     767     916     803    1086    1469    1531
River Rch & RM= UNT 166 IN BOCR,Reach-1,14237
     722     961    1153    1014    1371    1854    1947
River Rch & RM= UNT 166 IN BOCR,Reach-1,4290
     898    1217    1478    1316    1779    2406    2589
Boundary for River Rch & Prof#=UNT 166 IN BOCR,Reach-1,1
Up Type=0
Dn Type=3
Dn Slope=0.005
Boundary for River Rch & Prof#=UNT 166 IN BOCR,Reach-1,2
Up Type=0
Dn Type=3
Dn Slope=0.005
Boundary for River Rch & Prof#=UNT 166 IN BOCR,Reach-1,3
Up Type=0
Dn Type=3
Dn Slope=0.005
Boundary for River Rch & Prof#=UNT 166 IN BOCR,Reach-1,4
Up Type=0
Dn Type=3
Dn Slope=0.005
Boundary for River Rch & Prof#=UNT 166 IN BOCR,Reach-1,5
Up Type=0
Dn Type=3
Dn Slope=0.005
Boundary for River Rch & Prof#=UNT 166 IN BOCR,Reach-1,6
Up Type=0
Dn Type=3
Dn Slope=0.005
Boundary for River Rch & Prof#=UNT 166 IN BOCR,Reach-1,7
Up Type=0
Dn Type=3
Dn Slope=0.005

--- UNT 166 IN BOCR.g01 (geometry) ---

Geom Title=Existing Conditions
Program Version=4.10

River Reach=UNT 166 IN BOCR ,Reach-1
Reach XY= 30
      3716354.75       10631220.      3716566.75       10630706.
       3716387.5       10630635.       3716249.5       10630152.
        3715793.       10630303.      3715754.25       10629867.
       3715484.5       10629863.      3715070.75       10628986.
        3714701.       10629006.      3714163.75       10628602.
        3713749.       10628610.       3713633.5       10628138.
      3713322.25       10627899.      3713241.75       10627326.
        3713649.       10626955.       3713545.5       10626629.
      3713866.25       10626529.      3713781.25       10626286.
      3713935.25       10626192.        3713778.       10626078.
        3714007.       10625967.       3714020.5       10625549.
        3714668.       10625031.       3714455.5       10624126.
      3713694.75       10623251.       3713381.5       10620444.
      3713038.75       10619350.      3710708.75       10617208.
      3707874.75       10616506.       3707449.5       10614980.

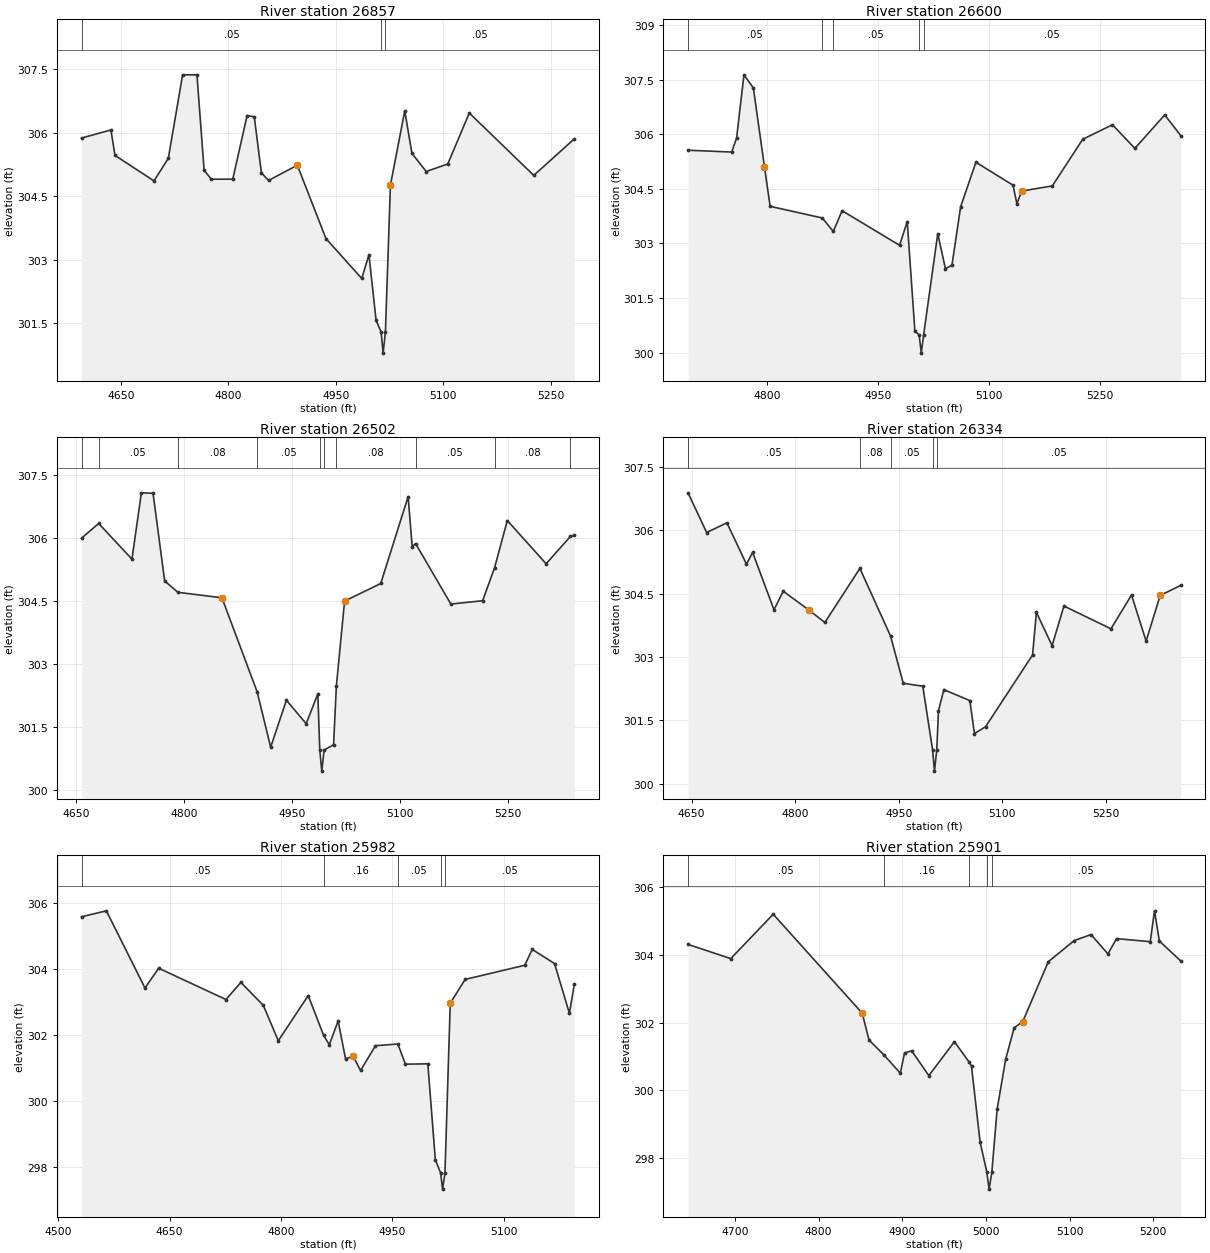
Type RM Length L Ch R = 1 ,26857   ,257,257,257
BEGIN DESCRIPTION:
UNT 166 IN BOCR 52.0
END DESCRIPTION:
XS GIS Cut Line= 2
      3716690.62      10631113.7      3716003.06     10631135.35
#Sta/Elev= 30
    4595  305.87    4636  306.06  4641.7  305.46  4696.1  304.86  4716.1  305.39
  4736.1  307.36  4756.1  307.36  4766.1  305.11  4776.1   304.9  4806.1   304.9
  4826.1   306.4  4836.1  306.37  4846.1  305.05  4856.1  304.87  4896.2  305.23
  4936.2   303.5  4986.2  302.56  4996.2  303.12  5006.2  301.57  5013.2   301.3
    5016   300.8  5019.2   301.3  5026.2  304.76  5046.2  306.51  5056.2  305.51
  5076.2  305.08  5106.3  305.26  5136.3  306.46  5226.3  304.99  5282.9  305.85
#Mann= 3 ,-1 , 0
    4595     .05       0  5013.2     .03       0  5019.2     .05       0
Bank Sta=4896.2,5026.2
XS Rating Curve= 0 ,0
Exp/Cntr=0.3,0.1

Type RM Length L Ch R = 1 ,26600   ,98,98,98
BEGIN DESCRIPTION:
Mapping XS 9c9367f6
END DESCRIPTION:
XS GIS Cut Line= 4
      3716687.81     10631092.03      3716488.15     10630987.87
       3716199.2     10630915.63      3716058.01     10630899.94
#Sta/Elev= 30
  4693.7  305.56  4752.7  305.51  4759.3   305.9  4769.2  307.63  4781.9  307.27
  4796.9   305.1  4804.5  304.02    4875   303.7  4889.7  303.33  4901.7   303.9
  4979.2  302.95  4989.6   303.6  4999.9   300.6  5005.7  300.49  5008.5  299.99
  5011.7  300.49  5030.8  303.27  5041.1  302.31  5049.9   302.4  5061.7  304.01
  5082.3  305.23  5132.4   304.6  5137.6  304.09  5144.2  304.44  5185.4  304.58
  5226.4  305.86  5266.6  306.26  5296.8  305.61  5337.1  306.53  5358.8  305.96
#Mann= 5 ,-1 , 0
  4693.7     .05       0    4875     .08       0  4889.7     .05       0
  5005.7     .03       0  5011.7     .05       0
Bank Sta=4796.9,5144.2
XS Rating Curve= 0 ,0
Exp/Cntr=0.3,0.1

Type RM Length L Ch R = 1 ,26502   ,168,168,168
BEGIN DESCRIPTION:
Mapping XS 431fd7cb
END DESCRIPTION:
XS GIS Cut Line= 3
      3716731.21     10631052.97      3716230.93     10630781.99
      3716123.34     10630737.73
#Sta/Elev= 30
  4657.4     306  4681.2  306.35  4727.5   305.5  4740.6  307.08  4756.8  307.07
    4773  304.98  4791.4  304.71  4852.6  304.58  4901.6  302.34  4920.4  301.02
  4942.3  302.14  4969.8  301.58    4986  302.29  4988.7  300.95  4991.5  300.45
  4994.7  300.95  5007.9  301.08  5011.8  302.48  5023.2   304.5  5073.5  304.92
  5111.6  306.99  5117.2   305.8    5122  305.87    5171  304.43  5215.2  304.51
  5231.9   305.3  5249.5  306.42  5303.5  305.39  5337.2  306.04  5342.7  306.07
#Mann= 10 ,-1 , 0
  4657.4     .08       0  4681.2     .05       0  4791.4     .08       0
  4901.6     .05       0  4988.7     .04       0  4994.7     .05       0
  5011.8     .08       0    5122     .05       0  5231.9     .08       0
  5337.2     .05       0
Bank Sta=4852.6,5023.2
XS Rating Curve= 0 ,0
Exp/Cntr=0.3,0.1

Type RM Length L Ch R = 1 ,26334   ,352,352,352
BEGIN DESCRIPTION:
Mapping XS 6a7dcdee
END DESCRIPTION:
XS GIS Cut Line= 3
      3716844.02     10630940.11      3716309.88     10630685.75
      3716190.37     10630662.31
#Sta/Elev= 30
  4644.8  306.89  4671.8  305.95  4701.1  306.18  4729.4   305.2  4738.3  305.48
  4769.3  304.12  4782.6  304.56  4820.2  304.11  4842.9  303.82  4893.6   305.1
    4938   303.5  4956.4  302.38  4984.7  302.31  4998.9   300.8  5001.6   300.3
  5004.9   300.8  5007.4  301.73  5015.2  302.23  5052.8  301.97  5059.5  301.19
  5075.5  301.35  5143.6  303.05  5149.2  304.06  5171.9  303.27    5189  304.21
  5257.1  303.67  5286.9  304.47    5308  303.38  5328.4  304.46  5358.2   304.7
#Mann= 5 ,-1 , 0
  4644.8     .05       0  4893.6     .08       0    4938     .05       0
  4998.9     .03       0  5004.9     .05       0
Bank Sta=4820.2,5328.4
XS Rating Curve= 0 ,0
Exp/Cntr=0.3,0.1

Type RM Length L Ch R = 1 ,25982   ,81,81,81
BEGIN DESCRIPTION:
Mapping XS a9256dba
END DESCRIPTION:
XS GIS Cut Line= 3
      3716852.76     10630575.54       3716303.1     10630640.68
        3716193.     10630636.33
#Sta/Elev= 30
  4531.3  305.59  4564.7  305.77  4616.7  303.43  4635.2  304.03  4725.8  303.08
  4745.9   303.6  4776.2   302.9  4796.3  301.83  4836.6   303.2  4857.4  301.99
    4865  301.71  4876.9  302.43  4886.9  301.28    4897  301.36  4907.1  300.93
  4927.2  301.68  4957.4  301.73  4967.5  301.12  4997.7  301.13  5007.8  298.22
  5014.8  297.83  5017.6  297.33  5020.8  297.83  5027.9  302.97    5048  303.69
  5128.3  304.12  5138.3   304.6  5168.4  304.17  5188.4  302.66    5195  303.54
#Mann= 5 ,-1 , 0
  4531.3     .05       0  4857.4     .16       0  4957.4     .05       0
  5014.8     .03       0  5020.8     .05       0
Bank Sta=4897,5027.9
XS Rating Curve= 0 ,0
Exp/Cntr=0.3,0.1

Type RM Length L Ch R = 1 ,25901   ,551,551,551
BEGIN DESCRIPTION:
UNT 166 IN BOCR 51.0
END DESCRIPTION:
XS GIS Cut Line= 2
      3716761.61     10630484.39      3716184.48     10630601.55
#Sta/Elev= 30
  4643.9  304.31    4695  303.89  4745.7   305.2  4852.1  302.28  4860.2  301.49
    4878  301.05  4897.6  300.51  4902.7  301.11  4911.2  301.17  4931.7  300.44
  4962.3  301.44  4979.8  300.84  4982.7  300.71  4992.9  298.49    5001  297.59
  5003.7  297.09    5007  297.59  5013.3  299.44  5023.5  300.92  5033.7  301.85
  5043.9  302.03  5074.5   303.8  5105.3  304.42  5125.5   304.6  5145.7  304.03
  5156.1  304.48  5196.3  304.39  5201.4   305.3  5207.2  304.41  5232.8  303.82
#Mann= 5 ,-1 , 0
  4643.9     .05       0    4878     .16       0  4979.8     .05       0
    5001     .03       0    5007     .05       0
Bank Sta=4852.1,5043.9
XS Rating Curve= 0 ,0
Exp/Cntr=0.3,0.1

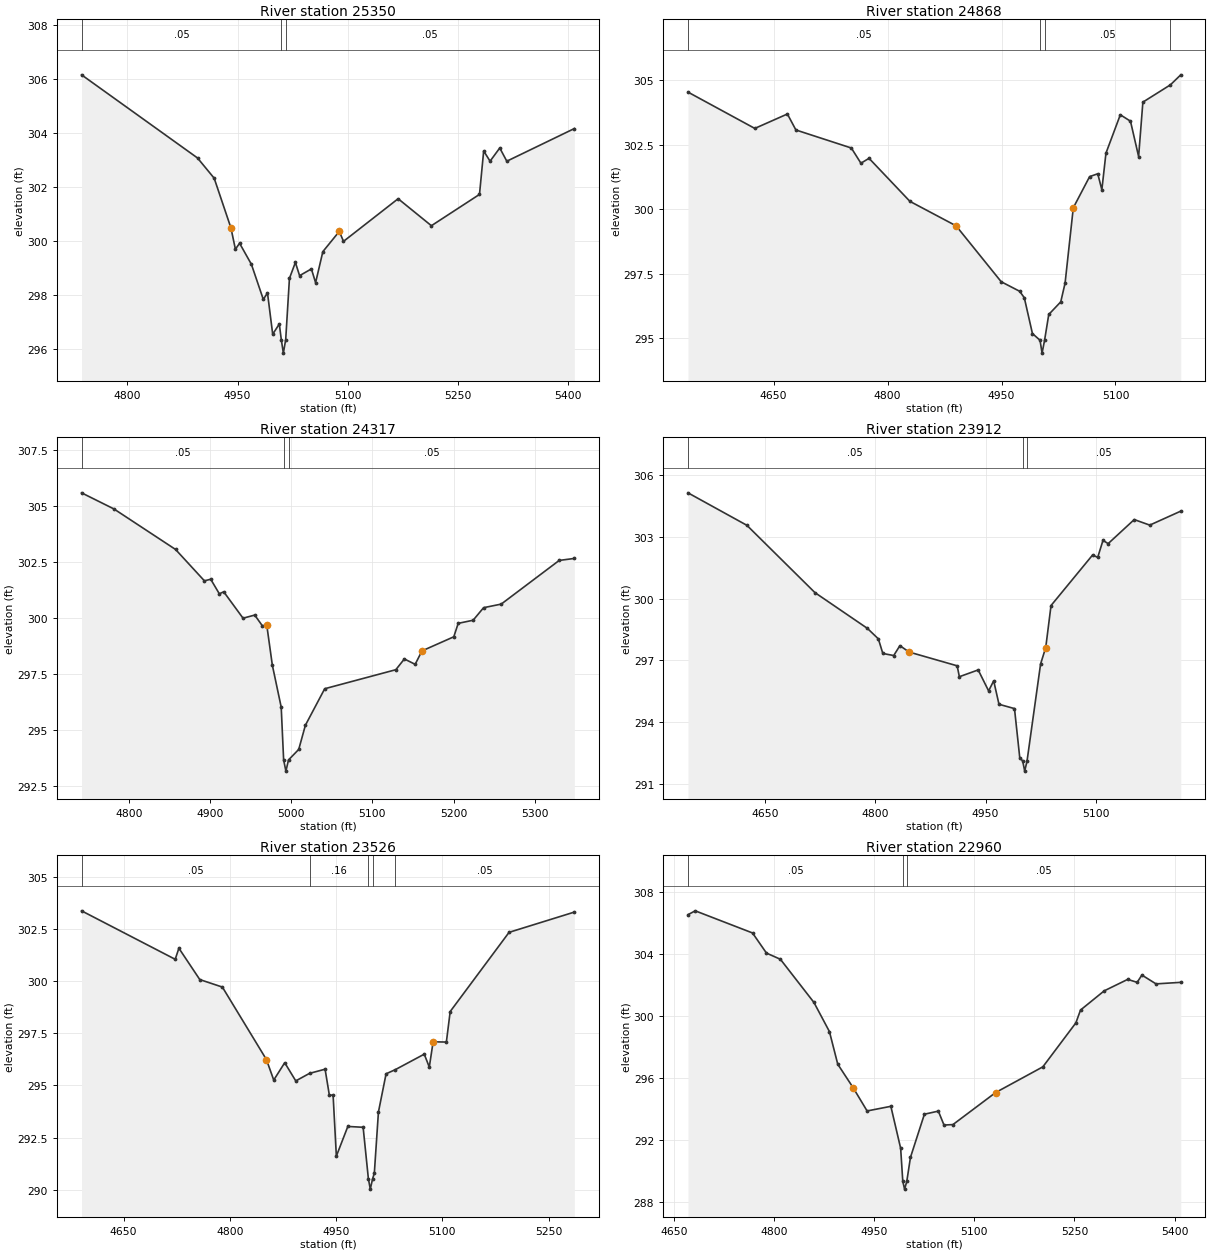
Type RM Length L Ch R = 1 ,25350   ,482,482,482
BEGIN DESCRIPTION:
UNT 166 IN BOCR 50.0
END DESCRIPTION:
XS GIS Cut Line= 2
       3716344.9     10629911.51      3716024.15       10630501.
#Sta/Elev= 30
  4737.6  306.14  4895.5  303.06  4918.2  302.31    4941  300.47  4947.1  299.68
  4952.8   299.9  4968.9  299.12  4985.1  297.82  4990.8  298.06  4997.9  296.53
  5006.9  296.91  5009.6  296.33  5012.4  295.83  5015.6  296.33  5020.7   298.6
  5028.8  299.19  5034.5   298.7  5050.6  298.95  5056.3  298.44  5066.2  299.59
  5088.6  300.34  5094.3  299.97  5168.7  301.55    5214  300.55  5279.5  301.71
  5285.2  303.32  5293.9  302.94  5307.1  303.43  5316.7  302.94  5408.7  304.15
#Mann= 3 ,-1 , 0
  4737.6     .05       0  5009.6     .03       0  5015.6     .05       0
Bank Sta=4941,5088.6
XS Rating Curve= 0 ,0
Exp/Cntr=0.3,0.1

Type RM Length L Ch R = 1 ,24868   ,551,551,551
BEGIN DESCRIPTION:
UNT 166 IN BOCR 49.0
END DESCRIPTION:
XS GIS Cut Line= 2
      3716015.05     10629898.47      3715776.34     10630501.76
#Sta/Elev= 30
  4537.2  304.55  4625.2  303.14  4668.1   303.7  4679.3  303.08  4752.3  302.38
  4764.9  301.79  4775.6  301.98  4829.4  300.31  4890.2  299.36  4949.6  297.19
  4973.9  296.82    4980  296.57  4990.7  295.18  5000.7  294.92  5003.4  294.42
  5006.7  294.92  5012.2  295.92    5028  296.41  5033.7  297.14  5044.5  300.06
    5066  301.27  5076.7  301.38  5082.1  300.76  5087.5  302.18  5106.4  303.67
  5119.8  303.42  5130.5  302.05  5136.1  304.16  5172.3  304.83    5186  305.22
#Mann= 4 ,-1 , 0
  4537.2     .05       0  5000.7     .03       0  5006.7     .05       0
  5172.3     .08       0
Bank Sta=4890.2,5044.5
XS Rating Curve= 0 ,0
Exp/Cntr=0.3,0.1

Type RM Length L Ch R = 1 ,24317   ,405,405,405
BEGIN DESCRIPTION:
UNT 166 IN BOCR 48.0
END DESCRIPTION:
XS GIS Cut Line= 2
       3716006.4     10629837.68      3715446.48     10630072.07
#Sta/Elev= 30
  4741.8  305.59  4781.7  304.87  4857.6  303.06  4893.1  301.66  4900.9  301.73
  4911.5  301.08  4916.9  301.17  4940.7  299.99  4955.1  300.13  4964.5  299.65
  4969.9  299.69  4976.8  297.89  4987.7  296.02  4990.7  293.66  4993.5  293.16
  4996.7  293.66  5009.3  294.13  5017.5  295.21  5041.3  296.84  5128.9  297.69
  5139.4  298.17  5152.7  297.93  5161.1  298.53  5200.3  299.16  5205.7  299.76
  5224.1   299.9    5237  300.46  5258.7  300.62  5330.1  302.57  5348.8  302.66
#Mann= 3 ,-1 , 0
  4741.8     .05       0  4990.7     .03       0  4996.7     .05       0
Bank Sta=4969.9,5161.1
XS Rating Curve= 0 ,0
Exp/Cntr=0.3,0.1

Type RM Length L Ch R = 1 ,23912   ,386,386,386
BEGIN DESCRIPTION:
UNT 166 IN BOCR 47.0
END DESCRIPTION:
XS GIS Cut Line= 3
      3715845.76     10629585.98      3715541.97     10629798.63
      3715325.86     10630006.09
#Sta/Elev= 30
  4545.2  305.14  4625.4  303.56  4717.9  300.29  4789.3  298.55  4804.2  298.04
  4810.3  297.33  4825.1  297.23  4833.5  297.71    4846   297.4  4911.4  296.73
  4914.4   296.2    4940  296.53  4954.2  295.51  4961.1     296  4968.3  294.86
  4989.4  294.65  4996.6  292.25  5000.5  292.11  5003.3  291.61  5006.5  292.11
  5024.9  296.82  5031.9  297.62  5039.1  299.66  5095.7  302.12  5102.6     302
  5109.8  302.83  5116.8  302.67  5152.3  303.84  5173.4  303.57  5215.6  304.25
#Mann= 3 ,-1 , 0
  4545.2     .05       0  5000.5     .03       0  5006.5     .05       0
Bank Sta=4846,5031.9
XS Rating Curve= 0 ,0
Exp/Cntr=0.3,0.1

Type RM Length L Ch R = 1 ,23526   ,566,566,566
BEGIN DESCRIPTION:
UNT 166 IN BOCR 46.0
END DESCRIPTION:
XS GIS Cut Line= 3
       3715741.6     10629390.65      3715403.08     10629481.79
      3715083.24     10629611.46
#Sta/Elev= 30
  4590.6  303.36  4722.8  301.04    4728  301.57  4757.5  300.07  4789.4  299.71
  4851.6  296.24  4861.9  295.26  4877.4  296.09    4893  295.22  4912.4  295.58
  4934.4  295.78  4940.4  294.54  4945.7  294.54  4950.3  291.62  4966.5  293.04
  4988.1     293  4995.5  290.54  4998.2  290.04  5001.5  290.54  5003.9   290.8
  5009.7  293.73  5020.5  295.56  5033.6  295.76  5074.4   296.5  5081.5  295.88
  5086.9  297.09  5105.6  297.08    5111  298.54  5194.1  302.33  5286.3   303.3
#Mann= 5 ,-1 , 0
  4590.6     .05       0  4912.4     .16       0  4995.5     .07       0
  5001.5     .16       0  5033.6     .05       0
Bank Sta=4851.6,5086.9
XS Rating Curve= 0 ,0
Exp/Cntr=0.3,0.1

Type RM Length L Ch R = 1 ,22960   ,422,422,422
BEGIN DESCRIPTION:
UNT 166 IN BOCR 45.0
END DESCRIPTION:
XS GIS Cut Line= 3
      3715411.77     10628917.55      3715068.88     10629164.95
      3714847.56     10629390.61
#Sta/Elev= 30
  4670.5  306.53  4681.4  306.78  4767.3  305.35  4788.2  304.05  4809.1  303.65
  4859.4  300.86  4882.6  298.98  4895.1  296.87  4918.2  295.35  4939.1  293.85
  4974.7  294.15  4989.4  291.44  4992.6   289.3  4995.3   288.8  4998.6   289.3
  5004.1  290.85    5025  293.64  5045.9  293.84  5054.4  292.94  5067.8  292.97
  5131.8  295.04  5202.6   296.7  5252.1  299.54  5259.1  300.37  5294.6  301.61
  5329.8  302.35    5344  302.16  5351.1  302.63  5372.3  302.06  5409.4  302.16
#Mann= 3 ,-1 , 0
  4670.5     .05       0  4992.6     .03       0  4998.6     .05       0
Bank Sta=4918.2,5131.8
XS Rating Curve= 0 ,0
Exp/Cntr=0.3,0.1

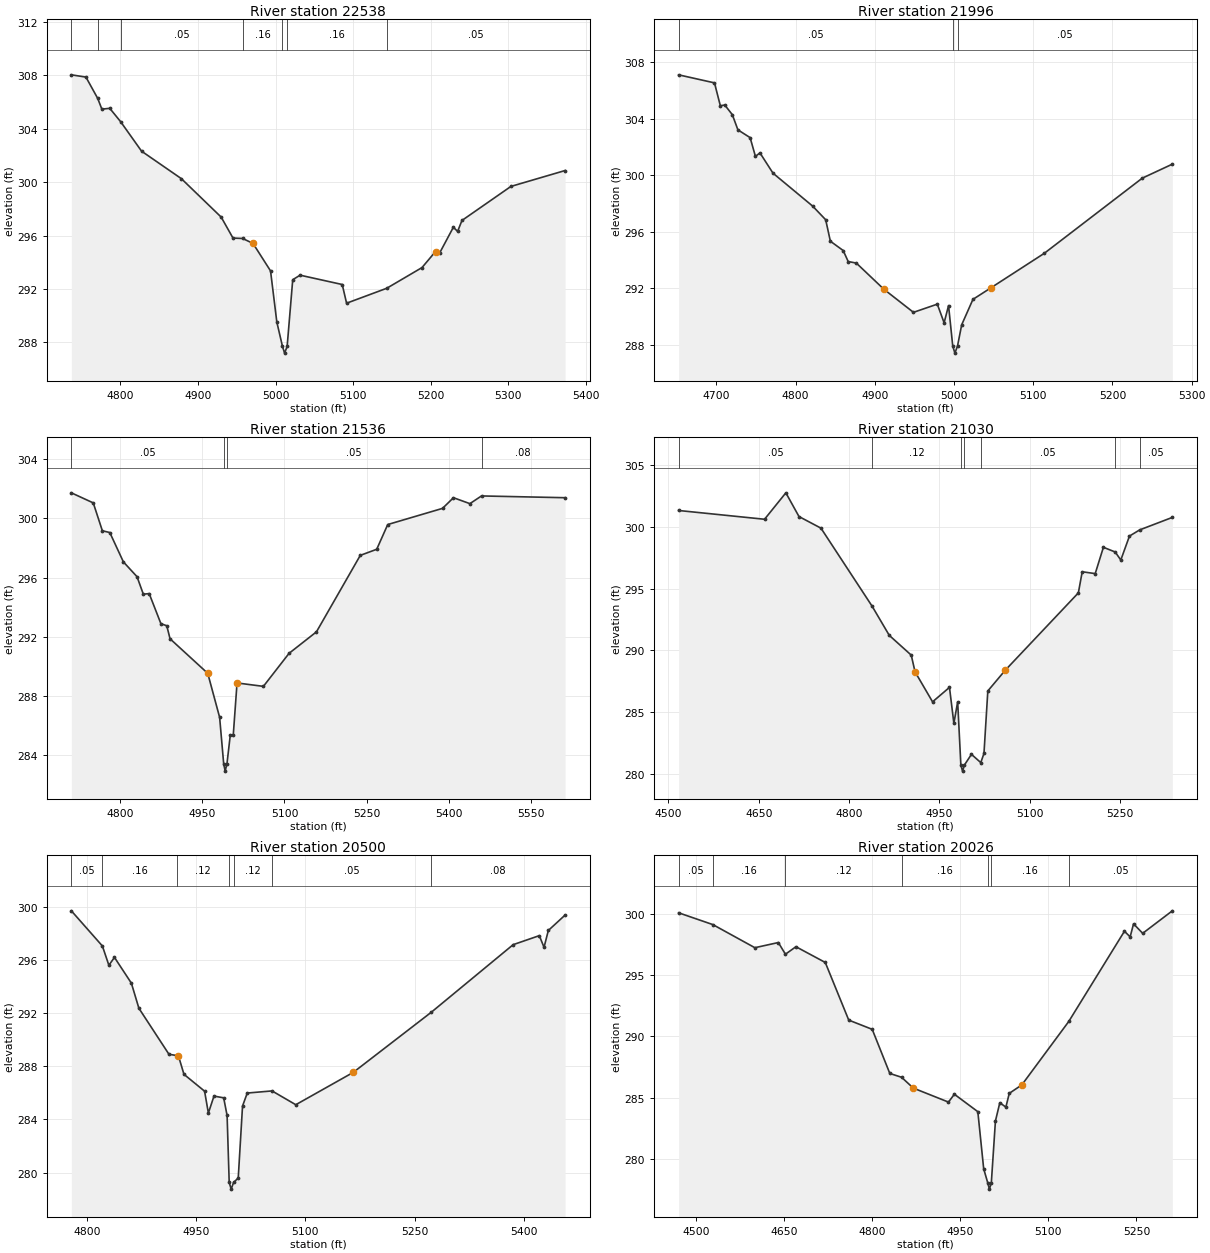
Type RM Length L Ch R = 1 ,22538   ,542,542,542
BEGIN DESCRIPTION:
UNT 166 IN BOCR 44.0
END DESCRIPTION:
XS GIS Cut Line= 3
      3714960.37     10628691.86      3714890.93     10629000.02
      3714756.38     10629290.81
#Sta/Elev= 30
  4736.8  308.05  4755.6  307.88  4770.8  306.28  4776.1  305.48  4786.3  305.54
  4800.3  304.54  4827.3  302.33  4878.6  300.27  4929.9  297.39  4945.1  295.82
  4957.5  295.79  4970.9  295.42  4993.5  293.36  5001.6  289.53  5008.9   287.7
  5011.6   287.2  5014.9   287.7  5022.1   292.7  5031.6  293.04  5085.9  292.34
  5091.5  290.94  5143.3  292.06  5188.7  293.61  5206.1  294.81  5211.6  294.72
  5229.1  296.63  5234.6  296.32  5240.2  297.14  5303.3  299.69  5373.1  300.88
#Mann= 7 ,-1 , 0
  4736.8     .05       0  4770.8     .16       0  4800.3     .05       0
  4957.5     .16       0  5008.9     .07       0  5014.9     .16       0
  5143.3     .05       0
Bank Sta=4970.9,5206.1
XS Rating Curve= 0 ,0
Exp/Cntr=0.3,0.1

Type RM Length L Ch R = 1 ,21996   ,460,460,460
BEGIN DESCRIPTION:
UNT 166 IN BOCR 43.0
END DESCRIPTION:
XS GIS Cut Line= 2
      3714669.59     10628539.92      3714383.94     10629093.91
#Sta/Elev= 30
  4652.3  307.12  4697.6  306.55    4705  304.93  4710.6  304.98  4720.1   304.3
  4727.2  303.22  4742.6  302.67  4749.3  301.34    4755  301.59  4771.5  300.15
  4821.5  297.82    4838  296.85  4843.9  295.33  4860.1  294.67  4866.4  293.89
  4876.7  293.78  4911.4  291.93  4948.8  290.29  4978.9  290.87  4987.5  289.55
  4993.1  290.77  4998.4   287.9  5001.1   287.4  5004.4   287.9  5009.7  289.41
  5023.9  291.21  5046.4  292.02  5113.9  294.47  5237.7   299.8  5275.6  300.79
#Mann= 3 ,-1 , 0
  4652.3     .05       0  4998.4     .03       0  5004.4     .05       0
Bank Sta=4911.4,5046.4
XS Rating Curve= 0 ,0
Exp/Cntr=0.3,0.1

Type RM Length L Ch R = 1 ,21536   ,506,506,506
BEGIN DESCRIPTION:
UNT 166 IN BOCR 42.0
END DESCRIPTION:
XS GIS Cut Line= 3
      3714248.58     10628327.25      3714114.02     10628683.18
      3714105.34     10629203.99
#Sta/Elev= 30
  4710.9  301.72  4750.9  301.04  4767.5  299.16  4781.1  299.04  4805.9  297.06
  4830.8  296.06  4842.3  294.88    4853  294.92  4874.4  292.89  4885.1  292.75
  4891.1  291.87  4959.9  289.54  4981.6  286.57    4989  283.44  4991.7  282.94
    4995  283.44  5001.1  285.39  5006.5  285.37  5013.4  288.89  5061.5  288.66
  5108.4  290.89  5158.4  292.34  5238.4   297.5  5268.4  297.91  5288.5  299.58
  5388.5  300.67  5408.5  301.39  5438.5  300.99  5459.7  301.51  5612.3  301.39
#Mann= 4 ,-1 , 0
  4710.9     .05       0    4989     .03       0    4995     .05       0
  5459.7     .08       0
Bank Sta=4959.9,5013.4
XS Rating Curve= 0 ,0
Exp/Cntr=0.3,0.1

Type RM Length L Ch R = 1 ,21030   ,530,530,530
BEGIN DESCRIPTION:
UNT 166 IN BOCR 41.0
END DESCRIPTION:
XS GIS Cut Line= 3
      3714099.65     10628260.16      3713699.61     10628560.19
      3713499.61     10628810.18
#Sta/Elev= 30
  4516.8  301.33  4659.6  300.62    4695  302.76  4716.8  300.84  4753.3   299.9
  4838.3  293.58  4866.8  291.22  4903.3  289.62  4909.6  288.27  4938.7  285.84
  4966.8  287.01  4974.1   284.1  4980.4  285.84  4985.7  280.73  4988.5  280.23
  4991.7  280.73  5003.3  281.59  5018.8  280.92  5024.1  281.66  5030.5  286.72
  5059.3  288.39  5180.9  294.66  5187.3  296.37  5208.9  296.22  5222.5  298.35
  5242.1  297.97  5251.4  297.32  5265.8  299.26  5282.8  299.76    5337  300.77
#Mann= 7 ,-1 , 0
  4516.8     .05       0  4838.3     .12       0  4985.7     .07       0
  4991.7     .12       0  5018.8     .05       0  5242.1     .08       0
  5282.8     .05       0
Bank Sta=4909.6,5059.3
XS Rating Curve= 0 ,0
Exp/Cntr=0.3,0.1

Type RM Length L Ch R = 1 ,20500   ,474,474,474
BEGIN DESCRIPTION:
UNT 166 IN BOCR 40.0
END DESCRIPTION:
XS GIS Cut Line= 3
      3713799.58      10628060.2      3713599.61     10628110.19
      3713199.63     10628360.18
#Sta/Elev= 30
  4778.9  299.72  4821.5  297.07  4830.4  295.62  4838.1  296.21  4861.3  294.27
  4871.6  292.38  4912.9  288.91  4924.5  288.81  4925.8  288.81  4933.5   287.4
  4961.8  286.13    4967  284.48  4974.7  285.76    4988  285.63  4992.7   284.3
  4995.6  279.25  4998.3  278.75  5001.6  279.25    5008  279.59  5013.9  285.01
  5020.4  285.99  5054.4  286.15    5087  285.11    5166  287.55  5273.3  292.09
  5385.4  297.17  5421.3  297.85  5427.8  296.97  5433.7  298.24  5456.7   299.4
#Mann= 7 ,-1 , 0
  4778.9     .05       0  4821.5     .16       0  4924.5     .12       0
  4995.6     .07       0  5001.6     .12       0  5054.4     .05       0
  5273.3     .08       0
Bank Sta=4925.8,5166
XS Rating Curve= 0 ,0
Exp/Cntr=0.3,0.1

Type RM Length L Ch R = 1 ,20026   ,515,515,515
BEGIN DESCRIPTION:
UNT 166 IN BOCR 39.0
END DESCRIPTION:
XS GIS Cut Line= 3
      3713849.59     10627860.19      3713299.61     10627860.19
      3713049.64     10628010.17
#Sta/Elev= 30
  4469.7  300.06  4528.1   299.1  4599.7  297.22  4639.7  297.64  4651.8  296.69
  4669.7   297.3  4719.7  296.02  4759.7  291.33  4799.7  290.58  4829.7  286.99
  4849.7  286.68  4869.7   285.8  4929.7  284.66  4939.7   285.3  4979.7  283.88
  4989.7  279.23  4996.7  278.08  4999.4  277.58  5002.7  278.08  5009.7  283.12
  5017.2  284.61  5027.5  284.25  5033.3  285.37  5054.7  286.06  5134.7  291.22
  5229.6  298.56  5239.3   298.1  5245.1  299.16  5260.7  298.39  5311.2  300.22
#Mann= 7 ,-1 , 0
  4469.7     .05       0  4528.1     .16       0  4651.8     .12       0
  4849.7     .16       0  4996.7     .07       0  5002.7     .16       0
  5134.7     .05       0
Bank Sta=4869.7,5054.7
XS Rating Curve= 0 ,0
Exp/Cntr=0.3,0.1

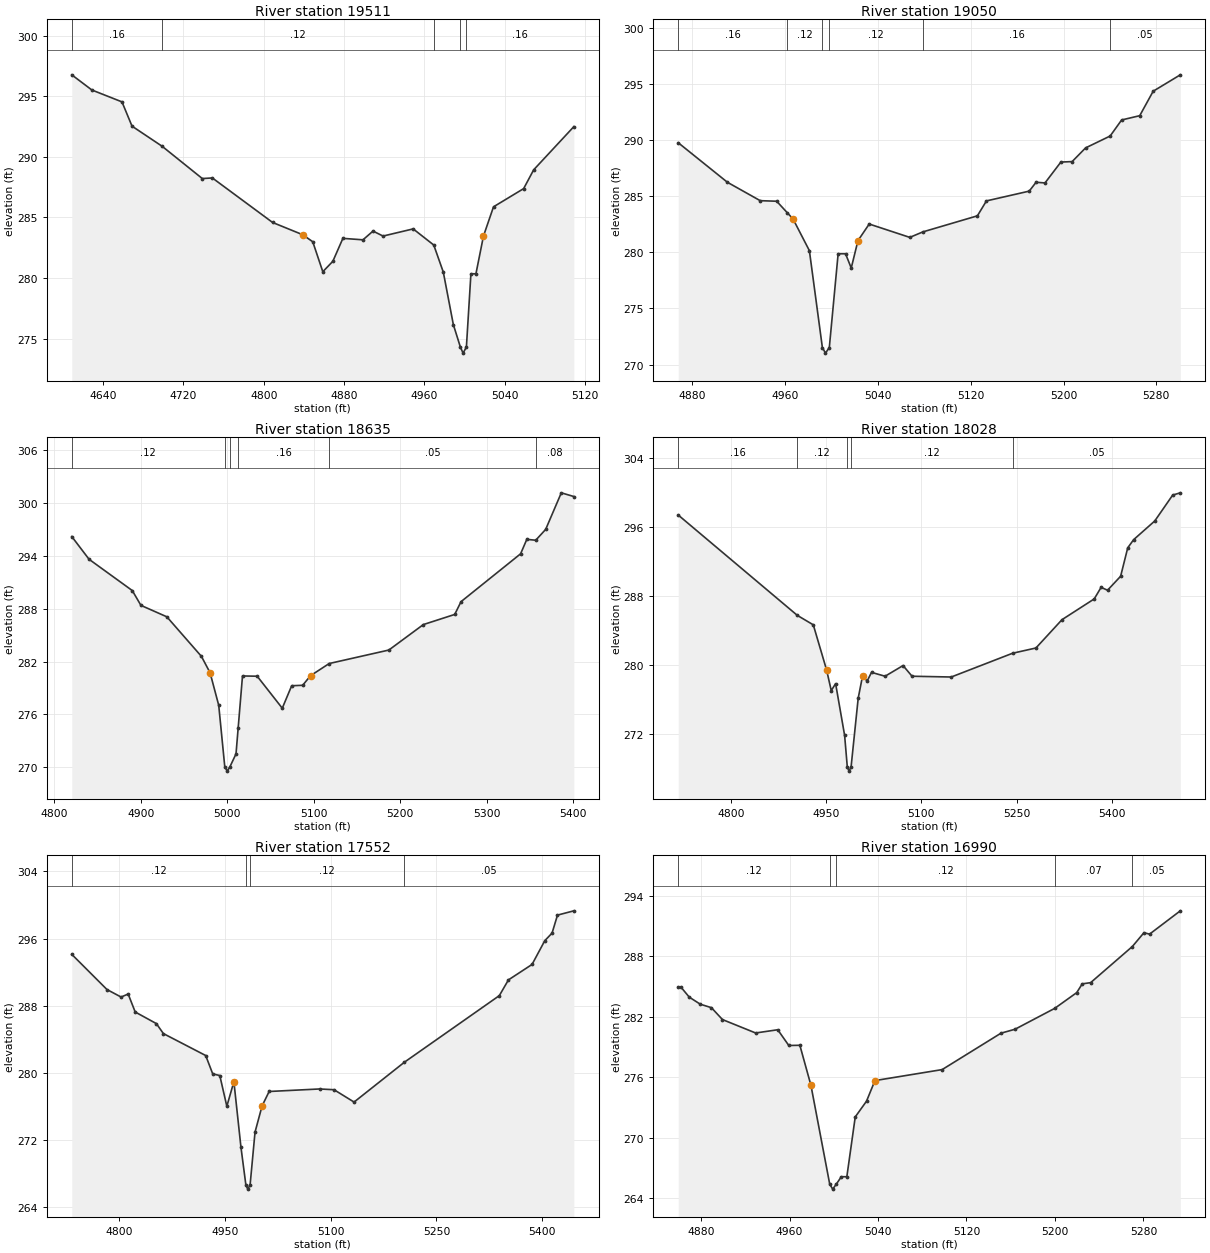
Type RM Length L Ch R = 1 ,19511   ,461,461,461
BEGIN DESCRIPTION:
UNT 166 IN BOCR 38.0
END DESCRIPTION:
XS GIS Cut Line= 3
       3713649.6     10627410.19      3713249.61     10627410.19
       3713149.6     10627410.19
#Sta/Elev= 30
  4608.8  296.76  4628.8  295.51  4658.8  294.53  4668.8  292.53  4698.8  290.87
  4738.8  288.21  4748.8  288.26  4808.8  284.59  4838.8  283.58  4848.8     283
  4858.8  280.53  4868.8  281.39  4878.8  283.28  4898.8  283.16  4908.8  283.88
  4918.8  283.47  4948.8  284.06  4969.3  282.73  4978.8   280.5  4988.8  276.17
  4995.8  274.32  4998.5  273.82  5001.8  274.32  5006.3  280.36  5011.3  280.36
  5018.8  283.47  5028.8  285.88  5058.8  287.38  5068.8  288.93  5108.8  292.49
#Mann= 5 ,-1 , 0
  4608.8     .16       0  4698.8     .12       0  4969.3     .16       0
  4995.8     .07       0  5001.8     .16       0
Bank Sta=4838.8,5018.8
XS Rating Curve= 0 ,0
Exp/Cntr=0.3,0.1

Type RM Length L Ch R = 1 ,19050   ,415,415,415
BEGIN DESCRIPTION:
UNT 166 IN BOCR 37.0
END DESCRIPTION:
XS GIS Cut Line= 3
      3713599.61     10627310.19      3713499.61     10627210.19
      3713249.58     10627060.17
#Sta/Elev= 30
  4867.7  289.76  4910.1  286.24  4938.4   284.6  4952.6  284.55  4961.7  283.53
  4966.7  282.97  4980.8  280.15    4992  271.52  4994.7  271.02    4998  271.52
  5005.6  279.87    5012  279.87  5016.9   278.6  5022.7  281.04  5032.4  282.52
  5067.4  281.33  5078.7  281.82  5125.7  283.25  5133.5  284.58  5170.4  285.45
  5176.3  286.24    5184  286.18  5197.7  288.04  5207.4  288.08    5219   289.3
  5240.2  290.36  5250.1  291.79  5265.7  292.17  5277.3  294.35  5300.7  295.81
#Mann= 6 ,-1 , 0
  4867.7     .16       0  4961.7     .12       0    4992     .07       0
    4998     .12       0  5078.7     .16       0  5240.2     .05       0
Bank Sta=4966.7,5022.7
XS Rating Curve= 0 ,0
Exp/Cntr=0.3,0.1

Type RM Length L Ch R = 1 ,18635   ,607,607,607
BEGIN DESCRIPTION:
UNT 166 IN BOCR 36.0
END DESCRIPTION:
XS GIS Cut Line= 3
      3713799.63     10626860.19      3713599.61     10626860.19
      3713249.62     10626710.19
#Sta/Elev= 30
    4820  296.19    4840  293.61    4890  290.06    4900  288.38    4930  287.08
    4970  282.59    4980  280.73    4990  277.04    4997  270.07  4999.8  269.57
    5003  270.07    5010  271.53  5012.5  274.48  5017.5  280.37  5034.5  280.34
  5063.5  276.71  5074.4  279.26  5087.1  279.31  5096.2   280.4  5117.8  281.78
  5186.8  283.31  5226.7   286.2    5263  287.35  5270.3   288.8  5339.2  294.23
  5346.4  295.87  5356.7  295.77  5368.2     297  5386.3  301.15  5400.8  300.73
#Mann= 6 ,-1 , 0
    4820     .12       0    4997     .07       0    5003     .12       0
  5012.5     .16       0  5117.8     .05       0  5356.7     .08       0
Bank Sta=4980,5096.2
XS Rating Curve= 0 ,0
Exp/Cntr=0.3,0.1

Type RM Length L Ch R = 1 ,18028   ,476,476,476
BEGIN DESCRIPTION:
UNT 166 IN BOCR 35.0
END DESCRIPTION:
XS GIS Cut Line= 3
      3714053.28     10626747.44      3713771.14     10626452.27
      3713397.92     10626365.48
#Sta/Elev= 30
  4716.7   297.4  4904.4  285.75  4929.6  284.65  4950.7  279.38  4957.9  277.01
  4964.8  277.82    4979  271.81  4983.2  268.16    4986  267.66  4989.2  268.16
  5000.4  276.13  5007.3  278.72  5014.5  278.12  5021.4  279.13  5042.8  278.68
  5071.1  279.92  5085.3  278.68  5147.1  278.59  5243.8  281.35  5280.6  281.96
  5321.7  285.25  5372.5  287.66  5383.3     289  5393.5  288.67  5414.1  290.29
  5425.3  293.59  5434.6  294.54  5467.9  296.71  5496.2  299.72  5508.2  299.98
#Mann= 5 ,-1 , 0
  4716.7     .16       0  4904.4     .12       0  4983.2     .07       0
  4989.2     .12       0  5243.8     .05       0
Bank Sta=4950.7,5007.3
XS Rating Curve= 0 ,0
Exp/Cntr=0.3,0.1

Type RM Length L Ch R = 1 ,17552   ,562,562,562
BEGIN DESCRIPTION:
UNT 166 IN BOCR 34.0
END DESCRIPTION:
XS GIS Cut Line= 3
      3714199.59     10626210.19      3713899.61     10626210.19
       3713499.6     10626110.19
#Sta/Elev= 30
  4732.7  294.12  4782.7  289.93  4802.7  289.04  4812.7   289.4  4822.7  287.26
  4852.7  285.88  4862.7  284.69  4922.7  282.08  4932.7  279.89  4942.7   279.7
  4952.7  276.04  4962.7  278.97  4972.7  271.18  4979.7  266.68  4982.4  266.18
  4985.7  266.68  4992.7  272.97  5002.7  276.08  5012.7   277.8  5084.2   278.1
  5104.8  278.01  5133.2  276.54  5204.7  281.29  5339.3  289.21  5352.2  291.08
  5385.7  292.92  5403.8  295.75  5414.1  296.65  5421.8  298.79    5445   299.3
#Mann= 4 ,-1 , 0
  4732.7     .12       0  4979.7     .07       0  4985.7     .12       0
  5204.7     .05       0
Bank Sta=4962.7,5002.7
XS Rating Curve= 0 ,0
Exp/Cntr=0.3,0.1

Type RM Length L Ch R = 1 ,16990   ,485,485,485
BEGIN DESCRIPTION:
UNT 166 IN BOCR 33.0
END DESCRIPTION:
XS GIS Cut Line= 3
      3714149.61     10625960.19      3713999.61     10625960.19
      3713699.64     10625910.19
#Sta/Elev= 30
  4859.3  284.92  4861.8  284.92  4869.3  283.93  4879.3  283.23  4889.3  282.89
  4899.3  281.71  4929.3  280.38  4949.3   280.7  4959.3  279.14  4969.3  279.16
  4979.3   275.2  4996.3   265.4    4999   264.9  5002.3   265.4  5006.8  266.13
  5011.8  266.13  5019.4  272.06  5029.6  273.62  5037.2  275.66    5098  276.75
  5151.2  280.36  5163.9  280.75  5199.8  282.82  5219.7  284.38  5224.7  285.25
  5232.3  285.37    5270  288.95  5280.5  290.32  5285.6  290.18  5313.4  292.49
#Mann= 5 ,-1 , 0
  4859.3     .12       0  4996.3     .07       0  5002.3     .12       0
  5199.8     .07       0    5270     .05       0
Bank Sta=4979.3,5037.2
XS Rating Curve= 0 ,0
Exp/Cntr=0.3,0.1

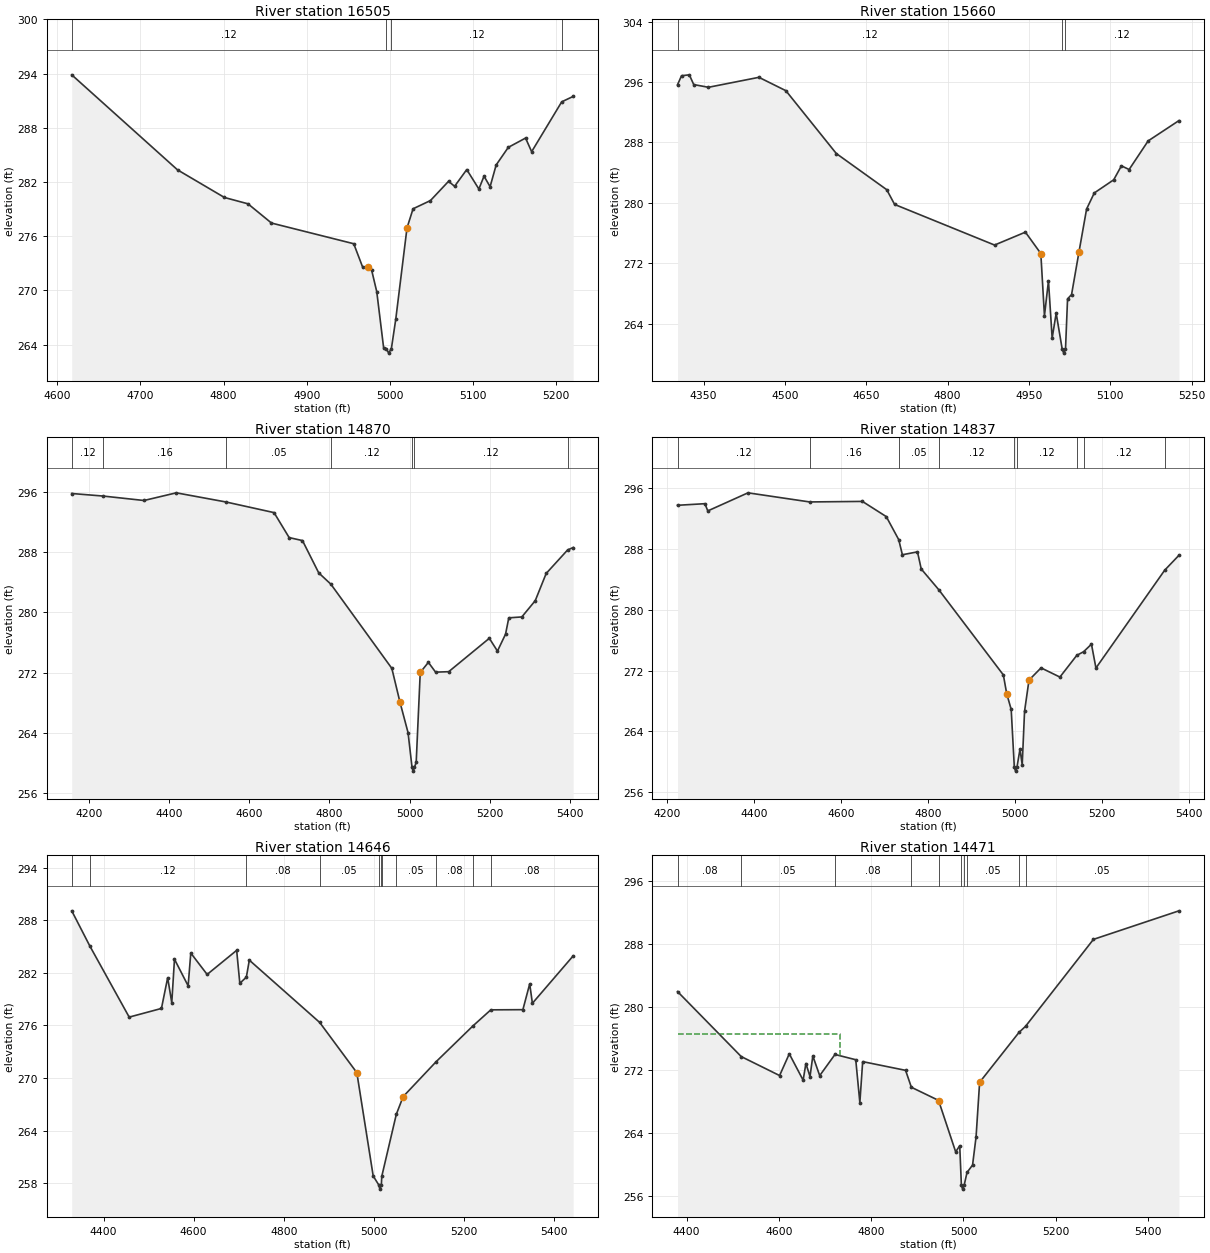
Type RM Length L Ch R = 1 ,16505   ,845,845,845
BEGIN DESCRIPTION:
UNT 166 IN BOCR 32.0
END DESCRIPTION:
XS GIS Cut Line= 3
       3714299.6     10625810.18      3714049.61     10625560.19
      3713849.64     10625410.21
#Sta/Elev= 30
  4617.3  293.87  4744.6  283.35  4801.1  280.29  4829.4  279.59  4857.7  277.46
  4956.7  275.17  4967.3  272.61    4974  272.61  4978.1   272.3  4984.4  269.86
  4992.7  263.63    4996  263.56  4998.7  263.06    5002  263.56  5007.3  266.83
  5020.8  276.92  5028.1  279.04    5049  279.95  5070.8  282.08  5078.1  281.53
  5092.7  283.38  5107.3  281.23  5113.5  282.65  5120.8  281.48  5128.1  283.89
  5142.7  285.84  5163.5  286.87  5170.8  285.36    5207  290.88  5220.8  291.48
#Mann= 4 ,-1 , 0
  4617.3     .12       0    4996     .07       0    5002     .12       0
    5207     .05       0
Bank Sta=4974,5020.8
XS Rating Curve= 0 ,0
Exp/Cntr=0.3,0.1

Type RM Length L Ch R = 1 ,15660   ,790,790,790
BEGIN DESCRIPTION:
UNT 166 IN BOCR 31.0
END DESCRIPTION:
XS GIS Cut Line= 3
      3714884.33     10625666.66       3714422.1     10625302.08
      3714195.62     10625054.03
#Sta/Elev= 30
  4301.9  295.63  4309.3  296.83  4323.7  296.95  4331.8  295.66    4359   295.3
    4452  296.62  4501.7  294.85  4594.7  286.53  4687.7  281.74  4702.2  279.79
  4886.5  274.41  4943.4  276.12  4971.8  273.29  4978.5  265.05  4985.9  269.68
  4992.7  262.08  5000.1  265.39  5011.3   260.6  5014.1   260.1  5017.3   260.6
  5021.1  267.28  5028.5  267.86  5042.1  273.47  5056.2  279.18  5070.4  281.31
  5106.2  283.05  5120.4   284.9  5134.6  284.41  5169.7   288.2  5226.5  290.89
#Mann= 3 ,-1 , 0
  4301.9     .12       0  5011.3     .07       0  5017.3     .12       0
Bank Sta=4971.8,5042.1
XS Rating Curve= 0 ,0
Exp/Cntr=0.3,0.1

Type RM Length L Ch R = 1 ,14870   ,33,33,33
BEGIN DESCRIPTION:
UNT 166 IN BOCR 30.0
END DESCRIPTION:
XS GIS Cut Line= 3
      3715446.43     10624976.56      3714955.95     10624887.58
      3714213.12     10625011.03
#Sta/Elev= 30
  4156.7   295.8  4235.3  295.46    4337  294.87  4417.7  295.89  4541.9  294.67
  4661.6  293.26  4699.3  289.94  4732.6  289.54  4773.1  285.25  4803.5  283.74
  4955.6  272.55  4975.9  268.06  4996.1     264    5006  259.39  5008.7  258.89
    5012  259.39  5016.4  260.06  5026.5  272.01  5046.8  273.35  5064.8  272.05
  5097.5  272.11  5198.9  276.55  5219.2  274.85  5239.4   277.1  5247.5  279.27
    5280  279.39  5313.5  281.55  5340.8  285.17  5394.2  288.29  5408.2  288.62
#Mann= 7 ,-1 , 0
  4156.7     .12       0  4235.3     .16       0  4541.9     .05       0
  4803.5     .12       0    5006     .07       0    5012     .12       0
  5394.2     .08       0
Bank Sta=4975.9,5026.5
XS Rating Curve= 0 ,0
Exp/Cntr=0.3,0.1

Type RM Length L Ch R = 1 ,14837   ,191,191,191
BEGIN DESCRIPTION:
Mapping XS 5355a65e
END DESCRIPTION:
XS GIS Cut Line= 2
      3715367.54     10624741.76      3714243.53     10624994.14
#Sta/Elev= 30
  4224.1  293.76    4287  293.97  4293.7  293.02    4386   295.4  4527.7   294.2
  4648.9  294.27  4703.7  292.27  4732.3  289.24  4740.7  287.25  4775.4  287.63
    4784  285.38  4824.4  282.64  4972.7  271.43  4980.4  268.96  4990.7  266.89
  4997.9  259.27  5000.7  258.77  5003.9  259.27  5010.9  261.66    5016  259.62
  5021.4  266.65  5031.6  270.75  5059.3  272.36  5102.6  271.15  5141.4  274.01
  5157.1  274.49  5175.1  275.48  5185.4  272.34  5343.4  285.22  5376.1  287.18
#Mann= 9 ,-1 , 0
  4224.1     .12       0  4527.7     .16       0  4732.3     .05       0
  4824.4     .12       0  4997.9     .07       0  5003.9     .12       0
  5141.4     .05       0  5157.1     .12       0  5343.4     .08       0
Bank Sta=4980.4,5031.6
XS Rating Curve= 0 ,0
Exp/Cntr=0.3,0.1

Type RM Length L Ch R = 1 ,14646   ,175,175,175
BEGIN DESCRIPTION:
Mapping XS 379cab6d
END DESCRIPTION:
XS GIS Cut Line= 2
      3715156.59     10624361.54      3714223.16     10624967.36
#Sta/Elev= 30
  4329.4  289.08  4369.7  285.05  4456.9  276.95  4528.5  277.94  4542.3  281.45
  4551.4  278.59  4557.4  283.56  4587.7  280.52  4593.6  284.26  4629.9  281.82
  4695.4  284.57  4702.4  280.81  4716.9  281.51  4723.5  283.45  4879.7  276.34
  4962.1  270.61  4998.4  258.82  5010.5  257.82  5013.3  257.32  5016.5  257.82
  5017.4  258.77  5049.7  265.86  5064.9  267.88  5138.4  271.88  5219.8  275.95
  5259.4  277.78  5330.6   277.8  5345.7  280.74  5351.7  278.53  5442.2  283.94
#Mann= 11 ,-1 , 0
  4329.4     .05       0  4369.7     .12       0  4716.9     .08       0
  4879.7     .05       0  5010.5     .03       0  5016.5     .05       0
  5017.4     .08       0  5049.7     .05       0  5138.4     .08       0
  5219.8     .05       0  5259.4     .08       0
Bank Sta=4962.1,5064.9
XS Rating Curve= 0 ,0
Exp/Cntr=0.3,0.1

Type RM Length L Ch R = 1 ,14471   ,234,234,234
BEGIN DESCRIPTION:
UNT 166 IN BOCR 29.0
END DESCRIPTION:
XS GIS Cut Line= 3
      3715008.12     10624241.77      3714547.18     10624551.67
      3714096.69      10624832.9
#Sta/Elev= 30
  4380.4  281.99  4518.5  273.72  4601.6  271.31  4622.6  274.07  4652.6  270.72
  4658.6  272.84  4667.5  271.18  4673.6   273.8  4688.5   271.3  4721.6  273.99
  4766.6  273.32  4775.5  267.87  4781.6  273.08  4874.6  271.97  4887.1  269.82
    4946  268.15  4946.6  268.04  4983.1  261.61  4991.9  262.39  4995.5  257.37
  4998.2  256.87  5001.5  257.37  5007.7  258.99  5019.7  259.93  5027.3  263.51
    5035  270.45  5120.4   276.8  5134.5  277.57  5281.6  288.62  5466.9  292.25
#Mann= 10 ,-1 , 0
  4380.4     .08       0  4518.5     .05       0  4721.6     .08       0
  4887.1     .16       0    4946     .08       0  4995.5     .07       0
  5001.5     .08       0  5007.7     .05       0  5120.4     .08       0
  5134.5     .05       0
#XS Ineff= 2 , 0
         4732.95  276.58
Permanent Ineff=
       F       F
Bank Sta=4946.6,5035
XS Rating Curve= 0 ,0
Exp/Cntr=0.3,0.1