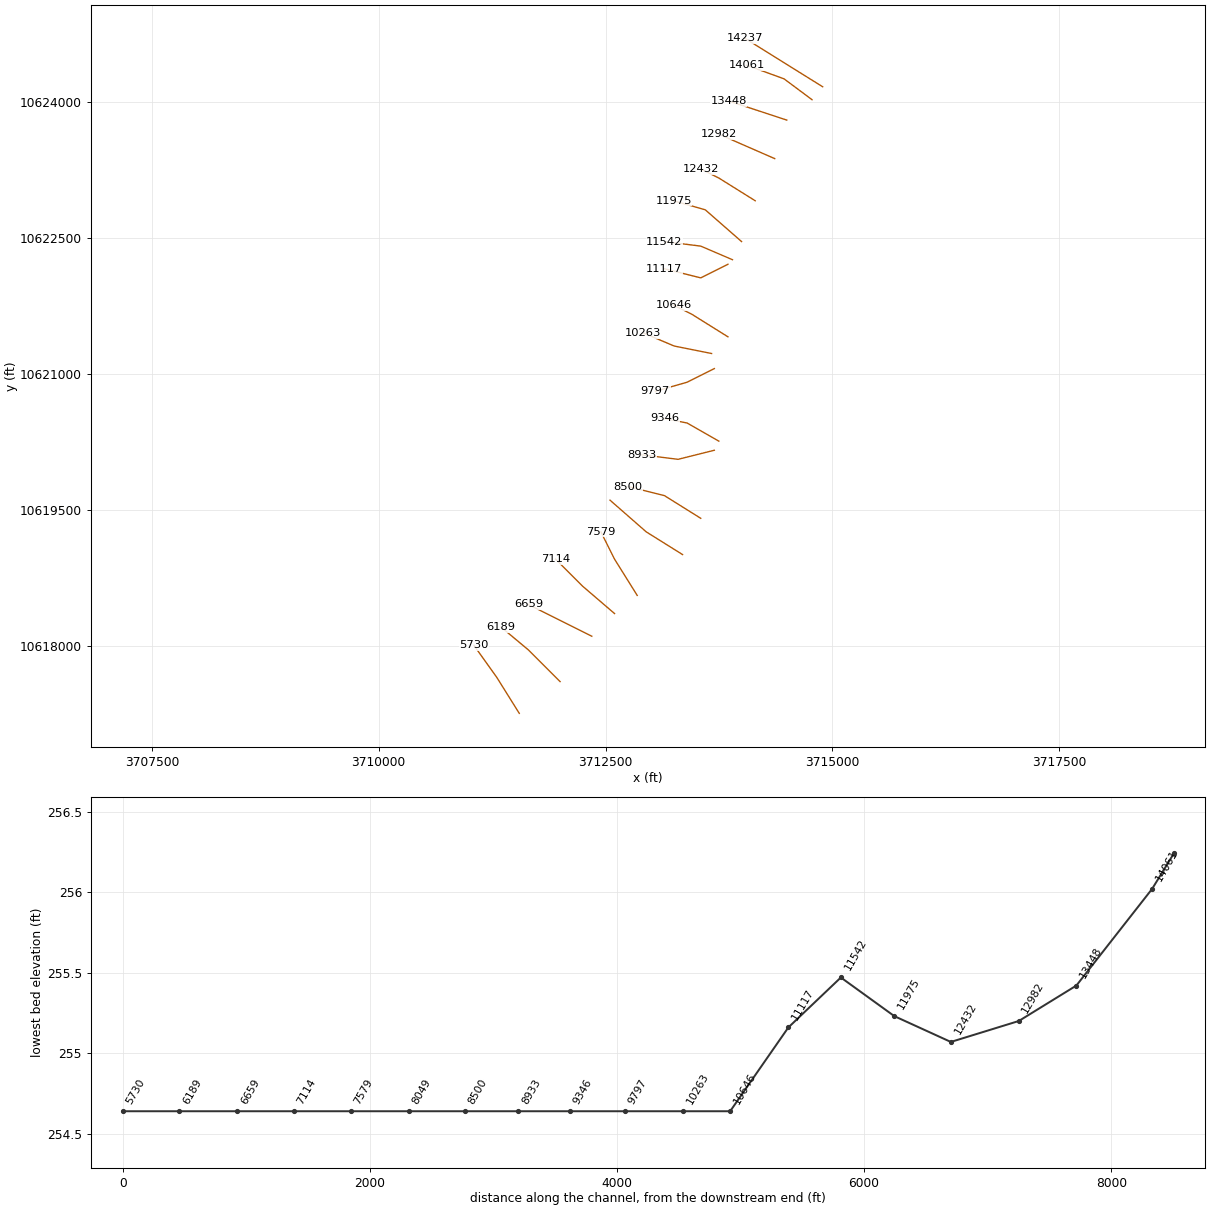
HEC-RAS study UNT 166 IN BOCR.prj: UNT 166 IN BOCR Base Level Engineering

--- UNT 166 IN BOCR.g01 (geometry) --- (continued)

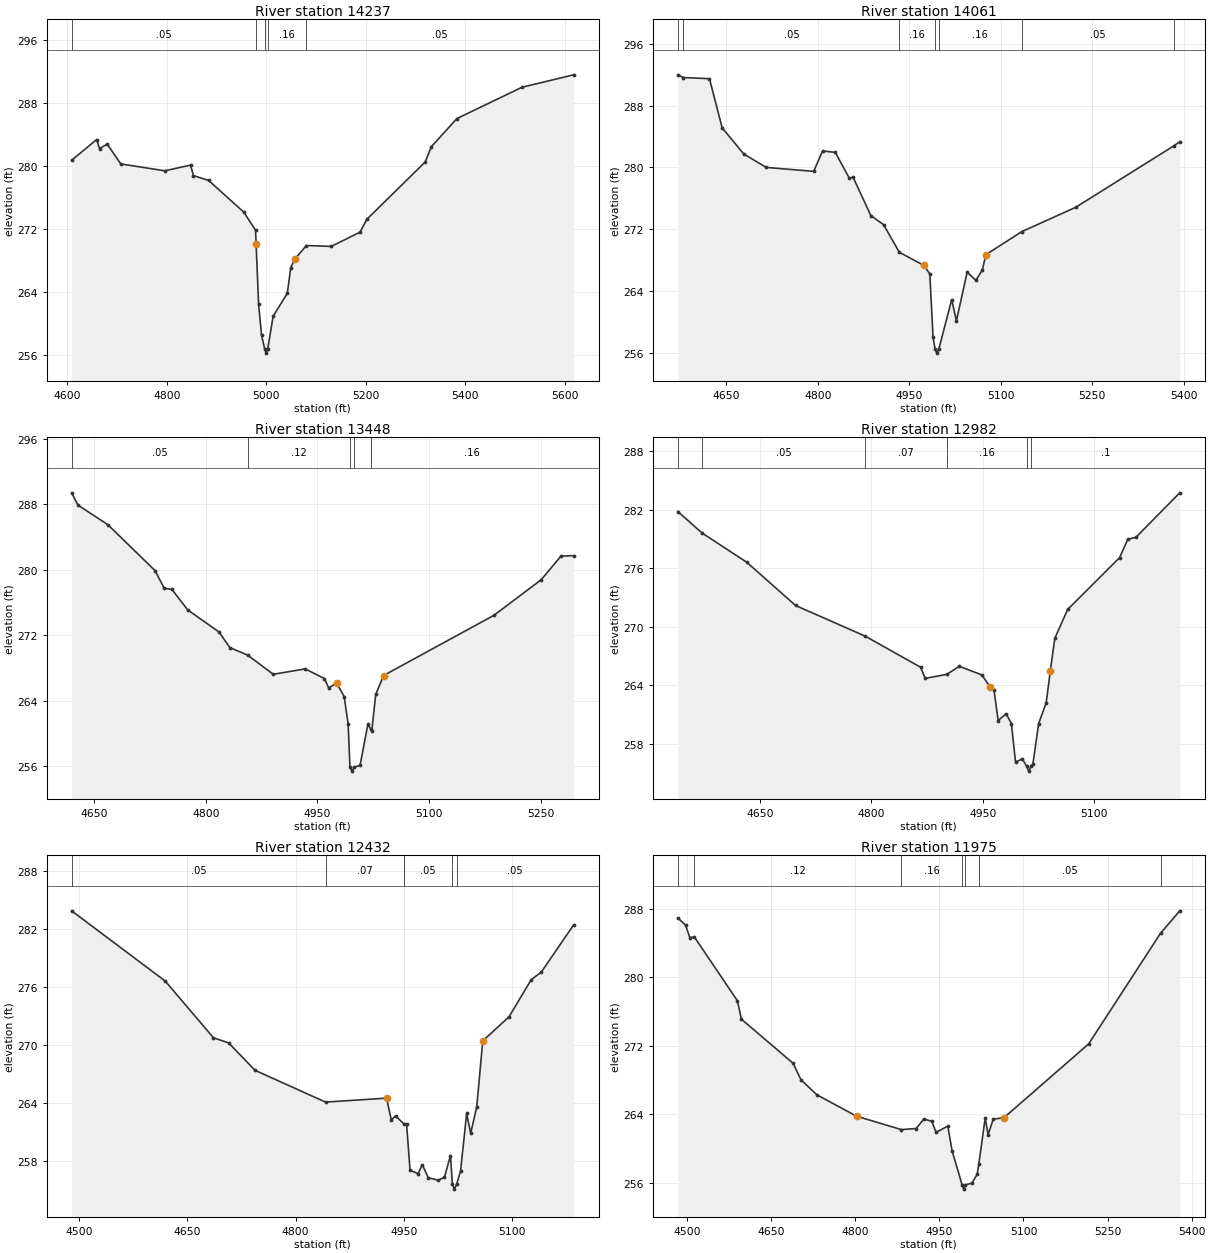
Type RM Length L Ch R = 1 ,14237   ,176,176,176
BEGIN DESCRIPTION:
Mapping XS 4912046b
END DESCRIPTION:
XS GIS Cut Line= 2
      3714893.55     10624166.24      3714036.76     10624700.11
#Sta/Elev= 30
  4608.5  280.76  4658.8  283.39  4664.7  282.23    4680  282.82  4707.4  280.29
  4795.7  279.42  4847.6  280.14  4853.5  278.81  4884.1  278.19  4954.8  274.16
  4978.4  271.86  4979.5  270.16  4984.5  262.46  4990.4  258.56  4996.8  256.74
  4999.6  256.24  5002.8  256.74  5013.7  260.92  5042.3  263.85  5049.1  267.09
  5057.7  268.22  5080.6  269.92  5130.8  269.81  5188.6  271.62  5202.3  273.26
  5319.6  280.54  5331.9  282.48  5383.3  286.06  5514.3  290.04    5618  291.62
#Mann= 5 ,-1 , 0
  4608.5     .05       0  4979.5     .16       0  4996.8     .07       0
  5002.8     .16       0  5080.6     .05       0
Bank Sta=4979.5,5057.7
XS Rating Curve= 0 ,0
Exp/Cntr=0.3,0.1

Type RM Length L Ch R = 1 ,14061   ,613,613,613
BEGIN DESCRIPTION:
UNT 166 IN BOCR 28.0
END DESCRIPTION:
XS GIS Cut Line= 3
      3714775.81     10624023.89      3714467.67      10624253.9
      3714055.34     10624403.64
#Sta/Elev= 30
  4570.6  291.97  4579.7  291.62  4622.5  291.47  4643.3  285.13  4678.7  281.75
  4715.6  280.01  4793.4   279.5    4808  282.13  4828.8  281.96  4851.8  278.63
    4858  278.75  4887.2  273.79  4908.1  272.61  4933.9  269.05  4974.3  267.34
  4983.9  266.25  4989.2  258.09  4992.6  256.52  4995.4  256.02  4998.6  256.52
  5019.8  262.94  5027.5  260.18  5045.1  266.48  5059.4  265.43  5070.1  266.77
  5075.7  268.73  5134.6  271.71  5223.5  274.87    5385  282.84  5393.8  283.32
#Mann= 7 ,-1 , 0
  4570.6     .16       0  4579.7     .05       0  4933.9     .16       0
  4992.6     .07       0  4998.6     .16       0  5134.6     .05       0
    5385     .16       0
Bank Sta=4974.3,5075.7
XS Rating Curve= 0 ,0
Exp/Cntr=0.3,0.1

Type RM Length L Ch R = 1 ,13448   ,466,466,466
BEGIN DESCRIPTION:
UNT 166 IN BOCR 27.0
END DESCRIPTION:
XS GIS Cut Line= 2
      3714497.69     10623799.07      3713857.12     10624009.99
#Sta/Elev= 30
  4619.7  289.42  4628.2  287.92  4668.2  285.54  4731.7  279.93    4744  277.78
  4754.5  277.61  4775.6  275.12  4817.7  272.42  4832.3  270.51  4856.3  269.59
  4890.6  267.25  4933.5  267.91  4959.4  266.73  4965.1  265.58  4975.6  266.19
  4985.9  264.53  4991.2  261.19  4993.7  255.92  4996.4  255.42  4999.7  255.92
  5007.2  256.11  5017.7  261.13  5021.4   260.6    5023  260.37  5028.3  264.79
  5038.8   267.1  5187.2  274.46  5250.7  278.81  5277.2  281.69  5294.1  281.75
#Mann= 5 ,-1 , 0
  4619.7     .05       0  4856.3     .12       0  4993.7     .07       0
  4999.7     .12       0  5021.4     .16       0
Bank Sta=4975.6,5038.8
XS Rating Curve= 0 ,0
Exp/Cntr=0.3,0.1

Type RM Length L Ch R = 1 ,12982   ,550,550,550
BEGIN DESCRIPTION:
UNT 166 IN BOCR 26.0
END DESCRIPTION:
XS GIS Cut Line= 2
      3714364.92     10623374.57      3713745.39     10623645.29
#Sta/Elev= 30
  4539.4  281.81  4572.3   279.6  4632.5   276.6    4698  272.18    4792  269.03
  4866.4  265.85  4872.6  264.71  4901.8  265.12  4918.6  265.95    4949  265.06
  4959.9  263.85  4965.4  263.48  4970.9  260.39  4981.7  261.08  4988.8  260.06
  4994.3  256.11  5003.5  256.47  5009.2   255.7    5012   255.2  5015.2   255.7
  5017.7  255.91  5025.4  260.07  5035.6   262.2  5041.1  265.43  5047.2  268.82
  5064.5  271.77  5134.5  277.09  5145.6  278.98  5156.3  279.16  5215.5  283.73
#Mann= 6 ,-1 , 0
  4539.4     .07       0  4572.3     .05       0    4792     .07       0
  4901.8     .16       0  5009.2     .07       0  5015.2      .1       0
Bank Sta=4959.9,5041.1
XS Rating Curve= 0 ,0
Exp/Cntr=0.3,0.1

Type RM Length L Ch R = 1 ,12432   ,457,457,457
BEGIN DESCRIPTION:
UNT 166 IN BOCR 25.0
END DESCRIPTION:
XS GIS Cut Line= 3
      3714149.62     10622910.18      3713749.61     10623160.19
      3713549.62     10623260.18
#Sta/Elev= 30
  4489.8  283.91  4619.5  276.63  4686.2  270.76  4707.4  270.22  4743.9  267.38
  4841.5  264.09  4926.1   264.5  4932.6  262.24  4938.5  262.65  4949.8  261.85
  4953.8  261.82  4958.6  257.02  4969.9  256.67  4975.5  257.62  4983.9  256.25
  4997.8  255.99  5006.2   256.3  5014.6  258.55  5017.2  255.57    5020  255.07
  5023.2  255.57  5028.6  256.98    5037  262.91  5042.6  260.85    5051  263.62
  5059.3  270.43  5095.7  272.93  5126.4  276.77  5140.4  277.56  5185.1  282.44
#Mann= 5 ,-1 , 0
  4489.8     .05       0  4841.5     .07       0  4949.8     .05       0
  5017.2    .035       0  5023.2     .05       0
Bank Sta=4926.1,5059.3
XS Rating Curve= 0 ,0
Exp/Cntr=0.3,0.1

Type RM Length L Ch R = 1 ,11975   ,433,433,433
BEGIN DESCRIPTION:
UNT 166 IN BOCR 24.0
END DESCRIPTION:
XS GIS Cut Line= 3
      3713999.63     10622460.17      3713599.61     10622810.19
      3713249.65     10622910.18
#Sta/Elev= 30
  4483.3   286.9  4497.1  286.07  4504.7   284.6  4512.8  284.68  4589.6  277.23
  4596.7  275.08  4688.8  269.94  4703.1  267.99  4731.5  266.24  4802.2  263.75
  4882.3  262.18  4908.5  262.31  4922.3  263.42  4936.5  263.14  4944.1  261.85
    4965  262.59  4972.6  259.72  4990.5  255.73  4993.2  255.23  4996.5  255.73
  5007.7  255.92  5017.4  256.95  5020.4   258.2  5031.7  263.53  5036.9   261.6
    5046  263.39  5065.5  263.59  5216.3  272.19  5344.5  285.11  5378.8  287.73
#Mann= 7 ,-1 , 0
  4483.3     .16       0  4512.8     .12       0  4882.3     .16       0
  4990.5     .07       0  4996.5     .16       0  5020.4     .05       0
  5344.5     .07       0
Bank Sta=4802.2,5065.5
XS Rating Curve= 0 ,0
Exp/Cntr=0.3,0.1

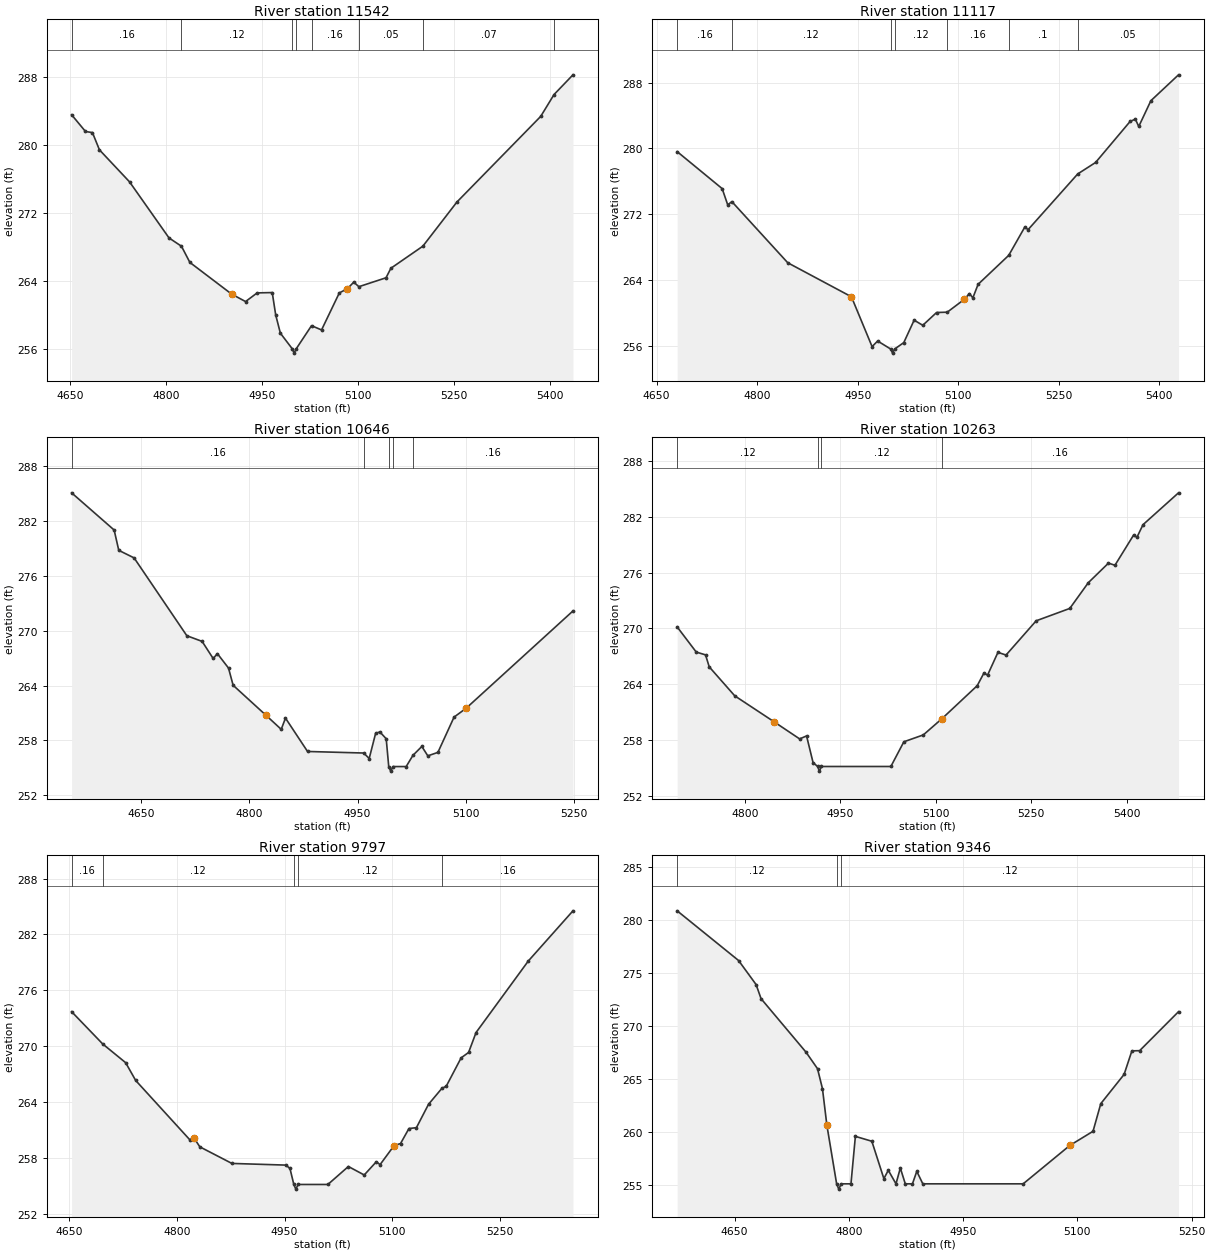
Type RM Length L Ch R = 1 ,11542   ,425,425,425
BEGIN DESCRIPTION:
UNT 166 IN BOCR 23.0
END DESCRIPTION:
XS GIS Cut Line= 3
      3713899.59      10622260.2      3713549.61     10622410.19
      3713149.59     10622460.19
#Sta/Elev= 30
  4652.7  283.53  4674.4  281.56  4685.3  281.43  4696.2   279.4  4743.3  275.63
    4805  269.03  4824.5  268.05  4837.6  266.15  4902.9  262.42  4924.7  261.54
  4942.8  262.56  4966.4   262.6  4971.8  259.97  4979.1  257.82  4997.8  255.97
  5000.6  255.47  5003.8  255.97  5027.8   258.7  5043.5   258.2  5071.3  262.56
  5083.9  263.05  5093.9  263.83  5101.8  263.29  5144.3  264.34  5151.9  265.46
  5201.9  268.06  5255.2  273.26  5386.2  283.34    5407  285.91  5436.6  288.23
#Mann= 8 ,-1 , 0
  4652.7     .16       0  4824.5     .12       0  4997.8     .07       0
  5003.8     .12       0  5027.8     .16       0  5101.8     .05       0
  5201.9     .07       0    5407     .05       0
Bank Sta=4902.9,5083.9
XS Rating Curve= 0 ,0
Exp/Cntr=0.3,0.1

Type RM Length L Ch R = 1 ,11117   ,471,471,471
BEGIN DESCRIPTION:
UNT 166 IN BOCR 22.0
END DESCRIPTION:
XS GIS Cut Line= 3
      3713849.58     10622210.17      3713549.61     10622060.19
       3713149.6     10622160.19
#Sta/Elev= 30
  4680.8  279.62  4747.9  275.13  4756.2  273.16  4762.4  273.55  4845.7  266.13
  4940.7     262  4971.5  255.95  4979.8  256.63  4999.2  255.66    5002  255.16
  5005.2  255.66  5018.8  256.44  5034.2  259.16  5047.1  258.54  5067.7  260.09
  5083.6  260.13  5108.9  261.68  5116.7  262.39  5121.8  261.87  5129.6  263.51
  5175.3  267.03  5199.1  270.44  5204.3  270.16  5278.2  276.91  5304.8   278.3
  5356.3  283.28  5364.1  283.56  5369.2  282.67  5387.3   285.8  5428.5  288.94
#Mann= 7 ,-1 , 0
  4680.8     .16       0  4762.4     .12       0  4999.2     .07       0
  5005.2     .12       0  5083.6     .16       0  5175.3      .1       0
  5278.2     .05       0
Bank Sta=4940.7,5108.9
XS Rating Curve= 0 ,0
Exp/Cntr=0.3,0.1

Type RM Length L Ch R = 1 ,10646   ,383,383,383
BEGIN DESCRIPTION:
UNT 166 IN BOCR 21.0
END DESCRIPTION:
XS GIS Cut Line= 3
       3713849.6     10621410.19      3713449.61     10621660.19
       3713249.6     10621760.19
#Sta/Elev= 30
  4553.4  285.08  4612.4  281.01  4618.8  278.79  4640.1  277.96  4713.2  269.45
  4734.4  268.83  4749.7  266.96  4755.6  267.49    4771  265.91  4777.4  264.03
  4822.8  260.76  4844.1  259.21    4850  260.44  4880.6  256.79  4958.5  256.62
  4966.1  256.02    4975  258.77  4980.9  258.93  4989.7  258.18  4993.2  255.14
  4995.9  254.64  4999.2  255.14  5017.4  255.14  5026.8  256.37  5039.1  257.34
  5047.4  256.31  5061.4  256.69  5083.8  260.55  5100.6  261.52  5248.7  272.16
#Mann= 5 ,-1 , 0
  4553.4     .16       0  4958.5     .12       0  4993.2     .07       0
  4999.2     .12       0  5026.8     .16       0
Bank Sta=4822.8,5100.6
XS Rating Curve= 0 ,0
Exp/Cntr=0.3,0.1

Type RM Length L Ch R = 1 ,10263   ,466,466,466
BEGIN DESCRIPTION:
UNT 166 IN BOCR 20.0
END DESCRIPTION:
XS GIS Cut Line= 3
      3713669.02     10621226.57      3713256.74     10621309.02
      3712918.24     10621452.23
#Sta/Elev= 30
  4693.4  270.17  4723.4  267.46    4738  267.16  4743.8  265.87  4783.9  262.75
  4845.8  259.95  4885.9  258.11  4896.8  258.43    4907  255.56  4914.2  255.14
  4916.9  254.64  4920.2  255.14  5029.3  255.14  5049.7   257.8  5080.3  258.54
  5109.8   260.3    5165  263.84  5175.7  265.22  5181.2  264.97  5197.6  267.43
  5210.3  267.14  5257.7  270.83  5310.5  272.16  5339.6  274.93  5371.3  277.04
  5381.5  276.81  5410.7  280.05  5416.1  279.83  5425.6  281.18  5481.4  284.61
#Mann= 4 ,-1 , 0
  4693.4     .12       0  4914.2     .07       0  4920.2     .12       0
  5109.8     .16       0
Bank Sta=4845.8,5109.8
XS Rating Curve= 0 ,0
Exp/Cntr=0.3,0.1

Type RM Length L Ch R = 1 ,9797    ,451,451,451
BEGIN DESCRIPTION:
UNT 166 IN BOCR 19.0
END DESCRIPTION:
XS GIS Cut Line= 3
      3713699.59     10621060.18      3713399.61     10620910.19
       3713049.6     10620810.19
#Sta/Elev= 30
    4653   273.7  4696.4  270.23  4728.4  268.22  4742.4  266.31  4817.9  259.94
  4823.5  260.16  4831.9  259.18  4876.6   257.4    4952  257.22  4957.6  256.86
    4963  255.14  4965.8  254.64    4969  255.14  5010.5  255.14  5039.1  257.07
  5061.2  256.16  5078.1  257.58  5083.3  257.27  5102.8  259.31  5111.9  259.54
  5123.6  261.15    5134  261.24  5150.9  263.75  5169.5  265.46  5175.6  265.69
  5196.4  268.74  5206.8  269.32  5217.2  271.46    5290  279.13  5352.4  284.53
#Mann= 5 ,-1 , 0
    4653     .16       0  4696.4     .12       0    4963     .07       0
    4969     .12       0  5169.5     .16       0
Bank Sta=4823.5,5102.8
XS Rating Curve= 0 ,0
Exp/Cntr=0.3,0.1

Type RM Length L Ch R = 1 ,9346    ,413,413,413
BEGIN DESCRIPTION:
UNT 166 IN BOCR 18.0
END DESCRIPTION:
XS GIS Cut Line= 3
      3713749.57     10620260.21      3713399.61     10620460.19
      3713149.63     10620510.18
#Sta/Elev= 30
  4574.7  280.91  4655.3  276.22  4678.3  273.95  4684.8  272.62  4743.8  267.57
  4758.9  266.01  4765.4  264.12  4771.2  260.67    4784  255.14  4786.8  254.64
    4790  255.14  4802.8  255.14  4808.6  259.62  4830.2  259.16    4846  255.63
  4851.8  256.42  4861.9  255.14  4867.6  256.63  4874.1  255.14  4883.5  255.14
  4889.2  256.32  4897.1  255.14  5028.8  255.14    5090  258.76  5120.5   260.1
  5130.7  262.71  5161.3  265.47  5171.5  267.69  5181.7  267.71  5232.7  271.39
#Mann= 3 ,-1 , 0
  4574.7     .12       0    4784     .07       0    4790     .12       0
Bank Sta=4771.2,5090
XS Rating Curve= 0 ,0
Exp/Cntr=0.3,0.1

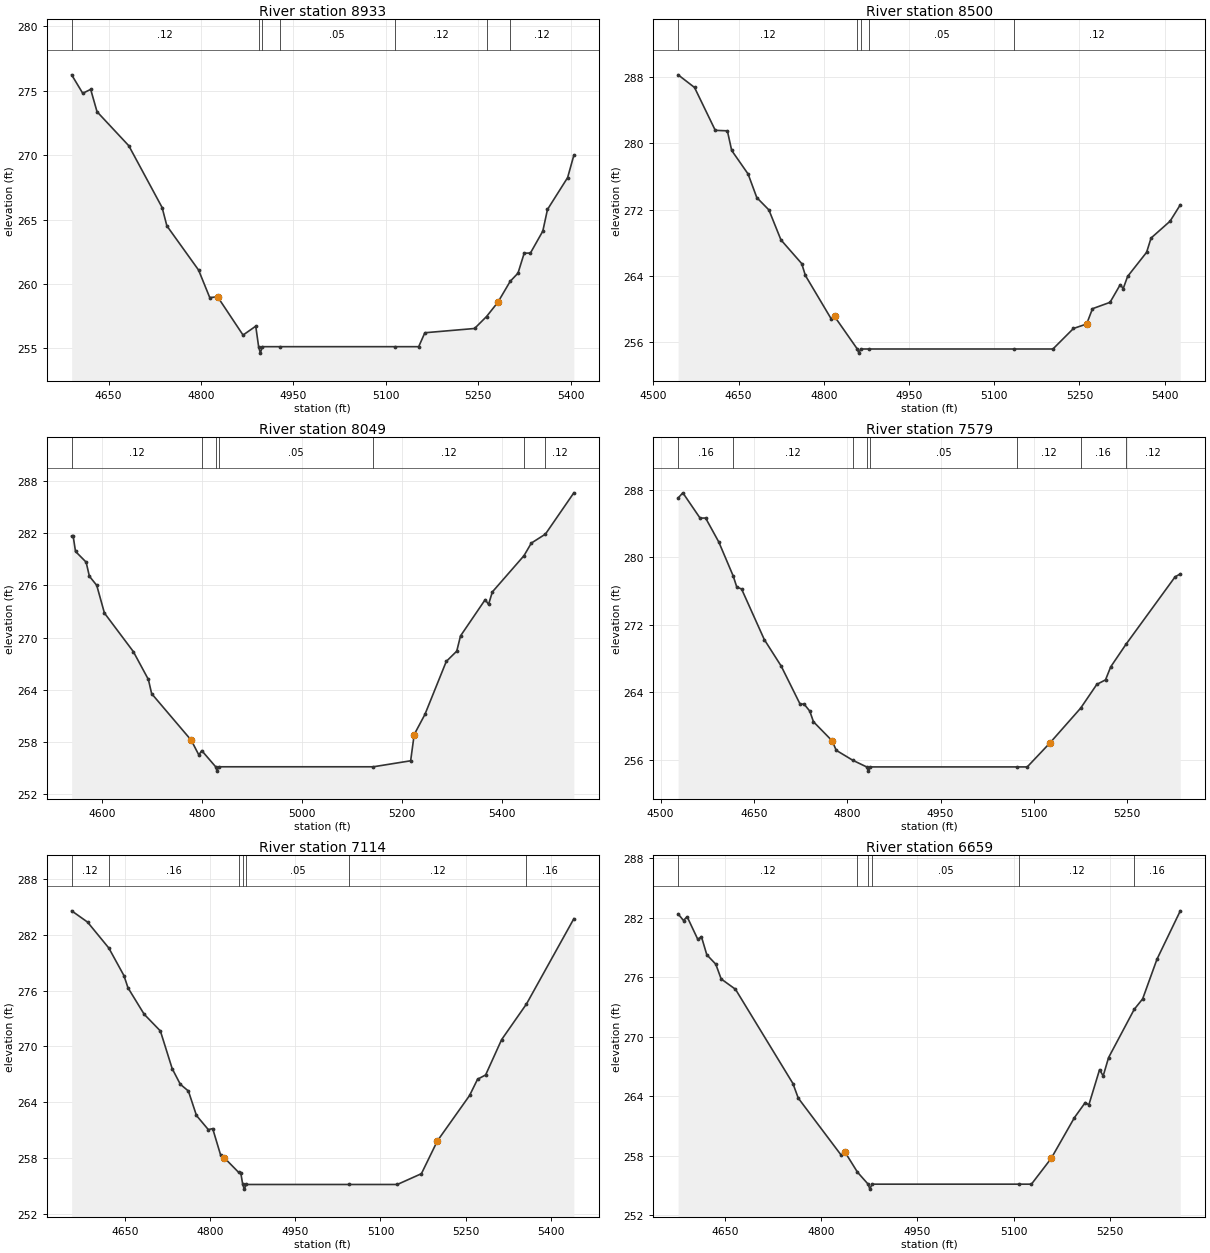
Type RM Length L Ch R = 1 ,8933    ,433,433,433
BEGIN DESCRIPTION:
UNT 166 IN BOCR 17.0
END DESCRIPTION:
XS GIS Cut Line= 3
       3713699.6     10620160.19      3713299.61     10620060.19
      3712899.62     10620110.19
#Sta/Elev= 30
    4590  276.22    4608  274.79  4620.9  275.09  4631.2  273.36  4682.8  270.72
  4736.9  265.93  4744.6  264.51  4796.1  261.08  4814.2  258.95  4827.1     259
  4868.3  256.04  4888.9  256.73  4893.6  255.14  4896.4  254.64  4899.6  255.14
  4928.1  255.14  5114.3  255.14  5153.5  255.14  5163.5  256.22  5244.2  256.55
  5263.7  257.48    5282  258.58  5302.1  260.21  5314.7  260.84  5324.8  262.39
  5334.9   262.4    5355   264.1  5362.6  265.78  5395.3  268.25  5405.4  269.98
#Mann= 7 ,-1 , 0
    4590     .12       0  4893.6    .033       0  4899.6     .12       0
  4928.1     .05       0  5114.3     .12       0  5263.7     .16       0
  5302.1     .12       0
Bank Sta=4827.1,5282
XS Rating Curve= 0 ,0
Exp/Cntr=0.3,0.1

Type RM Length L Ch R = 1 ,8500    ,451,451,451
BEGIN DESCRIPTION:
UNT 166 IN BOCR 16.0
END DESCRIPTION:
XS GIS Cut Line= 3
       3713549.6      10619410.2      3713149.61     10619660.19
       3712749.6     10619760.19
#Sta/Elev= 30
  4543.5  288.28  4572.4  286.75  4608.9  281.57  4630.2  281.51  4637.8  279.14
  4666.7  276.29    4682  273.44  4703.3  271.95  4724.5  268.33  4761.1  265.46
  4767.5  264.03  4812.9  258.79  4818.8  259.08  4858.9  255.14  4861.6  254.64
  4864.9  255.14  4879.4  255.14  5135.2  255.14  5203.3  255.14  5239.4  257.62
  5262.6  258.16  5272.9  260.01  5303.8  260.78  5321.8  262.92    5327  262.44
  5334.7  263.91  5368.2  266.83    5376  268.55  5409.5  270.59  5427.5  272.57
#Mann= 5 ,-1 , 0
  4543.5     .12       0  4858.9    .033       0  4864.9     .12       0
  4879.4     .05       0  5135.2     .12       0
Bank Sta=4818.8,5262.6
XS Rating Curve= 0 ,0
Exp/Cntr=0.3,0.1

Type RM Length L Ch R = 1 ,8049    ,470,470,470
BEGIN DESCRIPTION:
UNT 166 IN BOCR 15.0
END DESCRIPTION:
XS GIS Cut Line= 3
      3713349.61     10619010.19      3712949.61     10619260.19
      3712549.62     10619610.18
#Sta/Elev= 30
  4539.9  281.68  4542.9  281.68  4547.6  279.91  4568.8  278.68  4575.3  277.06
    4590  276.01  4605.4  272.82  4663.1  268.39  4693.2  265.18  4699.7  263.55
  4778.7   258.2    4794   256.5  4799.8     257  4827.6  255.14  4830.3  254.64
  4833.6  255.14  5142.6  255.14  5217.1  255.83  5224.2  258.85  5245.6  261.16
  5288.3  267.26  5309.2  268.44  5316.7  270.19  5366.1  274.37  5372.7  273.81
  5380.3  275.25  5443.5  279.42  5458.2  280.87  5486.3   281.9  5543.1  286.65
#Mann= 7 ,-1 , 0
  4539.9     .12       0  4799.8     .05       0  4827.6    .033       0
  4833.6     .05       0  5142.6     .12       0  5443.5     .16       0
  5486.3     .12       0
Bank Sta=4778.7,5224.2
XS Rating Curve= 0 ,0
Exp/Cntr=0.3,0.1

Type RM Length L Ch R = 1 ,7579    ,465,465,465
BEGIN DESCRIPTION:
UNT 166 IN BOCR 14.0
END DESCRIPTION:
XS GIS Cut Line= 3
      3712849.59     10618560.22      3712599.61     10618960.19
       3712449.6     10619260.21
#Sta/Elev= 30
  4528.3  287.05  4535.9  287.66  4563.6  284.66  4572.5  284.67  4593.7  281.82
  4616.8   277.8  4622.6  276.48  4630.3  276.25  4666.8  270.25  4693.9  267.11
  4724.6  262.55  4730.5  262.62  4739.9  261.76  4745.8   260.5  4775.9  258.23
  4782.4  257.11    4809  255.93  4831.3  255.14    4834  254.64  4837.3  255.14
  5072.6  255.14  5089.4  255.14  5125.7  257.97  5175.3  262.12  5201.2  264.93
  5215.2  265.47  5223.6  267.02  5248.1  269.69    5327  277.69  5335.4  278.04
#Mann= 8 ,-1 , 0
  4528.3     .16       0  4616.8     .12       0    4809     .05       0
  4831.3    .033       0  4837.3     .05       0  5072.6     .12       0
  5175.3     .16       0  5248.1     .12       0
Bank Sta=4775.9,5125.7
XS Rating Curve= 0 ,0
Exp/Cntr=0.3,0.1

Type RM Length L Ch R = 1 ,7114    ,455,455,455
BEGIN DESCRIPTION:
UNT 166 IN BOCR 13.0
END DESCRIPTION:
XS GIS Cut Line= 3
      3712599.59      10618360.2      3712249.61     10618660.19
      3711949.62     10618960.17
#Sta/Elev= 30
  4555.7  284.57  4583.7  283.36  4621.2  280.57  4647.9   277.6    4655  276.29
  4683.5  273.45  4712.1  271.65  4732.9   267.6  4747.2  265.92  4761.5  265.19
  4775.7  262.56  4796.6  261.04  4804.3  261.15  4818.5  258.26  4825.1  257.99
  4850.1  256.44  4853.7  256.42  4857.3  255.14    4860  254.64  4863.3  255.14
  5045.4  255.14  5129.8  255.14  5172.2   256.3  5200.5  259.84  5257.1  264.71
  5271.2  266.46  5285.4  266.92  5313.6  270.72  5357.4  274.55  5440.9  283.72
#Mann= 7 ,-1 , 0
  4555.7     .12       0  4621.2     .16       0  4850.1     .05       0
  4857.3    .033       0  4863.3     .05       0  5045.4     .12       0
  5357.4     .16       0
Bank Sta=4825.1,5200.5
XS Rating Curve= 0 ,0
Exp/Cntr=0.3,0.1

Type RM Length L Ch R = 1 ,6659    ,470,470,470
BEGIN DESCRIPTION:
UNT 166 IN BOCR 12.0
END DESCRIPTION:
XS GIS Cut Line= 3
      3712349.59      10618110.2      3711949.61     10618310.19
      3711649.61     10618460.19
#Sta/Elev= 30
    4577  282.39  4585.4  281.72    4591  282.11  4607.7  279.82  4613.3   280.1
  4621.7  278.27  4635.7  277.32  4644.1  275.83  4666.4  274.79  4755.9  265.29
  4764.2  263.82  4831.3  258.05  4836.9  258.39  4856.5  256.35  4873.1  255.14
  4875.8  254.64  4879.1  255.14  5108.7  255.14  5127.6  255.14  5158.4  257.74
  5194.7  261.86  5211.5  263.37  5217.1  263.14  5233.8  266.69  5239.4  266.05
  5247.8   267.9  5287.8  272.77  5300.9  273.82  5323.3  277.83  5359.6   282.7
#Mann= 6 ,-1 , 0
    4577     .12       0  4856.5     .05       0  4873.1    .033       0
  4879.1     .05       0  5108.7     .12       0  5287.8     .16       0
Bank Sta=4836.9,5158.4
XS Rating Curve= 0 ,0
Exp/Cntr=0.3,0.1

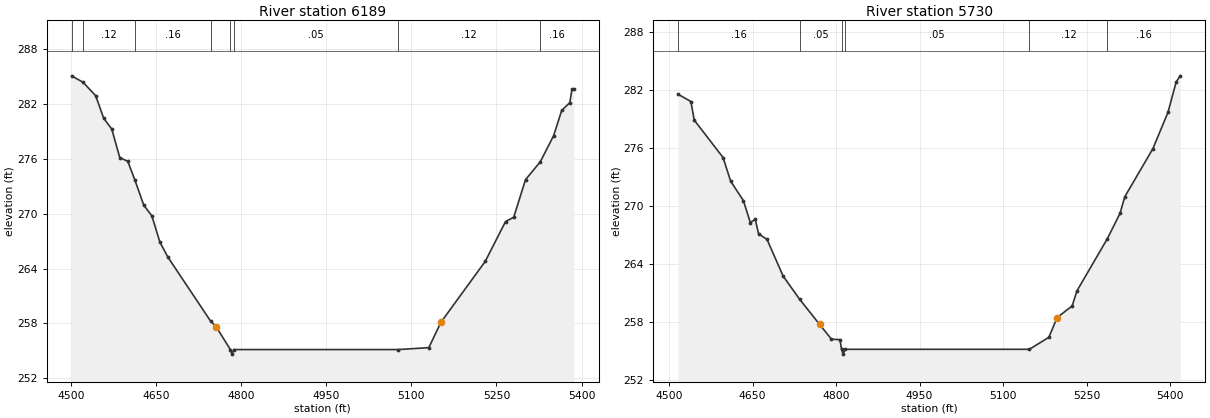
Type RM Length L Ch R = 1 ,6189    ,459,459,459
BEGIN DESCRIPTION:
UNT 166 IN BOCR 11.0
END DESCRIPTION:
XS GIS Cut Line= 3
      3711999.58     10617610.22      3711649.61     10617960.19
      3711349.65     10618210.16
#Sta/Elev= 30
    4501  285.09  4521.2  284.38  4543.4  282.91  4557.5  280.44  4571.7  279.27
  4585.8  276.15    4600  275.73  4612.6  273.67  4628.2  270.93  4642.4  269.77
  4656.5  266.91  4670.7  265.25  4746.1  258.24  4755.5  257.66  4780.8  255.14
  4783.6  254.64  4786.8  255.14  5076.9  255.14  5130.7  255.35  5152.1  258.13
  5230.2  264.79    5266  269.15  5280.4  269.61  5301.2  273.73  5327.2  275.68
  5350.7  278.53    5365   281.3  5379.3  282.16  5383.2  283.62  5386.4  283.62
#Mann= 8 ,-1 , 0
    4501     .16       0  4521.2     .12       0  4612.6     .16       0
  4746.1     .05       0  4780.8    .033       0  4786.8     .05       0
  5076.9     .12       0  5327.2     .16       0
Bank Sta=4755.5,5152.1
XS Rating Curve= 0 ,0
Exp/Cntr=0.3,0.1

Type RM Length L Ch R = 1 ,5730    ,460,460,460
BEGIN DESCRIPTION:
UNT 166 IN BOCR 10.0
END DESCRIPTION:
XS GIS Cut Line= 3
      3711549.59     10617260.22      3711299.61     10617660.19
      3711049.59     10618010.21
#Sta/Elev= 30
  4516.4  281.59  4539.4  280.83  4545.3  278.91  4597.1  275.03  4610.7  272.58
  4633.7  270.55  4646.1  268.27  4654.9  268.63  4660.8  267.13  4676.1  266.53
    4705  262.73  4734.6  260.33  4770.5  257.72  4791.7  256.19    4807  256.14
  4809.9  255.14  4812.7  254.64  4815.9  255.14  5147.2  255.14  5182.2  256.39
    5197  258.43    5224  259.64  5232.6   261.2  5287.4  266.63    5310  269.25
  5318.6  270.97    5369  275.95  5396.1  279.72  5410.8  282.87  5418.2   283.5
#Mann= 6 ,-1 , 0
  4516.4     .16       0  4734.6     .05       0  4809.9    .033       0
  4815.9     .05       0  5147.2     .12       0  5287.4     .16       0
Bank Sta=4770.5,5197
XS Rating Curve= 0 ,0
Exp/Cntr=0.3,0.1