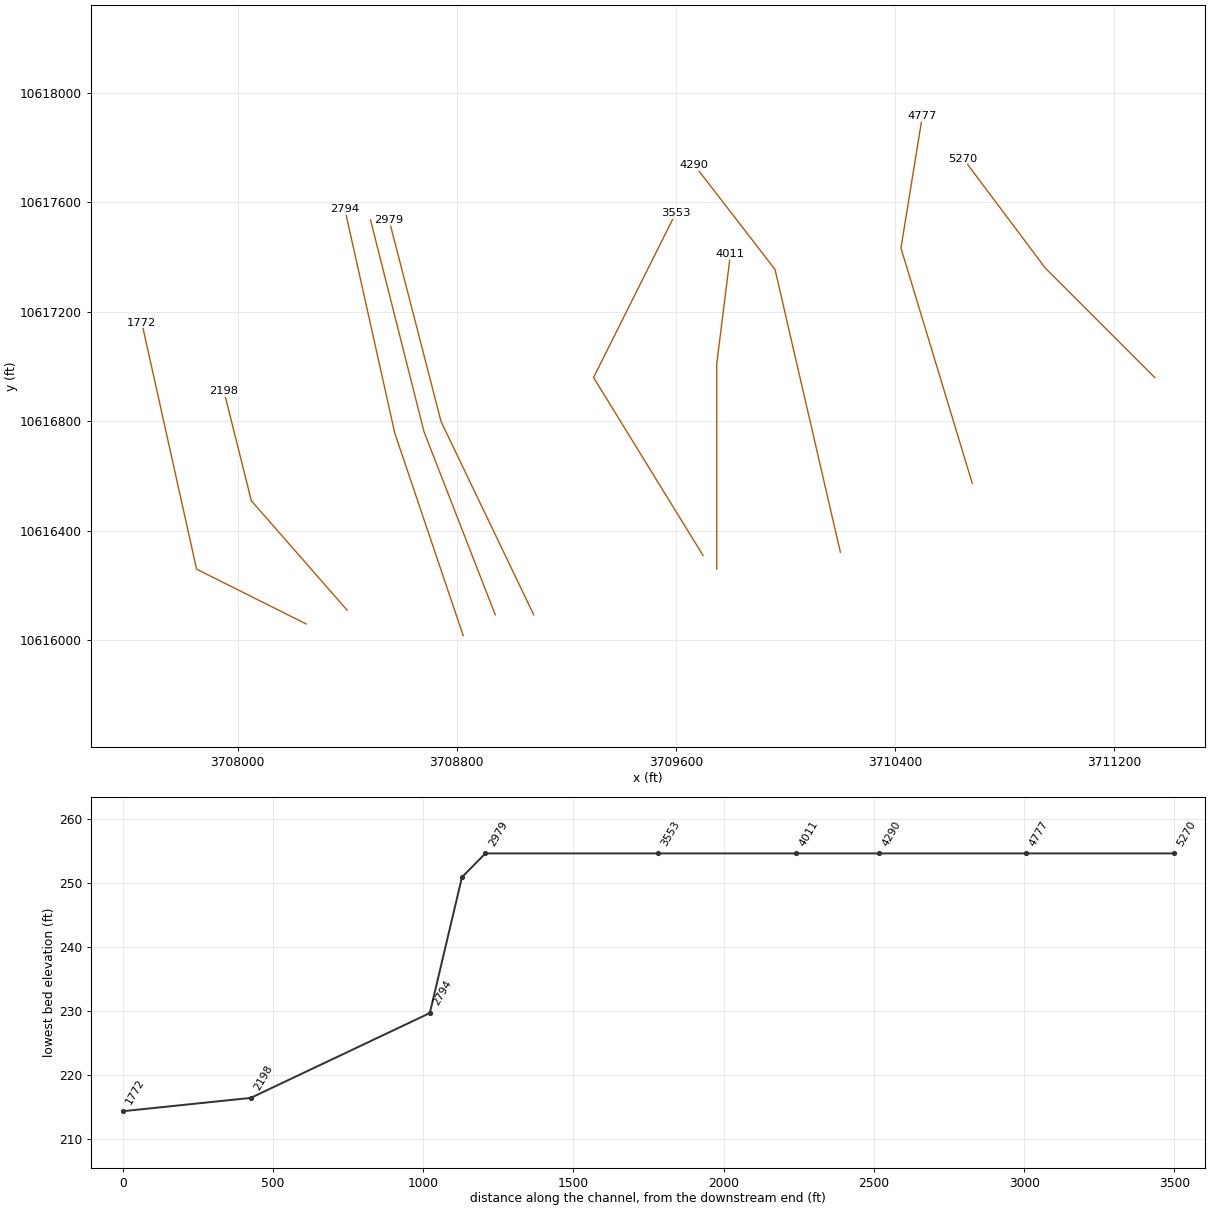
HEC-RAS study UNT 166 IN BOCR.prj: UNT 166 IN BOCR Base Level Engineering

--- UNT 166 IN BOCR.g01 (geometry) --- (continued)

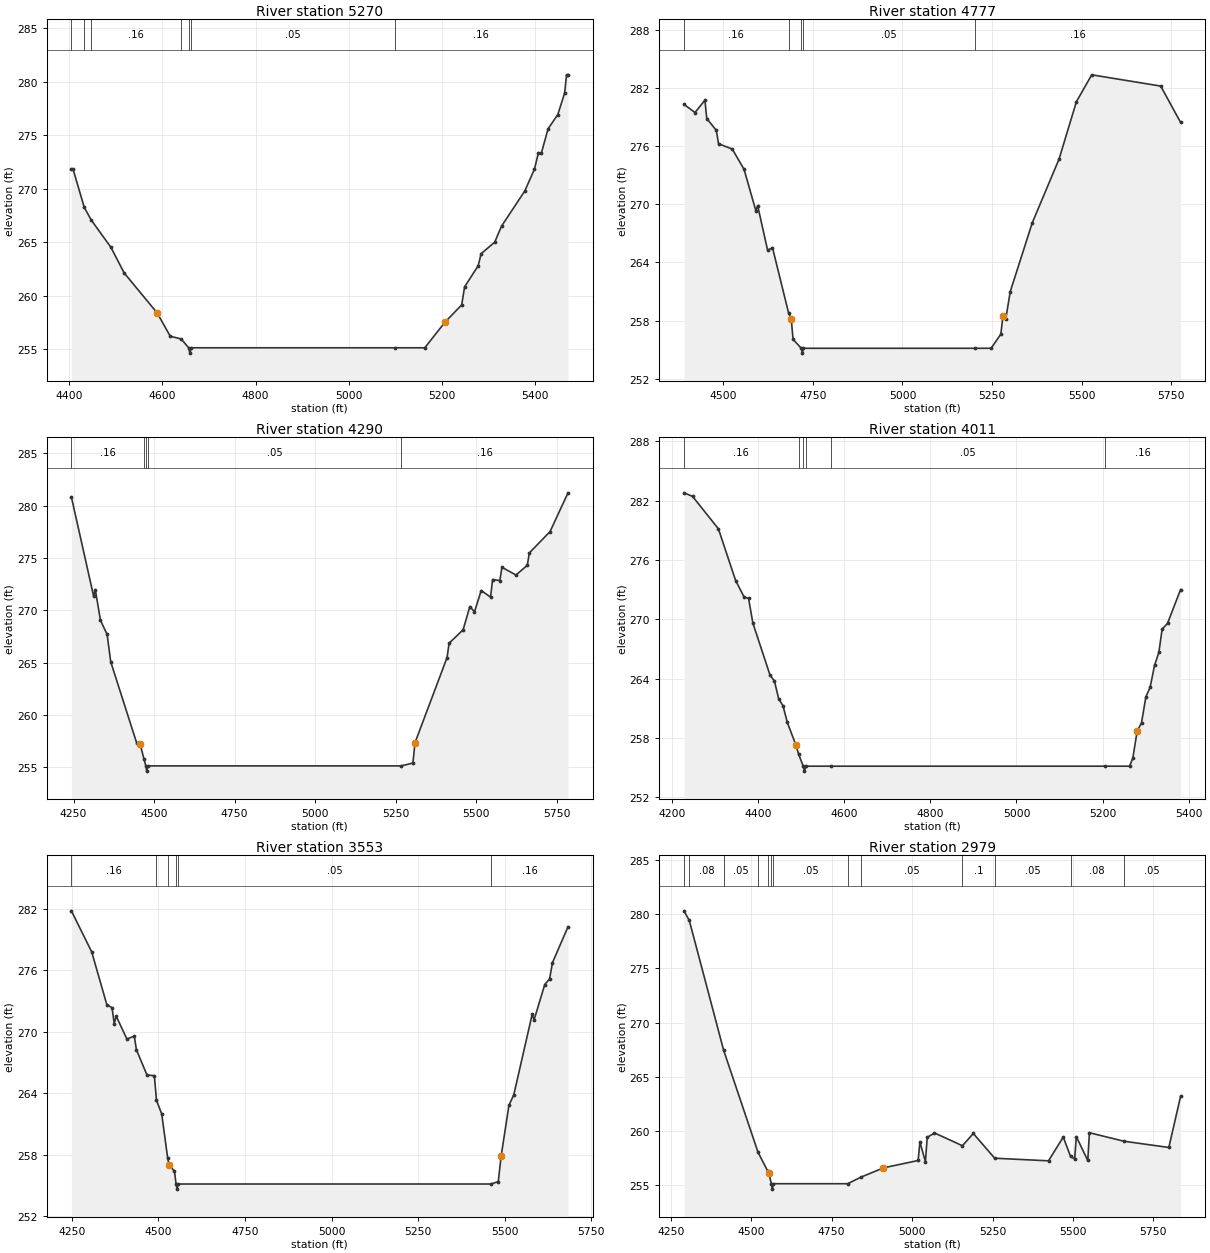
Type RM Length L Ch R = 1 ,5270    ,493,493,493
BEGIN DESCRIPTION:
UNT 166 IN BOCR 9.0
END DESCRIPTION:
XS GIS Cut Line= 3
      3711349.63     10616960.16      3710949.61     10617360.19
      3710649.62     10617760.17
#Sta/Elev= 30
  4404.7  271.84  4408.3  271.84  4432.4  268.26  4447.2  267.09  4489.6  264.53
  4517.9  262.14  4588.6  258.41  4616.9  256.22  4640.4  255.96  4656.3  255.14
    4659  254.64  4662.3  255.14  5098.4  255.14  5163.1  255.14  5206.9  257.56
  5242.3  259.15  5248.5  260.84  5277.7  262.81    5284  263.94  5313.1  265.01
  5327.7  266.51  5377.7   269.8  5398.5  271.85  5406.9  273.39  5413.1  273.32
  5427.7  275.62  5448.5  276.94  5463.1  278.95  5467.3  280.66  5470.4  280.66
#Mann= 7 ,-1 , 0
  4404.7     .16       0  4432.4     .05       0  4447.2     .16       0
  4640.4     .05       0  4656.3    .033       0  4662.3     .05       0
  5098.4     .16       0
Bank Sta=4588.6,5206.9
XS Rating Curve= 0 ,0
Exp/Cntr=0.3,0.1

Type RM Length L Ch R = 1 ,4777    ,487,487,487
BEGIN DESCRIPTION:
UNT 166 IN BOCR 8.0
END DESCRIPTION:
XS GIS Cut Line= 3
      3710682.96     10616573.75      3710422.53     10617433.15
      3710500.67     10617914.97
#Sta/Elev= 30
  4390.1  280.32  4420.9  279.48  4448.6  280.75  4453.8  278.86  4480.4  277.64
  4486.7  276.25  4524.9  275.71  4557.8  273.62  4590.7  269.35  4595.9  269.85
  4623.6  265.26  4637.2  265.53  4682.3  258.76  4689.4  258.21  4694.7  256.06
  4717.7  255.14  4720.5  254.64  4723.7  255.14  5201.9  255.14  5247.4  255.14
  5274.5   256.6  5280.4  258.47  5288.1  258.13  5300.7  260.98  5362.3   268.1
    5437  274.67  5485.5   280.6  5528.2  283.37  5720.7  282.21  5776.2  278.46
#Mann= 5 ,-1 , 0
  4390.1     .16       0  4682.3     .05       0  4717.7    .033       0
  4723.7     .05       0  5201.9     .16       0
Bank Sta=4689.4,5280.4
XS Rating Curve= 0 ,0
Exp/Cntr=0.3,0.1

Type RM Length L Ch R = 1 ,4290    ,279,279,279
BEGIN DESCRIPTION:
UNT 166 IN BOCR 7.0
END DESCRIPTION:
XS GIS Cut Line= 3
      3710201.18     10616322.07      3709962.47     10617355.03
      3709668.05     10617736.04
#Sta/Elev= 30
  4243.1  280.83  4312.3  271.33  4317.4  271.97  4333.5  269.03  4354.1  267.69
  4365.3  265.08  4445.6  257.35  4456.7   257.2  4468.7  255.77  4474.2  255.14
    4477  254.64  4480.2  255.14  5266.8  255.14  5303.3  255.41  5309.8  257.35
  5409.4  265.49  5415.7  266.86  5459.2  268.14    5480  270.35  5494.5  269.86
  5515.4  271.89  5544.4  271.26  5550.7  272.94  5573.3  272.84  5579.7  274.11
  5623.2  273.37  5658.5   274.3  5664.8  275.48  5729.1  277.52  5784.8  281.22
#Mann= 5 ,-1 , 0
  4243.1     .16       0  4468.7     .05       0  4474.2    .033       0
  4480.2     .05       0  5266.8     .16       0
Bank Sta=4456.7,5309.8
XS Rating Curve= 0 ,0
Exp/Cntr=0.3,0.1

Type RM Length L Ch R = 1 ,4011    ,458,458,458
BEGIN DESCRIPTION:
UNT 166 IN BOCR 6.0
END DESCRIPTION:
XS GIS Cut Line= 3
      3709749.61     10616260.23      3709749.61     10617010.19
      3709799.61     10617410.21
#Sta/Elev= 30
    4228  282.78    4248  282.42    4308  279.14    4348  273.91    4368  272.22
    4378  272.12    4388  269.61    4428  264.33    4438  263.76    4448  261.95
    4458  261.25    4468  259.56    4488  257.27  4494.2  256.35    4505  255.14
  4507.7  254.64    4511  255.14  4569.8  255.14  5206.3  255.14  5262.7  255.14
  5270.2  255.96  5280.3  258.69  5290.4  259.53  5300.5  262.15  5310.5  263.13
  5320.6  265.33  5330.7  266.64  5338.2  268.99  5350.8  269.58  5381.1     273
#Mann= 6 ,-1 , 0
    4228     .16       0  4494.2      .1       0    4505    .033       0
    4511      .1       0  4569.8     .05       0  5206.3     .16       0
Bank Sta=4488,5280.3
XS Rating Curve= 0 ,0
Exp/Cntr=0.3,0.1

Type RM Length L Ch R = 1 ,3553    ,574,574,574
BEGIN DESCRIPTION:
UNT 166 IN BOCR 5.0
END DESCRIPTION:
XS GIS Cut Line= 3
      3709699.62     10616310.18      3709299.61     10616960.19
      3709599.63     10617560.23
#Sta/Elev= 30
  4248.6  281.83  4307.3  277.82    4351  272.66    4366  272.37  4372.3  270.82
  4378.1  271.54    4409   269.3  4430.2  269.59  4436.5  268.25  4466.9  265.79
  4488.2  265.72  4494.4  263.31  4509.5  261.99  4526.6  257.69  4530.8  256.96
  4546.2  256.41  4550.9  255.14  4553.6  254.64  4556.9  255.14  5460.2  255.14
  5481.4  255.38  5489.8  257.91  5512.1  262.82  5526.1  263.85  5579.2  271.71
  5584.8  271.18  5615.6  274.63  5629.5  275.18  5637.9  276.77  5682.7  280.27
#Mann= 6 ,-1 , 0
  4248.6     .16       0  4494.4      .1       0  4526.6     .05       0
  4550.9    .033       0  4556.9     .05       0  5460.2     .16       0
Bank Sta=4530.8,5489.8
XS Rating Curve= 0 ,0
Exp/Cntr=0.3,0.1

Type RM Length L Ch R = 1 ,2979    ,78,78,78
BEGIN DESCRIPTION:
UNT 166 IN BOCR 4.0
END DESCRIPTION:
XS GIS Cut Line= 3
      3709081.41     10616093.05      3708742.85     10616798.82
      3708552.81     10617535.53
#Sta/Elev= 30
  4290.9   280.3  4307.5  279.41  4414.3  267.44    4521  258.05  4551.2   256.3
  4553.9  256.17  4562.7  255.14  4565.5  254.64  4568.7  255.14  4799.9  255.14
  4841.4  255.75  4911.1   256.6  5018.8  257.28  5024.3  258.99  5041.4  257.16
    5047  259.41  5069.6  259.82  5156.4  258.64  5190.3  259.77  5256.7  257.49
    5424  257.25  5469.8  259.44  5492.6  257.65  5505.3  257.42  5510.5  259.48
    5546  257.28  5551.2  259.84  5657.8  259.06    5798  258.48  5834.5   263.2
#Mann= 13 ,-1 , 0
  4290.9     .05       0  4307.5     .08       0  4414.3     .05       0
    4521     .16       0  4551.2     .05       0  4562.7     .04       0
  4568.7     .05       0  4799.9     .08       0  4841.4     .05       0
  5156.4      .1       0  5256.7     .05       0  5492.6     .08       0
  5657.8     .05       0
Bank Sta=4553.9,4911.1
XS Rating Curve= 0 ,0
Exp/Cntr=0.3,0.1

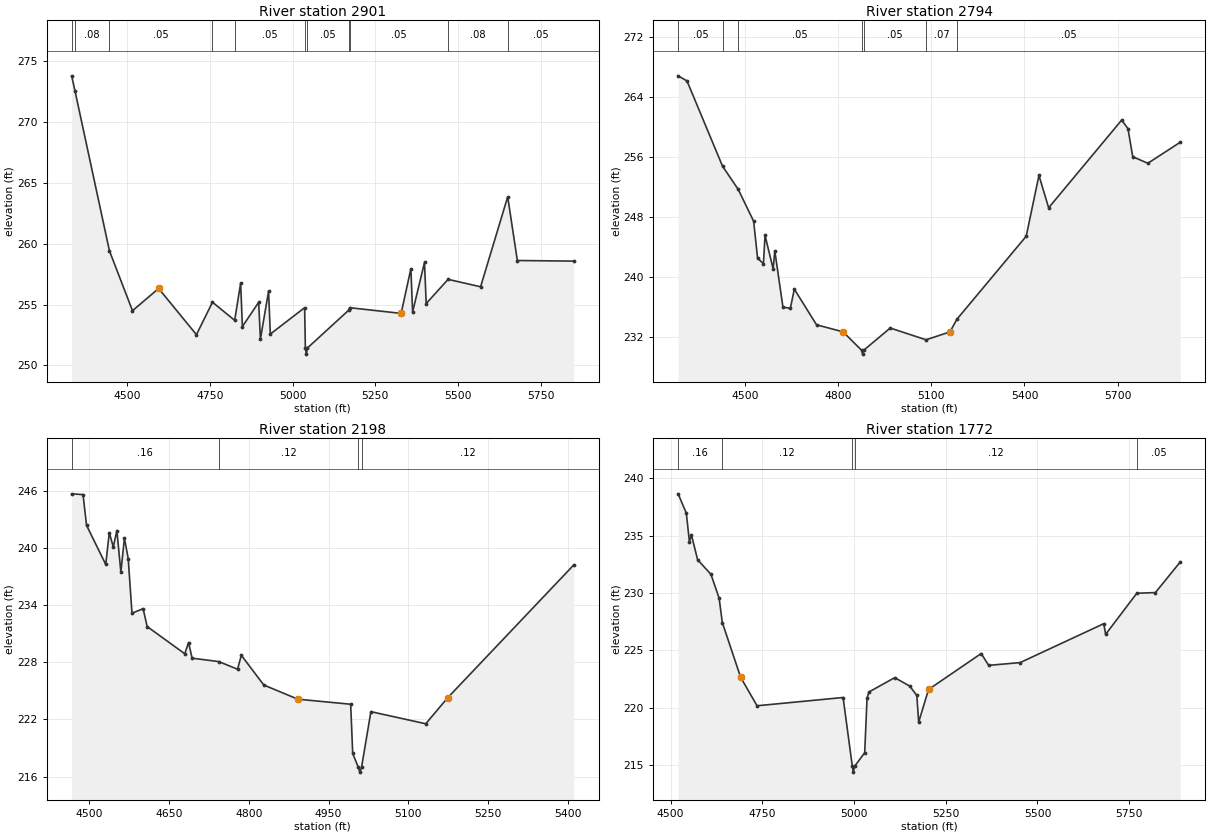
Type RM Length L Ch R = 1 ,2901    ,107,107,107
BEGIN DESCRIPTION:
Mapping XS aa564d73
END DESCRIPTION:
XS GIS Cut Line= 3
      3708940.76     10616093.09      3708680.35     10616762.36
       3708485.1     10617535.54
#Sta/Elev= 30
  4333.4  273.82  4343.7  272.55  4447.4  259.43    4517   254.5  4595.9  256.33
    4710  252.53  4758.4   255.2  4825.4  253.71  4843.4  256.76  4848.7   253.2
  4897.8  255.19  4903.1  252.17  4927.7   256.1    4933  252.58  5036.5  254.75
  5038.8  251.43  5041.6  250.93  5044.8  251.43    5169  254.53  5172.4  254.75
  5327.8  254.28  5357.2  257.96  5362.4   254.4  5398.3  258.47  5403.4  255.09
  5469.5  257.08  5567.6  256.47  5649.4  263.87  5678.5  258.63    5849  258.58
#Mann= 11 ,-1 , 0
  4333.4     .16       0  4343.7     .08       0  4447.4     .05       0
  4758.4     .08       0  4825.4     .05       0  5038.8     .04       0
  5044.8     .05       0    5169      .1       0  5172.4     .05       0
  5469.5     .08       0  5649.4     .05       0
Bank Sta=4595.9,5327.8
XS Rating Curve= 0 ,0
Exp/Cntr=0.3,0.1

Type RM Length L Ch R = 1 ,2794    ,596,596,596
BEGIN DESCRIPTION:
UNT 166 IN BOCR 3.0
END DESCRIPTION:
XS GIS Cut Line= 3
      3708823.58     10616017.56      3708573.58     10616757.16
      3708391.28     10617574.88
#Sta/Elev= 30
  4283.7  266.82  4312.3  266.14  4426.8  254.78  4477.5  251.67  4527.1  247.44
  4539.8  242.51  4558.6  241.78  4563.9  245.54    4590  241.07  4595.3  243.49
  4621.5     236  4645.4  235.82  4658.2  238.38  4729.8  233.63  4815.4  232.69
  4875.3  230.22  4878.1  229.72  4881.3  230.22  4967.4   233.2  5082.7  231.63
  5159.7  232.68  5182.3  234.37  5405.6  245.44  5446.6  253.54  5477.9  249.23
    5713  260.91  5733.5  259.79  5748.9  256.04  5797.5  255.16  5902.2  257.97
#Mann= 7 ,-1 , 0
  4283.7     .05       0  4426.8     .16       0  4477.5     .05       0
  4875.3     .03       0  4881.3     .05       0  5082.7     .07       0
  5182.3     .05       0
Bank Sta=4815.4,5159.7
XS Rating Curve= 0 ,0
Exp/Cntr=0.3,0.1

Type RM Length L Ch R = 1 ,2198    ,426,426,426
BEGIN DESCRIPTION:
UNT 166 IN BOCR 2.0
END DESCRIPTION:
XS GIS Cut Line= 3
      3708399.61     10616110.19      3708049.61     10616510.19
      3707949.61     10616910.17
#Sta/Elev= 30
  4467.2   245.7  4488.6  245.62  4495.2  242.39  4531.3  238.28  4537.9  241.62
  4545.5  240.12  4552.2  241.84  4559.7  237.48  4566.4  241.04  4573.5   238.9
  4580.6  233.16  4601.5  233.64  4609.1  231.76  4679.8   228.9  4686.9  230.08
  4693.6  228.44  4743.6  228.08    4779  227.28  4786.1  228.74  4828.3  225.62
  4892.4  224.13  4991.6   223.6  4995.4  218.43    5006  216.97  5008.8  216.47
    5012  216.97  5029.6  222.82  5132.7  221.55  5173.9  224.28    5411  238.24
#Mann= 4 ,-1 , 0
  4467.2     .16       0  4743.6     .12       0    5006     .07       0
    5012     .12       0
Bank Sta=4892.4,5173.9
XS Rating Curve= 0 ,0
Exp/Cntr=0.3,0.1

Type RM Length L Ch R = 1 ,1772    ,0,0,0
BEGIN DESCRIPTION:
UNT 166 IN BOCR 1.0
END DESCRIPTION:
XS GIS Cut Line= 3
      3708249.62     10616060.18      3707849.61     10616260.19
       3707649.6     10617160.21
#Sta/Elev= 30
  4520.3  238.63  4542.7  236.95  4551.1  234.46  4556.6  235.06  4573.4  232.89
  4609.8  231.62  4632.1  229.54  4640.8  227.42  4690.8  222.65  4735.5  220.17
  4970.1  220.89  4995.3  214.89    4998  214.39  5001.3  214.89    5029  216.08
  5035.4  220.81  5040.5  221.37  5110.9  222.62  5151.9  221.88  5171.1  221.07
  5176.2  218.75  5203.1  221.59  5346.6  224.72    5367  223.69  5452.8  223.93
  5680.8  227.32  5685.9  226.39  5770.9  229.97  5821.6  230.03  5889.5   232.7
#Mann= 5 ,-1 , 0
  4520.3     .16       0  4640.8     .12       0  4995.3     .07       0
  5001.3     .12       0  5770.9     .05       0
Bank Sta=4690.8,5203.1
XS Rating Curve= 0 ,0
Exp/Cntr=0.3,0.1

Chan Stop Cuts=-1
Use User Specified Reach Order=0
Composite Channel Slope=5