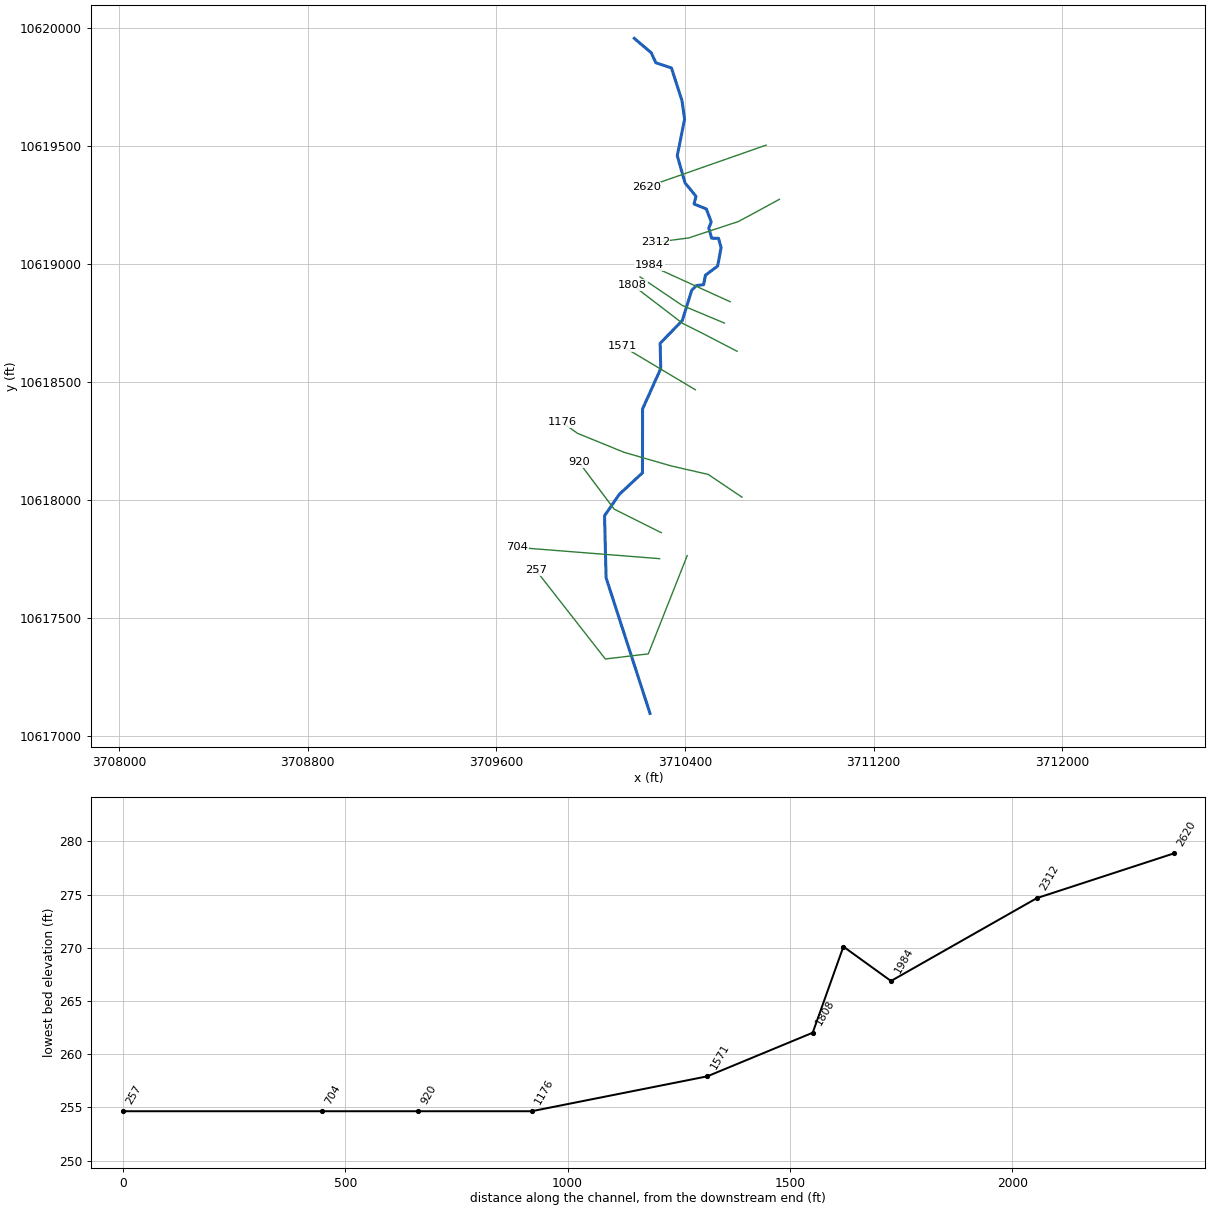
--- UNT 167 IN BOCR.prj (project) ---

Proj Title=UNT 167 IN BOCR Base Level Engineering
Current Plan=p01
Default Exp/Contr=0.3,0.1
English Units
Geom File=g01
Flow File=f01
Plan File=p01
Y Axis Title=Elevation
X Axis Title(PF)=Main Channel Distance
X Axis Title(XS)=Station
BEGIN DESCRIPTION:
UNT 167 IN BOCR
END DESCRIPTION:
DSS Export Rating Curves= 0
DSS Export Rating Curve Sorted= 0
DSS Export Volume Flow Curves= 0
DXF OffsetX= 0
DXF OffsetY= 0
DXF ScaleX= 1
DXF ScaleY= 10

--- UNT 167 IN BOCR.p01 (plan) ---

Plan Title=Multiple Run
Short Identifier=Multiple
Geom File=g01
Flow File=f01
Subcritical Flow
K Sum by GR= 0
Std Step Tol= 0.01
Critical Tol= 0.01
Num of Std Step Trials= 20
Max Error Tol= 0.3
Flow Tol Ratio= 0.001
Split Flow NTrial= 30
Split Flow Tol= 0.02
Split Flow Ratio= 0.02
Log Output Level= 0
Friction Slope Method= 1
Unsteady Friction Slope Method= 2
Unsteady Bridges Friction Slope Method= 1
Parabolic Critical Depth
Global Vel Dist=  1 , 1 , 1
Global Log Level= 0
CheckData=True
Encroach Param= -1, 0, 0, 0
BEGIN DESCRIPTION:
Multiple Run
END DESCRIPTION:

--- UNT 167 IN BOCR.f01 (steady flow) ---

Flow Title=Multiple
Program Version=4.10
Number of Profiles= 7
Profile Names=10-year,25-year,50-year,1pct_min,100-year,1pct_plu,500-year
River Rch & RM=UNT 167 IN BOCR,Reach-1         ,2620
     131     159     179     150     202     274     257
Boundary for River Rch & Prof#=UNT 167 IN BOCR,Reach-1         , 1
Up Type= 0
Dn Type= 3
Dn Slope=0.00001
Boundary for River Rch & Prof#=UNT 167 IN BOCR,Reach-1         , 2
Up Type= 0
Dn Type= 3
Dn Slope=0.00001
Boundary for River Rch & Prof#=UNT 167 IN BOCR,Reach-1         , 3
Up Type= 0
Dn Type= 3
Dn Slope=0.00001
Boundary for River Rch & Prof#=UNT 167 IN BOCR,Reach-1         , 4
Up Type= 0
Dn Type= 3
Dn Slope=0.00001
Boundary for River Rch & Prof#=UNT 167 IN BOCR,Reach-1         , 5
Up Type= 0
Dn Type= 3
Dn Slope=0.00001
Boundary for River Rch & Prof#=UNT 167 IN BOCR,Reach-1         , 6
Up Type= 0
Dn Type= 3
Dn Slope=0.00001
Boundary for River Rch & Prof#=UNT 167 IN BOCR,Reach-1         , 7
Up Type= 0
Dn Type= 3
Dn Slope=0.00001
DSS Import GetInterval= 0
DSS Import GetPeak= 0
DSS Import FillOption= 0

--- UNT 167 IN BOCR.g01 (geometry) ---

Geom Title=Existing Conditions
Program Version=4.10

River Reach=UNT 167 IN BOCR ,Reach-1
Reach XY= 30
      3710184.91     10619956.42      3710256.79     10619895.49
      3710276.58     10619852.78      3710342.73      10619830.9
      3710387.52     10619691.32      3710398.45     10619613.19
       3710367.3     10619458.79       3710400.2     10619343.57
      3710446.78     10619286.47      3710438.61     10619254.16
      3710490.69     10619232.67      3710511.31      10619178.2
      3710501.07     10619151.68      3710513.22     10619108.93
       3710542.3      10619108.5      3710553.15       10619069.
      3710538.75       10618991.      3710486.98     10618952.12
      3710478.74     10618911.75      3710448.14     10618908.06
      3710428.39     10618887.67      3710388.75       10618760.
      3710294.75       10618663.      3710297.25       10618556.
      3710220.25       10618385.      3710219.75       10618114.
      3710121.75       10618023.        3710059.       10617932.
       3710065.5       10617669.      3710251.75       10617094.

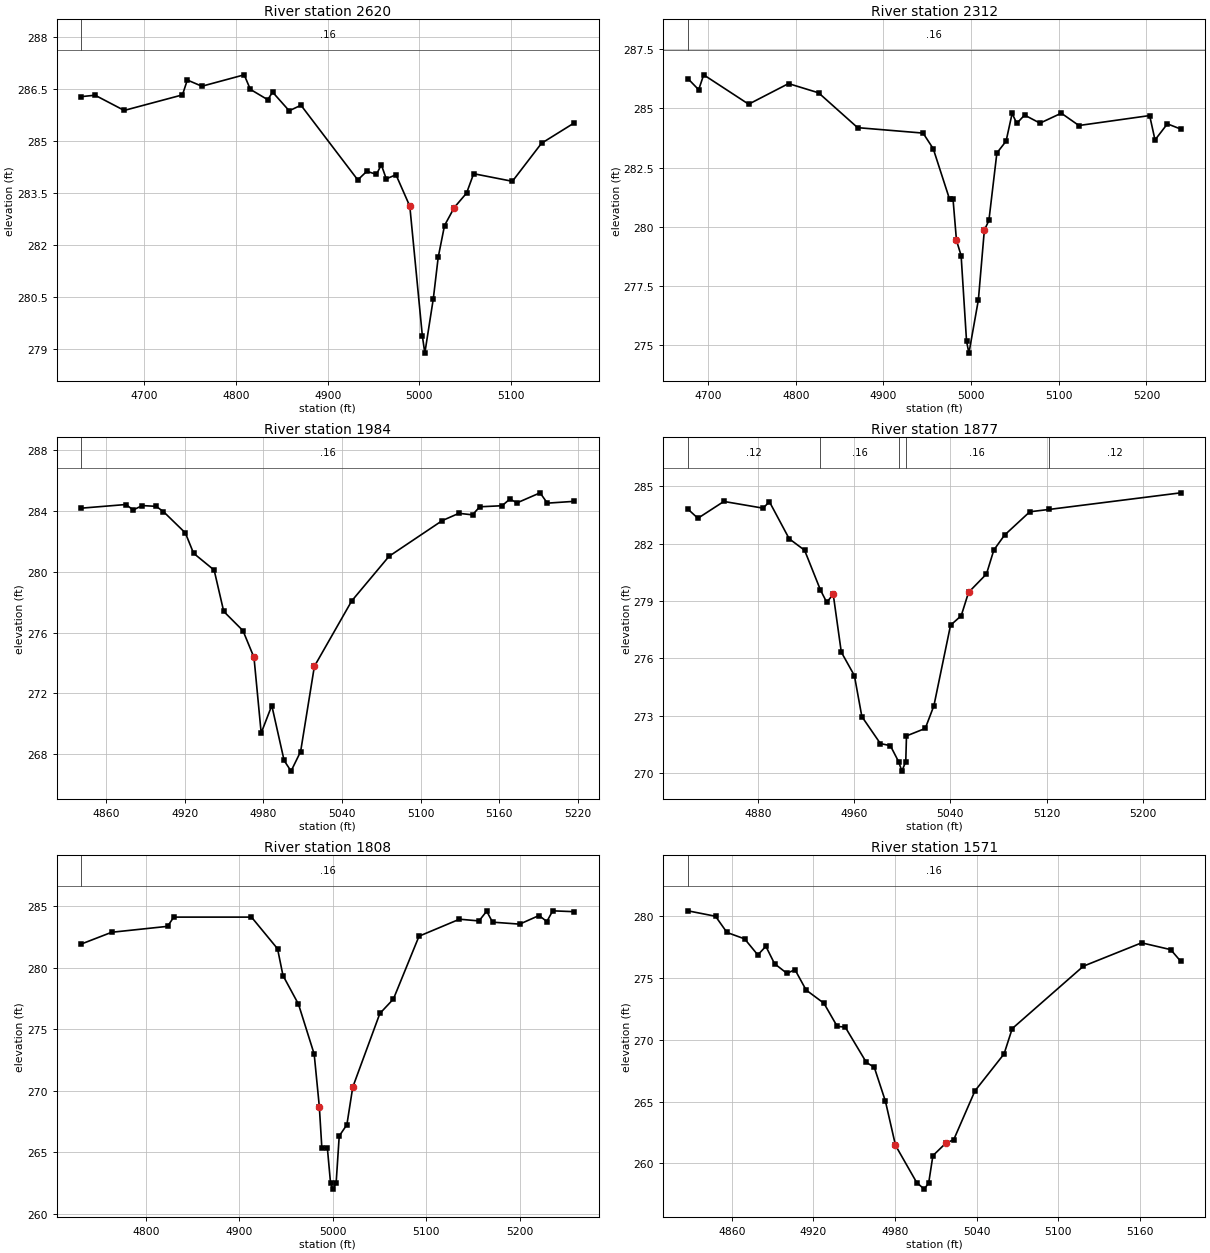
Type RM Length L Ch R = 1 ,2620    ,308,308,308
BEGIN DESCRIPTION:
UNT 167 IN BOCR 5.0
END DESCRIPTION:
XS GIS Cut Line= 2
      3710743.68     10619503.46      3710235.86      10619325.5
#Sta/Elev= 30
  4631.2  286.29  4646.1  286.33  4677.9  285.89  4741.5  286.34  4746.8  286.77
  4762.7  286.59  4808.9  286.92  4815.6   286.5  4834.6   286.2  4839.9  286.42
    4858  285.88  4870.9  286.04  4932.9  283.88  4942.8  284.13  4953.3  284.04
  4958.6  284.32    4964  283.91  4974.6  284.03  4989.7  283.12  5003.4  279.37
  5006.1  278.87  5015.4  280.45  5020.7  281.64  5027.6  282.56  5038.2  283.08
  5051.7   283.5  5059.4  284.06  5101.7  283.84  5133.5  284.94  5169.3  285.53
#Mann= 1 ,-1 , 0
  4631.2     .16       0
Bank Sta=4989.7,5038.2
XS Rating Curve= 0 ,0
Exp/Cntr=0.3,0.1

Type RM Length L Ch R = 1 ,2312    ,328,328,328
BEGIN DESCRIPTION:
Mapping XS cc59993c
END DESCRIPTION:
XS GIS Cut Line= 6
      3710800.48     10619273.78      3710676.78      10619206.5
      3710625.79     10619179.38      3710527.04     10619146.82
      3710415.28     10619109.93      3710274.41     10619091.51
#Sta/Elev= 30
  4676.9  286.26  4689.2  285.79  4694.9  286.42  4746.2  285.18  4791.7  286.05
    4826  285.66  4870.5  284.19  4945.2  283.96  4956.8   283.3  4975.5  281.16
  4979.4  281.16  4983.3  279.43  4988.6  278.79  4994.8  275.17  4997.5  274.67
  5008.3  276.92  5015.1  279.86  5020.3  280.27  5029.4  283.12  5039.9  283.62
  5046.8  284.79  5052.1  284.37    5061  284.72  5078.6  284.38  5102.9   284.8
    5123  284.28  5203.7   284.7  5209.8  283.67  5223.9  284.35  5239.2  284.13
#Mann= 1 ,-1 , 0
  4676.9     .16       0
Bank Sta=4983.3,5015.1
XS Rating Curve= 0 ,0
Exp/Cntr=0.3,0.1

Type RM Length L Ch R = 1 ,1984    ,107,107,107
BEGIN DESCRIPTION:
UNT 167 IN BOCR 4.0
END DESCRIPTION:
XS GIS Cut Line= 2
      3710591.81      10618839.4      3710249.48      10618995.4
#Sta/Elev= 30
  4841.1   284.2  4875.1  284.44  4880.6  284.08  4887.5  284.37  4898.1  284.32
  4903.6  283.98  4920.4  282.57  4926.7  281.23  4942.4  280.12  4949.7   277.4
  4964.4  276.13  4972.8  274.37  4978.3  269.39  4986.4   271.2  4995.8  267.58
  5001.1  266.88  5008.4  268.17  5018.9  273.78  5047.4  278.09  5075.9  281.03
  5116.5  283.38  5129.2  283.86  5139.6  283.76  5145.1  284.29  5162.2  284.36
  5168.1   284.8  5173.6  284.55  5191.2  285.21  5196.7  284.53  5217.3  284.65
#Mann= 1 ,-1 , 0
  4841.1     .16       0
Bank Sta=4972.8,5018.9
XS Rating Curve= 0 ,0
Exp/Cntr=0.3,0.1

Type RM Length L Ch R = 1 ,1877    ,69,69,69
BEGIN DESCRIPTION:
Mapping XS 8ee1f2b2
END DESCRIPTION:
XS GIS Cut Line= 3
      3710567.23     10618749.04      3710388.02     10618824.11
       3710209.6     10618944.79
#Sta/Elev= 30
  4821.9   283.8  4830.2  283.32  4851.8   284.2  4884.3  283.85  4889.7  284.18
  4906.1  282.25  4918.9  281.65  4932.1  279.57  4937.3  278.93  4942.7  279.35
  4949.4  276.33  4960.3   275.1  4966.5  272.96  4981.9  271.55  4990.2  271.44
    4997  270.61  4999.8  270.11    5003  270.61  5003.6  271.95  5019.2  272.34
  5026.4  273.53  5040.2  277.73  5049.1  278.23  5055.2  279.45  5070.1  280.41
  5076.2  281.66  5085.1  282.44  5106.1  283.66  5121.9  283.78  5231.6  284.65
#Mann= 5 ,-1 , 0
  4821.9     .12       0  4932.1     .16       0    4997     .07       0
    5003     .16       0  5121.9     .12       0
Bank Sta=4942.7,5055.2
XS Rating Curve= 0 ,0
Exp/Cntr=0.3,0.1

Type RM Length L Ch R = 1 ,1808    ,237,237,237
BEGIN DESCRIPTION:
Mapping XS 8d1cccd9
END DESCRIPTION:
XS GIS Cut Line= 4
      3710621.46     10618629.24      3710474.96      10618705.2
      3710390.33     10618747.52      3710177.62     10618910.31
#Sta/Elev= 30
  4731.1  281.92  4763.5  282.87  4823.3  283.35  4829.9   284.1  4913.1   284.1
    4941  281.53  4946.8  279.36  4963.4  277.03  4980.2  272.98  4985.7  268.72
  4988.4  265.37  4994.3  265.37  4997.7  262.52  5000.4  262.02  5003.7  262.52
    5007  266.33  5015.2  267.25  5021.5   270.3  5050.5  276.28    5065  277.45
  5092.4  282.55  5135.7  283.93  5156.6  283.79  5164.8  284.58  5171.1  283.69
  5200.1  283.53  5220.9  284.23  5229.2  283.74  5235.5  284.61  5258.6  284.54
#Mann= 1 ,-1 , 0
  4731.1     .16       0
Bank Sta=4985.7,5021.5
XS Rating Curve= 0 ,0
Exp/Cntr=0.3,0.1

Type RM Length L Ch R = 1 ,1571    ,395,395,395
BEGIN DESCRIPTION:
UNT 167 IN BOCR 3.0
END DESCRIPTION:
XS GIS Cut Line= 2
      3710444.26     10618466.13      3710133.21      10618651.9
#Sta/Elev= 30
  4827.7  280.44    4848     280  4856.4  278.69  4869.4  278.17  4879.1  276.87
    4885  277.57  4891.4  276.16  4900.5  275.38  4906.4  275.68  4914.6  274.03
  4927.7  272.96  4937.5  271.08  4943.3  271.04  4958.9  268.17  4964.7  267.78
  4972.9  265.03  4980.3  261.46  4995.9  258.45  5001.4  257.92  5004.7  258.42
  5007.8  260.63  5017.3  261.64  5023.1  261.92  5038.7  265.87  5060.1  268.86
  5066.1  270.91  5118.4  275.96  5161.2  277.85  5182.6   277.3    5190  276.35
#Mann= 1 ,-1 , 0
  4827.7     .16       0
Bank Sta=4980.3,5017.3
XS Rating Curve= 0 ,0
Exp/Cntr=0.3,0.1

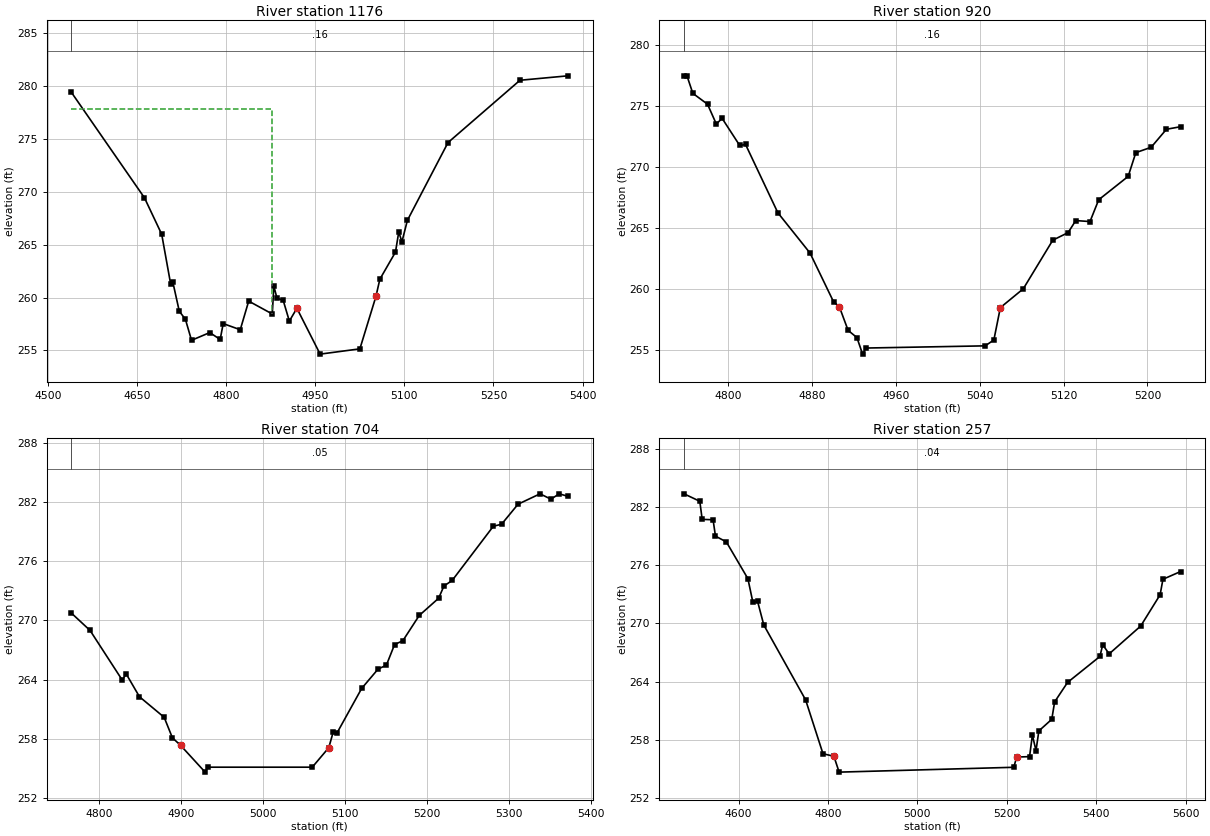
Type RM Length L Ch R = 1 ,1176    ,256,256,256
BEGIN DESCRIPTION:
Mapping XS 6f0ef288
END DESCRIPTION:
XS GIS Cut Line= 6
      3710641.63     10618010.97       3710498.4     10618107.33
      3710339.54     10618143.79      3710141.63     10618201.08
      3709943.71     10618281.81      3709878.63     10618328.67
#Sta/Elev= 30
  4539.8  279.43  4662.8  269.44  4691.8  265.99  4706.8   261.3  4710.5  261.47
  4721.4   258.7  4731.7  257.94    4742  255.95  4772.7  256.68  4790.2  256.03
  4795.3  257.53    4824  256.95  4838.2  259.66  4877.9  258.44  4880.5  261.09
  4885.8  259.93  4896.2  259.74  4906.6  257.77  4919.3  258.98  4958.4  254.64
  5025.3  255.14  5052.3   260.1  5058.9  261.73  5085.2   264.3  5090.7   266.2
  5096.1  265.28  5105.2   267.3  5173.6  274.67  5294.7  280.57  5375.4  280.99
#Mann= 1 ,-1 , 0
  4539.8     .16       0
#XS Ineff= 2 , 0
          4876.7  277.82
Permanent Ineff=
       F       F
Bank Sta=4919.3,5052.3
XS Rating Curve= 0 ,0
Exp/Cntr=0.3,0.1

Type RM Length L Ch R = 1 ,920     ,216,216,216
BEGIN DESCRIPTION:
UNT 167 IN BOCR 2.0
END DESCRIPTION:
XS GIS Cut Line= 3
      3710299.62     10617860.18      3710099.61     10617960.19
      3709949.62     10618160.18
#Sta/Elev= 30
    4758   277.5  4760.8   277.5  4766.4  276.06  4780.4  275.17  4788.8  273.54
  4794.3  274.01  4811.1  271.78  4816.7  271.86  4847.5  266.25  4878.2  262.94
  4900.6  258.94  4906.1  258.54  4914.5  256.59  4922.9     256  4928.3  254.64
  4931.5  255.14  5045.2  255.32  5053.5   255.8  5059.7  258.46  5081.6  260.01
  5109.7     264  5124.3  264.62  5131.6  265.61  5145.2  265.53  5153.5  267.32
  5181.6  269.24  5188.9  271.19  5203.5  271.63  5218.1  273.11  5231.6  273.32
#Mann= 1 ,-1 , 0
    4758     .16       0
Bank Sta=4906.1,5059.7
XS Rating Curve= 0 ,0
Exp/Cntr=0.3,0.1

Type RM Length L Ch R = 1 ,704     ,447,447,447
BEGIN DESCRIPTION:
Mapping XS fc219bc1
END DESCRIPTION:
XS GIS Cut Line= 2
      3710292.31       10617750.        3709689.     10617797.74
#Sta/Elev= 30
  4766.2  270.74    4789  268.98  4828.1  263.97  4833.1  264.57  4849.2  262.27
  4879.3  260.19  4889.3  258.12  4899.3  257.35  4929.2  254.64  4932.4  255.14
  5059.8  255.14  5079.9  257.11  5085.2  258.66  5090.2  258.64    5120  263.11
  5140.1  265.08  5150.1  265.46  5160.1  267.55  5170.2  267.94  5190.2   270.5
  5213.8  272.24  5220.3  273.48  5230.3  274.04  5280.5  279.53  5290.5  279.73
  5310.6  281.76  5337.4  282.81  5350.7  282.27  5360.8  282.81  5371.4  282.56
#Mann= 1 ,-1 , 0
  4766.2     .05       0
Bank Sta=4899.3,5079.9
XS Rating Curve= 0 ,0
Exp/Cntr=0.3,0.1

Type RM Length L Ch R = 1 ,257     ,0,0,0
BEGIN DESCRIPTION:
UNT 167 IN BOCR 1.0
END DESCRIPTION:
XS GIS Cut Line= 4
      3710409.53     10617763.05      3710244.58     10617346.35
      3710062.29     10617324.65      3709767.15     10617702.25
#Sta/Elev= 30
    4478   283.4  4513.3  282.63  4518.6  280.76    4543  280.72  4548.3  279.03
  4572.7  278.43  4620.9  274.63  4632.1  272.18  4642.4  272.32  4656.5  269.84
    4750  262.11  4788.9  256.54  4813.3  256.28    4825  254.64  5215.8  255.14
  5222.2   256.2  5251.1  256.24  5257.4  258.47  5265.5  256.86  5271.9   258.9
  5300.8   260.1  5307.2   261.9  5336.1  263.91  5408.4  266.59  5414.8   267.8
  5429.2  266.86  5499.8  269.74  5543.2  272.97  5549.5  274.57    5589  275.37
#Mann= 1 ,-1 , 0
    4478     .04       0
Bank Sta=4813.3,5222.2
XS Rating Curve= 0 ,0
Exp/Cntr=0.3,0.1

Chan Stop Cuts=-1
Use User Specified Reach Order=0
Composite Channel Slope=5