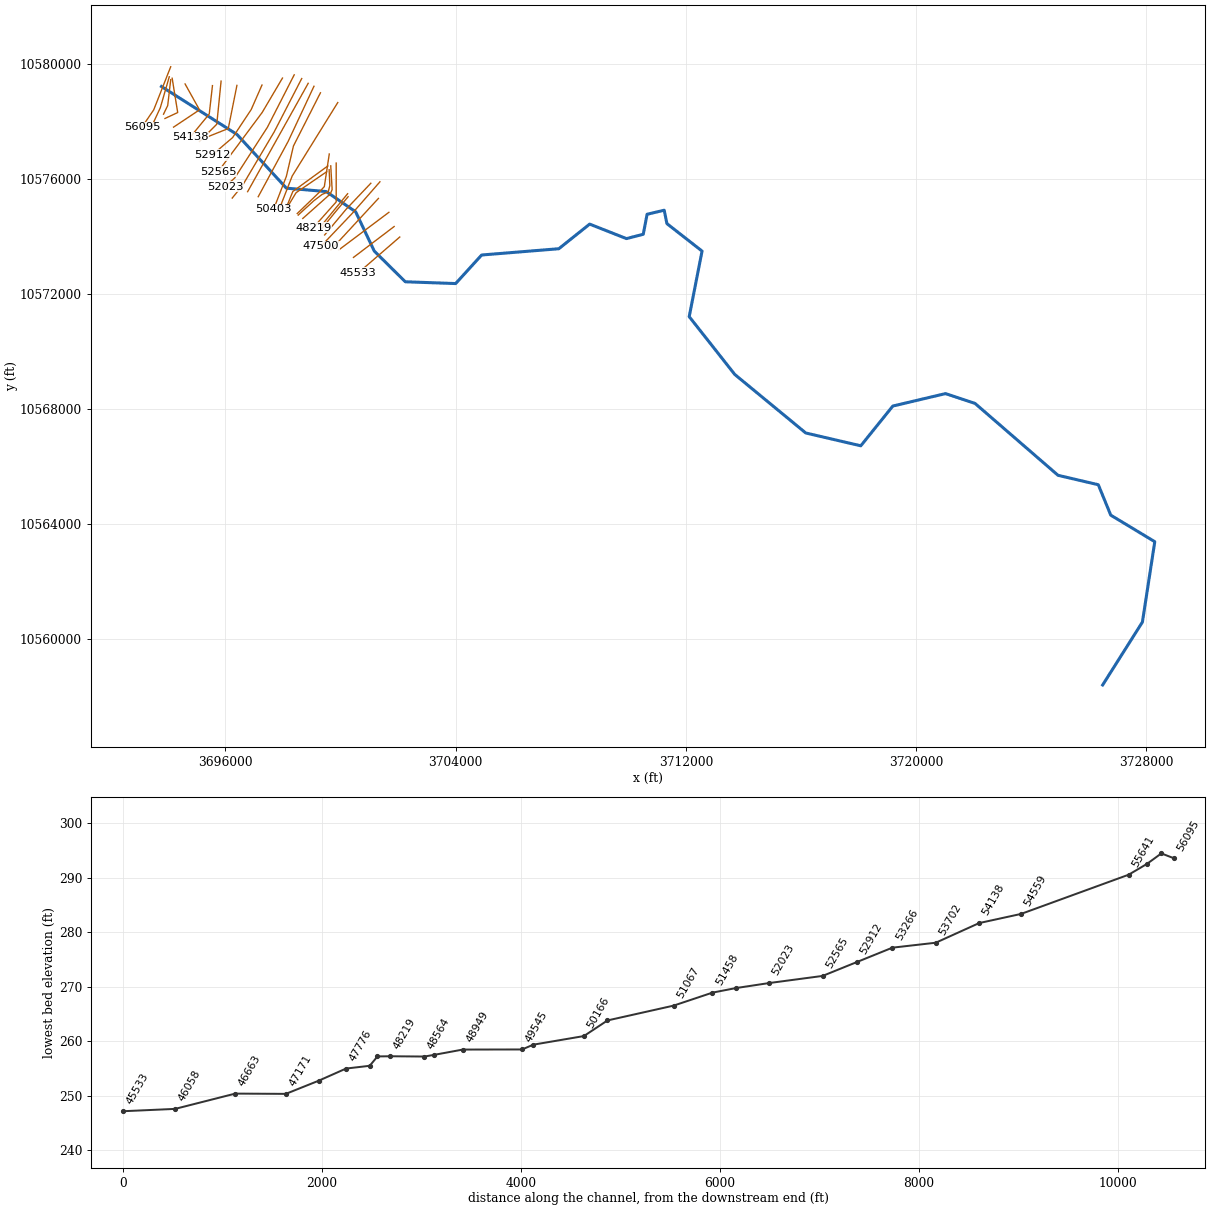
--- UNT 168 IN BOCR.prj (project) ---

Proj Title=UNT 168 IN BOCR Base Level Engineering
Current Plan=p01
Default Exp/Contr=0.3,0.1
English Units
Geom File=g01
Flow File=f01
Plan File=p01
Y Axis Title=Elevation
X Axis Title(PF)=Main Channel Distance
X Axis Title(XS)=Station
BEGIN DESCRIPTION:
UNT 168 IN BOCR
END DESCRIPTION:
DSS Export Rating Curves= 0
DSS Export Rating Curve Sorted= 0
DSS Export Volume Flow Curves= 0
DXF OffsetX= 0
DXF OffsetY= 0
DXF ScaleX= 1
DXF ScaleY= 10

--- UNT 168 IN BOCR.p01 (plan) ---

Plan Title=Multiple Run
Short Identifier=Multiple
Geom File=g01
Flow File=f01
Subcritical Flow
K Sum by GR= 0
Std Step Tol= 0.01
Critical Tol= 0.01
Num of Std Step Trials= 20
Max Error Tol= 0.3
Flow Tol Ratio= 0.001
Split Flow NTrial= 30
Split Flow Tol= 0.02
Split Flow Ratio= 0.02
Log Output Level= 0
Friction Slope Method= 1
Unsteady Friction Slope Method= 2
Unsteady Bridges Friction Slope Method= 1
Parabolic Critical Depth
Global Vel Dist=  1 , 1 , 1
Global Log Level= 0
CheckData=True
Encroach Param= -1, 0, 0, 0
BEGIN DESCRIPTION:
Multiple Run
END DESCRIPTION:

--- UNT 168 IN BOCR.f01 (steady flow) ---

Flow Title=Multiple
Program Version=4.10
Number of Profiles= 7
Profile Names=10-year,25-year,50-year,1pct_min,100-year,1pct_plu,500-year
River Rch & RM=UNT 168 IN BOCR,Reach-1         ,56095
     426     564     675     594     804    1087    1143
River Rch & RM=UNT 168 IN BOCR,Reach-1         ,55969
     632     862    1053     944    1277    1727    1888
River Rch & RM=UNT 168 IN BOCR,Reach-1         ,45533
     867    1198    1474    1331    1801    2435    2699
River Rch & RM=UNT 168 IN BOCR,Reach-1         ,38811
    1001    1389    1715    1553    2100    2840    3164
River Rch & RM=UNT 168 IN BOCR,Reach-1         ,31576
    1173    1637    2029    1843    2492    3370    3778
River Rch & RM=UNT 168 IN BOCR,Reach-1         ,28937
    1248    1736    2146    1943    2627    3553    3958
River Rch & RM=UNT 168 IN BOCR,Reach-1         ,20410
    1245    1720    2117    1906    2577    3485    3841
River Rch & RM=UNT 168 IN BOCR,Reach-1         ,5362
    1383    1918    2366    2135    2888    3906    4324
River Rch & RM=UNT 168 IN BOCR,Reach-1         ,4476
    1447    2007    2476    2235    3022    4087    4524
River Rch & RM=UNT 168 IN BOCR,Reach-1         ,960
    1500    2082    2571    2321    3139    4246    4705
Boundary for River Rch & Prof#=UNT 168 IN BOCR,Reach-1         , 1
Up Type= 0
Dn Type= 3
Dn Slope=0.003
Boundary for River Rch & Prof#=UNT 168 IN BOCR,Reach-1         , 2
Up Type= 0
Dn Type= 3
Dn Slope=0.003
Boundary for River Rch & Prof#=UNT 168 IN BOCR,Reach-1         , 3
Up Type= 0
Dn Type= 3
Dn Slope=0.003
Boundary for River Rch & Prof#=UNT 168 IN BOCR,Reach-1         , 4
Up Type= 0
Dn Type= 3
Dn Slope=0.003
Boundary for River Rch & Prof#=UNT 168 IN BOCR,Reach-1         , 5
Up Type= 0
Dn Type= 3
Dn Slope=0.003
Boundary for River Rch & Prof#=UNT 168 IN BOCR,Reach-1         , 6
Up Type= 0
Dn Type= 3
Dn Slope=0.003
Boundary for River Rch & Prof#=UNT 168 IN BOCR,Reach-1         , 7
Up Type= 0
Dn Type= 3
Dn Slope=0.003
DSS Import GetInterval= 0
DSS Import GetPeak= 0
DSS Import FillOption= 0

--- UNT 168 IN BOCR.g01 (geometry) ---

Geom Title=Existing Conditions
Program Version=4.10

River Reach=UNT 168 IN BOCR ,Reach-1
Reach XY= 30
      3693777.41      10579222.1        3696401.       10577556.
       3698117.5       10575688.      3699502.25       10575570.
      3700525.75       10574865.       3701171.5       10573501.
      3702250.75       10572433.      3703999.75       10572371.
      3704902.75       10573364.      3707584.25       10573582.
      3708655.75       10574438.        3709934.       10573934.
      3710517.75       10574085.        3710651.       10574780.
       3711245.5       10574921.      3711339.75       10574455.
       3712560.5       10573500.      3712114.25       10571221.
        3713697.       10569211.      3716163.25       10567176.
        3718076.       10566730.        3719188.       10568112.
      3721018.75       10568545.      3722044.75       10568204.
      3724929.25       10565704.      3726327.75       10565377.
      3726760.75       10564319.        3728290.       10563396.
       3727860.5       10560602.        3726479.       10558414.

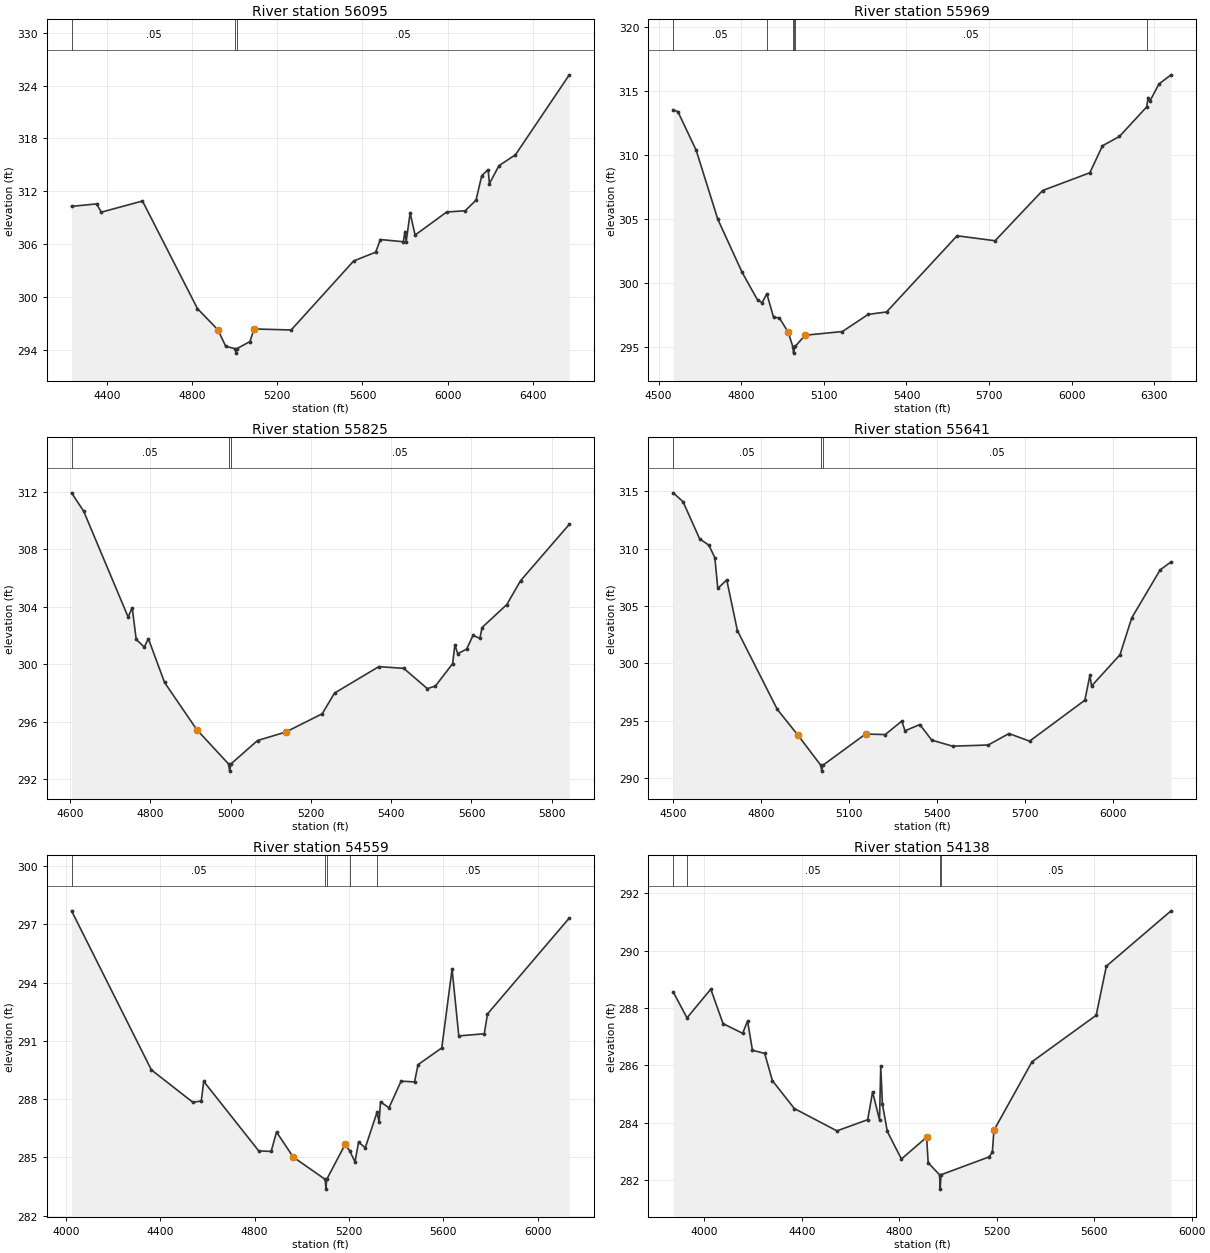
Type RM Length L Ch R = 1 ,56095   ,126,126,126
BEGIN DESCRIPTION:
UNT 168 IN BOCR 117.0
END DESCRIPTION:
XS GIS Cut Line= 3
       3694099.6     10579910.18      3693509.87      10578412.5
      3693099.59     10577810.16
#Sta/Elev= 30
  4233.2  310.28    4351  310.56  4372.9  309.62  4566.4  310.89  4824.8  298.65
    4921  296.25  4957.6  294.37  5003.3   294.1  5006.1   293.6  5009.3   294.1
  5071.5  294.92  5090.3  296.35  5264.9  296.23  5558.7  304.08  5661.7  305.07
  5684.1  306.51  5791.6  306.26  5799.8  307.41  5805.1  306.25  5823.8  309.52
  5847.2  307.02  5995.6  309.64  6082.3  309.78  6133.2  310.98  6160.2  313.76
    6190  314.46  6196.5  312.87  6240.9   314.9  6318.8  316.15  6571.6  325.23
#Mann= 3 ,-1 , 0
  4233.2     .05       0  5003.3     .03       0  5009.3     .05       0
Bank Sta=4921,5090.3
XS Rating Curve= 0 ,0
Exp/Cntr=0.3,0.1

Type RM Length L Ch R = 1 ,55969   ,144,144,144
BEGIN DESCRIPTION:
UNT 168 IN BOCR 116.0
END DESCRIPTION:
XS GIS Cut Line= 3
       3694049.6     10579560.16      3693738.17     10578483.84
      3693449.63     10577860.23
#Sta/Elev= 30
  4553.2  313.52    4570  313.38  4636.4  310.36  4714.8  304.97    4803  300.82
  4859.6  298.63  4875.9  298.45    4893  299.13  4917.5  297.29  4938.3  297.25
  4970.8  296.12  4987.4  294.99  4990.1  294.49  4993.4  294.99  4996.2  295.02
    5032  295.89  5167.4  296.18  5261.1  297.52  5327.7  297.71  5583.8  303.67
  5721.8  303.28  5894.5  307.21    6066   308.6  6111.9  310.71  6173.5  311.44
  6272.3  313.75  6277.8  314.48  6283.7  314.19  6316.8  315.54  6360.8  316.26
#Mann= 6 ,-1 , 0
  4553.2     .05       0    4893     .08       0  4987.4     .03       0
  4993.4     .08       0  4996.2     .05       0  6272.3     .08       0
Bank Sta=4970.8,5032
XS Rating Curve= 0 ,0
Exp/Cntr=0.3,0.1

Type RM Length L Ch R = 1 ,55825   ,184,184,184
BEGIN DESCRIPTION:
UNT 168 IN BOCR 115.0
END DESCRIPTION:
XS GIS Cut Line= 3
       3694099.6     10579460.15      3693995.11     10578560.23
      3693849.62     10578260.22
#Sta/Elev= 30
  4604.2  311.93  4634.4  310.65  4745.1  303.29  4755.2  303.94  4765.2  301.73
  4785.4   301.2  4795.4  301.79  4835.7  298.74  4916.2  295.45  4995.1  293.07
  4997.8  292.57  5001.1  293.07  5067.3   294.7  5137.7  295.29  5228.3  296.56
    5259     298  5369.3  299.84  5431.3  299.72  5490.1  298.31  5510.2  298.49
  5553.1  300.05  5558.7  301.36  5565.8  300.74    5588  301.06  5603.8  302.01
  5620.9  301.81  5626.4  302.56    5688  304.16  5722.3  305.82  5843.6  309.74
#Mann= 3 ,-1 , 0
  4604.2     .05       0  4995.1     .03       0  5001.1     .05       0
Bank Sta=4916.2,5137.7
XS Rating Curve= 0 ,0
Exp/Cntr=0.3,0.1

Type RM Length L Ch R = 1 ,55641   ,1082,1082,1082
BEGIN DESCRIPTION:
UNT 168 IN BOCR 114.0
END DESCRIPTION:
XS GIS Cut Line= 3
      3694149.62     10579510.14      3694342.33     10578317.17
      3693899.57     10578110.17
#Sta/Elev= 30
  4500.7  314.88  4534.1   314.1  4590.7  310.86  4622.2  310.31  4642.5  309.21
  4652.5  306.53    4683  307.28  4719.3  302.85  4855.2  295.98  4926.1  293.71
  5004.1  291.08  5006.9  290.58  5010.1  291.08  5156.5  293.82  5223.3  293.77
    5280  294.95  5290.8   294.1  5341.4  294.65  5381.9  293.29  5452.8  292.76
  5574.4  292.86  5645.3  293.86  5715.7   293.2    5904  296.77  5921.3  298.95
  5926.9  298.01  6023.8  300.74  6063.9  303.96  6160.8  308.15  6197.9  308.85
#Mann= 3 ,-1 , 0
  4500.7     .05       0  5004.1     .03       0  5010.1     .05       0
Bank Sta=4926.1,5156.5
XS Rating Curve= 0 ,0
Exp/Cntr=0.3,0.1

Type RM Length L Ch R = 1 ,54559   ,421,421,421
BEGIN DESCRIPTION:
UNT 168 IN BOCR 113.0
END DESCRIPTION:
XS GIS Cut Line= 3
      3694599.63     10579310.15      3695099.61     10578410.19
      3694199.59     10577810.18
#Sta/Elev= 30
  4023.3   297.7  4361.9  289.51    4538  287.84  4573.5  287.91  4583.8  288.92
  4817.2  285.34  4869.8  285.31  4892.7  286.31  4963.6  285.02  5099.4  283.87
  5102.1  283.37  5105.4  283.87  5183.5  285.67  5202.9  285.35  5225.6  284.77
  5240.6  285.79  5269.1   285.5    5319  287.33  5327.7  286.81  5333.7  287.86
  5369.8  287.56  5420.9  288.93    5478  288.89    5493  289.78  5593.6  290.64
  5637.2   294.7  5665.8  291.26  5773.9  291.37  5787.4  292.39  6134.5  297.33
#Mann= 5 ,-1 , 0
  4023.3     .05       0  5099.4     .03       0  5105.4     .05       0
  5202.9     .16       0    5319     .05       0
Bank Sta=4963.6,5183.5
XS Rating Curve= 0 ,0
Exp/Cntr=0.3,0.1

Type RM Length L Ch R = 1 ,54138   ,436,436,436
BEGIN DESCRIPTION:
UNT 168 IN BOCR 112.0
END DESCRIPTION:
XS GIS Cut Line= 3
      3695549.75     10579253.17      3695438.64     10578267.02
      3694772.22     10577454.82
#Sta/Elev= 30
  3872.3  288.56  3928.6  287.66  4026.3  288.66  4076.6  287.46  4157.1  287.12
  4177.2  287.55  4197.3  286.53  4247.6  286.42  4279.2  285.47  4369.1   284.5
    4544  283.72  4670.3  284.11  4690.4  285.08  4718.8   284.1  4723.8  285.97
  4730.7  284.66  4750.8   283.7  4808.7  282.74  4912.1   283.5  4918.6  282.61
  4965.1  282.19  4967.8  281.69  4971.1  282.19  5167.6  282.81  5181.9  282.97
  5188.4  283.74  5344.8  286.13  5608.2  287.75  5649.8  289.46  5915.3  291.39
#Mann= 4 ,-1 , 0
  3872.3     .08       0  3928.6     .05       0  4965.1     .03       0
  4971.1     .05       0
Bank Sta=4912.1,5188.4
XS Rating Curve= 0 ,0
Exp/Cntr=0.3,0.1

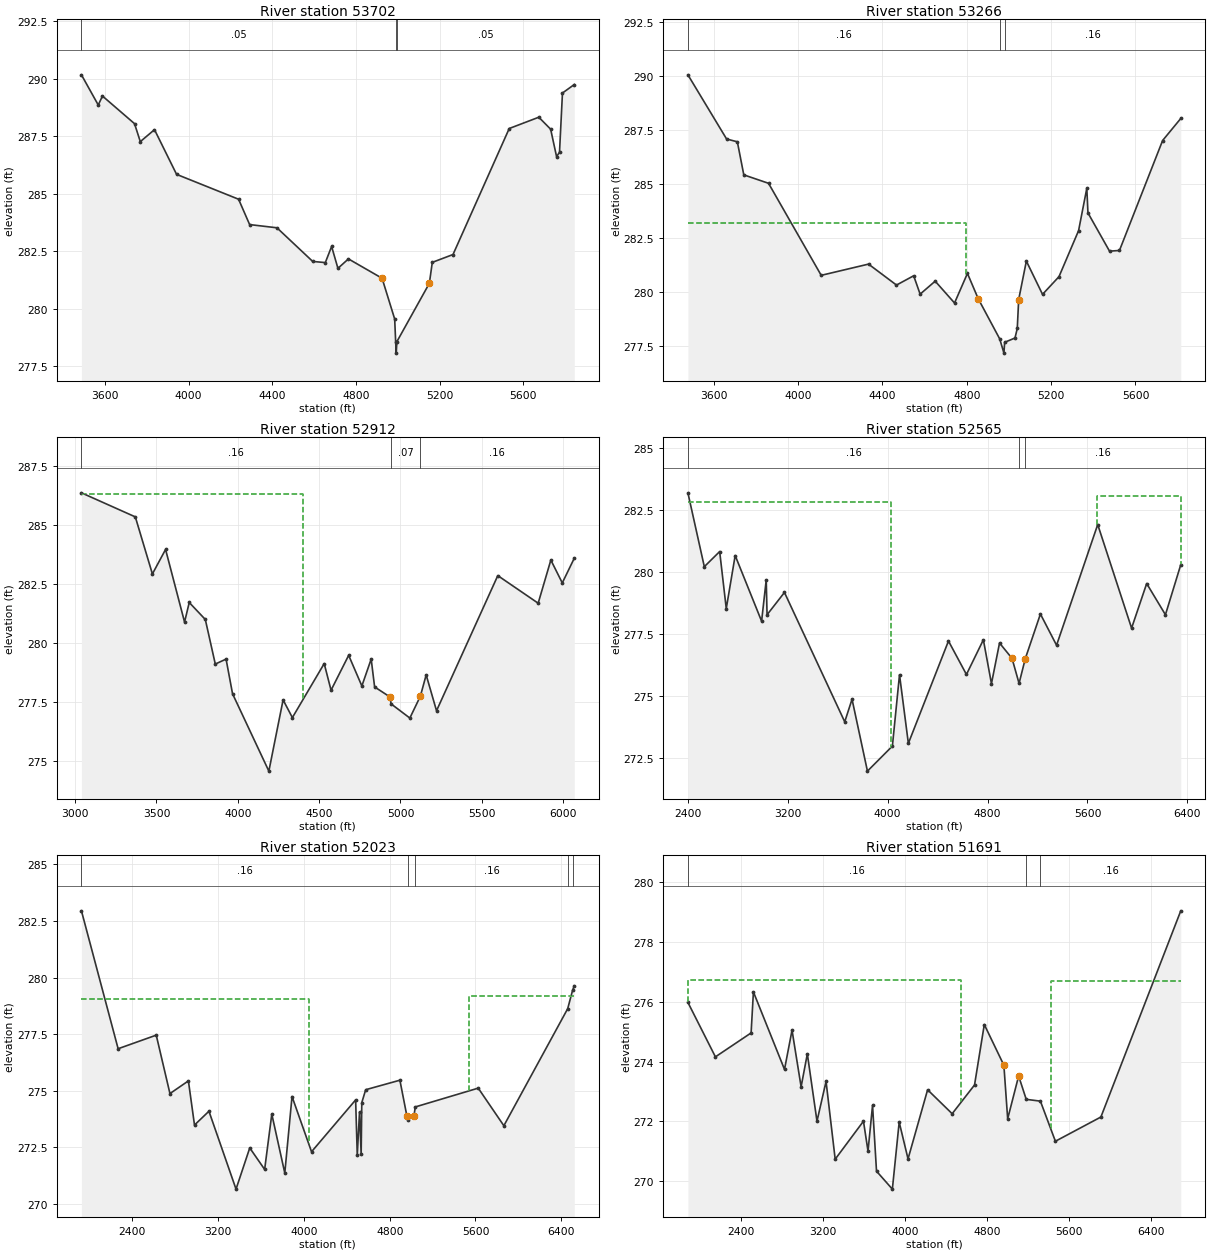
Type RM Length L Ch R = 1 ,53702   ,436,436,436
BEGIN DESCRIPTION:
UNT 168 IN BOCR 111.0
END DESCRIPTION:
XS GIS Cut Line= 3
      3695849.61     10579410.19      3695699.61     10577910.19
      3695099.62      10577310.2
#Sta/Elev= 30
  3487.5  290.16  3567.9  288.85    3588  289.24  3741.3  288.04  3768.9  287.26
  3836.7  287.78  3942.3  285.84  4238.7  284.76  4291.5  283.66  4422.1  283.52
    4593  282.06  4653.3  282.01  4683.4  282.71  4713.6  281.76  4763.8  282.17
  4924.6  281.33  4984.9  279.56  4989.5  278.58  4992.2  278.08  4995.5  278.58
  5150.6  281.11  5164.7  282.02  5263.7  282.36  5532.4  287.83  5673.8  288.32
  5730.4   287.8  5758.7  286.61  5772.8   286.8  5786.9  289.37  5843.5  289.74
#Mann= 3 ,-1 , 0
  3487.5     .05       0  4989.5     .03       0  4995.5     .05       0
Bank Sta=4924.6,5150.6
XS Rating Curve= 0 ,0
Exp/Cntr=0.3,0.1

Type RM Length L Ch R = 1 ,53266   ,354,354,354
BEGIN DESCRIPTION:
UNT 168 IN BOCR 110.0
END DESCRIPTION:
XS GIS Cut Line= 3
       3696399.6     10579260.14      3696099.61     10577760.19
      3695349.64      10577460.2
#Sta/Elev= 30
  3477.5  290.05    3661  287.08    3712  286.95  3742.6  285.42  3859.9  285.03
  4109.7  280.77  4334.1  281.29  4466.7  280.32  4548.2  280.75  4578.8   279.9
  4650.2   280.5    4742  279.49  4803.2  280.86  4854.2  279.69  4956.2  277.83
  4976.3  277.17  4979.6  277.67  5028.7  277.87  5039.5  278.31  5046.2  279.65
  5082.6  281.43  5159.3  279.89  5237.4  280.71  5330.3  282.84  5369.3   284.8
  5374.7  283.66    5477  281.89  5524.1  281.92  5728.8  287.01  5814.9  288.03
#Mann= 3 ,-1 , 0
  3477.5     .16       0  4956.2     .07       0  4979.6     .16       0
#XS Ineff= 2 , 0
         4796.59  283.19
Permanent Ineff=
       F       F
Bank Sta=4854.2,5046.2
XS Rating Curve= 0 ,0
Exp/Cntr=0.3,0.1

Type RM Length L Ch R = 1 ,52912   ,347,347,347
BEGIN DESCRIPTION:
UNT 168 IN BOCR 109.0
END DESCRIPTION:
XS GIS Cut Line= 4
      3697270.78     10579273.33      3696895.73     10578420.91
      3696251.14     10577447.57      3695542.81     10576843.41
#Sta/Elev= 30
    3039  286.35  3370.2  285.33  3475.2  282.91  3556.2  283.95  3672.9  280.87
  3701.7   281.7  3800.5  280.98  3861.8  279.09  3928.1   279.3  3967.9  277.83
  4191.1  274.55  4278.6  277.57  4335.7  276.82  4531.3  279.11  4573.4  277.98
  4681.7  279.46  4762.8  278.16  4820.1   279.3  4841.2  278.12  4934.4   277.7
  4942.7   277.4  5057.8   276.8  5122.6  277.73  5158.1  278.63  5221.8  277.11
  5598.4  282.84  5846.6  281.67  5924.5   283.5  5994.8  282.53  6068.7  283.58
#Mann= 3 ,-1 , 0
    3039     .16       0  4942.7     .07       0  5122.6     .16       0
#XS Ineff= 2 , 0
       0    4400  286.31               0
Permanent Ineff=
       F       F
Bank Sta=4934.4,5122.6
XS Rating Curve= 0 ,0
Exp/Cntr=0.3,0.1

Type RM Length L Ch R = 1 ,52565   ,542,542,542
BEGIN DESCRIPTION:
UNT 168 IN BOCR 108.0
END DESCRIPTION:
XS GIS Cut Line= 3
      3697982.59     10579516.39      3697278.68      10578321.3
      3695751.11     10576266.99
#Sta/Elev= 30
  2400.2  283.21  2531.7  280.23  2654.6  280.84  2707.4  278.54  2778.8  280.68
  2990.4  278.03  3027.5   279.7  3034.1  278.29  3173.4  279.19  3656.1  273.97
  3714.7  274.88    3838  271.98  4037.8  272.99  4094.8  275.87  4165.7   273.1
  4486.9  277.23  4630.8  275.88  4766.4  277.28  4831.1  275.51  4895.8  277.15
  4995.9  276.53  5052.2  275.52  5102.2  276.52  5223.2  278.32  5352.5  277.06
  5682.1  281.93  5953.3  277.75  6074.2  279.55  6224.4  278.29  6347.2  280.31
#Mann= 3 ,-1 , 0
  2400.2     .16       0  5052.2     .07       0  5102.2     .16       0
#XS Ineff= 2 , 0
         4025.09  282.84 5679.81          283.09
Permanent Ineff=
       F       F
Bank Sta=4995.9,5102.2
XS Rating Curve= 0 ,0
Exp/Cntr=0.3,0.1

Type RM Length L Ch R = 1 ,52023   ,332,332,332
BEGIN DESCRIPTION:
UNT 168 IN BOCR 107.0
END DESCRIPTION:
XS GIS Cut Line= 4
      3698390.59     10579629.27      3697459.17     10577805.49
      3696320.58     10576037.85      3695986.13     10575742.44
#Sta/Elev= 30
  1924.9  282.95  2267.1  276.86  2622.6  277.46  2750.4  274.88  2922.5  275.44
  2979.4  273.49  3114.1   274.1  3366.7  270.66  3494.7  272.48  3633.6  271.53
  3700.3  273.97  3821.5  271.37  3888.9  274.75  4070.9  272.31  4482.2   274.6
  4497.4  272.16  4518.5  274.07  4533.7   272.2  4539.6  274.48  4575.9  275.05
    4895  275.47  4960.2  273.89  4966.3  273.73  5025.8  273.89  5038.7  274.29
  5625.6  275.12  5864.6  273.46  6460.1  278.63  6505.5  279.44  6521.6  279.64
#Mann= 5 ,-1 , 0
  1924.9     .16       0  4966.3     .07       0  5038.7     .16       0
  6460.1     .08       0  6505.5     .05       0
#XS Ineff= 2 , 0
         4046.59  279.04 5537.63          279.17
Permanent Ineff=
       F       F
Bank Sta=4960.2,5025.8
XS Rating Curve= 0 ,0
Exp/Cntr=0.3,0.1

Type RM Length L Ch R = 1 ,51691   ,233,233,233
BEGIN DESCRIPTION:
UNT 168 IN BOCR 106.0
END DESCRIPTION:
XS GIS Cut Line= 4
      3698651.01     10579499.06      3697695.26     10577645.47
      3696586.98     10575770.72      3696236.98     10575344.15
#Sta/Elev= 30
  1877.5  275.98  2146.3  274.16    2495  274.96  2517.5  276.33  2821.3  273.74
  2894.8  275.05  2983.5  273.16  3044.3  274.26  3138.6  272.01  3227.2  273.34
  3316.4  270.74  3592.7  272.01  3637.1  271.01  3681.4  272.54  3720.1  270.34
    3875  269.74  3941.7  271.98  4028.1  270.75  4219.3  273.06  4459.2  272.26
  4677.7  273.22  4773.2  275.24  4964.4  273.88  5001.5  272.09  5108.7  273.52
  5182.8  272.74  5321.3  272.68  5467.7  271.34  5912.3  272.15  6692.6  279.04
#Mann= 3 ,-1 , 0
  1877.5     .16       0  5182.8     .07       0  5321.3     .16       0
#XS Ineff= 2 , 0
         4545.45  276.73 5421.59          276.69
Permanent Ineff=
       F       F
Bank Sta=4964.4,5108.7
XS Rating Curve= 0 ,0
Exp/Cntr=0.3,0.1

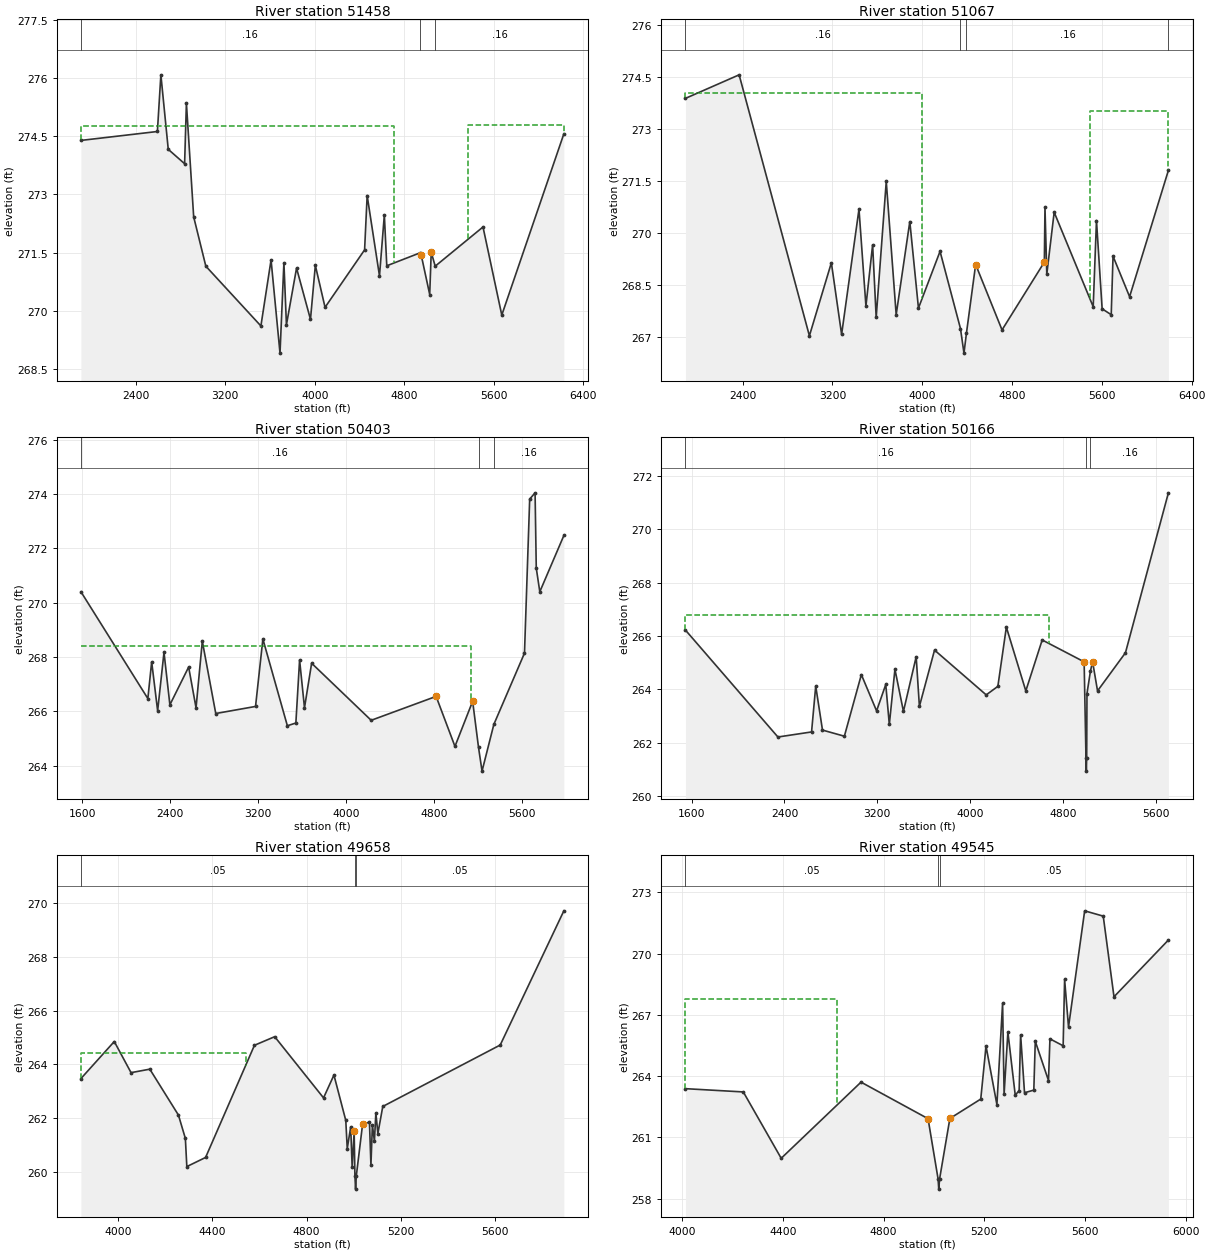
Type RM Length L Ch R = 1 ,51458   ,391,391,391
BEGIN DESCRIPTION:
Mapping XS c54c17ad
END DESCRIPTION:
XS GIS Cut Line= 2
      3698876.68     10579334.09      3696771.62     10575564.88
#Sta/Elev= 30
  1909.4  274.39  2592.9  274.62    2624  276.08    2690  274.16  2836.2  273.79
  2852.2  275.35  2917.3  272.42  3025.9  271.15  3518.2  269.61    3609  271.31
    3689  268.91  3723.9  271.24  3746.5  269.64  3836.9   271.1  3961.4  269.78
  4004.9  271.17  4091.7  270.09  4445.2  271.57  4468.1  272.97  4578.3   270.9
  4621.7  272.47  4643.5  271.16  4937.7  271.49  4951.9  271.43  5027.3  270.42
  5040.8  271.51  5076.4  271.15  5503.7  272.16  5671.6  269.89  6226.6  274.56
#Mann= 3 ,-1 , 0
  1909.4     .16       0  4937.7     .07       0  5076.4     .16       0
#XS Ineff= 2 , 0
          4712.5  274.76 5370.45          274.78
Permanent Ineff=
       F       F
Bank Sta=4951.9,5040.8
XS Rating Curve= 0 ,0
Exp/Cntr=0.3,0.1

Type RM Length L Ch R = 1 ,51067   ,664,664,664
BEGIN DESCRIPTION:
Mapping XS 04651af8
END DESCRIPTION:
XS GIS Cut Line= 3
      3699076.34     10579229.94      3698179.07     10577312.55
      3697140.38     10575390.97
#Sta/Elev= 30
  1891.5  273.88  2369.5  274.56  2995.3  267.02  3190.9  269.13  3282.2  267.06
  3436.9  270.68  3498.8  267.88  3558.4  269.65  3590.1  267.55  3679.8  271.48
  3768.2  267.63  3889.6  270.32  3966.6  267.82  4158.9  269.46  4340.8  267.23
    4372  266.52  4394.2   267.1    4476  269.08    4711  267.19  5087.9  269.15
  5093.5  270.73  5109.7   268.8  5175.4  270.59    5523  267.86  5552.2  270.35
  5602.6   267.8  5683.5  267.63  5699.7  269.32  5847.2  268.15  6192.8   271.8
#Mann= 4 ,-1 , 0
  1891.5     .16       0  4340.8     .07       0  4394.2     .16       0
  6192.8     .05       0
#XS Ineff= 2 , 0
         3996.42  274.03 5494.62          273.51
Permanent Ineff=
       F       F
Bank Sta=4476,5087.9
XS Rating Curve= 0 ,0
Exp/Cntr=0.3,0.1

Type RM Length L Ch R = 1 ,50403   ,237,237,237
BEGIN DESCRIPTION:
UNT 168 IN BOCR 105.0
END DESCRIPTION:
XS GIS Cut Line= 4
      3699302.02      10579004.2      3698364.38     10577155.32
      3698116.93     10576096.24      3697672.04     10574946.04
#Sta/Elev= 30
  1588.6   270.4  2197.4  266.47  2232.2  267.82  2286.5  266.02  2344.3  268.17
  2397.9  266.24  2568.6  267.63  2635.9  266.13  2692.9  268.58  2815.3  265.92
  3177.2  266.18    3244  268.66  3466.7  265.47  3544.1  265.57    3578  267.89
  3622.6  266.13  3687.5  267.77  4229.3  265.67  4820.1  266.55  4991.6  264.71
  5152.5  266.37  5206.1  264.67    5238   263.8  5345.5  265.52  5624.2  268.14
  5671.5  273.81  5720.6  274.04  5731.4  271.27  5763.6   270.4  5982.5  272.47
#Mann= 3 ,-1 , 0
  1588.6     .16       0  5206.1     .07       0  5345.5     .16       0
#XS Ineff= 2 , 0
         5142.05  268.41
Permanent Ineff=
       F       F
Bank Sta=4820.1,5152.5
XS Rating Curve= 0 ,0
Exp/Cntr=0.3,0.1

Type RM Length L Ch R = 1 ,50166   ,508,508,508
BEGIN DESCRIPTION:
Mapping XS 1ad8dfc6
END DESCRIPTION:
XS GIS Cut Line= 3
       3699903.6     10578663.92      3698320.91     10576111.82
      3697899.89     10575031.05
#Sta/Elev= 30
  1546.6  266.22  2343.4  262.21  2633.5   262.4  2669.4  264.12  2727.7  262.47
  2916.3  262.24  3062.8  264.55    3194  263.19  3273.1  264.18  3303.8  262.68
  3352.2  264.75  3425.5  263.17  3535.3  265.22  3563.1  263.36  3693.6  265.47
    4139  263.79  4239.4  264.11  4312.6  266.33  4480.4  263.94  4621.6  265.85
  4983.1  265.03  4999.1  261.43  5001.9  260.93  5005.1  261.43  5007.6  263.84
  5037.5  264.68  5055.8  265.04  5098.7  263.94  5339.3  265.37  5709.5  271.37
#Mann= 3 ,-1 , 0
  1546.6     .16       0  4999.1     .07       0  5037.5     .16       0
#XS Ineff= 2 , 0
         4681.82   266.8
Permanent Ineff=
       F       F
Bank Sta=4983.1,5055.8
XS Rating Curve= 0 ,0
Exp/Cntr=0.3,0.1

Type RM Length L Ch R = 1 ,49658   ,113,113,113
BEGIN DESCRIPTION:
Mapping XS 60fd847f
END DESCRIPTION:
XS GIS Cut Line= 3
      3699557.89     10576459.04      3698342.61     10575573.63
      3698138.63     10575070.19
#Sta/Elev= 30
  3843.7  263.47    3985  264.85  4056.1  263.69  4135.6  263.82  4256.9  262.11
  4286.3  261.24  4292.5  260.19    4372  260.53  4579.1  264.71  4664.9  265.03
  4871.9  262.75    4916   263.6  4966.2  261.91  4972.4  260.86    4987  261.67
  4993.2  260.17  5001.7   261.5  5004.9  259.85  5007.7  259.35  5010.9  259.85
  5037.3  261.76  5066.5  261.85  5072.8  260.25    5079  261.75  5087.5  261.13
  5093.7  262.19  5102.2  261.42    5123  262.43  5620.8  264.72  5890.5  269.72
#Mann= 3 ,-1 , 0
  3843.7     .05       0  5004.9     .03       0  5010.9     .05       0
#XS Ineff= 2 , 0
         4541.19  264.44
Permanent Ineff=
       F       F
Bank Sta=5001.7,5037.3
XS Rating Curve= 0 ,0
Exp/Cntr=0.3,0.1

Type RM Length L Ch R = 1 ,49545   ,596,596,596
BEGIN DESCRIPTION:
Mapping XS 630fb4fe
END DESCRIPTION:
XS GIS Cut Line= 3
      3699518.86     10576259.41      3698455.46     10575530.22
      3698130.91     10574993.63
#Sta/Elev= 30
  4013.9  263.39  4243.4  263.23  4393.8  259.98  4710.6  263.71  4976.6  261.92
  5016.4  258.97  5019.1  258.47  5022.4  258.97  5063.2  261.93  5185.7  262.88
  5206.7  265.47  5249.8  262.61  5272.4  267.57  5278.4  263.13  5293.4  266.16
  5322.6  263.07  5338.1   263.3  5343.9  266.03  5359.4  263.19  5396.3  263.32
  5402.1  265.71  5454.5  263.79  5460.3  265.83  5512.7  265.49  5518.5  268.74
    5534  266.41  5598.1   272.1  5671.8  271.84  5714.5  267.89  5930.4  270.67
#Mann= 3 ,-1 , 0
  4013.9     .05       0  5016.4     .03       0  5022.4     .05       0
#XS Ineff= 2 , 0
         4617.05  267.79
Permanent Ineff=
       F       F
Bank Sta=4976.6,5063.2
XS Rating Curve= 0 ,0
Exp/Cntr=0.3,0.1

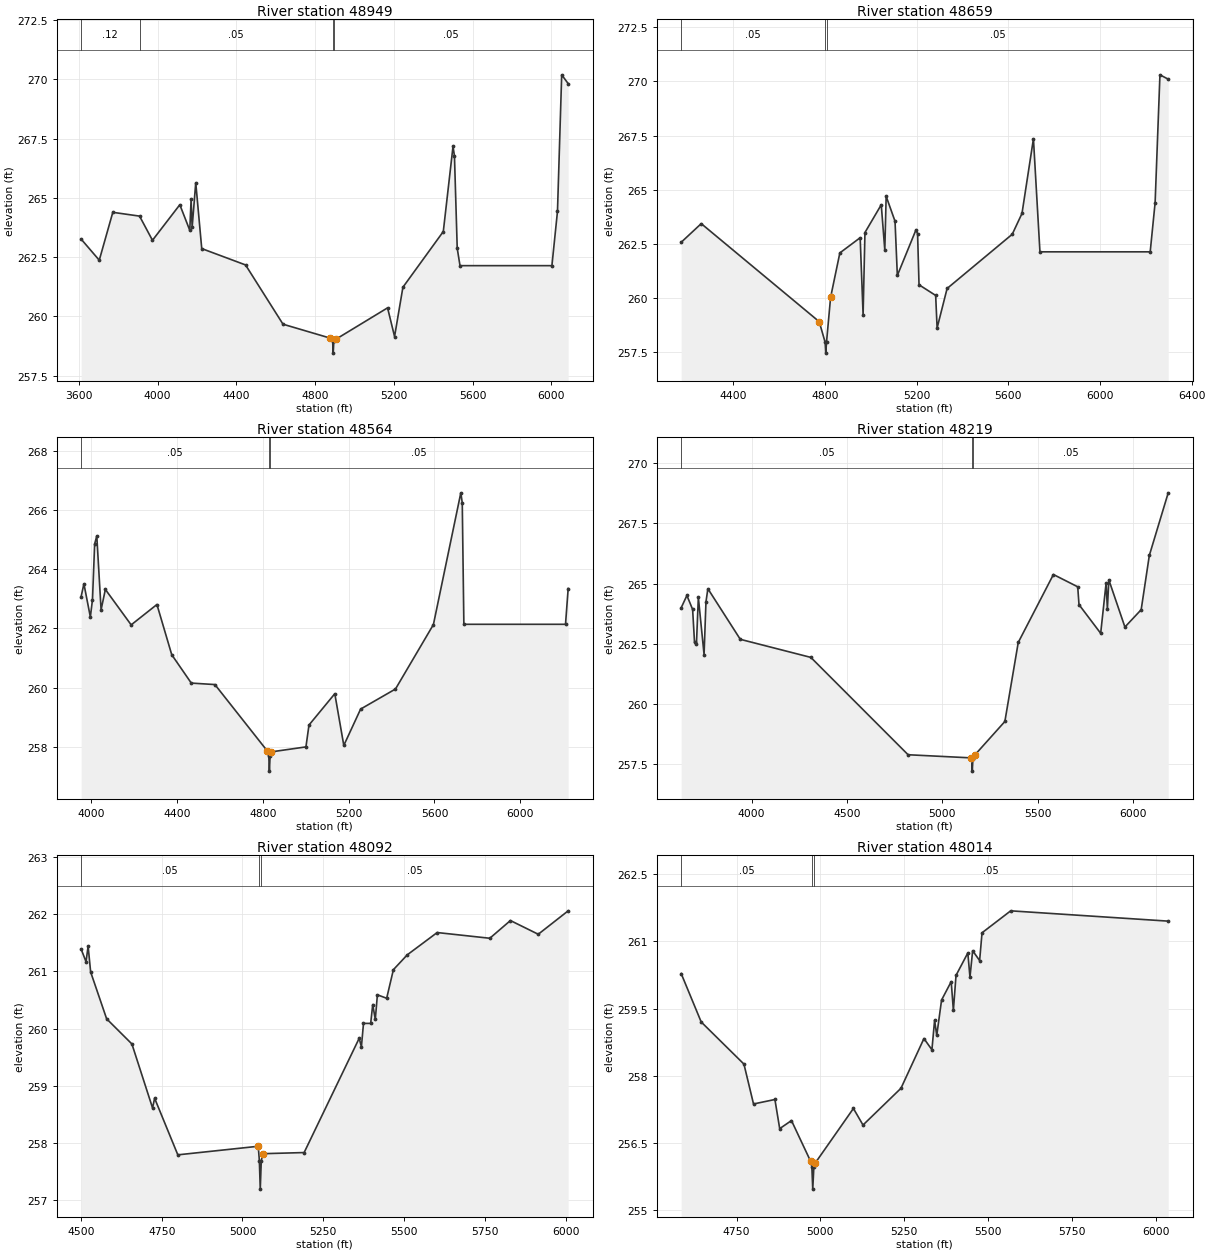
Type RM Length L Ch R = 1 ,48949   ,290,290,290
BEGIN DESCRIPTION:
Mapping XS c5aada6c
END DESCRIPTION:
XS GIS Cut Line= 4
      3699608.45     10576875.68      3699437.23     10575744.28
      3699235.84     10575518.59      3698496.28     10574806.81
#Sta/Elev= 30
  3612.1  263.26  3704.1  262.37  3772.9  264.39  3908.7  264.23  3974.3  263.21
  4113.2  264.71  4163.8  263.63  4170.6  264.96  4175.7  263.75  4194.1  265.64
  4224.5  262.86    4447  262.17  4637.2  259.67  4878.1  259.08  4889.3  258.95
  4892.1  258.45  4895.3  258.95  4906.5  259.04  5168.2  260.36  5203.7  259.15
  5246.1  261.23  5451.2  263.58  5500.5  267.17  5507.8  266.77  5521.9  262.87
    5536  262.14  6002.7  262.14    6031  264.43  6052.4  270.19  6085.3  269.82
#Mann= 4 ,-1 , 0
  3612.1     .12       0  3908.7     .05       0  4889.3     .03       0
  4895.3     .05       0
Bank Sta=4878.1,4906.5
XS Rating Curve= 0 ,0
Exp/Cntr=0.3,0.1

Type RM Length L Ch R = 1 ,48659   ,95,95,95
BEGIN DESCRIPTION:
Mapping XS f9b06d54
END DESCRIPTION:
XS GIS Cut Line= 6
       3699603.9     10576327.58       3699628.2     10575779.01
      3699572.65     10575560.26      3699364.31     10575473.45
      3699069.17     10575247.76      3698527.53     10574751.25
#Sta/Elev= 30
    4173  262.58  4260.5  263.44  4775.2  258.92    4801  257.97  4803.7  257.47
    4807  257.97  4824.8  260.04  4865.2  262.09  4953.8  262.79  4966.6  259.24
  4974.7  263.03  5045.8  264.31  5061.3  262.22  5067.2   264.7  5105.9  263.55
    5116  261.05  5197.5  263.16  5204.3  262.97  5210.6  260.62  5283.2  260.13
  5289.5  258.63  5333.1  260.45  5617.3  262.95  5659.8  263.91  5709.7  267.35
  5738.1  262.14  6219.1  262.14  6240.6  264.41  6261.6   270.3  6297.7   270.1
#Mann= 3 ,-1 , 0
    4173     .05       0    4801     .03       0    4807     .05       0
Bank Sta=4775.2,4824.8
XS Rating Curve= 0 ,0
Exp/Cntr=0.3,0.1

Type RM Length L Ch R = 1 ,48564   ,345,345,345
BEGIN DESCRIPTION:
Mapping XS 62842664
END DESCRIPTION:
XS GIS Cut Line= 4
      3699659.45     10576463.03      3699708.06     10575640.12
      3699645.56     10575487.34       3698688.4     10574634.21
#Sta/Elev= 30
  3952.1  263.08    3965  263.51    3995  262.39    4005  262.97  4015.1  264.86
  4025.1  265.13  4045.1  262.63  4065.1  263.32  4185.4  262.12  4305.6  262.81
  4374.7  261.11  4465.8  260.15    4576   260.1  4819.6  257.86  4827.4  257.67
  4830.1  257.17  4833.4  257.67  4837.1  257.82  5000.6  257.99  5014.8  258.73
  5135.2  259.79  5177.2  258.04  5255.6  259.27  5418.3  259.95  5595.1  262.13
    5723  266.59  5729.7  266.25  5737.2  262.14  6211.3  262.14  6223.7  263.35
#Mann= 3 ,-1 , 0
  3952.1     .05       0  4827.4     .03       0  4833.4     .05       0
Bank Sta=4819.6,4837.1
XS Rating Curve= 0 ,0
Exp/Cntr=0.3,0.1

Type RM Length L Ch R = 1 ,48219   ,127,127,127
BEGIN DESCRIPTION:
UNT 168 IN BOCR 102.0
END DESCRIPTION:
XS GIS Cut Line= 3
      3699849.61     10576560.21      3699849.61     10575210.19
       3699049.6     10574310.17
#Sta/Elev= 30
  3631.2     264  3661.2  264.51  3691.2  263.93  3701.2  262.56  3711.2  262.49
  3721.2  264.43  3751.2  262.06  3761.2  264.25  3771.2  264.79  3941.2  262.69
  4311.2  261.94  4821.2   257.9  5151.4  257.77  5155.1  257.72  5157.8  257.22
  5161.1  257.72  5172.3   257.9  5328.7  259.28  5398.9  262.56  5583.3  265.38
  5710.8  264.87  5717.5  264.13  5831.2  262.94  5859.7  265.03  5866.4  263.95
  5873.9  265.16  5958.3   263.2  6043.6  263.92  6086.3  266.17  6185.4  268.77
#Mann= 3 ,-1 , 0
  3631.2     .05       0  5155.1     .03       0  5161.1     .05       0
Bank Sta=5151.4,5172.3
XS Rating Curve= 0 ,0
Exp/Cntr=0.3,0.1

Type RM Length L Ch R = 1 ,48092   ,78,78,78
BEGIN DESCRIPTION:
Mapping XS 282cb9fb
END DESCRIPTION:
XS GIS Cut Line= 2
      3700246.28     10575494.31       3699287.9     10574331.06
#Sta/Elev= 30
  4500.7  261.39  4515.8  261.17  4522.3  261.44  4530.1  260.99  4579.6  260.17
  4657.8  259.73  4721.7  258.61  4728.1  258.78  4799.9  257.79  5048.8  257.94
  5052.2  257.69    5055  257.19  5058.2  257.69  5063.1  257.81  5190.8  257.83
  5361.2  259.83    5368  259.68  5374.5  260.09  5396.7  260.09  5403.1  260.42
    5411  260.16  5417.5  260.59  5446.2  260.53    5467  261.03    5510  261.29
  5602.5  261.68  5765.4  261.58  5829.2  261.89  5915.3  261.65  6007.9  262.06
#Mann= 3 ,-1 , 0
  4500.7     .05       0  5052.2     .03       0  5058.2     .05       0
Bank Sta=5048.8,5063.1
XS Rating Curve= 0 ,0
Exp/Cntr=0.3,0.1

Type RM Length L Ch R = 1 ,48014   ,238,238,238
BEGIN DESCRIPTION:
Mapping XS ee91a542
END DESCRIPTION:
XS GIS Cut Line= 3
      3700263.61      10575390.1      3699798.34     10574834.56
      3699340.02      10574268.6
#Sta/Elev= 30
  4584.7  260.28  4644.4   259.2  4771.9  258.26  4800.5  257.37  4864.3  257.47
  4878.6  256.82  4913.7     257  4970.9  256.09  4974.5  255.97  4977.2  255.47
  4980.5  255.97  4985.3  256.06  5098.5  257.27  5127.1   256.9  5240.3  257.72
  5308.9  258.83  5332.7  258.58  5340.7  259.24  5347.1   258.9  5361.5  259.69
  5390.2   260.1  5396.7  259.46  5404.6  260.24  5439.8  260.74  5446.2   260.2
  5454.2  260.79    5475  260.57  5482.2  261.19  5567.7  261.68  6037.6  261.45
#Mann= 3 ,-1 , 0
  4584.7     .05       0  4974.5     .03       0  4980.5     .05       0
Bank Sta=4970.9,4985.3
XS Rating Curve= 0 ,0
Exp/Cntr=0.3,0.1

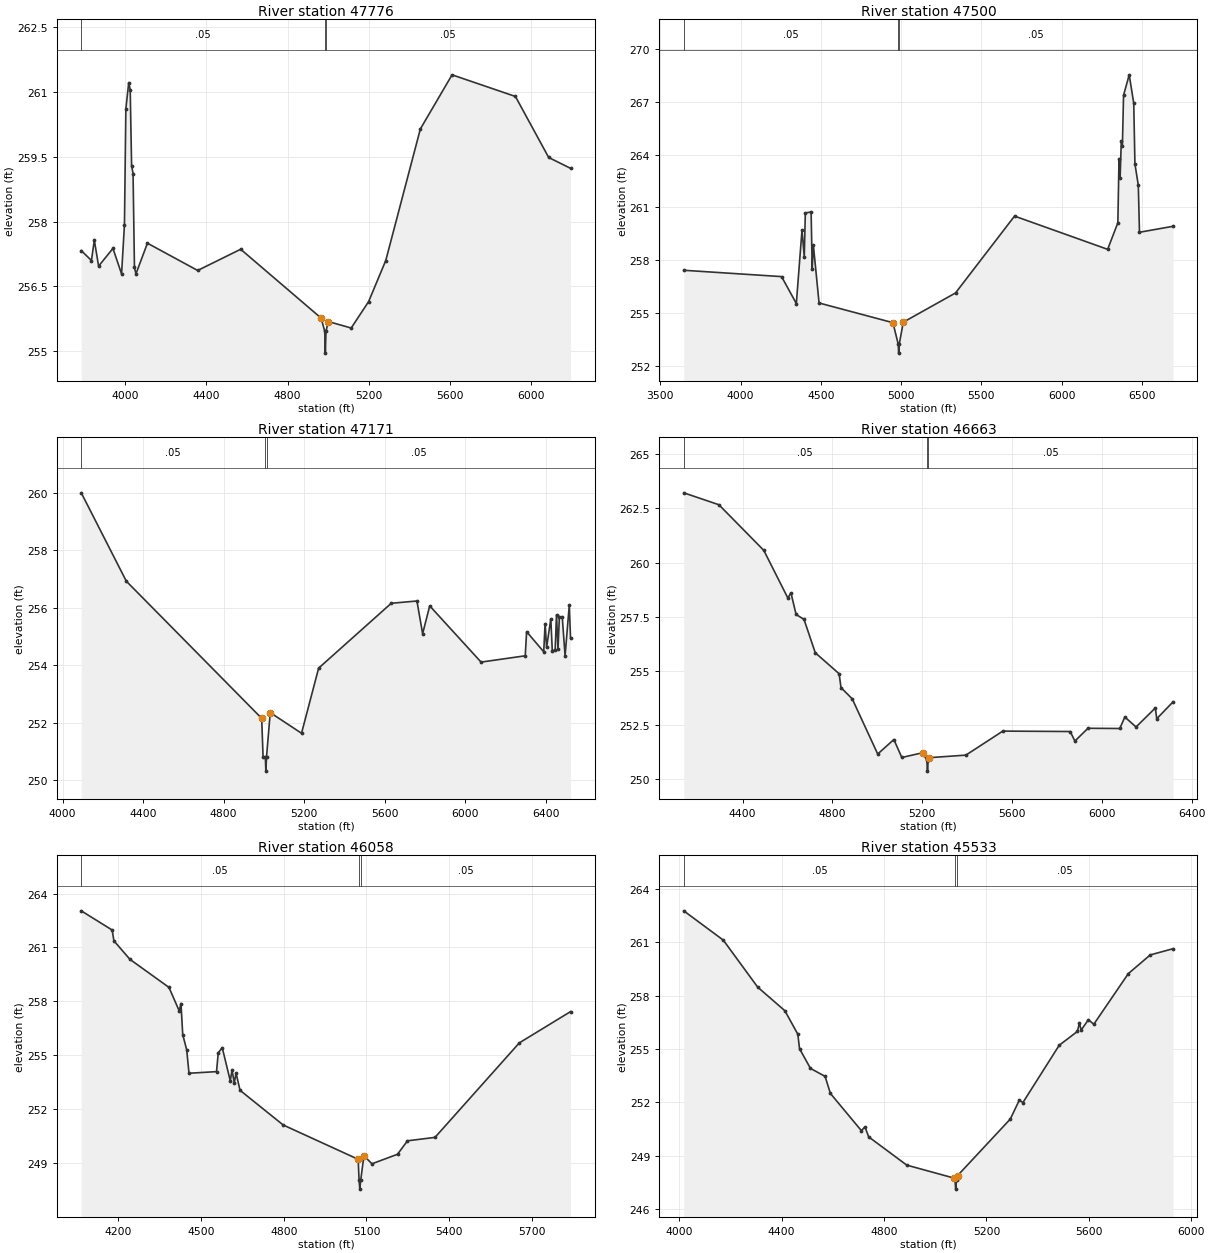
Type RM Length L Ch R = 1 ,47776   ,276,276,276
BEGIN DESCRIPTION:
UNT 168 IN BOCR 101.0
END DESCRIPTION:
XS GIS Cut Line= 3
      3701051.82     10575858.87      3700199.61     10574960.19
      3699447.68     10574060.29
#Sta/Elev= 30
  3783.1  257.33  3833.3   257.1  3847.5  257.57  3868.6  256.97  3939.3  257.38
  3981.8  256.79    3996  257.93  4002.9   260.6    4017  261.21  4024.3  261.05
  4031.2  259.29  4038.4  259.11  4045.3  256.94  4052.6  256.79  4109.2   257.5
  4356.8  256.87  4568.8  257.36  4965.2  255.77  4983.2  255.46    4986  254.96
  4989.2  255.46  5000.4  255.69  5113.4  255.54  5199.2  256.15  5283.8   257.1
  5454.3  260.14  5610.5  261.39  5922.8  260.89  6086.8  259.48  6194.3  259.23
#Mann= 3 ,-1 , 0
  3783.1     .05       0  4983.2     .03       0  4989.2     .05       0
Bank Sta=4965.2,5000.4
XS Rating Curve= 0 ,0
Exp/Cntr=0.3,0.1

Type RM Length L Ch R = 1 ,47500   ,329,329,329
BEGIN DESCRIPTION:
Mapping XS 558c5a0c
END DESCRIPTION:
XS GIS Cut Line= 3
      3701369.53     10575909.58      3700411.19     10574815.81
       3699313.4      10573660.8
#Sta/Elev= 30
  3646.2  257.43  4255.5  257.07  4347.5  255.54  4382.7  259.71  4396.9  258.19
  4403.5  260.69  4439.6  260.74  4446.3  257.51  4453.8  258.84    4489  255.57
  4949.2  254.45  4982.3  253.22    4985  252.72  4988.3  253.22  5013.8  254.48
    5339  256.14  5706.7  260.51  6286.7  258.62  6350.3  260.13  6357.5  263.78
  6364.4  262.69  6371.7  264.76  6378.6  264.51  6385.8  267.38    6421  268.54
  6449.3  266.92  6456.6  263.48  6477.7  262.26  6484.9  259.59  6693.9  259.93
#Mann= 3 ,-1 , 0
  3646.2     .05       0  4982.3     .03       0  4988.3     .05       0
Bank Sta=4949.2,5013.8
XS Rating Curve= 0 ,0
Exp/Cntr=0.3,0.1

Type RM Length L Ch R = 1 ,47171   ,508,508,508
BEGIN DESCRIPTION:
Mapping XS c880056d
END DESCRIPTION:
XS GIS Cut Line= 2
      3701315.69     10575330.56      3699666.49     10573545.08
#Sta/Elev= 30
  4092.7  260.01  4316.6  256.93  4989.1  252.15  4995.9  250.81  5007.1  250.81
  5009.8  250.31  5013.1  250.81  5031.6  252.35    5187  251.63    5272   253.9
  5632.7  256.16  5760.3  256.24  5788.6   255.1  5823.8  256.07  6078.9  254.11
  6298.4  254.33  6305.2  255.17  6390.2  254.47    6397  255.45  6404.4  254.62
  6425.4  255.62  6432.7  254.51  6446.9  254.53  6453.7  255.76  6461.1  254.55
  6467.9  255.69  6482.1  255.69  6496.3  254.33  6517.2   256.1  6523.3  254.96
#Mann= 3 ,-1 , 0
  4092.7     .05       0  5007.1     .03       0  5013.1     .05       0
Bank Sta=4989.1,5031.6
XS Rating Curve= 0 ,0
Exp/Cntr=0.3,0.1

Type RM Length L Ch R = 1 ,46663   ,605,605,605
BEGIN DESCRIPTION:
Mapping XS c7712b39
END DESCRIPTION:
XS GIS Cut Line= 2
      3701680.28     10574848.79      3699937.98     10573540.69
#Sta/Elev= 30
  4138.3  263.22  4294.8  262.67  4494.8  260.56  4601.8  258.36  4615.6   258.6
  4638.5   257.6  4673.9  257.37  4723.9  255.83  4830.2  254.86  4838.5  254.22
  4888.5   253.7    5002  251.15  5073.9  251.82  5109.3  250.99    5202  251.21
  5220.8  250.86  5223.6  250.36  5226.8  250.86  5230.1  250.98  5394.7   251.1
  5559.2  252.21  5859.2  252.19    5880  251.75  5938.3  252.34    6080  252.33
  6102.4  252.86  6152.4   252.4  6238.3  253.28  6244.5  252.78    6317  253.56
#Mann= 3 ,-1 , 0
  4138.3     .05       0  5220.8     .03       0  5226.8     .05       0
Bank Sta=5202,5230.1
XS Rating Curve= 0 ,0
Exp/Cntr=0.3,0.1

Type RM Length L Ch R = 1 ,46058   ,525,525,525
BEGIN DESCRIPTION:
Mapping XS 4a93f3e2
END DESCRIPTION:
XS GIS Cut Line= 2
      3701862.55     10574353.98      3700450.13     10573280.28
#Sta/Elev= 30
  4065.7  263.04  4177.8  261.97  4184.1  261.37  4242.2  260.34  4383.7  258.78
    4421  257.47  4427.3  257.88  4433.7  256.15  4448.1   255.3  4456.4     254
  4556.2  254.09  4562.5  255.14    4577  255.42  4606.1  253.58  4612.4  254.17
  4620.7  253.47    4627  254.01  4641.5  253.05    4798  251.12  5069.9  249.21
  5073.1  248.05  5075.9  247.55  5079.1  248.05  5090.7  249.41  5119.8  248.96
  5212.5  249.49  5248.7  250.24  5348.5  250.43  5654.2  255.69  5839.9  257.43
#Mann= 3 ,-1 , 0
  4065.7     .05       0  5073.1     .03       0  5079.1     .05       0
Bank Sta=5069.9,5090.7
XS Rating Curve= 0 ,0
Exp/Cntr=0.3,0.1

Type RM Length L Ch R = 1 ,45533   ,492,492,492
BEGIN DESCRIPTION:
Mapping XS a178d91d
END DESCRIPTION:
XS GIS Cut Line= 2
      3702057.85     10573989.39      3700613.57     10572740.29
#Sta/Elev= 30
  4018.5  262.77    4173  261.12    4307  258.48  4413.3  257.15  4463.7  255.83
  4470.3  255.02    4513  253.91  4570.1  253.46  4590.9   252.5  4711.6  250.41
  4725.8  250.62  4740.1  250.06  4888.8  248.47  5073.5  247.74  5077.1  247.62
  5079.8  247.12  5083.1  247.62  5087.1  247.88  5292.9  251.06    5328  252.12
  5342.2  251.99  5483.8  255.21    5555  255.99  5562.7  256.47  5569.3  256.06
  5597.8  256.65  5618.7  256.39  5753.6  259.24  5839.1  260.29    5928  260.64
#Mann= 3 ,-1 , 0
  4018.5     .05       0  5077.1     .03       0  5083.1     .05       0
Bank Sta=5073.5,5087.1
XS Rating Curve= 0 ,0
Exp/Cntr=0.3,0.1