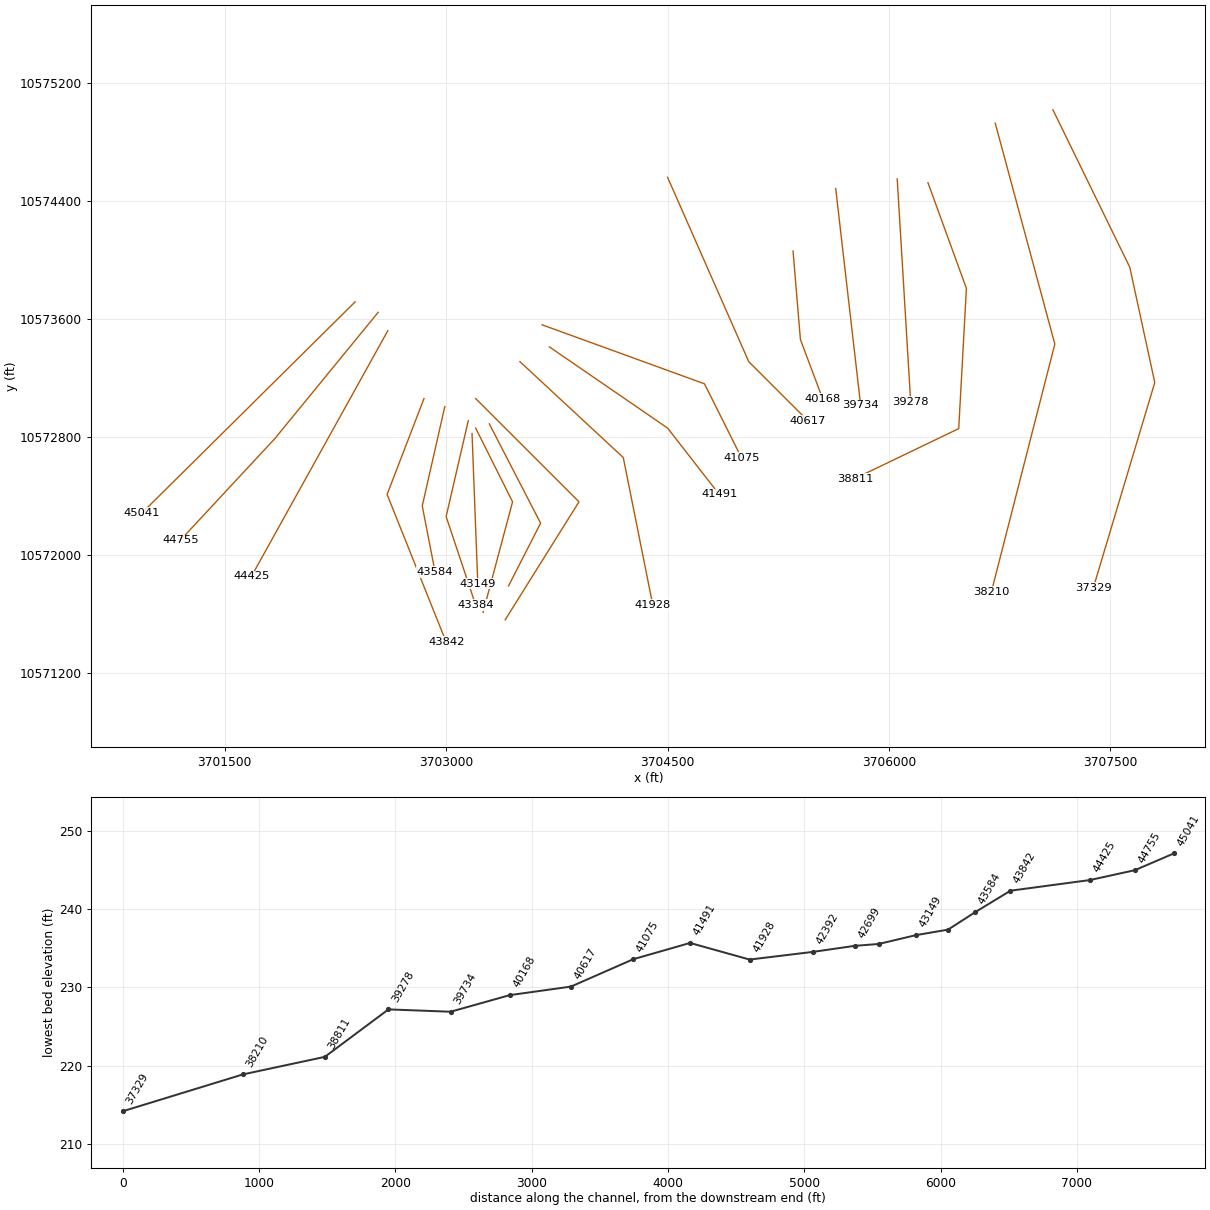
HEC-RAS study UNT 168 IN BOCR.prj: UNT 168 IN BOCR Base Level Engineering

--- UNT 168 IN BOCR.g01 (geometry) --- (continued)

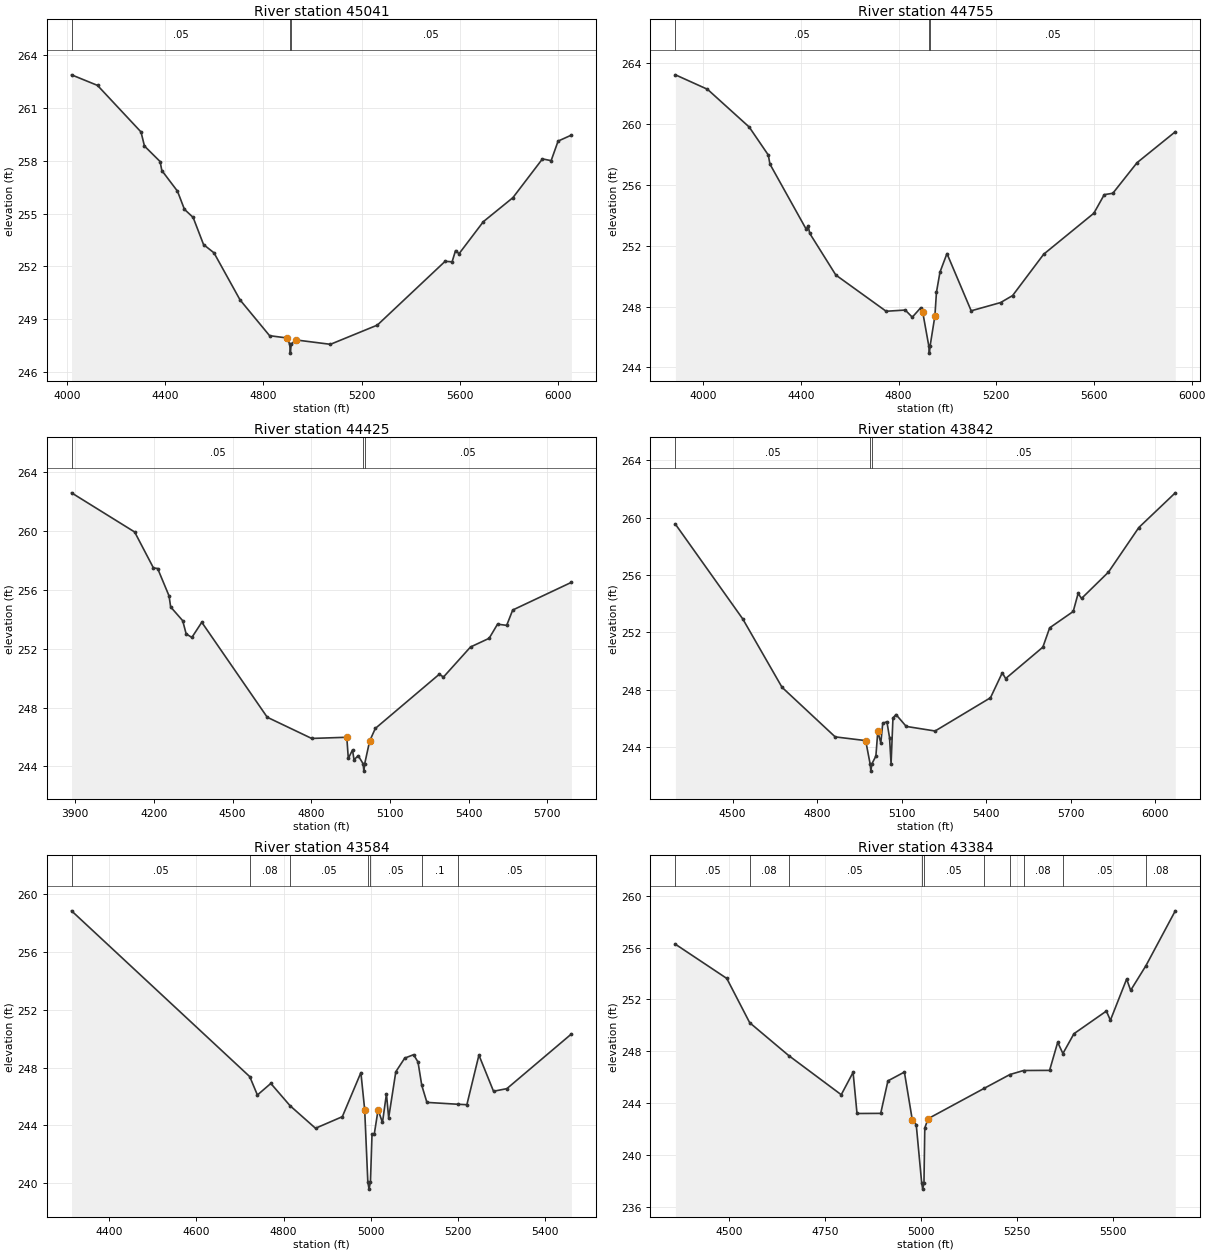
Type RM Length L Ch R = 1 ,45041   ,286,286,286
BEGIN DESCRIPTION:
Mapping XS 444181d0
END DESCRIPTION:
XS GIS Cut Line= 2
       3702383.4     10573715.98      3700938.86     10572284.45
#Sta/Elev= 30
  4019.6  262.87  4125.3  262.27  4302.2  259.63  4316.3  258.83  4379.9  257.95
    4387  257.44  4450.6  256.27  4478.9  255.24  4514.3  254.78  4556.7  253.24
  4599.2  252.77  4705.2   250.1  4825.4  248.07  4896.1  247.94  4907.3  247.58
    4910  247.08  4913.3  247.58  4931.5  247.83  5072.9  247.58  5263.8  248.67
  5539.6  252.29  5567.9  252.26    5582   252.9  5596.2  252.72  5695.2  254.54
  5815.3   255.9  5935.6   258.1  5970.9     258  5999.2  259.11  6053.3  259.45
#Mann= 3 ,-1 , 0
  4019.6     .05       0  4907.3     .03       0  4913.3     .05       0
Bank Sta=4896.1,4931.5
XS Rating Curve= 0 ,0
Exp/Cntr=0.3,0.1

Type RM Length L Ch R = 1 ,44755   ,330,330,330
BEGIN DESCRIPTION:
Mapping XS 6fc5930b
END DESCRIPTION:
XS GIS Cut Line= 3
      3702539.25     10573644.84      3701837.84     10572787.17
      3701198.94     10572099.66
#Sta/Elev= 30
  3886.5  263.22  4017.7  262.27  4188.6  259.79  4266.8  257.95  4273.3  257.36
  4422.2  253.07  4429.8  253.31  4436.2  252.81  4543.2  250.07  4749.2  247.69
  4827.4  247.77  4856.2   247.3  4891.3  247.93  4899.2  247.61  4923.5  245.44
  4926.3  244.94  4929.5  245.44  4948.8  247.38  4955.2  248.94  4969.6  250.26
  4998.2  251.48  5097.4  247.72  5217.6  248.26  5266.9  248.72  5394.4  251.44
  5599.7  254.13  5642.2  255.35  5677.3  255.44  5776.5  257.45    5933  259.48
#Mann= 3 ,-1 , 0
  3886.5     .05       0  4923.5     .03       0  4929.5     .05       0
Bank Sta=4899.2,4948.8
XS Rating Curve= 0 ,0
Exp/Cntr=0.3,0.1

Type RM Length L Ch R = 1 ,44425   ,583,583,583
BEGIN DESCRIPTION:
Mapping XS 70800f8c
END DESCRIPTION:
XS GIS Cut Line= 2
       3702604.7     10573520.61      3701680.56     10571854.55
#Sta/Elev= 30
  3886.2  262.58  4126.8  259.92  4198.4  257.48  4214.4  257.44  4257.9  255.58
    4264  254.83  4309.8   253.9  4323.1     253  4344.9  252.76  4382.6  253.79
  4632.1  247.34  4801.5   245.9  4935.4  245.98  4941.1  244.54  4957.2  245.12
  4962.9  244.45  4978.9  244.73  4997.6  244.18  5000.4  243.68  5003.6  244.18
  5022.4  245.72  5044.1  246.58  5287.9  250.26  5303.9  250.07  5406.9  252.11
  5477.9   252.7  5509.9  253.66  5544.8  253.58  5567.7  254.62  5791.4   256.5
#Mann= 3 ,-1 , 0
  3886.2     .05       0  4997.6     .03       0  5003.6     .05       0
Bank Sta=4935.4,5022.4
XS Rating Curve= 0 ,0
Exp/Cntr=0.3,0.1

Type RM Length L Ch R = 1 ,43842   ,258,258,258
BEGIN DESCRIPTION:
UNT 168 IN BOCR 93.0
END DESCRIPTION:
XS GIS Cut Line= 3
      3702849.61      10573060.2      3702599.61     10572410.19
      3702999.62     10571410.15
#Sta/Elev= 30
    4297  259.55  4535.9  252.94  4675.2  248.17  4863.8  244.71    4972  244.45
  4987.8  242.82  4990.5  242.32  4993.8  242.82  5008.2  243.37    5015  245.09
  5025.7  244.29  5032.5  245.65  5047.3  245.77  5056.7  244.65  5062.1  242.83
  5068.8  246.03  5079.6  246.27  5115.9  245.44  5218.3  245.12  5414.8  247.44
  5456.6  249.18  5468.7  248.78  5600.6  250.97  5624.8  252.32  5708.3  253.46
  5725.8  254.72  5737.9  254.37  5833.5  256.21  5941.2  259.32  6070.5  261.74
#Mann= 3 ,-1 , 0
    4297     .05       0  4987.8     .04       0  4993.8     .05       0
Bank Sta=4972,5015
XS Rating Curve= 0 ,0
Exp/Cntr=0.3,0.1

Type RM Length L Ch R = 1 ,43584   ,200,200,200
BEGIN DESCRIPTION:
Mapping XS 94a7c315
END DESCRIPTION:
XS GIS Cut Line= 3
      3702990.62     10573005.92      3702837.84     10572332.31
      3702924.55     10571884.85
#Sta/Elev= 30
  4313.8  258.84  4722.6  247.37  4740.1   246.1  4770.9   246.9    4815  245.36
  4873.4   243.8  4934.9   244.6  4977.5  247.65  4986.2  245.08  4993.4  240.09
  4996.2  239.59  4999.4  240.09    5003  243.38  5008.1  243.38  5016.9  245.07
    5027   244.2  5036.1  246.18  5041.2  244.52  5057.6  247.71    5078  248.65
  5098.4  248.89  5108.5  248.38  5117.1  246.77  5128.9  245.59  5200.1  245.46
  5220.6  245.43  5248.2  248.86  5281.7  246.36  5312.3  246.54  5460.3  250.32
#Mann= 7 ,-1 , 0
  4313.8     .05       0  4722.6     .08       0    4815     .05       0
  4993.4     .04       0  4999.4     .05       0  5117.1      .1       0
  5200.1     .05       0
Bank Sta=4986.2,5016.9
XS Rating Curve= 0 ,0
Exp/Cntr=0.3,0.1

Type RM Length L Ch R = 1 ,43384   ,235,235,235
BEGIN DESCRIPTION:
UNT 168 IN BOCR 92.0
END DESCRIPTION:
XS GIS Cut Line= 3
      3703149.62     10572910.23      3702999.61     10572260.19
      3703199.61     10571660.18
#Sta/Elev= 30
  4361.4  256.26  4494.9  253.62  4554.5   250.2  4656.1  247.66  4792.5  244.64
  4823.3  246.37  4833.5  243.19  4895.1   243.2  4913.9  245.71  4956.7  246.39
  4977.2   242.7  4987.5  242.32  5001.6  237.85  5004.3  237.35  5007.6  237.85
  5009.7  242.07  5018.3  242.79  5164.6  245.14  5231.1   246.2  5266.7  246.51
  5334.2  246.52  5355.3  248.69  5368.8  247.82  5397.5  249.35  5481.8   251.1
  5492.3  250.39  5534.5  253.57    5545   252.7  5584.8  254.61    5661  258.84
#Mann= 10 ,-1 , 0
  4361.4     .05       0  4554.5     .08       0  4656.1     .05       0
  5001.6     .03       0  5007.6     .05       0  5164.6     .08       0
  5231.1     .05       0  5266.7     .08       0  5368.8     .05       0
  5584.8     .08       0
Bank Sta=4977.2,5018.3
XS Rating Curve= 0 ,0
Exp/Cntr=0.3,0.1

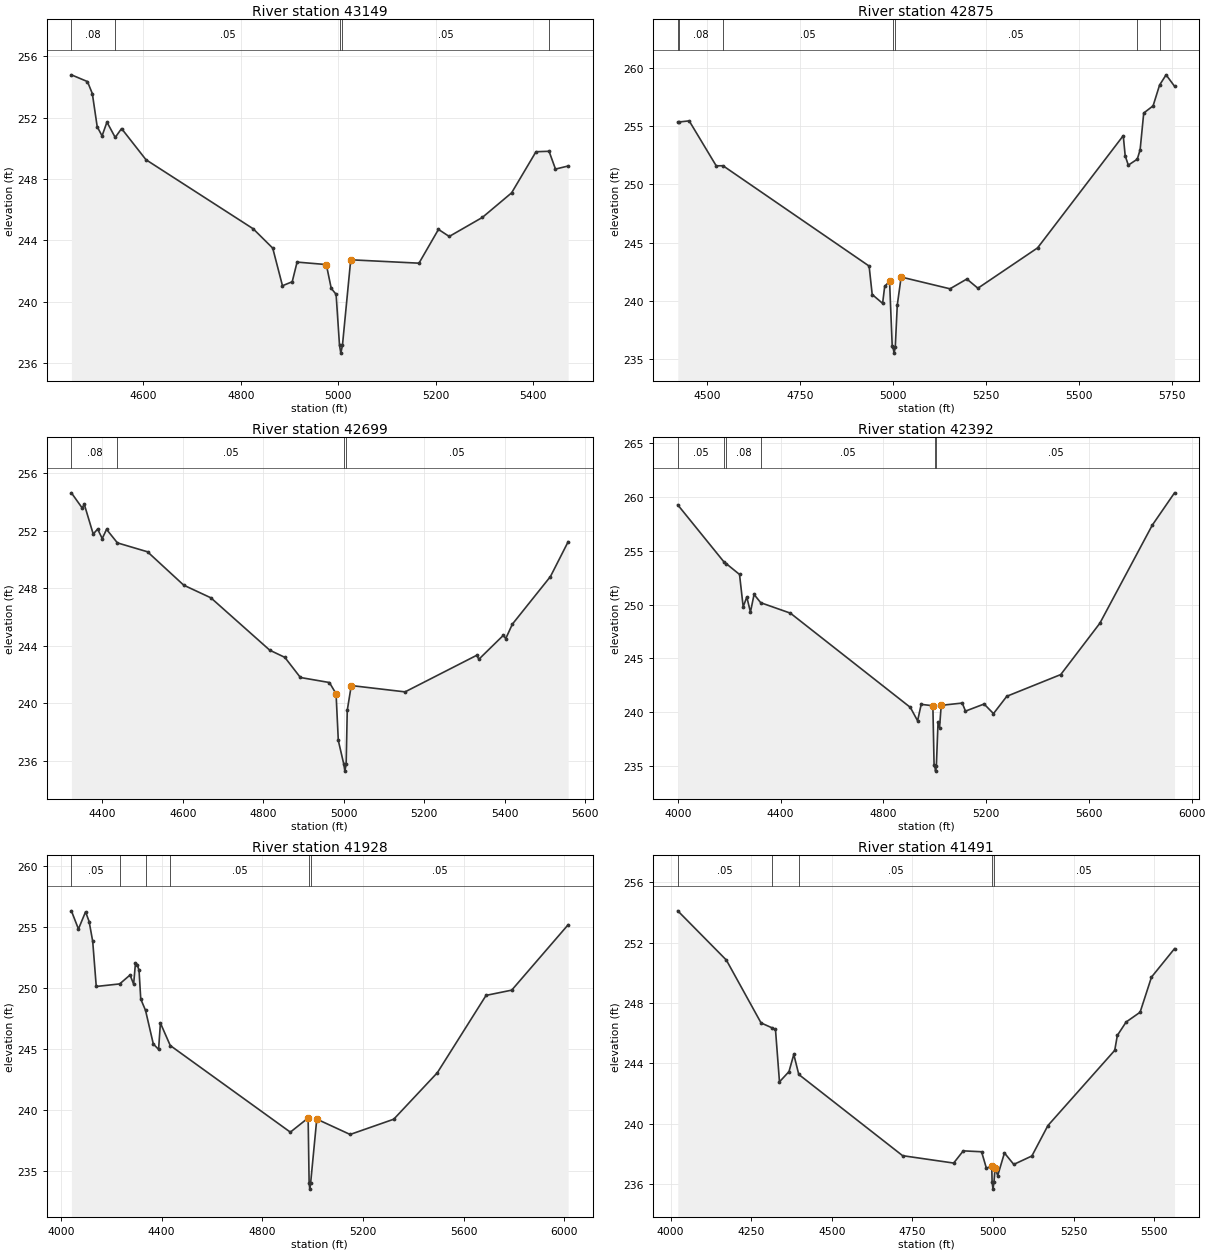
Type RM Length L Ch R = 1 ,43149   ,274,274,274
BEGIN DESCRIPTION:
Mapping XS efcc3b55
END DESCRIPTION:
XS GIS Cut Line= 2
      3703175.04     10572823.15      3703214.06      10571804.2
#Sta/Elev= 30
  4452.2  254.78  4485.2  254.34  4495.2  253.56  4505.2   251.4  4515.2   250.8
  4525.2   251.7  4542.2   250.7  4555.2  251.28  4605.3  249.25  4825.4  244.75
  4865.5  243.49  4885.5  241.04  4905.5   241.3  4915.5  242.58  4975.5  242.42
  4985.6  240.87  4995.6  240.48  5002.6  237.15  5005.3  236.65  5008.6  237.15
  5025.6  242.73  5165.7  242.51  5205.7  244.71  5227.8  244.25  5295.8  245.49
  5355.8  247.09  5405.9  249.77  5432.7   249.8  5445.9  248.64  5471.9  248.84
#Mann= 5 ,-1 , 0
  4452.2     .08       0  4542.2     .05       0  5002.6     .03       0
  5008.6     .05       0  5432.7     .08       0
Bank Sta=4975.5,5025.6
XS Rating Curve= 0 ,0
Exp/Cntr=0.3,0.1

Type RM Length L Ch R = 1 ,42875   ,176,176,176
BEGIN DESCRIPTION:
UNT 168 IN BOCR 91.0
END DESCRIPTION:
XS GIS Cut Line= 3
      3703199.63     10572860.15      3703449.61     10572360.19
      3703249.61     10571610.18
#Sta/Elev= 30
  4420.9  255.35  4423.4  255.35  4451.6  255.45  4524.3  251.59  4542.5   251.6
  4935.2  242.99  4943.5  240.55  4971.5  239.79  4977.1  241.25  4990.2  241.69
  4997.3  236.13  4999.5  236.02  5002.3  235.52  5005.5  236.02  5010.9  239.64
  5021.3  242.05  5152.6  241.04  5197.9  241.88  5227.6  241.09    5388  244.55
  5618.3  254.18  5623.5  252.45  5631.9  251.65  5655.9  252.16  5663.6  252.96
  5673.3  256.12  5698.5  256.74  5715.9  258.52  5733.4   259.4  5756.1  258.42
#Mann= 7 ,-1 , 0
  4420.9     .05       0  4423.4     .08       0  4542.5     .05       0
  4999.5     .03       0  5005.5     .05       0  5655.9     .08       0
  5715.9     .05       0
Bank Sta=4990.2,5021.3
XS Rating Curve= 0 ,0
Exp/Cntr=0.3,0.1

Type RM Length L Ch R = 1 ,42699   ,307,307,307
BEGIN DESCRIPTION:
Mapping XS 0398fd15
END DESCRIPTION:
XS GIS Cut Line= 3
       3703292.2     10572888.31      3703639.45     10572215.53
      3703422.45      10571790.2
#Sta/Elev= 30
  4323.3  254.63  4349.8  253.59  4355.5  253.82  4377.6  251.76  4388.5  252.11
    4400  251.45  4410.7  252.09  4437.7  251.15  4512.5  250.53  4602.5  248.21
    4670  247.33  4816.3  243.69  4853.8  243.19  4892.5  241.79  4964.6  241.44
  4981.1  240.66  4986.7  237.41  5000.2  235.78    5003  235.28  5006.2  235.78
  5008.9   239.5  5018.9  241.23  5152.6  240.79  5330.4  243.33  5336.1  243.06
  5397.1  244.73  5402.7  244.49  5419.3   245.5  5513.9  248.81  5557.9  251.23
#Mann= 4 ,-1 , 0
  4323.3     .08       0  4437.7     .05       0  5000.2     .03       0
  5006.2     .05       0
Bank Sta=4981.1,5018.9
XS Rating Curve= 0 ,0
Exp/Cntr=0.3,0.1

Type RM Length L Ch R = 1 ,42392   ,464,464,464
BEGIN DESCRIPTION:
UNT 168 IN BOCR 90.0
END DESCRIPTION:
XS GIS Cut Line= 3
       3703199.6      10573060.2      3703899.61     10572360.19
      3703399.59     10571560.15
#Sta/Elev= 30
    4000  259.27    4180  253.96  4188.3  253.81  4240.4   252.8  4254.6  249.79
  4268.7   250.7  4282.9   249.3    4297  250.94    4323  250.17  4438.4   249.2
  4905.1  240.44  4933.4  239.19  4947.5  240.72  4992.9  240.59  4997.6  235.05
  5000.5  235.01  5003.3  234.51  5006.5  235.01    5013  239.05  5018.9  238.55
  5025.3  240.63  5107.3  240.84  5119.7  240.09  5192.2  240.75  5228.8  239.86
  5280.6  241.47  5490.6  243.49  5642.7  248.26  5846.7  257.38  5933.4  260.39
#Mann= 6 ,-1 , 0
    4000     .05       0    4180      .1       0  4188.3     .08       0
    4323     .05       0  5000.5     .03       0  5006.5     .05       0
Bank Sta=4992.9,5025.3
XS Rating Curve= 0 ,0
Exp/Cntr=0.3,0.1

Type RM Length L Ch R = 1 ,41928   ,437,437,437
BEGIN DESCRIPTION:
UNT 168 IN BOCR 89.0
END DESCRIPTION:
XS GIS Cut Line= 3
      3703499.62     10573310.18      3704199.61     10572660.19
       3704399.6     10571660.23
#Sta/Elev= 30
    4041  256.34  4069.1  254.85  4097.4  256.26  4111.6  255.46  4125.8  253.84
  4139.9  250.14    4233  250.35  4274.3  251.08  4288.5  250.33  4295.8  252.06
  4302.6  251.94    4310  251.46  4316.8  249.11  4335.8  248.18  4366.7  245.43
  4387.7  244.98    4395  247.14  4434.1   245.3  4911.5   238.2  4982.3  239.36
  4986.2  234.03  4988.9  233.53  4992.2  234.03  5016.6  239.27  5149.2  238.01
  5322.6  239.26  5495.9  243.07  5689.7  249.41  5791.7  249.84    6016   255.2
#Mann= 6 ,-1 , 0
    4041     .05       0    4233      .1       0  4335.8     .08       0
  4434.1     .05       0  4986.2     .03       0  4992.2     .05       0
Bank Sta=4982.3,5016.6
XS Rating Curve= 0 ,0
Exp/Cntr=0.3,0.1

Type RM Length L Ch R = 1 ,41491   ,416,416,416
BEGIN DESCRIPTION:
UNT 168 IN BOCR 88.0
END DESCRIPTION:
XS GIS Cut Line= 3
      3703699.63     10573410.18      3704499.61     10572860.19
      3704849.61     10572410.18
#Sta/Elev= 30
    4022  254.12  4172.8  250.85  4280.4  246.68  4313.9  246.36  4325.1  246.25
  4337.5  242.77    4367  243.45  4381.9  244.59  4397.4  243.26  4719.5  237.87
  4877.8  237.38  4907.6  238.19  4964.4  238.13  4979.3  237.04    4996  237.17
    4997  236.15  4999.8  235.65    5003  236.15  5006.4  237.05  5014.5  236.55
  5035.3  238.05  5064.3  237.29  5120.4  237.85  5170.2  239.87  5377.4  244.86
  5385.5  245.85  5412.7  246.74  5456.1  247.39  5491.4  249.72  5562.9  251.61
#Mann= 5 ,-1 , 0
    4022     .05       0  4313.9     .08       0  4397.4     .05       0
    4997     .03       0    5003     .05       0
Bank Sta=4996,5006.4
XS Rating Curve= 0 ,0
Exp/Cntr=0.3,0.1

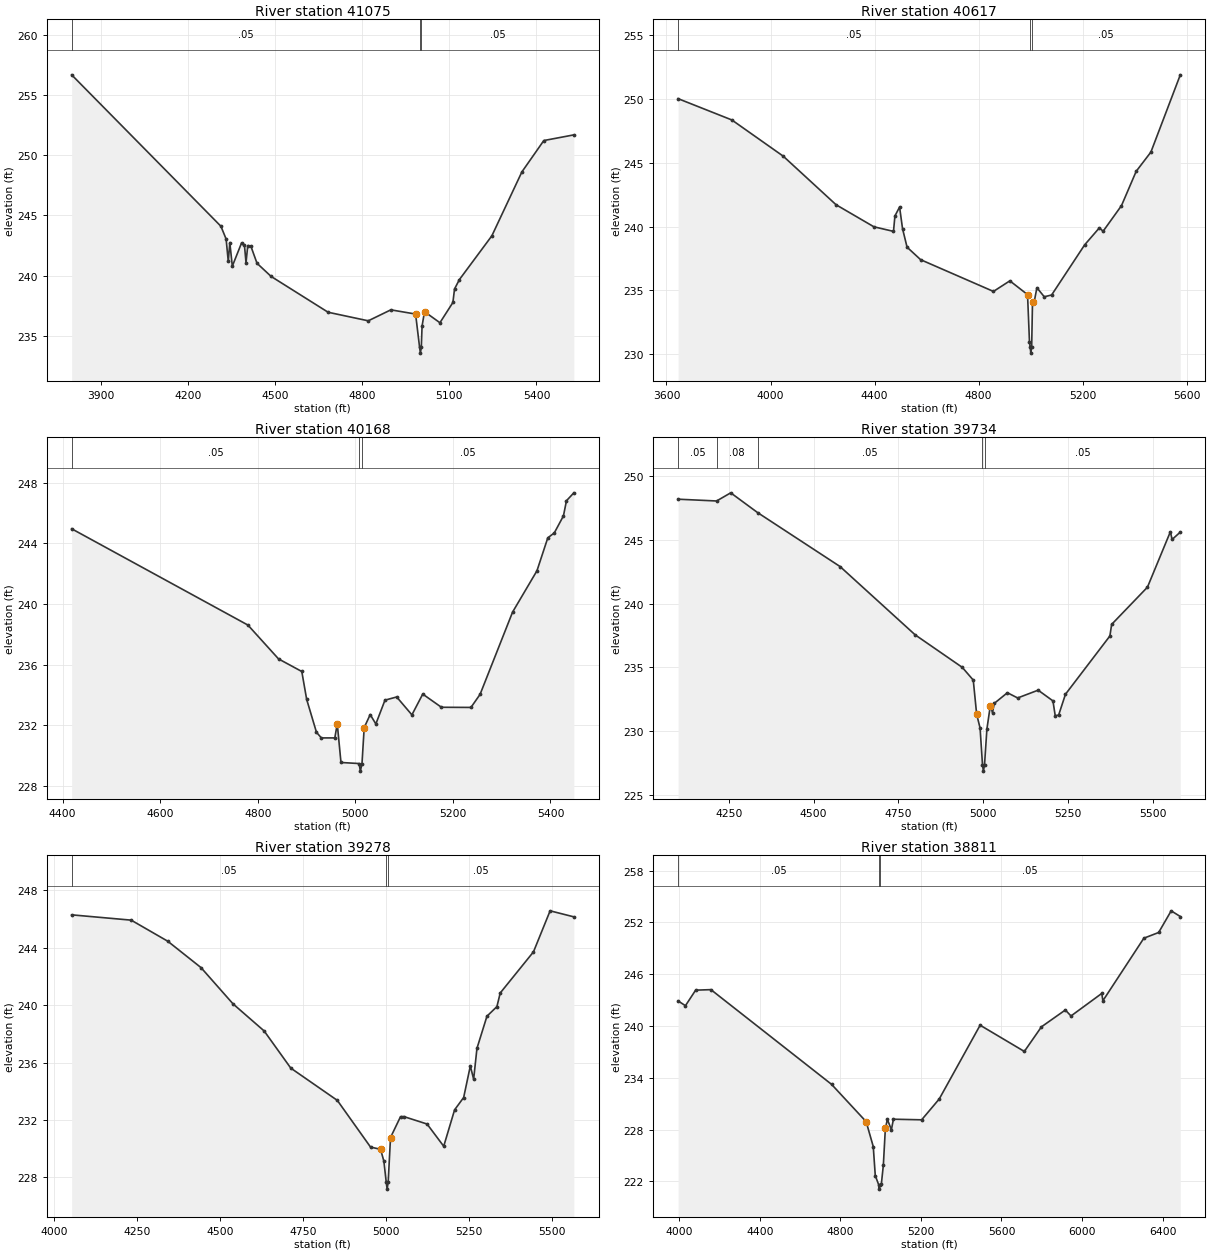
Type RM Length L Ch R = 1 ,41075   ,458,458,458
BEGIN DESCRIPTION:
UNT 168 IN BOCR 87.0
END DESCRIPTION:
XS GIS Cut Line= 3
       3703649.6     10573560.19      3704749.61     10573160.19
      3704999.61     10572660.18
#Sta/Elev= 30
  3799.3  256.66  4313.4   244.1  4331.3  243.04  4338.7  241.18    4344  242.75
  4352.6  240.79  4384.5  242.72  4394.5  242.51  4399.8  241.08  4405.8   242.5
  4416.5  242.45  4437.7  241.03  4486.3  239.94  4682.5  236.97  4820.8  236.26
  4898.6  237.17  4983.8  236.82  4997.5  234.08  5000.3  233.58  5003.5  234.08
  5006.1  235.82  5014.5  237.02  5067.6   236.1  5112.3  237.78  5117.9   238.9
  5134.7  239.68  5246.5  243.31  5349.9  248.61  5425.4  251.21  5528.8  251.68
#Mann= 3 ,-1 , 0
  3799.3     .05       0  4997.5     .03       0  5003.5     .05       0
Bank Sta=4983.8,5014.5
XS Rating Curve= 0 ,0
Exp/Cntr=0.3,0.1

Type RM Length L Ch R = 1 ,40617   ,449,449,449
BEGIN DESCRIPTION:
UNT 168 IN BOCR 86.0
END DESCRIPTION:
XS GIS Cut Line= 3
       3704499.6      10574560.2      3705049.61     10573310.19
      3705449.58     10572910.22
#Sta/Elev= 30
  3644.7  250.04  3851.3  248.37  4048.9  245.53  4252.1  241.72  4397.6  239.99
    4473  239.63  4478.5  240.84  4496.4  241.54  4507.8  239.84  4525.2  238.39
  4577.3  237.41  4857.4  234.92  4920.5  235.75  4988.5  234.67    4996  230.94
  4998.4  230.58  5001.2  230.08  5004.4  230.58  5007.6  234.08  5013.9  234.08
  5024.5  235.21  5052.8   234.5  5081.1  234.64  5208.4  238.58  5264.9  239.91
  5279.1  239.64  5349.8  241.65  5406.3  244.34  5462.9  245.85    5576  251.91
#Mann= 3 ,-1 , 0
  3644.7     .05       0  4998.4     .03       0  5004.4     .05       0
Bank Sta=4988.5,5007.6
XS Rating Curve= 0 ,0
Exp/Cntr=0.3,0.1

Type RM Length L Ch R = 1 ,40168   ,434,434,434
BEGIN DESCRIPTION:
UNT 168 IN BOCR 85.0
END DESCRIPTION:
XS GIS Cut Line= 3
      3705349.61     10574060.23      3705399.61     10573460.19
       3705549.6     10573060.21
#Sta/Elev= 30
  4418.6  244.97  4779.9  238.62  4842.6  236.39  4890.3  235.56  4900.3  233.72
  4920.4  231.55  4930.4  231.18    4958  231.18    4963  232.11  4970.6  229.56
  5007.7  229.49  5010.4  228.99  5013.7  229.49  5018.2  231.86  5030.5  232.72
  5042.1   232.1  5060.8  233.67  5084.8  233.88    5116   232.7  5138.2  234.07
  5176.5   233.2    5237  233.19  5255.7  234.05  5322.4  239.48  5372.3   242.2
  5394.5  244.37  5407.9   244.7  5426.6  245.82  5432.8  246.82  5447.9  247.34
#Mann= 3 ,-1 , 0
  4418.6     .05       0  5007.7     .03       0  5013.7     .05       0
Bank Sta=4963,5018.2
XS Rating Curve= 0 ,0
Exp/Cntr=0.3,0.1

Type RM Length L Ch R = 1 ,39734   ,456,456,456
BEGIN DESCRIPTION:
Mapping XS 737cb825
END DESCRIPTION:
XS GIS Cut Line= 2
      3705638.58     10574484.15       3705807.7     10573014.05
#Sta/Elev= 30
    4101   248.2  4214.4  248.06    4256   248.7  4335.2  247.15  4578.1  242.92
  4799.5  237.56  4938.3  235.01  4970.7  234.01  4980.7  231.33  4990.8  230.25
  4997.9  227.37  5000.6  226.87  5003.9  227.37  5010.9  230.17    5021  232.01
  5027.4  231.45  5032.4  232.18  5071.3  233.02  5101.5  232.61  5161.9  233.22
  5205.5  232.38  5212.2  231.22  5222.3  231.27  5242.4   232.9  5373.3  237.47
  5378.5  238.38    5484   241.3  5551.6  245.65  5556.6  245.04  5580.8  245.62
#Mann= 5 ,-1 , 0
    4101     .05       0  4214.4     .08       0  4335.2     .05       0
  4997.9     .03       0  5003.9     .05       0
Bank Sta=4980.7,5021
XS Rating Curve= 0 ,0
Exp/Cntr=0.3,0.1

Type RM Length L Ch R = 1 ,39278   ,467,467,467
BEGIN DESCRIPTION:
Mapping XS 26958aac
END DESCRIPTION:
XS GIS Cut Line= 2
      3706055.24     10574549.28      3706146.39     10573038.82
#Sta/Elev= 30
    4053   246.3  4232.4  245.93  4342.6  244.46  4442.8  242.62  4539.3  240.09
  4633.1   238.2  4713.3  235.61  4853.5  233.36  4953.7   230.1  4983.8  229.95
  4993.8  229.12  5000.8  227.67  5003.6  227.17  5006.8  227.67  5013.8  230.77
  5043.9  232.22  5053.9  232.23    5124  231.71  5174.1  230.16  5206.9   232.7
  5234.2  233.56  5254.3  235.76  5264.3  234.84  5274.3  236.99  5304.4  239.23
  5334.4   239.9  5344.4  240.85  5444.6  243.72  5494.7  246.58  5566.2  246.16
#Mann= 3 ,-1 , 0
    4053     .05       0  5000.8     .03       0  5006.8     .05       0
Bank Sta=4983.8,5013.8
XS Rating Curve= 0 ,0
Exp/Cntr=0.3,0.1

Type RM Length L Ch R = 1 ,38811   ,601,601,601
BEGIN DESCRIPTION:
Mapping XS cbf9c9f4
END DESCRIPTION:
XS GIS Cut Line= 4
      3706263.56     10574523.28      3706523.99     10573807.09
      3706471.91     10572856.57      3705768.78     10572518.03
#Sta/Elev= 30
  3993.9  242.91  4030.3  242.36  4080.9  244.16  4156.8  244.22    4756  233.25
  4927.8  228.93  4963.2  226.04  4973.2  222.68  4990.2  221.61    4993  221.11
  4996.2  221.61  5003.2  221.65  5013.3  223.89  5023.3  228.14  5033.3  229.19
  5053.3  227.99  5063.3  229.21  5203.5  229.14  5290.8  231.55    5494   240.1
  5713.6  237.06  5798.5  239.91  5917.2  241.86  5945.4  241.17  6098.2  243.78
  6103.7  242.93  6307.3  250.18  6380.8  250.84    6443  253.35  6488.3  252.69
#Mann= 3 ,-1 , 0
  3993.9     .05       0  4990.2     .03       0  4996.2     .05       0
Bank Sta=4927.8,5023.3
XS Rating Curve= 0 ,0
Exp/Cntr=0.3,0.1

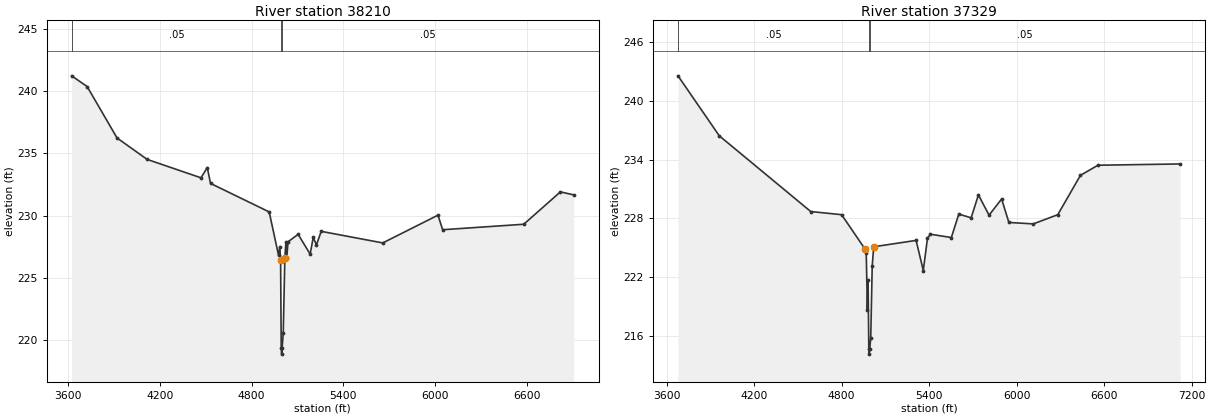
Type RM Length L Ch R = 1 ,38210   ,881,881,881
BEGIN DESCRIPTION:
UNT 168 IN BOCR 80.0
END DESCRIPTION:
XS GIS Cut Line= 3
       3706719.3     10574926.91      3707122.95     10573429.49
      3706693.25     10571749.75
#Sta/Elev= 30
  3622.2  241.22  3723.5  240.36  3919.2  236.23  4115.9  234.51  4468.1  233.03
  4509.5  233.85  4530.8  232.58  4914.6  230.29  4975.6  226.81    4984  227.51
  4989.2   226.4  4993.3  219.37    4996  218.87  4999.3  219.37  5006.6  220.58
    5017  226.57    5024  227.89  5029.2  226.57  5037.7  227.89  5103.8  228.49
  5182.7   226.9  5202.4  228.24    5224  227.65  5254.9  228.73  5657.5   227.8
  6018.8  230.03  6049.3  228.86    6580   229.3  6819.7   231.9  6906.9  231.66
#Mann= 3 ,-1 , 0
  3622.2     .05       0  4993.3     .03       0  4999.3     .05       0
Bank Sta=4989.2,5017
XS Rating Curve= 0 ,0
Exp/Cntr=0.3,0.1

Type RM Length L Ch R = 1 ,37329   ,887,887,887
BEGIN DESCRIPTION:
UNT 168 IN BOCR 79.0
END DESCRIPTION:
XS GIS Cut Line= 4
      3707109.92     10575018.04      3707630.76     10573950.32
      3707800.03     10573169.07      3707383.35      10571775.8
#Sta/Elev= 30
  3678.8  242.53  3961.7  236.42  4588.8   228.7  4800.2  228.38    4959  224.92
  4969.2  224.49  4976.9  218.67    4982  221.69  4986.7  214.67  4989.5  214.17
  4992.7  214.67  4999.9   215.8  5010.2   223.2  5020.4  225.11    5311  225.76
  5360.2  222.69  5388.8  225.97  5409.4  226.39  5552.5  226.05  5603.6  228.44
  5688.1  228.06  5738.1  230.39  5811.1  228.33  5897.2  229.98  5946.8  227.59
  6113.8  227.44  6282.2  228.38  6437.4  232.39  6557.5  233.42  7120.4  233.55
#Mann= 3 ,-1 , 0
  3678.8     .05       0  4986.7     .03       0  4992.7     .05       0
Bank Sta=4959,5020.4
XS Rating Curve= 0 ,0
Exp/Cntr=0.3,0.1