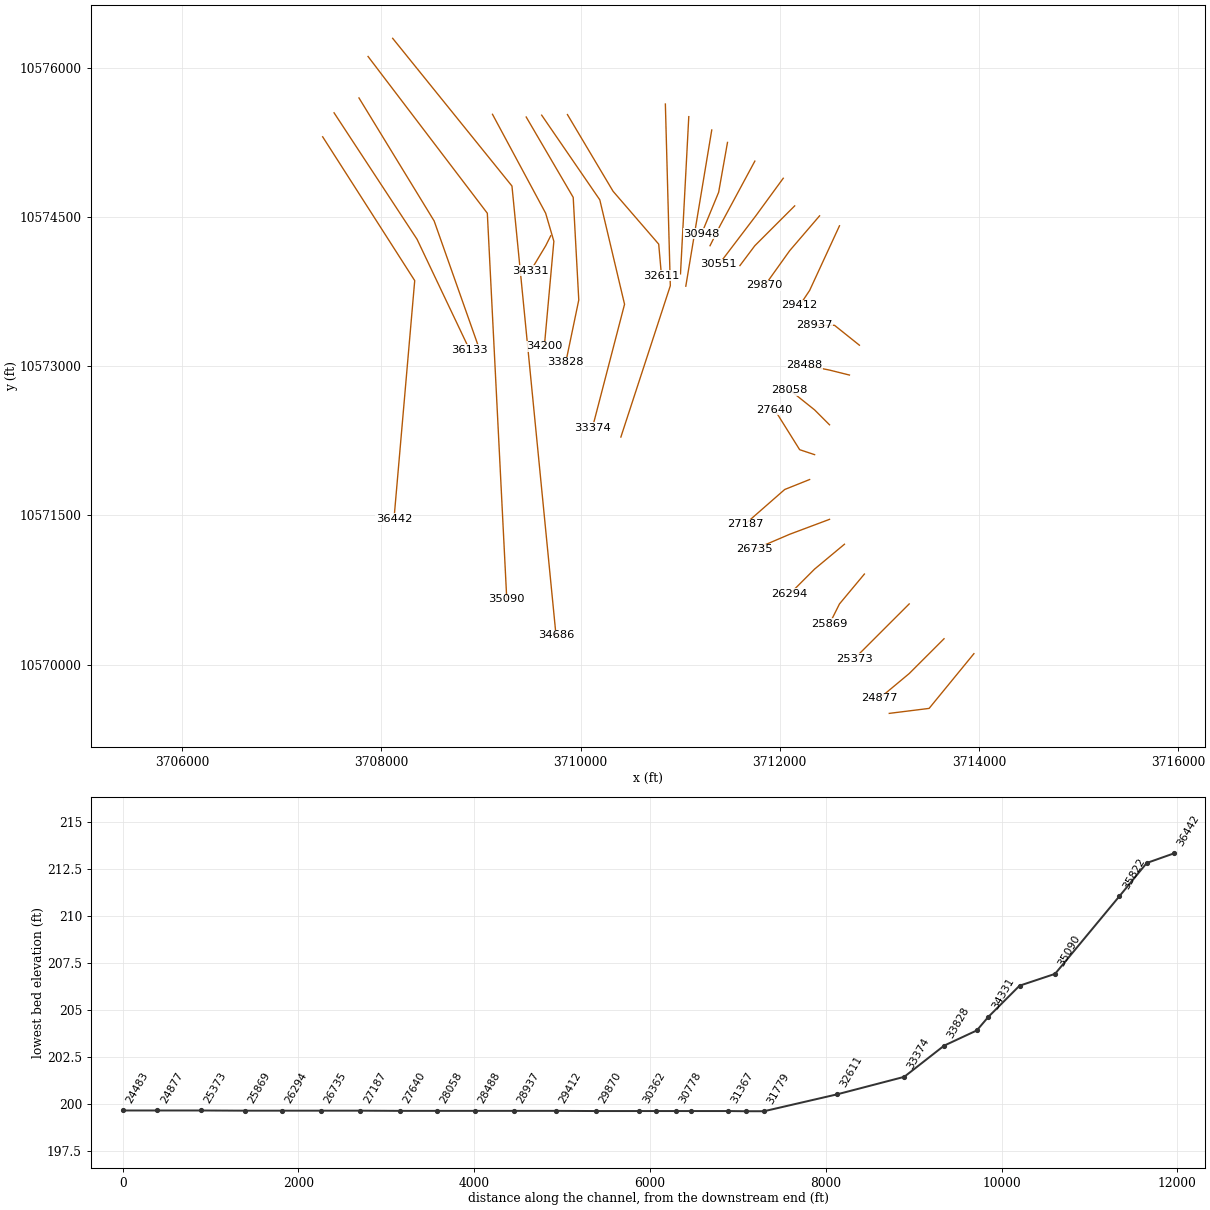
HEC-RAS study UNT 168 IN BOCR.prj: UNT 168 IN BOCR Base Level Engineering

--- UNT 168 IN BOCR.g01 (geometry) --- (continued)

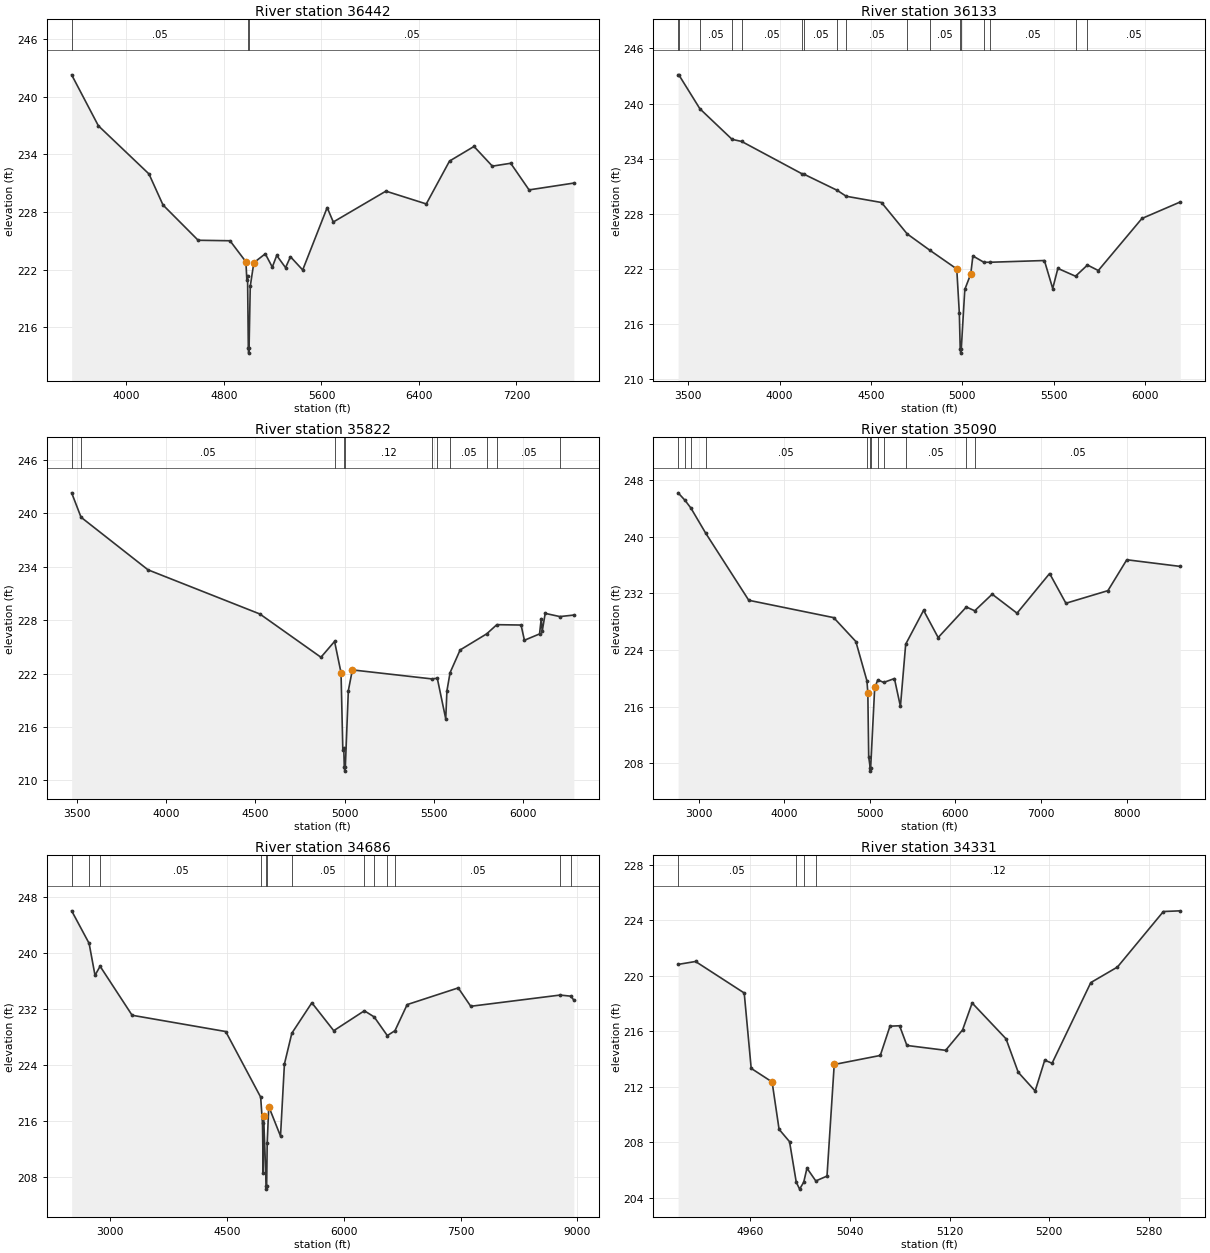
Type RM Length L Ch R = 1 ,36442   ,309,309,309
BEGIN DESCRIPTION:
UNT 168 IN BOCR 78.0
END DESCRIPTION:
XS GIS Cut Line= 3
      3707409.43     10575304.46      3708333.89     10573859.18
      3708125.63     10571464.27
#Sta/Elev= 30
  3550.9  242.27  3770.1  236.97  4185.1  231.96  4300.4  228.73  4588.7  225.06
  4849.9  225.01  4980.5  222.82    4988  220.93  4993.9  221.39  5000.2  213.82
  5002.9  213.32  5006.2  213.82  5016.1  220.28  5045.5  222.73  5139.3  223.65
  5196.9  222.27  5233.2  223.48  5305.7  222.21  5345.8  223.35  5446.2  221.97
    5647  228.46  5697.2  226.96  6128.8  230.17    6460  228.84  6650.7   233.3
  6851.5  234.82  7002.1  232.77  7152.6  233.07  7303.2   230.3  7670.5  231.01
#Mann= 3 ,-1 , 0
  3550.9     .05       0  5000.2     .03       0  5006.2     .05       0
Bank Sta=4980.5,5045.5
XS Rating Curve= 0 ,0
Exp/Cntr=0.3,0.1

Type RM Length L Ch R = 1 ,36133   ,311,311,311
BEGIN DESCRIPTION:
Mapping XS 8c0c86fe
END DESCRIPTION:
XS GIS Cut Line= 3
      3707523.91     10575545.53      3708357.26     10574274.67
      3708884.43     10573164.83
#Sta/Elev= 30
  3444.5  243.13  3449.3   243.1  3563.7  239.43  3739.9   236.1  3792.5  235.87
  4123.2  232.34  4135.7  232.28  4314.8  230.55  4364.5   229.9  4557.6  229.22
  4698.1   225.8  4822.1  224.02  4969.5  221.98  4983.6  217.14  4988.3  213.31
  4991.1  212.81  4994.3  213.31  5013.5  219.75  5046.2  221.44  5057.7   223.4
  5117.6  222.71  5151.6  222.71  5449.1   222.9  5494.6  219.85  5522.8  222.04
  5619.5  221.19  5684.8  222.41  5744.1  221.81  5982.9  227.48  6192.9  229.28
#Mann= 17 ,-1 , 0
  3444.5     .05       0  3449.3     .08       0  3563.7     .05       0
  3739.9     .08       0  3792.5     .05       0  4123.2     .08       0
  4135.7     .05       0  4314.8     .08       0  4364.5     .05       0
  4698.1     .08       0  4822.1     .05       0  4988.3     .04       0
  4994.3     .05       0  5117.6     .08       0  5151.6     .05       0
  5619.5     .08       0  5684.8     .05       0
Bank Sta=4969.5,5046.2
XS Rating Curve= 0 ,0
Exp/Cntr=0.3,0.1

Type RM Length L Ch R = 1 ,35822   ,732,732,732
BEGIN DESCRIPTION:
UNT 168 IN BOCR 77.0
END DESCRIPTION:
XS GIS Cut Line= 3
      3707773.98     10575695.13       3708529.2     10574458.13
      3708983.98     10573168.81
#Sta/Elev= 30
  3469.2   242.3  3521.8  239.56  3897.6  233.65  4524.8  228.69  4867.4  223.83
  4943.8  225.61    4980  222.09  4990.1   213.4  4995.4  213.62  4998.2  211.54
  5000.9  211.04  5004.2  211.54    5021  220.08  5043.6  222.41    5489   221.4
  5519.9  221.47  5567.3  216.91  5573.8  220.04  5591.6   222.1    5648  224.65
  5796.9  226.46  5853.8  227.49  5989.8  227.45  6008.5  225.74  6093.4  226.45
  6102.9  228.17  6108.2  226.74  6125.2  228.76  6207.3   228.4  6285.7  228.57
#Mann= 11 ,-1 , 0
  3469.2     .08       0  3521.8     .05       0  4943.8     .12       0
  4998.2     .07       0  5004.2     .12       0    5489     .05       0
  5519.9     .16       0  5591.6     .05       0  5796.9     .08       0
  5853.8     .05       0  6207.3     .08       0
Bank Sta=4980,5043.6
XS Rating Curve= 0 ,0
Exp/Cntr=0.3,0.1

Type RM Length L Ch R = 1 ,35090   ,404,404,404
BEGIN DESCRIPTION:
UNT 168 IN BOCR 76.0
END DESCRIPTION:
XS GIS Cut Line= 3
      3707865.17     10576111.74      3709063.05     10574536.26
      3709258.37     10570656.03
#Sta/Elev= 30
  2761.2   246.2  2842.6  245.13  2910.9  244.04    3082  240.53  3586.2  231.03
  4578.1  228.58  4836.6  225.21  4966.5  219.64  4976.7  217.91  4986.7  208.96
  5003.8  207.41  5006.5  206.91  5009.8  207.41  5056.8  218.72    5094   219.8
  5161.6  219.43  5287.1  219.98  5357.2  216.04  5418.7  224.83  5627.6  229.61
  5797.8  225.77    6127  230.08    6225  229.55  6428.6  231.89  6718.9  229.21
  7099.4  234.81  7289.7  230.61  7780.3  232.39  8000.6  236.75  8625.5  235.81
#Mann= 12 ,-1 , 0
  2761.2     .08       0  2842.6     .05       0  2910.9     .08       0
    3082     .05       0  4966.5     .12       0  5003.8     .07       0
  5009.8     .12       0    5094     .16       0  5161.6     .12       0
  5418.7     .05       0    6127     .08       0    6225     .05       0
Bank Sta=4976.7,5056.8
XS Rating Curve= 0 ,0
Exp/Cntr=0.3,0.1

Type RM Length L Ch R = 1 ,34686   ,355,355,355
BEGIN DESCRIPTION:
UNT 168 IN BOCR 75.0
END DESCRIPTION:
XS GIS Cut Line= 3
      3708112.55     10576294.05      3709310.45      10574809.7
      3709752.97     10570293.34
#Sta/Elev= 30
    2508  245.96  2732.1  241.32  2807.9  236.76    2873  238.06    3284  231.07
  4485.3  228.75  4933.8   219.4  4957.5  215.64  4966.7  208.61  4971.7  216.73
  5004.8  206.78  5007.5  206.28  5010.8  206.78  5017.8  212.83  5037.9  218.06
  5188.6  213.84  5238.9  224.12    5334  228.51  5590.8  232.85  5871.9  228.87
  6264.8  231.71  6391.1  230.83  6559.4  228.17  6657.6  228.87    6814  232.59
  7469.5  234.97  7630.2  232.35  8777.1  233.95  8915.9  233.79  8953.4  233.22
#Mann= 13 ,-1 , 0
    2508     .05       0  2732.1     .08       0    2873     .05       0
  4933.8     .12       0  5004.8     .07       0  5010.8     .12       0
    5334     .05       0  6264.8     .08       0  6391.1     .05       0
  6559.4     .07       0  6657.6     .05       0  8777.1     .08       0
  8915.9     .05       0
Bank Sta=4971.7,5037.9
XS Rating Curve= 0 ,0
Exp/Cntr=0.3,0.1

Type RM Length L Ch R = 1 ,34331   ,131,131,131
BEGIN DESCRIPTION:
UNT 168 IN BOCR 74.0
END DESCRIPTION:
XS GIS Cut Line= 3
      3709699.63     10574310.22      3709649.61     10574210.19
       3709499.6     10573960.18
#Sta/Elev= 30
  4901.9  220.81  4915.9  221.02    4955  218.75  4960.6  213.32  4977.4  212.34
    4983  208.93  4991.4  208.04  4996.8  205.12  4999.5  204.62  5002.8  205.12
  5005.4  206.13  5012.5  205.21  5021.5  205.56  5027.3   213.6  5064.3  214.25
  5072.1  216.36  5079.8  216.39  5085.7  214.97  5116.8  214.62  5130.4  216.09
  5138.1  218.03  5165.3  215.45  5175.1  213.04  5188.7  211.69  5196.4  213.91
  5202.3  213.69  5233.4   219.5  5254.8  220.62  5291.7  224.62  5305.3  224.67
#Mann= 4 ,-1 , 0
  4901.9     .05       0  4996.8     .03       0  5002.8     .05       0
  5012.5     .12       0
Bank Sta=4977.4,5027.3
XS Rating Curve= 0 ,0
Exp/Cntr=0.3,0.1

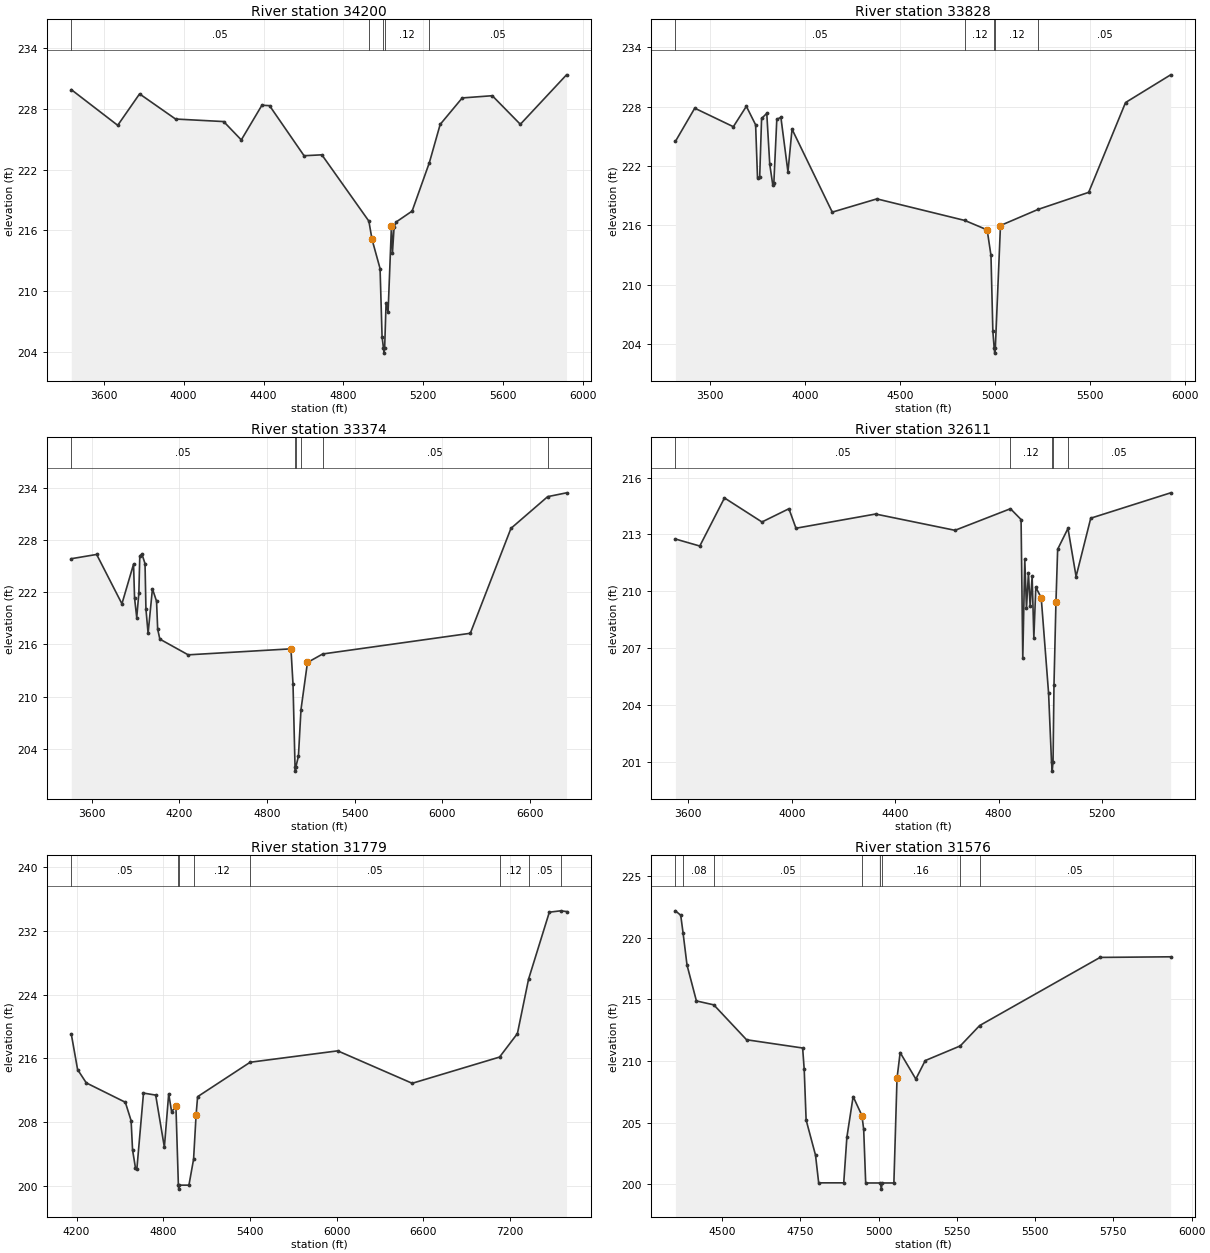
Type RM Length L Ch R = 1 ,34200   ,372,372,372
BEGIN DESCRIPTION:
Mapping XS 53afcfee
END DESCRIPTION:
XS GIS Cut Line= 4
      3709114.86     10575530.53      3709648.72      10574536.6
      3709731.18     10574254.49      3709635.69     10573199.75
#Sta/Elev= 30
    3437  229.89  3669.5  226.37  3779.1  229.47  3959.3  226.99  4200.4  226.74
  4288.7  224.93    4392  228.35  4430.2  228.31  4603.2  223.37  4692.4  223.46
  4927.9  216.92  4943.8  215.11    4984  212.24    4994  205.54    5001   204.4
  5003.8   203.9    5007   204.4  5014.1  208.85  5024.1  207.93  5041.1  216.48
  5046.1  213.78  5054.2  216.32  5064.3  216.83  5144.6  217.91  5231.2   222.7
  5285.2  226.46  5395.6  229.07  5546.2  229.29  5686.8  226.47  5918.2  231.35
#Mann= 5 ,-1 , 0
    3437     .05       0  4927.9     .12       0    5001     .07       0
    5007     .12       0  5231.2     .05       0
Bank Sta=4943.8,5041.1
XS Rating Curve= 0 ,0
Exp/Cntr=0.3,0.1

Type RM Length L Ch R = 1 ,33828   ,454,454,454
BEGIN DESCRIPTION:
Mapping XS f600cb56
END DESCRIPTION:
XS GIS Cut Line= 4
      3709453.46     10575503.35      3709925.52     10574695.87
      3709981.42      10573664.8      3709850.98     10573037.44
#Sta/Elev= 30
  3317.4  224.48  3419.1  227.83  3622.5  225.96    3691  228.02  3739.8  226.15
  3749.7  220.81  3761.3   220.9  3771.2  226.79  3798.5  227.31  3814.2  222.17
  3829.9  220.11  3835.7  220.23  3851.4   226.7  3872.9  226.91  3910.1   221.4
  3931.6  225.71  4143.5  217.33  4378.6  218.67  4841.9  216.49  4959.5  215.54
  4979.6  212.96  4989.5   205.3  4996.5  203.59  4999.3  203.09  5002.5  203.59
  5029.6  215.98  5228.2  217.61  5494.3  219.33  5688.4   228.4  5926.1   231.2
#Mann= 5 ,-1 , 0
  3317.4     .05       0  4841.9     .12       0  4996.5     .07       0
  5002.5     .12       0  5228.2     .05       0
Bank Sta=4959.5,5029.6
XS Rating Curve= 0 ,0
Exp/Cntr=0.3,0.1

Type RM Length L Ch R = 1 ,33374   ,763,763,763
BEGIN DESCRIPTION:
Mapping XS 5648ebc5
END DESCRIPTION:
XS GIS Cut Line= 4
      3709608.76     10575521.96      3710192.61     10574671.03
      3710441.06     10573621.32      3710118.08      10572379.1
#Sta/Elev= 30
  3458.7  225.87  3632.4  226.36  3805.7  220.68  3885.3  225.24  3892.3  221.33
  3907.2  219.09  3921.7  221.92  3928.2   226.2  3943.1  226.39    3964   225.3
  3970.2  220.09    3985  217.29  4014.8   222.4    4043  220.98  4050.7  217.76
  4065.6  216.62  4259.8  214.81  4964.2   215.5  4978.3  211.43  4992.1  201.93
  4994.8  201.43  4998.1  201.93  5015.4  203.15    5033  208.52  5077.3  213.93
  5181.9  214.91  6193.4  217.29    6472  229.36  6723.7  233.01  6852.9  233.45
#Mann= 6 ,-1 , 0
  3458.7     .05       0  4992.1     .03       0  4998.1     .05       0
    5033     .12       0  5181.9     .05       0  6723.7     .08       0
Bank Sta=4964.2,5077.3
XS Rating Curve= 0 ,0
Exp/Cntr=0.3,0.1

Type RM Length L Ch R = 1 ,32611   ,832,832,832
BEGIN DESCRIPTION:
Mapping XS c00c693d
END DESCRIPTION:
XS GIS Cut Line= 4
      3709867.48      10575527.9       3710325.8     10574757.09
      3710784.13     10574225.84      3710811.91     10573909.88
#Sta/Elev= 30
    3550  212.76  3644.2  212.39  3739.7  214.93  3884.7  213.66    3989  214.36
  4016.3  213.33    4324  214.08  4631.4  213.22  4845.9  214.36    4887  213.79
  4893.6  206.45  4901.3  211.68  4907.9  209.11  4915.5  210.96  4922.1  209.21
  4929.8  210.79  4936.4  207.54    4944  210.21  4964.9  209.66  4993.4  204.62
  5004.7     201  5007.4   200.5  5010.7     201  5014.3  205.05  5021.9  209.42
  5028.5  212.22  5068.4  213.32  5099.8  210.78  5156.5  213.86  5465.6   215.2
#Mann= 5 ,-1 , 0
    3550     .05       0  4845.9     .12       0  5004.7     .07       0
  5010.7     .12       0  5068.4     .05       0
Bank Sta=4964.9,5021.9
XS Rating Curve= 0 ,0
Exp/Cntr=0.3,0.1

Type RM Length L Ch R = 1 ,31779   ,203,203,203
BEGIN DESCRIPTION:
Mapping XS c3c7cab5
END DESCRIPTION:
XS GIS Cut Line= 3
        3710851.     10575633.81      3710900.69     10573807.66
      3710404.21     10572287.19
#Sta/Elev= 30
    4164  219.05  4207.6   214.6  4267.7  212.93  4537.8   210.5  4577.8  208.19
  4587.8  204.52  4607.8  202.27  4617.8  202.17  4663.5  211.65  4747.8   211.4
  4807.9  204.86  4837.9  211.57  4857.9  209.32  4887.9  209.98  4904.9   200.1
  4907.6   199.6  4910.9   200.1  4977.9   200.1    5010  203.35  5027.4  208.92
  5037.9   211.2  5401.4  215.52  6007.2  216.95  6522.6  212.88    7127  216.17
  7250.5  219.12  7327.6  225.94  7471.4  234.35  7549.3  234.52  7590.3  234.43
#Mann= 8 ,-1 , 0
    4164     .05       0  4904.9     .03       0  4910.9     .05       0
    5010     .12       0  5401.4     .05       0    7127     .12       0
  7327.6     .05       0  7549.3     .08       0
Bank Sta=4887.9,5027.4
XS Rating Curve= 0 ,0
Exp/Cntr=0.3,0.1

Type RM Length L Ch R = 1 ,31576   ,209,209,209
BEGIN DESCRIPTION:
Mapping XS cc923b80
END DESCRIPTION:
XS GIS Cut Line= 2
      3711086.22     10575507.11      3711002.88     10573927.21
#Sta/Elev= 30
  4350.8  222.18  4367.7  221.82    4375  220.42  4387.8  217.78  4417.8  214.87
  4473.4  214.55    4578  211.72  4757.2  211.05  4762.2  209.31  4768.3  205.21
  4798.3  202.36  4808.4  200.11  4888.5  200.11  4898.5  203.81  4918.5  207.11
  4946.6  205.57  4952.2  204.45  4958.6   200.1  5005.6   200.1  5008.4   199.6
  5011.6   200.1  5048.7   200.1  5058.7  208.59  5068.7  210.68  5118.8  208.53
  5148.8  210.03  5260.8  211.22  5322.6  212.87  5707.4   218.4  5932.9  218.45
#Mann= 8 ,-1 , 0
  4350.8     .05       0    4375     .08       0  4473.4     .05       0
  4946.6     .16       0  5005.6     .07       0  5011.6     .16       0
  5260.8     .12       0  5322.6     .05       0
Bank Sta=4946.6,5058.7
XS Rating Curve= 0 ,0
Exp/Cntr=0.3,0.1

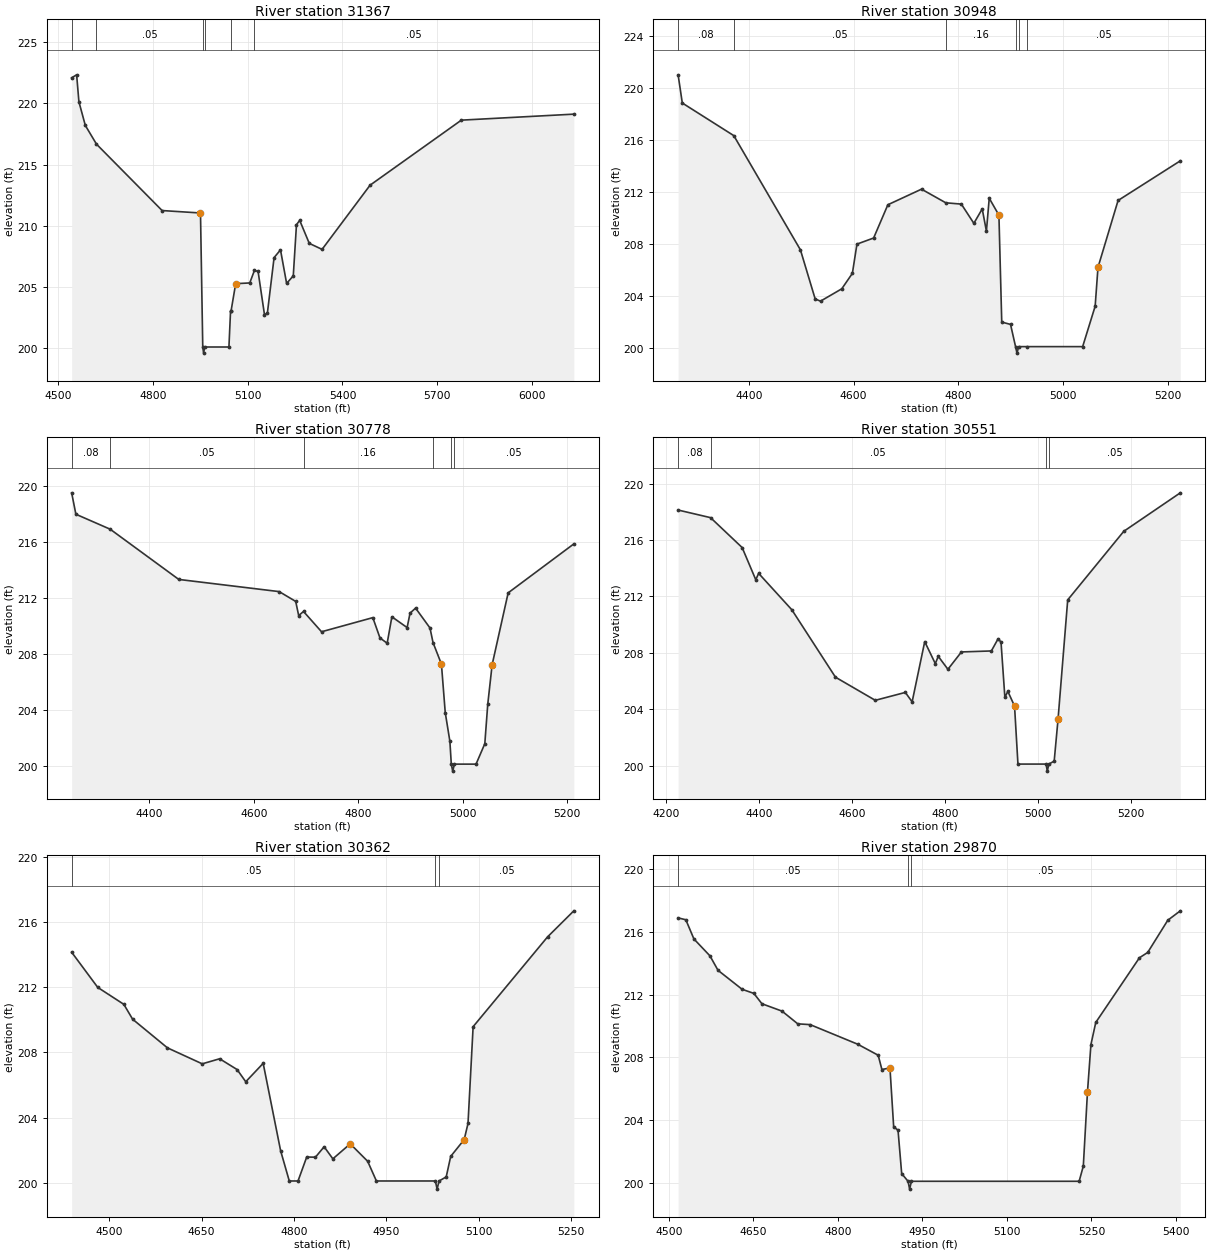
Type RM Length L Ch R = 1 ,31367   ,419,419,419
BEGIN DESCRIPTION:
Mapping XS 1687e8c8
END DESCRIPTION:
XS GIS Cut Line= 2
      3711316.85     10575372.92      3711056.28      10573803.3
#Sta/Elev= 30
    4542  222.09  4557.8  222.33    4565  220.13  4585.3   218.2  4620.7  216.67
  4828.6  211.25  4950.2  211.05  4957.4  200.11  4960.1  199.61  4963.4  200.11
  5040.3  200.11  5045.4  203.01  5047.2  203.07  5061.7  205.28  5106.3  205.34
  5121.1  206.36  5132.7  206.28    5153  202.74  5162.2  202.89  5183.4  207.41
  5203.7  208.04  5223.1   205.3  5244.2  205.92  5254.3  210.09  5264.5  210.45
  5294.9  208.57  5335.4  208.08  5487.5  213.32  5776.7  218.63  6133.1  219.12
#Mann= 6 ,-1 , 0
    4542     .08       0  4620.7     .05       0  4957.4     .03       0
  4963.4     .05       0  5047.2     .16       0  5121.1     .05       0
Bank Sta=4950.2,5061.7
XS Rating Curve= 0 ,0
Exp/Cntr=0.3,0.1

Type RM Length L Ch R = 1 ,30948   ,170,170,170
BEGIN DESCRIPTION:
Mapping XS 427b1cf1
END DESCRIPTION:
XS GIS Cut Line= 3
      3711474.96     10575248.08      3711385.99     10574746.82
      3711214.57     10574330.21
#Sta/Elev= 30
  4264.8  221.03  4272.8  218.86  4371.2  216.35  4498.5  207.56  4526.7  203.78
  4536.9  203.61  4577.5  204.56  4597.8  205.75  4606.5     208  4638.4  208.47
  4665.6  211.03  4729.9  212.23  4776.3  211.18    4806  211.08  4829.9   209.6
  4845.9  210.71  4853.9     209  4859.3  211.53  4877.8  210.23  4883.2     202
    4900  201.82  4909.6  200.11  4912.3  199.61  4915.6  200.11  4931.4  200.11
  5037.8  200.11  5061.7  203.22  5067.1  206.21  5105.5  211.36  5224.4  214.41
#Mann= 6 ,-1 , 0
  4264.8     .08       0  4371.2     .05       0  4776.3     .16       0
  4909.6     .03       0  4915.6     .16       0  4931.4     .05       0
Bank Sta=4877.8,5067.1
XS Rating Curve= 0 ,0
Exp/Cntr=0.3,0.1

Type RM Length L Ch R = 1 ,30778   ,227,227,227
BEGIN DESCRIPTION:
UNT 168 IN BOCR 67.0
END DESCRIPTION:
XS GIS Cut Line= 3
      3711749.59     10575060.15      3711399.61     10574410.19
      3711299.61     10574210.19
#Sta/Elev= 30
    4251   219.5  4259.1  217.97  4324.8   216.9  4456.2  213.31  4648.5  212.44
  4680.1  211.74  4685.8  210.73  4695.1  211.02  4729.6  209.57  4827.8  210.58
  4841.5  209.13  4855.3  208.75  4864.3  210.64  4893.5  209.87  4899.1   210.9
  4909.7  211.26  4937.3  209.84  4943.1   208.8  4959.2  207.26  4966.5   203.8
  4975.4  201.74  4978.1  200.11  4980.8  199.61  4984.1  200.11  5025.5  200.11
  5042.3  201.57  5047.9  204.38  5056.3  207.21    5087  212.35  5212.8  215.85
#Mann= 6 ,-1 , 0
    4251     .08       0  4324.8     .05       0  4695.1     .16       0
  4943.1     .05       0  4978.1     .03       0  4984.1     .05       0
Bank Sta=4959.2,5056.3
XS Rating Curve= 0 ,0
Exp/Cntr=0.3,0.1

Type RM Length L Ch R = 1 ,30551   ,189,189,189
BEGIN DESCRIPTION:
Mapping XS 6f07a65d
END DESCRIPTION:
XS GIS Cut Line= 3
      3712034.84     10574887.85      3711759.25     10574510.27
      3711388.18     10574022.03
#Sta/Elev= 30
  4226.2  218.12    4296  217.58    4364  215.46  4393.3  213.18  4399.5  213.63
  4470.9  211.05  4564.8  206.27  4650.5  204.63  4715.2  205.19  4729.8  204.52
  4756.9  208.79  4779.7  207.23    4786  207.75  4806.8  206.83  4835.9  208.06
  4900.3  208.13  4914.9     209  4921.1  208.75  4929.4  204.83  4935.7  205.27
  4950.2  204.22  4957.5  200.11    5018  200.11  5020.7  199.61    5024  200.11
  5035.5  200.32  5043.8  203.29  5064.6  211.75  5185.2  216.61  5306.9  219.34
#Mann= 4 ,-1 , 0
  4226.2     .08       0    4296     .05       0    5018     .03       0
    5024     .05       0
Bank Sta=4950.2,5043.8
XS Rating Curve= 0 ,0
Exp/Cntr=0.3,0.1

Type RM Length L Ch R = 1 ,30362   ,492,492,492
BEGIN DESCRIPTION:
UNT 168 IN BOCR 66.0
END DESCRIPTION:
XS GIS Cut Line= 3
       3712149.6     10574610.18      3711749.61     10574210.19
       3711599.6     10574010.17
#Sta/Elev= 30
  4438.9  214.15  4481.3  211.99  4523.7  210.95  4537.9  210.04  4594.5  208.28
    4651   207.3  4679.3  207.61  4707.6  206.95  4721.7   206.2    4750  207.33
  4778.3  201.97  4792.4  200.11  4806.6  200.11  4820.7  201.58  4834.9  201.57
    4849  202.21  4863.2  201.47  4891.4  202.39  4919.7  201.32  4933.9  200.11
  5029.7  200.11  5032.5  199.61  5035.7  200.11  5047.3  200.36  5054.6  201.62
  5076.5  202.65  5082.7  203.64    5091  209.58  5211.9  215.09  5254.6  216.69
#Mann= 3 ,-1 , 0
  4438.9     .05       0  5029.7     .03       0  5035.7     .05       0
Bank Sta=4891.4,5076.5
XS Rating Curve= 0 ,0
Exp/Cntr=0.3,0.1

Type RM Length L Ch R = 1 ,29870   ,458,458,458
BEGIN DESCRIPTION:
UNT 168 IN BOCR 65.0
END DESCRIPTION:
XS GIS Cut Line= 3
      3712399.59     10574510.16      3712099.61     10574160.19
      3711849.59     10573810.16
#Sta/Elev= 30
  4516.7  216.89  4530.4  216.77  4544.7  215.55  4573.2  214.47  4587.5  213.55
  4630.3  212.34  4651.1  212.08  4665.4  211.42  4701.1  210.95    4729  210.14
    4751  210.09  4835.5  208.84  4871.7  208.14  4878.3  207.23  4892.6  207.33
  4899.2  203.57  4906.9  203.37  4913.4   200.6  4924.7  200.11  4927.5  199.61
  4930.7  200.11  5228.3  200.11  5235.7  201.08  5243.1  205.81  5249.2  208.82
  5257.8  210.23  5335.3  214.35    5350  214.69  5385.6  216.74  5407.8  217.34
#Mann= 3 ,-1 , 0
  4516.7     .05       0  4924.7     .03       0  4930.7     .05       0
Bank Sta=4892.6,5243.1
XS Rating Curve= 0 ,0
Exp/Cntr=0.3,0.1

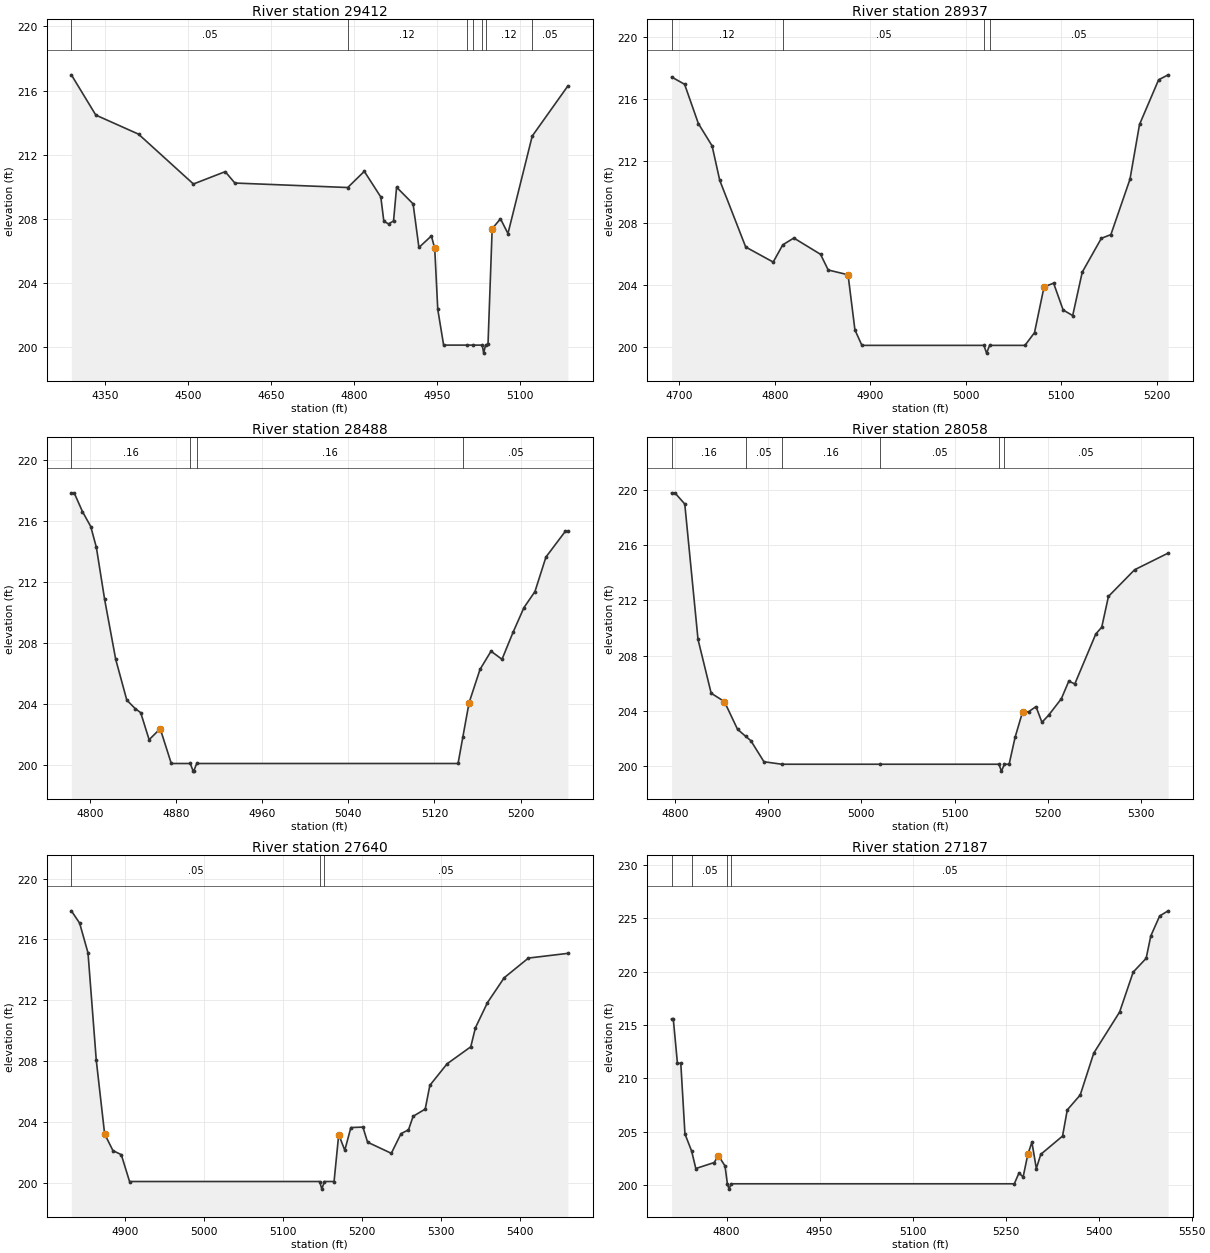
Type RM Length L Ch R = 1 ,29412   ,475,475,475
BEGIN DESCRIPTION:
UNT 168 IN BOCR 64.0
END DESCRIPTION:
XS GIS Cut Line= 3
      3712599.62     10574410.21      3712299.61     10573760.19
       3712199.6     10573610.18
#Sta/Elev= 30
  4289.6  216.98  4333.7  214.47  4410.8  213.28  4509.9  210.17  4567.3  210.94
  4584.7  210.23  4788.4  209.95  4818.3  210.96  4848.1  209.36  4853.6  207.84
  4862.3  207.68  4871.1  207.87  4876.6  209.97  4906.4  208.93  4916.9  206.21
  4939.4  206.93  4945.4  206.16  4950.9  202.35  4961.5  200.12  5003.4  200.12
    5014  200.12  5031.1  200.12  5033.8  199.62  5037.1  200.12  5041.6  200.18
  5049.1  207.38  5064.1     208  5077.6  207.08  5121.4  213.16  5185.8  216.29
#Mann= 7 ,-1 , 0
  4289.6     .05       0  4788.4     .12       0  5003.4     .05       0
    5014     .12       0  5031.1     .07       0  5037.1     .12       0
  5121.4     .05       0
Bank Sta=4945.4,5049.1
XS Rating Curve= 0 ,0
Exp/Cntr=0.3,0.1

Type RM Length L Ch R = 1 ,28937   ,449,449,449
BEGIN DESCRIPTION:
UNT 168 IN BOCR 63.0
END DESCRIPTION:
XS GIS Cut Line= 3
      3712799.57     10573210.22      3712549.61     10573410.19
      3712349.62     10573410.19
#Sta/Elev= 30
  4691.9  217.42  4705.5  216.95  4719.9  214.42  4734.3  212.98  4742.3  210.76
  4769.5  206.46  4798.3  205.49  4808.3   206.6  4819.9  207.04  4847.9  205.99
  4855.9  204.98  4876.7  204.67  4883.9  201.12  4891.2  200.12    5019  200.12
  5021.8  199.62    5025  200.12    5062  200.12    5072  200.94    5082  203.89
    5092  204.13    5102   202.4    5112  202.04    5122  204.84    5142  207.02
    5152  207.26    5172  210.83    5182  214.36    5202  217.24    5212  217.56
#Mann= 4 ,-1 , 0
  4691.9     .12       0  4808.3     .05       0    5019    .033       0
    5025     .05       0
Bank Sta=4876.7,5082
XS Rating Curve= 0 ,0
Exp/Cntr=0.3,0.1

Type RM Length L Ch R = 1 ,28488   ,430,430,430
BEGIN DESCRIPTION:
UNT 168 IN BOCR 62.0
END DESCRIPTION:
XS GIS Cut Line= 3
      3712699.61     10572910.19      3712499.61     10572960.19
      3712249.61     10573010.19
#Sta/Elev= 29
  4782.9  217.86  4785.5  217.86  4793.2  216.63  4800.9  215.65  4806.1  214.29
  4813.8  210.87  4824.1  206.94  4834.4  204.27  4842.2  203.72  4847.3  203.45
  4855.1  201.68  4865.4   202.4  4875.7  200.12  4893.3  200.12    4896  199.62
  4896.5  199.62  4899.3  200.12    5142  200.12  5146.5  201.88  5152.2   204.1
  5162.4  206.29  5172.6  207.48  5182.8  206.95    5193  208.71  5203.2  210.34
  5213.4  211.39  5223.6  213.65  5241.5  215.33    5244  215.33
#Mann= 4 ,-1 , 0
  4782.9     .16       0  4893.3     .07       0  4899.3     .16       0
  5146.5     .05       0
Bank Sta=4865.4,5152.2
XS Rating Curve= 0 ,0
Exp/Cntr=0.3,0.1

Type RM Length L Ch R = 1 ,28058   ,418,418,418
BEGIN DESCRIPTION:
UNT 168 IN BOCR 61.0
END DESCRIPTION:
XS GIS Cut Line= 3
      3712499.61     10572410.18      3712349.61     10572560.19
       3712099.6     10572760.19
#Sta/Elev= 30
  4796.7   219.8  4800.2   219.8  4810.8  218.99    4825  209.17  4839.1  205.27
  4853.3  204.66  4867.4  202.65    4876  202.15  4881.6  201.83  4895.7   200.3
  4914.8  200.12  5020.2  200.12  5147.5  200.12  5150.3  199.62  5153.5  200.12
  5158.5  200.12  5164.9  202.07  5172.9  203.91  5179.3  203.92  5187.3   204.3
  5193.7  203.16  5200.9  203.68  5214.5  204.87  5222.5  206.15  5228.9  205.94
  5251.4  209.56  5257.8  210.06    5265  212.29    5293  214.22    5329  215.43
#Mann= 6 ,-1 , 0
  4796.7     .16       0    4876     .05       0  4914.8     .16       0
  5020.2     .05       0  5147.5     .07       0  5153.5     .05       0
Bank Sta=4853.3,5172.9
XS Rating Curve= 0 ,0
Exp/Cntr=0.3,0.1

Type RM Length L Ch R = 1 ,27640   ,453,453,453
BEGIN DESCRIPTION:
UNT 168 IN BOCR 60.0
END DESCRIPTION:
XS GIS Cut Line= 3
      3712349.62     10572110.19      3712199.61     10572160.19
      3711949.62     10572560.17
#Sta/Elev= 30
  4831.5  217.88    4842  217.07  4852.6  215.12  4863.1  208.07  4873.7  203.24
  4884.2  202.15  4894.8  201.88  4905.3  200.12  5146.4  200.12  5149.2  199.62
  5152.4  200.12  5164.7  200.12  5170.6   203.2  5178.3  202.17    5186  203.66
  5201.3  203.69  5207.2   202.7  5237.3  201.97  5249.6  203.26  5259.1  203.51
    5265   204.4  5280.3  204.87  5286.2  206.43    5308  207.84  5338.1  208.96
    5344  210.21  5359.3  211.86  5380.5  213.49  5411.2  214.78  5461.3  215.09
#Mann= 3 ,-1 , 0
  4831.5     .05       0  5146.4    .033       0  5152.4     .05       0
Bank Sta=4873.7,5170.6
XS Rating Curve= 0 ,0
Exp/Cntr=0.3,0.1

Type RM Length L Ch R = 1 ,27187   ,452,452,452
BEGIN DESCRIPTION:
UNT 168 IN BOCR 59.0
END DESCRIPTION:
XS GIS Cut Line= 3
      3712299.59     10571860.18      3712049.61     10571760.19
      3711649.65     10571410.22
#Sta/Elev= 30
  4711.4  215.57  4714.1  215.57  4720.8  211.41  4726.2  211.42  4732.9   204.8
  4743.7  203.19  4750.4  201.56    4780  202.12  4786.8  202.77  4797.5   201.8
  4801.3  200.13    4804  199.63  4807.3  200.13    5264  200.13  5271.5  201.14
  5278.2  200.77  5285.8  202.88  5292.4  204.03  5299.5  201.56  5306.7  202.89
  5341.8   204.6  5349.4  207.05  5370.3  208.45  5392.1  212.37  5433.8  216.22
  5455.7  219.96  5476.6  221.25  5484.1  223.35  5498.4  225.22  5512.1   225.7
#Mann= 4 ,-1 , 0
  4711.4     .08       0  4743.7     .05       0  4801.3    .033       0
  4807.3     .05       0
Bank Sta=4786.8,5285.8
XS Rating Curve= 0 ,0
Exp/Cntr=0.3,0.1

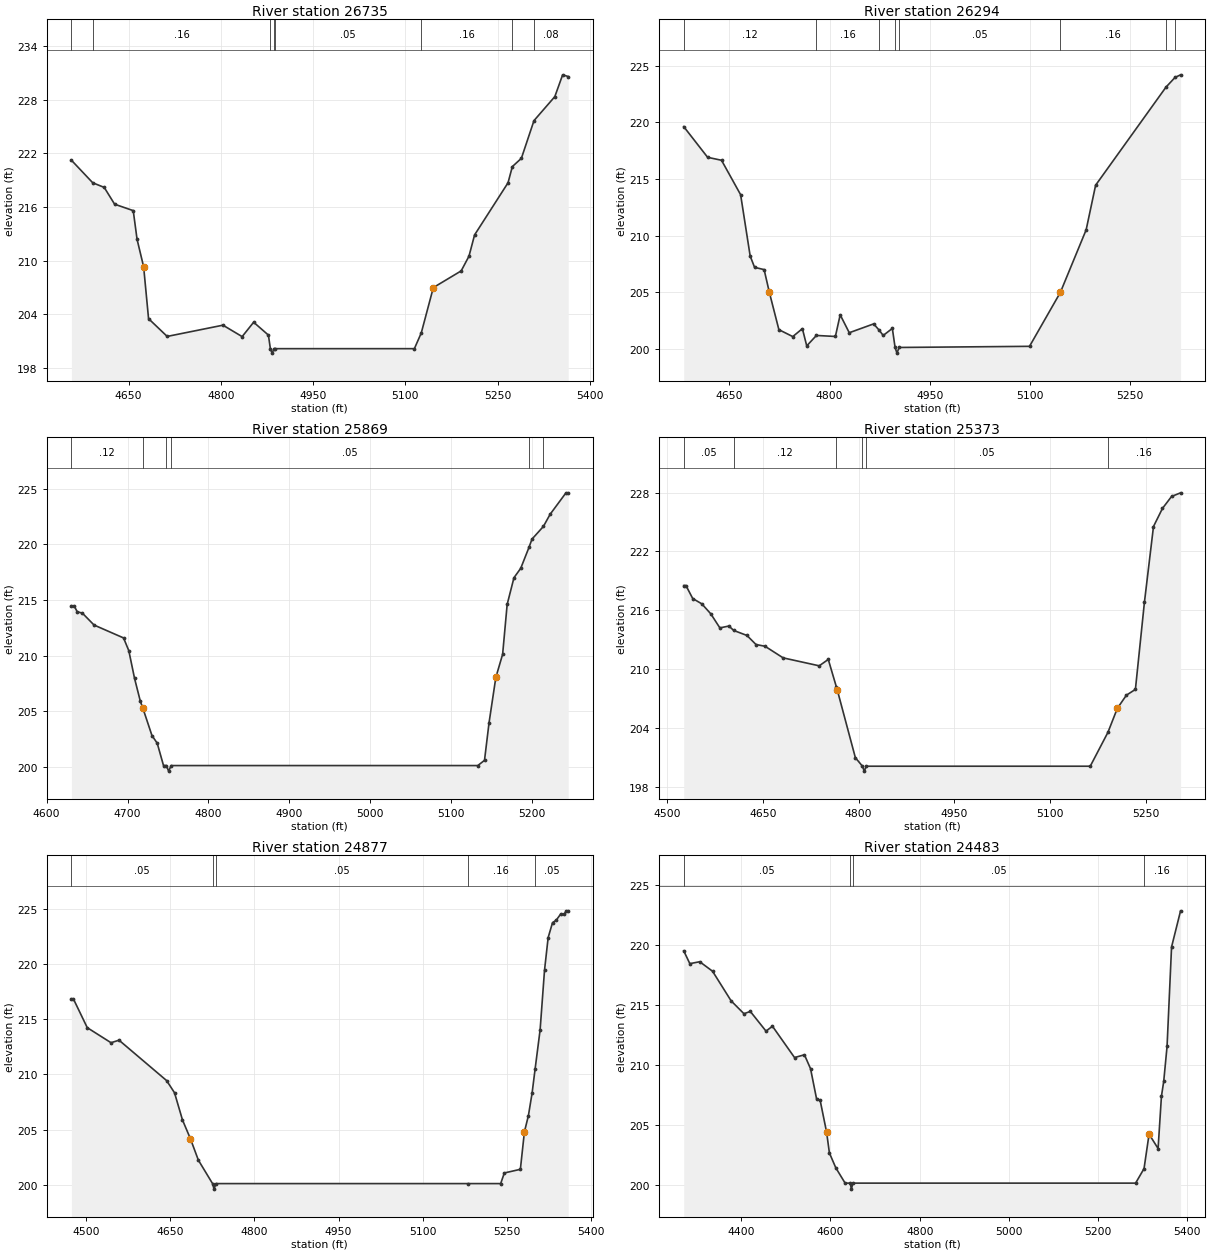
Type RM Length L Ch R = 1 ,26735   ,441,441,441
BEGIN DESCRIPTION:
UNT 168 IN BOCR 58.0
END DESCRIPTION:
XS GIS Cut Line= 3
      3712499.61     10571460.19      3712099.61     10571310.19
       3711749.6     10571160.18
#Sta/Elev= 30
    4557  221.24  4591.7  218.71  4610.4  218.19  4627.3  216.31  4657.6  215.59
  4663.8  212.38  4674.5   209.3  4682.5  203.49  4712.8   201.5  4803.5  202.76
  4834.7  201.48  4853.4  203.09  4877.4  201.65  4880.6  200.13  4883.4  199.63
  4886.6  200.13  4887.5  200.13  5114.8  200.13    5126  201.89  5145.6  206.97
  5190.9  208.84  5203.6  210.49  5212.7  212.87  5267.1  218.71  5274.1  220.52
  5288.8  221.45  5309.3  225.67  5343.2  228.36  5355.9   230.8    5365  230.61
#Mann= 8 ,-1 , 0
    4557     .05       0  4591.7     .16       0  4880.6    .033       0
  4886.6     .16       0  4887.5     .05       0    5126     .16       0
  5274.1     .05       0  5309.3     .08       0
Bank Sta=4674.5,5145.6
XS Rating Curve= 0 ,0
Exp/Cntr=0.3,0.1

Type RM Length L Ch R = 1 ,26294   ,425,425,425
BEGIN DESCRIPTION:
UNT 168 IN BOCR 57.0
END DESCRIPTION:
XS GIS Cut Line= 3
      3712649.58     10571210.17      3712349.61     10570960.19
      3712099.63     10570710.21
#Sta/Elev= 30
  4581.6  219.62  4617.4  216.91  4638.2  216.65  4666.8  213.61  4681.1   208.2
  4687.7   207.2    4702     207  4709.8     205  4724.1   201.7  4744.9  201.09
  4759.3  201.79  4765.8  200.27  4780.3  201.19  4808.7   201.1  4815.9  203.01
  4829.5  201.43    4866  202.21  4874.5  201.64  4880.3  201.19    4894  201.81
  4898.1  200.13  4900.9  199.63  4904.1  200.13  5099.4  200.23  5145.6  204.99
  5184.2  210.51  5198.4  214.45  5303.7   223.1  5317.3  223.96  5325.6  224.19
#Mann= 8 ,-1 , 0
  4581.6     .12       0  4780.3     .16       0  4874.5     .05       0
  4898.1    .033       0  4904.1     .05       0  5145.6     .16       0
  5303.7     .05       0  5317.3     .08       0
Bank Sta=4709.8,5145.6
XS Rating Curve= 0 ,0
Exp/Cntr=0.3,0.1

Type RM Length L Ch R = 1 ,25869   ,496,496,496
BEGIN DESCRIPTION:
UNT 168 IN BOCR 56.0
END DESCRIPTION:
XS GIS Cut Line= 3
      3712849.63     10570910.22      3712599.61     10570610.19
      3712499.59     10570410.15
#Sta/Elev= 30
  4630.6  214.49  4633.9  214.49  4637.8  213.96  4644.3  213.82  4658.6  212.76
  4695.1   211.6  4701.6  210.45  4708.7  207.96  4715.9  205.89    4719  205.28
  4730.2  202.83  4736.7  202.14  4744.5  200.13    4748  200.13  4750.8  199.63
    4754  200.13    5133  200.13  5141.3   200.6  5146.9  203.97  5155.3  208.05
  5163.7  210.13  5169.3  214.61  5177.7  217.01  5186.1  217.86  5196.4  219.76
    5200  220.48  5214.1  221.62  5222.4  222.71    5242  224.64  5244.8  224.64
#Mann= 6 ,-1 , 0
  4630.6     .12       0    4719     .05       0    4748    .033       0
    4754     .05       0  5196.4     .16       0  5214.1     .05       0
Bank Sta=4719,5155.3
XS Rating Curve= 0 ,0
Exp/Cntr=0.3,0.1

Type RM Length L Ch R = 1 ,25373   ,496,496,496
BEGIN DESCRIPTION:
UNT 168 IN BOCR 55.0
END DESCRIPTION:
XS GIS Cut Line= 3
       3713299.6     10570610.18      3712949.61     10570260.19
      3712749.61     10570060.19
#Sta/Elev= 30
  4526.2  218.53  4529.7  218.53  4540.3  217.21  4554.5  216.67  4568.6  215.65
  4582.8  214.22  4596.9  214.41  4604.5  213.96  4625.2  213.45  4639.3  212.53
  4653.5  212.35  4681.8  211.17  4738.3  210.36  4752.5  211.01    4765  208.25
  4766.6   207.9  4794.9  201.01    4806  200.14  4808.8  199.64    4812  200.14
  5162.6  200.14  5190.3  203.59    5205  206.03  5219.2  207.37  5233.3  207.96
  5247.4  216.82  5261.6  224.54  5275.7  226.39  5289.9   227.6    5304  227.97
#Mann= 6 ,-1 , 0
  4526.2     .05       0  4604.5     .12       0    4765     .05       0
    4806    .033       0    4812     .05       0  5190.3     .16       0
Bank Sta=4766.6,5205
XS Rating Curve= 0 ,0
Exp/Cntr=0.3,0.1

Type RM Length L Ch R = 1 ,24877   ,394,394,394
BEGIN DESCRIPTION:
UNT 168 IN BOCR 54.0
END DESCRIPTION:
XS GIS Cut Line= 3
      3713649.61     10570260.19      3713299.61     10569910.19
       3712999.6     10569660.18
#Sta/Elev= 30
  4473.8  216.84  4477.3  216.84  4502.1  214.23  4544.5  212.87  4558.7   213.1
  4643.5  209.45  4657.6  208.35  4671.8  205.89  4685.9   204.2  4700.1  202.26
  4725.4  200.14  4728.1  199.64  4731.4  200.14  5179.8  200.14  5238.9  200.14
  5245.4   201.1    5274  201.43  5281.2  204.81  5288.3  206.28  5294.9  208.32
  5300.3  210.51  5309.2  214.04    5317   219.4  5323.5  222.37  5331.3  223.72
  5337.8  223.94  5345.6  224.48  5352.1   224.5    5356  224.79  5359.3  224.79
#Mann= 5 ,-1 , 0
  4473.8     .05       0  4725.4    .033       0  4731.4     .05       0
  5179.8     .16       0  5300.3     .05       0
Bank Sta=4685.9,5281.2
XS Rating Curve= 0 ,0
Exp/Cntr=0.3,0.1

Type RM Length L Ch R = 1 ,24483   ,412,412,412
BEGIN DESCRIPTION:
UNT 168 IN BOCR 53.0
END DESCRIPTION:
XS GIS Cut Line= 3
      3713949.63     10570110.21      3713499.61     10569560.19
      3713099.59     10569510.19
#Sta/Elev= 30
    4271  219.49  4284.7  218.42  4306.9  218.58  4335.6  217.79  4377.3  215.32
    4406  214.25  4420.3  214.44  4455.5   212.8  4469.9  213.21  4519.4   210.6
  4541.6  210.83  4555.3  209.67  4568.9  207.14  4576.8  207.04  4591.2   204.4
  4597.6  202.65    4612  201.41  4632.8  200.14  4644.2  200.14  4646.9  199.64
  4650.2  200.14    5284  200.14  5302.9  201.35  5314.2  204.22  5334.4  203.02
  5341.9  207.37    5347  208.61  5354.5  211.52  5364.6  219.81  5384.8  222.82
#Mann= 4 ,-1 , 0
    4271     .05       0  4644.2    .033       0  4650.2     .05       0
  5302.9     .16       0
Bank Sta=4591.2,5314.2
XS Rating Curve= 0 ,0
Exp/Cntr=0.3,0.1