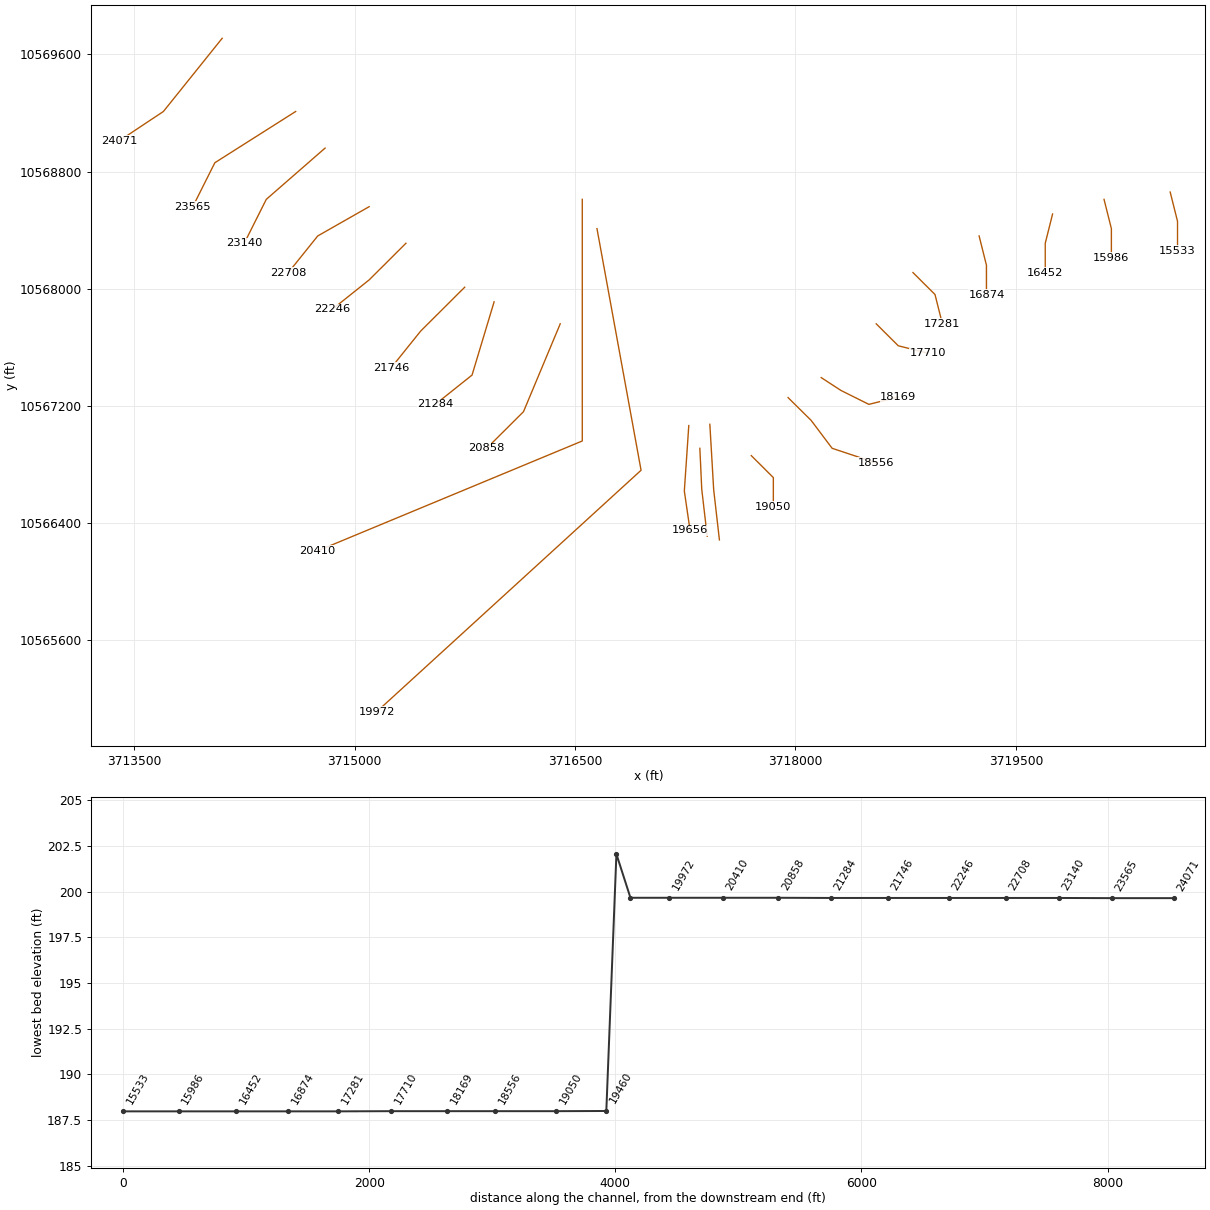
HEC-RAS study UNT 168 IN BOCR.prj: UNT 168 IN BOCR Base Level Engineering

--- UNT 168 IN BOCR.g01 (geometry) --- (continued)

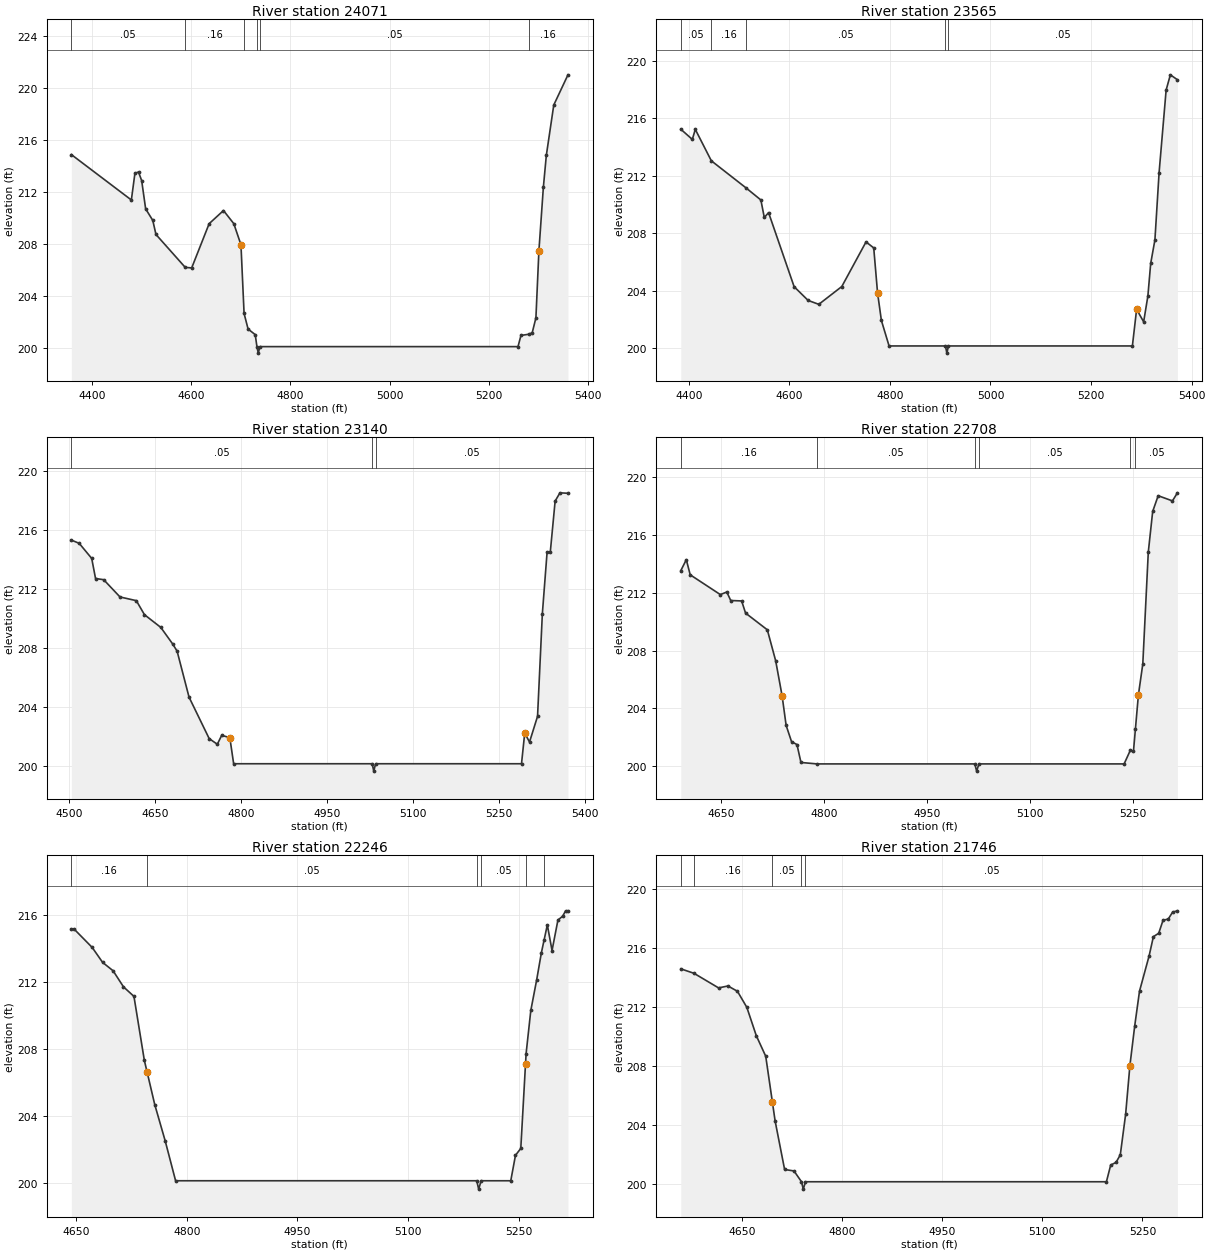
Type RM Length L Ch R = 1 ,24071   ,506,506,506
BEGIN DESCRIPTION:
UNT 168 IN BOCR 52.0
END DESCRIPTION:
XS GIS Cut Line= 3
      3714099.61     10569710.19      3713699.61     10569210.19
      3713399.59     10569010.17
#Sta/Elev= 30
  4358.4   214.9  4479.3  211.41  4486.5  213.46  4493.7  213.56  4500.1   212.9
  4508.1  210.73  4522.5  209.84  4528.9  208.76  4587.9  206.23  4600.9  206.19
  4636.1  209.59    4665   210.6  4685.8  209.59  4700.2  207.97  4706.5  202.69
  4714.6  201.49    4729  201.06  4732.4  200.14  4735.1  199.64  4738.4  200.14
  5258.6  200.14  5264.6     201  5280.2  201.09  5287.2   201.2  5294.7  202.35
  5300.7  207.48  5309.7  212.38  5315.7  214.84  5330.7  218.71  5359.3  221.03
#Mann= 6 ,-1 , 0
  4358.4     .05       0  4587.9     .16       0  4706.5     .05       0
  4732.4    .033       0  4738.4     .05       0  5280.2     .16       0
Bank Sta=4700.2,5300.7
XS Rating Curve= 0 ,0
Exp/Cntr=0.3,0.1

Type RM Length L Ch R = 1 ,23565   ,425,425,425
BEGIN DESCRIPTION:
UNT 168 IN BOCR 51.0
END DESCRIPTION:
XS GIS Cut Line= 3
      3714599.65     10569210.21      3714049.61     10568860.19
       3713899.6     10568560.17
#Sta/Elev= 30
  4384.3  215.24  4407.2  214.53  4413.1  215.23    4445  213.04  4513.7  211.16
  4543.5  210.31  4550.3  209.09  4558.8  209.43  4609.6  204.27  4637.5  203.31
  4658.7  203.04  4704.4  204.28  4752.6  207.39  4767.9  206.97  4775.5  203.84
  4783.1  201.92  4798.4  200.14  4910.5  200.14  4913.3  199.64  4916.5  200.14
  5282.2  200.14  5290.6  202.69  5304.6  201.82    5313  203.62  5318.6  205.89
    5327  207.53  5335.3  212.22  5349.3  217.97  5357.7  219.03  5371.7  218.69
#Mann= 5 ,-1 , 0
  4384.3     .05       0    4445     .16       0  4513.7     .05       0
  4910.5    .033       0  4916.5     .05       0
Bank Sta=4775.5,5290.6
XS Rating Curve= 0 ,0
Exp/Cntr=0.3,0.1

Type RM Length L Ch R = 1 ,23140   ,432,432,432
BEGIN DESCRIPTION:
UNT 168 IN BOCR 50.0
END DESCRIPTION:
XS GIS Cut Line= 3
      3714799.58     10568960.16      3714399.61     10568610.19
       3714249.6     10568310.16
#Sta/Elev= 30
  4504.1  215.29  4517.8  215.07  4539.6  214.05  4546.3  212.69  4560.5  212.61
    4589  211.44  4617.5  211.19  4631.7  210.24  4660.2  209.38  4681.1  208.25
  4688.7  207.77  4709.5  204.66  4744.7  201.85  4758.9  201.47  4766.5  202.07
  4780.7  201.92  4787.4  200.15  5029.2  200.15    5032  199.65  5035.2  200.15
  5289.9  200.15  5295.5  202.22  5303.9  201.62  5317.9  203.36  5326.3  210.31
  5334.6  214.49  5340.2   214.5  5348.6  217.93    5357  218.49    5371  218.46
#Mann= 3 ,-1 , 0
  4504.1     .05       0  5029.2    .033       0  5035.2     .05       0
Bank Sta=4780.7,5295.5
XS Rating Curve= 0 ,0
Exp/Cntr=0.3,0.1

Type RM Length L Ch R = 1 ,22708   ,462,462,462
BEGIN DESCRIPTION:
UNT 168 IN BOCR 49.0
END DESCRIPTION:
XS GIS Cut Line= 3
      3715099.64     10568560.21      3714749.61     10568360.19
      3714549.61     10568110.19
#Sta/Elev= 30
  4591.8  213.54  4599.8   214.3  4605.5  213.25  4649.4  211.88  4658.8  212.06
  4664.5  211.47  4680.4  211.44  4686.1   210.6  4717.8  209.44    4730  207.29
  4739.4  204.85  4745.2  202.82  4753.1  201.69    4761  201.49  4766.8  200.25
  4790.1  200.15    5020  200.15  5022.7  199.65    5026  200.15  5237.5  200.15
  5246.5  201.09  5251.1  201.02  5253.9  202.54  5258.3  204.93  5264.7  207.07
  5272.7  214.82  5279.1  217.64  5287.1  218.73  5307.9  218.37  5315.1  218.93
#Mann= 6 ,-1 , 0
  4591.8     .16       0  4790.1     .05       0    5020    .033       0
    5026     .05       0  5246.5     .08       0  5253.9     .05       0
Bank Sta=4739.4,5258.3
XS Rating Curve= 0 ,0
Exp/Cntr=0.3,0.1

Type RM Length L Ch R = 1 ,22246   ,500,500,500
BEGIN DESCRIPTION:
UNT 168 IN BOCR 48.0
END DESCRIPTION:
XS GIS Cut Line= 3
      3715349.61     10568310.19      3715099.61     10568060.19
      3714849.62      10567860.2
#Sta/Elev= 30
  4643.4  215.19  4646.9  215.19  4671.7  214.08  4685.8  213.19    4700  212.69
  4714.1  211.73  4728.3  211.16  4742.4  207.34  4746.1  206.65  4756.5   204.7
  4770.7  202.53  4784.8  200.15  5193.3  200.15    5196  199.65  5199.3  200.15
  5239.5  200.15  5245.9  201.67  5253.1  202.08  5259.5  207.11  5260.3  207.74
  5266.7  210.32  5274.7  212.16  5281.1  213.78  5284.7  214.52  5289.1  215.43
  5295.5   213.9  5303.5  215.72  5309.9  215.95  5313.9  216.27  5317.1  216.27
#Mann= 6 ,-1 , 0
  4643.4     .16       0  4746.1     .05       0  5193.3    .033       0
  5199.3     .05       0  5259.5     .16       0  5284.7     .05       0
Bank Sta=4746.1,5259.5
XS Rating Curve= 0 ,0
Exp/Cntr=0.3,0.1

Type RM Length L Ch R = 1 ,21746   ,462,462,462
BEGIN DESCRIPTION:
UNT 168 IN BOCR 47.0
END DESCRIPTION:
XS GIS Cut Line= 3
      3715749.61     10568010.19      3715449.61     10567710.19
      3715249.62     10567460.21
#Sta/Elev= 30
  4558.1  214.57  4577.8  214.27  4614.7  213.28  4628.8  213.41    4643  213.05
  4657.1  211.96  4671.2  210.05  4685.4  208.65  4695.3  205.57  4699.5  204.26
  4713.7  200.98  4727.8  200.88    4739  200.15  4741.7  199.65    4745  200.15
  5196.1  200.15  5202.5  201.28  5210.5  201.46  5216.9  201.97  5224.9  204.72
  5231.3  208.02  5238.5   210.7  5245.7  213.06  5260.1  215.45  5266.5  216.75
  5274.5  216.98  5280.9  217.85  5288.9  217.95  5295.3  218.41  5302.5   218.5
#Mann= 5 ,-1 , 0
  4558.1     .05       0  4577.8     .16       0  4695.3     .05       0
    4739    .033       0    4745     .05       0
Bank Sta=4695.3,5231.3
XS Rating Curve= 0 ,0
Exp/Cntr=0.3,0.1

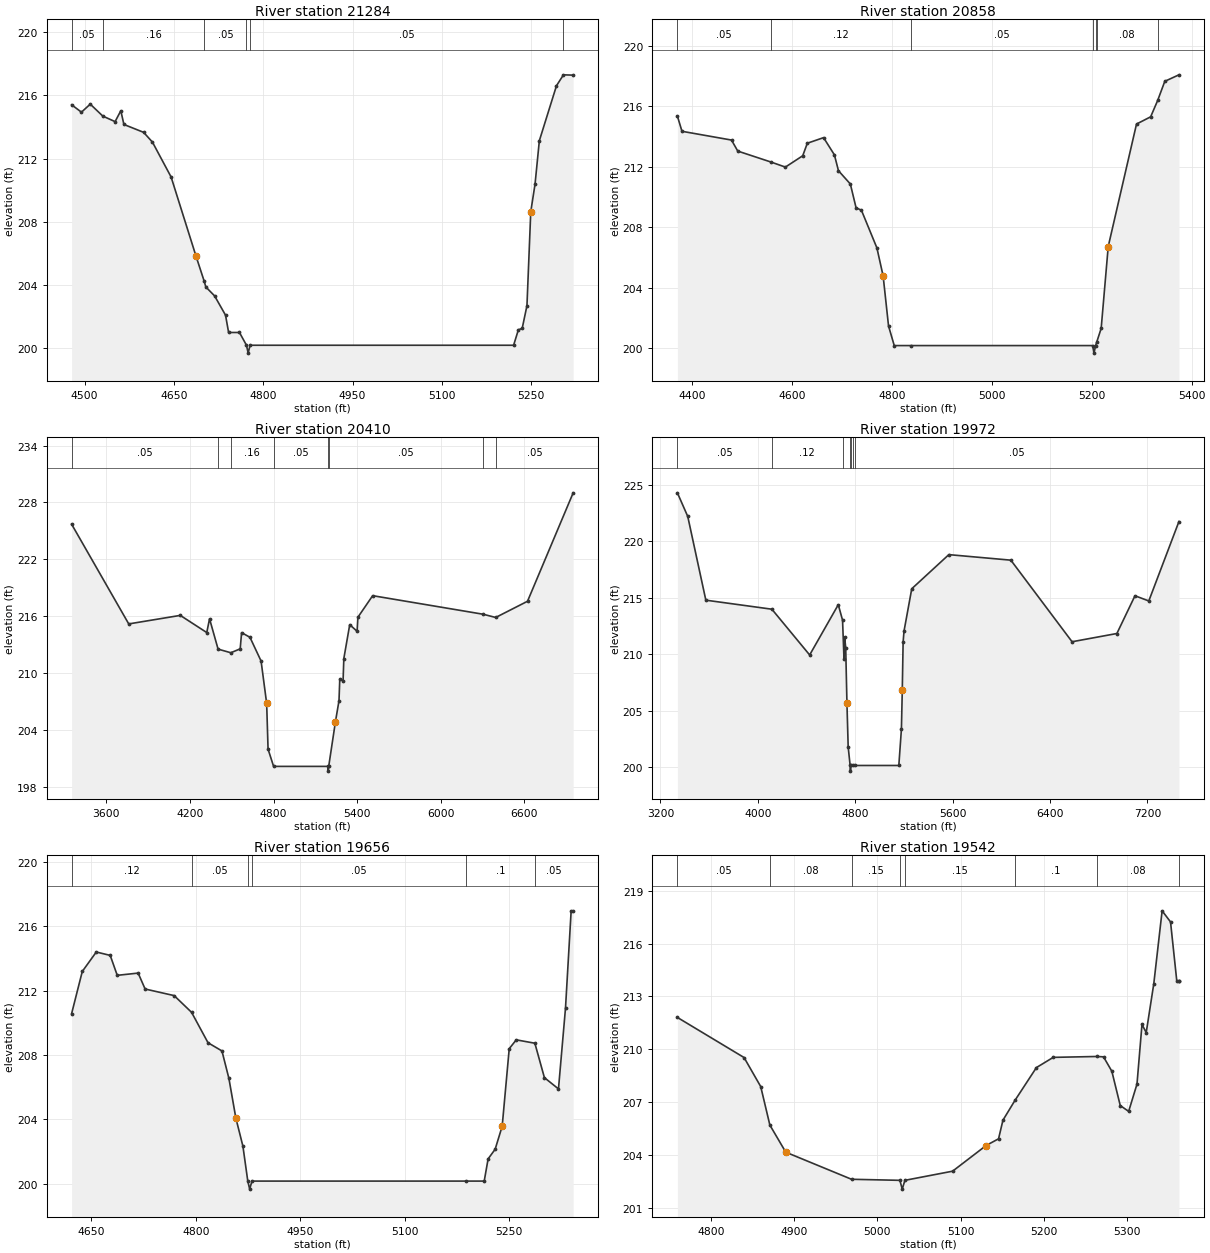
Type RM Length L Ch R = 1 ,21284   ,426,426,426
BEGIN DESCRIPTION:
UNT 168 IN BOCR 46.0
END DESCRIPTION:
XS GIS Cut Line= 3
       3715949.6     10567910.15      3715799.61     10567410.19
      3715549.63     10567210.21
#Sta/Elev= 30
  4478.3  215.41  4494.8  214.94  4509.6  215.45  4530.7  214.69  4551.3  214.34
  4560.9  215.03  4566.1  214.16  4599.2  213.66    4614  213.04  4645.3  210.83
  4687.1  205.81    4701   204.2  4703.6  203.85  4718.4  203.28  4736.7  202.06
  4741.9  200.96  4760.1  200.96  4771.9  200.15  4774.7  199.65  4777.9  200.15
  5220.4  200.15  5228.4  201.13  5234.8  201.22  5242.8  202.66  5249.2  208.62
  5256.4  210.38  5263.6  213.13  5292.4  216.62  5304.1  217.31  5320.4  217.29
#Mann= 6 ,-1 , 0
  4478.3     .05       0  4530.7     .16       0    4701     .05       0
  4771.9    .033       0  4777.9     .05       0  5304.1     .08       0
Bank Sta=4687.1,5249.2
XS Rating Curve= 0 ,0
Exp/Cntr=0.3,0.1

Type RM Length L Ch R = 1 ,20858   ,448,448,448
BEGIN DESCRIPTION:
UNT 168 IN BOCR 45.0
END DESCRIPTION:
XS GIS Cut Line= 3
      3716399.61      10567760.2      3716149.61     10567160.19
      3715899.59     10566910.16
#Sta/Elev= 30
    4371  215.36  4380.2  214.35  4479.3  213.77  4491.8  213.04  4558.7  212.31
  4587.1  211.98  4621.8  212.73    4631  213.56  4663.5  213.93  4685.2  212.79
  4693.3  211.74  4717.1  210.86  4728.5  209.29  4739.3  209.12  4770.2  206.63
  4782.7  204.77  4793.5  201.46  4804.9  200.16  4838.5  200.16  5201.9  200.16
  5204.6  199.66  5207.9  200.16  5209.9  200.37    5219   201.3  5233.1  206.72
  5289.7  214.83    5318  215.31    5332  216.39  5346.3  217.66  5374.6  218.09
#Mann= 7 ,-1 , 0
    4371     .05       0  4558.7     .12       0  4838.5     .05       0
  5201.9    .033       0  5207.9     .05       0  5209.9     .08       0
    5332     .05       0
Bank Sta=4782.7,5233.1
XS Rating Curve= 0 ,0
Exp/Cntr=0.3,0.1

Type RM Length L Ch R = 1 ,20410   ,438,438,438
BEGIN DESCRIPTION:
UNT 168 IN BOCR 44.0
END DESCRIPTION:
XS GIS Cut Line= 3
      3716549.61     10568610.22      3716549.61     10566960.19
      3714749.64      10566210.2
#Sta/Elev= 30
  3350.6  225.71  3760.6  215.19  4130.6  216.09  4320.6  214.28  4340.6  215.73
  4401.9  212.53  4493.3  212.15  4560.6  212.56  4570.6  214.27  4630.6  213.78
  4710.6  211.27  4750.6   206.8  4760.6  201.98  4800.4  200.16  5189.9  200.16
  5192.7  199.66  5195.9  200.16  5244.4  204.89  5269.8  207.09  5275.3  209.34
  5299.1  209.21  5304.5  211.54  5346.8  215.11  5399.8  214.41  5405.3  215.89
  5511.4  218.17  6304.9  216.21  6394.5  215.87  6622.9  217.58  6950.6  229.02
#Mann= 8 ,-1 , 0
  3350.6     .05       0  4401.9     .12       0  4493.3     .16       0
  4800.4     .05       0  5189.9    .033       0  5195.9     .05       0
  6304.9     .08       0  6394.5     .05       0
Bank Sta=4750.6,5244.4
XS Rating Curve= 0 ,0
Exp/Cntr=0.3,0.1

Type RM Length L Ch R = 1 ,19972   ,316,316,316
BEGIN DESCRIPTION:
UNT 168 IN BOCR 43.0
END DESCRIPTION:
XS GIS Cut Line= 3
      3716649.62     10568410.15      3716949.61     10566760.19
      3715149.63     10565110.21
#Sta/Elev= 30
  3339.6  224.29  3424.7   222.2  3573.3  214.79  4115.6  213.99  4425.8  209.94
  4660.9  214.39    4696  213.02  4707.9  209.57    4713  211.54  4721.9  210.57
    4732  205.67  4742.2   201.8  4758.2  200.16    4761  199.66  4764.2  200.16
  4780.6  200.16    4795  200.16  5158.1  200.16  5179.4  203.38  5186.5  206.85
  5193.3  211.07  5200.7  212.05  5264.2   215.8  5568.8  218.82  6078.1  218.33
  6580.7  211.11  6948.8  211.84  7097.4  215.18  7210.9  214.72  7458.4  221.75
#Mann= 7 ,-1 , 0
  3339.6     .05       0  4115.6     .12       0    4696     .07       0
  4758.2    .033       0  4764.2     .07       0  4780.6     .12       0
    4795     .05       0
Bank Sta=4732,5186.5
XS Rating Curve= 0 ,0
Exp/Cntr=0.3,0.1

Type RM Length L Ch R = 1 ,19656   ,114,114,114
BEGIN DESCRIPTION:
Mapping XS 89d39d4b
END DESCRIPTION:
XS GIS Cut Line= 3
      3717274.36     10567065.49      3717243.98     10566618.42
      3717283.04     10566349.35
#Sta/Elev= 30
  4621.8  210.57  4637.1  213.19  4657.2   214.4  4677.2  214.19  4687.3  212.95
  4717.3  213.09  4727.3   212.1    4769  211.69    4794  210.65  4817.6  208.76
  4837.6  208.25  4847.6  206.54  4857.6  204.07  4867.7  202.33  4874.7  200.16
  4877.4  199.66  4880.7  200.16  5188.3  200.16  5214.1  200.16  5219.7  201.54
  5229.8  202.14  5239.9  203.57    5250  208.39  5260.1  208.94  5286.8  208.73
  5300.5  206.59  5320.7  205.89  5330.8  210.92  5338.9  216.96  5341.8  216.96
#Mann= 6 ,-1 , 0
  4621.8     .12       0    4794     .05       0  4874.7    .033       0
  4880.7     .05       0  5188.3      .1       0  5286.8     .05       0
Bank Sta=4857.6,5239.9
XS Rating Curve= 0 ,0
Exp/Cntr=0.3,0.1

Type RM Length L Ch R = 1 ,19542   ,82,82,82
BEGIN DESCRIPTION:
UNT 168 IN BOCR 42.0
END DESCRIPTION:
XS GIS Cut Line= 3
      3717349.61     10566910.21      3717362.47     10566630.14
      3717399.61     10566310.15
#Sta/Elev= 30
  4759.7  211.81  4839.8  209.53  4859.8  207.88  4870.8  205.69  4889.9  204.15
  4968.9  202.61    5027  202.55  5029.8  202.05    5033  202.55  5090.3  203.07
  5130.6  204.53  5145.5  204.91  5150.8  205.97  5165.3   207.1    5191  208.96
  5211.2  209.54  5263.6  209.59  5271.6  209.57  5281.6  208.75  5291.7   206.8
  5301.8  206.47  5311.8  208.02  5317.8  211.41  5322.9  210.95    5332  213.73
    5342  217.87  5352.1  217.24  5359.6  213.89  5361.9  213.89  5362.2  213.89
#Mann= 8 ,-1 , 0
  4759.7     .05       0  4870.8     .08       0  4968.9     .15       0
    5027     .07       0    5033     .15       0  5165.3      .1       0
  5263.6     .08       0  5361.9     .05       0
Bank Sta=4889.9,5130.6
XS Rating Curve= 0 ,0
Exp/Cntr=0.3,0.1

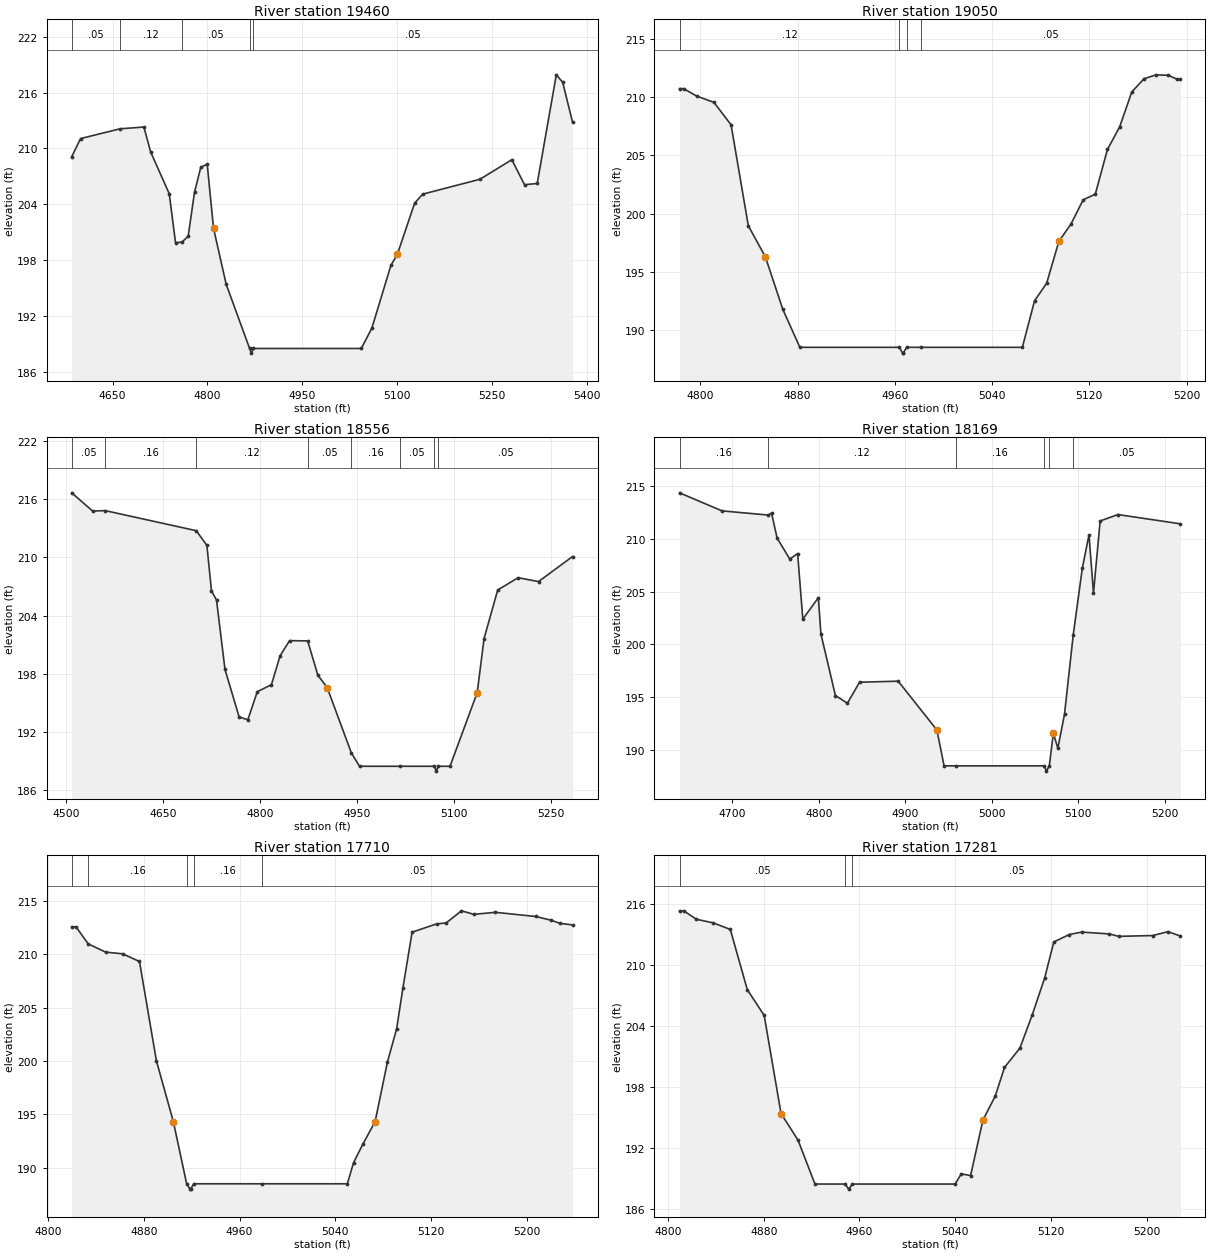
Type RM Length L Ch R = 1 ,19460   ,410,410,410
BEGIN DESCRIPTION:
Mapping XS b5b03bb1
END DESCRIPTION:
XS GIS Cut Line= 3
      3717417.59     10567074.18      3717443.63      10566627.1
      3717482.64     10566284.66
#Sta/Elev= 30
  4585.4   209.1  4599.4  211.05  4661.8   212.1  4699.6  212.29  4710.4   209.6
  4739.7  205.13  4749.7  199.86  4759.8  199.93  4769.7  200.55  4779.7  205.28
  4789.7  207.98  4799.8  208.29  4809.8  201.41  4829.8   195.4  4866.9   188.5
  4869.6     188  4872.9   188.5  5043.6   188.5  5060.3  190.68  5090.5  197.43
  5100.6   198.6    5128  204.11  5140.8  205.08  5231.4  206.68  5281.8  208.78
  5301.9  206.09    5322  206.23  5352.2   217.9  5362.3   217.1  5377.9   212.8
#Mann= 5 ,-1 , 0
  4585.4     .05       0  4661.8     .12       0  4759.8     .05       0
  4866.9     .03       0  4872.9     .05       0
Bank Sta=4809.8,5100.6
XS Rating Curve= 0 ,0
Exp/Cntr=0.3,0.1

Type RM Length L Ch R = 1 ,19050   ,494,494,494
BEGIN DESCRIPTION:
UNT 168 IN BOCR 41.0
END DESCRIPTION:
XS GIS Cut Line= 3
      3717699.61     10566860.19      3717849.61     10566710.19
      3717849.61     10566510.22
#Sta/Elev= 29
  4782.8  210.75  4786.3  210.75  4796.9  210.11  4811.1  209.57  4825.2  207.64
  4839.4  198.95  4853.5  196.26  4867.7  191.78  4881.8  188.49  4963.6  188.49
  4966.4  187.99  4966.9  187.99  4969.6  188.49  4981.3  188.49  5064.9  188.49
  5074.9  192.49  5084.9  194.01  5094.9   197.6  5104.9   199.1  5114.9  201.18
  5124.9  201.67  5134.9  205.52  5144.9  207.45  5154.9  210.46  5164.9   211.6
  5174.9  211.94  5184.9   211.9  5192.4  211.55  5194.9  211.55
#Mann= 4 ,-1 , 0
  4782.8     .12       0  4963.6    .033       0  4969.6     .12       0
  4981.3     .05       0
Bank Sta=4853.5,5094.9
XS Rating Curve= 0 ,0
Exp/Cntr=0.3,0.1

Type RM Length L Ch R = 1 ,18556   ,387,387,387
BEGIN DESCRIPTION:
UNT 168 IN BOCR 40.0
END DESCRIPTION:
XS GIS Cut Line= 4
      3717949.82     10567256.39      3718106.44     10567101.09
      3718249.61     10566910.19       3718549.6     10566810.19
#Sta/Elev= 30
  4508.1  216.65  4540.6  214.77  4559.7  214.82    4701  212.75  4717.4  211.23
  4724.5  206.55  4732.3  205.61  4745.4  198.46  4767.3  193.57  4780.8  193.28
  4795.4  196.17  4817.3  196.89  4830.8  199.88  4845.4  201.43  4873.4   201.4
  4889.2  197.87  4903.7  196.58    4941  189.87  4953.7  188.49  5015.8  188.49
  5069.7  188.49  5072.4  187.99  5075.7  188.49  5093.8  188.49  5135.9  196.08
  5146.5  201.64  5167.6  206.64  5199.2  207.91  5230.8  207.51  5283.5  210.09
#Mann= 8 ,-1 , 0
  4508.1     .05       0  4559.7     .16       0    4701     .12       0
  4873.4     .05       0    4941     .16       0  5015.8     .05       0
  5069.7     .07       0  5075.7     .05       0
Bank Sta=4903.7,5135.9
XS Rating Curve= 0 ,0
Exp/Cntr=0.3,0.1

Type RM Length L Ch R = 1 ,18169   ,459,459,459
BEGIN DESCRIPTION:
UNT 168 IN BOCR 39.0
END DESCRIPTION:
XS GIS Cut Line= 4
      3718175.09     10567393.11      3718309.51     10567305.24
      3718499.61     10567210.19      3718699.62     10567260.19
#Sta/Elev= 30
  4638.8  214.38  4687.9  212.67  4741.6  212.27  4745.2  212.47  4751.7  210.08
  4766.3   208.1  4775.4  208.62  4781.4   202.4  4799.4  204.44  4802.3  201.01
  4819.1  195.16    4833  194.43    4847  196.42  4891.7  196.52  4936.5  191.89
  4944.8  188.49  4958.8  188.49  5060.5  188.49  5063.2  187.99  5066.5  188.49
  5071.2  191.57  5076.4  190.16  5084.1  193.39  5094.2  200.92  5104.7  207.24
  5112.4   210.4  5117.6  204.87  5125.3  211.71  5145.9  212.32  5218.1  211.44
#Mann= 6 ,-1 , 0
  4638.8     .16       0  4741.6     .12       0  4958.8     .16       0
  5060.5     .07       0  5066.5     .16       0  5094.2     .05       0
Bank Sta=4936.5,5071.2
XS Rating Curve= 0 ,0
Exp/Cntr=0.3,0.1

Type RM Length L Ch R = 1 ,17710   ,429,429,429
BEGIN DESCRIPTION:
UNT 168 IN BOCR 38.0
END DESCRIPTION:
XS GIS Cut Line= 3
      3718549.59     10567760.21      3718699.61     10567610.19
      3718899.59     10567560.19
#Sta/Elev= 30
  4819.8  212.58  4823.4  212.58  4833.6  210.98  4848.1  210.21  4862.3  210.05
  4876.4  209.33  4890.5  200.04  4904.7  194.31  4915.8  188.49  4918.6  187.99
  4919.1  187.99  4921.8  188.49  4979.1  188.49    5050  188.49  5055.2  190.47
  5062.9  192.19  5073.2  194.32  5083.5  199.91  5091.2  203.03  5096.4  206.84
  5104.1  212.08  5124.7  212.86  5132.5  212.94  5145.3  214.08  5155.7  213.75
  5173.7  213.94  5207.2  213.55  5220.1   213.2  5227.8   212.9  5238.1  212.76
#Mann= 5 ,-1 , 0
  4819.8     .05       0  4833.6     .16       0  4915.8    .033       0
  4921.8     .16       0  4979.1     .05       0
Bank Sta=4904.7,5073.2
XS Rating Curve= 0 ,0
Exp/Cntr=0.3,0.1

Type RM Length L Ch R = 1 ,17281   ,407,407,407
BEGIN DESCRIPTION:
UNT 168 IN BOCR 37.0
END DESCRIPTION:
XS GIS Cut Line= 3
      3718799.61     10568110.19      3718949.61     10567960.19
      3718999.61     10567760.17
#Sta/Elev= 30
  4809.7  215.34  4813.2  215.34  4823.8  214.51    4838  214.15  4852.1  213.51
  4866.3  207.59  4880.4  205.06  4894.5  195.41  4908.7  192.79  4922.8  188.48
  4948.1  188.48  4950.9  187.98  4954.1  188.48  5039.9  188.48    5045  189.48
  5052.8  189.31  5063.1  194.77  5073.4  197.13  5081.1  199.94    5094  201.85
  5104.3  205.12  5114.6  208.71  5122.3  212.28  5135.2  213.01  5145.5  213.25
  5168.7  213.07  5176.4  212.83  5204.8  212.91  5217.7  213.29    5228  212.86
#Mann= 3 ,-1 , 0
  4809.7     .05       0  4948.1    .033       0  4954.1     .05       0
Bank Sta=4894.5,5063.1
XS Rating Curve= 0 ,0
Exp/Cntr=0.3,0.1

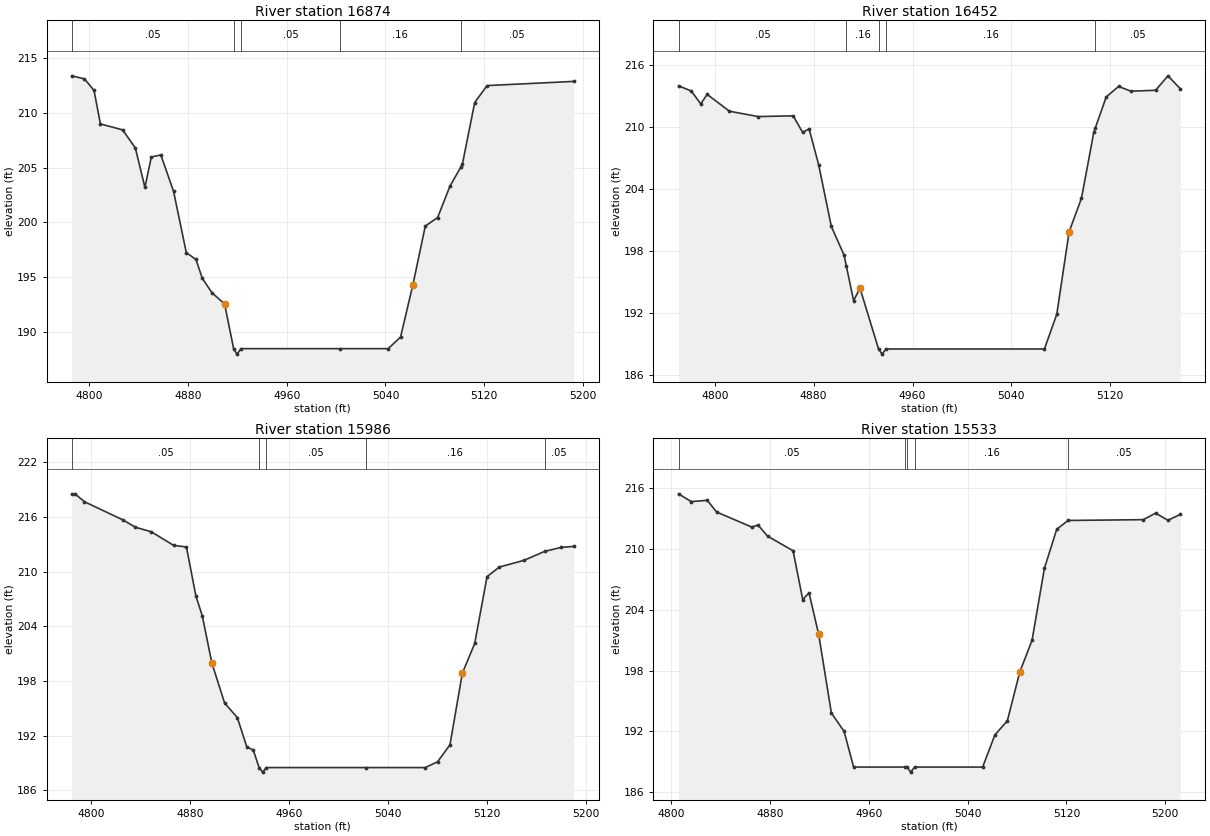
Type RM Length L Ch R = 1 ,16874   ,422,422,422
BEGIN DESCRIPTION:
UNT 168 IN BOCR 36.0
END DESCRIPTION:
XS GIS Cut Line= 3
      3719249.61     10568360.16      3719299.61     10568160.19
      3719299.61     10567960.22
#Sta/Elev= 30
  4786.1  213.37  4796.4  213.09  4804.1  212.04  4809.3  208.98  4827.3  208.44
  4837.6  206.78  4845.3  203.19  4850.5  205.97  4858.2  206.15  4868.5  202.83
  4878.8  197.24  4886.6  196.62  4891.7  194.91  4899.5  193.59  4909.8  192.55
  4917.1  188.48  4919.8  187.98  4923.1  188.48  5002.9  188.48  5042.2  188.48
  5052.2  189.54  5062.2  194.31  5072.2  199.66  5082.2  200.44  5092.2  203.31
    5101  205.05  5102.2  205.29  5112.2  210.93  5122.2  212.48  5192.2  212.86
#Mann= 5 ,-1 , 0
  4786.1     .05       0  4917.1    .033       0  4923.1     .05       0
  5002.9     .16       0    5101     .05       0
Bank Sta=4909.8,5062.2
XS Rating Curve= 0 ,0
Exp/Cntr=0.3,0.1

Type RM Length L Ch R = 1 ,16452   ,466,466,466
BEGIN DESCRIPTION:
UNT 168 IN BOCR 35.0
END DESCRIPTION:
XS GIS Cut Line= 3
      3719749.61     10568510.19      3719699.61     10568310.19
      3719699.61     10568110.14
#Sta/Elev= 30
  4770.6  213.99  4780.9  213.49  4788.6  212.24  4793.8  213.16  4811.8  211.53
    4835  211.01  4863.4  211.08  4871.1  209.47  4876.3  209.82    4884  206.35
  4894.3  200.36  4904.6  197.58  4906.5  196.49  4912.3  193.17  4917.5  194.37
  4932.5  188.48  4935.3  187.98  4938.5  188.48  5066.8  188.48  5076.8  191.85
  5086.8  199.85  5096.8   203.1  5106.8  209.51  5108.1  209.95  5116.8  212.91
  5126.8  213.93  5136.8  213.47  5156.8  213.56  5166.8  214.96  5176.8   213.7
#Mann= 5 ,-1 , 0
  4770.6     .05       0  4906.5     .16       0  4932.5     .07       0
  4938.5     .16       0  5108.1     .05       0
Bank Sta=4917.5,5086.8
XS Rating Curve= 0 ,0
Exp/Cntr=0.3,0.1

Type RM Length L Ch R = 1 ,15986   ,453,453,453
BEGIN DESCRIPTION:
UNT 168 IN BOCR 34.0
END DESCRIPTION:
XS GIS Cut Line= 3
      3720099.61     10568610.17      3720149.61     10568410.19
      3720149.61     10568210.23
#Sta/Elev= 30
  4784.2  218.55  4786.8  218.55  4794.5  217.68  4825.4   215.7  4835.7  214.88
  4848.6  214.38  4866.6  212.89    4877  212.71  4884.7  207.31  4889.8  205.17
  4897.6  199.96  4907.9  195.57  4918.2  193.97  4925.9  190.74  4931.1  190.41
  4935.8  188.48  4938.6  187.98  4941.8  188.48    5022  188.48  5070.3  188.48
  5080.3  189.12  5090.3  190.99  5100.3  198.85  5110.3  202.11  5120.3  209.46
  5130.3  210.51  5150.3  211.25  5166.8  212.22  5180.3  212.67  5190.3  212.77
#Mann= 5 ,-1 , 0
  4784.2     .05       0  4935.8     .03       0  4941.8     .05       0
    5022     .16       0  5166.8     .05       0
Bank Sta=4897.6,5100.3
XS Rating Curve= 0 ,0
Exp/Cntr=0.3,0.1

Type RM Length L Ch R = 1 ,15533   ,464,464,464
BEGIN DESCRIPTION:
UNT 168 IN BOCR 33.0
END DESCRIPTION:
XS GIS Cut Line= 3
      3720549.61     10568660.17      3720599.61     10568460.19
      3720599.61     10568260.22
#Sta/Elev= 30
  4806.1  215.46  4816.4  214.69  4829.3  214.82    4837  213.66  4865.3  212.18
  4870.5  212.37  4878.2  211.28  4898.8  209.84  4906.6  205.02  4911.7  205.68
  4919.5  201.59  4929.8  193.82  4940.1     192  4947.8  188.48    4989  188.48
  4991.2  188.48  4993.9  187.98  4997.2  188.48  5052.2  188.48  5062.2  191.67
  5072.2  193.04  5082.2  197.84  5092.2     201  5102.2   208.1  5112.2  211.97
  5121.4  212.83  5182.2  212.91  5192.2  213.55  5202.2  212.85  5212.2  213.43
#Mann= 5 ,-1 , 0
  4806.1     .05       0    4989     .16       0  4991.2     .07       0
  4997.2     .16       0  5121.4     .05       0
Bank Sta=4919.5,5082.2
XS Rating Curve= 0 ,0
Exp/Cntr=0.3,0.1