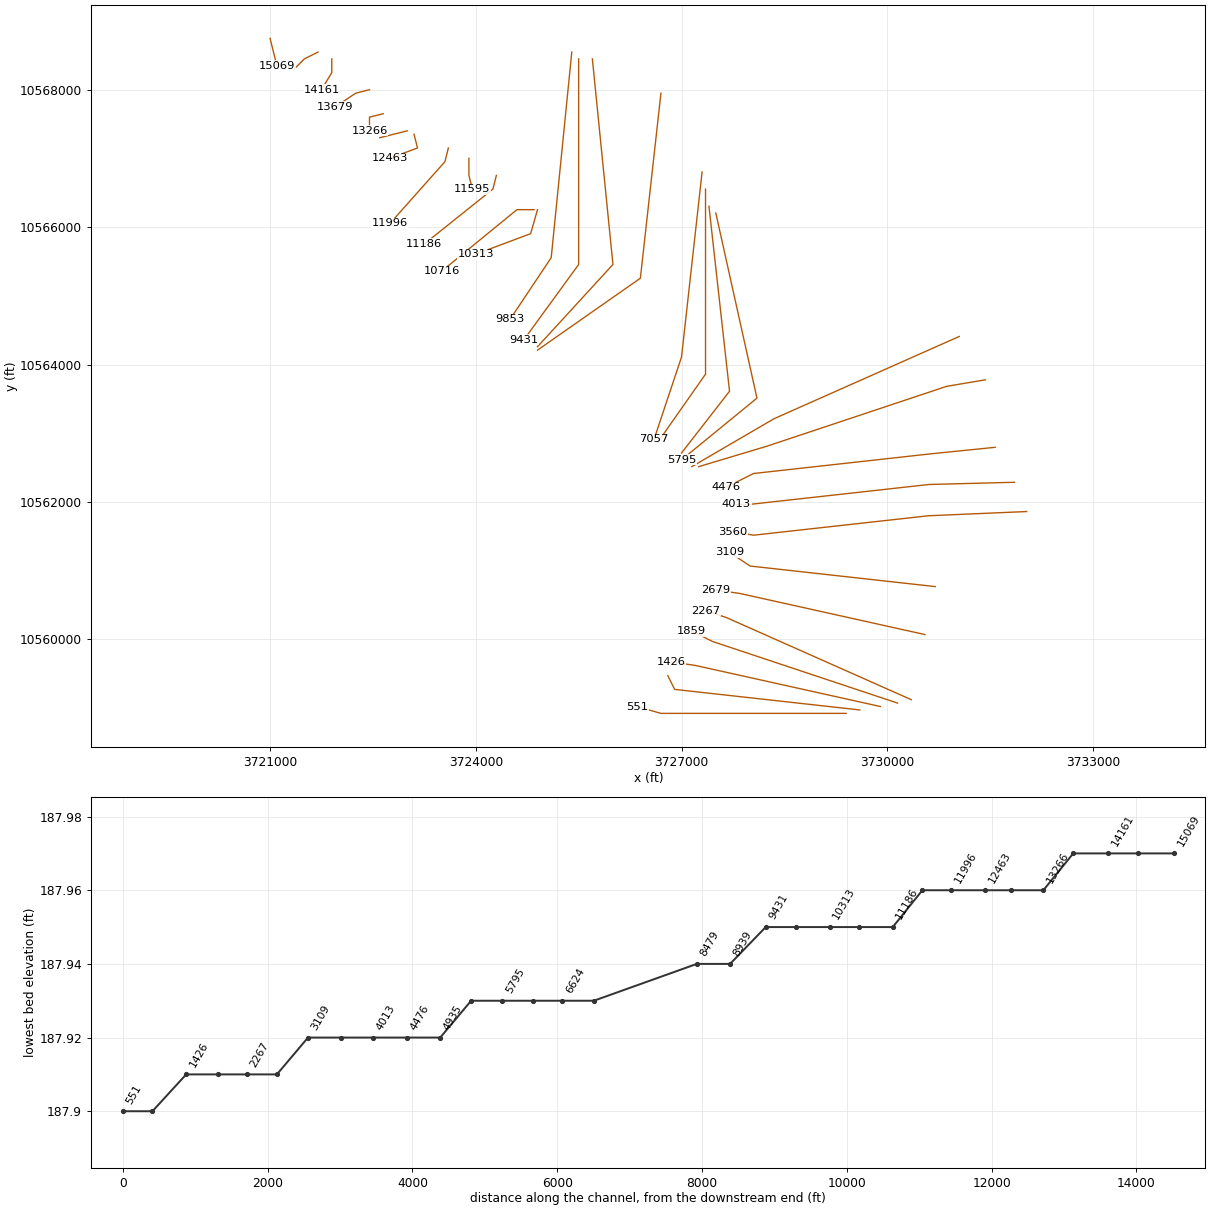
HEC-RAS study UNT 168 IN BOCR.prj: UNT 168 IN BOCR Base Level Engineering

--- UNT 168 IN BOCR.g01 (geometry) --- (continued)

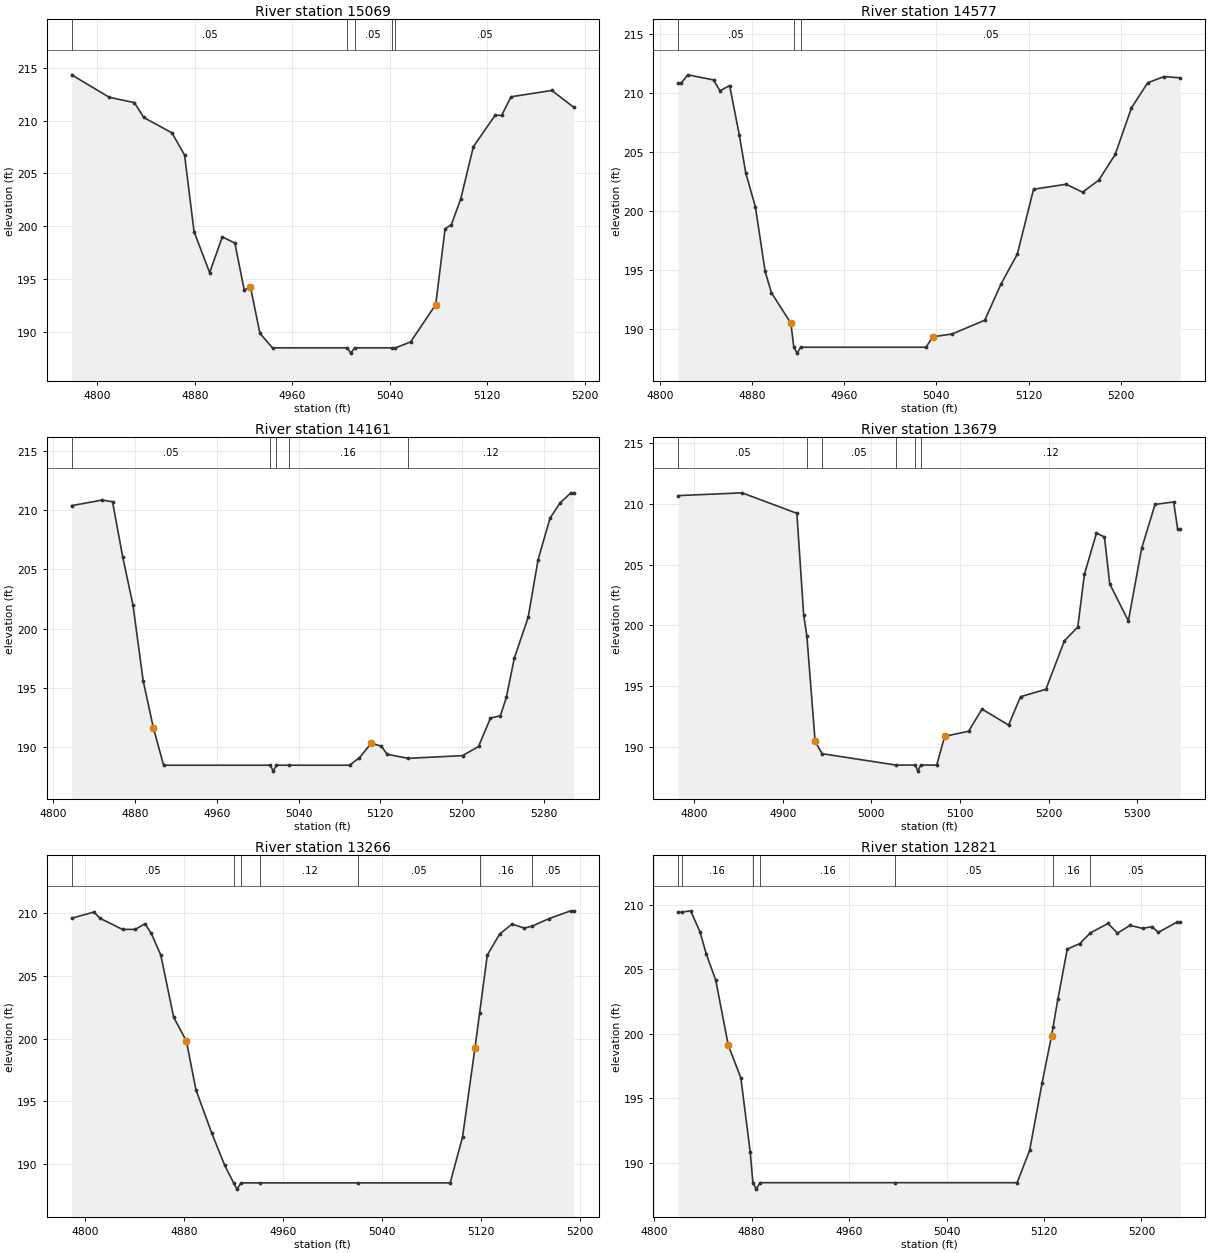
Type RM Length L Ch R = 1 ,15069   ,492,492,492
BEGIN DESCRIPTION:
UNT 168 IN BOCR 32.0
END DESCRIPTION:
XS GIS Cut Line= 3
      3720999.62     10568760.15      3721049.61     10568560.19
      3721099.62     10568360.16
#Sta/Elev= 30
  4778.9  214.33  4809.8   212.2  4830.4   211.7  4838.1  210.29  4861.3  208.83
  4871.6  206.73  4879.4  199.48  4892.2  195.59  4902.6  198.98  4912.9  198.39
  4920.6  193.94  4925.7  194.23  4933.5  189.84  4943.8  188.47  5005.2  188.47
    5008  187.97  5011.2  188.47  5041.8  188.47  5044.7  188.47  5057.2  189.03
  5077.8  192.57  5085.5  199.74  5090.7  200.15  5098.4   202.6  5108.7  207.52
  5126.7  210.52  5131.9  210.48  5139.6  212.25  5173.1  212.85  5191.2  211.25
#Mann= 5 ,-1 , 0
  4778.9     .05       0  5005.2     .03       0  5011.2     .05       0
  5041.8     .16       0  5044.7     .05       0
Bank Sta=4925.7,5077.8
XS Rating Curve= 0 ,0
Exp/Cntr=0.3,0.1

Type RM Length L Ch R = 1 ,14577   ,416,416,416
BEGIN DESCRIPTION:
UNT 168 IN BOCR 31.0
END DESCRIPTION:
XS GIS Cut Line= 3
      3721699.59     10568560.18      3721499.61     10568460.19
      3721349.62      10568310.2
#Sta/Elev= 30
  4815.9  210.84  4818.7  210.84  4824.3  211.52  4846.6  211.09  4852.2  210.17
  4860.6  210.61    4869  206.42  4874.6  203.21    4883  200.32  4891.4  194.88
  4896.9  193.07  4913.7  190.51  4916.3  188.47  4919.1  187.97  4922.3  188.47
  5031.1  188.47  5036.7  189.35  5053.6  189.59  5081.9  190.75  5096.1  193.83
  5110.2  196.35  5124.3  201.84  5152.6  202.26  5166.8  201.59  5180.9  202.61
  5195.1  204.78  5209.2  208.72  5223.3  210.85  5237.5  211.37  5251.6  211.27
#Mann= 3 ,-1 , 0
  4815.9     .05       0  4916.3     .03       0  4922.3     .05       0
Bank Sta=4913.7,5036.7
XS Rating Curve= 0 ,0
Exp/Cntr=0.3,0.1

Type RM Length L Ch R = 1 ,14161   ,482,482,482
BEGIN DESCRIPTION:
UNT 168 IN BOCR 30.0
END DESCRIPTION:
XS GIS Cut Line= 3
      3721899.61     10568460.23      3721899.61     10568260.19
       3721749.6     10568010.18
#Sta/Elev= 30
  4817.9  210.39  4847.9  210.86  4857.9  210.72  4867.9  206.05  4877.9  202.01
  4887.9  195.61  4897.9  191.63  4907.9  188.47  5012.4  188.47  5015.2  187.97
  5018.4  188.47  5030.2  188.47  5089.9  188.47  5099.6   189.1  5111.2  190.33
    5121  190.08  5126.8  189.39  5147.3  189.05  5200.6  189.28  5216.2  190.05
  5227.9  192.45  5237.6  192.65  5243.4  194.19  5251.2   197.5  5264.8  200.96
  5274.5  205.83  5286.2  209.33  5295.9  210.61  5306.6  211.47  5309.5  211.47
#Mann= 5 ,-1 , 0
  4817.9     .05       0  5012.4    .033       0  5018.4     .05       0
  5030.2     .16       0  5147.3     .12       0
Bank Sta=4897.9,5111.2
XS Rating Curve= 0 ,0
Exp/Cntr=0.3,0.1

Type RM Length L Ch R = 1 ,13679   ,413,413,413
BEGIN DESCRIPTION:
UNT 168 IN BOCR 29.0
END DESCRIPTION:
XS GIS Cut Line= 3
       3722449.6     10568010.19      3722249.61     10567960.19
      3721949.61     10567760.19
#Sta/Elev= 30
  4781.9   210.7    4854  210.93  4915.9  209.24  4923.6  200.84  4927.2  199.11
  4936.5  190.43  4944.3  189.41  5027.7  188.47  5049.6  188.47  5052.4  187.97
  5055.6  188.47  5073.7  188.47  5082.7  190.84  5109.7  191.26  5124.8  193.09
  5154.8  191.77  5168.3  194.11  5196.9  194.72  5217.9  198.73  5232.9  199.86
  5240.4  204.21    5254  207.61    5263  207.29    5269  203.41    5290  200.36
    5305  206.36  5320.1  209.97  5341.1  210.18  5345.6  207.95  5348.6  207.95
#Mann= 6 ,-1 , 0
  4781.9     .05       0  4927.2     .12       0  4944.3     .05       0
  5027.7     .12       0  5049.6    .033       0  5055.6     .12       0
Bank Sta=4936.5,5082.7
XS Rating Curve= 0 ,0
Exp/Cntr=0.3,0.1

Type RM Length L Ch R = 1 ,13266   ,445,445,445
BEGIN DESCRIPTION:
UNT 168 IN BOCR 28.0
END DESCRIPTION:
XS GIS Cut Line= 3
       3722649.6     10567660.19      3722449.61     10567610.19
      3722449.61     10567410.24
#Sta/Elev= 30
  4789.1  209.62  4807.1  210.11  4812.3   209.6  4830.3  208.72  4840.6  208.73
  4848.4  209.18  4853.5   208.4  4861.2  206.67  4871.6   201.7  4881.9   199.8
  4889.6   195.9  4902.5  192.41  4912.8  189.88  4920.1  188.46  4922.8  187.96
  4926.1  188.46  4941.8  188.46  5020.9  188.46  5095.2  188.46  5105.2  192.13
  5115.2  199.21    5119  202.04  5125.2  206.67  5135.2  208.35  5145.2  209.15
  5155.2  208.83  5161.3  208.98  5175.2  209.59  5192.7  210.21  5195.2  210.21
#Mann= 7 ,-1 , 0
  4789.1     .05       0  4920.1     .07       0  4926.1     .05       0
  4941.8     .12       0  5020.9     .05       0    5119     .16       0
  5161.3     .05       0
Bank Sta=4881.9,5115.2
XS Rating Curve= 0 ,0
Exp/Cntr=0.3,0.1

Type RM Length L Ch R = 1 ,12821   ,358,358,358
BEGIN DESCRIPTION:
UNT 168 IN BOCR 27.0
END DESCRIPTION:
XS GIS Cut Line= 3
      3722999.56     10567410.18      3722799.61     10567360.19
      3722599.57     10567310.18
#Sta/Elev= 30
  4819.6  209.44  4822.5  209.45  4829.9  209.55  4837.6  207.91  4842.7   206.2
  4850.5  204.17  4860.8  199.12  4871.1  196.59  4878.8  190.83    4881  188.46
  4883.7  187.96    4887  188.46  4997.9  188.46  5097.9  188.46  5108.2  190.97
  5118.5  196.23  5126.2  199.86  5127.4  200.52  5131.4  202.71  5139.1  206.58
  5149.4  207.01  5158.1  207.84  5172.6  208.57  5180.3  207.82  5190.6  208.42
  5200.9  208.19  5208.7  208.32  5213.8  207.88  5229.3  208.68  5231.9  208.68
#Mann= 7 ,-1 , 0
  4819.6     .05       0  4822.5     .16       0    4881     .03       0
    4887     .16       0  4997.9     .05       0  5127.4     .16       0
  5158.1     .05       0
Bank Sta=4860.8,5126.2
XS Rating Curve= 0 ,0
Exp/Cntr=0.3,0.1

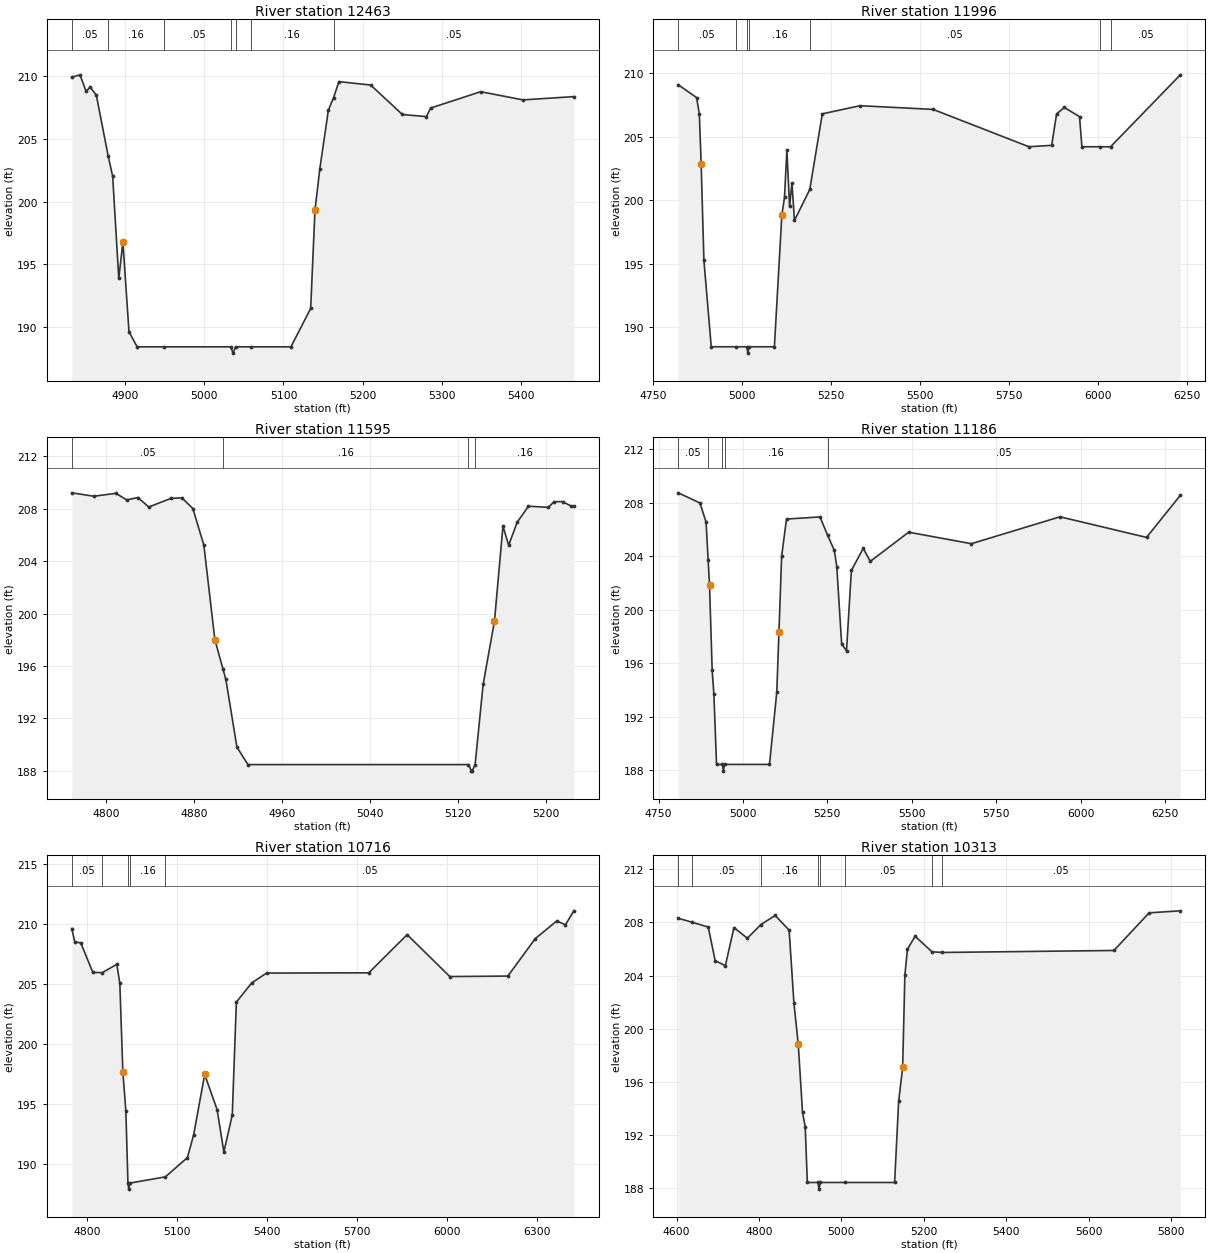
Type RM Length L Ch R = 1 ,12463   ,467,467,467
BEGIN DESCRIPTION:
UNT 168 IN BOCR 26.0
END DESCRIPTION:
XS GIS Cut Line= 3
       3723099.6     10567360.23      3723149.61     10567160.19
      3722749.61     10567010.19
#Sta/Elev= 30
  4832.9  209.87  4843.3  210.06    4851  208.74  4856.1  209.09  4863.9  208.44
  4878.7  203.65  4884.5     202  4892.2  193.89  4897.4  196.77  4905.1  189.65
  4915.4  188.46  4949.6  188.46  5033.5  188.46  5036.3  187.96  5039.5  188.46
  5058.4  188.46  5109.4  188.46  5134.3  191.51  5139.7   199.3  5145.9  202.62
  5156.6  207.25  5163.2  208.25  5169.9  209.52    5210  209.25    5250  206.91
  5280.3  206.74  5285.6  207.42  5348.8  208.72  5402.2  208.07  5466.3  208.33
#Mann= 7 ,-1 , 0
  4832.9     .05       0  4878.7     .16       0  4949.6     .05       0
  5033.5     .03       0  5039.5     .05       0  5058.4     .16       0
  5163.2     .05       0
Bank Sta=4897.4,5139.7
XS Rating Curve= 0 ,0
Exp/Cntr=0.3,0.1

Type RM Length L Ch R = 1 ,11996   ,401,401,401
BEGIN DESCRIPTION:
UNT 168 IN BOCR 25.0
END DESCRIPTION:
XS GIS Cut Line= 3
       3723599.6     10567160.16      3723549.61     10566960.19
       3722749.6     10566060.18
#Sta/Elev= 30
  4820.2  209.08  4871.7  208.07  4879.4   206.8  4884.6  202.85  4892.3  195.27
  4912.9  188.46  4982.1  188.46    5013  188.46  5015.8  187.96    5019  188.46
  5090.3  188.46  5111.2  198.81  5118.7  200.22  5125.4  203.95  5132.9  199.53
  5139.6  201.35  5146.7   198.4  5189.7  200.84  5224.9  206.79  5331.1  207.43
    5536  207.14  5805.3   204.2  5869.2  204.31    5883  206.79  5904.8  207.29
  5947.4  206.57  5954.1   204.2  6005.1   204.2  6034.6   204.2  6230.5  209.86
#Mann= 7 ,-1 , 0
  4820.2     .05       0  4982.1     .16       0    5013     .07       0
    5019     .16       0  5189.7     .05       0  6005.1     .07       0
  6034.6     .05       0
Bank Sta=4884.6,5111.2
XS Rating Curve= 0 ,0
Exp/Cntr=0.3,0.1

Type RM Length L Ch R = 1 ,11595   ,409,409,409
BEGIN DESCRIPTION:
UNT 168 IN BOCR 24.0
END DESCRIPTION:
XS GIS Cut Line= 3
      3723899.61     10567010.16      3723899.61     10566760.19
       3723949.6     10566560.22
#Sta/Elev= 30
  4768.9  209.22  4788.9  208.96  4808.9  209.18  4818.9  208.68  4828.9  208.86
  4838.9  208.14  4858.9  208.79  4868.9  208.84  4878.9  208.02  4888.9  205.22
  4898.9     198  4906.3  195.75  4908.9  194.96  4918.9   189.8  4928.9  188.46
  5129.3  188.46    5132  187.96  5132.5  187.96  5135.3  188.46  5142.6  194.59
  5152.9  199.42  5160.6  206.68  5165.8  205.22  5173.5  206.97  5183.8   208.2
  5201.8  208.11    5207  208.54  5214.7  208.55  5222.5  208.21    5225  208.21
#Mann= 4 ,-1 , 0
  4768.9     .05       0  4906.3     .16       0  5129.3     .07       0
  5135.3     .16       0
Bank Sta=4898.9,5152.9
XS Rating Curve= 0 ,0
Exp/Cntr=0.3,0.1

Type RM Length L Ch R = 1 ,11186   ,470,470,470
BEGIN DESCRIPTION:
UNT 168 IN BOCR 23.0
END DESCRIPTION:
XS GIS Cut Line= 3
       3724299.6     10566760.17      3724249.61     10566560.19
      3723249.58     10565760.16
#Sta/Elev= 30
  4808.4  208.74  4872.8  207.98  4890.8  206.55    4897   203.7  4901.1  201.82
  4908.9  195.47    4914  193.69  4921.8  188.45  4939.4  188.45  4942.1  187.95
  4945.4  188.45  5078.6  188.45  5100.2  193.84  5106.6  198.31  5114.6  204.01
    5129  206.78  5228.2  206.94  5250.7  205.57  5270.7  204.44  5277.9  203.22
  5292.3  197.46  5306.7  196.94  5321.1  202.94  5356.3  204.59  5377.1  203.62
  5490.8   205.8  5676.5  204.94    5939  206.95  6195.1  205.41  6295.2  208.55
#Mann= 5 ,-1 , 0
  4808.4     .05       0    4897     .16       0  4939.4     .07       0
  4945.4     .16       0  5250.7     .05       0
Bank Sta=4901.1,5106.6
XS Rating Curve= 0 ,0
Exp/Cntr=0.3,0.1

Type RM Length L Ch R = 1 ,10716   ,403,403,403
BEGIN DESCRIPTION:
UNT 168 IN BOCR 22.0
END DESCRIPTION:
XS GIS Cut Line= 3
      3724849.63     10566260.19      3724599.61     10566260.19
       3723499.6     10565360.18
#Sta/Elev= 30
  4750.2   209.6  4760.2  208.49  4780.2  208.41  4820.2  205.96  4851.6  205.93
  4900.2  206.63  4910.2  205.04  4920.2  197.72  4930.2  194.47  4937.2  188.45
    4940  187.95  4943.2  188.45  5061.8  188.97  5135.2  190.57    5156  192.47
  5192.6  197.48  5234.2  194.54  5256.5  191.03  5284.5  194.12  5298.1  203.49
  5349.1  205.08  5398.6   205.9  5738.8  205.92  5866.6  209.09  6008.7  205.61
  6201.8  205.65    6293  208.76  6364.8  210.23  6393.5  209.91  6421.5  211.07
#Mann= 5 ,-1 , 0
  4750.2     .05       0  4851.6     .16       0  4937.2     .07       0
  4943.2     .16       0  5061.8     .05       0
Bank Sta=4920.2,5192.6
XS Rating Curve= 0 ,0
Exp/Cntr=0.3,0.1

Type RM Length L Ch R = 1 ,10313   ,460,460,460
BEGIN DESCRIPTION:
UNT 168 IN BOCR 21.0
END DESCRIPTION:
XS GIS Cut Line= 3
       3724899.6     10566260.16      3724799.61     10565910.19
      3723999.59     10565610.18
#Sta/Elev= 30
  4604.1  208.31  4637.1  208.02  4676.9  207.65  4693.8  205.12  4718.5  204.75
  4739.3  207.61  4771.8  206.81  4804.7  207.84  4839.4  208.52  4873.2  207.42
  4884.9  201.91  4895.3  198.87  4905.7  193.72  4912.2  192.65  4917.4  188.45
    4943  188.45  4945.7  187.95    4949  188.45  5007.9  188.45  5129.2  188.45
    5139  194.55  5148.7   197.1  5154.1  204.04  5160.3  205.98    5179  206.96
  5219.8  205.79  5244.7  205.74  5661.4  205.89  5746.8  208.72  5822.5  208.87
#Mann= 8 ,-1 , 0
  4604.1     .16       0  4637.1     .05       0  4804.7     .16       0
    4943     .07       0    4949     .16       0  5007.9     .05       0
  5219.8     .16       0  5244.7     .05       0
Bank Sta=4895.3,5148.7
XS Rating Curve= 0 ,0
Exp/Cntr=0.3,0.1

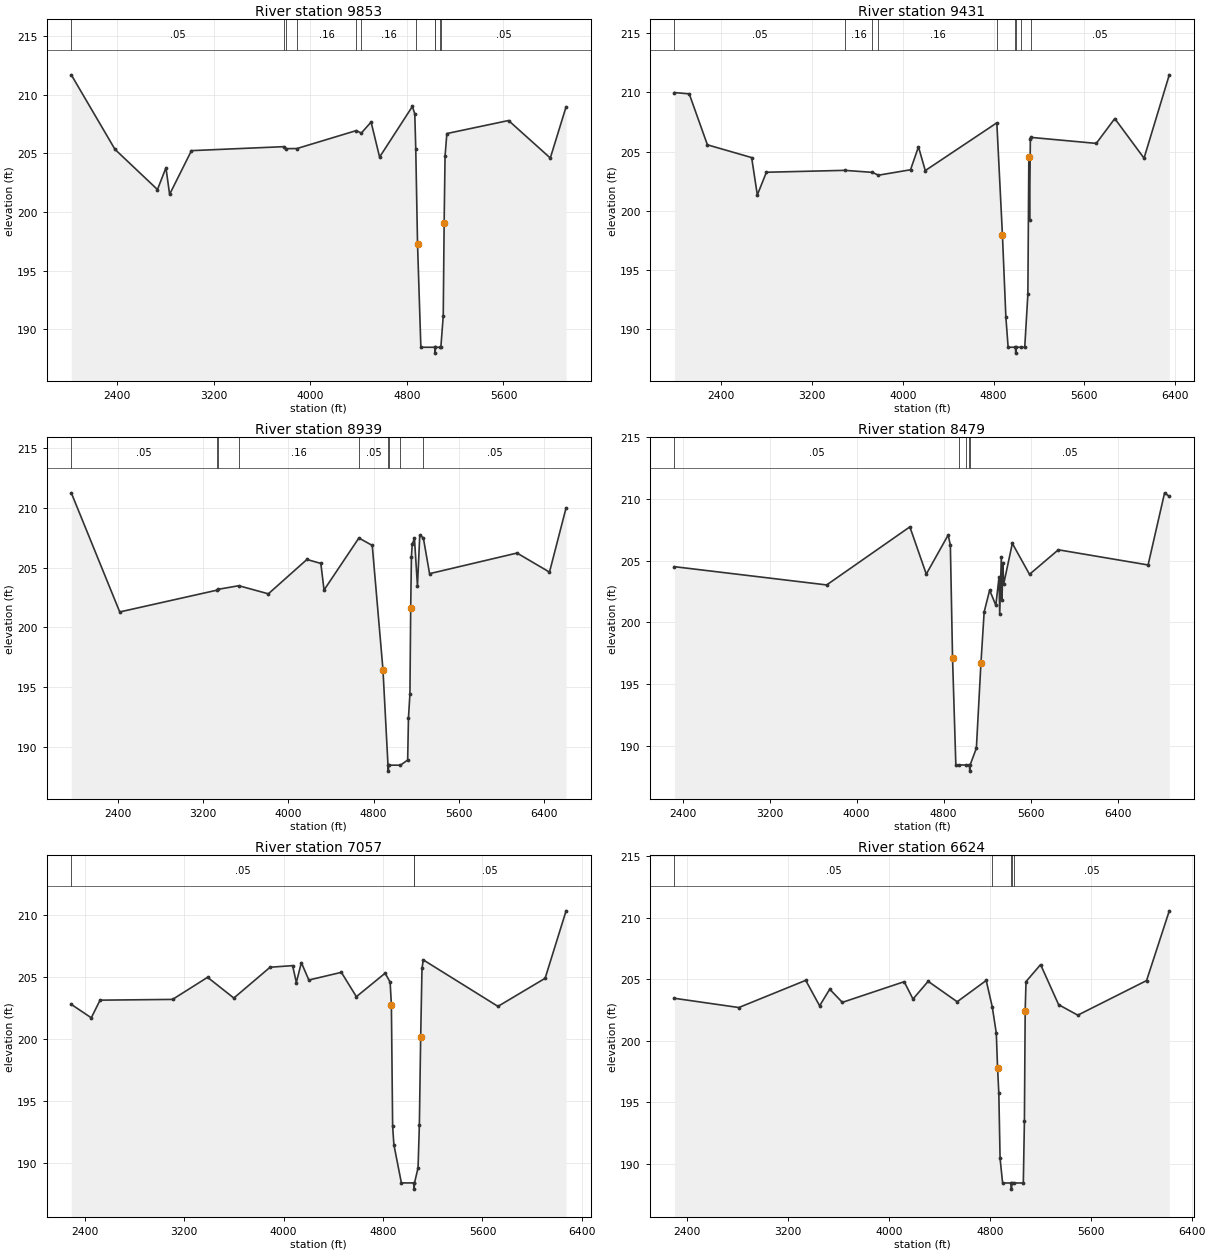
Type RM Length L Ch R = 1 ,9853    ,422,422,422
BEGIN DESCRIPTION:
UNT 168 IN BOCR 20.0
END DESCRIPTION:
XS GIS Cut Line= 3
      3725399.61     10568560.21      3725099.61     10565560.19
      3724499.58     10564660.15
#Sta/Elev= 30
  2021.5   211.7  2383.3  205.34  2735.1  201.91  2805.4  203.77  2835.6   201.5
  3016.5  205.23  3781.6  205.57  3802.7   205.4  3889.8  205.41  4380.8  206.94
    4423  206.73  4503.8  207.67  4574.2  204.68  4845.5     209  4865.6  208.37
  4873.6  205.38  4888.3  197.26  4915.9  188.45    5031  188.45  5033.7  187.95
    5037  188.45  5076.6  188.45  5081.3  188.45  5101.1  191.11  5108.6  199.06
  5116.1  204.75  5131.1  206.69  5641.9   207.8  5987.5   204.6  6118.2  208.97
#Mann= 11 ,-1 , 0
  2021.5     .05       0  3781.6     .12       0  3802.7     .05       0
  3889.8     .16       0  4380.8     .05       0    4423     .16       0
  4873.6     .05       0    5031     .03       0    5037     .05       0
  5076.6     .16       0  5081.3     .05       0
Bank Sta=4888.3,5108.6
XS Rating Curve= 0 ,0
Exp/Cntr=0.3,0.1

Type RM Length L Ch R = 1 ,9431    ,492,492,492
BEGIN DESCRIPTION:
UNT 168 IN BOCR 19.0
END DESCRIPTION:
XS GIS Cut Line= 3
      3725499.61     10568460.16      3725499.61     10565460.19
      3724699.62     10564360.21
#Sta/Elev= 30
    1988  209.99    2118  209.88    2278  205.57    2668  204.49    2718  201.33
    2798  203.25  3487.6  203.41  3731.9  203.24  3784.7     203    4068  203.46
    4138   205.4    4198  203.39  4828.5  207.43    4878  197.91    4908  191.01
    4928  188.45  4992.3  188.45  4995.1  187.95  4998.3  188.45  5040.9  188.45
  5074.5  188.45    5102  192.93  5110.5  204.51  5116.6  199.21    5124  206.08
  5127.4   206.2  5704.8  205.69  5867.8  207.79  6125.6  204.44  6348.1  211.49
#Mann= 9 ,-1 , 0
    1988     .05       0  3487.6     .16       0  3731.9     .12       0
  3784.7     .16       0  4828.5     .05       0  4992.3     .03       0
  4998.3     .05       0  5040.9     .16       0  5127.4     .05       0
Bank Sta=4878,5110.5
XS Rating Curve= 0 ,0
Exp/Cntr=0.3,0.1

Type RM Length L Ch R = 1 ,8939    ,460,460,460
BEGIN DESCRIPTION:
UNT 168 IN BOCR 18.0
END DESCRIPTION:
XS GIS Cut Line= 3
      3725699.61     10568460.16      3725999.61     10565460.19
      3724899.62      10564260.2
#Sta/Elev= 30
  1963.4  211.28  2418.1  201.29  3327.1  203.11  3336.5  203.18  3535.3  203.49
  3812.5  202.81  4174.3  205.69    4305  205.36  4335.1  203.13  4661.9  207.49
  4787.4  206.87  4887.9  196.46  4935.1  188.44  4937.9  187.94  4941.1  188.44
    5052  188.44  5119.8  188.87  5127.2   192.4  5141.1  194.43  5148.2  201.64
    5155   205.9  5162.4  206.97  5183.4  207.46  5211.7  203.45  5233.3  207.71
  5266.7  207.51  5325.2   204.5  6145.9  206.23  6450.5  204.63  6606.2  210.02
#Mann= 9 ,-1 , 0
  1963.4     .05       0  3327.1     .16       0  3336.5     .05       0
  3535.3     .16       0  4661.9     .05       0  4935.1     .03       0
  4941.1     .05       0    5052     .12       0  5266.7     .05       0
Bank Sta=4887.9,5148.2
XS Rating Curve= 0 ,0
Exp/Cntr=0.3,0.1

Type RM Length L Ch R = 1 ,8479    ,1422,1422,1422
BEGIN DESCRIPTION:
UNT 168 IN BOCR 17.0
END DESCRIPTION:
XS GIS Cut Line= 3
      3726699.61     10567960.23      3726399.61     10565260.19
      3724899.64     10564210.21
#Sta/Elev= 30
    2326  204.52  3724.6  203.04  4489.3  207.75  4640.2  203.92  4841.4  207.09
  4861.5  206.28  4881.7  197.08  4911.9  188.44  4936.8  188.44  5003.6  188.44
  5037.1  188.44  5039.9  187.94  5043.1  188.44  5100.6   189.8  5142.5  196.68
  5172.1  200.85  5222.7  202.62  5279.4  201.39    5309  203.69  5315.1  200.67
  5329.9  205.28  5336.1  201.85  5344.8   204.8  5350.9  203.08  5431.1  206.41
  5588.9   203.9    5854  205.89  6678.8  204.66  6830.5  210.51  6873.6  210.22
#Mann= 5 ,-1 , 0
    2326     .05       0  4936.8      .1       0  5003.6     .05       0
  5037.1     .07       0  5043.1     .05       0
Bank Sta=4881.7,5142.5
XS Rating Curve= 0 ,0
Exp/Cntr=0.3,0.1

Type RM Length L Ch R = 1 ,7057    ,433,433,433
BEGIN DESCRIPTION:
UNT 168 IN BOCR 16.0
END DESCRIPTION:
XS GIS Cut Line= 3
      3727299.61     10566810.23      3726999.61     10564110.19
       3726599.6     10562910.16
#Sta/Elev= 30
    2291   202.8    2452  201.72  2522.5  203.14    3106   203.2  3387.8  204.98
    3599  203.31  3890.8  205.79  4071.9  205.92  4102.1  204.56  4142.4  206.16
  4202.7  204.76  4464.3  205.38  4585.1  203.42  4816.5  205.31  4856.7  204.59
  4866.8  202.79  4876.9     193  4886.9  191.51  4947.3  188.43  5046.8  188.43
  5049.6  187.93  5052.8  188.43  5081.4  189.64    5092  193.08  5102.5  200.14
  5113.1  205.69  5123.6  206.38  5724.4  202.64  6103.9   204.9  6272.6  210.33
#Mann= 3 ,-1 , 0
    2291     .05       0  5046.8     .03       0  5052.8     .05       0
Bank Sta=4866.8,5102.5
XS Rating Curve= 0 ,0
Exp/Cntr=0.3,0.1

Type RM Length L Ch R = 1 ,6624    ,413,413,413
BEGIN DESCRIPTION:
UNT 168 IN BOCR 15.0
END DESCRIPTION:
XS GIS Cut Line= 3
      3727349.61     10566560.22      3727349.61     10563860.19
       3726649.6     10562860.18
#Sta/Elev= 30
    2302  203.44    2812  202.69    3342   204.9    3452  202.83    3532  204.18
    3632  203.11    4122  204.79    4192  203.38    4312  204.82    4542  203.16
    4772  204.89  4820.1  202.74    4852  200.61    4862   197.8    4872  195.72
    4882  190.42    4902  188.43    4969  188.43  4971.8  187.93    4975  188.43
  4994.6  188.43  5066.1  188.43  5074.8   193.5  5080.9  202.44  5087.5   204.8
    5203  206.18    5346  202.92  5497.7  202.07  6042.6  204.88  6222.7  210.55
#Mann= 5 ,-1 , 0
    2302     .05       0  4820.1     .16       0    4969     .03       0
    4975     .16       0  4994.6     .05       0
Bank Sta=4862,5080.9
XS Rating Curve= 0 ,0
Exp/Cntr=0.3,0.1

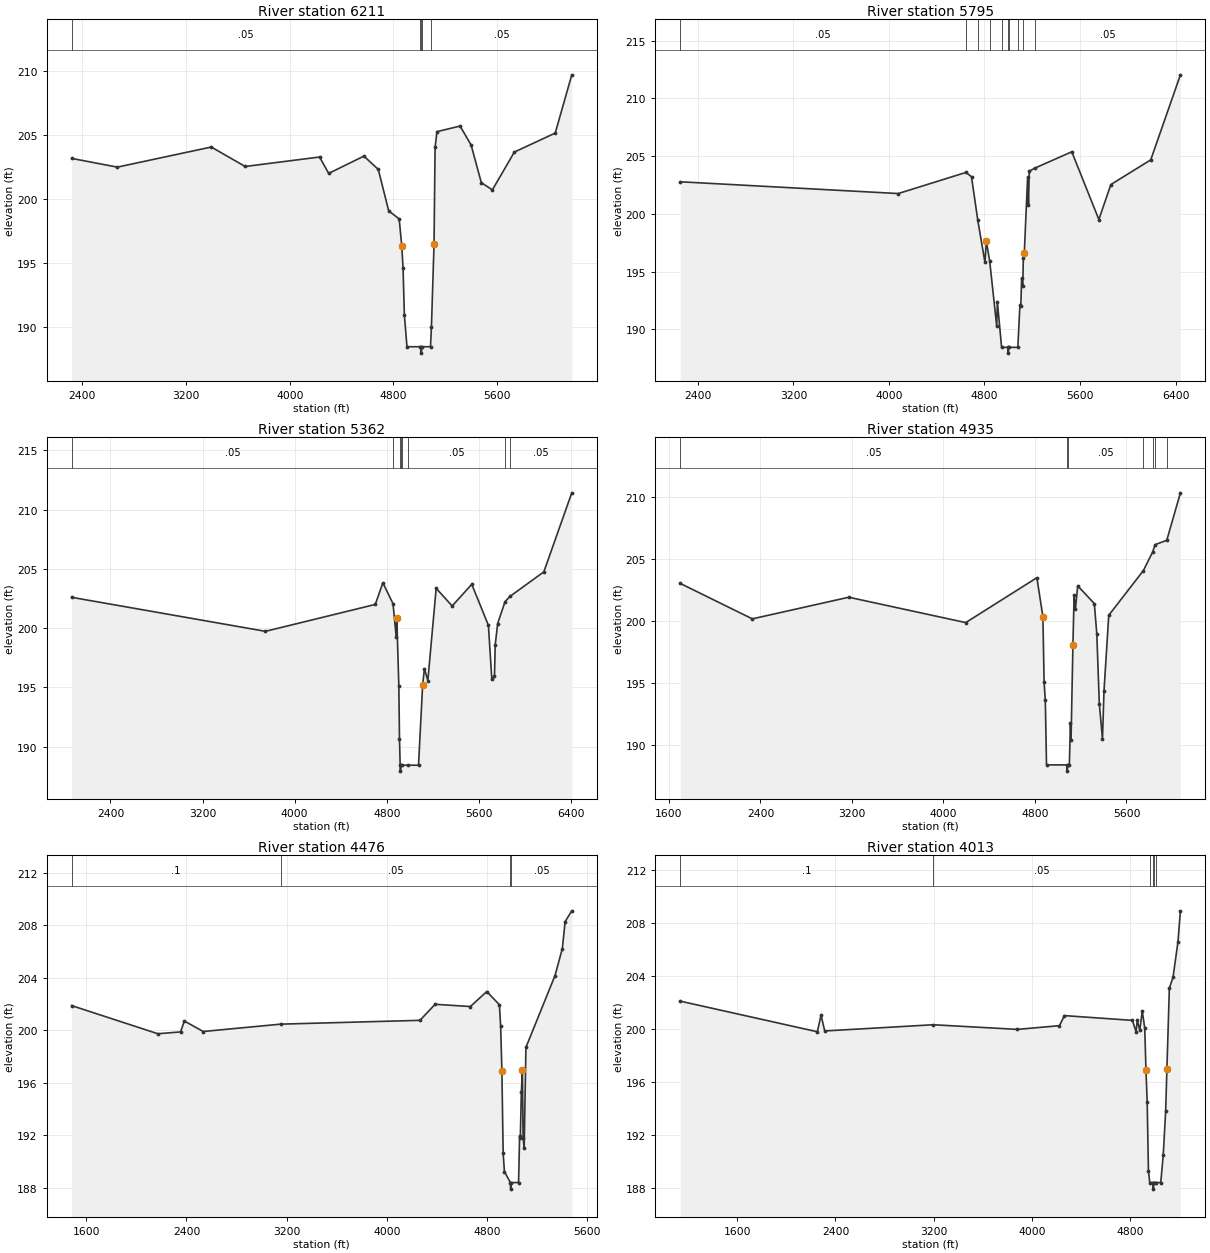
Type RM Length L Ch R = 1 ,6211    ,416,416,416
BEGIN DESCRIPTION:
UNT 168 IN BOCR 14.0
END DESCRIPTION:
XS GIS Cut Line= 3
      3727399.61     10566310.21      3727699.61     10563610.19
      3726999.62      10562710.2
#Sta/Elev= 30
  2318.2  203.14  2670.4  202.46  3394.8  204.03  3656.4  202.51  4229.9  203.25
  4300.3  201.97    4572  203.32  4682.7  202.28  4763.2  199.04  4843.7  198.42
  4863.8  196.31  4873.9  194.55  4883.9  190.92    4904  188.43  5005.6  188.43
  5011.7  188.43  5014.5  187.93  5017.7  188.43  5085.5  188.43  5092.7  190.01
  5112.7  196.44  5120.8     204  5135.3  205.23  5313.5  205.67  5398.6  204.19
  5477.3  201.25  5562.4  200.68  5732.5  203.64  6047.4  205.12    6175  209.67
#Mann= 5 ,-1 , 0
  2318.2     .05       0  5005.6     .16       0  5011.7     .03       0
  5017.7     .16       0  5092.7     .05       0
Bank Sta=4863.8,5112.7
XS Rating Curve= 0 ,0
Exp/Cntr=0.3,0.1

Type RM Length L Ch R = 1 ,5795    ,433,433,433
BEGIN DESCRIPTION:
UNT 168 IN BOCR 13.0
END DESCRIPTION:
XS GIS Cut Line= 3
       3727499.6     10566210.22      3728099.61     10563510.19
      3726999.58     10562610.17
#Sta/Elev= 30
  2253.4  202.78  4078.1  201.76  4644.7  203.59  4691.5  203.22  4744.3  199.43
  4804.2  195.79  4815.7  197.61    4844  195.89  4902.8  190.25  4907.9   192.4
  4943.6  188.43  4997.1  188.43  4999.8  187.93  5003.1  188.43  5079.4  188.43
  5096.8  192.07  5104.7  192.04  5111.2  194.41  5120.5  193.75  5125.5  196.15
  5133.4  196.57  5161.4  203.17  5168.6  200.77  5175.1   203.7  5220.9  203.96
  5531.1  205.38  5757.9  199.51  5858.4  202.54  6192.2  204.68  6440.6  212.05
#Mann= 10 ,-1 , 0
  2253.4     .05       0  4644.7      .1       0  4744.3     .05       0
    4844     .08       0  4943.6     .05       0  4997.1     .03       0
  5003.1     .05       0  5079.4     .16       0  5120.5     .08       0
  5220.9     .05       0
Bank Sta=4815.7,5133.4
XS Rating Curve= 0 ,0
Exp/Cntr=0.3,0.1

Type RM Length L Ch R = 1 ,5362    ,427,427,427
BEGIN DESCRIPTION:
UNT 168 IN BOCR 12.0
END DESCRIPTION:
XS GIS Cut Line= 3
      3731049.63      10564410.2      3728349.61     10563210.19
      3727149.63      10562510.2
#Sta/Elev= 30
  2063.1   202.6  3746.3  199.73  4700.4     202  4766.1  203.83  4854.3  202.06
  4881.7  199.28  4887.1  200.83  4904.9  195.12  4910.4  190.66  4916.3  188.43
    4919  187.93  4922.3  188.43  4935.6  188.43  4988.5  188.43  5075.7  188.43
  5111.6  195.21  5127.3  196.58  5156.7  195.57  5229.1  203.36    5368  201.87
  5538.3   203.7    5683  200.23  5712.4  195.69  5735.6  195.94  5741.8  198.57
  5763.3  200.39  5827.1  202.23  5869.1  202.67  6164.3  204.75    6407  211.42
#Mann= 8 ,-1 , 0
  2063.1     .05       0  4854.3     .08       0  4916.3     .03       0
  4922.3     .08       0  4935.6      .1       0  4988.5     .05       0
  5827.1     .08       0  5869.1     .05       0
Bank Sta=4887.1,5111.6
XS Rating Curve= 0 ,0
Exp/Cntr=0.3,0.1

Type RM Length L Ch R = 1 ,4935    ,459,459,459
BEGIN DESCRIPTION:
UNT 168 IN BOCR 11.0
END DESCRIPTION:
XS GIS Cut Line= 4
      3731428.14      10563777.1      3730866.03     10563682.33
      3728249.61     10562810.19      3727249.63      10562510.2
#Sta/Elev= 30
  1699.4  203.02  2328.9  200.17  3172.2  201.91  4194.7  199.87  4816.6  203.48
  4869.3  200.34  4879.8  195.08  4890.4  193.61  4900.9  188.42  5079.2  188.42
    5082  187.92  5085.2  188.42  5100.5  188.42    5110  191.77  5115.3  190.43
  5131.8   198.1  5142.2  202.07  5153.5  200.94  5173.6  202.83  5318.9   201.4
  5340.6  198.95  5362.4  193.36  5390.2   190.5  5403.2  194.35    5445  200.46
    5748  204.06  5828.6  205.55  5850.1  206.14  5952.2  206.49  6071.4  210.31
#Mann= 7 ,-1 , 0
  1699.4     .05       0  5079.2     .03       0  5085.2     .05       0
    5748     .08       0  5828.6     .05       0  5850.1     .08       0
  5952.2     .05       0
Bank Sta=4869.3,5131.8
XS Rating Curve= 0 ,0
Exp/Cntr=0.3,0.1

Type RM Length L Ch R = 1 ,4476    ,463,463,463
BEGIN DESCRIPTION:
UNT 168 IN BOCR 10.0
END DESCRIPTION:
XS GIS Cut Line= 4
      3731573.99     10562792.73      3730616.09     10562695.35
      3728049.61     10562410.19      3727649.63      10562210.2
#Sta/Elev= 30
  1483.5  201.88  2171.4  199.74  2353.2  199.88  2382.5  200.71  2533.3  199.91
  3152.3  200.47  4263.9  200.76  4384.7  201.98  4666.4  201.81  4797.2  202.95
  4897.8  201.95  4907.9  200.32  4917.9  196.91    4928  190.66  4938.1  189.26
  4985.4  188.42  4988.1  187.92  4991.4  188.42    5051  188.42  5059.4  191.96
  5064.9  191.81  5073.3   195.3  5081.7  196.95  5087.3  191.83  5095.7  191.03
  5109.7   198.7  5341.7  204.16  5400.4  206.22  5422.7  208.27  5475.8  209.09
#Mann= 4 ,-1 , 0
  1483.5      .1       0  3152.3     .05       0  4985.4     .03       0
  4991.4     .05       0
Bank Sta=4917.9,5081.7
XS Rating Curve= 0 ,0
Exp/Cntr=0.3,0.1

Type RM Length L Ch R = 1 ,4013    ,453,453,453
BEGIN DESCRIPTION:
UNT 168 IN BOCR 9.0
END DESCRIPTION:
XS GIS Cut Line= 4
      3731855.26     10562282.32      3730608.85      10562250.1
      3727999.61     10561960.19      3727799.63     10561960.19
#Sta/Elev= 30
  1136.7  202.11  2252.7   199.8  2282.7  201.05  2312.7  199.86  3195.8  200.33
  3881.9  199.98    4224  200.26  4264.3  201.02  4817.7  200.66  4847.8  199.81
  4857.9  200.68    4878   199.9  4898.1  201.37  4918.3  200.08  4928.3  196.93
  4938.4  194.46  4948.5   189.3  4959.2  188.42  4985.7  188.42  4988.5  187.92
  4991.7  188.42  5006.6  188.42  5048.8  188.42  5068.8  190.47  5088.8  193.83
  5098.8  196.97  5118.8  203.09  5148.8  203.92  5188.8  206.59  5208.8  208.93
#Mann= 6 ,-1 , 0
  1136.7      .1       0  3195.8     .05       0  4959.2     .07       0
  4985.7     .07       0  4991.7     .07       0  5006.6     .05       0
Bank Sta=4928.3,5098.8
XS Rating Curve= 0 ,0
Exp/Cntr=0.3,0.1

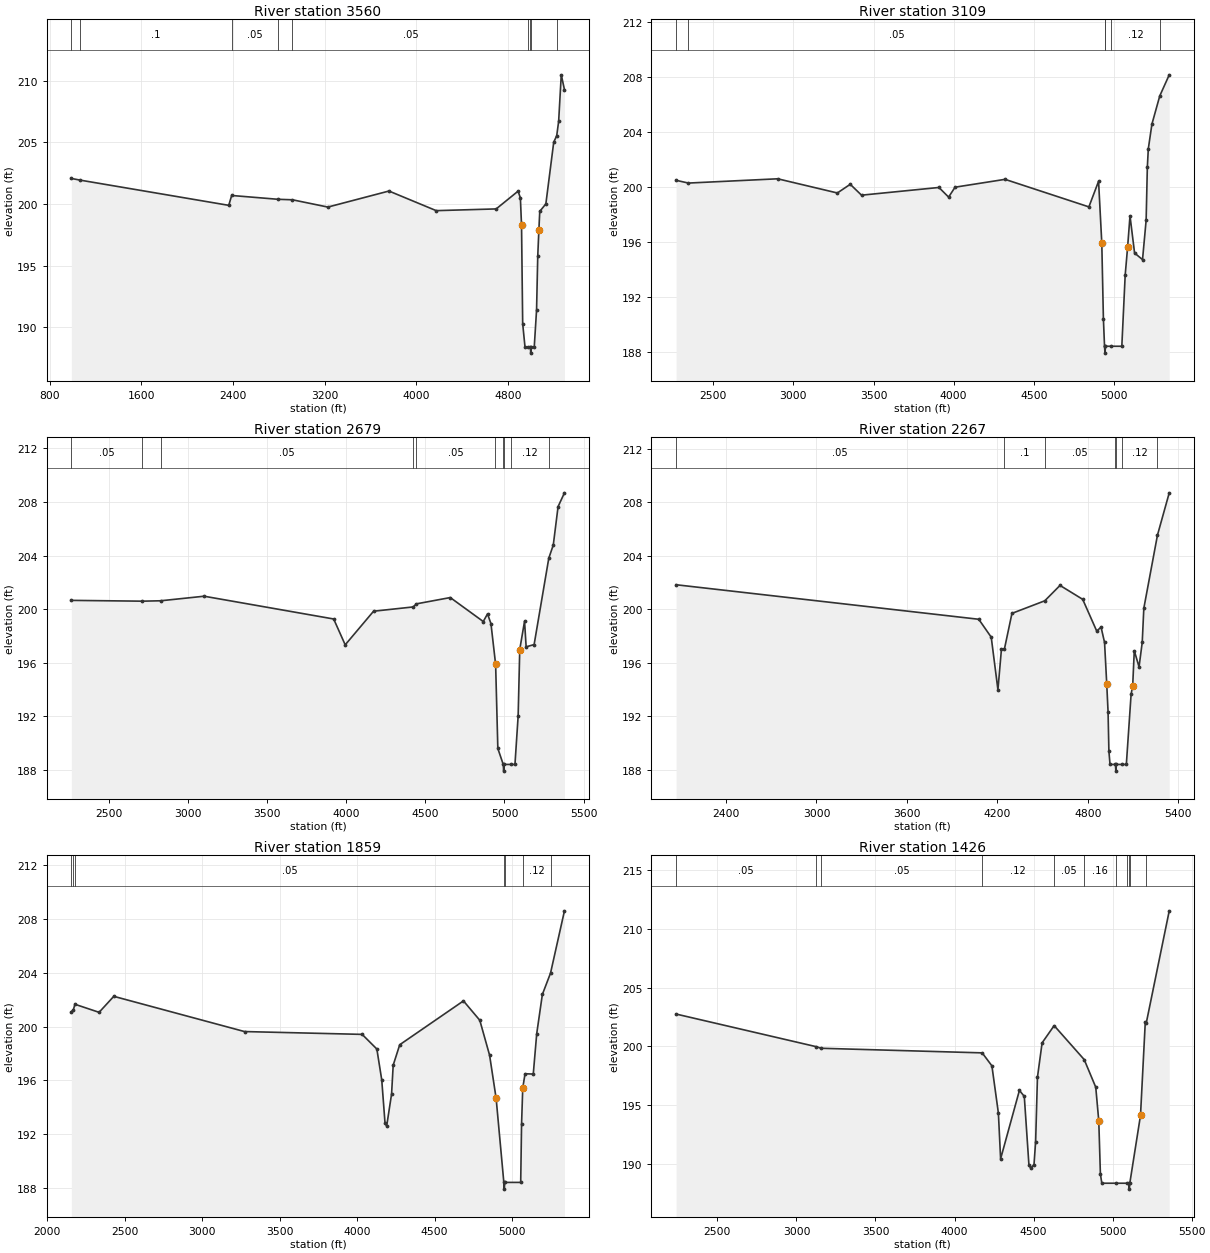
Type RM Length L Ch R = 1 ,3560    ,451,451,451
BEGIN DESCRIPTION:
UNT 168 IN BOCR 8.0
END DESCRIPTION:
XS GIS Cut Line= 4
      3732032.31     10561855.23      3730599.97     10561793.56
      3728049.61     10561510.19      3727749.57      10561560.2
#Sta/Elev= 30
     990  202.08  1069.5  201.94    2364   199.9  2389.4   200.7  2794.4  200.39
  2920.2  200.35  3228.9  199.76  3762.2  201.06  4174.7  199.47  4697.9  199.61
  4889.1  201.05  4909.2   200.5  4919.3  198.27  4929.3  190.31  4949.5  188.42
  4977.8  188.42  4996.9  188.42  4999.6  187.92  5002.9  188.42  5030.3  188.42
  5050.5  191.43  5060.7  195.76  5070.8  197.94  5078.4  199.41  5131.6  200.02
  5200.1  205.01  5226.4  205.55  5243.2  206.71    5266  210.48  5293.9  209.28
#Mann= 9 ,-1 , 0
     990     .05       0  1069.5      .1       0  2389.4     .05       0
  2794.4      .1       0  2920.2     .05       0  4977.8     .12       0
  4996.9     .07       0  5002.9     .12       0  5226.4     .16       0
Bank Sta=4919.3,5070.8
XS Rating Curve= 0 ,0
Exp/Cntr=0.3,0.1

Type RM Length L Ch R = 1 ,3109    ,430,430,430
BEGIN DESCRIPTION:
UNT 168 IN BOCR 7.0
END DESCRIPTION:
XS GIS Cut Line= 3
      3730699.56     10560760.19      3727999.61     10561060.19
      3727699.63     10561260.18
#Sta/Elev= 30
  2268.3  200.47    2345  200.27  2902.1  200.58  3274.4  199.55  3354.9  200.18
  3425.3  199.39  3908.3  199.95  3968.7  199.25  4008.9  199.97  4320.8  200.54
    4844  198.54  4904.4   200.4  4924.5  195.91  4934.6   190.4  4941.6  188.42
  4944.4  187.92  4947.6  188.42    4982  188.42  5049.5  188.42  5070.5  193.59
  5085.5   195.6  5100.5  197.89  5129.1  195.19  5178.7  194.71  5201.2  197.57
  5208.7  201.41  5214.7  202.75  5237.3  204.55  5286.3   206.6  5345.4  208.13
#Mann= 6 ,-1 , 0
  2268.3      .1       0    2345     .05       0  4941.6     .07       0
  4947.6     .05       0    4982     .12       0  5286.3     .16       0
Bank Sta=4924.5,5085.5
XS Rating Curve= 0 ,0
Exp/Cntr=0.3,0.1

Type RM Length L Ch R = 1 ,2679    ,412,412,412
BEGIN DESCRIPTION:
UNT 168 IN BOCR 6.0
END DESCRIPTION:
XS GIS Cut Line= 3
      3730549.64     10560060.18      3727849.61     10560660.19
      3727499.66     10560710.18
#Sta/Elev= 30
  2260.1  200.66  2709.6   200.6  2825.7  200.63  3100.1  200.97  3919.6  199.27
  3992.6  197.34  4171.9  199.85  4422.7  200.17  4443.4   200.4  4657.2  200.87
  4865.9  199.08  4892.8  199.65  4914.6  198.92    4942  196.09    4944  195.92
  4958.1   189.6  4992.3  188.41    4995  187.91  4998.3  188.41  5043.8  188.41
  5066.4  188.41  5086.6  192.04  5096.7  196.99    5127   199.1  5137.1  197.19
  5187.6  197.36  5280.4  203.81  5308.8  204.79  5339.1  207.66  5379.5  208.69
#Mann= 10 ,-1 , 0
  2260.1     .05       0  2709.6      .1       0  2825.7     .05       0
  4422.7      .1       0  4443.4     .05       0    4942     .16       0
  4992.3     .07       0  4998.3     .16       0  5043.8     .12       0
  5280.4     .05       0
Bank Sta=4944,5096.7
XS Rating Curve= 0 ,0
Exp/Cntr=0.3,0.1

Type RM Length L Ch R = 1 ,2267    ,408,408,408
BEGIN DESCRIPTION:
UNT 168 IN BOCR 5.0
END DESCRIPTION:
XS GIS Cut Line= 3
      3730349.63     10559110.18      3727649.61     10560310.19
      3727349.62     10560410.19
#Sta/Elev= 30
  2069.3  201.84  4076.7  199.26  4159.5  197.92  4203.9  193.99  4227.2  197.03
  4247.2  197.05  4296.9   199.7  4514.6  200.64  4615.7  201.79  4766.1  200.75
  4859.1  198.38  4887.9  198.67  4911.1  197.53  4925.5  194.45  4934.4  192.34
  4939.9  189.41  4947.4  188.41  4983.4  188.41  4986.1  187.91  4989.4  188.41
  5029.9  188.41  5055.6  188.41  5087.2  193.65  5097.8   194.3  5108.3  196.91
  5139.9   195.7    5161  197.53  5171.6  200.08  5262.1  205.55  5340.2  208.71
#Mann= 7 ,-1 , 0
  2069.3     .05       0  4247.2      .1       0  4514.6     .05       0
  4983.4     .03       0  4989.4     .05       0  5029.9     .12       0
  5262.1     .05       0
Bank Sta=4925.5,5097.8
XS Rating Curve= 0 ,0
Exp/Cntr=0.3,0.1

Type RM Length L Ch R = 1 ,1859    ,433,433,433
BEGIN DESCRIPTION:
UNT 168 IN BOCR 4.0
END DESCRIPTION:
XS GIS Cut Line= 3
      3730149.57      10559060.2      3727449.61     10559960.19
      3727149.62     10560110.18
#Sta/Elev= 30
  2156.4   201.1  2169.6  201.25  2179.7  201.66  2335.6  201.06  2430.4  202.25
  3273.7  199.63  4032.6  199.42  4127.5  198.33  4159.1  196.03  4180.2  192.82
  4190.8   192.6  4222.4  194.98  4232.9  197.13  4275.1  198.65  4686.2  201.91
  4791.6  200.47  4854.8  197.87    4897  194.66  4946.7  188.41  4949.5  187.91
  4952.7  188.41  5055.5  188.41  5061.1  192.76  5068.7  195.43  5083.5  196.49
  5136.6  196.47  5158.9  199.48  5195.3  202.39    5248  203.98  5337.8  208.61
#Mann= 7 ,-1 , 0
  2156.4     .05       0  2169.6     .08       0  2179.7     .05       0
  4946.7     .03       0  4952.7     .05       0  5068.7     .12       0
    5248     .05       0
Bank Sta=4897,5068.7
XS Rating Curve= 0 ,0
Exp/Cntr=0.3,0.1

Type RM Length L Ch R = 1 ,1426    ,466,466,466
BEGIN DESCRIPTION:
UNT 168 IN BOCR 3.0
END DESCRIPTION:
XS GIS Cut Line= 3
      3729899.63     10559010.18      3727199.61     10559610.19
      3726849.65     10559660.18
#Sta/Elev= 30
  2238.8  202.75  3123.3  199.99  3155.7  199.85    4175  199.46  4236.4  198.36
  4277.4  194.36  4291.5  190.48  4410.5  196.28  4441.3  195.77  4470.7  189.94
  4482.2  189.69  4502.7  189.99    4513  191.94  4524.5  197.39    4554  200.31
  4630.1  201.77  4820.3  198.89  4893.3  196.55  4912.5  193.68  4922.7  189.19
  4931.7  188.41  5024.3  188.41  5094.1  188.41  5102.7  188.41  5105.5  187.91
  5108.7  188.41  5176.4  194.16  5206.7   202.1  5213.3  202.02  5358.2   211.5
#Mann= 11 ,-1 , 0
  2238.8     .05       0  3123.3      .1       0  3155.7     .05       0
    4175     .12       0  4630.1     .05       0  4820.3     .16       0
  5024.3     .05       0  5094.1     .12       0  5102.7     .07       0
  5108.7     .12       0  5213.3     .05       0
Bank Sta=4912.5,5176.4
XS Rating Curve= 0 ,0
Exp/Cntr=0.3,0.1

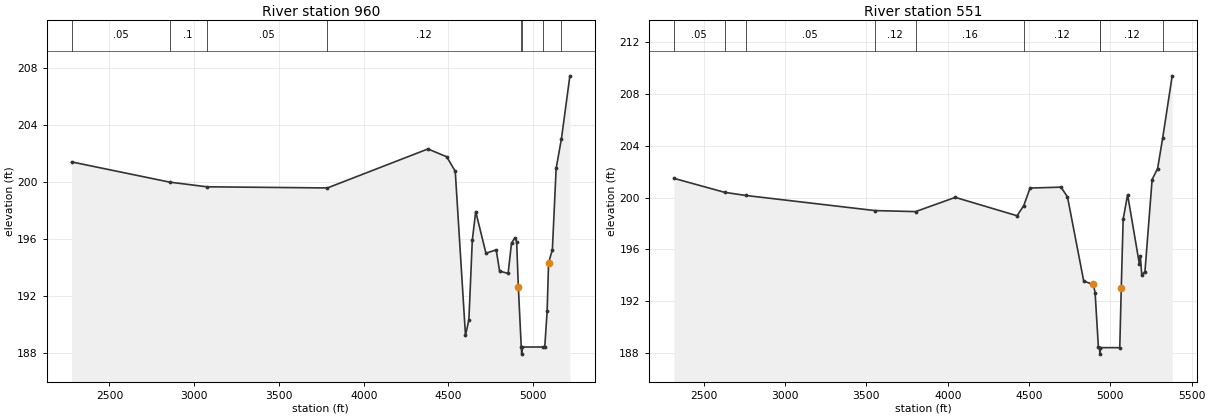
Type RM Length L Ch R = 1 ,960     ,409,409,409
BEGIN DESCRIPTION:
UNT 168 IN BOCR 2.0
END DESCRIPTION:
XS GIS Cut Line= 3
      3729599.66     10558960.18      3726899.61     10559260.19
       3726799.6     10559460.22
#Sta/Elev= 30
  2276.3  201.41  2854.5  199.99  3074.1  199.66  3785.7  199.58  4379.2  202.32
  4489.9  201.77  4540.2  200.75  4600.6  189.21  4620.7  190.33  4640.8  195.91
  4660.9  197.92  4721.3  194.99  4781.7  195.23  4801.8  193.74  4852.1  193.57
  4872.2  195.71  4892.3  196.07  4902.4  195.81  4912.5  192.61  4929.6   188.4
  4932.3   187.9  4935.6   188.4    5059   188.4  5068.4   188.4  5082.4  190.94
  5090.8  194.32  5113.2  195.23  5135.5  200.95  5166.6  203.03  5216.6  207.46
#Mann= 8 ,-1 , 0
  2276.3     .05       0  2854.5      .1       0  3074.1     .05       0
  3785.7     .12       0  4929.6     .07       0  4935.6     .12       0
    5059     .16       0  5166.6     .05       0
Bank Sta=4912.5,5090.8
XS Rating Curve= 0 ,0
Exp/Cntr=0.3,0.1

Type RM Length L Ch R = 1 ,551     ,0,0,0
BEGIN DESCRIPTION:
UNT 168 IN BOCR 1.0
END DESCRIPTION:
XS GIS Cut Line= 3
      3729399.61     10558910.19      3726699.61     10558910.19
      3726349.61     10559010.19
#Sta/Elev= 30
  2316.4  201.48  2628.3   200.4  2756.9  200.16  3552.3  198.99  3802.4  198.91
  4046.4  200.01  4426.4  198.59  4467.8  199.38  4506.4  200.73  4696.4   200.8
  4736.4  200.05  4836.4  193.54  4896.4  193.28  4906.4  192.62  4926.4  188.46
  4933.4   188.4  4936.1   187.9  4939.4   188.4    5058   188.4  5067.1     193
  5078.8  198.32  5106.1  200.22  5178.9  194.84  5184.1  195.51  5193.2  194.04
  5212.7  194.26  5256.9  201.39  5290.7  202.24  5321.5  204.57  5380.4   209.4
#Mann= 9 ,-1 , 0
  2316.4     .05       0  2628.3      .1       0  2756.9     .05       0
  3552.3     .12       0  3802.4     .16       0  4467.8     .12       0
  4933.4     .07       0  4939.4     .12       0  5321.5     .05       0
Bank Sta=4896.4,5067.1
XS Rating Curve= 0 ,0
Exp/Cntr=0.3,0.1

Chan Stop Cuts=-1
Use User Specified Reach Order=0
Composite Channel Slope=5