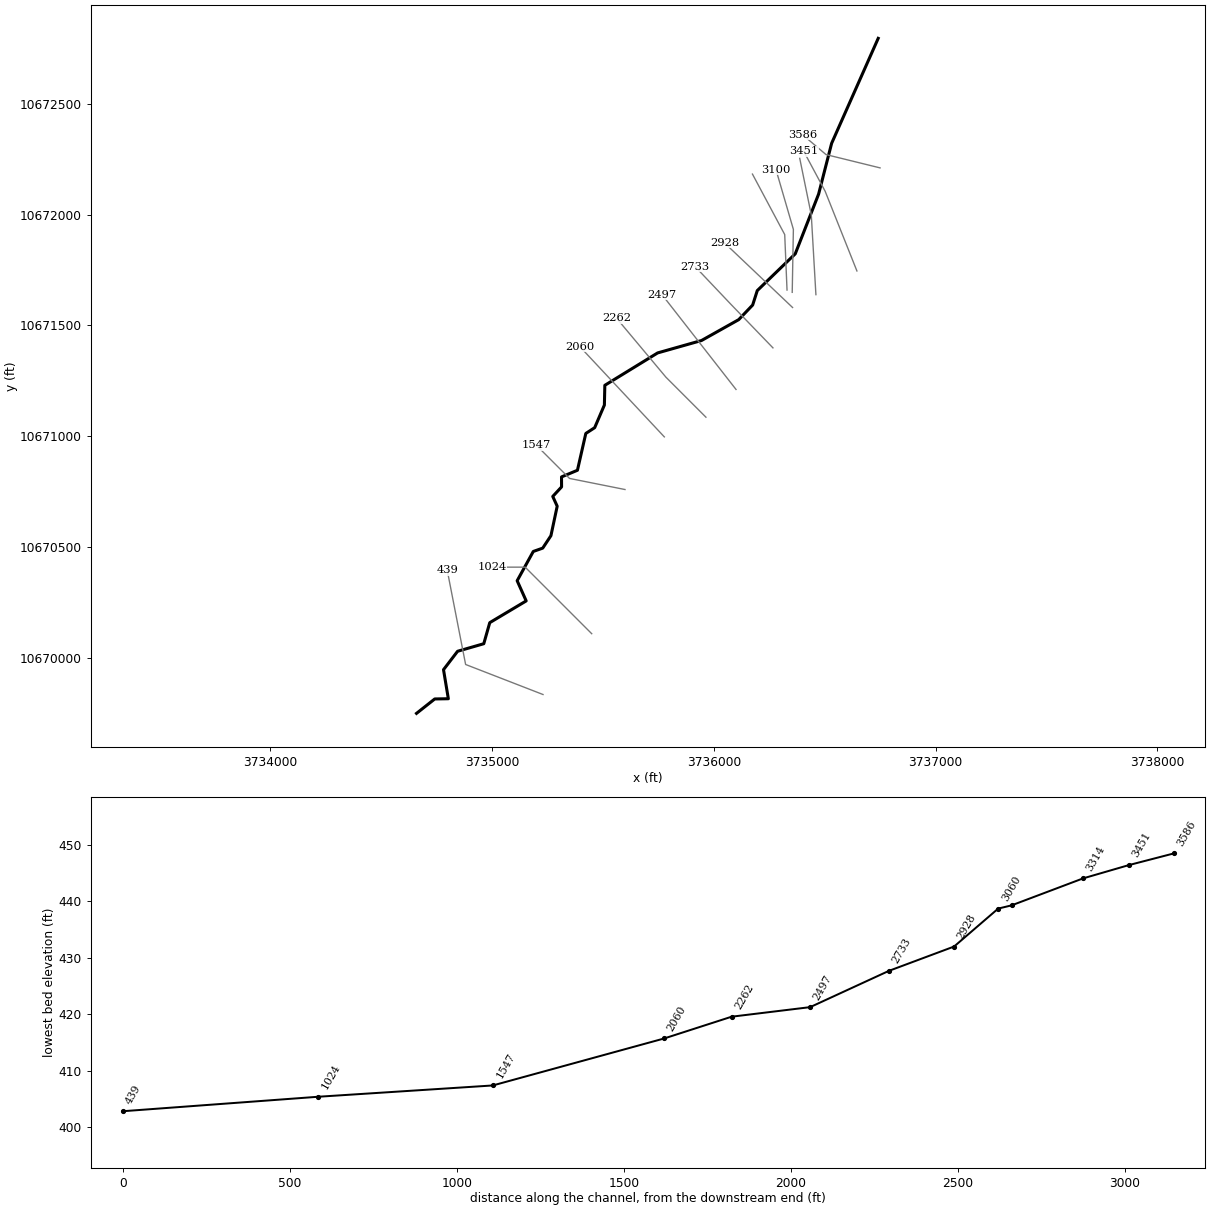
--- UNT 171 IN BOCR.prj (project) ---

Proj Title=UNT 171 IN BOCR Base Level Engineering
Current Plan=p01
Default Exp/Contr=0.3,0.1
English Units
Geom File=g01
Flow File=f01
Plan File=p01
BEGIN DESCRIPTION:
UNT 171 IN BOCR
END DESCRIPTION:

--- UNT 171 IN BOCR.p01 (plan) ---

Plan Title=Multiple Run
Short Identifier=Multiple
Geom File=g01
Flow File=f01
Subcritical Flow
K Sum by GR= 0
Std Step Tol= 0.01
Critical Tol= 0.01
Num of Std Step Trials= 20
Max Error Tol= 0.3
Flow Tol Ratio= 0.001
Split Flow NTrial= 30
Split Flow Tol= 0.02
Split Flow Ratio= 0.02
Log Output Level= 0
Friction Slope Method= 1
Unsteady Friction Slope Method= 2
Unsteady Bridges Friction Slope Method= 1
Parabolic Critical Depth
Global Vel Dist=  1 , 1 , 1
Global Log Level= 0
CheckData=True
Encroach Param= -1, 0, 0, 0
BEGIN DESCRIPTION:
Multiple Run
END DESCRIPTION:

--- UNT 171 IN BOCR.f01 (steady flow) ---

Flow Title=Multiple
Number of Profiles=7
Profile Names=10-year,25-year,50-year,1pct_min,100-year,1pct_plu,500-year
River Rch & RM= UNT 171 IN BOCR,Reach-1,3586
     309     406     484     426     576     779     817
Boundary for River Rch & Prof#=UNT 171 IN BOCR,Reach-1,1
Up Type=0
Dn Type=3
Dn Slope=0.005
Boundary for River Rch & Prof#=UNT 171 IN BOCR,Reach-1,2
Up Type=0
Dn Type=3
Dn Slope=0.005
Boundary for River Rch & Prof#=UNT 171 IN BOCR,Reach-1,3
Up Type=0
Dn Type=3
Dn Slope=0.005
Boundary for River Rch & Prof#=UNT 171 IN BOCR,Reach-1,4
Up Type=0
Dn Type=3
Dn Slope=0.005
Boundary for River Rch & Prof#=UNT 171 IN BOCR,Reach-1,5
Up Type=0
Dn Type=3
Dn Slope=0.005
Boundary for River Rch & Prof#=UNT 171 IN BOCR,Reach-1,6
Up Type=0
Dn Type=3
Dn Slope=0.005
Boundary for River Rch & Prof#=UNT 171 IN BOCR,Reach-1,7
Up Type=0
Dn Type=3
Dn Slope=0.005

--- UNT 171 IN BOCR.g01 (geometry) ---

Geom Title=Existing Conditions

River Reach=UNT 171 IN BOCR,Reach-1
Reach XY= 30
      3736741.21     10672794.23      3736531.25     10672321.00
      3736472.50     10672092.00      3736367.16     10671822.62
      3736196.00     10671657.00      3736175.25     10671592.00
      3736112.25     10671526.00      3735944.75     10671432.00
      3735746.75     10671376.00      3735508.75     10671230.00
      3735506.75     10671141.00      3735463.00     10671039.00
      3735423.00     10671013.00      3735385.25     10670847.00
      3735313.50     10670817.00      3735313.75     10670772.00
      3735274.00     10670729.00      3735294.00     10670685.00
      3735265.75     10670552.00      3735228.75     10670496.00
      3735186.25     10670481.00      3735113.50     10670349.00
      3735154.25     10670258.00      3734990.00     10670160.00
      3734963.00     10670065.00      3734845.00     10670031.00
      3734781.50     10669948.00      3734803.25     10669817.00
      3734742.00     10669816.00      3734659.75     10669751.00

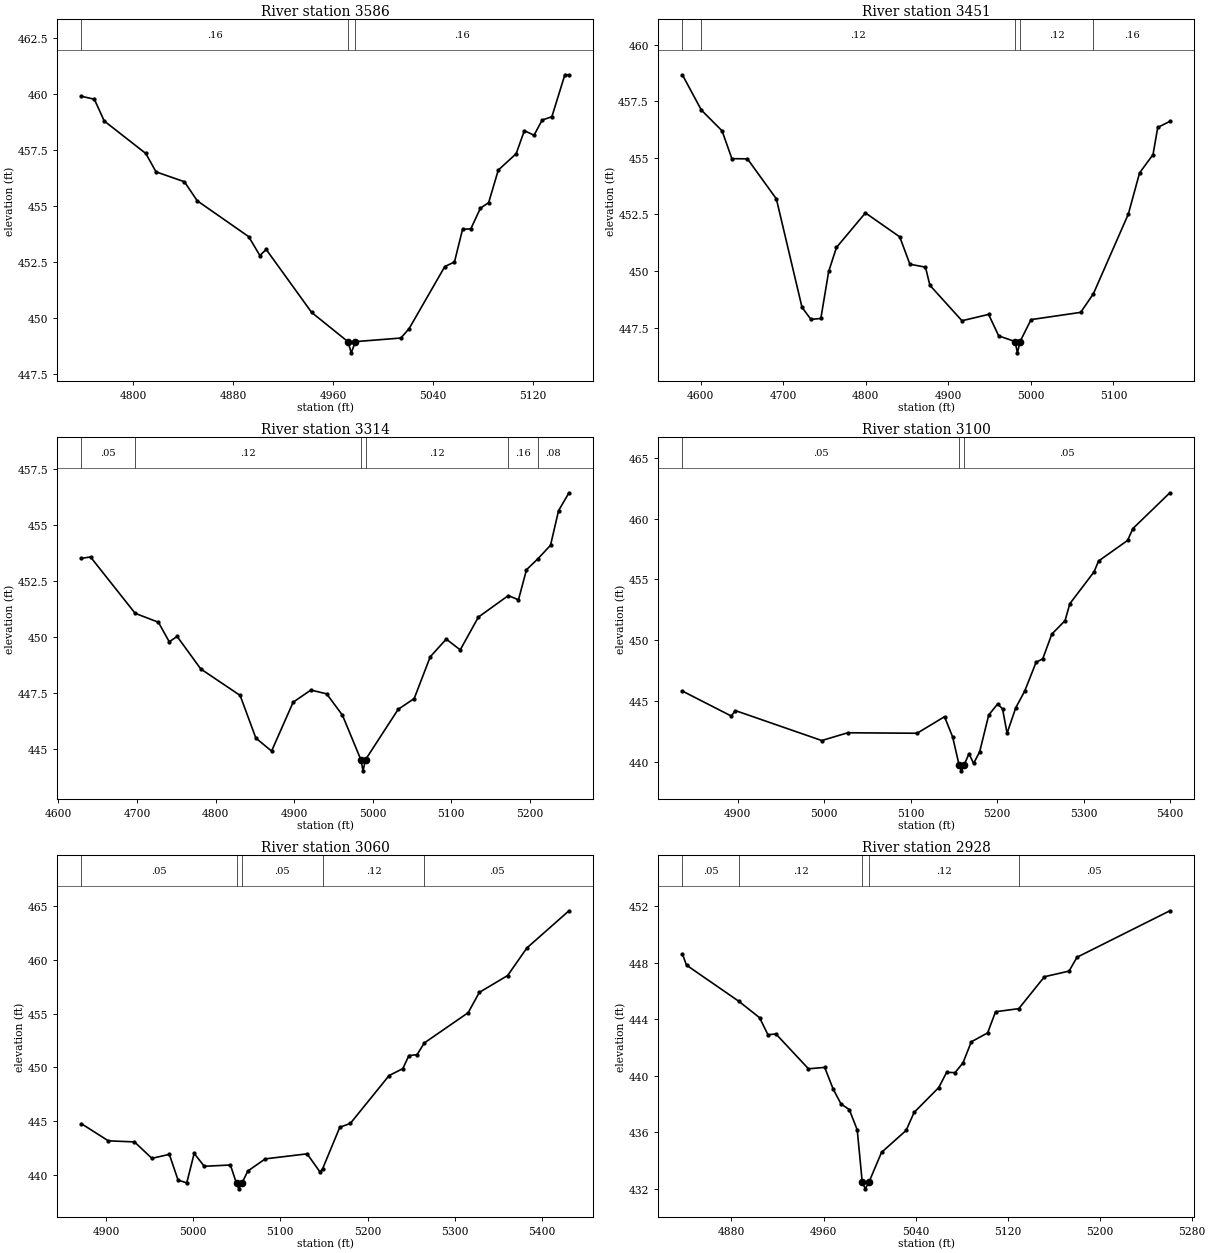
Type RM Length L Ch R = 1,3586,135,135,135
BEGIN DESCRIPTION:
UNT 171 IN BOCR 8.0
END DESCRIPTION:
XS GIS Cut Line= 3
      3736749.62     10672210.19      3736506.00     10672270.11
      3736399.60     10672360.20
#Sta/Elev= 30
  4758.4  459.89  4768.7  459.76  4776.6  458.79  4809.9  457.34  4818.1  456.52
  4840.8  456.08  4851.1  455.23  4892.3  453.63  4901.2  452.79  4906.3  453.06
  4942.7  450.25  4971.7  448.95  4974.4  448.45  4977.7  448.95  5014.1  449.11
  5020.7  449.53  5049.3  452.30  5057.0  452.50  5063.5  453.96  5070.1  453.98
  5077.8  454.90  5084.4  455.15  5092.1  456.60  5106.4  457.33  5113.0  458.36
  5120.7  458.15  5127.2  458.83  5135.0  458.98  5145.4  460.85  5148.7  460.85
#Mann=3,-1,0
  4758.4    0.16       0  4971.7    0.07       0  4977.7    0.16       0
Bank Sta=4971.7,4977.7
Exp/Cntr=0.3,0.1

Type RM Length L Ch R = 1,3451,137,137,137
BEGIN DESCRIPTION:
Mapping XS ce4c1652
END DESCRIPTION:
XS GIS Cut Line= 3
      3736645.22     10671745.47      3736502.01     10672104.81
      3736405.66     10672284.48
#Sta/Elev= 30
  4577.7  458.68  4600.7  457.12  4625.8  456.20  4637.7  454.97  4656.6  454.96
  4691.6  453.19  4722.7  448.39  4733.5  447.86  4745.5  447.90  4755.0  449.98
  4764.4  451.04  4799.5  452.57  4841.1  451.51  4853.4  450.30  4872.3  450.17
  4877.6  449.37  4916.5  447.80  4948.8  448.08  4961.0  447.13  4980.9  446.88
  4983.7  446.38  4986.9  446.88  5000.2  447.85  5060.3  448.17  5075.7  448.99
  5118.1  452.52  5131.7  454.34  5148.0  455.15  5153.7  456.35  5168.4  456.62
#Mann=5,-1,0
  4577.7    0.05       0  4600.7    0.12       0  4980.9    0.07       0
  4986.9    0.12       0  5075.7    0.16       0
Bank Sta=4980.9,4986.9
Exp/Cntr=0.3,0.1

Type RM Length L Ch R = 1,3314,214,214,214
BEGIN DESCRIPTION:
Mapping XS 85b39ff4
END DESCRIPTION:
XS GIS Cut Line= 3
      3736460.34     10671638.67      3736439.51     10671998.04
      3736387.43     10672253.21
#Sta/Elev= 30
  4629.4  453.50  4640.9  453.56  4697.7  451.05  4727.3  450.65  4741.1  449.78
  4751.1  450.02  4781.2  448.57  4831.3  447.39  4851.3  445.49  4871.3  444.91
  4898.8  447.09  4921.4  447.63  4941.4  447.46  4961.5  446.51  4984.9  444.53
  4987.7  444.03  4990.9  444.53  5032.4  446.77  5052.8  447.25  5073.2  449.11
  5093.6  449.90  5111.4  449.42  5134.5  450.88  5172.6  451.84  5185.5  451.65
  5195.7  452.99  5210.0  453.47  5226.3  454.08  5236.5  455.62  5249.8  456.42
#Mann=6,-1,0
  4629.4    0.05       0  4697.7    0.12       0  4984.9    0.07       0
  4990.9    0.12       0  5172.6    0.16       0  5210.0    0.08       0
Bank Sta=4984.9,4990.9
Exp/Cntr=0.3,0.1

Type RM Length L Ch R = 1,3100,40,40,40
BEGIN DESCRIPTION:
UNT 171 IN BOCR 7.0
END DESCRIPTION:
XS GIS Cut Line= 3
      3736353.57     10671649.08      3736358.78     10671932.94
      3736280.65     10672201.18
#Sta/Elev= 30
  4836.2  445.82  4892.6  443.77  4897.6  444.21  4997.3  441.75  5027.3  442.39
  5107.4  442.35  5139.1  443.71  5148.5  442.05  5155.9  439.76  5158.7  439.26
  5161.9  439.76  5167.4  440.67  5172.7  439.87  5179.7  440.82  5190.2  443.85
  5200.6  444.77  5206.2  444.34  5211.4  442.35  5221.4  444.44  5231.8  445.82
  5244.9  448.18  5252.6  448.47  5263.1  450.50  5278.4  451.61  5283.9  453.00
  5311.9  455.62  5317.1  456.51  5350.6  458.20  5356.8  459.18  5399.5  462.12
#Mann=3,-1,0
  4836.2    0.05       0  5155.9    0.04       0  5161.9    0.05       0
Bank Sta=5155.9,5161.9
Exp/Cntr=0.3,0.1

Type RM Length L Ch R = 1,3060,132,132,132
BEGIN DESCRIPTION:
Mapping XS 04fd060c
END DESCRIPTION:
XS GIS Cut Line= 3
      3736330.13     10671659.45      3736319.72     10671909.50
      3736174.24     10672182.27
#Sta/Elev= 30
  4871.8  444.75  4902.6  443.16  4932.6  443.06  4952.6  441.53  4972.6  441.90
  4982.6  439.51  4992.6  439.24  5001.1  441.99  5012.7  440.79  5042.7  440.91
  5049.7  439.19  5052.4  438.69  5055.7  439.19  5062.7  440.35  5082.7  441.48
  5130.7  441.95  5145.5  440.26  5148.5  440.56  5168.2  444.42  5180.3  444.78
  5224.8  449.24  5240.5  449.88  5247.5  451.10  5256.8  451.18  5265.3  452.28
  5315.5  455.09  5328.3  456.98  5360.8  458.55  5382.9  461.12  5431.2  464.58
#Mann=5,-1,0
  4871.8    0.05       0  5049.7    0.04       0  5055.7    0.05       0
  5148.5    0.12       0  5265.3    0.05       0
Bank Sta=5049.7,5055.7
Exp/Cntr=0.3,0.1

Type RM Length L Ch R = 1,2928,195,195,195
BEGIN DESCRIPTION:
UNT 171 IN BOCR 6.0
END DESCRIPTION:
XS GIS Cut Line= 2
      3736355.13     10671580.75      3736047.82     10671872.44
#Sta/Elev= 30
  4837.3  448.62  4840.9  447.82  4886.4  445.26  4904.4  444.10  4911.7  442.89
  4918.6  442.95  4946.9  440.48  4961.0  440.58  4968.3  439.06  4975.2  437.99
  4982.4  437.59  4989.3  436.15  4993.6  432.48  4996.3  431.98  4999.6  432.48
  5010.4  434.56  5031.8  436.12  5038.7  437.39  5060.1  439.15  5067.0  440.23
  5074.3  440.21  5081.2  440.90  5088.4  442.39  5102.6  443.02  5109.5  444.52
  5129.7  444.74  5152.0  447.00  5173.4  447.40  5180.3  448.38  5261.0  451.67
#Mann=5,-1,0
  4837.3    0.05       0  4886.4    0.12       0  4993.6    0.07       0
  4999.6    0.12       0  5129.7    0.05       0
Bank Sta=4993.6,4999.6
Exp/Cntr=0.3,0.1

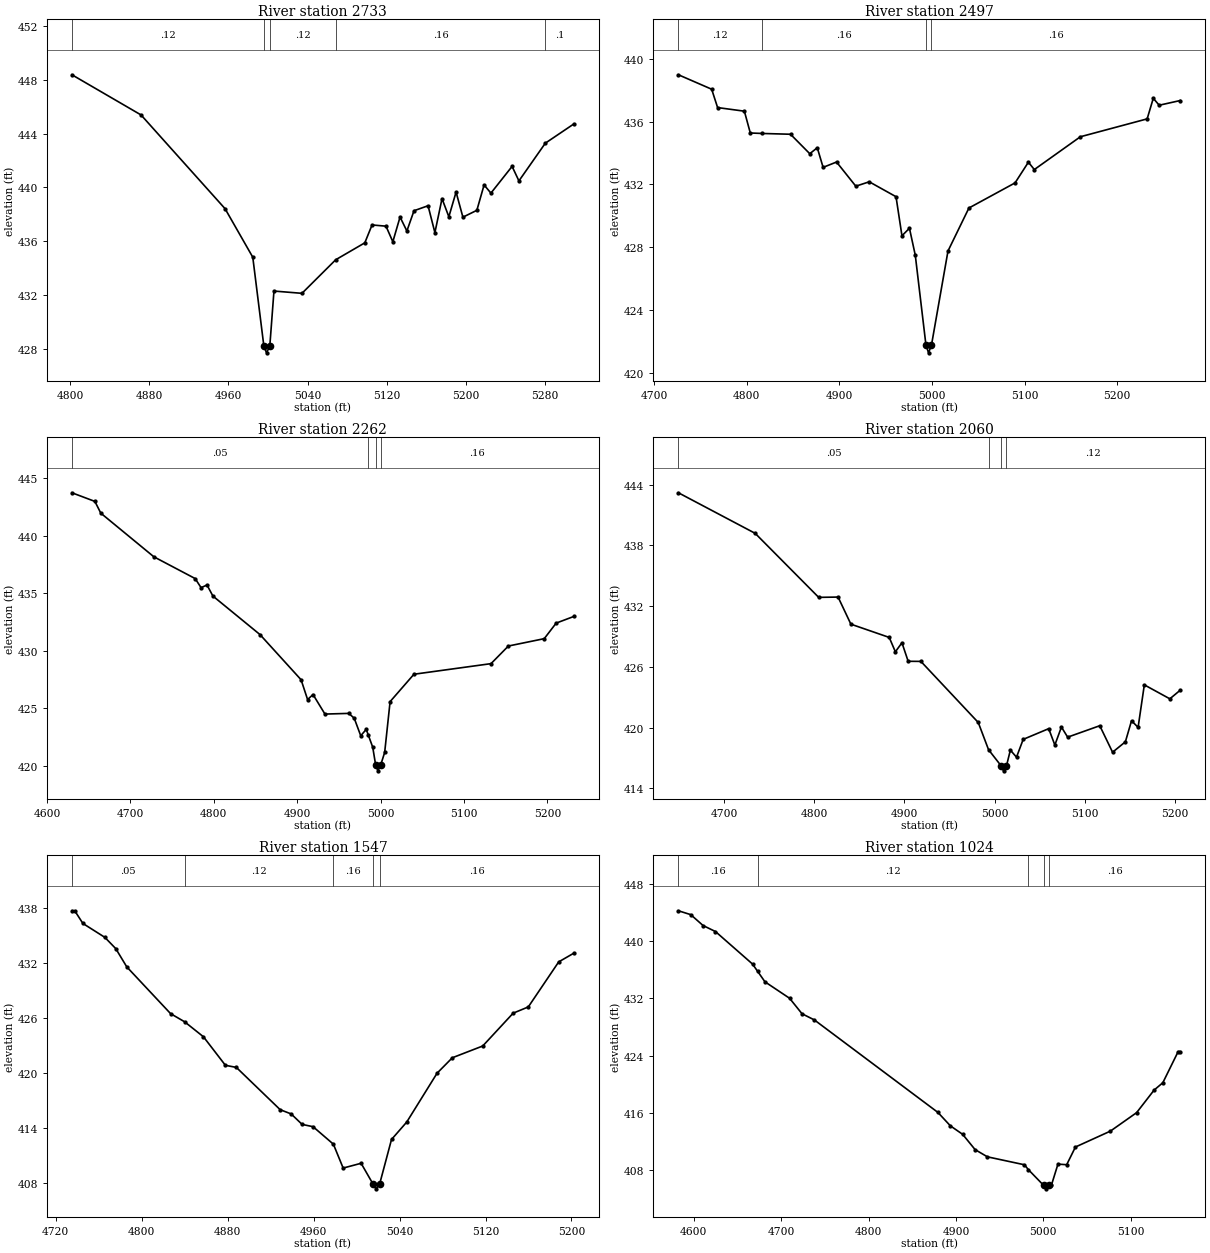
Type RM Length L Ch R = 1,2733,236,236,236
BEGIN DESCRIPTION:
Mapping XS 5897f59d
END DESCRIPTION:
XS GIS Cut Line= 3
      3736266.69     10671398.72      3736075.71     10671596.64
      3735916.02     10671765.01
#Sta/Elev= 30
  4802.0  448.38  4871.8  445.39  4956.7  438.41  4984.7  434.80  4995.9  428.18
  4998.6  427.68  5001.9  428.18  5006.1  432.28  5034.4  432.11  5068.5  434.61
  5097.9  435.87  5105.2  437.20  5119.3  437.11  5126.2  435.95  5133.5  437.79
  5140.4  436.75  5147.6  438.26  5161.8  438.63  5168.7  436.63  5175.9  439.16
  5182.8  437.81  5190.1  439.65  5197.0  437.78  5211.1  438.29  5218.4  440.18
  5225.3  439.57  5246.7  441.56  5253.6  440.48  5280.3  443.29  5309.1  444.72
#Mann=5,-1,0
  4802.0    0.12       0  4995.9    0.07       0  5001.9    0.12       0
  5068.5    0.16       0  5280.3     0.1       0
Bank Sta=4995.9,5001.9
Exp/Cntr=0.3,0.1

Type RM Length L Ch R = 1,2497,235,235,235
BEGIN DESCRIPTION:
UNT 171 IN BOCR 5.0
END DESCRIPTION:
XS GIS Cut Line= 2
      3736100.19     10671211.31      3735766.84     10671638.42
#Sta/Elev= 30
  4726.3  438.98  4762.2  438.06  4768.6  436.89  4797.5  436.66  4803.9  435.27
  4817.0  435.24  4847.3  435.19  4868.1  433.95  4876.2  434.33  4882.5  433.08
  4897.0  433.42  4917.8  431.88  4932.3  432.16  4961.2  431.21  4967.6  428.72
  4975.7  429.20  4982.0  427.48  4993.5  421.76  4996.3  421.26  4999.5  421.76
  5017.3  427.75  5039.9  430.49  5089.7  432.09  5104.1  433.41  5110.5  432.94
  5160.2  435.03  5232.3  436.17  5238.9  437.48  5245.3  437.04  5268.1  437.34
#Mann=4,-1,0
  4726.3    0.12       0  4817.0    0.16       0  4993.5    0.07       0
  4999.5    0.16       0
Bank Sta=4993.5,4999.5
Exp/Cntr=0.3,0.1

Type RM Length L Ch R = 1,2262,202,202,202
BEGIN DESCRIPTION:
Mapping XS b8708467
END DESCRIPTION:
XS GIS Cut Line= 3
      3735964.59     10671086.23      3735784.04     10671266.78
      3735561.79     10671532.44
#Sta/Elev= 30
  4630.0  443.72  4657.5  442.97  4664.6  441.95  4728.2  438.16  4777.7  436.27
  4784.8  435.48  4791.9  435.71  4799.0  434.75  4855.5  431.40  4904.7  427.48
  4912.5  425.76  4919.0  426.20  4933.3  424.50  4961.9  424.56  4968.4  424.14
  4976.2  422.62  4982.8  423.17  4985.2  422.69  4990.6  421.62  4994.1  420.07
  4996.8  419.57  5000.1  420.07  5004.9  421.17  5011.4  425.58  5040.0  427.96
  5132.4  428.88  5153.2  430.41  5196.2  431.05  5210.5  432.40  5231.7  432.98
#Mann=4,-1,0
  4630.0    0.05       0  4985.2    0.16       0  4994.1    0.07       0
  5000.1    0.16       0
Bank Sta=4994.1,5000.1
Exp/Cntr=0.3,0.1

Type RM Length L Ch R = 1,2060,513,513,513
BEGIN DESCRIPTION:
UNT 171 IN BOCR 4.0
END DESCRIPTION:
XS GIS Cut Line= 2
      3735776.96     10670997.47      3735396.76     10671403.71
#Sta/Elev= 30
  4649.4  443.21  4734.5  439.20  4804.9  432.87  4826.4  432.90  4840.6  430.22
  4883.1  428.91  4889.9  427.49  4897.2  428.38  4904.1  426.55  4918.2  426.54
  4981.8  420.50  4993.2  417.81  5007.1  416.22  5009.8  415.72  5013.1  416.22
  5017.4  417.77  5024.2  417.07  5031.6  418.83  5059.9  419.89  5066.7  418.27
  5074.0  420.05  5080.9  419.05  5116.5  420.18  5130.7  417.56  5144.9  418.59
  5151.7  420.67  5159.0  420.02  5165.9  424.22  5194.2  422.84  5205.8  423.70
#Mann=4,-1,0
  4649.4    0.05       0  4993.2    0.16       0  5007.1    0.07       0
  5013.1    0.12       0
Bank Sta=5007.1,5013.1
Exp/Cntr=0.3,0.1

Type RM Length L Ch R = 1,1547,523,523,523
BEGIN DESCRIPTION:
UNT 171 IN BOCR 3.0
END DESCRIPTION:
XS GIS Cut Line= 3
      3735599.65     10670760.18      3735349.61     10670810.19
      3735199.63     10670960.17
#Sta/Elev= 30
  4735.1  437.66  4737.7  437.66  4745.3  436.28  4765.7  434.77  4775.9  433.54
  4786.1  431.56  4826.9  426.47  4840.0  425.58  4857.5  423.95  4877.9  420.85
  4888.1  420.62  4928.9  416.02  4939.1  415.56  4949.3  414.42  4959.5  414.17
  4978.4  412.27  4987.5  409.67  5004.2  410.19  5015.4  407.91  5018.1  407.41
  5021.4  407.91  5032.5  412.78  5046.7  414.68  5074.9  419.99  5089.1  421.67
  5117.4  422.95  5145.7  426.52  5159.8  427.20  5188.1  432.10  5202.2  433.05
#Mann=5,-1,0
  4735.1    0.05       0  4840.0    0.12       0  4978.4    0.16       0
  5015.4    0.07       0  5021.4    0.16       0
Bank Sta=5015.4,5021.4
Exp/Cntr=0.3,0.1

Type RM Length L Ch R = 1,1024,585,585,585
BEGIN DESCRIPTION:
UNT 171 IN BOCR 2.0
END DESCRIPTION:
XS GIS Cut Line= 3
      3735449.58     10670110.22      3735149.61     10670410.19
      3734999.63     10670410.19
#Sta/Elev= 30
  4582.5  444.24  4596.6  443.70  4610.7  442.18  4624.9  441.34  4667.3  436.80
  4673.2  435.77  4681.5  434.32  4709.7  432.02  4723.9  429.86  4738.0  429.00
  4879.4  416.08  4893.6  414.21  4907.7  413.02  4921.9  410.89  4936.0  409.88
  4978.4  408.77  4982.8  408.10  5000.2  405.91  5002.9  405.41  5006.2  405.91
  5009.2  405.91  5016.7  408.86  5026.7  408.78  5036.7  411.25  5076.7  413.47
  5106.7  416.05  5126.7  419.20  5136.7  420.23  5154.2  424.57  5156.7  424.57
#Mann=5,-1,0
  4582.5    0.16       0  4673.2    0.12       0  4982.8    0.16       0
  5000.2    0.07       0  5006.2    0.16       0
Bank Sta=5000.2,5006.2
Exp/Cntr=0.3,0.1

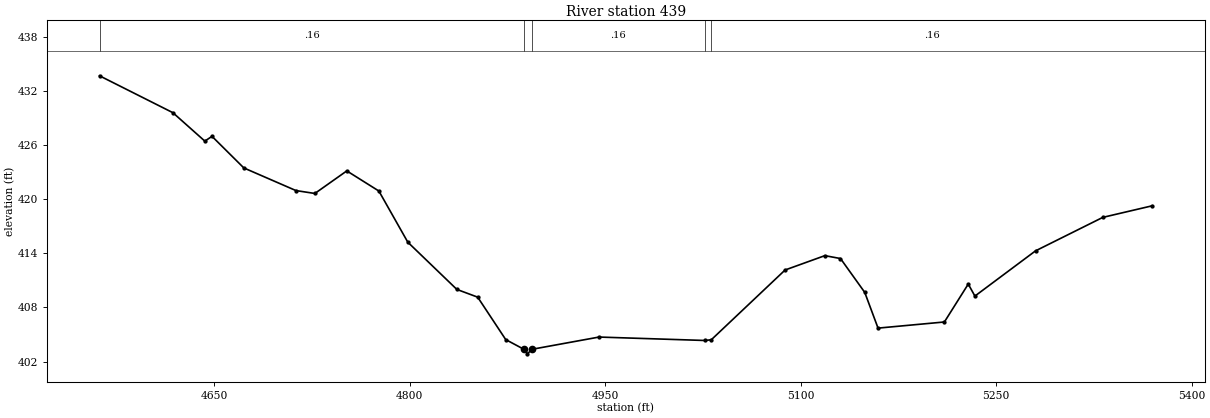
Type RM Length L Ch R = 1,439,0,0,0
BEGIN DESCRIPTION:
UNT 171 IN BOCR 1.0
END DESCRIPTION:
XS GIS Cut Line= 3
      3735230.08     10669836.00      3734881.14     10669971.41
      3734798.14     10670396.79
#Sta/Elev= 30
  4562.2  433.66  4618.5  429.57  4643.0  426.42  4648.5  426.95  4672.9  423.45
  4712.9  420.94  4727.4  420.62  4751.9  423.12  4776.5  420.89  4798.7  415.22
  4836.3  409.99  4852.3  409.13  4873.8  404.43  4887.8  403.35  4890.5  402.85
  4893.8  403.35  4945.4  404.71  5026.6  404.33  5031.5  404.41  5088.1  412.14
  5118.6  413.73  5130.6  413.41  5149.2  409.66  5159.4  405.70  5210.3  406.38
  5228.6  410.58  5233.7  409.25  5280.2  414.26  5331.8  417.97  5369.9  419.26
#Mann=5,-1,0
  4562.2    0.16       0  4887.8    0.07       0  4893.8    0.16       0
  5026.6    0.12       0  5031.5    0.16       0
Bank Sta=4887.8,4893.8
Exp/Cntr=0.3,0.1

Chan Stop Cuts=-1