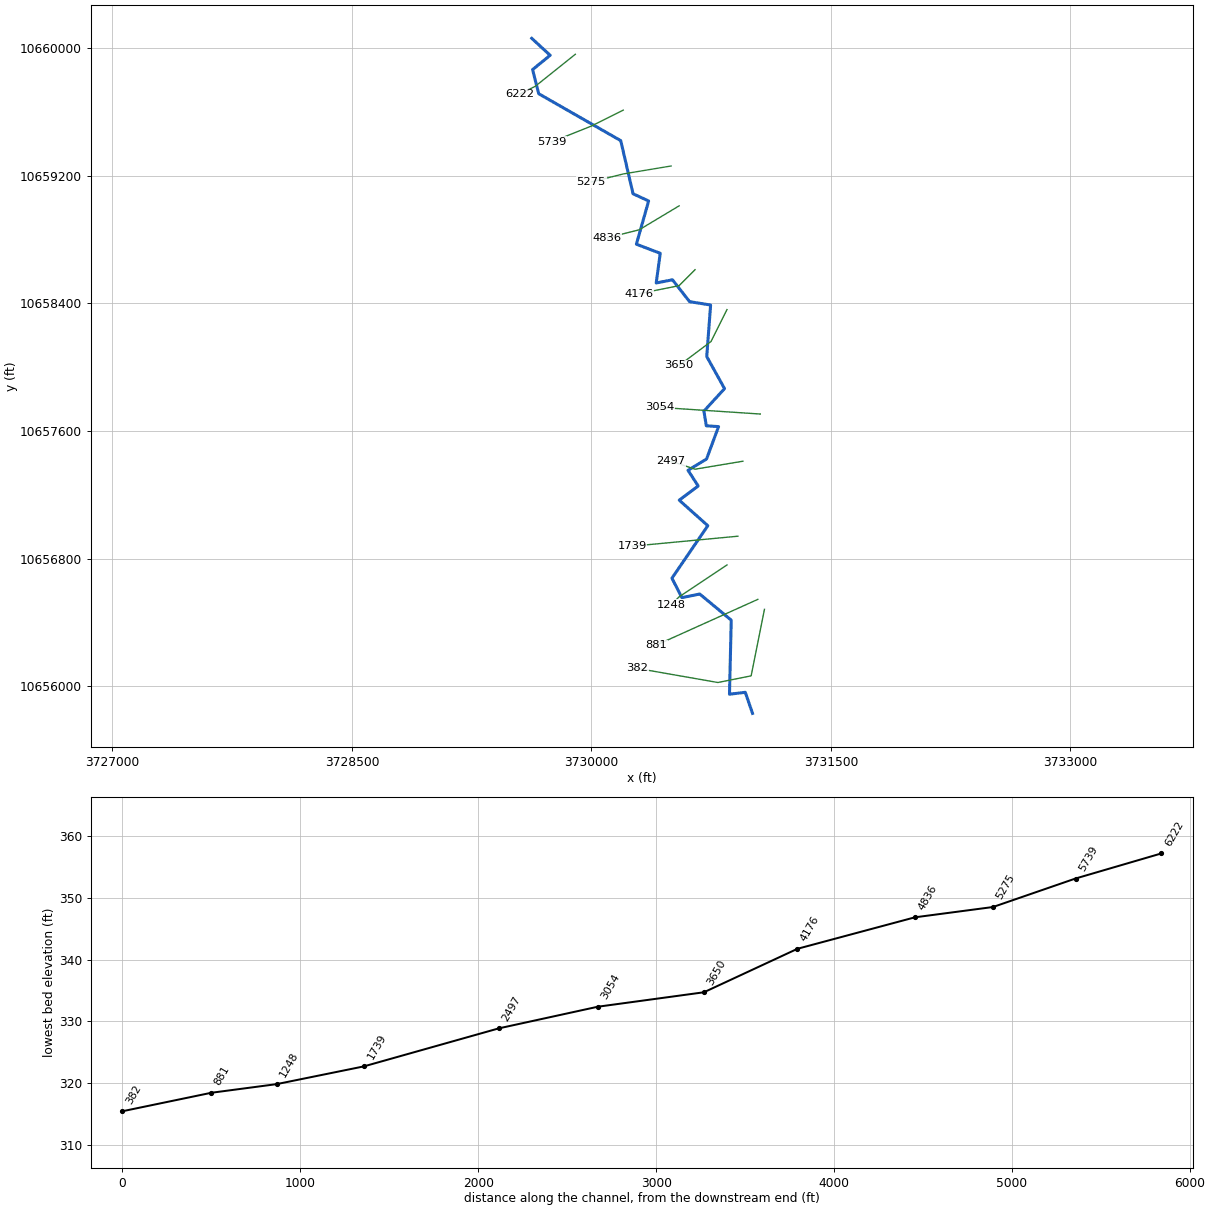
--- UNT 172 IN BOCR.prj (project) ---

Proj Title=UNT 172 IN BOCR Base Level Engineering
Current Plan=p01
Default Exp/Contr=0.3,0.1
English Units
Geom File=g01
Flow File=f01
Plan File=p01
BEGIN DESCRIPTION:
UNT 172 IN BOCR
END DESCRIPTION:

--- UNT 172 IN BOCR.p01 (plan) ---

Plan Title=Multiple Run
Short Identifier=Multiple
Geom File=g01
Flow File=f01
Subcritical Flow
K Sum by GR= 0
Std Step Tol= 0.01
Critical Tol= 0.01
Num of Std Step Trials= 20
Max Error Tol= 0.3
Flow Tol Ratio= 0.001
Split Flow NTrial= 30
Split Flow Tol= 0.02
Split Flow Ratio= 0.02
Log Output Level= 0
Friction Slope Method= 1
Unsteady Friction Slope Method= 2
Unsteady Bridges Friction Slope Method= 1
Parabolic Critical Depth
Global Vel Dist=  1 , 1 , 1
Global Log Level= 0
CheckData=True
Encroach Param= -1, 0, 0, 0
BEGIN DESCRIPTION:
Multiple Run
END DESCRIPTION:

--- UNT 172 IN BOCR.f01 (steady flow) ---

Flow Title=Multiple
Number of Profiles=7
Profile Names=10-year,25-year,50-year,1pct_min,100-year,1pct_plu,500-year
River Rch & RM= UNT 172 IN BOCR,Reach-1,6222
     390     515     616     542     733     992    1042
Boundary for River Rch & Prof#=UNT 172 IN BOCR,Reach-1,1
Up Type=0
Dn Type=3
Dn Slope=0.005
Boundary for River Rch & Prof#=UNT 172 IN BOCR,Reach-1,2
Up Type=0
Dn Type=3
Dn Slope=0.005
Boundary for River Rch & Prof#=UNT 172 IN BOCR,Reach-1,3
Up Type=0
Dn Type=3
Dn Slope=0.005
Boundary for River Rch & Prof#=UNT 172 IN BOCR,Reach-1,4
Up Type=0
Dn Type=3
Dn Slope=0.005
Boundary for River Rch & Prof#=UNT 172 IN BOCR,Reach-1,5
Up Type=0
Dn Type=3
Dn Slope=0.005
Boundary for River Rch & Prof#=UNT 172 IN BOCR,Reach-1,6
Up Type=0
Dn Type=3
Dn Slope=0.005
Boundary for River Rch & Prof#=UNT 172 IN BOCR,Reach-1,7
Up Type=0
Dn Type=3
Dn Slope=0.005

--- UNT 172 IN BOCR.g01 (geometry) ---

Geom Title=Existing Conditions

River Reach=UNT 172 IN BOCR,Reach-1
Reach XY= 30
      3729626.52     10660060.09      3729741.75     10659954.00
      3729631.75     10659864.00      3729670.25     10659713.00
      3730184.00     10659419.00      3730261.25     10659086.00
      3730358.75     10659041.00      3730282.00     10658770.00
      3730431.50     10658713.00      3730406.25     10658527.00
      3730508.25     10658547.00      3730615.25     10658410.00
      3730747.00     10658389.00      3730722.75     10658066.00
      3730834.25     10657865.00      3730705.00     10657724.00
      3730720.00     10657632.00      3730797.00     10657627.00
      3730721.50     10657424.00      3730605.50     10657353.00
      3730669.25     10657255.00      3730550.50     10657166.00
      3730729.50     10657006.00      3730504.75     10656677.00
      3730567.25     10656555.00      3730678.75     10656578.00
      3730876.25     10656414.00      3730865.25     10655950.00
      3730964.25     10655962.00      3731009.50     10655830.00

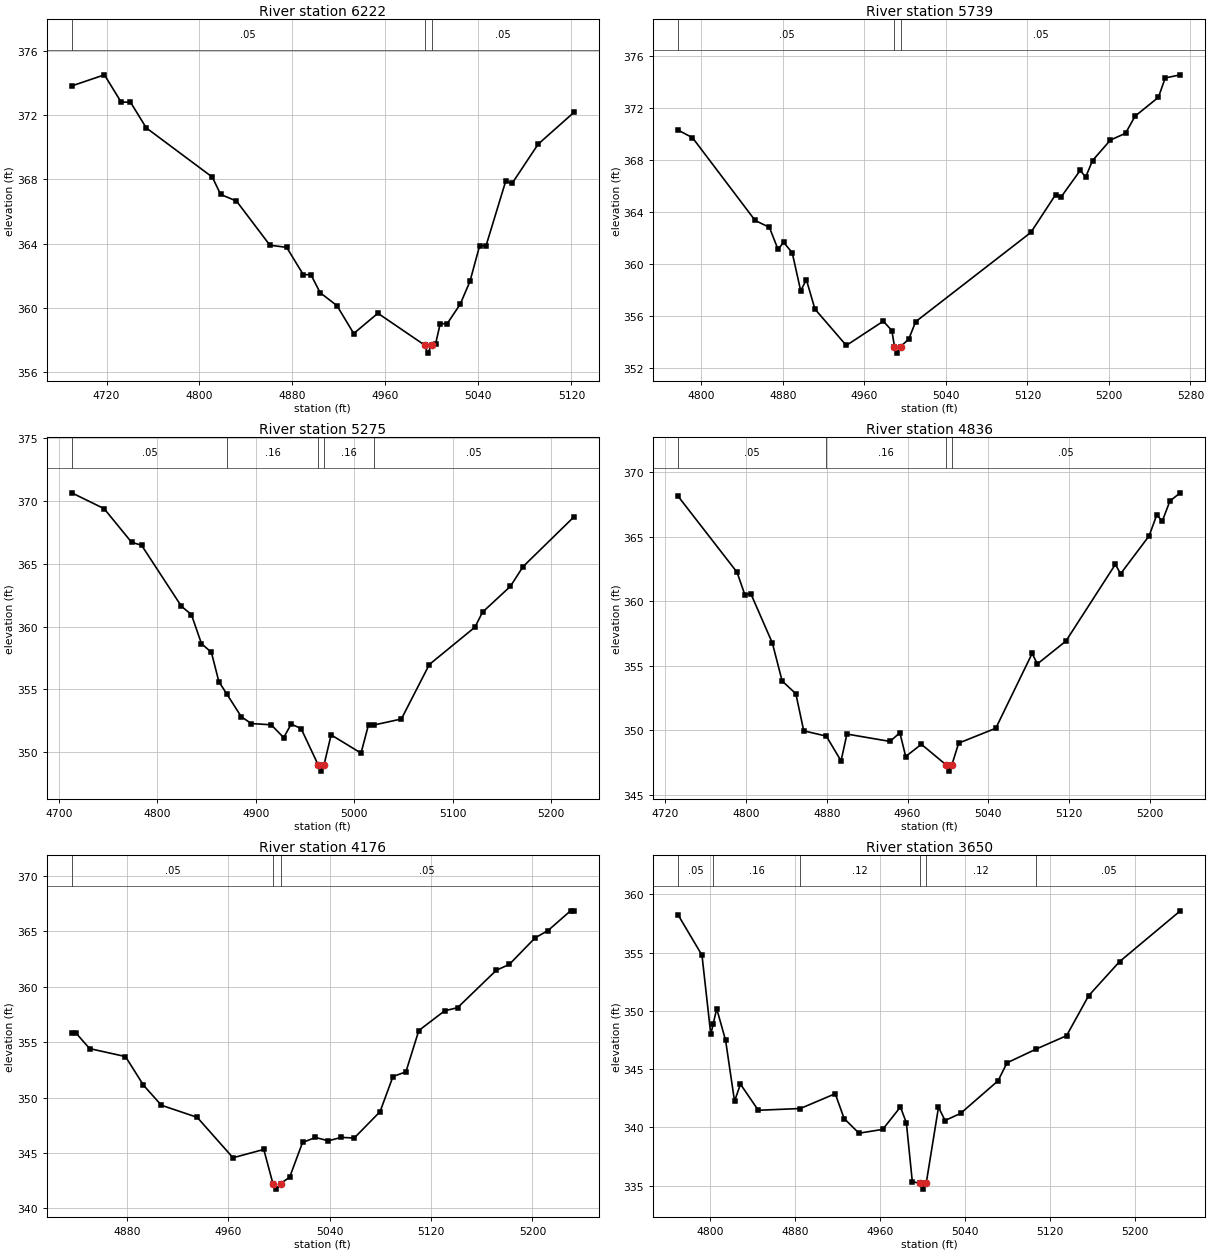
Type RM Length L Ch R = 1,6222,483,483,483
BEGIN DESCRIPTION:
UNT 172 IN BOCR 11.0
END DESCRIPTION:
XS GIS Cut Line= 3
      3729899.64     10659960.21      3729649.61     10659760.19
      3729549.61     10659710.19
#Sta/Elev= 30
  4690.1  373.82  4718.2  374.51  4732.6  372.81  4740.6  372.81  4754.2  371.21
  4811.0  368.15  4818.2  367.07  4831.8  366.66  4860.6  363.91  4875.0  363.78
  4889.4  362.07  4895.8  362.09  4903.8  360.96  4918.3  360.15  4932.7  358.42
  4953.5  359.68  4993.7  357.70  4996.4  357.20  4999.7  357.70  5003.1  357.76
  5007.1  359.03  5013.1  359.03  5024.3  360.24  5032.7  361.66  5041.0  363.87
  5046.6  363.89  5063.4  367.88  5069.0  367.76  5091.4  370.20  5122.1  372.17
#Mann=3,-1,0
  4690.1    0.05       0  4993.7    0.03       0  4999.7    0.05       0
Bank Sta=4993.7,4999.7
Exp/Cntr=0.3,0.1

Type RM Length L Ch R = 1,5739,464,464,464
BEGIN DESCRIPTION:
UNT 172 IN BOCR 10.0
END DESCRIPTION:
XS GIS Cut Line= 3
      3730199.65     10659610.21      3729999.61     10659510.19
      3729749.62     10659410.19
#Sta/Elev= 30
  4777.2  370.29  4791.2  369.71  4852.7  363.34  4866.7  362.81  4875.1  361.13
  4880.7  361.65  4889.1  360.86  4897.4  357.93  4903.0  358.78  4911.4  356.52
  4942.2  353.72  4978.5  355.59  4986.9  354.87  4989.5  353.63  4992.2  353.13
  4995.5  353.63  5003.5  354.21  5010.3  355.55  5123.4  362.42  5147.6  365.32
  5153.0  365.14  5171.8  367.19  5177.2  366.68  5183.9  367.95  5201.5  369.53
  5216.3  370.05  5225.7  371.37  5248.6  372.82  5255.3  374.31  5270.1  374.55
#Mann=3,-1,0
  4777.2    0.05       0  4989.5    0.03       0  4995.5    0.05       0
Bank Sta=4989.5,4995.5
Exp/Cntr=0.3,0.1

Type RM Length L Ch R = 1,5275,439,439,439
BEGIN DESCRIPTION:
UNT 172 IN BOCR 9.0
END DESCRIPTION:
XS GIS Cut Line= 3
      3730499.58     10659260.18      3730199.61     10659210.19
      3729999.58     10659160.18
#Sta/Elev= 30
  4712.9  370.62  4745.8  369.36  4773.7  366.69  4783.8  366.46  4824.4  361.60
  4834.5  360.95  4844.7  358.64  4854.8  357.95  4862.4  355.62  4870.7  354.61
  4885.2  352.83  4895.4  352.29  4915.6  352.19  4928.3  351.17  4935.9  352.25
  4946.0  351.89  4963.3  349.01  4966.1  348.51  4969.3  349.01  4976.5  351.39
  5006.9  349.94  5014.5  352.20  5020.3  352.18  5047.9  352.65  5076.3  356.98
  5122.7  359.95  5130.4  361.14  5158.7  363.19  5171.6  364.76  5223.2  368.70
#Mann=5,-1,0
  4712.9    0.05       0  4870.7    0.16       0  4963.3    0.07       0
  4969.3    0.16       0  5020.3    0.05       0
Bank Sta=4963.3,4969.3
Exp/Cntr=0.3,0.1

Type RM Length L Ch R = 1,4836,660,660,660
BEGIN DESCRIPTION:
UNT 172 IN BOCR 8.0
END DESCRIPTION:
XS GIS Cut Line= 3
      3730549.63     10659010.20      3730299.61     10658860.19
      3730099.64     10658810.20
#Sta/Elev= 30
  4732.7  368.11  4791.0  362.24  4798.8  360.48  4804.6  360.59  4826.0  356.76
  4835.7  353.82  4849.3  352.83  4857.1  349.96  4879.5  349.55  4894.1  347.63
  4899.9  349.71  4942.6  349.14  4952.4  349.81  4958.2  347.97  4973.7  348.92
  4998.0  347.34  5000.7  346.84  5004.0  347.34  5010.7  349.01  5047.5  350.16
  5083.5  355.95  5088.7  355.14  5117.0  356.91  5166.0  362.85  5171.2  362.12
  5199.5  365.06  5207.2  366.71  5212.4  366.17  5220.1  367.76  5230.4  368.39
#Mann=4,-1,0
  4732.7    0.05       0  4879.5    0.16       0  4998.0    0.07       0
  5004.0    0.05       0
Bank Sta=4998,5004
Exp/Cntr=0.3,0.1

Type RM Length L Ch R = 1,4176,526,526,526
BEGIN DESCRIPTION:
UNT 172 IN BOCR 7.0
END DESCRIPTION:
XS GIS Cut Line= 3
      3730649.61     10658610.19      3730549.61     10658510.19
      3730299.58     10658460.18
#Sta/Elev= 30
  4836.3  355.80  4839.8  355.80  4850.4  354.42  4878.7  353.70  4892.9  351.12
  4907.0  349.31  4935.3  348.22  4963.6  344.57  4987.9  345.32  4995.1  342.24
  4997.9  341.74  5001.1  342.24  5008.3  342.81  5018.5  345.95  5028.7  346.40
  5038.9  346.10  5049.1  346.41  5059.3  346.35  5079.7  348.73  5089.9  351.90
  5100.1  352.32  5110.3  356.05  5130.7  357.83  5140.9  358.11  5171.5  361.49
  5181.7  362.01  5202.1  364.41  5212.3  365.07  5230.1  366.85  5232.7  366.85
#Mann=3,-1,0
  4836.3    0.05       0  4995.1    0.03       0  5001.1    0.05       0
Bank Sta=4995.1,5001.1
Exp/Cntr=0.3,0.1

Type RM Length L Ch R = 1,3650,596,596,596
BEGIN DESCRIPTION:
UNT 172 IN BOCR 6.0
END DESCRIPTION:
XS GIS Cut Line= 3
      3730849.61     10658360.19      3730749.61     10658160.19
      3730549.61     10658010.19
#Sta/Elev= 30
  4769.6  358.21  4792.0  354.77  4800.3  347.97  4802.5  348.84  4805.9  350.18
  4814.3  347.45  4822.7  342.24  4828.3  343.70  4845.1  341.46  4884.8  341.61
  4917.7  342.88  4926.1  340.75  4940.1  339.49  4962.5  339.82  4979.2  341.74
  4984.8  340.38  4990.4  335.33  4997.5  335.19  5000.2  334.69  5003.5  335.19
  5015.1  341.72  5021.3  340.58  5035.9  341.19  5071.3  343.99  5079.7  345.53
  5107.4  346.72  5135.9  347.86  5156.7  351.29  5185.9  354.22  5243.2  358.58
#Mann=6,-1,0
  4769.6    0.05       0  4802.5    0.16       0  4884.8    0.12       0
  4997.5    0.07       0  5003.5    0.12       0  5107.4    0.05       0
Bank Sta=4997.5,5003.5
Exp/Cntr=0.3,0.1

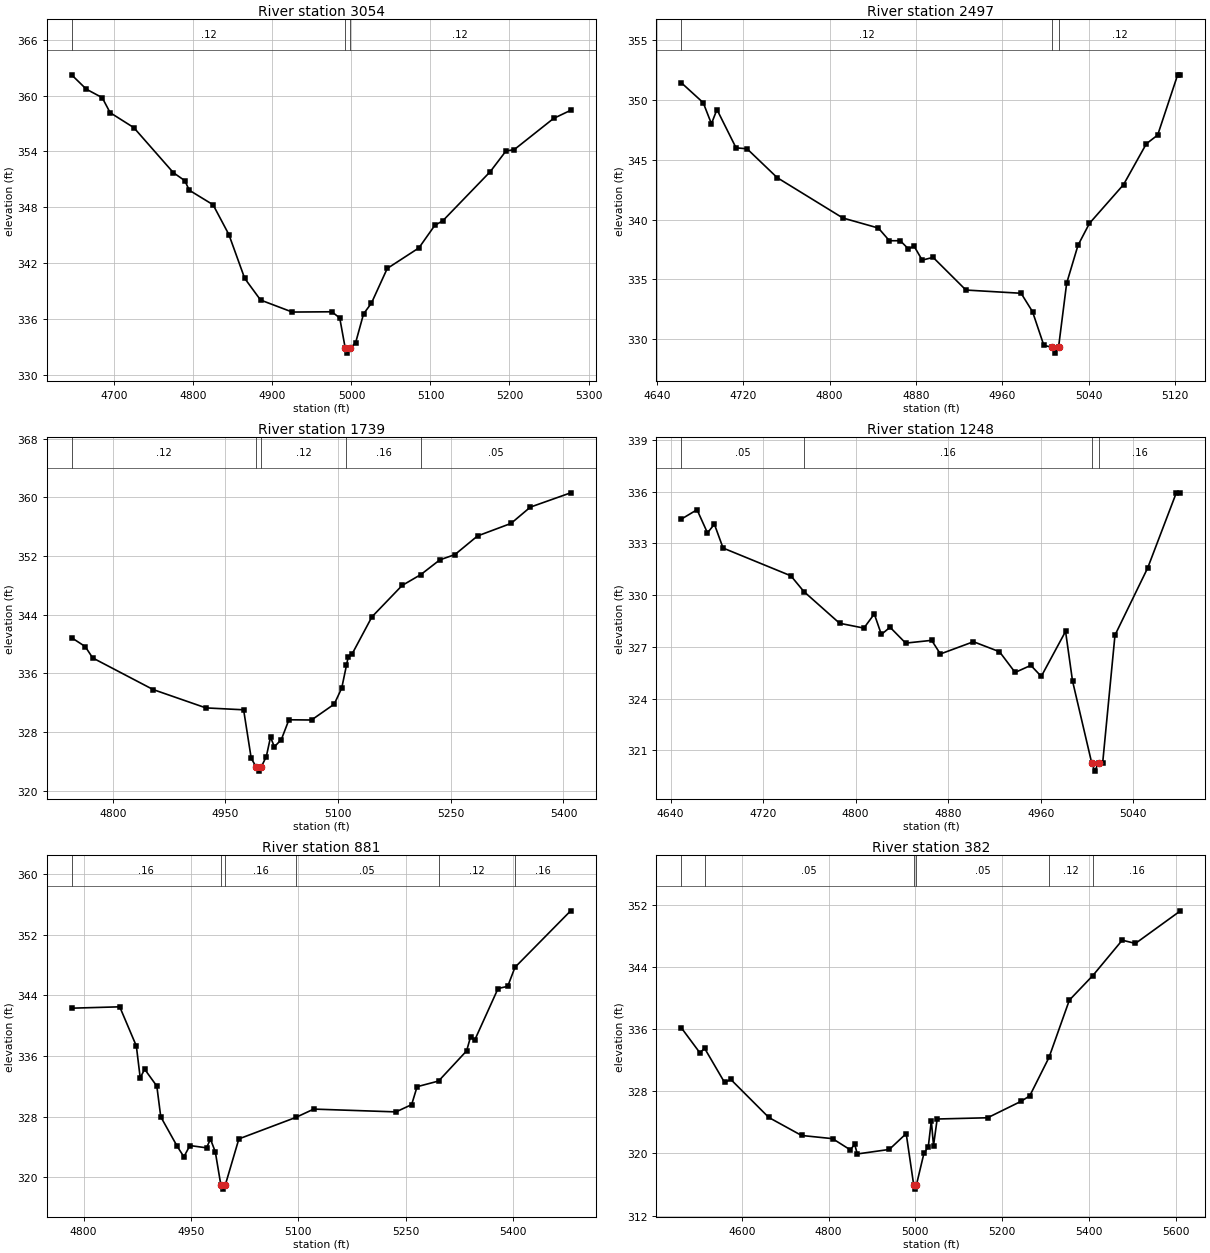
Type RM Length L Ch R = 1,3054,557,557,557
BEGIN DESCRIPTION:
UNT 172 IN BOCR 5.0
END DESCRIPTION:
XS GIS Cut Line= 2
      3731058.18     10657705.79      3730428.05     10657747.45
#Sta/Elev= 30
  4645.9  362.23  4664.5  360.69  4684.6  359.78  4694.6  358.17  4724.6  356.56
  4774.7  351.72  4789.1  350.87  4794.8  349.84  4824.9  348.28  4844.9  345.08
  4864.9  340.38  4885.0  338.05  4925.1  336.76  4975.2  336.79  4985.2  336.12
  4992.2  332.85  4995.0  332.35  4998.2  332.85  5005.3  333.47  5015.3  336.56
  5025.3  337.72  5045.3  341.44  5085.4  343.65  5105.5  346.07  5115.5  346.55
  5175.6  351.83  5195.7  354.07  5205.7  354.18  5255.8  357.55  5277.4  358.42
#Mann=3,-1,0
  4645.9    0.12       0  4992.2    0.07       0  4998.2    0.12       0
Bank Sta=4992.2,4998.2
Exp/Cntr=0.3,0.1

Type RM Length L Ch R = 1,2497,758,758,758
BEGIN DESCRIPTION:
UNT 172 IN BOCR 4.0
END DESCRIPTION:
XS GIS Cut Line= 3
      3730949.56     10657410.18      3730649.61     10657360.19
      3730499.61     10657410.19
#Sta/Elev= 30
  4662.7  351.42  4682.9  349.76  4690.5  348.00  4695.6  349.19  4713.3  345.99
  4723.5  345.91  4751.4  343.50  4812.2  340.13  4845.1  339.29  4855.3  338.23
  4865.4  338.23  4873.0  337.54  4878.1  337.79  4885.7  336.61  4895.8  336.84
  4926.2  334.11  4977.3  333.84  4987.9  332.30  4998.4  329.48  5006.0  329.34
  5008.7  328.84  5012.0  329.34  5019.5  334.68  5030.0  337.85  5040.6  339.68
  5072.2  342.92  5093.3  346.33  5103.8  347.06  5122.3  352.09  5124.9  352.09
#Mann=3,-1,0
  4662.7    0.12       0  5006.0    0.07       0  5012.0    0.12       0
Bank Sta=5006,5012
Exp/Cntr=0.3,0.1

Type RM Length L Ch R = 1,1739,491,491,491
BEGIN DESCRIPTION:
UNT 172 IN BOCR 3.0
END DESCRIPTION:
XS GIS Cut Line= 2
      3730917.62     10656940.16      3730256.17     10656877.66
#Sta/Elev= 30
  4745.2  340.87  4763.3  339.66  4773.3  338.11  4853.7  333.80  4924.0  331.30
  4974.2  331.04  4984.3  324.43  4991.3  323.18  4994.1  322.68  4997.3  323.18
  5004.4  324.66  5010.0  327.32  5015.1  325.99  5024.4  326.98  5034.5  329.68
  5064.6  329.65  5094.8  331.81  5104.8  334.00  5111.1  337.10  5113.4  338.23
  5118.4  338.61  5145.0  343.71  5185.2  347.99  5210.2  349.48  5235.4  351.48
  5255.5  352.20  5285.6  354.74  5330.2  356.45  5355.9  358.67  5409.6  360.62
#Mann=5,-1,0
  4745.2    0.12       0  4991.3    0.07       0  4997.3    0.12       0
  5111.1    0.16       0  5210.2    0.05       0
Bank Sta=4991.3,4997.3
Exp/Cntr=0.3,0.1

Type RM Length L Ch R = 1,1248,367,367,367
BEGIN DESCRIPTION:
UNT 172 IN BOCR 2.0
END DESCRIPTION:
XS GIS Cut Line= 3
      3730849.60     10656760.18      3730549.61     10656560.19
      3730499.58     10656510.16
#Sta/Elev= 30
  4649.4  334.41  4662.9  334.95  4671.9  333.61  4677.9  334.11  4685.4  332.73
  4744.0  331.12  4755.2  330.21  4786.1  328.37  4807.1  328.09  4816.1  328.91
  4822.2  327.72  4829.7  328.14  4843.2  327.22  4865.7  327.38  4873.2  326.59
  4901.8  327.30  4924.3  326.72  4937.8  325.52  4951.4  325.93  4960.4  325.29
  4981.4  327.90  4987.4  325.03  5003.9  320.30  5006.7  319.80  5009.9  320.30
  5013.5  320.30  5024.1  327.68  5052.4  331.58  5077.1  335.93  5080.7  335.93
#Mann=4,-1,0
  4649.4    0.05       0  4755.2    0.16       0  5003.9    0.07       0
  5009.9    0.16       0
Bank Sta=5003.9,5009.9
Exp/Cntr=0.3,0.1

Type RM Length L Ch R = 1,881,499,499,499
BEGIN DESCRIPTION:
Mapping XS 8b16ff40
END DESCRIPTION:
XS GIS Cut Line= 2
      3731042.57     10656544.31      3730407.15     10656257.86
#Sta/Elev= 30
  4783.4  342.32  4850.6  342.50  4873.8  337.32  4879.2  333.11  4885.4  334.25
  4902.4  332.02  4907.9  327.96  4931.0  324.04  4940.2  322.67  4948.6  324.16
  4971.8  323.86  4977.3  325.01  4984.1  323.32  4991.9  318.90  4994.7  318.40
  4997.9  318.90  5017.0  325.04  5096.3  327.87  5121.6  328.98  5236.4  328.61
  5258.3  329.57  5265.9  331.94  5295.9  332.69  5335.1  336.68  5340.7  338.57
  5346.2  338.06  5379.0  344.92  5392.5  345.21  5402.6  347.72  5480.4  355.19
#Mann=6,-1,0
  4783.4    0.16       0  4991.9    0.07       0  4997.9    0.16       0
  5096.3    0.05       0  5295.9    0.12       0  5402.6    0.16       0
Bank Sta=4991.9,4997.9
Exp/Cntr=0.3,0.1

Type RM Length L Ch R = 1,382,0,0,0
BEGIN DESCRIPTION:
UNT 172 IN BOCR 1.0
END DESCRIPTION:
XS GIS Cut Line= 4
      3731084.27     10656481.85      3731000.93     10656065.16
      3730792.60     10656023.49      3730287.40     10656112.03
#Sta/Elev= 30
  4460.8  336.17  4503.3  332.97  4514.3  333.54  4560.2  329.15  4574.7  329.53
  4662.2  324.64  4737.8  322.32  4809.2  321.91  4850.0  320.47  4860.2  321.17
  4866.2  319.94  4939.9  320.52  4978.9  322.56  4996.3  315.91  4999.0  315.41
  5002.3  315.91  5019.7  320.00  5029.9  320.89  5036.8  324.22  5041.9  321.01
  5050.3  324.44  5166.6  324.60  5243.4  326.71  5263.7  327.42  5308.1  332.37
  5355.0  339.75  5409.2  342.92  5476.9  347.47  5507.3  347.05  5611.1  351.25
#Mann=6,-1,0
  4460.8    0.16       0  4514.3    0.05       0  4996.3    0.03       0
  5002.3    0.05       0  5308.1    0.12       0  5409.2    0.16       0
Bank Sta=4996.3,5002.3
Exp/Cntr=0.3,0.1

Chan Stop Cuts=-1