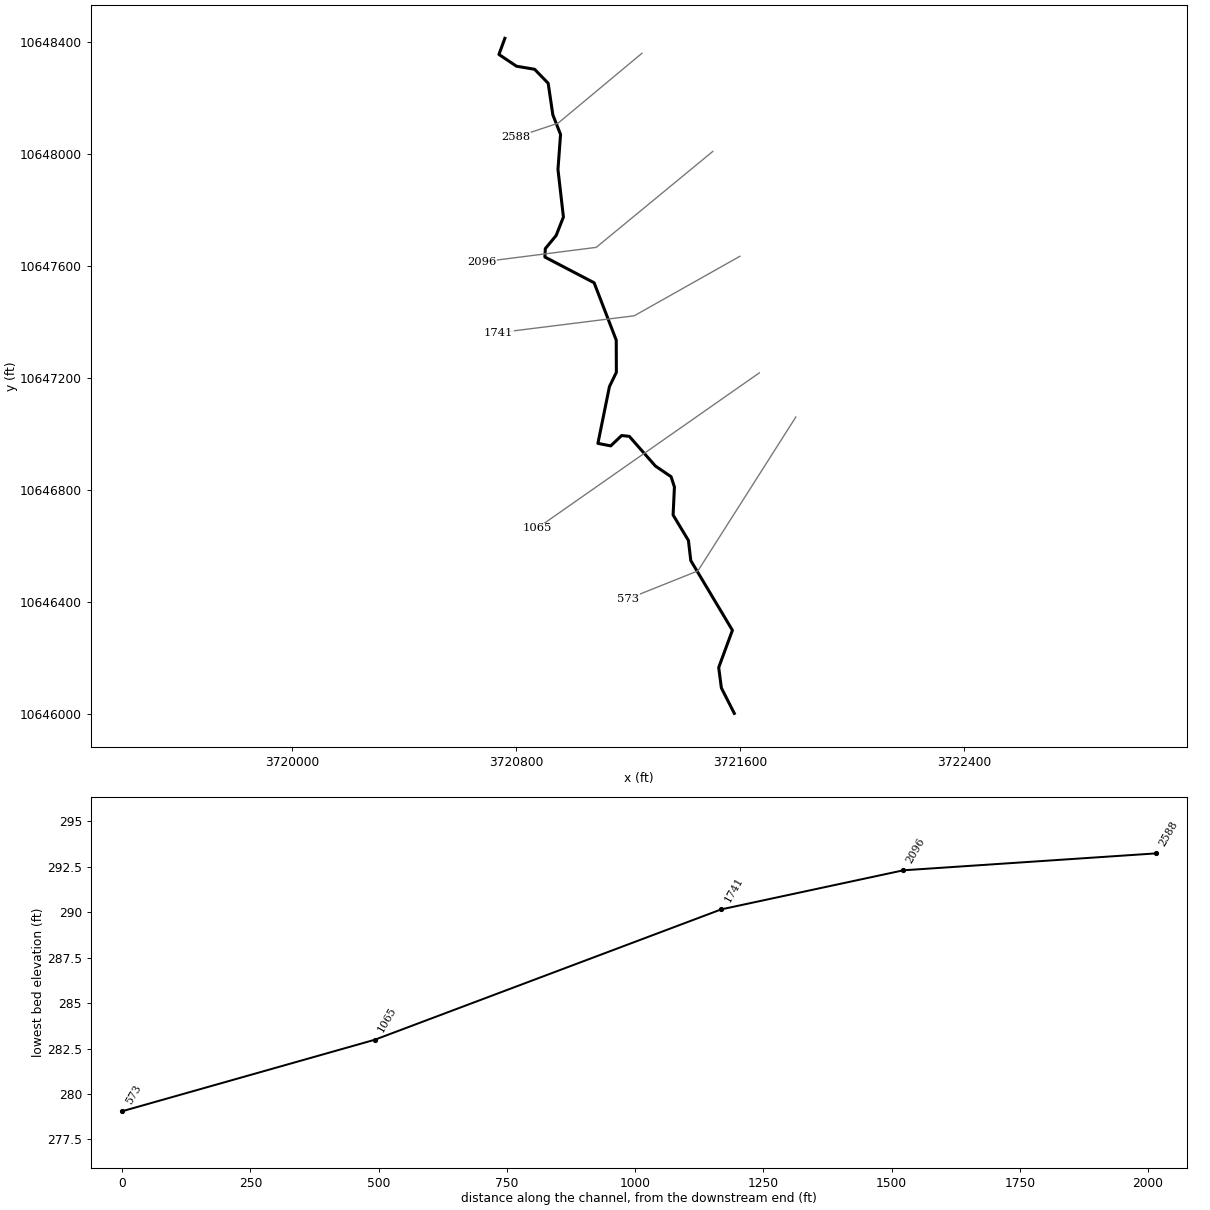
--- UNT 173 IN BOCR.prj (project) ---

Proj Title=UNT 173 IN BOCR Base Level Engineering
Current Plan=p01
Default Exp/Contr=0.3,0.1
English Units
Geom File=g01
Flow File=f01
Plan File=p01
Y Axis Title=Elevation
X Axis Title(PF)=Main Channel Distance
X Axis Title(XS)=Station
BEGIN DESCRIPTION:
UNT 173 IN BOCR
END DESCRIPTION:
DSS Export Rating Curves= 0
DSS Export Rating Curve Sorted= 0
DSS Export Volume Flow Curves= 0
DXF OffsetX= 0
DXF OffsetY= 0
DXF ScaleX= 1
DXF ScaleY= 10

--- UNT 173 IN BOCR.p01 (plan) ---

Plan Title=Multiple Run
Short Identifier=Multiple
Geom File=g01
Flow File=f01
Subcritical Flow
K Sum by GR= 0
Std Step Tol= 0.01
Critical Tol= 0.01
Num of Std Step Trials= 20
Max Error Tol= 0.3
Flow Tol Ratio= 0.001
Split Flow NTrial= 30
Split Flow Tol= 0.02
Split Flow Ratio= 0.02
Log Output Level= 0
Friction Slope Method= 1
Unsteady Friction Slope Method= 2
Unsteady Bridges Friction Slope Method= 1
Parabolic Critical Depth
Global Vel Dist=  1 , 1 , 1
Global Log Level= 0
CheckData=True
Encroach Param= -1, 0, 0, 0
BEGIN DESCRIPTION:
Multiple Run
END DESCRIPTION:

--- UNT 173 IN BOCR.f01 (steady flow) ---

Flow Title=Multiple
Program Version=4.10
Number of Profiles= 7
Profile Names=10-year,25-year,50-year,1pct_min,100-year,1pct_plu,500-year
River Rch & RM=UNT 173 IN BOCR,Reach-1         ,2588
     402     529     631     554     749    1013    1058
Boundary for River Rch & Prof#=UNT 173 IN BOCR,Reach-1         , 1
Up Type= 0
Dn Type= 3
Dn Slope=0.007
Boundary for River Rch & Prof#=UNT 173 IN BOCR,Reach-1         , 2
Up Type= 0
Dn Type= 3
Dn Slope=0.007
Boundary for River Rch & Prof#=UNT 173 IN BOCR,Reach-1         , 3
Up Type= 0
Dn Type= 3
Dn Slope=0.007
Boundary for River Rch & Prof#=UNT 173 IN BOCR,Reach-1         , 4
Up Type= 0
Dn Type= 3
Dn Slope=0.007
Boundary for River Rch & Prof#=UNT 173 IN BOCR,Reach-1         , 5
Up Type= 0
Dn Type= 3
Dn Slope=0.007
Boundary for River Rch & Prof#=UNT 173 IN BOCR,Reach-1         , 6
Up Type= 0
Dn Type= 3
Dn Slope=0.007
Boundary for River Rch & Prof#=UNT 173 IN BOCR,Reach-1         , 7
Up Type= 0
Dn Type= 3
Dn Slope=0.007
DSS Import GetInterval= 0
DSS Import GetPeak= 0
DSS Import FillOption= 0

--- UNT 173 IN BOCR.g01 (geometry) ---

Geom Title=Existing Conditions
Program Version=4.10

River Reach=UNT 173 IN BOCR ,Reach-1
Reach XY= 30
      3720759.72     10648413.62       3720738.5       10648356.
      3720801.25       10648314.        3720866.       10648303.
       3720914.5       10648253.      3720931.25       10648140.
      3720958.75       10648070.       3720949.5       10647945.
        3720969.       10647775.        3720943.       10647709.
      3720904.25       10647662.      3720902.75       10647632.
      3721078.75       10647540.      3721157.75       10647335.
      3721158.25       10647220.       3721133.5       10647169.
      3721092.25       10646966.        3721138.       10646957.
        3721177.       10646994.       3721204.5       10646991.
      3721297.75       10646885.      3721353.75       10646847.
      3721365.75       10646810.        3721361.       10646710.
      3721415.75       10646619.      3721424.25       10646547.
        3721573.       10646298.        3721524.       10646165.
       3721533.5       10646092.      3721579.75       10646001.

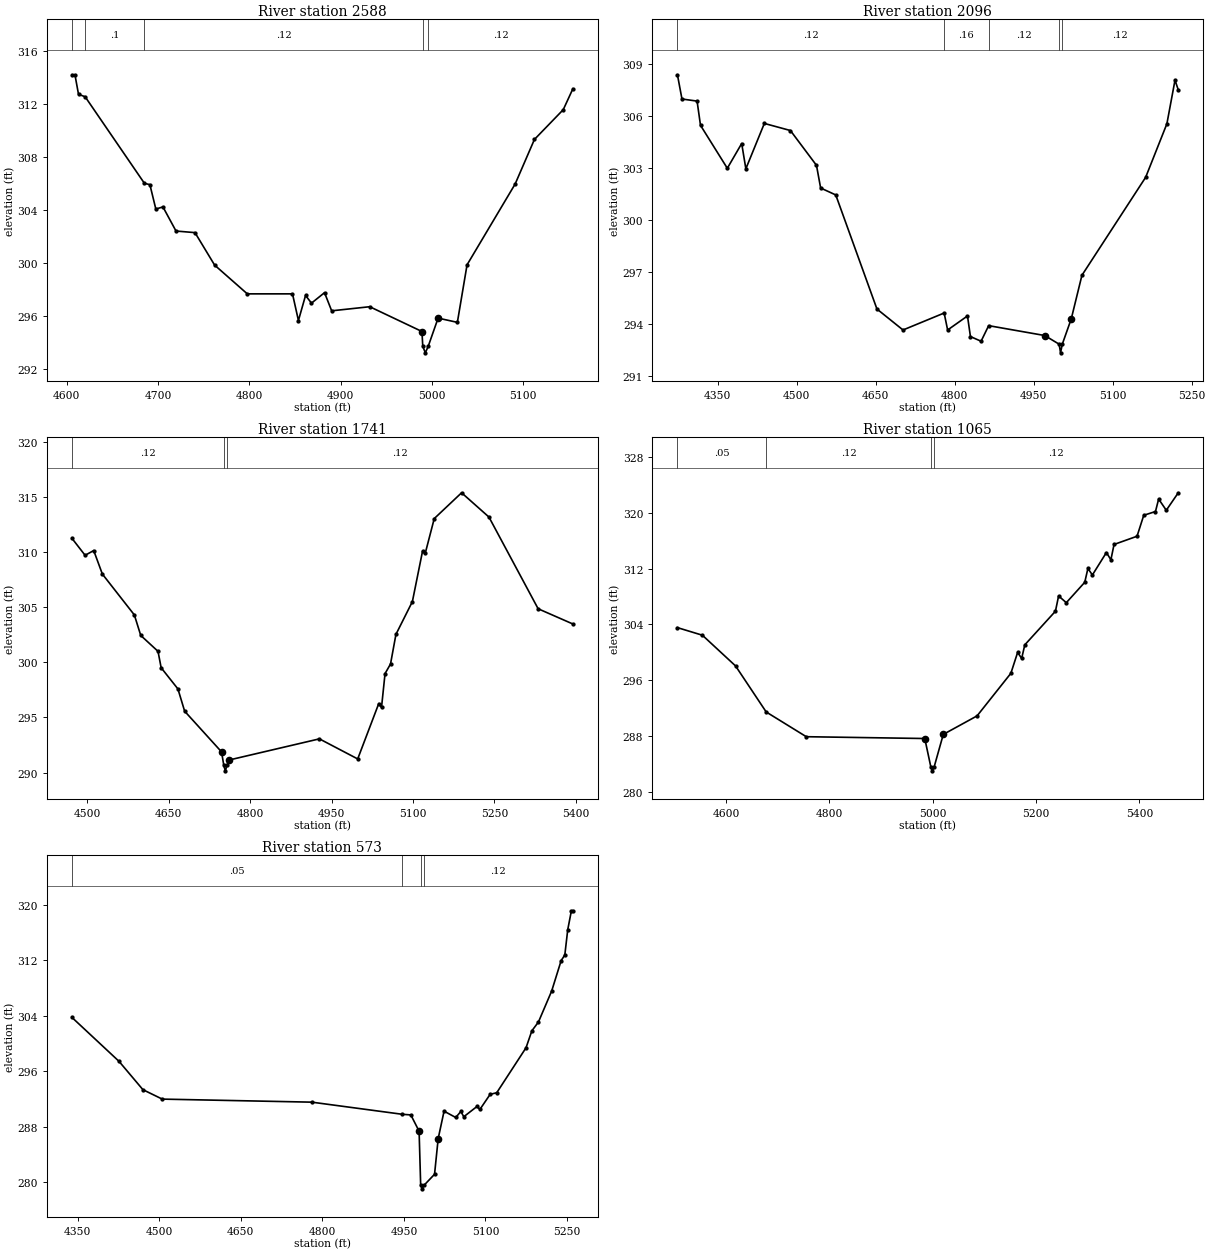
Type RM Length L Ch R = 1 ,2588    ,492,492,492
BEGIN DESCRIPTION:
UNT 173 IN BOCR 5.0
END DESCRIPTION:
XS GIS Cut Line= 3
       3721249.6     10648360.18      3720949.61     10648110.19
      3720799.62     10648060.19
#Sta/Elev= 30
  4605.7  314.22  4608.9  314.22  4612.8  312.75  4620.1  312.56    4685  306.03
    4691  305.93  4697.5  304.09  4705.3  304.25  4719.6  302.43  4740.4  302.31
  4761.9  299.86  4797.7  297.69  4847.2  297.69  4853.7  295.68  4861.5  297.57
    4868  296.99  4882.3  297.78  4890.1  296.41  4931.8  296.72    4989  294.85
  4989.9  293.74  4992.7  293.24  4995.9  293.74  5006.7  295.86  5027.8  295.54
  5038.4  299.88  5091.1  305.98  5112.2  309.34  5143.8  311.59  5154.3  313.16
#Mann= 5 ,-1 , 0
  4605.7     .16       0  4620.1      .1       0    4685     .12       0
  4989.9     .07       0  4995.9     .12       0
Bank Sta=4989,5006.7
XS Rating Curve= 0 ,0
Exp/Cntr=0.3,0.1

Type RM Length L Ch R = 1 ,2096    ,355,355,355
BEGIN DESCRIPTION:
UNT 173 IN BOCR 4.0
END DESCRIPTION:
XS GIS Cut Line= 3
      3721502.82     10648009.41      3721086.17     10647666.53
      3720678.17     10647614.45
#Sta/Elev= 30
  4273.6  308.37  4282.2  306.97  4310.9  306.85  4317.4  305.45  4368.3  302.97
  4395.6   304.4  4403.5  302.94  4438.6  305.56  4488.1  305.15  4537.6  303.14
  4545.5  301.83  4574.2  301.43  4652.4  294.84  4701.9  293.63    4780  294.61
  4786.6  293.63  4824.3  294.44  4829.9  293.25  4850.1  292.98  4864.5  293.88
    4971  293.31  4998.3  292.81    5001  292.31  5004.3  292.81  5021.4  294.28
  5041.6  296.79  5162.6  302.45  5202.9  305.54  5218.3  308.06  5224.5   307.5
#Mann= 5 ,-1 , 0
  4273.6     .12       0    4780     .16       0  4864.5     .12       0
  4998.3     .07       0  5004.3     .12       0
Bank Sta=4971,5021.4
XS Rating Curve= 0 ,0
Exp/Cntr=0.3,0.1

Type RM Length L Ch R = 1 ,1741    ,676,676,676
BEGIN DESCRIPTION:
UNT 173 IN BOCR 3.0
END DESCRIPTION:
XS GIS Cut Line= 3
       3721599.7     10647634.68      3721222.12     10647422.02
      3720736.06     10647361.26
#Sta/Elev= 30
  4471.5  311.24  4495.6  309.71  4511.5  310.14  4527.4  308.01  4586.4   304.3
  4598.2  302.44    4630     301  4635.8  299.51  4666.7  297.59  4679.1  295.57
  4747.1  291.88  4751.3  290.66    4754  290.16  4757.3  290.66    4760  291.13
  4927.5  293.06  4998.1  291.24  5036.9  296.26    5042  295.91  5048.5  298.98
  5058.6  299.85  5068.6  302.54  5098.9  305.51  5117.6  310.08  5122.6  309.89
  5139.2  313.04  5189.6  315.38    5240  313.18  5330.7  304.86  5394.7  303.48
#Mann= 3 ,-1 , 0
  4471.5     .12       0  4751.3     .07       0  4757.3     .12       0
Bank Sta=4747.1,4760
XS Rating Curve= 0 ,0
Exp/Cntr=0.3,0.1

Type RM Length L Ch R = 1 ,1065    ,492,492,492
BEGIN DESCRIPTION:
UNT 173 IN BOCR 2.0
END DESCRIPTION:
XS GIS Cut Line= 2
      3721669.16     10647218.01      3720874.87     10646662.45
#Sta/Elev= 30
  4505.9  303.54  4554.2  302.45  4618.4  298.04  4677.7  291.43  4755.3  287.88
  4984.6  287.62  4996.5  283.48  4999.2  282.98  5002.5  283.48  5020.4  288.21
  5085.8  290.87  5151.2  296.98  5164.3  299.98  5172.1  299.12  5178.2  301.07
  5237.5   305.9  5243.6  308.09  5258.5  307.12  5294.2  310.05  5300.3  312.03
    5309   311.1  5336.1  314.32  5344.8  313.28  5350.9  315.48  5395.4  316.66
  5408.4  319.67  5431.1  320.21  5437.2     322    5452  320.39  5475.2   322.9
#Mann= 4 ,-1 , 0
  4505.9     .05       0  4677.7     .12       0  4996.5     .07       0
  5002.5     .12       0
Bank Sta=4984.6,5020.4
XS Rating Curve= 0 ,0
Exp/Cntr=0.3,0.1

Type RM Length L Ch R = 1 ,573     ,0,0,0
BEGIN DESCRIPTION:
UNT 173 IN BOCR 1.0
END DESCRIPTION:
XS GIS Cut Line= 3
      3721799.63     10647060.22      3721449.61     10646510.19
      3721199.63      10646410.2
#Sta/Elev= 30
  4339.6  303.76    4426  297.44    4470  293.35  4505.6  291.99  4780.7  291.55
  4947.2   289.8  4962.8  289.71    4978  287.36  4980.9  279.55  4983.7  279.05
  4986.9  279.55  5006.4  281.15  5013.1   286.3  5023.9  290.25  5045.4  289.34
  5054.8  290.21  5060.2  289.45  5084.5  290.93  5089.8   290.5  5108.7  292.68
  5120.8  292.91  5174.7   299.4  5185.4  301.84  5197.5  303.11  5221.8  307.57
  5239.3  311.97    5246  312.77  5251.4  316.43  5258.1  319.15  5260.8  319.15
#Mann= 4 ,-1 , 0
  4339.6     .05       0  4947.2     .12       0  4980.9     .07       0
  4986.9     .12       0
Bank Sta=4978,5013.1
XS Rating Curve= 0 ,0
Exp/Cntr=0.3,0.1

Chan Stop Cuts=-1
Use User Specified Reach Order=0
Composite Channel Slope=5