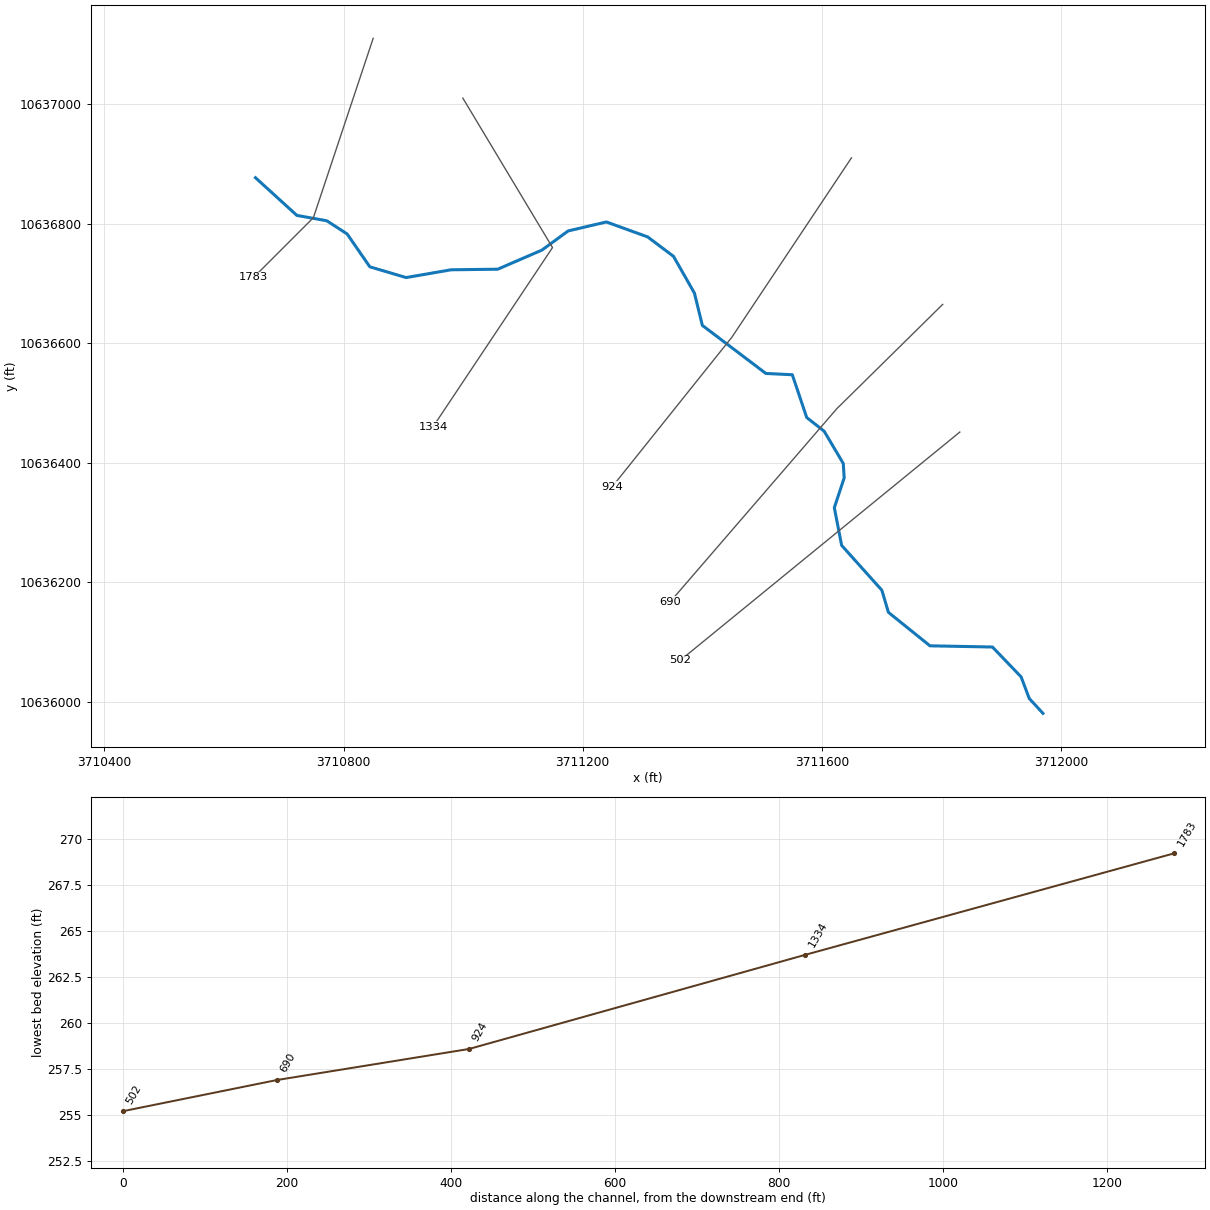
--- UNT 174 IN BOCR.prj (project) ---

Proj Title=UNT 174 IN BOCR Base Level Engineering
Current Plan=p01
Default Exp/Contr=0.3,0.1
English Units
Geom File=g01
Flow File=f01
Plan File=p01
BEGIN DESCRIPTION:
UNT 174 IN BOCR
END DESCRIPTION:

--- UNT 174 IN BOCR.p01 (plan) ---

Plan Title=Multiple Run
Short Identifier=Multiple
Geom File=g01
Flow File=f01
Subcritical Flow
K Sum by GR= 0
Std Step Tol= 0.01
Critical Tol= 0.01
Num of Std Step Trials= 20
Max Error Tol= 0.3
Flow Tol Ratio= 0.001
Split Flow NTrial= 30
Split Flow Tol= 0.02
Split Flow Ratio= 0.02
Log Output Level= 0
Friction Slope Method= 1
Unsteady Friction Slope Method= 2
Unsteady Bridges Friction Slope Method= 1
Parabolic Critical Depth
Global Vel Dist=  1 , 1 , 1
Global Log Level= 0
CheckData=True
Encroach Param= -1, 0, 0, 0
BEGIN DESCRIPTION:
Multiple Run
END DESCRIPTION:

--- UNT 174 IN BOCR.f01 (steady flow) ---

Flow Title=Multiple
Number of Profiles=7
Profile Names=10-year,25-year,50-year,1pct_min,100-year,1pct_plu,500-year
River Rch & RM= UNT 174 IN BOCR,Reach-1,1783
     387     510     609     535     724     979    1025
Boundary for River Rch & Prof#=UNT 174 IN BOCR,Reach-1,1
Up Type=0
Dn Type=3
Dn Slope=0.005
Boundary for River Rch & Prof#=UNT 174 IN BOCR,Reach-1,2
Up Type=0
Dn Type=3
Dn Slope=0.005
Boundary for River Rch & Prof#=UNT 174 IN BOCR,Reach-1,3
Up Type=0
Dn Type=3
Dn Slope=0.005
Boundary for River Rch & Prof#=UNT 174 IN BOCR,Reach-1,4
Up Type=0
Dn Type=3
Dn Slope=0.005
Boundary for River Rch & Prof#=UNT 174 IN BOCR,Reach-1,5
Up Type=0
Dn Type=3
Dn Slope=0.005
Boundary for River Rch & Prof#=UNT 174 IN BOCR,Reach-1,6
Up Type=0
Dn Type=3
Dn Slope=0.005
Boundary for River Rch & Prof#=UNT 174 IN BOCR,Reach-1,7
Up Type=0
Dn Type=3
Dn Slope=0.005

--- UNT 174 IN BOCR.g01 (geometry) ---

Geom Title=Existing Conditions

River Reach=UNT 174 IN BOCR,Reach-1
Reach XY= 30
      3710652.75     10636877.00      3710722.00     10636814.00
      3710772.00     10636805.00      3710806.00     10636783.00
      3710844.00     10636728.00      3710904.75     10636710.00
      3710980.00     10636723.00      3711058.00     10636724.00
      3711132.00     10636756.00      3711175.75     10636788.00
      3711239.75     10636803.00      3711308.75     10636778.00
      3711352.03     10636745.43      3711387.00     10636684.00
      3711400.25     10636630.00      3711506.46     10636549.61
      3711550.73     10636547.44      3711574.83     10636475.89
      3711604.00     10636453.00      3711636.00     10636399.00
      3711637.50     10636375.00      3711621.00     10636325.00
      3711633.25     10636262.00      3711700.50     10636187.00
      3711711.50     10636150.00      3711781.00     10636094.00
      3711885.50     10636092.00      3711933.50     10636042.00
      3711947.00     10636006.00      3711970.00     10635981.00

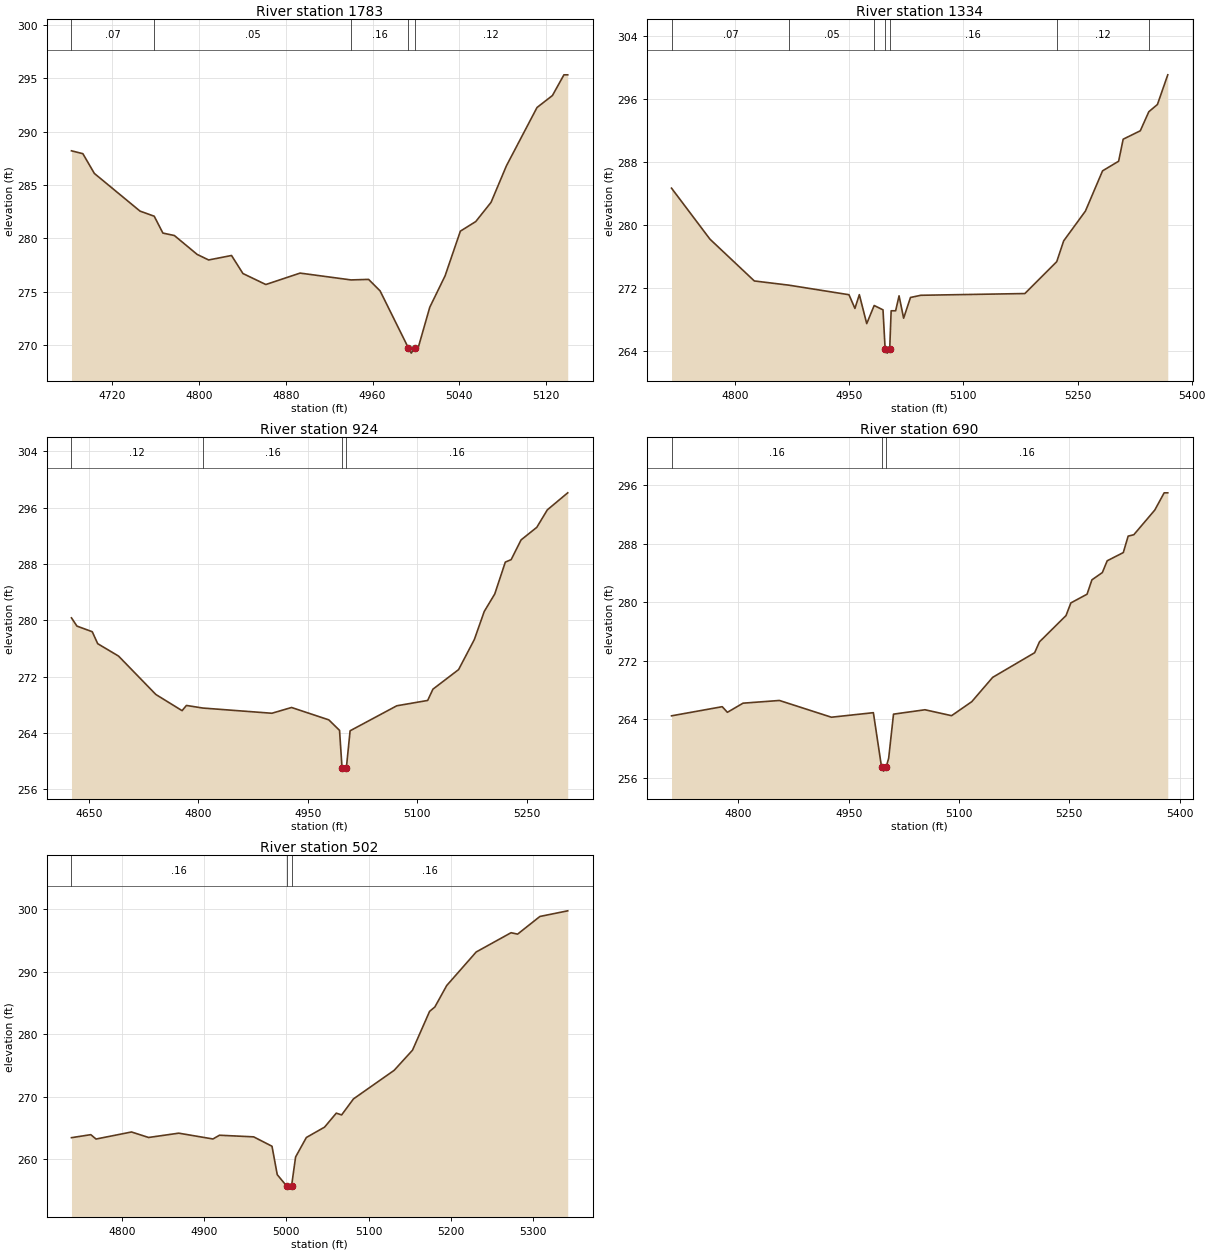
Type RM Length L Ch R = 1,1783,449,449,449
BEGIN DESCRIPTION:
UNT 174 IN BOCR 3.0
END DESCRIPTION:
XS GIS Cut Line= 3
      3710849.60     10637110.17      3710749.61     10636810.19
      3710649.63     10636710.21
#Sta/Elev= 30
  4682.4  288.20  4692.9  287.93  4703.5  286.08  4745.6  282.55  4758.7  282.07
  4766.7  280.49  4777.3  280.26  4798.3  278.49  4808.9  277.97  4830.0  278.39
  4840.5  276.70  4861.6  275.67  4893.2  276.74  4940.2  276.10  4956.4  276.15
  4967.0  275.07  4993.0  269.74  4995.7  269.24  4999.0  269.74  5002.1  269.74
  5012.8  273.54  5026.9  276.48  5041.0  280.67  5055.2  281.57  5069.3  283.37
  5083.5  286.80  5111.7  292.26  5125.9  293.38  5136.5  295.32  5140.0  295.32
#Mann=5,-1,0
  4682.4    0.07       0  4758.7    0.05       0  4940.2    0.16       0
  4993.0    0.07       0  4999.0    0.12       0
Bank Sta=4993,4999
Exp/Cntr=0.3,0.1

Type RM Length L Ch R = 1,1334,410,410,410
BEGIN DESCRIPTION:
UNT 174 IN BOCR 2.0
END DESCRIPTION:
XS GIS Cut Line= 3
      3710999.63     10637010.15      3711149.61     10636760.19
      3710949.58     10636460.15
#Sta/Elev= 30
  4716.5  284.68  4767.0  278.20  4825.3  272.89  4871.1  272.35  4949.7  271.14
  4957.5  269.40  4963.3  271.15  4973.0  267.47  4982.8  269.77  4994.4  269.22
  4997.2  264.22  5000.0  263.72  5003.2  264.22  5005.1  269.10  5011.0  269.10
  5015.5  271.00  5021.5  268.16  5030.5  270.79  5044.1  271.07  5180.8  271.29
  5222.7  275.34  5231.8  277.98  5260.4  281.77  5282.9  286.88  5304.0  288.10
  5310.0  290.90  5332.5  291.97  5343.7  294.39  5355.0  295.31  5368.6  299.08
#Mann=7,-1,0
  4716.5    0.07       0  4871.1    0.05       0  4982.8    0.16       0
  4997.2    0.07       0  5003.2    0.16       0  5222.7    0.12       0
  5343.7    0.16       0
Bank Sta=4997.2,5003.2
Exp/Cntr=0.3,0.1

Type RM Length L Ch R = 1,924,234,234,234
BEGIN DESCRIPTION:
UNT 174 IN BOCR 1.0
END DESCRIPTION:
XS GIS Cut Line= 3
      3711649.60     10636910.18      3711449.61     10636610.19
      3711249.61     10636360.19
#Sta/Elev= 30
  4625.8  280.36  4633.3  279.19  4654.3  278.39  4661.8  276.69  4690.4  274.93
  4741.5  269.48  4777.5  267.18  4783.5  267.92  4805.9  267.55  4900.7  266.81
  4927.7  267.63  4978.8  265.87  4993.5  264.38  4996.9  259.09  4999.7  258.59
  5002.9  259.09  5008.0  264.32  5072.0  267.87  5114.4  268.63  5121.6  270.23
  5156.8  273.01  5178.4  277.28  5192.0  281.27  5206.4  283.75  5220.9  288.28
  5228.9  288.63  5242.5  291.43  5264.1  293.22  5278.5  295.70  5306.5  298.12
#Mann=4,-1,0
  4625.8    0.12       0  4805.9    0.16       0  4996.9    0.07       0
  5002.9    0.16       0
Bank Sta=4996.9,5002.9
Exp/Cntr=0.3,0.1

Type RM Length L Ch R = 1,690,188,188,188
BEGIN DESCRIPTION:
Mapping XS 53c3c1e9
END DESCRIPTION:
XS GIS Cut Line= 3
      3711802.27     10636665.13      3711625.18     10636490.65
      3711346.55     10636167.75
#Sta/Elev= 30
  4708.9  264.46  4777.9  265.71  4784.9  264.94  4806.2  266.19  4855.7  266.56
  4926.4  264.27  4983.5  264.89  4994.7  257.40  4997.5  256.90  5000.7  257.40
  5004.3  258.66  5010.9  264.69  5053.7  265.29  5089.9  264.48  5117.3  266.39
  5145.8  269.72  5202.9  273.09  5209.5  274.58  5245.6  278.17  5252.2  279.90
  5274.2  281.09  5280.8  283.05  5295.0  284.05  5301.6  285.66  5323.5  286.78
  5330.1  289.03  5337.8  289.22  5366.3  292.59  5379.1  294.95  5384.0  294.95
#Mann=3,-1,0
  4708.9    0.16       0  4994.7    0.07       0  5000.7    0.16       0
Bank Sta=4994.7,5000.7
Exp/Cntr=0.3,0.1

Type RM Length L Ch R = 1,502,0,0,0
BEGIN DESCRIPTION:
Mapping XS a855fc63
END DESCRIPTION:
XS GIS Cut Line= 2
      3711830.91     10636451.58      3711363.40     10636069.79
#Sta/Elev= 30
  4738.7  263.43  4762.2  263.91  4768.6  263.21  4811.7  264.34  4832.5  263.46
  4869.2  264.15  4910.8  263.22  4918.7  263.82  4960.3  263.56  4982.6  262.06
  4989.0  257.51  5000.4  255.70  5003.2  255.20  5006.4  255.70  5011.3  260.34
  5024.4  263.46  5046.5  265.11  5060.8  267.35  5067.3  267.07  5081.7  269.63
  5131.2  274.20  5153.5  277.42  5174.3  283.63  5180.7  284.33  5195.1  287.76
  5231.0  293.13  5273.4  296.21  5281.3  295.98  5308.5  298.81  5342.3  299.71
#Mann=3,-1,0
  4738.7    0.16       0  5000.4    0.07       0  5006.4    0.16       0
Bank Sta=5000.4,5006.4
Exp/Cntr=0.3,0.1

Chan Stop Cuts=-1