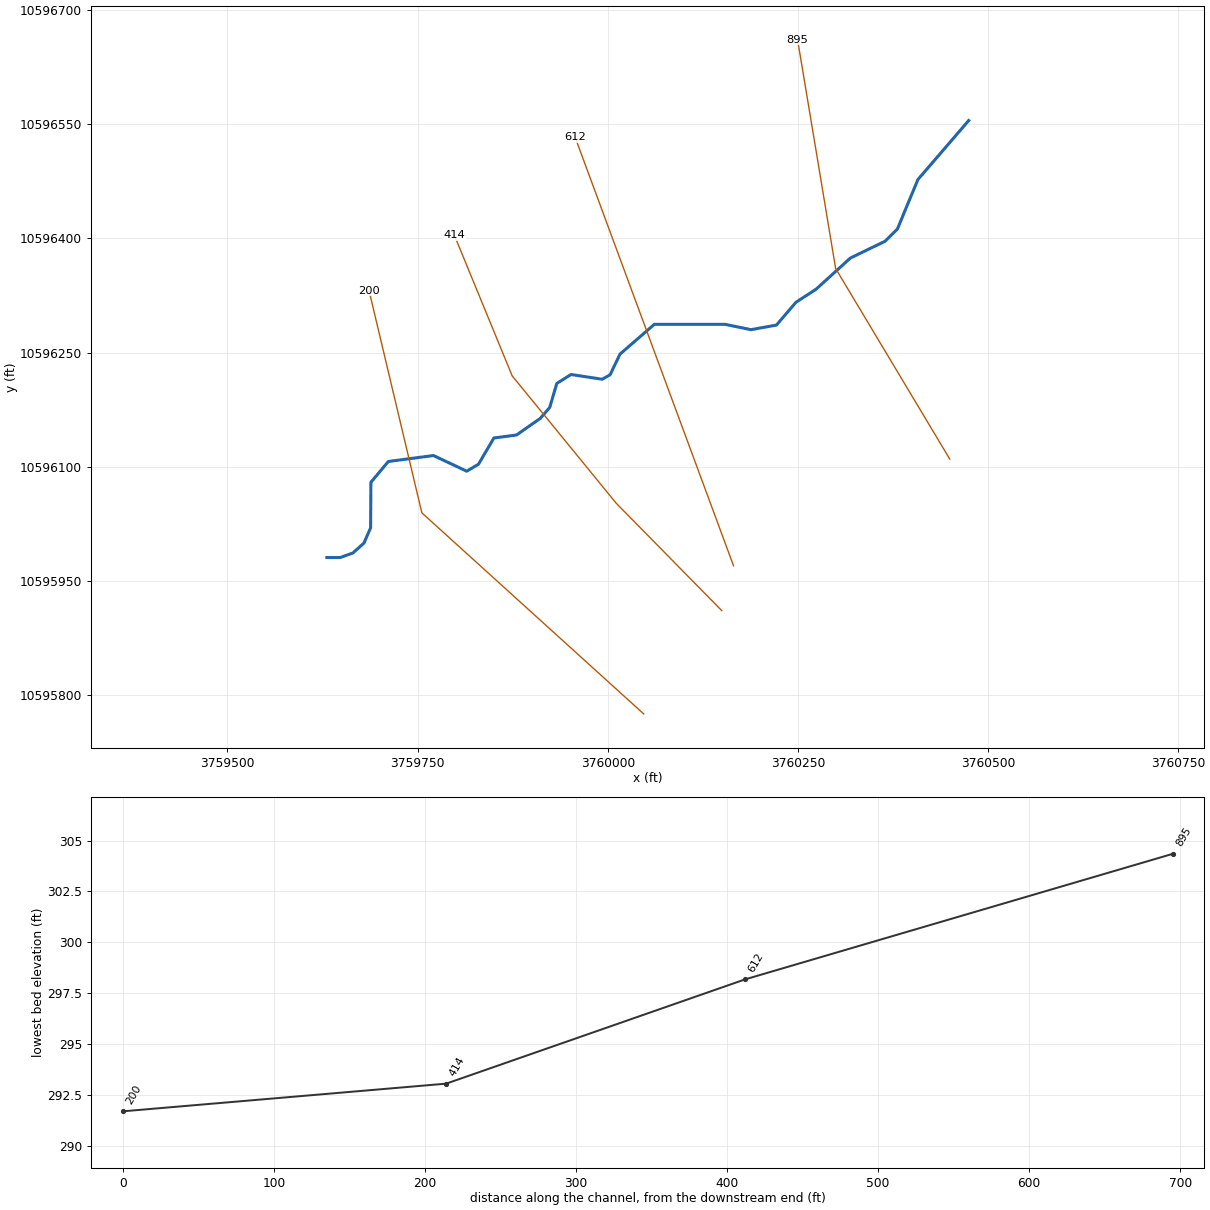
--- UNT 175 IN BOCR.prj (project) ---

Proj Title=UNT 175 IN BOCR Base Level Engineering
Current Plan=p01
Default Exp/Contr=0.3,0.1
English Units
Geom File=g01
Flow File=f01
Plan File=p01
BEGIN DESCRIPTION:
UNT 175 IN BOCR
END DESCRIPTION:

--- UNT 175 IN BOCR.p01 (plan) ---

Plan Title=Multiple Run
Short Identifier=Multiple
Geom File=g01
Flow File=f01
Subcritical Flow
K Sum by GR= 0
Std Step Tol= 0.01
Critical Tol= 0.01
Num of Std Step Trials= 20
Max Error Tol= 0.3
Flow Tol Ratio= 0.001
Split Flow NTrial= 30
Split Flow Tol= 0.02
Split Flow Ratio= 0.02
Log Output Level= 0
Friction Slope Method= 1
Unsteady Friction Slope Method= 2
Unsteady Bridges Friction Slope Method= 1
Parabolic Critical Depth
Global Vel Dist=  1 , 1 , 1
Global Log Level= 0
CheckData=True
Encroach Param= -1, 0, 0, 0
BEGIN DESCRIPTION:
Multiple Run
END DESCRIPTION:

--- UNT 175 IN BOCR.f01 (steady flow) ---

Flow Title=Multiple
Number of Profiles=7
Profile Names=10-year,25-year,50-year,1pct_min,100-year,1pct_plu,500-year
River Rch & RM= UNT 175 IN BOCR,Reach-1,895
     206     264     309     268     363     491     499
Boundary for River Rch & Prof#=UNT 175 IN BOCR,Reach-1,1
Up Type=0
Dn Type=3
Dn Slope=0.005
Boundary for River Rch & Prof#=UNT 175 IN BOCR,Reach-1,2
Up Type=0
Dn Type=3
Dn Slope=0.005
Boundary for River Rch & Prof#=UNT 175 IN BOCR,Reach-1,3
Up Type=0
Dn Type=3
Dn Slope=0.005
Boundary for River Rch & Prof#=UNT 175 IN BOCR,Reach-1,4
Up Type=0
Dn Type=3
Dn Slope=0.005
Boundary for River Rch & Prof#=UNT 175 IN BOCR,Reach-1,5
Up Type=0
Dn Type=3
Dn Slope=0.005
Boundary for River Rch & Prof#=UNT 175 IN BOCR,Reach-1,6
Up Type=0
Dn Type=3
Dn Slope=0.005
Boundary for River Rch & Prof#=UNT 175 IN BOCR,Reach-1,7
Up Type=0
Dn Type=3
Dn Slope=0.005

--- UNT 175 IN BOCR.g01 (geometry) ---

Geom Title=Existing Conditions

River Reach=UNT 175 IN BOCR,Reach-1
Reach XY= 30
      3760474.49     10596554.39      3760407.75     10596477.00
      3760380.75     10596412.00      3760364.50     10596396.00
      3760319.00     10596374.00      3760273.75     10596333.00
      3760247.50     10596316.00      3760221.75     10596286.00
      3760188.25     10596280.00      3760154.25     10596287.00
      3760061.25     10596287.00      3760016.06     10596247.86
      3760003.12     10596220.85      3759992.70     10596214.94
      3759951.73     10596221.19      3759932.98     10596209.39
      3759923.75     10596178.00      3759911.32     10596163.62
      3759880.01     10596141.76      3759850.34     10596137.86
      3759830.03     10596103.40      3759814.66     10596094.28
      3759770.91     10596114.86      3759711.50     10596107.00
      3759688.62     10596079.70      3759688.25     10596020.00
      3759679.50     10596000.00      3759665.00     10595987.00
      3759648.25     10595981.00      3759630.75     10595981.00

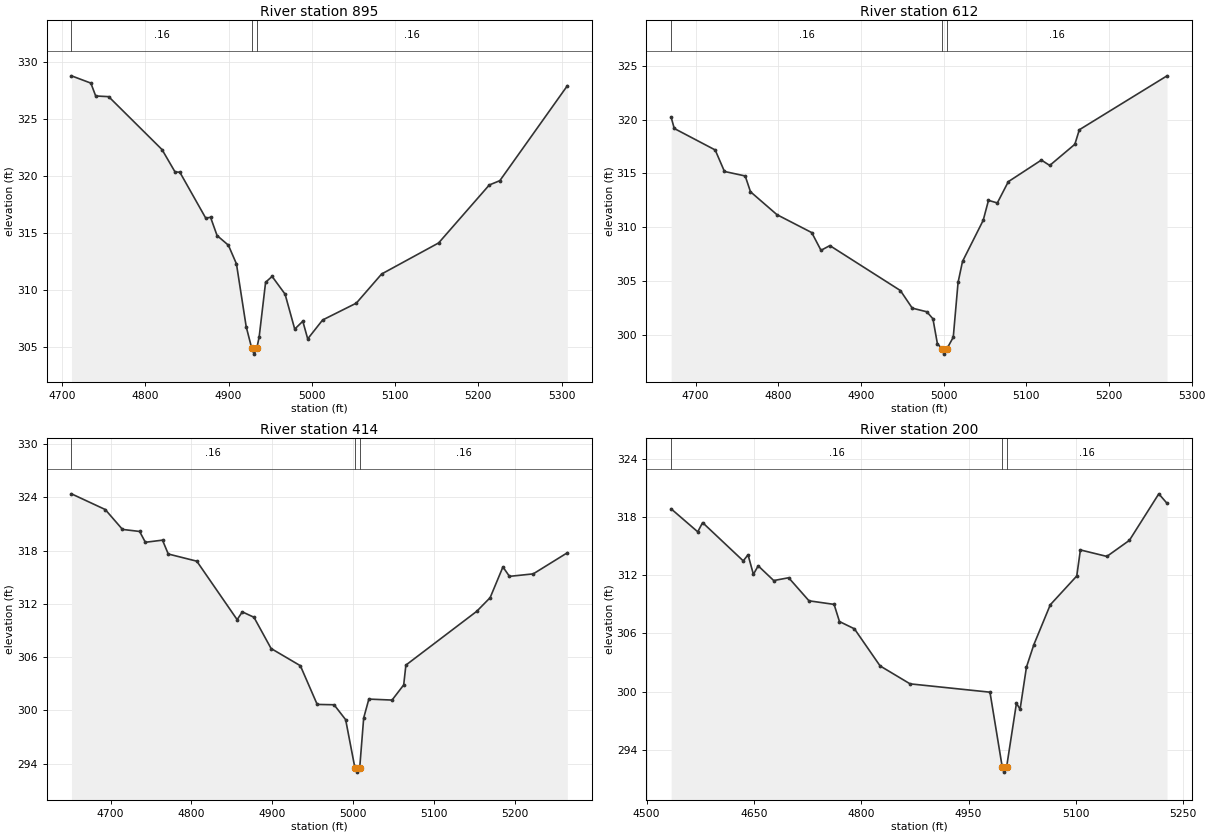
Type RM Length L Ch R = 1,895,283,283,283
BEGIN DESCRIPTION:
UNT 175 IN BOCR 2.0
END DESCRIPTION:
XS GIS Cut Line= 3
      3760449.60     10596110.20      3760299.61     10596360.19
      3760249.61     10596660.21
#Sta/Elev= 30
  4711.3  328.80  4734.6  328.16  4740.4  327.03  4756.0  326.97  4820.1  322.32
  4835.7  320.36  4841.5  320.33  4872.6  316.30  4878.4  316.37  4886.2  314.77
  4899.8  313.92  4909.5  312.28  4921.2  306.76  4927.9  304.85  4930.7  304.35
  4933.9  304.85  4936.8  305.87  4944.5  310.66  4952.3  311.18  4967.9  309.62
  4979.5  306.55  4989.2  307.24  4995.1  305.69  5013.0  307.35  5053.5  308.83
  5083.9  311.39  5152.4  314.12  5213.2  319.21  5225.9  319.59  5307.0  327.93
#Mann=3,-1,0
  4711.3    0.16       0  4927.9    0.07       0  4933.9    0.16       0
Bank Sta=4927.9,4933.9
Exp/Cntr=0.3,0.1

Type RM Length L Ch R = 1,612,198,198,198
BEGIN DESCRIPTION:
Mapping XS b55eed69
END DESCRIPTION:
XS GIS Cut Line= 2
      3760165.36     10595970.16      3759957.01     10596532.72
#Sta/Elev= 30
  4670.3  320.23  4674.1  319.18  4723.6  317.18  4734.8  315.18  4759.9  314.76
  4766.3  313.29  4798.3  311.16  4840.4  309.49  4851.6  307.84  4862.3  308.28
  4947.6  304.10  4962.0  302.46  4979.6  302.12  4987.0  301.47  4992.4  299.15
  4997.9  298.68  5000.7  298.18  5003.9  298.68  5011.6  299.75  5017.4  304.85
  5022.8  306.81  5047.8  310.63  5054.2  312.49  5064.9  312.25  5078.2  314.23
  5118.2  316.24  5128.3  315.74  5158.7  317.71  5164.1  319.06  5270.2  324.08
#Mann=3,-1,0
  4670.3    0.16       0  4997.9    0.07       0  5003.9    0.16       0
Bank Sta=4997.9,5003.9
Exp/Cntr=0.3,0.1

Type RM Length L Ch R = 1,414,214,214,214
BEGIN DESCRIPTION:
Mapping XS 80dbd8c2
END DESCRIPTION:
XS GIS Cut Line= 4
      3760149.93     10595911.28      3760011.05     10596052.33
      3759874.33     10596219.43      3759798.39     10596403.86
#Sta/Elev= 30
  4651.6  324.41  4693.4  322.64  4714.7  320.40  4735.9  320.17  4743.0  318.95
  4764.2  319.19  4771.3  317.63  4806.6  316.82  4856.5  310.23  4862.9  311.11
  4877.3  310.50  4898.5  306.98  4934.7  305.04  4955.5  300.68  4976.4  300.64
  4990.7  298.96  5002.1  293.55  5004.8  293.05  5008.1  293.55  5013.0  299.15
  5019.4  301.28  5048.1  301.17  5062.5  302.88  5065.2  305.11  5152.8  311.17
  5169.4  312.71  5185.2  316.17  5193.3  315.11  5222.7  315.39  5264.9  317.77
#Mann=3,-1,0
  4651.6    0.16       0  5002.1    0.07       0  5008.1    0.16       0
Bank Sta=5002.1,5008.1
Exp/Cntr=0.3,0.1

Type RM Length L Ch R = 1,200,0,0,0
BEGIN DESCRIPTION:
UNT 175 IN BOCR 1.0
END DESCRIPTION:
XS GIS Cut Line= 3
      3760047.31     10595775.74      3759755.62     10596039.65
      3759686.17     10596331.34
#Sta/Elev= 30
  4534.2  318.86  4571.4  316.49  4578.2  317.44  4635.0  313.49  4641.7  314.12
  4649.2  312.10  4655.9  312.98  4677.6  311.46  4698.5  311.75  4726.9  309.37
  4762.0  309.00  4769.5  307.23  4790.4  306.48  4826.3  302.65  4868.2  300.80
  4979.9  299.94  4997.1  292.19  4999.8  291.69  5003.1  292.19  5016.9  298.80
  5022.0  298.18  5030.9  302.53  5041.2  304.84  5064.2  308.96  5101.2  311.93
  5106.3  314.62  5143.3  313.95  5174.8  315.61  5215.9  320.41  5227.4  319.43
#Mann=3,-1,0
  4534.2    0.16       0  4997.1    0.07       0  5003.1    0.16       0
Bank Sta=4997.1,5003.1
Exp/Cntr=0.3,0.1

Chan Stop Cuts=-1