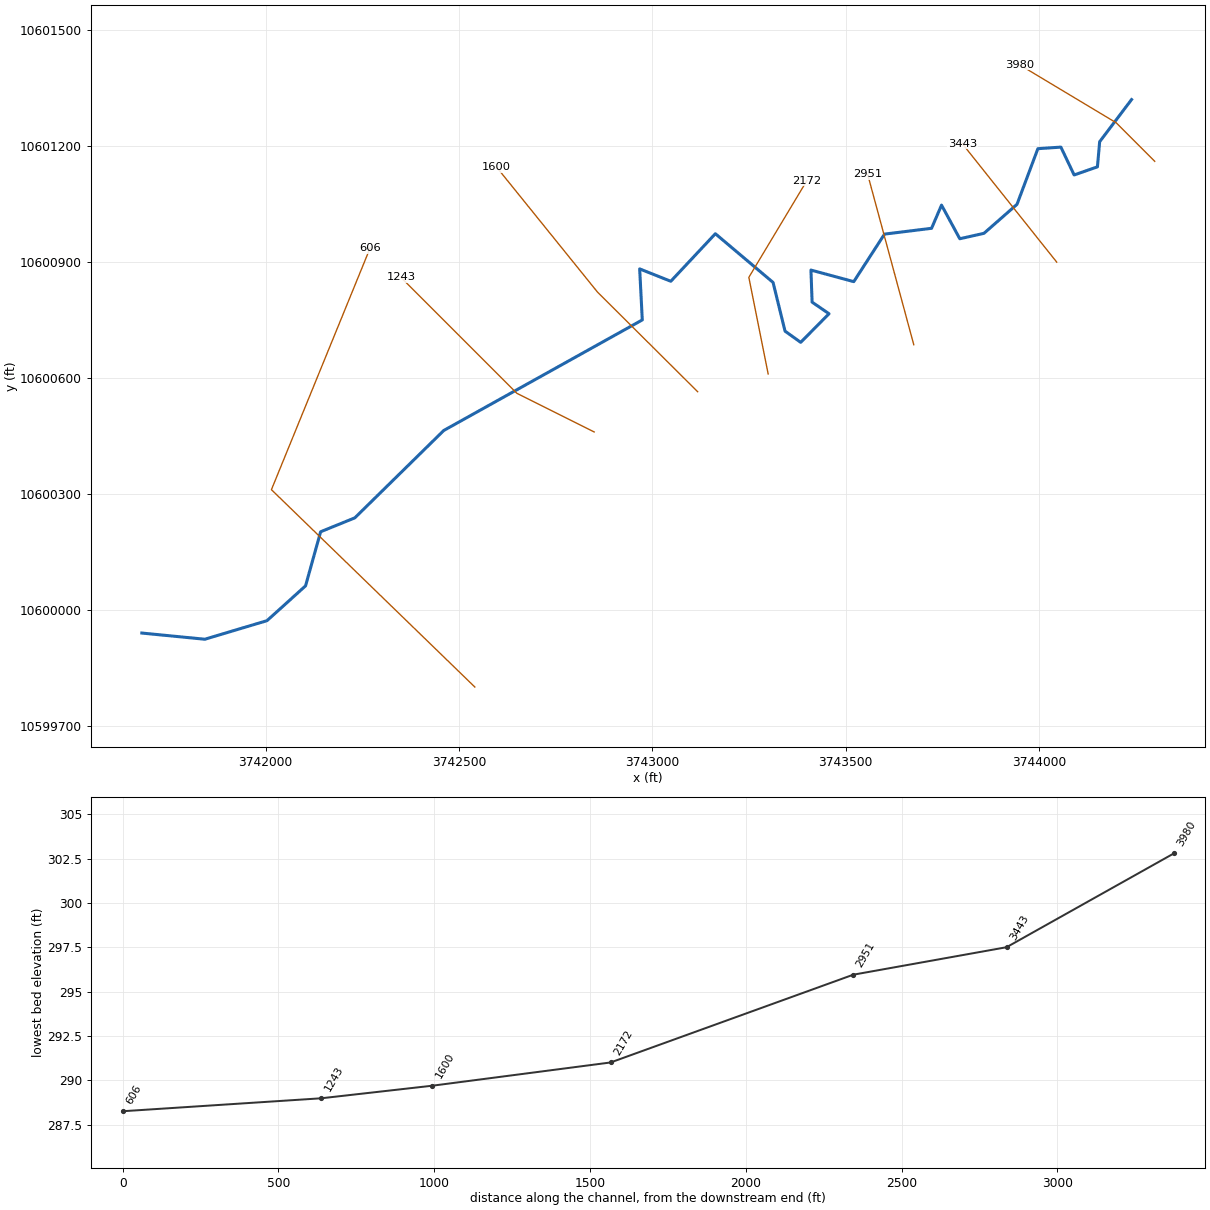
--- UNT 176 IN BOCR.prj (project) ---

Proj Title=UNT 176 IN BOCR Base Level Engineering
Current Plan=p01
Default Exp/Contr=0.3,0.1
English Units
Geom File=g01
Flow File=f01
Plan File=p01
Y Axis Title=Elevation
X Axis Title(PF)=Main Channel Distance
X Axis Title(XS)=Station
BEGIN DESCRIPTION:
UNT 176 IN BOCR
END DESCRIPTION:
DSS Export Rating Curves= 0
DSS Export Rating Curve Sorted= 0
DSS Export Volume Flow Curves= 0
DXF OffsetX= 0
DXF OffsetY= 0
DXF ScaleX= 1
DXF ScaleY= 10

--- UNT 176 IN BOCR.p01 (plan) ---

Plan Title=Multiple Run
Short Identifier=Multiple
Geom File=g01
Flow File=f01
Subcritical Flow
K Sum by GR= 0
Std Step Tol= 0.01
Critical Tol= 0.01
Num of Std Step Trials= 20
Max Error Tol= 0.3
Flow Tol Ratio= 0.001
Split Flow NTrial= 30
Split Flow Tol= 0.02
Split Flow Ratio= 0.02
Log Output Level= 0
Friction Slope Method= 1
Unsteady Friction Slope Method= 2
Unsteady Bridges Friction Slope Method= 1
Parabolic Critical Depth
Global Vel Dist=  1 , 1 , 1
Global Log Level= 0
CheckData=True
Encroach Param= -1, 0, 0, 0
BEGIN DESCRIPTION:
Multiple Run
END DESCRIPTION:

--- UNT 176 IN BOCR.f01 (steady flow) ---

Flow Title=Multiple
Program Version=4.10
Number of Profiles= 7
Profile Names=10-year,25-year,50-year,1pct_min,100-year,1pct_plu,500-year
River Rch & RM=UNT 176 IN BOCR,Reach-1         ,3980
     365     479     572     502     679     919     961
Boundary for River Rch & Prof#=UNT 176 IN BOCR,Reach-1         , 1
Up Type= 0
Dn Type= 3
Dn Slope=0.005
Boundary for River Rch & Prof#=UNT 176 IN BOCR,Reach-1         , 2
Up Type= 0
Dn Type= 3
Dn Slope=0.005
Boundary for River Rch & Prof#=UNT 176 IN BOCR,Reach-1         , 3
Up Type= 0
Dn Type= 3
Dn Slope=0.005
Boundary for River Rch & Prof#=UNT 176 IN BOCR,Reach-1         , 4
Up Type= 0
Dn Type= 3
Dn Slope=0.005
Boundary for River Rch & Prof#=UNT 176 IN BOCR,Reach-1         , 5
Up Type= 0
Dn Type= 3
Dn Slope=0.005
Boundary for River Rch & Prof#=UNT 176 IN BOCR,Reach-1         , 6
Up Type= 0
Dn Type= 3
Dn Slope=0.005
Boundary for River Rch & Prof#=UNT 176 IN BOCR,Reach-1         , 7
Up Type= 0
Dn Type= 3
Dn Slope=0.005
DSS Import GetInterval= 0
DSS Import GetPeak= 0
DSS Import FillOption= 0

--- UNT 176 IN BOCR.g01 (geometry) ---

Geom Title=Existing Conditions

River Reach=UNT 176 IN BOCR,Reach-1
Reach XY= 30
      3744239.50     10601320.00      3744157.00     10601211.00
      3744151.25     10601146.00      3744091.00     10601125.00
      3744056.75     10601197.00      3743997.25     10601193.00
      3743943.25     10601049.00      3743857.75     10600974.00
      3743795.25     10600960.00      3743748.00     10601047.00
      3743722.25     10600987.00      3743600.50     10600972.00
      3743521.00     10600849.00      3743410.25     10600879.00
      3743413.25     10600796.00      3743457.00     10600766.00
      3743383.75     10600692.00      3743343.25     10600721.00
      3743312.25     10600847.00      3743163.00     10600973.00
      3743047.75     10600850.00      3742967.25     10600882.00
      3742974.00     10600750.00      3742460.50     10600464.00
      3742230.50     10600238.00      3742142.00     10600202.00
      3742103.00     10600062.00      3742003.25     10599972.00
      3741842.50     10599924.00      3741679.50     10599940.00

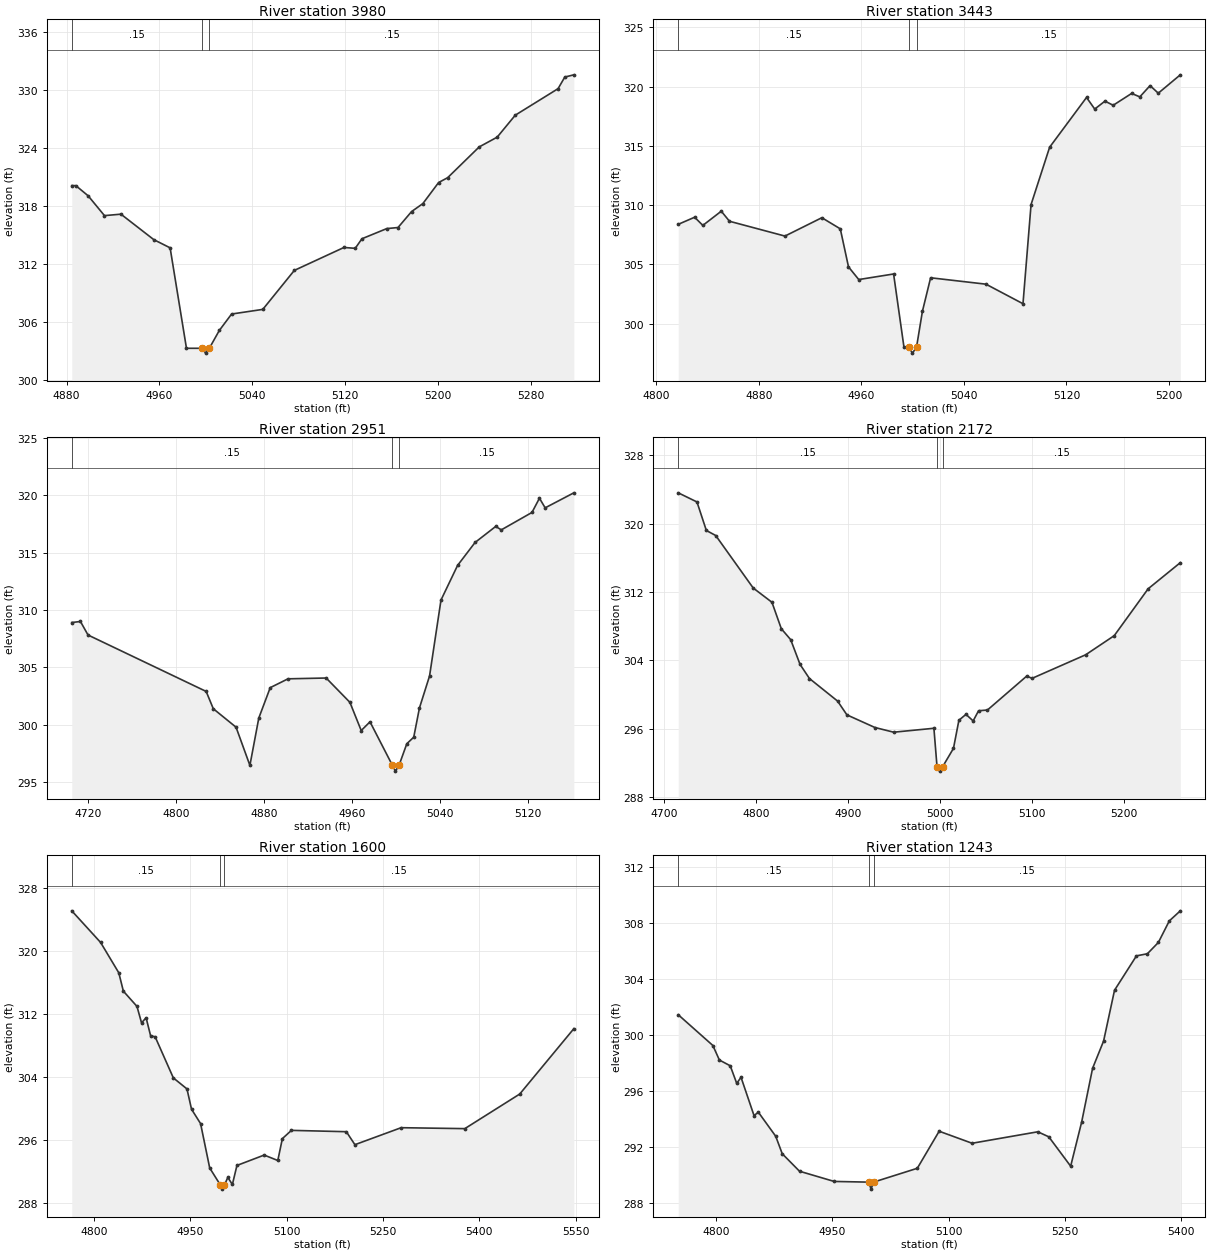
Type RM Length L Ch R = 1,3980,537,537,537
BEGIN DESCRIPTION:
UNT 176 IN BOCR 7.0
END DESCRIPTION:
XS GIS Cut Line= 3
      3744299.57     10601160.22      3744199.61     10601260.19
      3743949.63     10601410.18
#Sta/Elev= 30
  4884.4  320.11  4887.9  320.11  4898.5  319.06  4912.6  317.01  4926.8  317.16
  4955.1  314.53  4969.2  313.68  4983.3  303.30  4997.0  303.30  4999.8  302.80
  5003.0  303.30  5011.6  305.14  5022.2  306.84  5049.1  307.32  5076.3  311.35
  5119.1  313.72  5128.8  313.63  5134.6  314.62  5156.0  315.67  5165.7  315.78
  5177.4  317.43  5187.1  318.25  5200.7  320.43  5208.5  320.93  5235.7  324.11
  5251.2  325.12  5266.8  327.39  5303.7  330.13  5309.5  331.33  5317.3  331.56
#Mann=3,-1,0
  4884.4    0.15       0  4997.0    0.05       0  5003.0    0.15       0
Bank Sta=4997,5003
Exp/Cntr=0.3,0.1

Type RM Length L Ch R = 1,3443,492,492,492
BEGIN DESCRIPTION:
UNT 176 IN BOCR 6.0
END DESCRIPTION:
XS GIS Cut Line= 2
      3744045.99     10600899.44      3743801.81     10601205.97
#Sta/Elev= 30
  4817.0  308.38  4829.8  308.98  4836.2  308.29  4850.6  309.49  4857.0  308.64
  4900.3  307.39  4929.1  308.94  4943.5  308.00  4949.9  304.79  4957.9  303.72
  4985.1  304.19  4993.2  298.01  4997.0  298.01  4999.8  297.51  5003.0  298.01
  5007.6  301.04  5014.0  303.87  5057.2  303.33  5086.1  301.68  5092.4  310.05
  5106.9  314.89  5135.7  319.09  5142.1  318.11  5150.1  318.78  5156.5  318.43
  5170.9  319.43  5177.3  319.14  5185.3  320.09  5191.7  319.45  5208.9  321.00
#Mann=3,-1,0
  4817.0    0.15       0  4997.0    0.05       0  5003.0    0.15       0
Bank Sta=4997,5003
Exp/Cntr=0.3,0.1

Type RM Length L Ch R = 1,2951,779,779,779
BEGIN DESCRIPTION:
UNT 176 IN BOCR 5.0
END DESCRIPTION:
XS GIS Cut Line= 2
      3743676.21     10600685.90      3743556.87     10601126.94
#Sta/Elev= 30
  4705.2  308.92  4713.1  309.01  4720.0  307.83  4827.5  302.91  4834.0  301.40
  4854.7  299.79  4867.3  296.46  4875.4  300.59  4885.8  303.24  4902.0  304.01
  4936.7  304.08  4958.3  301.96  4968.6  299.50  4976.6  300.26  4997.0  296.46
  4999.8  295.96  5003.0  296.46  5010.1  298.35  5016.4  298.92  5021.6  301.47
  5030.8  304.26  5041.2  310.88  5056.3  313.90  5072.2  315.90  5091.0  317.30
  5096.1  317.00  5124.0  318.52  5130.8  319.76  5136.0  318.92  5162.1  320.23
#Mann=3,-1,0
  4705.2    0.15       0  4997.0    0.05       0  5003.0    0.15       0
Bank Sta=4997,5003
Exp/Cntr=0.3,0.1

Type RM Length L Ch R = 1,2172,572,572,572
BEGIN DESCRIPTION:
UNT 176 IN BOCR 4.0
END DESCRIPTION:
XS GIS Cut Line= 3
      3743299.61     10600610.20      3743249.61     10600860.19
      3743399.62     10601110.20
#Sta/Elev= 30
  4715.3  323.61  4735.7  322.54  4745.9  319.20  4756.1  318.61  4796.9  312.46
  4817.3  310.79  4827.5  307.69  4837.7  306.41  4847.9  303.51  4858.1  301.86
  4888.7  299.22  4898.9  297.60  4929.4  296.12  4949.8  295.57  4993.6  296.03
  4997.0  291.51  4999.8  291.01  5003.0  291.51  5014.9  293.68  5020.8  296.97
  5028.5  297.66  5036.3  296.89  5042.2  298.08  5051.9  298.17  5094.6  302.14
  5100.5  301.88  5158.8  304.64  5189.9  306.88  5226.8  312.37  5261.8  315.43
#Mann=3,-1,0
  4715.3    0.15       0  4997.0    0.05       0  5003.0    0.15       0
Bank Sta=4997,5003
Exp/Cntr=0.3,0.1

Type RM Length L Ch R = 1,1600,357,357,357
BEGIN DESCRIPTION:
UNT 176 IN BOCR 3.0
END DESCRIPTION:
XS GIS Cut Line= 3
      3743117.23     10600564.24      3742858.09     10600822.08
      3742596.83     10601145.72
#Sta/Elev= 30
  4765.5  325.08  4810.4  321.06  4838.7  317.20  4845.8  314.87  4867.0  312.93
  4874.1  310.84  4881.2  311.48  4888.2  309.20  4895.3  309.06  4923.6  303.84
  4944.8  302.44  4951.9  299.86  4966.0  298.03  4980.2  292.39  4997.0  290.20
  4999.8  289.70  5003.0  290.20  5008.4  291.19  5015.5  290.29  5022.6  292.71
  5065.0  294.03  5086.2  293.34  5093.3  296.12  5107.4  297.17  5192.9  297.00
  5206.2  295.35  5278.2  297.51  5377.3  297.39  5462.8  301.79  5547.0  310.10
#Mann=3,-1,0
  4765.5    0.15       0  4997.0    0.05       0  5003.0    0.15       0
Bank Sta=4997,5003
Exp/Cntr=0.3,0.1

Type RM Length L Ch R = 1,1243,637,637,637
BEGIN DESCRIPTION:
UNT 176 IN BOCR 2.0
END DESCRIPTION:
XS GIS Cut Line= 3
      3742849.60     10600460.19      3742649.61     10600560.19
      3742349.58     10600860.21
#Sta/Elev= 30
  4751.0  301.46  4795.7  299.26  4804.1  298.22  4818.1  297.81  4826.5  296.55
  4832.0  296.99  4848.8  294.25  4854.4  294.49  4876.8  292.77  4885.2  291.52
  4907.5  290.27  4952.2  289.54  4997.0  289.49  4999.8  288.99  5003.0  289.49
  5059.5  290.48  5087.7  293.13  5130.2  292.27  5215.0  293.09  5229.2  292.73
  5257.4  290.63  5271.6  293.79  5285.7  297.63  5299.9  299.58  5314.0  303.21
  5342.3  305.67  5356.4  305.82  5370.6  306.63  5384.7  308.17  5398.9  308.89
#Mann=3,-1,0
  4751.0    0.15       0  4997.0    0.05       0  5003.0    0.15       0
Bank Sta=4997,5003
Exp/Cntr=0.3,0.1

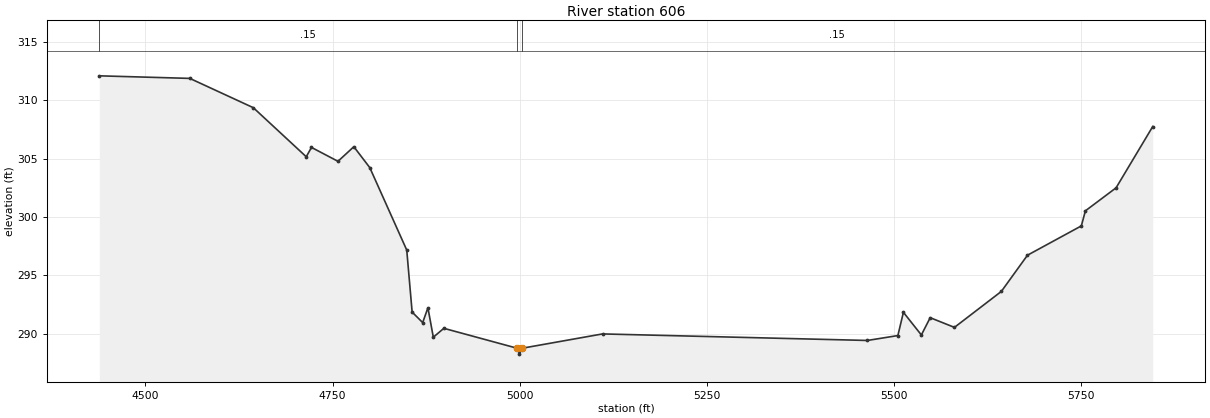
Type RM Length L Ch R = 1,606,0,0,0
BEGIN DESCRIPTION:
UNT 176 IN BOCR 1.0
END DESCRIPTION:
XS GIS Cut Line= 3
      3742540.80     10599800.46      3742014.75     10600310.89
      3742269.81     10600935.54
#Sta/Elev= 30
  4438.4  312.09  4559.3  311.87  4644.2  309.36  4714.9  305.16  4721.9  305.96
  4757.3  304.77  4778.5  306.02  4799.8  304.23  4849.2  297.17  4856.4  291.86
  4870.5  290.96  4877.5  292.23  4884.7  289.71  4898.8  290.47  4997.0  288.76
  4999.8  288.26  5003.0  288.76  5110.8  289.99  5464.8  289.43  5505.5  289.85
  5512.9  291.84  5536.9  289.90  5548.7  291.38  5581.1  290.55  5643.8  293.63
  5678.7  296.73  5750.7  299.24  5756.1  300.53  5797.1  302.50  5846.1  307.75
#Mann=3,-1,0
  4438.4    0.15       0  4997.0    0.05       0  5003.0    0.15       0
Bank Sta=4997,5003
Exp/Cntr=0.3,0.1

Chan Stop Cuts=-1