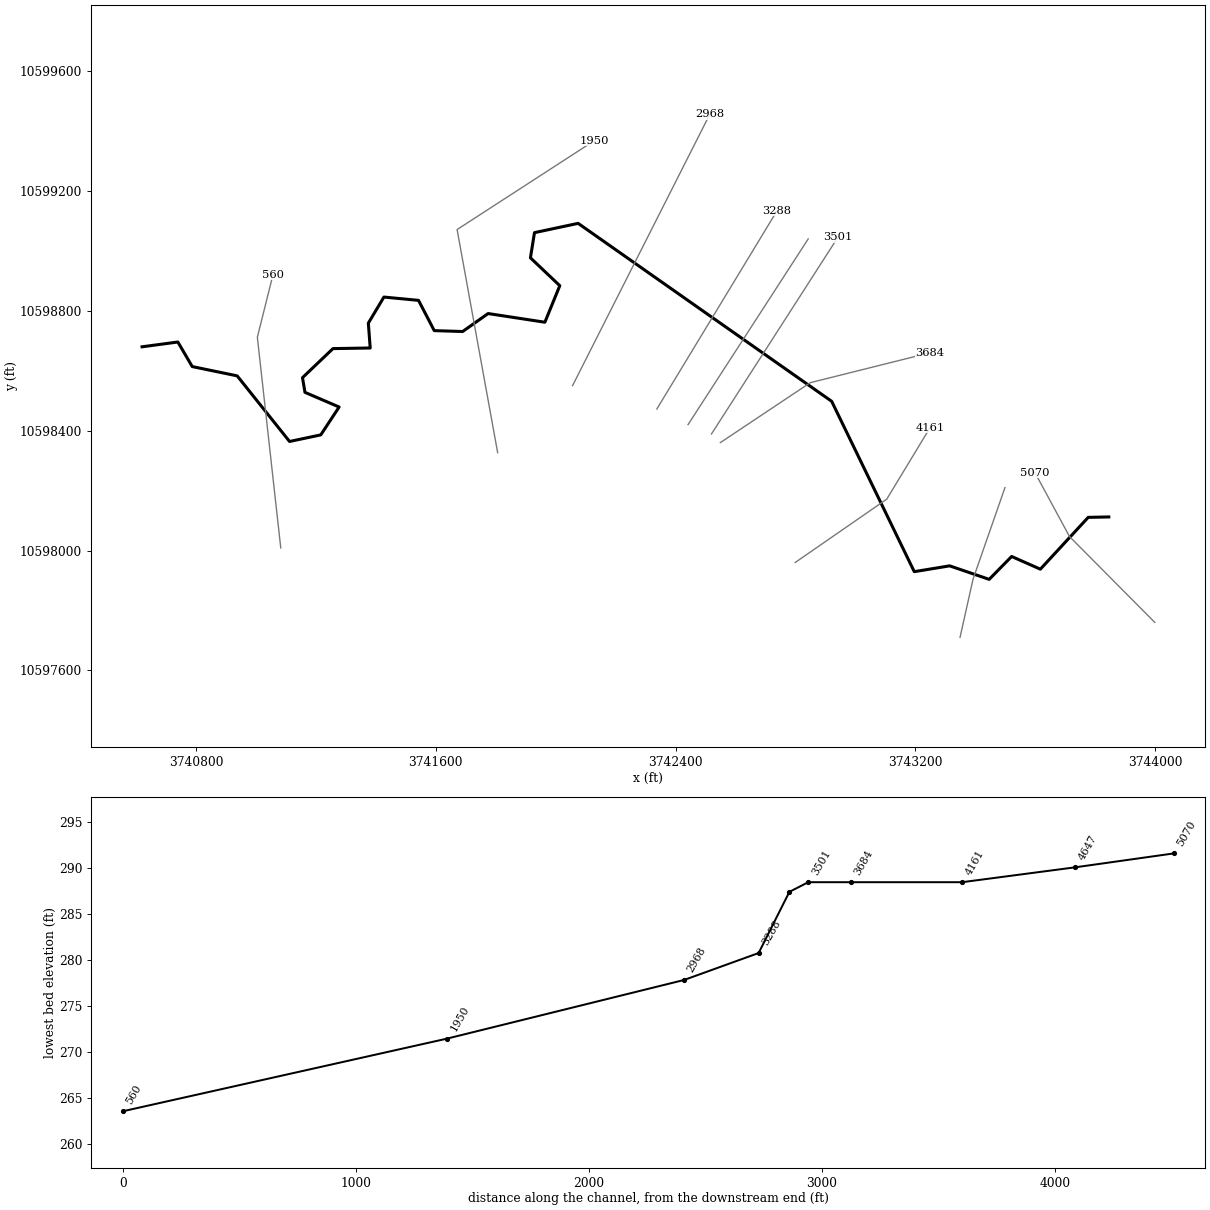
--- UNT 177 IN BOCR.prj (project) ---

Proj Title=UNT 177 IN BOCR Base Level Engineering
Current Plan=p01
Default Exp/Contr=0.3,0.1
English Units
Geom File=g01
Flow File=f01
Plan File=p01
BEGIN DESCRIPTION:
UNT 177 IN BOCR
END DESCRIPTION:

--- UNT 177 IN BOCR.p01 (plan) ---

Plan Title=Multiple Run
Short Identifier=Multiple
Geom File=g01
Flow File=f01
Subcritical Flow
K Sum by GR= 0
Std Step Tol= 0.01
Critical Tol= 0.01
Num of Std Step Trials= 20
Max Error Tol= 0.3
Flow Tol Ratio= 0.001
Split Flow NTrial= 30
Split Flow Tol= 0.02
Split Flow Ratio= 0.02
Log Output Level= 0
Friction Slope Method= 1
Unsteady Friction Slope Method= 2
Unsteady Bridges Friction Slope Method= 1
Parabolic Critical Depth
Global Vel Dist=  1 , 1 , 1
Global Log Level= 0
CheckData=True
Encroach Param= -1, 0, 0, 0
BEGIN DESCRIPTION:
Multiple Run
END DESCRIPTION:

--- UNT 177 IN BOCR.f01 (steady flow) ---

Flow Title=Multiple
Number of Profiles=7
Profile Names=10-year,25-year,50-year,1pct_min,100-year,1pct_plu,500-year
River Rch & RM= UNT 177 IN BOCR,Reach-1,5070
     333     435     517     452     612     827     859
Boundary for River Rch & Prof#=UNT 177 IN BOCR,Reach-1,1
Up Type=0
Dn Type=3
Dn Slope=0.005
Boundary for River Rch & Prof#=UNT 177 IN BOCR,Reach-1,2
Up Type=0
Dn Type=3
Dn Slope=0.005
Boundary for River Rch & Prof#=UNT 177 IN BOCR,Reach-1,3
Up Type=0
Dn Type=3
Dn Slope=0.005
Boundary for River Rch & Prof#=UNT 177 IN BOCR,Reach-1,4
Up Type=0
Dn Type=3
Dn Slope=0.005
Boundary for River Rch & Prof#=UNT 177 IN BOCR,Reach-1,5
Up Type=0
Dn Type=3
Dn Slope=0.005
Boundary for River Rch & Prof#=UNT 177 IN BOCR,Reach-1,6
Up Type=0
Dn Type=3
Dn Slope=0.005
Boundary for River Rch & Prof#=UNT 177 IN BOCR,Reach-1,7
Up Type=0
Dn Type=3
Dn Slope=0.005

--- UNT 177 IN BOCR.g01 (geometry) ---

Geom Title=Existing Conditions

River Reach=UNT 177 IN BOCR,Reach-1
Reach XY= 30
      3743846.16     10598112.12      3743777.41     10598110.73
      3743617.69     10597937.81      3743521.85     10597980.17
      3743446.85     10597903.79      3743314.91     10597948.92
      3743196.85     10597929.48      3742921.24     10598498.04
      3742075.00     10599092.00      3741929.25     10599061.00
      3741915.75     10598977.00      3742013.75     10598884.00
      3741964.00     10598762.00      3741774.50     10598791.00
      3741689.50     10598731.00      3741594.75     10598734.00
      3741542.25     10598835.00      3741426.75     10598846.00
      3741374.75     10598759.00      3741381.00     10598676.00
      3741256.75     10598674.00      3741155.00     10598577.00
      3741163.25     10598528.00      3741277.25     10598479.00
      3741216.00     10598386.00      3741111.75     10598364.00
      3740937.00     10598583.00      3740787.00     10598614.00
      3740739.00     10598696.00      3740619.50     10598680.00

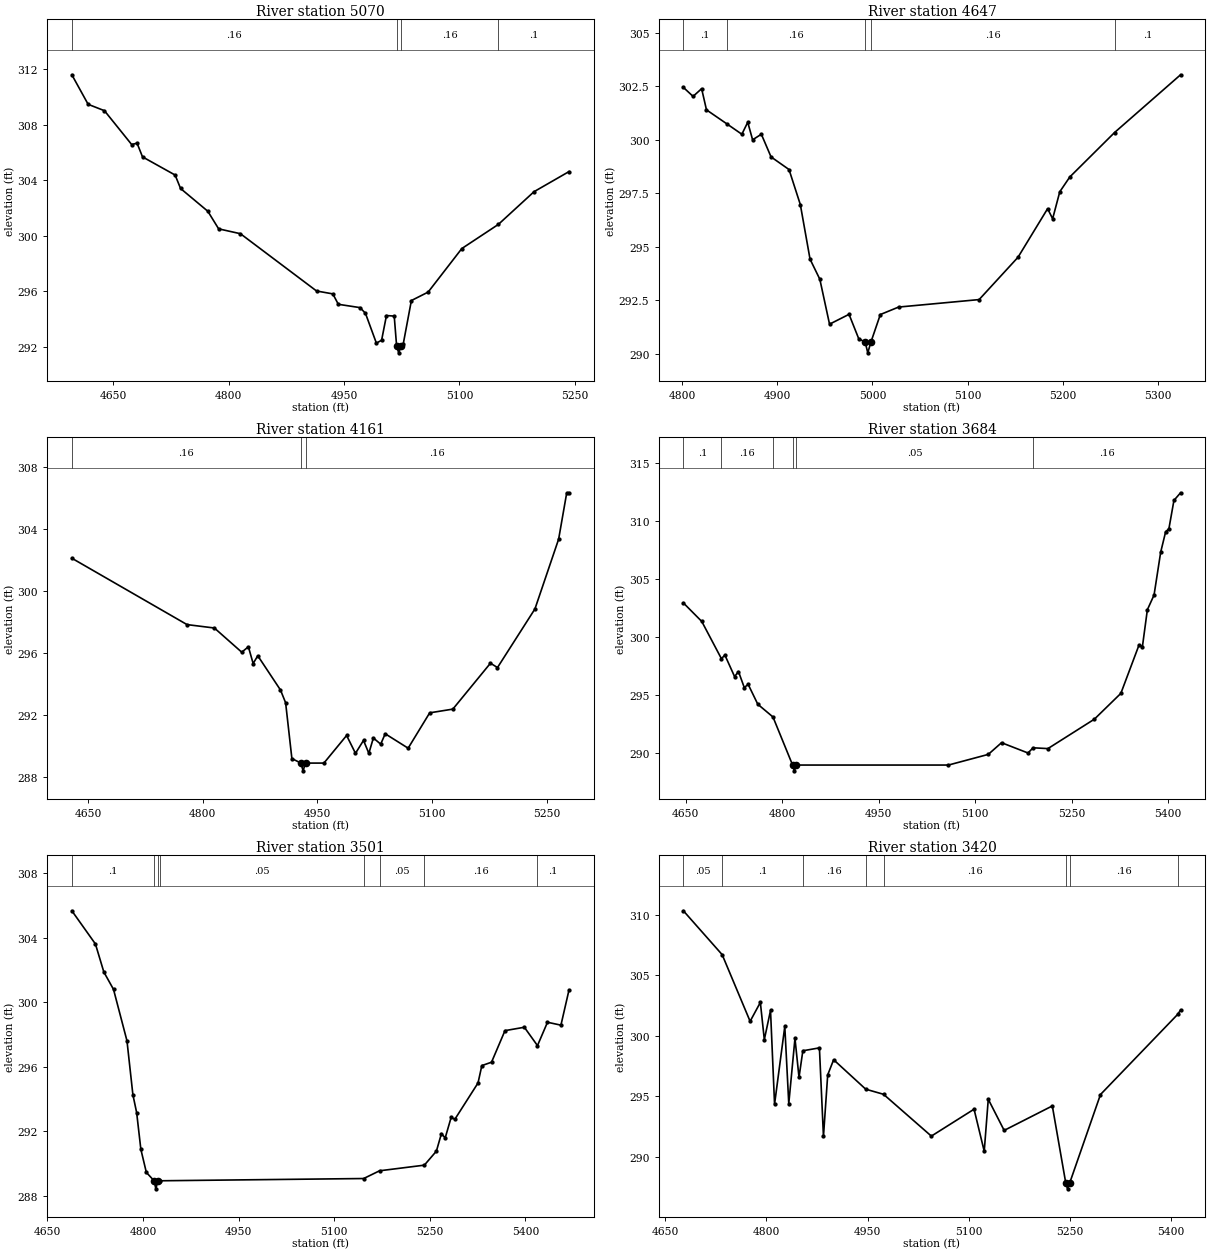
Type RM Length L Ch R = 1,5070,423,423,423
BEGIN DESCRIPTION:
UNT 177 IN BOCR 7.0
END DESCRIPTION:
XS GIS Cut Line= 3
      3743999.60     10597760.20      3743714.91     10598046.84
      3743599.61     10598260.18
#Sta/Elev= 30
  4596.0  311.60  4617.2  309.47  4638.4  309.01  4673.8  306.57  4680.8  306.67
  4687.9  305.68  4730.3  304.37  4737.4  303.40  4772.8  301.76  4786.9  300.49
  4815.2  300.14  4914.2  296.01  4935.4  295.80  4942.5  295.05  4970.8  294.81
  4977.8  294.40  4992.0  292.25  4998.8  292.46  5005.1  294.24  5015.2  294.20
  5018.3  292.05  5021.0  291.55  5024.3  292.05  5026.9  292.18  5037.5  295.32
  5059.3  295.93  5103.1  299.07  5150.6  300.81  5197.0  303.17  5242.5  304.62
#Mann=4,-1,0
  4596.0    0.16       0  5018.3    0.07       0  5024.3    0.16       0
  5150.6     0.1       0
Bank Sta=5018.3,5024.3
Exp/Cntr=0.3,0.1

Type RM Length L Ch R = 1,4647,486,486,486
BEGIN DESCRIPTION:
UNT 177 IN BOCR 6.0
END DESCRIPTION:
XS GIS Cut Line= 3
      3743349.61     10597710.19      3743392.96     10597904.20
      3743499.60     10598210.15
#Sta/Elev= 30
  4801.2  302.45  4811.4  302.03  4820.4  302.39  4825.5  301.40  4847.1  300.74
  4862.7  300.26  4868.9  300.82  4874.0  300.00  4883.2  300.26  4893.4  299.20
  4912.3  298.61  4924.2  296.97  4934.4  294.42  4944.7  293.48  4954.9  291.38
  4975.4  291.84  4985.6  290.70  4992.4  290.54  4995.1  290.04  4998.4  290.54
  5008.3  291.83  5027.5  292.18  5112.2  292.53  5153.1  294.51  5184.2  296.78
  5189.5  296.31  5197.0  297.57  5207.5  298.26  5254.6  300.34  5324.0  303.04
#Mann=5,-1,0
  4801.2     0.1       0  4847.1    0.16       0  4992.4    0.07       0
  4998.4    0.16       0  5254.6     0.1       0
Bank Sta=4992.4,4998.4
Exp/Cntr=0.3,0.1

Type RM Length L Ch R = 1,4161,477,477,477
BEGIN DESCRIPTION:
UNT 177 IN BOCR 5.0
END DESCRIPTION:
XS GIS Cut Line= 3
      3742799.61     10597960.19      3743105.04     10598171.49
      3743249.63     10598410.22
#Sta/Elev= 30
  4628.6  302.13  4779.3  297.85  4815.1  297.63  4850.9  296.07  4859.6  296.42
  4865.8  295.34  4871.9  295.84  4901.6  293.63  4908.3  292.81  4916.5  289.21
  4928.4  288.92  4931.1  288.42  4934.4  288.92  4958.4  288.92  4988.1  290.70
  4999.7  289.55  5010.2  290.38  5017.2  289.55  5023.1  290.54  5032.7  290.14
  5038.6  290.81  5068.6  289.88  5096.8  292.16  5127.1  292.40  5176.3  295.36
  5185.5  295.08  5234.5  298.86  5265.5  303.36  5276.1  306.35  5279.1  306.35
#Mann=3,-1,0
  4628.6    0.16       0  4928.4    0.07       0  4934.4    0.16       0
Bank Sta=4928.4,4934.4
Exp/Cntr=0.3,0.1

Type RM Length L Ch R = 1,3684,183,183,183
BEGIN DESCRIPTION:
UNT 177 IN BOCR 4.0
END DESCRIPTION:
XS GIS Cut Line= 3
      3742549.59     10598360.18      3742849.61     10598560.19
      3743249.62     10598660.19
#Sta/Elev= 30
  4646.2  302.92  4674.8  301.32  4705.3  298.11  4710.8  298.41  4725.8  296.56
  4731.9  296.99  4740.9  295.61  4746.9  295.89  4761.9  294.17  4785.5  293.07
  4816.0  288.92  4818.7  288.42  4822.0  288.92  5058.3  288.92  5120.2  289.84
  5140.8  290.85  5182.0  289.96  5189.8  290.41  5212.9  290.34  5285.1  292.88
  5326.3  295.11  5354.7  299.31  5359.8  299.14  5367.5  302.33  5377.9  303.60
  5388.2  307.30  5395.9  309.06  5401.0  309.33  5408.8  311.77  5419.1  312.43
#Mann=6,-1,0
  4646.2     0.1       0  4705.3    0.16       0  4785.5    0.05       0
  4816.0   0.033       0  4822.0    0.05       0  5189.8    0.16       0
Bank Sta=4816,4822
Exp/Cntr=0.3,0.1

Type RM Length L Ch R = 1,3501,81,81,81
BEGIN DESCRIPTION:
Mapping XS 12bdd5a8
END DESCRIPTION:
XS GIS Cut Line= 2
      3742519.98     10598389.05      3742941.82     10599045.25
#Sta/Elev= 30
  4688.2  305.68  4725.2  303.62  4738.4  301.88  4753.6  300.80  4774.7  297.61
  4784.0  294.26  4789.9  293.15  4796.5  290.87  4805.1  289.44  4817.3  288.92
  4820.0  288.42  4823.3  288.92  4825.9  288.92  5146.1  289.06  5171.0  289.54
  5241.3  289.89  5260.2  290.76  5268.1  291.85  5274.0  291.58  5283.3  292.85
  5289.2  292.74  5325.5  294.99  5331.5  296.07  5346.7  296.28  5367.8  298.24
  5398.2  298.45  5418.8  297.31  5434.5  298.76  5455.6  298.58  5468.3  300.77
#Mann=8,-1,0
  4688.2     0.1       0  4817.3   0.033       0  4823.3     0.1       0
  4825.9    0.05       0  5146.1    0.16       0  5171.0    0.05       0
  5241.3    0.16       0  5418.8     0.1       0
Bank Sta=4817.3,4823.3
Exp/Cntr=0.3,0.1

Type RM Length L Ch R = 1,3420,132,132,132
BEGIN DESCRIPTION:
Mapping XS 56c19254
END DESCRIPTION:
XS GIS Cut Line= 2
      3742441.84     10598420.28      3742842.87     10599040.06
#Sta/Elev= 30
  4676.6  310.31  4734.2  306.69  4775.7  301.19  4790.9  302.75  4796.8  299.68
  4806.0  302.09  4812.0  294.35  4827.2  300.77  4833.1  294.40  4842.3  299.78
  4848.3  296.57  4854.0  298.76  4878.6  299.00  4884.6  291.69  4890.9  296.77
  4899.7  298.02  4947.4  295.59  4973.8  295.17  5044.8  291.72  5108.2  293.94
  5123.3  290.47  5129.3  294.76  5152.9  292.19  5224.4  294.21  5244.3  287.87
  5247.0  287.37  5250.3  287.87  5295.9  295.15  5410.8  301.78  5414.8  302.13
#Mann=8,-1,0
  4676.6    0.05       0  4734.2     0.1       0  4854.0    0.16       0
  4947.4    0.05       0  4973.8    0.16       0  5244.3    0.07       0
  5250.3    0.16       0  5410.8     0.1       0
Bank Sta=5244.3,5250.3
Exp/Cntr=0.3,0.1

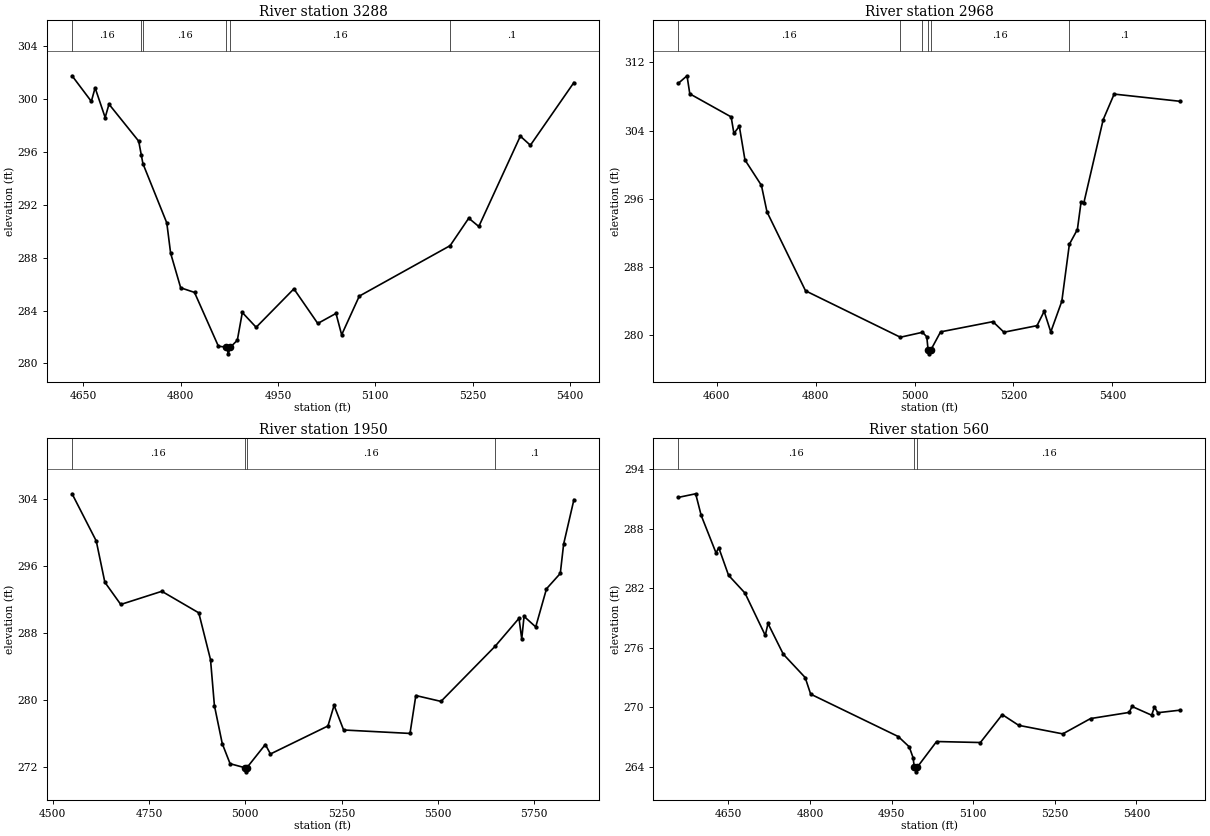
Type RM Length L Ch R = 1,3288,320,320,320
BEGIN DESCRIPTION:
UNT 177 IN BOCR 3.0
END DESCRIPTION:
XS GIS Cut Line= 2
      3742337.67     10598472.36      3742738.69     10599133.78
#Sta/Elev= 30
  4632.7  301.77  4662.4  299.83  4668.2  300.86  4683.7  298.61  4689.6  299.62
  4735.4  296.82  4739.4  295.77  4741.9  295.12  4778.7  290.63  4784.6  288.34
  4800.1  285.72  4821.4  285.37  4858.2  281.30  4870.7  281.22  4873.5  280.72
  4876.7  281.22  4887.4  281.75  4895.1  283.85  4916.4  282.73  4974.6  285.64
  5011.4  283.02  5039.5  283.78  5048.2  282.16  5075.4  285.09  5215.4  288.91
  5244.1  290.99  5259.6  290.36  5323.6  297.20  5339.1  296.51  5406.2  301.26
#Mann=6,-1,0
  4632.7    0.16       0  4739.4     0.1       0  4741.9    0.16       0
  4870.7    0.07       0  4876.7    0.16       0  5215.4     0.1       0
Bank Sta=4870.7,4876.7
Exp/Cntr=0.3,0.1

Type RM Length L Ch R = 1,2968,1018,1018,1018
BEGIN DESCRIPTION:
UNT 177 IN BOCR 2.0
END DESCRIPTION:
XS GIS Cut Line= 2
      3742056.41     10598550.46      3742514.31     10599455.86
#Sta/Elev= 30
  4522.7  309.57  4540.0  310.44  4545.6  308.32  4629.2  305.61  4634.8  303.67
  4645.7  304.52  4657.1  300.56  4690.4  297.57  4701.7  294.45  4779.6  285.19
  4971.3  279.74  5016.0  280.32  5024.7  279.79  5027.3  278.29  5030.1  277.79
  5033.3  278.29  5052.6  280.37  5158.4  281.57  5180.7  280.33  5247.6  281.10
  5262.0  282.78  5275.4  280.36  5297.7  283.96  5313.0  290.66  5329.2  292.39
  5336.7  295.65  5342.3  295.53  5381.3  305.28  5403.5  308.29  5537.3  307.44
#Mann=6,-1,0
  4522.7    0.16       0  4971.3     0.1       0  5016.0    0.16       0
  5027.3    0.07       0  5033.3    0.16       0  5313.0     0.1       0
Bank Sta=5027.3,5033.3
Exp/Cntr=0.3,0.1

Type RM Length L Ch R = 1,1950,1390,1390,1390
BEGIN DESCRIPTION:
Mapping XS a19c80fb
END DESCRIPTION:
XS GIS Cut Line= 3
      3741806.42     10598326.51      3741671.00     10599071.31
      3742129.34     10599368.19
#Sta/Elev= 30
  4550.1  304.57  4612.9  298.94  4635.2  294.02  4676.5  291.37  4783.2  292.94
  4879.1  290.37  4909.6  284.79  4919.7  279.31  4940.1  274.77  4960.4  272.38
  4998.1  271.91  5000.8  271.41  5004.1  271.91  5051.9  274.67  5065.2  273.54
  5214.5  276.88  5230.4  279.34  5255.2  276.40  5427.6  275.99  5442.7  280.51
  5508.0  279.81  5648.9  286.40  5710.6  289.72  5717.7  287.26  5723.7  289.95
  5754.0  288.69  5782.0  293.24  5817.8  295.07  5826.5  298.57  5853.2  303.87
#Mann=4,-1,0
  4550.1    0.16       0  4998.1    0.07       0  5004.1    0.16       0
  5648.9     0.1       0
Bank Sta=4998.1,5004.1
Exp/Cntr=0.3,0.1

Type RM Length L Ch R = 1,560,0,0,0
BEGIN DESCRIPTION:
UNT 177 IN BOCR 1.0
END DESCRIPTION:
XS GIS Cut Line= 3
      3741082.46     10598008.78      3741004.33     10598711.94
      3741056.41     10598920.25
#Sta/Elev= 30
  4558.5  291.14  4590.1  291.50  4600.2  289.33  4627.5  285.55  4632.5  286.08
  4650.5  283.30  4680.7  281.51  4718.0  277.25  4723.0  278.45  4751.1  275.36
  4791.3  273.01  4801.4  271.34  4962.4  267.07  4982.5  266.04  4989.7  264.93
  4991.7  264.02  4994.5  263.52  4997.7  264.02  5032.8  266.57  5113.3  266.47
  5153.5  269.28  5183.7  268.20  5264.7  267.34  5315.7  268.88  5386.8  269.50
  5391.9  270.10  5428.0  269.22  5433.1  270.04  5439.4  269.47  5480.7  269.73
#Mann=3,-1,0
  4558.5    0.16       0  4991.7    0.07       0  4997.7    0.16       0
Bank Sta=4991.7,4997.7
Exp/Cntr=0.3,0.1

Chan Stop Cuts=-1