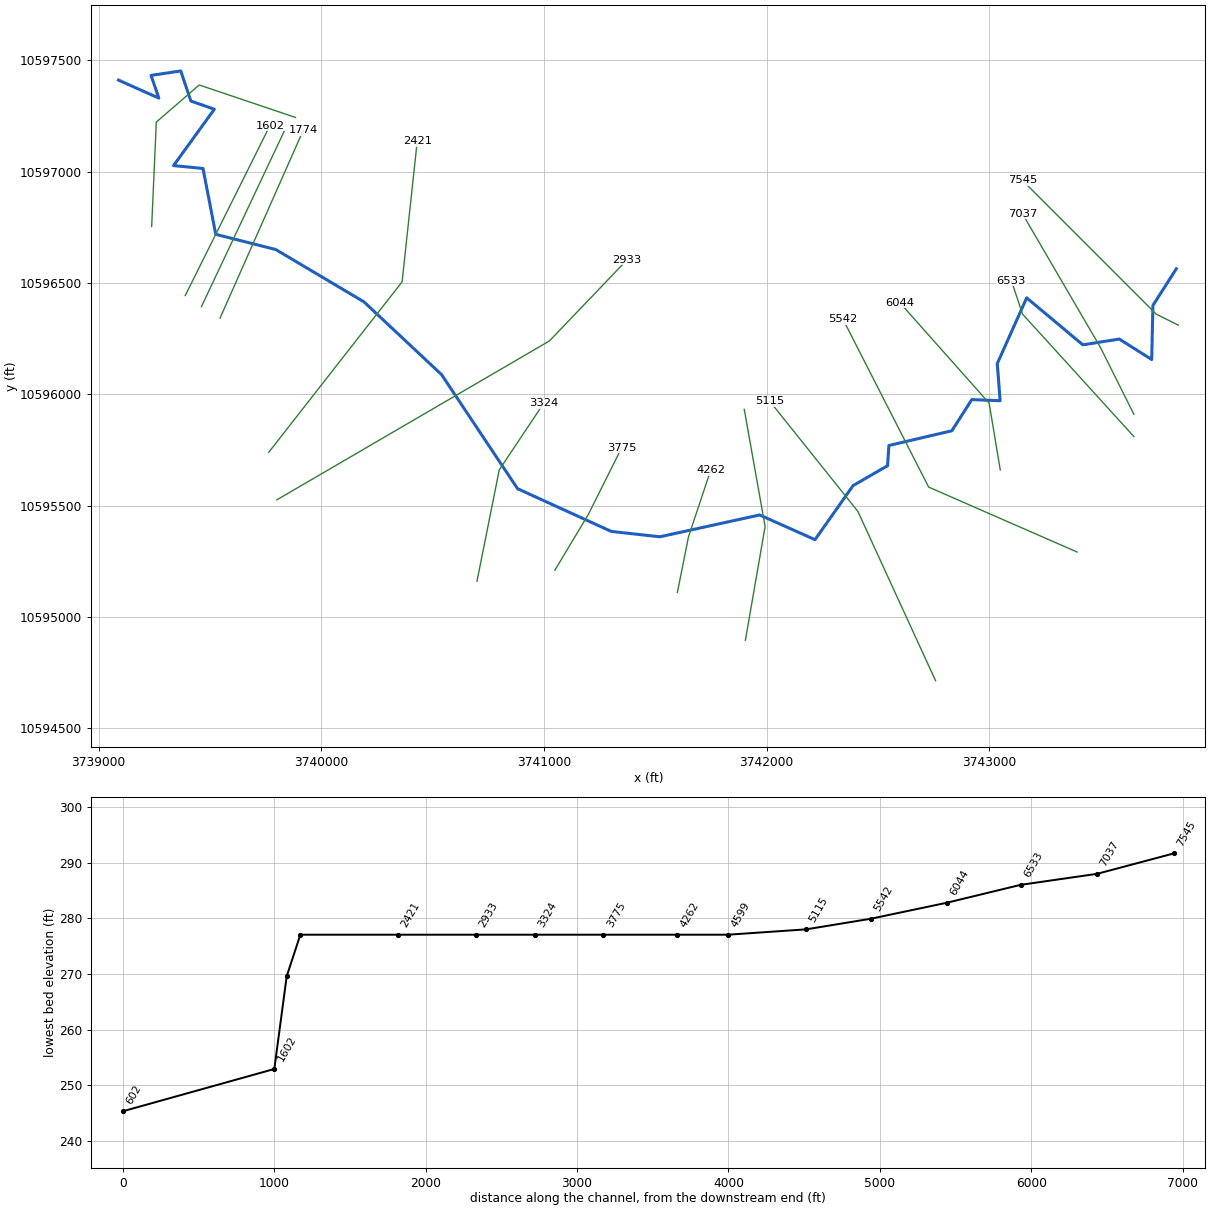
--- UNT 178 IN BOCR.prj (project) ---

Proj Title=UNT 178 IN BOCR Base Level Engineering
Current Plan=p01
Default Exp/Contr=0.3,0.1
English Units
Geom File=g01
Flow File=f01
Plan File=p01
BEGIN DESCRIPTION:
UNT 178 IN BOCR
END DESCRIPTION:

--- UNT 178 IN BOCR.p01 (plan) ---

Plan Title=Multiple Run
Short Identifier=Multiple
Geom File=g01
Flow File=f01
Subcritical Flow
K Sum by GR= 0
Std Step Tol= 0.01
Critical Tol= 0.01
Num of Std Step Trials= 20
Max Error Tol= 0.3
Flow Tol Ratio= 0.001
Split Flow NTrial= 30
Split Flow Tol= 0.02
Split Flow Ratio= 0.02
Log Output Level= 0
Friction Slope Method= 1
Unsteady Friction Slope Method= 2
Unsteady Bridges Friction Slope Method= 1
Parabolic Critical Depth
Global Vel Dist=  1 , 1 , 1
Global Log Level= 0
CheckData=True
Encroach Param= -1, 0, 0, 0
BEGIN DESCRIPTION:
Multiple Run
END DESCRIPTION:

--- UNT 178 IN BOCR.f01 (steady flow) ---

Flow Title=Multiple
Number of Profiles=7
Profile Names=10-year,25-year,50-year,1pct_min,100-year,1pct_plu,500-year
River Rch & RM= UNT 178 IN BOCR,Reach-1,7545
     417     550     658     579     783    1060    1113
Boundary for River Rch & Prof#=UNT 178 IN BOCR,Reach-1,1
Up Type=0
Dn Type=3
Dn Slope=0.005
Boundary for River Rch & Prof#=UNT 178 IN BOCR,Reach-1,2
Up Type=0
Dn Type=3
Dn Slope=0.005
Boundary for River Rch & Prof#=UNT 178 IN BOCR,Reach-1,3
Up Type=0
Dn Type=3
Dn Slope=0.005
Boundary for River Rch & Prof#=UNT 178 IN BOCR,Reach-1,4
Up Type=0
Dn Type=3
Dn Slope=0.005
Boundary for River Rch & Prof#=UNT 178 IN BOCR,Reach-1,5
Up Type=0
Dn Type=3
Dn Slope=0.005
Boundary for River Rch & Prof#=UNT 178 IN BOCR,Reach-1,6
Up Type=0
Dn Type=3
Dn Slope=0.005
Boundary for River Rch & Prof#=UNT 178 IN BOCR,Reach-1,7
Up Type=0
Dn Type=3
Dn Slope=0.005

--- UNT 178 IN BOCR.g01 (geometry) ---

Geom Title=Existing Conditions

River Reach=UNT 178 IN BOCR,Reach-1
Reach XY= 30
      3743840.16     10596563.37      3743735.25     10596399.00
      3743729.75     10596156.00      3743584.00     10596248.00
      3743420.50     10596222.00      3743168.25     10596433.00
      3743036.25     10596138.00      3743049.00     10595971.00
      3742921.75     10595976.00      3742832.25     10595836.00
      3742549.50     10595770.00      3742543.50     10595679.00
      3742388.75     10595590.00      3742217.75     10595347.00
      3741969.00     10595458.00      3741521.00     10595360.00
      3741303.00     10595384.00      3740881.75     10595576.00
      3740540.75     10596088.00      3740192.00     10596415.00
      3739796.00     10596650.00      3739526.43     10596718.30
      3739469.25     10597014.00      3739337.00     10597027.00
      3739520.00     10597280.00      3739414.75     10597317.00
      3739369.25     10597452.00      3739236.00     10597432.00
      3739270.75     10597330.00      3739089.50     10597411.00

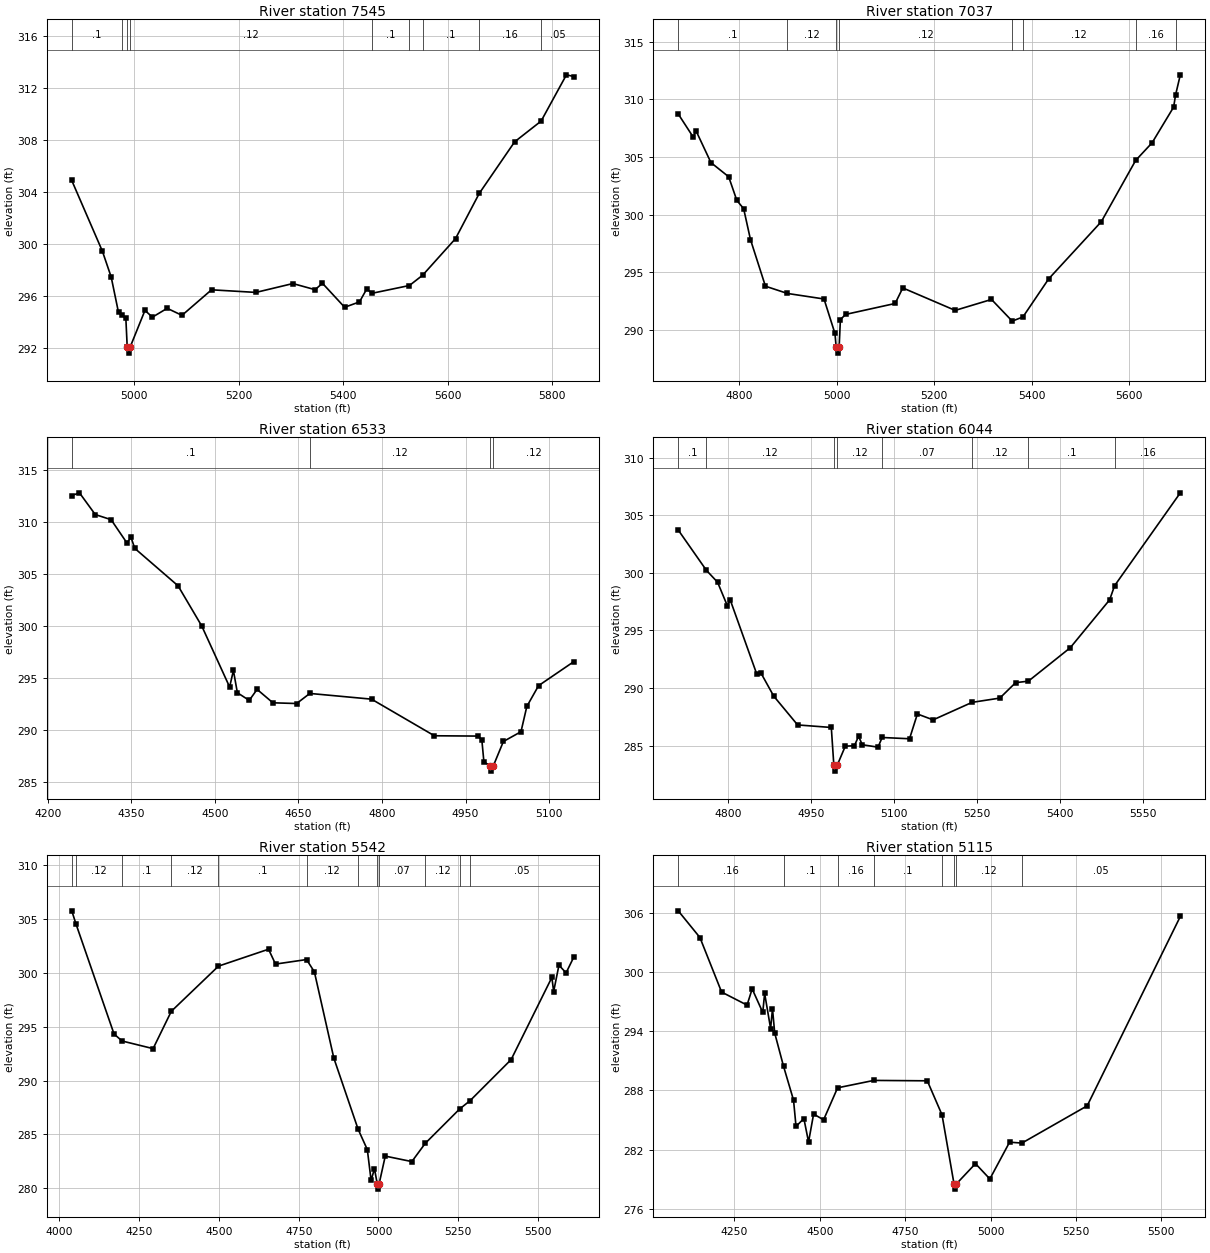
Type RM Length L Ch R = 1,7545,508,508,508
BEGIN DESCRIPTION:
UNT 178 IN BOCR 14.0
END DESCRIPTION:
XS GIS Cut Line= 3
      3743849.57     10596310.21      3743749.61     10596360.19
      3743149.60     10596960.20
#Sta/Elev= 30
  4880.8  304.89  4939.4  299.46  4956.2  297.48  4970.2  294.76  4976.6  294.55
  4984.2  294.35  4986.8  292.14  4989.5  291.64  4992.8  292.14  5020.8  294.92
  5035.0  294.40  5063.3  295.08  5091.6  294.54  5148.1  296.50  5233.0  296.30
  5303.7  296.98  5346.1  296.51  5360.3  297.00  5402.7  295.16  5431.0  295.57
  5445.1  296.57  5454.7  296.23  5526.6  296.83  5551.9  297.62  5614.8  300.43
  5660.2  303.90  5727.9  307.86  5778.5  309.45  5826.9  313.00  5841.1  312.87
#Mann=9,-1,0
  4880.8     0.1       0  4976.6    0.12       0  4986.8    0.07       0
  4992.8    0.12       0  5454.7     0.1       0  5526.6    0.12       0
  5551.9     0.1       0  5660.2    0.16       0  5778.5    0.05       0
Bank Sta=4986.8,4992.8
Exp/Cntr=0.3,0.1

Type RM Length L Ch R = 1,7037,504,504,504
BEGIN DESCRIPTION:
UNT 178 IN BOCR 13.0
END DESCRIPTION:
XS GIS Cut Line= 3
      3743649.63     10595910.16      3743499.61     10596210.19
      3743149.59     10596810.22
#Sta/Elev= 30
  4674.7  308.73  4705.5  306.72  4711.1  307.28  4741.8  304.51  4778.2  303.28
  4794.9  301.23  4808.9  300.51  4822.9  297.83  4853.6  293.78  4898.8  293.15
  4973.8  292.67  4996.2  289.68  4998.8  288.47  5001.5  287.97  5004.8  288.47
  5007.4  290.88  5018.0  291.33  5119.7  292.28  5135.4  293.63  5242.9  291.68
  5317.4  292.63  5359.9  290.75  5381.9  291.11  5434.8  294.42  5542.7  299.38
  5613.2  304.70  5646.9  306.23  5691.1  309.33  5695.1  310.39  5704.8  312.13
#Mann=8,-1,0
  4674.7     0.1       0  4898.8    0.12       0  4998.8    0.07       0
  5004.8    0.12       0  5359.9     0.1       0  5381.9    0.12       0
  5613.2    0.16       0  5695.1     0.1       0
Bank Sta=4998.8,5004.8
Exp/Cntr=0.3,0.1

Type RM Length L Ch R = 1,6533,489,489,489
BEGIN DESCRIPTION:
UNT 178 IN BOCR 12.0
END DESCRIPTION:
XS GIS Cut Line= 3
      3743649.58     10595810.22      3743149.61     10596360.19
      3743099.60     10596510.22
#Sta/Elev= 30
  4243.0  312.50  4256.8  312.76  4285.2  310.67  4313.6  310.18  4341.9  307.95
  4349.4  308.47  4356.1  307.42  4433.8  303.82  4476.4  299.95  4526.4  294.09
  4533.2  295.68  4540.3  293.54  4561.6  292.80  4575.7  293.86  4604.1  292.57
  4646.7  292.50  4670.4  293.47  4781.2  292.92  4894.0  289.40  4972.4  289.37
  4979.2  289.01  4982.9  286.90  4993.8  286.50  4996.5  286.00  4999.8  286.50
  5017.9  288.85  5049.5  289.79  5060.0  292.22  5081.1  294.22  5144.4  296.53
#Mann=4,-1,0
  4243.0     0.1       0  4670.4    0.12       0  4993.8    0.07       0
  4999.8    0.12       0
Bank Sta=4993.8,4999.8
Exp/Cntr=0.3,0.1

Type RM Length L Ch R = 1,6044,502,502,502
BEGIN DESCRIPTION:
UNT 178 IN BOCR 11.0
END DESCRIPTION:
XS GIS Cut Line= 3
      3743049.61     10595660.15      3742999.61     10595960.19
      3742599.58     10596410.22
#Sta/Elev= 30
  4710.3  303.71  4761.2  300.21  4781.3  299.18  4799.0  297.13  4804.1  297.65
  4852.3  291.17  4859.9  291.27  4882.7  289.29  4925.8  286.79  4986.6  286.57
  4991.2  283.28  4993.9  282.78  4997.2  283.28  5011.9  284.95  5028.3  284.98
  5035.8  285.81  5042.5  285.07  5070.9  284.86  5078.4  285.70  5127.8  285.59
  5142.0  287.74  5170.4  287.23  5240.7  288.75  5290.8  289.12  5319.3  290.46
  5342.3  290.59  5417.9  293.49  5489.0  297.65  5498.0  298.88  5616.6  306.94
#Mann=8,-1,0
  4710.3     0.1       0  4761.2    0.12       0  4991.2    0.07       0
  4997.2    0.12       0  5078.4    0.07       0  5240.7    0.12       0
  5342.3     0.1       0  5498.0    0.16       0
Bank Sta=4991.2,4997.2
Exp/Cntr=0.3,0.1

Type RM Length L Ch R = 1,5542,427,427,427
BEGIN DESCRIPTION:
UNT 178 IN BOCR 10.0
END DESCRIPTION:
XS GIS Cut Line= 3
      3743394.64     10595291.52      3742728.00     10595583.17
      3742343.41     10596336.76
#Sta/Elev= 30
  4038.7  305.78  4051.9  304.56  4171.2  294.33  4196.4  293.68  4293.6  292.97
  4350.7  296.44  4498.6  300.64  4655.4  302.21  4677.3  300.83  4774.6  301.25
  4799.1  300.11  4860.1  292.09  4936.3  285.47  4965.1  283.58  4976.9  280.72
  4987.5  281.81  4996.1  280.41  4998.8  279.91  5002.1  280.41  5021.3  282.98
  5104.6  282.47  5146.5  284.16  5254.5  287.36  5287.4  288.14  5415.8  291.95
  5543.5  299.59  5549.1  298.28  5565.7  300.73  5588.0  300.01  5612.4  301.49
#Mann=12,-1,0
  4038.7     0.1       0  4051.9    0.12       0  4196.4     0.1       0
  4350.7    0.12       0  4498.6     0.1       0  4774.6    0.12       0
  4936.3    0.07       0  4996.1    0.07       0  5002.1    0.07       0
  5146.5    0.12       0  5254.5     0.1       0  5287.4    0.05       0
Bank Sta=4996.1,5002.1
Exp/Cntr=0.3,0.1

Type RM Length L Ch R = 1,5115,516,516,516
BEGIN DESCRIPTION:
UNT 178 IN BOCR 9.0
END DESCRIPTION:
XS GIS Cut Line= 3
      3742759.25     10594713.39      3742410.29     10595473.80
      3742014.52     10595968.51
#Sta/Elev= 30
  4085.3  306.17  4148.8  303.47  4212.3  297.95  4286.8  296.63  4301.8  298.27
  4332.8  295.89  4338.3  297.82  4355.8  294.26  4361.3  296.26  4367.8  293.80
  4393.8  290.42  4422.9  287.02  4430.2  284.36  4453.2  285.15  4466.9  282.78
  4481.7  285.61  4510.9  285.02  4551.9  288.26  4658.0  289.01  4814.6  288.97
  4857.7  285.53  4893.0  278.51  4895.7  278.01  4899.0  278.51  4955.7  280.59
  4997.8  279.04  5055.5  282.76  5091.7  282.67  5282.8  286.44  5555.5  305.60
#Mann=8,-1,0
  4085.3    0.16       0  4393.8     0.1       0  4551.9    0.16       0
  4658.0     0.1       0  4857.7    0.12       0  4893.0    0.07       0
  4899.0    0.12       0  5091.7    0.05       0
Bank Sta=4893,4899
Exp/Cntr=0.3,0.1

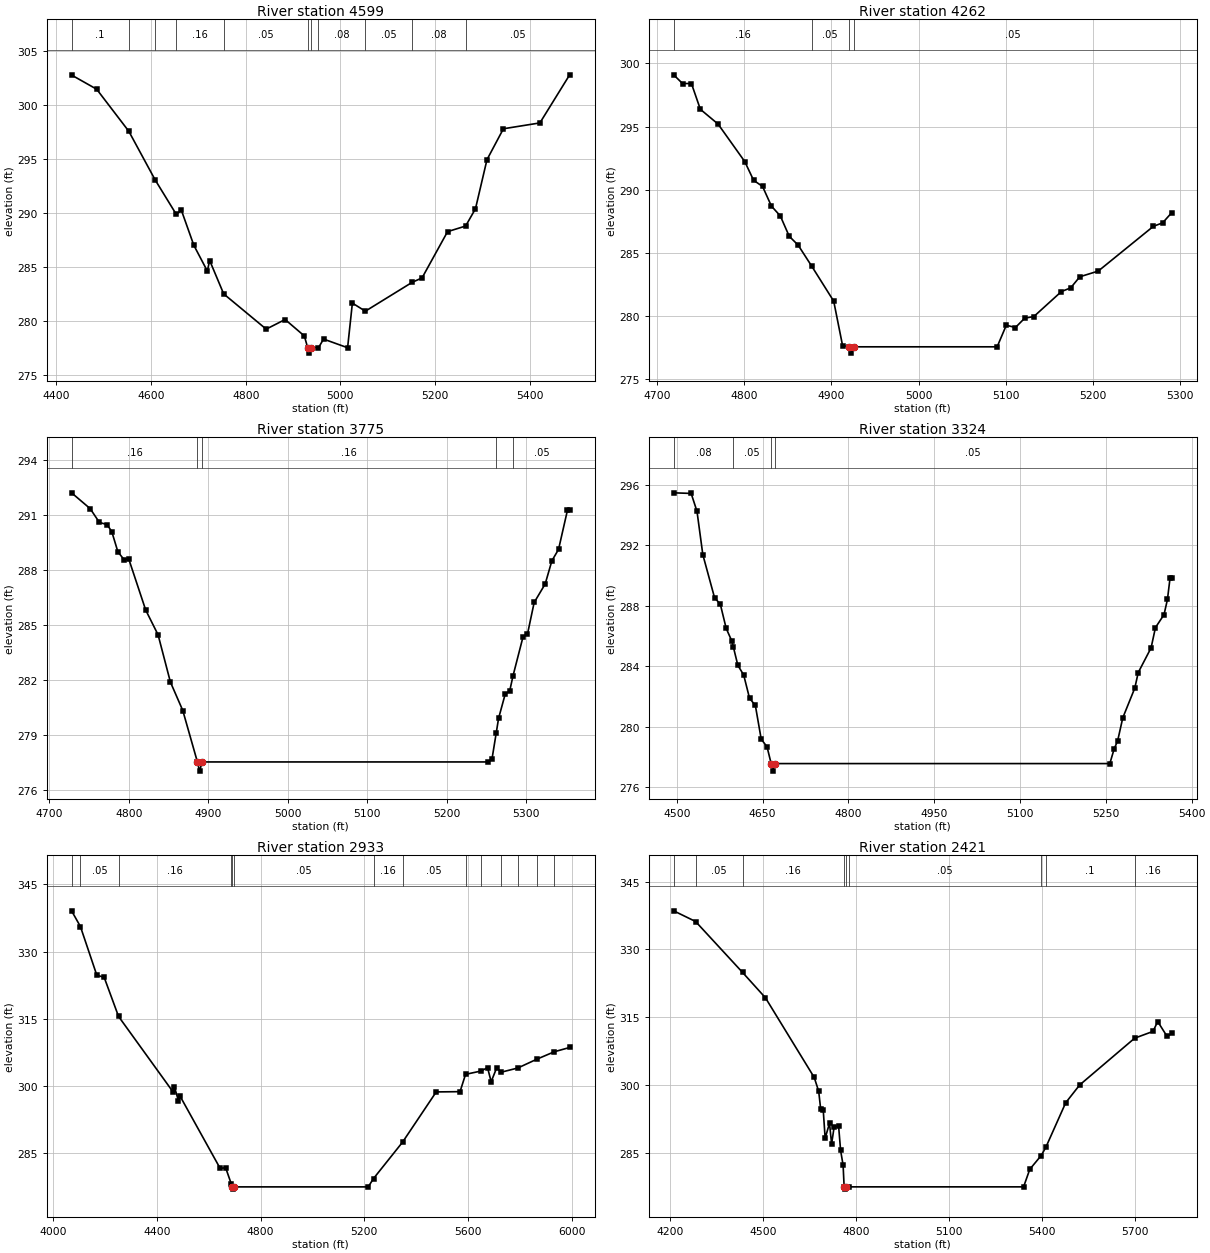
Type RM Length L Ch R = 1,4599,337,337,337
BEGIN DESCRIPTION:
UNT 178 IN BOCR 8.0
END DESCRIPTION:
XS GIS Cut Line= 3
      3741905.08     10594895.64      3741993.63     10595406.09
      3741899.88     10595932.13
#Sta/Elev= 30
  4432.1  302.78  4485.1  301.47  4553.0  297.58  4608.8  293.07  4653.2  289.90
  4664.2  290.26  4690.4  287.03  4718.9  284.65  4723.9  285.62  4753.5  282.53
  4843.3  279.27  4883.3  280.16  4923.9  278.64  4931.0  277.55  4933.8  277.05
  4937.0  277.55  4953.8  277.55  4964.5  278.35  5015.3  277.55  5025.4  281.68
  5052.8  280.93  5151.7  283.60  5172.6  284.01  5226.5  288.29  5264.7  288.81
  5285.5  290.41  5309.8  294.95  5344.5  297.81  5421.6  298.35  5484.5  302.80
#Mann=11,-1,0
  4432.1     0.1       0  4553.0    0.05       0  4608.8     0.1       0
  4653.2    0.16       0  4753.5    0.05       0  4931.0    0.07       0
  4937.0    0.05       0  4953.8    0.08       0  5052.8    0.05       0
  5151.7    0.08       0  5264.7    0.05       0
Bank Sta=4931,4937
Exp/Cntr=0.3,0.1

Type RM Length L Ch R = 1,4262,487,487,487
BEGIN DESCRIPTION:
UNT 178 IN BOCR 7.0
END DESCRIPTION:
XS GIS Cut Line= 3
      3741599.62     10595110.23      3741649.61     10595360.19
      3741749.60     10595660.15
#Sta/Elev= 30
  4719.1  299.10  4729.3  298.41  4739.5  298.41  4749.7  296.37  4770.0  295.20
  4800.6  292.23  4810.8  290.74  4821.0  290.26  4831.2  288.70  4841.4  287.92
  4851.6  286.31  4861.8  285.61  4877.3  283.95  4902.6  281.17  4912.8  277.64
  4920.0  277.55  4922.8  277.05  4926.0  277.55  5090.0  277.55  5100.5  279.26
  5111.0  279.08  5121.6  279.82  5132.1  279.95  5163.7  281.93  5174.3  282.22
  5184.8  283.10  5205.9  283.55  5269.2  287.10  5279.7  287.37  5290.2  288.18
#Mann=4,-1,0
  4719.1    0.16       0  4877.3    0.05       0  4920.0   0.033       0
  4926.0    0.05       0
Bank Sta=4920,4926
Exp/Cntr=0.3,0.1

Type RM Length L Ch R = 1,3775,451,451,451
BEGIN DESCRIPTION:
UNT 178 IN BOCR 6.0
END DESCRIPTION:
XS GIS Cut Line= 3
      3741049.59     10595210.16      3741199.61     10595460.19
      3741349.61     10595760.20
#Sta/Elev= 30
  4727.9  292.20  4751.3  291.34  4762.9  290.59  4772.6  290.47  4778.5  290.09
  4786.2  288.99  4794.0  288.56  4799.8  288.61  4821.2  285.82  4836.8  284.47
  4852.3  281.90  4867.9  280.35  4886.3  277.55  4889.0  277.05  4892.3  277.55
  5251.5  277.55  5257.1  277.70  5262.5  279.14  5265.4  279.92  5273.8  281.25
  5279.4  281.41  5283.6  282.24  5296.2  284.36  5301.8  284.51  5310.2  286.23
  5324.1  287.24  5332.5  288.50  5340.9  289.12  5352.1  291.25  5354.9  291.25
#Mann=5,-1,0
  4727.9    0.16       0  4886.3   0.033       0  4892.3    0.16       0
  5262.5    0.16       0  5283.6    0.05       0
Bank Sta=4886.3,4892.3
Exp/Cntr=0.3,0.1

Type RM Length L Ch R = 1,3324,391,391,391
BEGIN DESCRIPTION:
UNT 178 IN BOCR 5.0
END DESCRIPTION:
XS GIS Cut Line= 3
      3740699.60     10595160.15      3740799.61     10595660.19
      3740999.61     10595960.19
#Sta/Elev= 30
  4494.7  295.49  4525.3  295.45  4535.5  294.26  4545.7  291.39  4566.1  288.55
  4576.3  288.10  4586.5  286.51  4596.7  285.64  4599.2  285.25  4606.9  284.06
  4617.1  283.42  4627.3  281.88  4637.5  281.40  4647.7  279.17  4657.9  278.66
  4665.1  277.55  4667.9  277.05  4671.1  277.55  5257.0  277.55  5264.5  278.52
  5270.6  279.05  5279.6  280.58  5300.6  282.55  5306.6  283.58  5329.1  285.22
  5336.7  286.56  5351.7  287.42  5357.7  288.43  5362.2  289.84  5365.2  289.84
#Mann=4,-1,0
  4494.7    0.08       0  4599.2    0.05       0  4665.1   0.033       0
  4671.1    0.05       0
Bank Sta=4665.1,4671.1
Exp/Cntr=0.3,0.1

Type RM Length L Ch R = 1,2933,512,512,512
BEGIN DESCRIPTION:
UNT 178 IN BOCR 4.0
END DESCRIPTION:
XS GIS Cut Line= 3
      3739800.96     10595525.91      3741024.88     10596239.42
      3741373.85     10596604.02
#Sta/Elev= 30
  4071.1  339.12  4105.2  335.62  4168.4  324.77  4196.9  324.28  4252.3  315.57
  4462.0  298.77  4467.8  299.88  4483.5  296.73  4489.3  297.82  4644.0  281.70
  4665.5  281.81  4687.1  278.23  4691.6  277.55  4694.3  277.05  4697.6  277.55
  5215.5  277.55  5235.8  279.41  5347.8  287.52  5477.7  298.73  5569.6  298.79
  5590.9  302.65  5651.3  303.40  5675.6  304.16  5689.7  301.02  5710.8  304.07
  5728.4  303.13  5792.3  304.06  5865.9  306.03  5933.3  307.69  5992.5  308.64
#Mann=14,-1,0
  4071.1    0.16       0  4105.2    0.05       0  4252.3    0.16       0
  4687.1    0.05       0  4691.6   0.033       0  4697.6    0.05       0
  5235.8    0.16       0  5347.8    0.05       0  5590.9    0.08       0
  5651.3    0.05       0  5728.4    0.08       0  5792.3    0.05       0
  5865.9    0.08       0  5933.3    0.05       0
Bank Sta=4691.6,4697.6
Exp/Cntr=0.3,0.1

Type RM Length L Ch R = 1,2421,647,647,647
BEGIN DESCRIPTION:
UNT 178 IN BOCR 3.0
END DESCRIPTION:
XS GIS Cut Line= 3
      3739764.48     10595739.45      3740363.42     10596505.05
      3740431.12     10597135.17
#Sta/Elev= 30
  4212.0  338.53  4282.7  336.17  4434.3  324.91  4507.8  319.33  4665.2  301.72
  4679.6  298.66  4686.0  294.72  4694.1  294.64  4700.4  288.30  4714.5  291.61
  4721.2  287.03  4729.4  290.79  4743.8  290.97  4750.2  285.61  4758.3  282.33
  4761.6  277.55  4764.4  277.05  4767.6  277.55  4776.2  277.55  5340.1  277.55
  5360.2  281.44  5396.9  284.47  5411.8  286.28  5475.9  296.13  5521.1  300.07
  5698.3  310.40  5757.2  311.89  5772.6  314.07  5802.7  310.79  5817.8  311.45
#Mann=9,-1,0
  4212.0    0.16       0  4282.7    0.05       0  4434.3    0.16       0
  4761.6   0.033       0  4767.6    0.16       0  4776.2    0.05       0
  5396.9    0.16       0  5411.8     0.1       0  5698.3    0.16       0
Bank Sta=4761.6,4767.6
Exp/Cntr=0.3,0.1

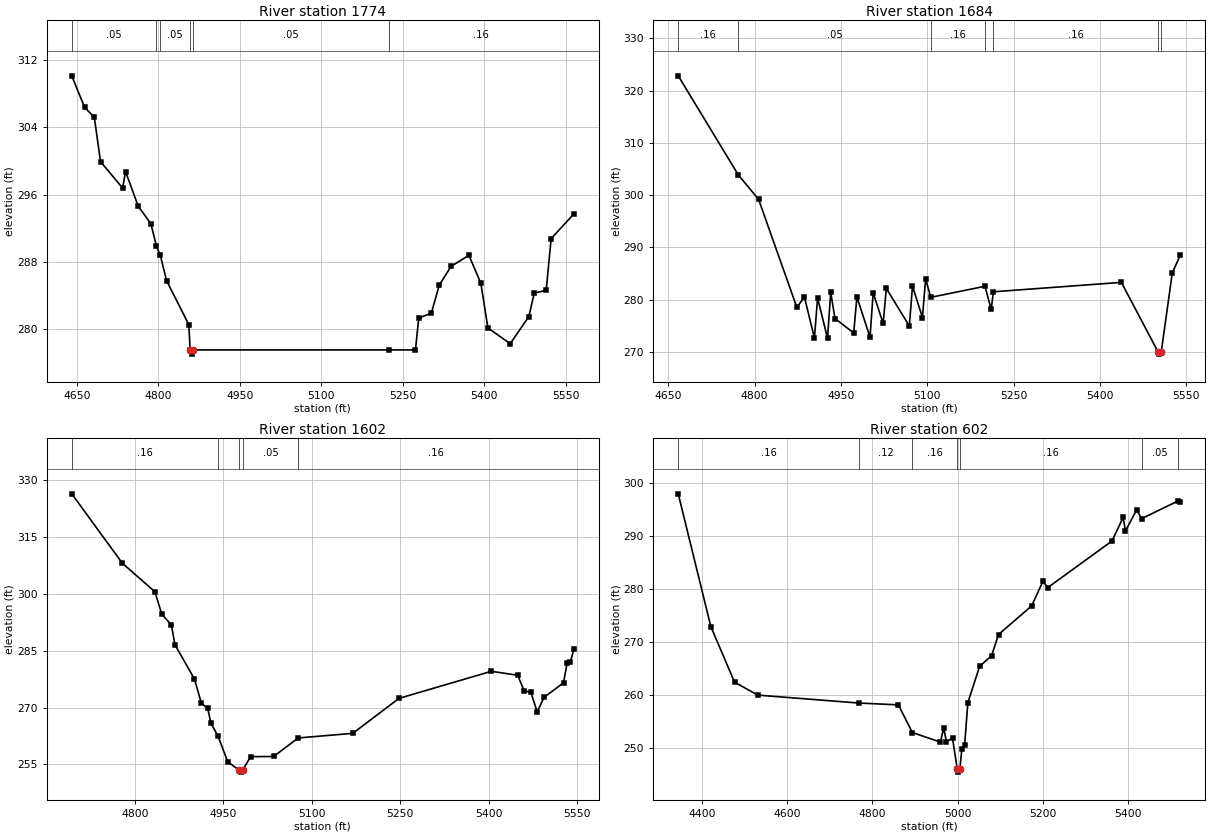
Type RM Length L Ch R = 1,1774,90,90,90
BEGIN DESCRIPTION:
Mapping XS 893b7fd5
END DESCRIPTION:
XS GIS Cut Line= 2
      3739545.71     10596341.86      3739920.06     10597186.74
#Sta/Elev= 30
  4640.9  310.14  4664.6  306.38  4682.4  305.22  4693.8  299.94  4734.5  296.80
  4739.9  298.76  4763.2  294.64  4786.5  292.55  4796.8  289.88  4803.9  288.80
  4815.3  285.80  4856.3  280.56  4858.8  277.55  4861.6  277.05  4864.8  277.55
  5224.4  277.55  5273.5  277.55  5279.5  281.35  5302.7  281.91  5317.2  285.24
  5339.1  287.49  5371.9  288.80  5393.8  285.48  5406.8  280.17  5447.9  278.29
  5482.1  281.51  5492.2  284.33  5514.1  284.62  5523.2  290.78  5565.0  293.72
#Mann=6,-1,0
  4640.9    0.05       0  4796.8    0.16       0  4803.9    0.05       0
  4858.8   0.033       0  4864.8    0.05       0  5224.4    0.16       0
Bank Sta=4858.8,4864.8
Exp/Cntr=0.3,0.1

Type RM Length L Ch R = 1,1684,82,82,82
BEGIN DESCRIPTION:
Mapping XS 1cef2097
END DESCRIPTION:
XS GIS Cut Line= 2
      3739462.37     10596393.92      3739834.67     10597182.78
#Sta/Elev= 30
  4667.2  322.82  4771.6  303.87  4806.8  299.20  4873.2  278.58  4886.5  280.49
  4903.8  272.69  4909.3  280.35  4926.6  272.63  4932.1  281.44  4939.5  276.42
  4972.1  273.66  4977.6  280.56  5000.4  272.84  5005.9  281.32  5023.2  275.48
  5028.7  282.17  5068.7  274.99  5074.2  282.60  5091.5  276.61  5097.0  284.03
  5105.8  280.47  5200.1  282.58  5210.9  278.17  5214.8  281.53  5437.1  283.33
  5500.5  270.11  5503.2  269.61  5506.5  270.11  5525.6  285.19  5539.5  288.50
#Mann=7,-1,0
  4667.2    0.16       0  4771.6    0.05       0  5105.8    0.16       0
  5200.1    0.05       0  5214.8    0.16       0  5500.5    0.04       0
  5506.5    0.16       0
Bank Sta=5500.5,5506.5
Exp/Cntr=0.3,0.1

Type RM Length L Ch R = 1,1602,1000,1000,1000
BEGIN DESCRIPTION:
UNT 178 IN BOCR 2.0
END DESCRIPTION:
XS GIS Cut Line= 2
      3739389.47     10596443.43      3739769.36     10597205.83
#Sta/Elev= 30
  4692.9  326.43  4778.7  308.11  4833.9  300.57  4845.7  294.64  4861.9  291.81
  4868.0  286.57  4901.1  277.54  4912.7  271.16  4923.5  269.79  4929.1  265.82
  4941.0  262.45  4957.4  255.72  4976.8  253.45  4979.5  252.95  4982.8  253.45
  4996.2  257.03  5035.4  257.08  5077.0  261.97  5169.7  263.19  5248.0  272.42
  5404.7  279.57  5449.5  278.53  5460.2  274.44  5471.9  273.99  5482.5  268.85
  5494.2  272.70  5527.2  276.54  5533.4  281.86  5539.0  282.08  5544.7  285.41
#Mann=5,-1,0
  4692.9    0.16       0  4941.0    0.05       0  4976.8    0.04       0
  4982.8    0.05       0  5077.0    0.16       0
Bank Sta=4976.8,4982.8
Exp/Cntr=0.3,0.1

Type RM Length L Ch R = 1,602,0,0,0
BEGIN DESCRIPTION:
UNT 178 IN BOCR 1.0
END DESCRIPTION:
XS GIS Cut Line= 4
      3739238.71     10596753.62      3739259.54     10597222.35
      3739452.25     10597389.02      3739884.54     10597243.19
#Sta/Elev= 30
  4343.4  297.91  4420.0  272.86  4475.7  262.36  4530.2  259.91  4768.3  258.41
  4860.9  258.07  4893.7  252.85  4959.6  251.04  4967.3  253.70  4973.9  251.14
  4988.1  251.77  4999.4  245.87  5002.1  245.37  5005.4  245.87  5010.0  249.73
  5016.6  250.49  5024.2  258.51  5051.8  265.32  5079.9  267.35  5096.3  271.35
  5174.3  276.77  5200.5  281.37  5212.3  280.22  5363.1  289.01  5389.3  293.49
  5394.6  290.90  5420.8  294.86  5433.0  293.24  5519.0  296.59  5523.6  296.33
#Mann=7,-1,0
  4343.4    0.16       0  4768.3    0.12       0  4893.7    0.16       0
  4999.4    0.07       0  5005.4    0.16       0  5433.0    0.05       0
  5519.0    0.16       0
Bank Sta=4999.4,5005.4
Exp/Cntr=0.3,0.1

Chan Stop Cuts=-1