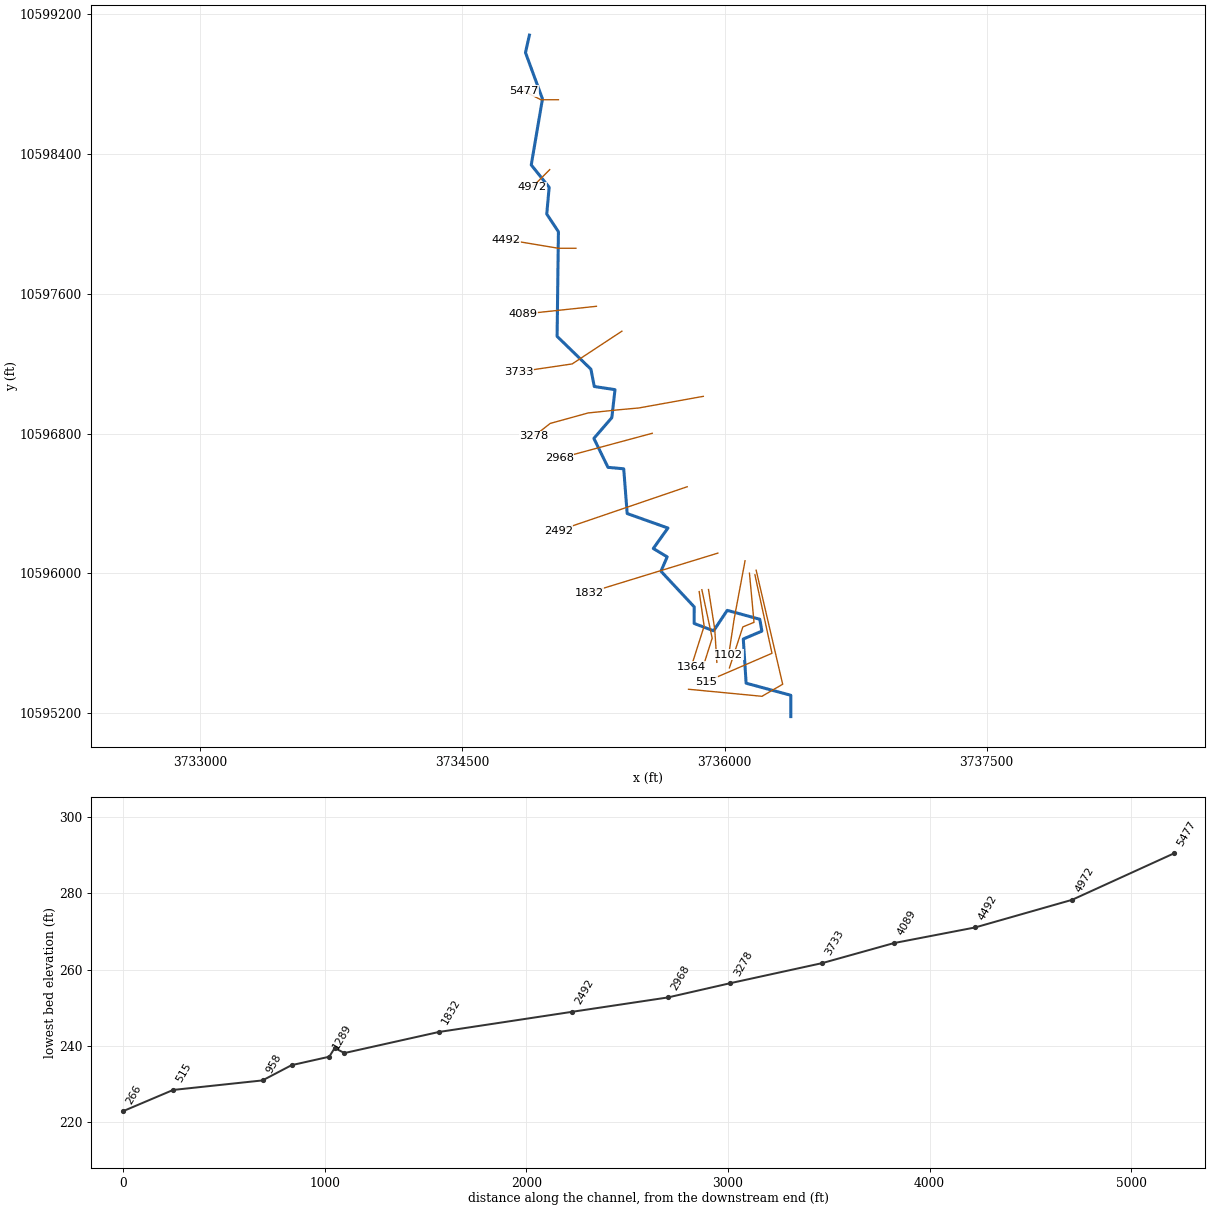
--- UNT 179 IN BOCR.prj (project) ---

Proj Title=UNT 179 IN BOCR Base Level Engineering
Current Plan=p01
Default Exp/Contr=0.3,0.1
English Units
Geom File=g01
Flow File=f01
Plan File=p01
Y Axis Title=Elevation
X Axis Title(PF)=Main Channel Distance
X Axis Title(XS)=Station
BEGIN DESCRIPTION:
UNT 179 IN BOCR
END DESCRIPTION:
DSS Export Rating Curves= 0
DSS Export Rating Curve Sorted= 0
DSS Export Volume Flow Curves= 0
DXF OffsetX= 0
DXF OffsetY= 0
DXF ScaleX= 1
DXF ScaleY= 10

--- UNT 179 IN BOCR.p01 (plan) ---

Plan Title=Multiple Run
Short Identifier=Multiple
Geom File=g01
Flow File=f01
Subcritical Flow
K Sum by GR= 0
Std Step Tol= 0.01
Critical Tol= 0.01
Num of Std Step Trials= 20
Max Error Tol= 0.3
Flow Tol Ratio= 0.001
Split Flow NTrial= 30
Split Flow Tol= 0.02
Split Flow Ratio= 0.02
Log Output Level= 0
Friction Slope Method= 1
Unsteady Friction Slope Method= 2
Unsteady Bridges Friction Slope Method= 1
Parabolic Critical Depth
Global Vel Dist=  1 , 1 , 1
Global Log Level= 0
CheckData=True
Encroach Param= -1, 0, 0, 0
BEGIN DESCRIPTION:
Multiple Run
END DESCRIPTION:

--- UNT 179 IN BOCR.f01 (steady flow) ---

Flow Title=Multiple
Program Version=4.10
Number of Profiles= 7
Profile Names=10-year,25-year,50-year,1pct_min,100-year,1pct_plu,500-year
River Rch & RM=UNT 179 IN BOCR,Reach-1         ,5477
     341     449     536     472     638     863     906
Boundary for River Rch & Prof#=UNT 179 IN BOCR,Reach-1         , 1
Up Type= 0
Dn Type= 3
Dn Slope=0.008
Boundary for River Rch & Prof#=UNT 179 IN BOCR,Reach-1         , 2
Up Type= 0
Dn Type= 3
Dn Slope=0.008
Boundary for River Rch & Prof#=UNT 179 IN BOCR,Reach-1         , 3
Up Type= 0
Dn Type= 3
Dn Slope=0.008
Boundary for River Rch & Prof#=UNT 179 IN BOCR,Reach-1         , 4
Up Type= 0
Dn Type= 3
Dn Slope=0.008
Boundary for River Rch & Prof#=UNT 179 IN BOCR,Reach-1         , 5
Up Type= 0
Dn Type= 3
Dn Slope=0.008
Boundary for River Rch & Prof#=UNT 179 IN BOCR,Reach-1         , 6
Up Type= 0
Dn Type= 3
Dn Slope=0.008
Boundary for River Rch & Prof#=UNT 179 IN BOCR,Reach-1         , 7
Up Type= 0
Dn Type= 3
Dn Slope=0.008
DSS Import GetInterval= 0
DSS Import GetPeak= 0
DSS Import FillOption= 0

--- UNT 179 IN BOCR.g01 (geometry) ---

Geom Title=Existing Conditions
Program Version=4.10

River Reach=UNT 179 IN BOCR ,Reach-1
Reach XY= 30
       3734883.5       10599080.        3734861.       10598980.
      3734958.25       10598715.        3734894.       10598337.
       3734996.5       10598209.      3734982.75       10598056.
       3735049.5       10597955.        3735042.       10597356.
       3735235.5       10597168.      3735254.75       10597069.
      3735373.25       10597051.      3735355.25       10596891.
       3735252.5       10596772.      3735333.09     10596606.53
      3735423.25       10596598.        3735443.       10596342.
      3735676.25       10596259.       3735592.5       10596142.
        3735672.       10596094.      3735636.25       10596012.
       3735826.5       10595808.      3735826.25       10595713.
      3735937.75       10595671.       3736015.5       10595788.
        3736202.       10595737.      3736213.75       10595669.
       3736107.5       10595624.      3736123.75       10595371.
      3736379.25       10595302.       3736379.5       10595180.

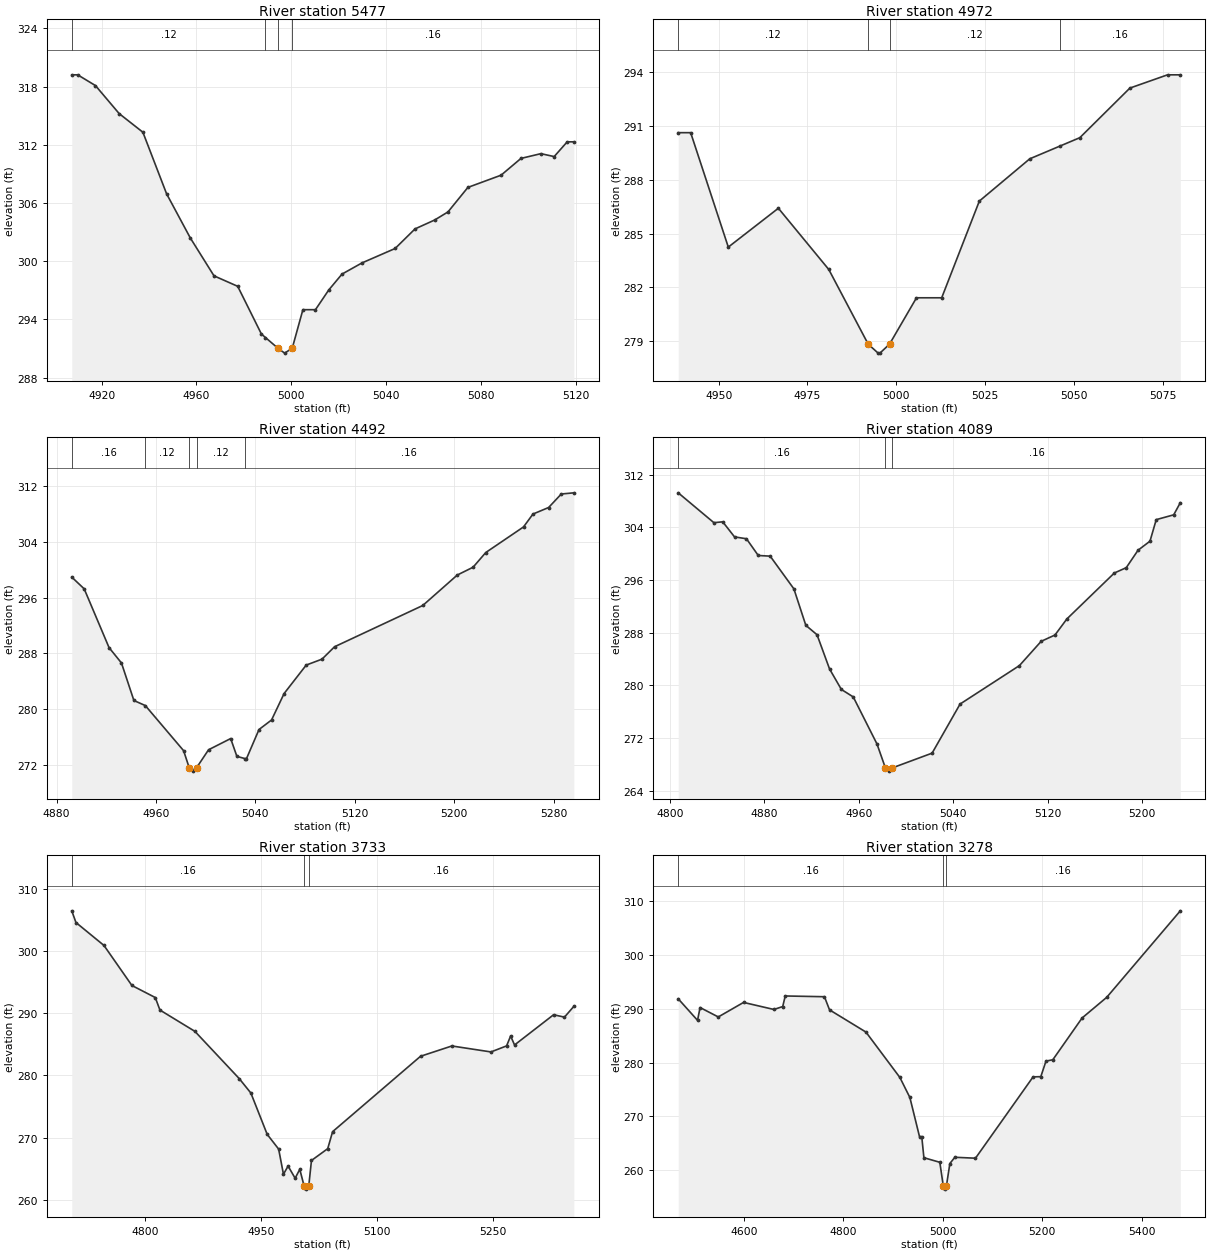
Type RM Length L Ch R = 1 ,5477    ,505,505,505
BEGIN DESCRIPTION:
UNT 179 IN BOCR 10.0
END DESCRIPTION:
XS GIS Cut Line= 3
      3735049.65     10598710.19      3734949.61     10598710.19
      3734849.65     10598760.17
#Sta/Elev= 30
  4907.4  319.22  4909.9  319.22  4917.4  318.11  4927.4  315.22  4937.4   313.3
  4947.4  306.95  4957.4   302.4  4967.4  298.49  4977.4  297.41  4987.4  292.49
  4989.1  292.13  4994.4  291.02  4997.2  290.52  5000.4  291.02  5004.9     295
  5010.2     295  5015.8  297.03  5021.4  298.67  5029.8  299.82  5043.8  301.31
  5052.2  303.33  5060.5  304.25  5066.1  305.08  5074.5  307.61  5088.5  308.87
  5096.9   310.6  5105.3  311.09  5110.9  310.79  5116.4  312.31  5119.2  312.31
#Mann= 4 ,-1 , 0
  4907.4     .12       0  4989.1     .16       0  4994.4     .07       0
  5000.4     .16       0
Bank Sta=4994.4,5000.4
XS Rating Curve= 0 ,0
Exp/Cntr=0.3,0.1

Type RM Length L Ch R = 1 ,4972    ,480,480,480
BEGIN DESCRIPTION:
UNT 179 IN BOCR 9.0
END DESCRIPTION:
XS GIS Cut Line= 3
      3734999.58     10598310.16      3734949.61     10598260.19
      3734899.59     10598210.17
#Sta/Elev= 18
  4938.6  290.64  4942.1  290.64  4952.7  284.25  4966.8  286.42    4981     283
  4992.1  278.83  4994.9  278.33  4995.4  278.33  4998.1  278.83  5005.7  281.42
  5012.8  281.42  5023.4  286.82  5037.6  289.18  5046.2   289.9  5051.7  290.36
  5065.8  293.13  5076.4  293.87    5080  293.87
#Mann= 4 ,-1 , 0
  4938.6     .12       0  4992.1     .07       0  4998.1     .12       0
  5046.2     .16       0
Bank Sta=4992.1,4998.1
XS Rating Curve= 0 ,0
Exp/Cntr=0.3,0.1

Type RM Length L Ch R = 1 ,4492    ,403,403,403
BEGIN DESCRIPTION:
UNT 179 IN BOCR 8.0
END DESCRIPTION:
XS GIS Cut Line= 3
      3735149.59     10597860.19      3735049.61     10597860.19
      3734749.63     10597910.19
#Sta/Elev= 30
  4892.2  298.97  4902.2  297.28  4922.2  288.84  4932.2  286.63  4942.2  281.24
  4951.4  280.51  4982.2  274.03  4986.7  271.59  4989.4  271.09  4992.7  271.59
  5002.3  274.16  5020.1  275.77  5025.1  273.21  5031.4   272.9  5032.7  272.83
  5042.9  277.07    5053  278.44  5063.1  282.24  5080.9  286.33  5093.6  287.18
  5103.7  288.96  5174.7  294.89  5202.5  299.27  5215.2  300.39  5225.4   302.5
  5255.8  306.18  5263.4  308.03    5276  308.97  5286.2  310.91  5296.3  311.08
#Mann= 5 ,-1 , 0
  4892.2     .16       0  4951.4     .12       0  4986.7     .07       0
  4992.7     .12       0  5031.4     .16       0
Bank Sta=4986.7,4992.7
XS Rating Curve= 0 ,0
Exp/Cntr=0.3,0.1

Type RM Length L Ch R = 1 ,4089    ,356,356,356
BEGIN DESCRIPTION:
Mapping XS 0ec7f602
END DESCRIPTION:
XS GIS Cut Line= 2
      3735267.06     10597528.12      3734844.05     10597483.05
#Sta/Elev= 30
  4807.1  309.22  4837.3  304.69  4844.8  304.82  4854.8  302.53  4864.9  302.25
  4874.9  299.71    4885  299.61  4905.1  294.64  4915.2  289.11  4924.7  287.68
  4935.3  282.49  4945.3  279.38  4955.4  278.24  4975.5   271.1  4982.6  267.48
  4985.3  266.98  4988.6  267.48  5022.2  269.71  5045.9  277.16  5096.2     283
  5114.6  286.68  5126.3  287.64  5136.4  290.08  5176.6  297.05  5186.7  297.86
  5196.7  300.51  5206.8  301.88  5212.1  305.15  5226.9  305.88  5232.5  307.72
#Mann= 3 ,-1 , 0
  4807.1     .16       0  4982.6     .07       0  4988.6     .16       0
Bank Sta=4982.6,4988.6
XS Rating Curve= 0 ,0
Exp/Cntr=0.3,0.1

Type RM Length L Ch R = 1 ,3733    ,455,455,455
BEGIN DESCRIPTION:
Mapping XS b1252e09
END DESCRIPTION:
XS GIS Cut Line= 3
      3735412.86     10597385.74      3735128.18     10597198.26
      3734823.65     10597153.28
#Sta/Elev= 30
  4705.3  306.49  4710.7  304.61  4746.9  300.92    4783  294.48  4813.2  292.54
  4819.2  290.53  4864.4   287.1  4921.6  279.51  4936.7  277.18  4957.8  270.53
  4972.6  268.16  4978.8  264.12  4984.8  265.43  4993.9  263.47  4999.9  264.91
  5005.5  262.22  5008.3  261.72  5011.5  262.22    5015  266.33    5036  268.23
  5042.3  270.96  5155.9  283.09  5196.4  284.75  5246.9  283.79  5267.1  284.76
  5272.3  286.35  5277.4  284.91  5327.8  289.77  5341.9  289.39    5354  291.12
#Mann= 3 ,-1 , 0
  4705.3     .16       0  5005.5     .07       0  5011.5     .16       0
Bank Sta=5005.5,5011.5
XS Rating Curve= 0 ,0
Exp/Cntr=0.3,0.1

Type RM Length L Ch R = 1 ,3278    ,310,310,310
BEGIN DESCRIPTION:
Mapping XS 1c11db96
END DESCRIPTION:
XS GIS Cut Line= 6
      3735878.86     10597012.77      3735510.39     10596946.37
      3735395.81     10596935.95      3735220.03     10596917.72
      3735002.58     10596857.83      3734910.34     10596785.08
#Sta/Elev= 30
  4468.1  291.84  4506.9  287.84    4512  290.22  4548.6  288.47  4599.4  291.17
  4660.4  289.86  4678.1   290.4  4683.2  292.37    4762  292.23  4772.2  289.79
  4845.4  285.66  4913.6  277.22  4933.7   273.5  4953.1  266.21  4957.6  266.21
  4961.9   262.3  4993.9  261.45    5001  256.96  5003.8  256.46    5007  256.96
  5014.1  261.22  5024.1  262.38  5065.6  262.21  5181.4  277.33  5196.9  277.37
  5207.3  280.26    5221  280.51  5279.9  288.28  5329.4  292.12  5477.3   308.2
#Mann= 3 ,-1 , 0
  4468.1     .16       0    5001     .07       0    5007     .16       0
Bank Sta=5001,5007
XS Rating Curve= 0 ,0
Exp/Cntr=0.3,0.1

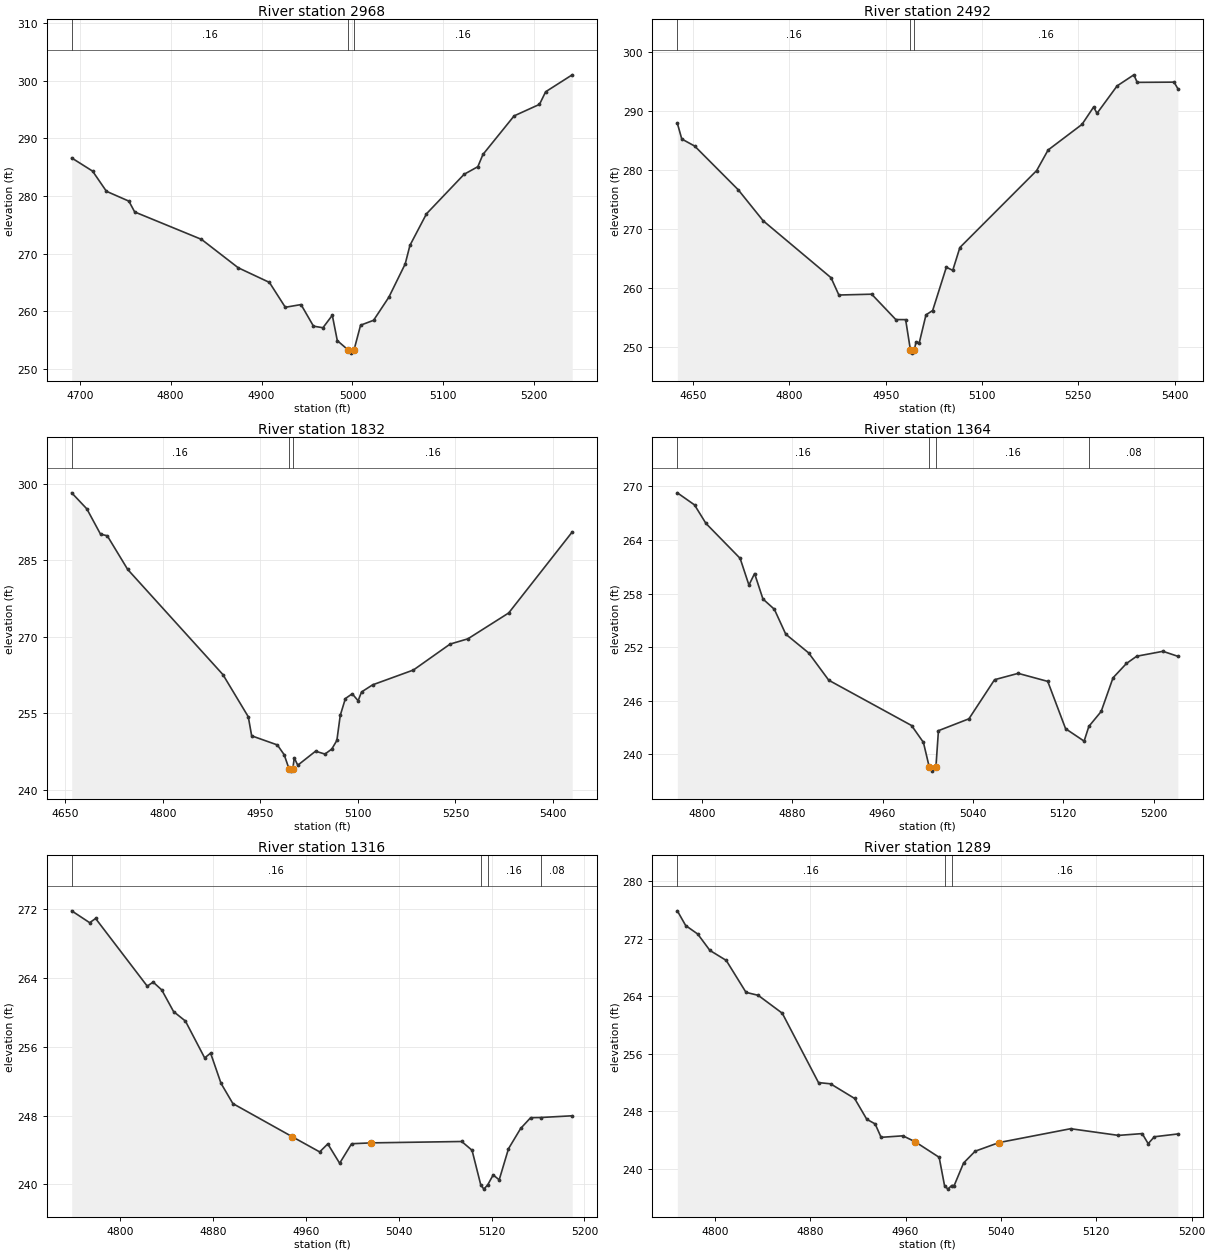
Type RM Length L Ch R = 1 ,2968    ,476,476,476
BEGIN DESCRIPTION:
UNT 179 IN BOCR 5.0
END DESCRIPTION:
XS GIS Cut Line= 2
      3735586.48     10596801.27      3735054.83     10596658.05
#Sta/Elev= 30
  4691.1   286.6  4714.1  284.31  4729.3  280.81    4754   279.1  4760.4  277.22
  4833.9  272.46  4874.3  267.53  4908.6  264.99  4926.1  260.67  4943.4  261.14
  4957.1  257.39  4967.5  257.12  4977.8  259.28  4983.3  254.88  4995.6  253.21
  4998.3  252.71  5001.6  253.21  5008.9  257.56  5023.2  258.41    5040  262.42
    5058   268.2  5063.2  271.42  5081.4   276.9  5122.8  283.76  5137.9  285.08
  5143.5   287.2  5177.8   293.9  5205.7   295.9  5212.5  298.09  5241.7  301.03
#Mann= 3 ,-1 , 0
  4691.1     .16       0  4995.6     .07       0  5001.6     .16       0
Bank Sta=4995.6,5001.6
XS Rating Curve= 0 ,0
Exp/Cntr=0.3,0.1

Type RM Length L Ch R = 1 ,2492    ,660,660,660
BEGIN DESCRIPTION:
UNT 179 IN BOCR 4.0
END DESCRIPTION:
XS GIS Cut Line= 2
      3735786.14     10596495.28       3735048.3     10596243.54
#Sta/Elev= 30
  4625.5  287.98  4632.4   285.3  4652.5   284.1  4720.4  276.67  4759.2  271.41
  4864.9  261.74  4877.1   258.8  4928.2  258.94  4965.8  254.63  4981.1  254.62
  4988.6  249.43  4991.4  248.93  4994.6  249.43  4997.2   250.8  5002.4  250.71
  5012.8  255.43  5023.2  256.17  5044.5  263.52  5054.5  262.99  5065.6  266.87
  5185.2  279.94    5203  283.43  5255.8  287.78  5273.9  290.73  5279.2  289.66
  5310.5  294.32  5336.6   296.2  5341.8  294.92  5399.2  294.96  5405.1  293.85
#Mann= 3 ,-1 , 0
  4625.5     .16       0  4988.6     .07       0  4994.6     .16       0
Bank Sta=4988.6,4994.6
XS Rating Curve= 0 ,0
Exp/Cntr=0.3,0.1

Type RM Length L Ch R = 1 ,1832    ,468,468,468
BEGIN DESCRIPTION:
UNT 179 IN BOCR 3.0
END DESCRIPTION:
XS GIS Cut Line= 2
      3735961.93     10596115.51      3735226.27     10595889.82
#Sta/Elev= 30
    4660  298.27  4683.3  295.12  4704.3  290.16  4714.7  289.84  4746.1  283.23
  4892.5  262.59  4931.5  254.31  4936.7  250.57  4976.2  248.78  4986.7  246.86
    4994  244.14  4996.7  243.64    5000  244.14  5002.2  246.23  5007.6   244.8
  5034.9  247.55  5049.4  246.99  5059.9  247.98  5067.7  249.67  5072.9  254.58
  5080.8  257.89  5091.3  258.82  5100.4  257.45  5105.6  259.18  5122.7  260.58
  5185.4  263.49  5241.8  268.58  5269.1  269.61  5331.9  274.69  5429.5  290.58
#Mann= 3 ,-1 , 0
    4660     .16       0    4994     .07       0    5000     .16       0
Bank Sta=4994,5000
XS Rating Curve= 0 ,0
Exp/Cntr=0.3,0.1

Type RM Length L Ch R = 1 ,1364    ,48,48,48
BEGIN DESCRIPTION:
Mapping XS a8bb29ae
END DESCRIPTION:
XS GIS Cut Line= 3
      3735855.26     10595895.23      3735883.48     10595697.72
      3735809.68     10595465.48
#Sta/Elev= 30
  4778.3  269.28  4793.5  267.93  4803.6  265.86  4833.9  261.94  4841.7  258.95
  4846.7  260.24  4854.1  257.39  4864.2  256.24  4874.3  253.45  4894.5  251.36
  4912.4  248.29  4985.7  243.22  4996.2  241.33  5001.3  238.61    5004  238.11
  5007.3  238.61  5009.5  242.64  5036.5  243.97  5059.2  248.35  5080.1  249.06
  5106.3  248.16  5122.1  242.86  5138.5  241.47  5142.7  243.12  5153.6  244.79
  5164.1  248.56    5176  250.17  5185.1  250.98  5208.3  251.53  5221.5  250.97
#Mann= 4 ,-1 , 0
  4778.3     .16       0  5001.3     .07       0  5007.3     .16       0
  5142.7     .08       0
Bank Sta=5001.3,5007.3
XS Rating Curve= 0 ,0
Exp/Cntr=0.3,0.1

Type RM Length L Ch R = 1 ,1316    ,27,27,27
BEGIN DESCRIPTION:
UNT 179 IN BOCR 2.0
END DESCRIPTION:
XS GIS Cut Line= 3
      3735870.46     10595906.05       3735929.5       10595629.
      3735884.79     10595487.89
#Sta/Elev= 30
  4758.2  271.82  4773.7  270.44  4778.8  270.93  4823.3  263.06  4828.4  263.53
  4835.8  262.62    4846   260.1  4856.2     259  4872.8  254.71  4877.9  255.27
  4886.9  251.75  4897.1   249.4  4948.2  245.55  4971.9  243.78  4978.9  244.71
  4989.1  242.46  4999.4  244.73  5016.4  244.83  5094.3  244.99  5103.2  243.97
  5110.7  239.95  5113.4  239.45  5116.7  239.95  5121.4   241.1  5126.6  240.53
  5134.6  244.15  5145.1  246.51  5153.7  247.76  5162.3  247.78  5189.5  247.98
#Mann= 4 ,-1 , 0
  4758.2     .16       0  5110.7     .07       0  5116.7     .16       0
  5162.3     .08       0
Bank Sta=4948.2,5016.4
XS Rating Curve= 0 ,0
Exp/Cntr=0.3,0.1

Type RM Length L Ch R = 1 ,1289    ,187,187,187
BEGIN DESCRIPTION:
Mapping XS c1d7e556
END DESCRIPTION:
XS GIS Cut Line= 3
      3735908.44     10595907.12      3735944.24     10595680.35
      3735956.18      10595490.5
#Sta/Elev= 30
  4768.6  275.89  4775.6  273.84  4785.7  272.66  4795.9  270.38  4809.6  268.99
  4826.2  264.54  4836.4  264.13  4856.6  261.64    4887  251.98  4897.1  251.81
  4917.3  249.77  4927.5  246.87  4934.5  246.23  4939.5  244.36  4957.8  244.57
    4968  243.75  4988.2  241.58  4992.7  237.65  4995.5  237.15  4998.7  237.65
  5000.8  237.65  5008.7  240.79  5018.4  242.43  5038.4  243.63  5098.5  245.56
  5138.6  244.63  5158.5  244.88  5163.5  243.48  5168.7  244.44  5188.4  244.83
#Mann= 3 ,-1 , 0
  4768.6     .16       0  4992.7     .07       0  4998.7     .16       0
Bank Sta=4968,5038.4
XS Rating Curve= 0 ,0
Exp/Cntr=0.3,0.1

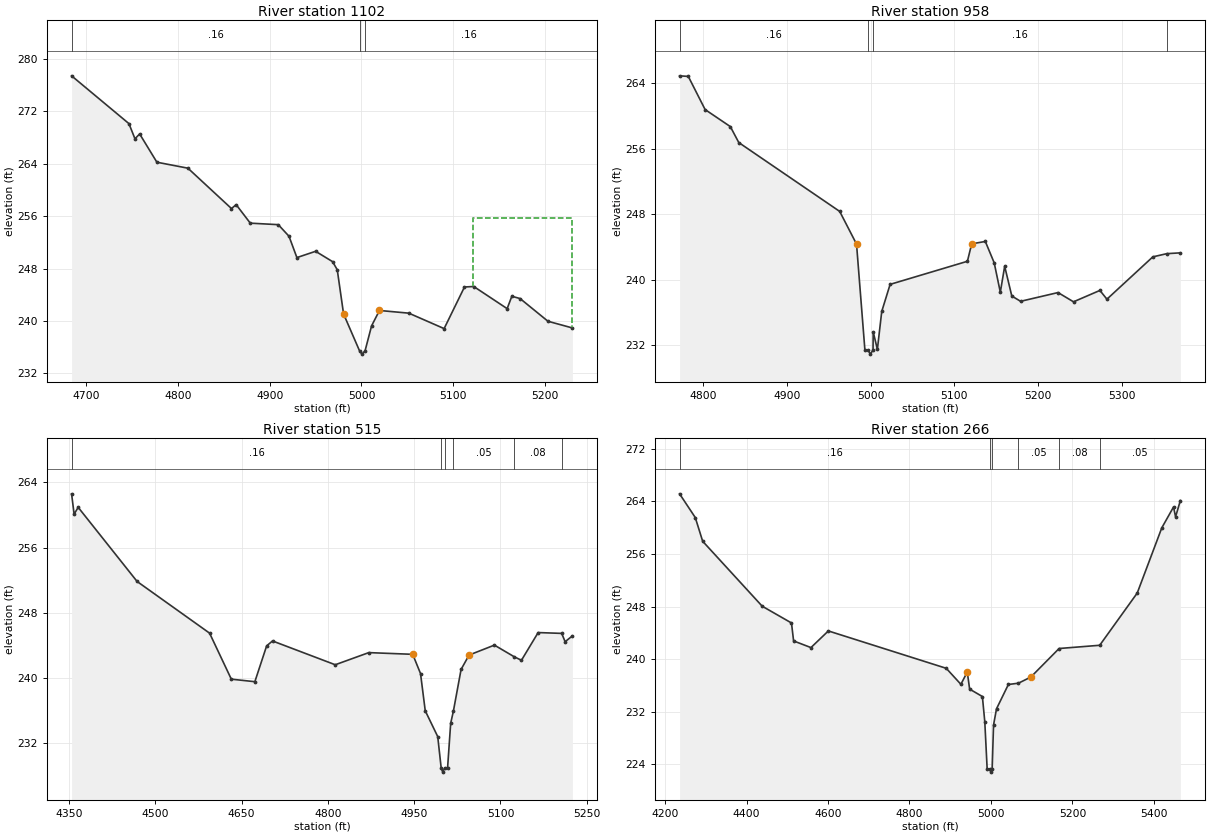
Type RM Length L Ch R = 1 ,1102    ,144,144,144
BEGIN DESCRIPTION:
Mapping XS 1cb3a17a
END DESCRIPTION:
XS GIS Cut Line= 3
      3736117.64     10596071.63      3736055.14      10595738.3
      3736024.09     10595533.88
#Sta/Elev= 30
    4684  277.45  4746.5  270.15  4753.1  267.83  4758.2  268.57    4777  264.25
  4810.8  263.34  4858.3  257.17  4863.4  257.77  4878.8  254.94  4909.3  254.71
    4921  252.94  4929.6  249.68    4950  250.64  4968.5  249.06  4973.6  247.82
  4980.5  241.06  4997.9  235.43  5000.6  234.93  5003.9  235.43    5011  239.24
  5019.6   241.6  5051.6  241.19  5090.1  238.83  5112.3  245.19  5122.4  245.26
  5158.8  241.88  5163.9  243.77  5172.9  243.42  5203.3  239.95  5229.9  238.93
#Mann= 3 ,-1 , 0
    4684     .16       0  4997.9     .07       0  5003.9     .16       0
#XS Ineff= 2 , 0
                         5121.86          255.78
Permanent Ineff=
       F       F
Bank Sta=4980.5,5019.6
XS Rating Curve= 0 ,0
Exp/Cntr=0.3,0.1

Type RM Length L Ch R = 1 ,958     ,443,443,443
BEGIN DESCRIPTION:
Mapping XS 72be1d0c
END DESCRIPTION:
XS GIS Cut Line= 4
      3736142.85     10596000.56      3736168.89     10595719.29
      3736105.09     10595693.25      3736028.28     10595458.91
#Sta/Elev= 30
    4772  264.92  4782.4  264.85  4802.5   260.8  4832.6  258.72  4842.7  256.77
  4963.2  248.36  4983.3  244.37  4993.3  231.43    4997  231.43  4999.8  230.93
    5003  231.43  5003.2  233.65  5008.2  231.51  5013.4  236.14  5023.4  239.45
  5115.7  242.27  5120.8   244.4  5137.1  244.69  5147.7  242.08    5155  238.49
  5160.2  241.66  5168.7  238.03  5179.2  237.38  5223.9  238.45  5242.4  237.32
  5273.9  238.71  5282.3  237.64  5337.1  242.81  5353.8   243.2    5370   243.3
#Mann= 4 ,-1 , 0
    4772     .16       0    4997     .07       0    5003     .16       0
  5353.8     .05       0
Bank Sta=4983.3,5120.8
XS Rating Curve= 0 ,0
Exp/Cntr=0.3,0.1

Type RM Length L Ch R = 1 ,515     ,249,249,249
BEGIN DESCRIPTION:
Mapping XS 2f1037a5
END DESCRIPTION:
XS GIS Cut Line= 4
      3736174.09     10595991.45      3736271.75     10595542.21
      3735909.78     10595385.96      3735895.47     10595378.15
#Sta/Elev= 30
  4354.7  262.59  4359.1   260.1  4366.2  260.93  4468.6  251.83  4594.5  245.49
  4632.3  239.84  4673.2  239.53  4693.7  243.93  4703.9  244.53  4812.9  241.61
  4871.2   243.1  4947.5  242.89  4961.1  240.53  4969.3  235.96    4991  232.79
    4997  228.93  4999.8  228.43    5003  228.93  5008.1  228.93  5013.5  234.42
  5018.2  235.91  5031.6  241.04  5045.5   242.8  5089.5  244.02  5124.2  242.58
  5136.5  242.16  5165.5  245.56  5206.4  245.46  5212.4  244.44    5225  245.15
#Mann= 6 ,-1 , 0
  4354.7     .16       0    4997     .07       0    5003     .16       0
  5018.2     .05       0  5124.2     .08       0  5206.4     .05       0
Bank Sta=4947.5,5045.5
XS Rating Curve= 0 ,0
Exp/Cntr=0.3,0.1

Type RM Length L Ch R = 1 ,266     ,0,0,0
BEGIN DESCRIPTION:
UNT 179 IN BOCR 1.0
END DESCRIPTION:
XS GIS Cut Line= 4
      3736181.16     10596017.72      3736332.95     10595365.12
      3736214.46     10595296.11      3735794.24     10595336.44
#Sta/Elev= 30
  4235.7  265.14  4274.2  261.54  4292.4  257.93  4438.5  248.06  4510.4  245.51
  4515.6  242.78  4558.2  241.77  4600.9   244.3  4890.3  238.62  4926.2  236.19
  4941.9  238.05  4947.7  235.46    4979  234.33  4984.9  230.51  4990.7  223.34
    4997  223.34  4999.8  222.84    5003  223.34  5006.4  230.01  5013.7  232.47
  5042.8  236.16  5067.6  236.36  5097.9  237.29  5167.3  241.63    5267  242.12
  5359.1  250.06  5419.4  259.97  5448.2  263.14  5453.2  261.65    5465  264.12
#Mann= 6 ,-1 , 0
  4235.7     .16       0    4997     .07       0    5003     .16       0
  5067.6     .05       0  5167.3     .08       0    5267     .05       0
Bank Sta=4941.9,5097.9
XS Rating Curve= 0 ,0
Exp/Cntr=0.3,0.1

Chan Stop Cuts=-1
Use User Specified Reach Order=0
Composite Channel Slope=5