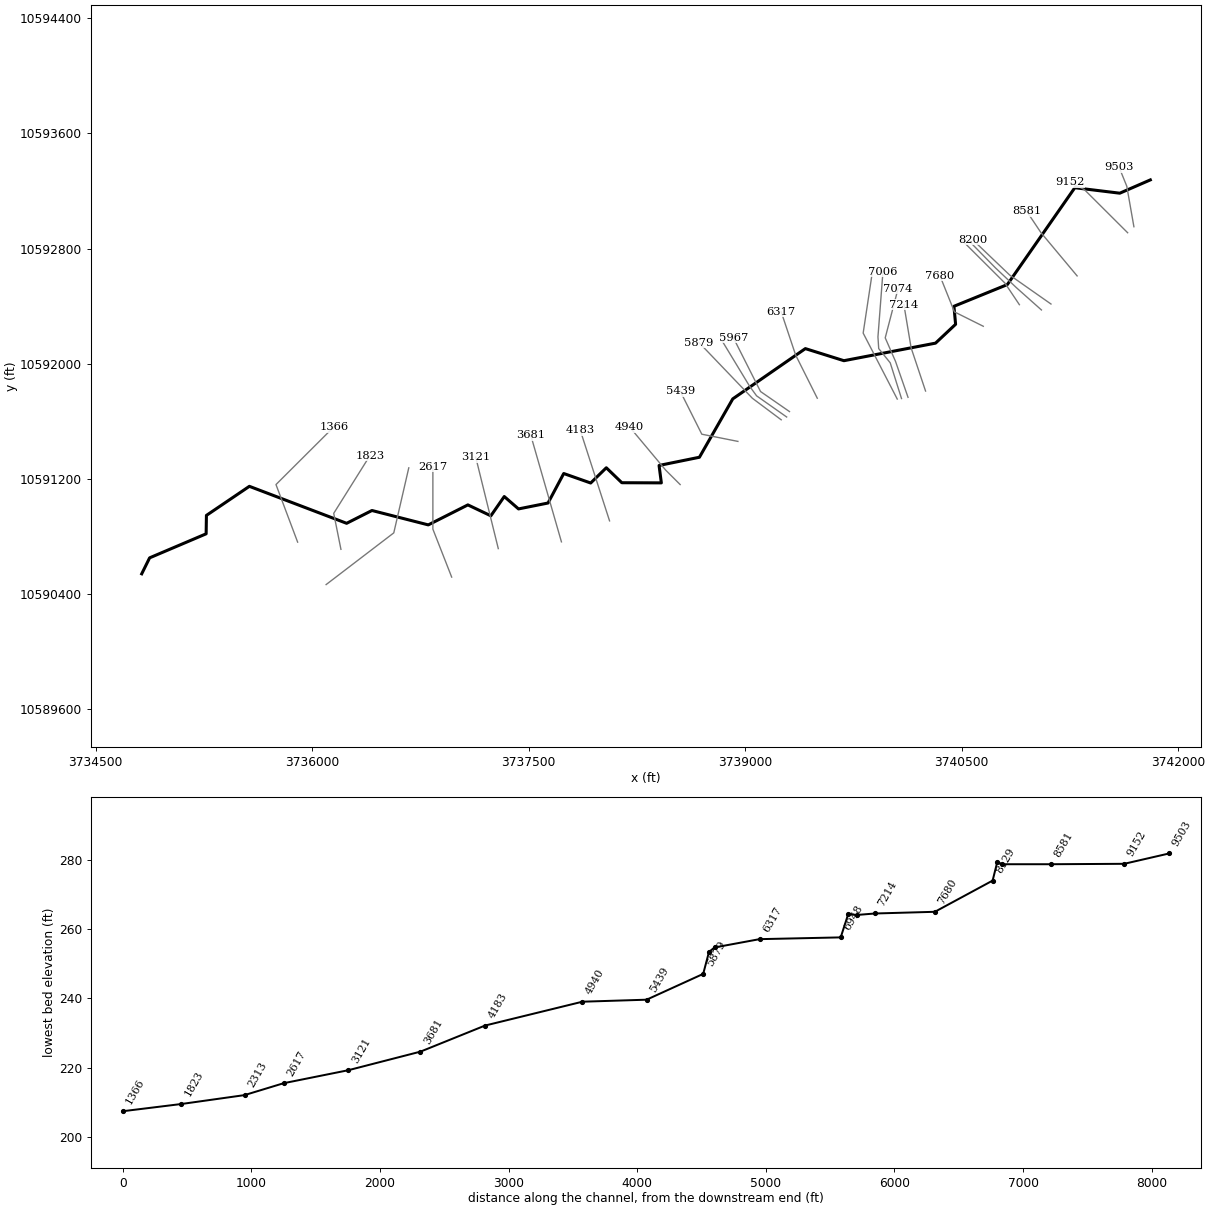
--- UNT 180 IN BOCR.prj (project) ---

Proj Title=UNT 180 IN BOCR Base Level Engineering
Current Plan=p01
Default Exp/Contr=0.3,0.1
English Units
Geom File=g01
Flow File=f01
Plan File=p01
Y Axis Title=Elevation
X Axis Title(PF)=Main Channel Distance
X Axis Title(XS)=Station
BEGIN DESCRIPTION:
UNT 180 IN BOCR
END DESCRIPTION:
DSS Export Rating Curves= 0
DSS Export Rating Curve Sorted= 0
DSS Export Volume Flow Curves= 0
DXF OffsetX= 0
DXF OffsetY= 0
DXF ScaleX= 1
DXF ScaleY= 10

--- UNT 180 IN BOCR.p01 (plan) ---

Plan Title=Multiple Run
Short Identifier=Multiple
Geom File=g01
Flow File=f01
Subcritical Flow
K Sum by GR= 0
Std Step Tol= 0.01
Critical Tol= 0.01
Num of Std Step Trials= 20
Max Error Tol= 0.3
Flow Tol Ratio= 0.001
Split Flow NTrial= 30
Split Flow Tol= 0.02
Split Flow Ratio= 0.02
Log Output Level= 0
Friction Slope Method= 1
Unsteady Friction Slope Method= 2
Unsteady Bridges Friction Slope Method= 1
Parabolic Critical Depth
Global Vel Dist=  1 , 1 , 1
Global Log Level= 0
CheckData=True
Encroach Param= -1, 0, 0, 0
BEGIN DESCRIPTION:
Multiple Run
END DESCRIPTION:

--- UNT 180 IN BOCR.f01 (steady flow) ---

Flow Title=Multiple
Number of Profiles=7
Profile Names=10-year,25-year,50-year,1pct_min,100-year,1pct_plu,500-year
River Rch & RM= UNT 180 IN BOCR,Reach-1,9503
     517     694     839     746    1009    1365    1465
River Rch & RM= UNT 180 IN BOCR,Reach-1,2313
     933    1298    1609    1463    1979    2677    3008
Boundary for River Rch & Prof#=UNT 180 IN BOCR,Reach-1,1
Up Type=0
Dn Type=3
Dn Slope=0.005
Boundary for River Rch & Prof#=UNT 180 IN BOCR,Reach-1,2
Up Type=0
Dn Type=3
Dn Slope=0.005
Boundary for River Rch & Prof#=UNT 180 IN BOCR,Reach-1,3
Up Type=0
Dn Type=3
Dn Slope=0.005
Boundary for River Rch & Prof#=UNT 180 IN BOCR,Reach-1,4
Up Type=0
Dn Type=3
Dn Slope=0.005
Boundary for River Rch & Prof#=UNT 180 IN BOCR,Reach-1,5
Up Type=0
Dn Type=3
Dn Slope=0.005
Boundary for River Rch & Prof#=UNT 180 IN BOCR,Reach-1,6
Up Type=0
Dn Type=3
Dn Slope=0.005
Boundary for River Rch & Prof#=UNT 180 IN BOCR,Reach-1,7
Up Type=0
Dn Type=3
Dn Slope=0.005

--- UNT 180 IN BOCR.g01 (geometry) ---

Geom Title=Existing Conditions
Program Version=4.10

River Reach=UNT 180 IN BOCR ,Reach-1
Reach XY= 30
      3741806.74     10593277.34      3741595.25       10593185.
      3741283.75       10593223.      3740816.25       10592550.
      3740446.25       10592399.      3740457.75       10592274.
      3740318.75       10592143.        3739684.       10592021.
        3739417.       10592105.      3738914.14     10591755.74
        3738683.       10591350.       3738403.5       10591293.
      3738419.25       10591172.       3738145.5       10591173.
        3738038.       10591277.      3737929.75       10591171.
        3737743.       10591237.      3737634.25       10591032.
      3737429.75       10590991.        3737331.       10591077.
      3737238.25       10590943.        3737079.       10591019.
      3736804.75       10590880.       3736414.5       10590980.
        3736239.       10590891.      3735565.25       10591148.
      3735267.75       10590946.      3735265.75       10590818.
      3734874.25       10590651.       3734819.5       10590540.

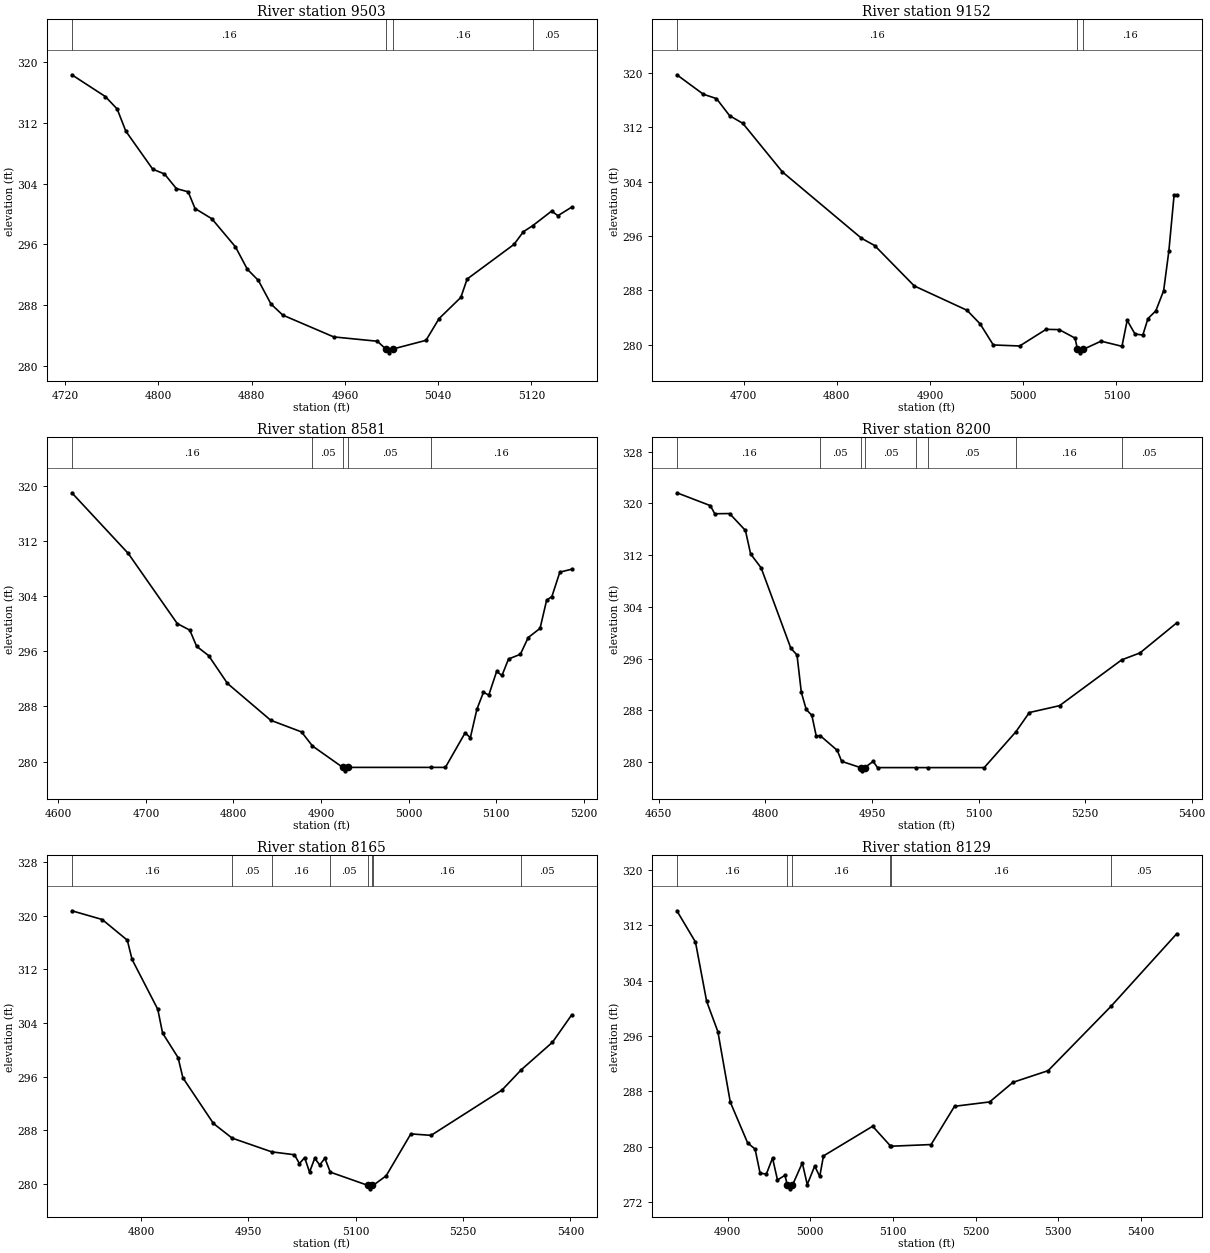
Type RM Length L Ch R = 1 ,9503    ,351,351,351
BEGIN DESCRIPTION:
UNT 180 IN BOCR 18.0
END DESCRIPTION:
XS GIS Cut Line= 3
      3741692.98     10592951.87      3741643.74     10593233.26
      3741590.14     10593366.09
#Sta/Elev= 30
  4725.7  318.26  4754.4  315.41  4764.6  313.77    4772  310.87  4795.1  305.88
  4805.2  305.25  4815.4  303.33  4825.5  302.91  4831.4  300.72  4845.8  299.38
  4866.1  295.69  4876.3  292.75  4885.8  291.28  4896.6  288.19  4906.7  286.74
  4950.4  283.88  4987.9  283.31  4995.1  282.29  4997.8  281.79  5001.1  282.29
  5029.6  283.43  5040.8  286.28  5059.5  289.06  5064.9  291.47  5105.1  296.01
  5113.2  297.68  5121.1  298.46  5137.4  300.38  5142.8  299.78  5154.6   300.9
#Mann= 4 ,-1 , 0
  4725.7     .16       0  4995.1     .07       0  5001.1     .16       0
  5121.1     .05       0
Bank Sta=4995.1,5001.1
XS Rating Curve= 0 ,0
Exp/Cntr=0.3,0.1

Type RM Length L Ch R = 1 ,9152    ,571,571,571
BEGIN DESCRIPTION:
UNT 180 IN BOCR 17.0
END DESCRIPTION:
XS GIS Cut Line= 3
      3741649.63     10592910.17      3741349.61     10593210.19
       3741249.6     10593260.19
#Sta/Elev= 30
  4628.5  319.75  4656.8  316.89    4671  316.24  4685.1  313.72  4699.2   312.6
  4741.7  305.44  4826.5  295.67  4840.7  294.59  4883.1  288.65  4939.7  285.06
  4953.8  283.05  4967.9  279.95  4996.2   279.8  5024.5  282.25  5038.6  282.21
  5055.6  280.96  5058.2  279.29  5060.9  278.79  5064.2  279.29  5083.5  280.51
  5105.9  279.75  5111.5  283.57  5119.9  281.56  5128.3  281.41  5133.8  283.84
  5142.2  284.97  5150.6  287.94  5156.2  293.79  5161.8  302.03  5164.6  302.03
#Mann= 3 ,-1 , 0
  4628.5     .16       0  5058.2     .07       0  5064.2     .16       0
Bank Sta=5058.2,5064.2
XS Rating Curve= 0 ,0
Exp/Cntr=0.3,0.1

Type RM Length L Ch R = 1 ,8581    ,381,381,381
BEGIN DESCRIPTION:
UNT 180 IN BOCR 16.0
END DESCRIPTION:
XS GIS Cut Line= 3
       3741299.6      10592610.2      3741049.61     10592910.19
       3740949.6     10593060.21
#Sta/Elev= 30
  4615.4  318.97  4679.8  310.18  4735.8  300.01  4750.1  299.06  4757.9  296.72
  4771.6  295.37  4793.1  291.34  4842.5     286  4877.7  284.31  4890.2  282.27
  4924.8  279.17  4927.5  278.67  4930.8  279.17  5025.3  279.17    5042  279.17
  5064.5  284.17  5070.5  283.48    5078  287.61  5085.5  290.07  5091.5  289.64
  5100.5  293.07  5106.6  292.49  5114.1  294.88  5127.6  295.56  5136.6  297.99
  5150.1  299.32  5157.6   303.4  5163.6  303.93  5172.7  307.47  5186.2  307.89
#Mann= 5 ,-1 , 0
  4615.4     .16       0  4890.2     .05       0  4924.8    .033       0
  4930.8     .05       0  5025.3     .16       0
Bank Sta=4924.8,4930.8
XS Rating Curve= 0 ,0
Exp/Cntr=0.3,0.1

Type RM Length L Ch R = 1 ,8200    ,35,35,35
BEGIN DESCRIPTION:
Mapping XS 7da293e4
END DESCRIPTION:
XS GIS Cut Line= 3
      3741118.53     10592414.78      3740833.16     10592615.51
      3740577.05     10592860.77
#Sta/Elev= 30
  4675.4  321.64  4722.6  319.65  4728.7   318.4  4749.6  318.43  4771.9  315.82
  4779.2  312.19    4794  310.04  4835.8  297.62  4844.5  296.57  4850.6  290.79
  4857.5  288.15  4865.4  287.24  4871.6  284.03  4876.9  284.13  4901.2  281.83
  4907.3  280.14  4933.9  279.17  4936.6  278.67  4939.9  279.17  4951.7  280.13
  4957.8  279.17  5012.2  279.17  5028.9  279.17    5108  279.17  5152.6  284.71
  5171.5  287.68    5214  288.74  5301.5  295.82  5327.2  296.89  5378.9  301.53
#Mann= 8 ,-1 , 0
  4675.4     .16       0  4876.9     .05       0  4933.9     .03       0
  4939.9     .05       0  5012.2     .16       0  5028.9     .05       0
  5152.6     .16       0  5301.5     .05       0
Bank Sta=4933.9,4939.9
XS Rating Curve= 0 ,0
Exp/Cntr=0.3,0.1

Type RM Length L Ch R = 1 ,8165    ,36,36,36
BEGIN DESCRIPTION:
Mapping XS ccc3d042
END DESCRIPTION:
XS GIS Cut Line= 4
      3741052.36     10592373.53      3740879.82     10592527.62
      3740733.33     10592666.51      3740547.83     10592856.33
#Sta/Elev= 30
  4703.3  320.73  4745.7  319.43  4780.8  316.35  4787.5  313.47  4823.4  306.05
  4830.1  302.51  4851.8  298.84  4858.5  295.84  4901.2  289.03  4927.3  286.85
  4982.7   284.8  5014.5  284.37  5021.4  283.04  5028.7  283.96  5035.5  281.78
  5042.8  283.85  5049.7  282.85    5057  283.84  5064.5  281.78  5117.5  279.79
  5120.2  279.29  5123.5  279.79  5124.2  279.79  5142.6  281.23  5177.1  287.48
  5205.4  287.26  5304.4     294  5331.3  297.02  5375.1  301.14  5401.9  305.21
#Mann= 8 ,-1 , 0
  4703.3     .16       0  4927.3     .05       0  4982.7     .16       0
  5064.5     .05       0  5117.5     .07       0  5123.5     .05       0
  5124.2     .16       0  5331.3     .05       0
Bank Sta=5117.5,5123.5
XS Rating Curve= 0 ,0
Exp/Cntr=0.3,0.1

Type RM Length L Ch R = 1 ,8129    ,449,449,449
BEGIN DESCRIPTION:
UNT 180 IN BOCR 15.0
END DESCRIPTION:
XS GIS Cut Line= 3
       3740899.6      10592410.2      3740799.61     10592560.19
      3740499.63     10592860.17
#Sta/Elev= 30
  4838.6  314.07  4861.1  309.56  4874.6  301.01  4888.2  296.63  4903.2  286.47
  4924.2  280.57  4933.2  279.69  4939.2  276.23  4946.8  276.07  4954.3  278.39
  4960.3  275.23  4969.3   275.9  4972.3  274.45    4975  273.95  4978.3  274.45
  4990.3  277.69  4996.3  274.57  5005.3  277.23  5011.4  275.74  5015.9   278.7
  5075.4  282.98  5096.9  280.14  5097.7   280.1  5146.1  280.34  5174.4  285.86
  5216.9  286.49  5245.1  289.32  5287.6     291    5364  300.33  5443.1  310.75
#Mann= 6 ,-1 , 0
  4838.6     .16       0  4972.3     .07       0  4978.3     .16       0
  5096.9     .05       0  5097.7     .16       0    5364     .05       0
Bank Sta=4972.3,4978.3
XS Rating Curve= 0 ,0
Exp/Cntr=0.3,0.1

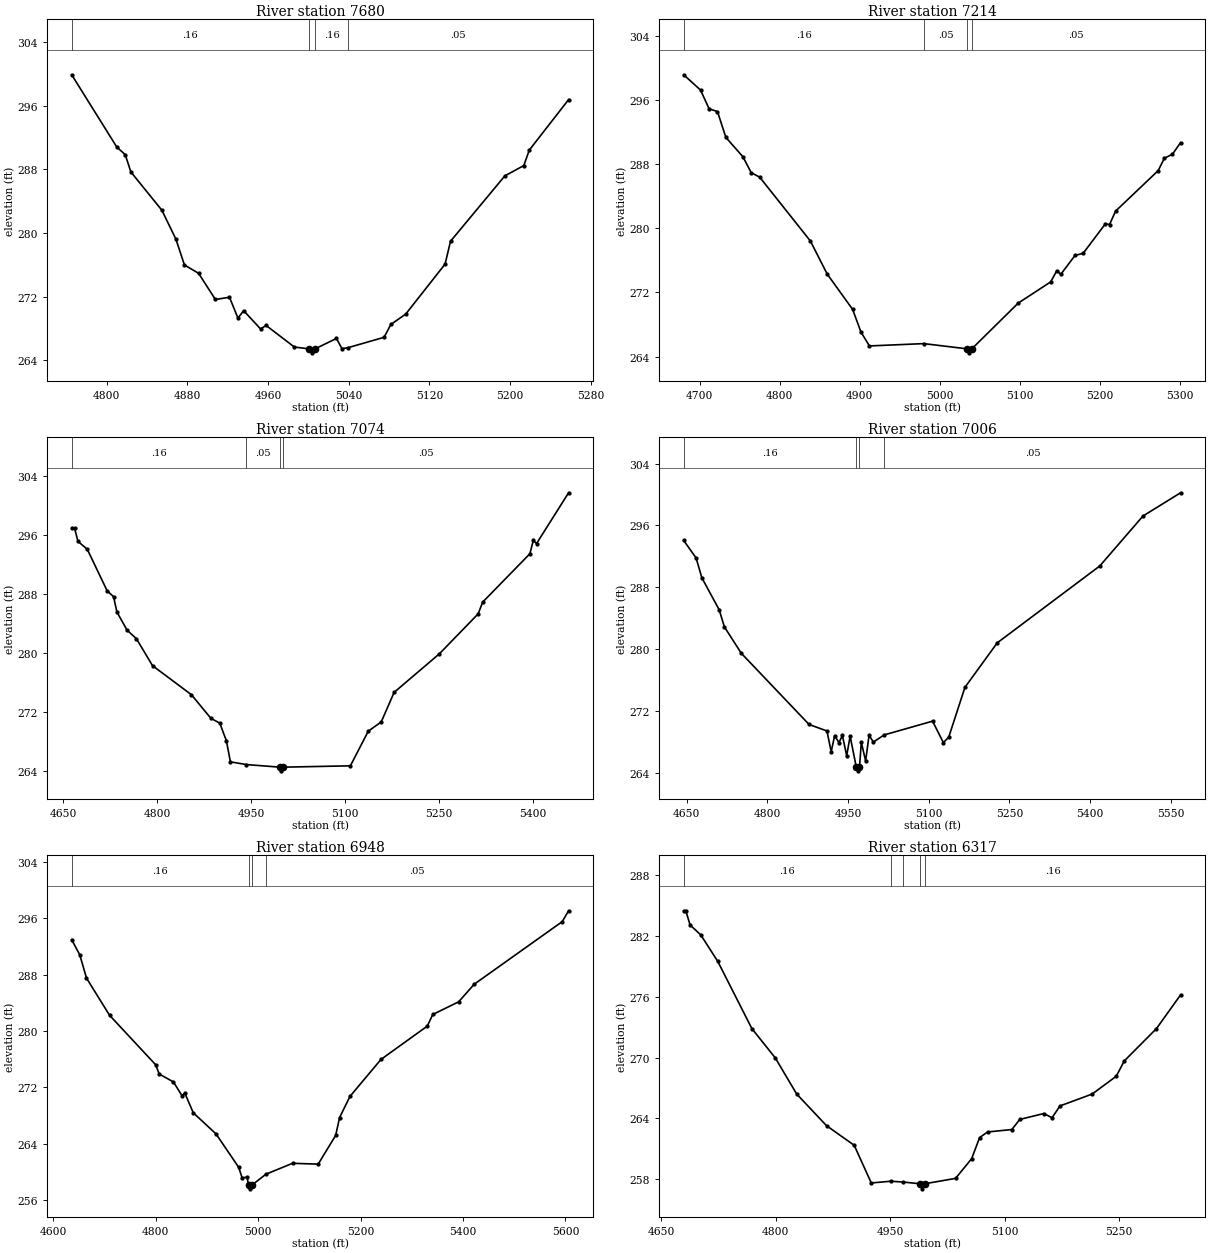
Type RM Length L Ch R = 1 ,7680    ,466,466,466
BEGIN DESCRIPTION:
UNT 180 IN BOCR 14.0
END DESCRIPTION:
XS GIS Cut Line= 3
       3740649.6      10592260.2      3740449.61     10592360.19
      3740349.63     10592610.14
#Sta/Elev= 30
  4765.2  299.86  4809.9  290.79  4818.3  289.83  4823.9  287.66  4854.6  282.86
  4868.6  279.21    4877  275.98    4891  274.94  4907.7  271.65  4921.7  271.93
  4930.1   269.3  4935.7  270.25  4952.5  267.95    4958  268.39    4986  265.68
  5000.6  265.45  5003.4  264.95  5006.6  265.45  5027.8  266.76  5033.2  265.48
  5039.3   265.6    5075   266.9  5081.7  268.51  5096.5  269.82  5135.5  276.09
  5140.9  278.96  5194.8  287.17  5213.6  288.46    5219   290.4    5258  296.74
#Mann= 4 ,-1 , 0
  4765.2     .16       0  5000.6     .07       0  5006.6     .16       0
  5039.3     .05       0
Bank Sta=5000.6,5006.6
XS Rating Curve= 0 ,0
Exp/Cntr=0.3,0.1

Type RM Length L Ch R = 1 ,7214    ,140,140,140
BEGIN DESCRIPTION:
UNT 180 IN BOCR 13.0
END DESCRIPTION:
XS GIS Cut Line= 3
      3740249.62     10591810.15      3740149.61     10592110.19
      3740099.61     10592410.18
#Sta/Elev= 30
  4680.2  299.12  4701.3  297.21  4711.9  294.89  4722.4  294.53  4732.9  291.31
    4754  288.92  4764.6  286.91  4775.1  286.36  4838.4   278.4  4859.4  274.28
  4891.1  269.88  4901.6  267.04  4912.1  265.32    4980  265.61    5034  264.96
  5036.8  264.46    5040  264.96  5097.9  270.66  5138.4   273.3    5146  274.69
  5151.1  274.25  5168.8   276.6    5179  276.87  5206.8  280.55  5211.9  280.45
  5219.5  282.13  5272.7  287.18  5280.3  288.71  5290.5  289.22  5300.6  290.66
#Mann= 4 ,-1 , 0
  4680.2     .16       0    4980     .05       0    5034     .03       0
    5040     .05       0
Bank Sta=5034,5040
XS Rating Curve= 0 ,0
Exp/Cntr=0.3,0.1

Type RM Length L Ch R = 1 ,7074    ,68,68,68
BEGIN DESCRIPTION:
UNT 180 IN BOCR 12.0
END DESCRIPTION:
XS GIS Cut Line= 4
      3740128.17     10591766.58      3740041.37     10592016.58
      3739970.19     10592179.77      3740058.73     10592520.06
#Sta/Elev= 30
  4663.2  296.93  4667.8  296.93  4673.2  295.16  4688.2  294.06  4719.9  288.44
  4730.1  287.66  4735.4  285.59  4751.7  283.11  4766.6  281.96  4792.4   278.3
  4854.6  274.36  4885.8  271.15  4899.9  270.51  4910.5  268.11  4916.9  265.26
  4942.4  264.89  4995.7  264.54  4998.5  264.04  5001.7  264.54  5108.7  264.72
  5137.3  269.42    5158  270.67  5178.6  274.68    5251  279.91    5313  285.33
  5320.1  286.91  5395.6  293.47  5401.1  295.28  5406.3  294.86  5457.5  301.74
#Mann= 4 ,-1 , 0
  4663.2     .16       0  4942.4     .05       0  4995.7     .03       0
  5001.7     .05       0
Bank Sta=4995.7,5001.7
XS Rating Curve= 0 ,0
Exp/Cntr=0.3,0.1

Type RM Length L Ch R = 1 ,7006    ,58,58,58
BEGIN DESCRIPTION:
Mapping XS 71f2b469
END DESCRIPTION:
XS GIS Cut Line= 5
      3740083.02     10591757.94      3740004.91     10592006.16
      3739925.05     10592105.12      3739919.84     10592186.72
      3739954.56     10592639.84
#Sta/Elev= 30
  4644.5  294.06  4667.6  291.79  4678.3  289.22  4710.4   285.1  4720.2  282.87
  4751.7  279.45  4877.6  270.24  4910.8   269.4  4918.7  266.71  4925.1   268.8
  4933.1  267.89  4939.5  268.82  4947.5   266.2  4953.9  268.72  4965.3  264.74
  4968.1  264.24  4971.3  264.74  4974.7  267.94  4982.7  265.52  4989.1  268.84
  4997.1  267.97  5017.3  268.89  5107.1  270.67  5127.2  267.89  5137.2  268.61
  5167.3  275.05  5227.4  280.81    5418  290.76  5498.2  297.22  5568.1  300.23
#Mann= 4 ,-1 , 0
  4644.5     .16       0  4965.3     .07       0  4971.3     .16       0
  5017.3     .05       0
Bank Sta=4965.3,4971.3
XS Rating Curve= 0 ,0
Exp/Cntr=0.3,0.1

Type RM Length L Ch R = 1 ,6948    ,631,631,631
BEGIN DESCRIPTION:
Mapping XS 330daa2a
END DESCRIPTION:
XS GIS Cut Line= 3
      3740053.51     10591754.46      3739817.41     10592212.76
      3739884.87     10592662.49
#Sta/Elev= 30
  4635.8  292.97  4651.6  290.83  4664.7  287.52  4709.7  282.24  4799.7  275.21
  4806.7  273.89  4834.5  272.76  4851.1  270.81  4856.7  271.18  4873.2  268.38
  4917.6  265.38  4961.9  260.63  4968.5  259.15  4978.4  259.21  4981.1  258.07
  4983.8  257.57  4987.1  258.07  5015.1  259.65  5067.1   261.2  5117.1  261.08
  5151.3  265.17  5158.9   267.7  5179.1   270.7  5239.7  275.96  5330.2   280.7
  5340.9  282.35  5391.4  284.15  5421.8  286.65  5593.7  295.55  5606.1  297.09
#Mann= 4 ,-1 , 0
  4635.8     .16       0  4981.1     .07       0  4987.1     .16       0
  5015.1     .05       0
Bank Sta=4981.1,4987.1
XS Rating Curve= 0 ,0
Exp/Cntr=0.3,0.1

Type RM Length L Ch R = 1 ,6317    ,350,350,350
BEGIN DESCRIPTION:
UNT 180 IN BOCR 11.0
END DESCRIPTION:
XS GIS Cut Line= 3
       3739499.6      10591760.2      3739349.61     10592060.19
      3739249.62     10592360.16
#Sta/Elev= 30
  4679.1  284.49  4681.9  284.49  4687.5  283.09  4701.5  282.11  4723.8   279.5
  4768.5  272.87  4799.3  269.97  4827.2  266.42  4866.4  263.29  4902.7  261.36
  4925.1  257.64  4950.6  257.81  4967.1  257.73  4989.1  257.56  4991.9  257.06
  4995.1  257.56  5035.6  258.09  5056.7  260.03  5067.2  262.12  5077.7  262.67
  5109.4  262.91  5119.9  263.91  5151.5  264.49  5162.1  264.07  5172.6  265.24
  5214.8  266.41  5246.4  268.17  5256.9  269.68  5299.1  272.87  5330.7  276.19
#Mann= 5 ,-1 , 0
  4679.1     .16       0  4950.6     .05       0  4967.1     .16       0
  4989.1     .07       0  4995.1     .16       0
Bank Sta=4989.1,4995.1
XS Rating Curve= 0 ,0
Exp/Cntr=0.3,0.1

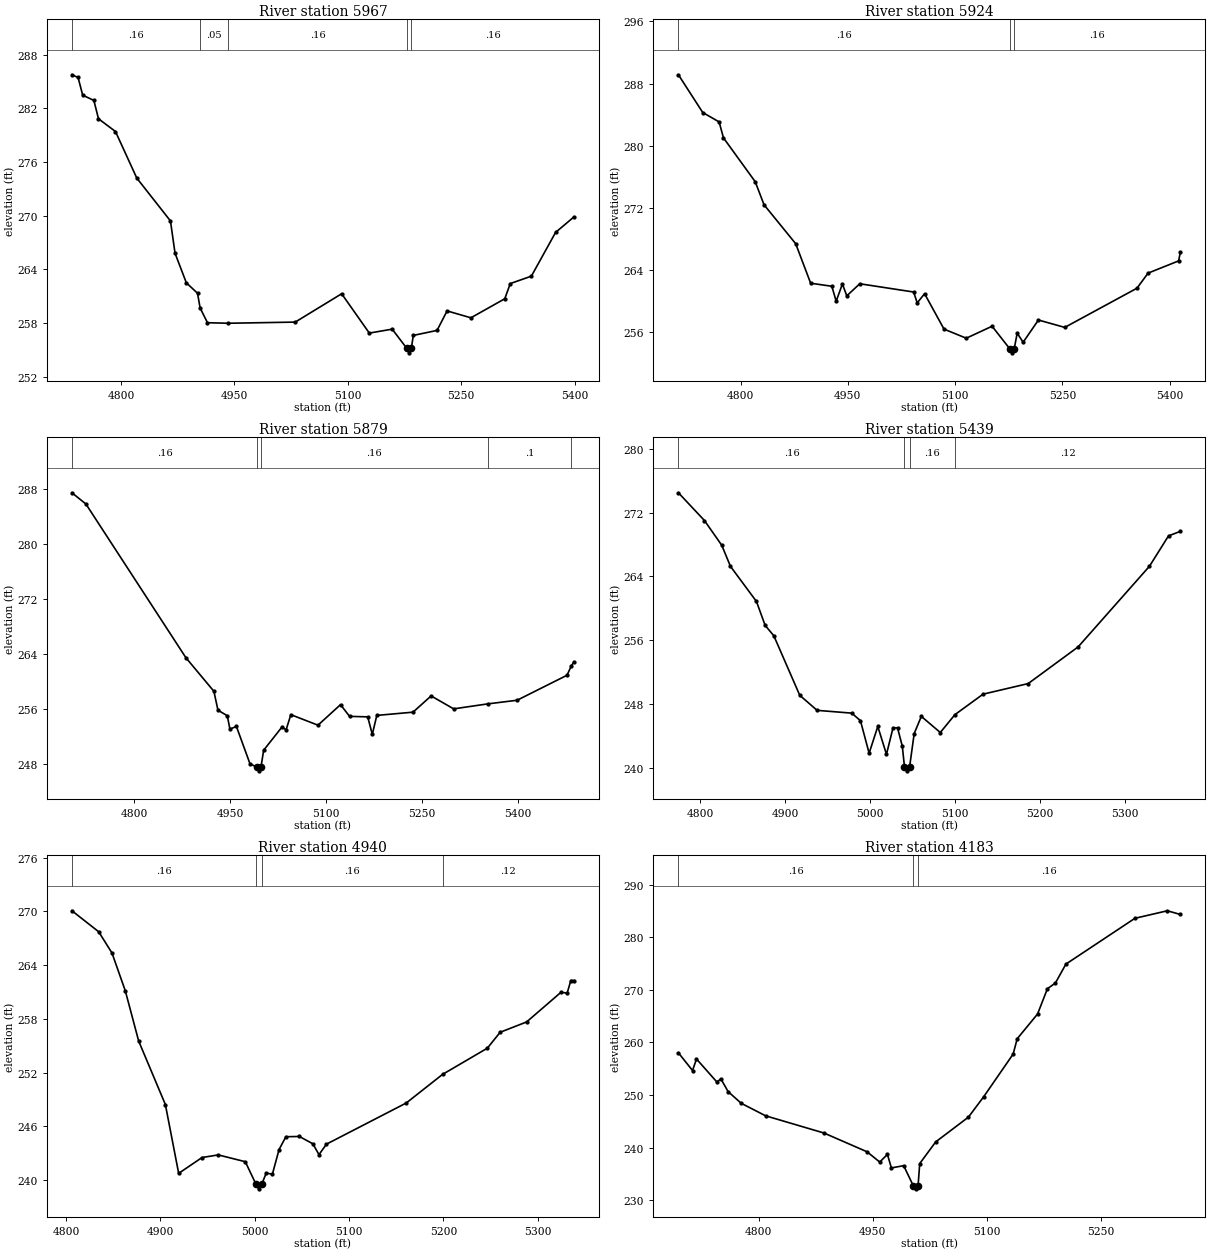
Type RM Length L Ch R = 1 ,5967    ,43,43,43
BEGIN DESCRIPTION:
Mapping XS 78c27e27
END DESCRIPTION:
XS GIS Cut Line= 3
      3739306.88     10591667.52      3739106.38     10591806.83
      3738917.58     10592181.84
#Sta/Elev= 30
    4735  285.77  4743.1  285.47  4749.2  283.49    4764   282.9  4770.1  280.85
  4792.6  279.42  4820.8  274.21  4865.3  269.42  4871.4   265.8  4886.3   262.5
  4901.1  261.33  4904.6  259.67  4914.3  258.03  4941.8  257.97  5030.4   258.1
  5091.8  261.27  5128.4  256.87  5158.7  257.31    5178  255.16  5180.8  254.66
    5184  255.16  5186.6  256.61    5218  257.17  5231.3  259.35  5262.8  258.58
  5307.6  260.71  5314.9  262.41  5342.8  263.24  5374.8  268.13    5399  269.86
#Mann= 5 ,-1 , 0
    4735     .16       0  4904.6     .05       0  4941.8     .16       0
    5178     .07       0    5184     .16       0
Bank Sta=5178,5184
XS Rating Curve= 0 ,0
Exp/Cntr=0.3,0.1

Type RM Length L Ch R = 1 ,5924    ,45,45,45
BEGIN DESCRIPTION:
Mapping XS cddbd67c
END DESCRIPTION:
XS GIS Cut Line= 4
      3739287.37     10591629.75      3739079.04     10591776.88
      3739030.86     10591843.29      3738842.26     10592155.45
#Sta/Elev= 30
  4713.1  289.13  4747.1  284.28    4770  283.07  4776.1  281.02  4820.5  275.38
  4832.8  272.42  4877.1  267.41    4898  262.33  4927.6  261.94  4933.7  260.02
  4942.4  262.23  4948.5  260.71  4966.7  262.26    5042   261.2    5047   259.8
  5057.3  260.98  5084.5  256.43  5115.6  255.26  5151.7   256.8  5176.6  253.88
  5179.4  253.38  5182.6  253.88  5186.8  255.91  5195.1  254.74  5216.5   257.6
  5253.3  256.65  5354.3  261.69  5369.8  263.63  5412.5   265.2  5414.9  266.29
#Mann= 3 ,-1 , 0
  4713.1     .16       0  5176.6     .07       0  5182.6     .16       0
Bank Sta=5176.6,5182.6
XS Rating Curve= 0 ,0
Exp/Cntr=0.3,0.1

Type RM Length L Ch R = 1 ,5879    ,440,440,440
BEGIN DESCRIPTION:
UNT 180 IN BOCR 10.0
END DESCRIPTION:
XS GIS Cut Line= 3
      3739249.58     10591610.21      3739049.61     10591760.19
      3738680.65     10592146.56
#Sta/Elev= 30
    4703  287.42  4724.8  285.79  4881.1  263.46  4924.8  258.59  4931.1  255.85
  4945.7  255.04  4949.8  253.11    4960  253.48  4981.1  248.08  4992.3  247.54
    4995  247.04  4998.3  247.54  5002.5  250.03  5030.8  253.36  5037.7  253.02
    5045   255.2  5087.4  253.67  5122.6  256.65  5136.8  254.95  5165.1  254.88
  5172.3  252.33  5179.3  255.09  5235.9  255.56  5264.2  257.92  5299.4  256.04
  5352.4  256.76  5398.5  257.29  5476.5  260.92  5483.2  262.27  5487.2  262.84
#Mann= 5 ,-1 , 0
    4703     .16       0  4992.3     .07       0  4998.3     .16       0
  5352.4      .1       0  5483.2     .12       0
Bank Sta=4992.3,4998.3
XS Rating Curve= 0 ,0
Exp/Cntr=0.3,0.1

Type RM Length L Ch R = 1 ,5439    ,499,499,499
BEGIN DESCRIPTION:
UNT 180 IN BOCR 9.0
END DESCRIPTION:
XS GIS Cut Line= 3
      3738949.58     10591460.19      3738699.61     10591510.19
      3738549.62     10591810.16
#Sta/Elev= 30
  4774.6  274.49  4805.2  271.01  4825.6   267.9  4835.8  265.26  4866.4  260.85
  4876.6  257.85  4886.8  256.55  4917.3  249.08  4937.7  247.19  4978.5  246.84
  4988.7  245.89  4998.9  241.81  5009.1  245.17  5019.3  241.67    5027     245
  5032.3     245  5037.9   242.7  5040.5   240.1  5043.2   239.6  5046.5   240.1
  5051.9  244.28  5060.3  246.43  5082.6  244.41  5099.8  246.65  5132.9  249.22
    5186  250.55  5244.7  255.15  5328.6  265.27    5351  269.08  5364.9  269.65
#Mann= 4 ,-1 , 0
  4774.6     .16       0  5040.5     .07       0  5046.5     .16       0
  5099.8     .12       0
Bank Sta=5040.5,5046.5
XS Rating Curve= 0 ,0
Exp/Cntr=0.3,0.1

Type RM Length L Ch R = 1 ,4940    ,757,757,757
BEGIN DESCRIPTION:
UNT 180 IN BOCR 8.0
END DESCRIPTION:
XS GIS Cut Line= 3
      3738549.62     10591160.18      3738449.61     10591260.19
      3738199.64     10591560.15
#Sta/Elev= 30
  4806.4  270.08  4834.7  267.74  4848.8  265.37    4863  261.12  4877.1  255.53
  4905.4  248.44  4919.5  240.75  4944.3  242.52  4961.5  242.81  4990.1  242.05
  5001.5  239.52  5004.2  239.02  5007.5  239.52  5012.3  240.79  5018.8  240.65
  5025.9  243.41  5033.1  244.84  5047.4  244.87  5061.7  244.05  5068.2  242.84
  5076.1  244.01  5160.7  248.61  5199.1   251.8  5246.6  254.73  5260.2  256.51
  5288.2  257.66  5324.7  260.98  5331.2  260.88  5335.1  262.29  5338.3  262.29
#Mann= 4 ,-1 , 0
  4806.4     .16       0  5001.5     .07       0  5007.5     .16       0
  5199.1     .12       0
Bank Sta=5001.5,5007.5
XS Rating Curve= 0 ,0
Exp/Cntr=0.3,0.1

Type RM Length L Ch R = 1 ,4183    ,502,502,502
BEGIN DESCRIPTION:
Mapping XS 27d13837
END DESCRIPTION:
XS GIS Cut Line= 2
      3738060.45     10590907.95       3737857.8     10591536.69
#Sta/Elev= 30
  4694.4  258.03    4713  254.66  4718.2  256.86    4745  252.48  4750.3  253.07
  4759.8  250.65  4777.1  248.42  4809.2  246.04  4885.9  242.77  4942.6   239.2
  4959.4  237.24  4969.5   238.7  4974.7  236.12  4990.9  236.55  5003.8  232.64
  5006.5  232.14  5009.8  232.64    5012  236.95    5033  241.07  5076.1  245.79
    5096  249.63    5135   257.8  5140.3  260.71  5167.1  265.42  5180.1  270.24
  5190.6  271.32  5204.4  274.92  5295.3  283.64  5337.9  285.07    5355  284.37
#Mann= 3 ,-1 , 0
  4694.4     .16       0  5003.8     .07       0  5009.8     .16       0
Bank Sta=5003.8,5009.8
XS Rating Curve= 0 ,0
Exp/Cntr=0.3,0.1

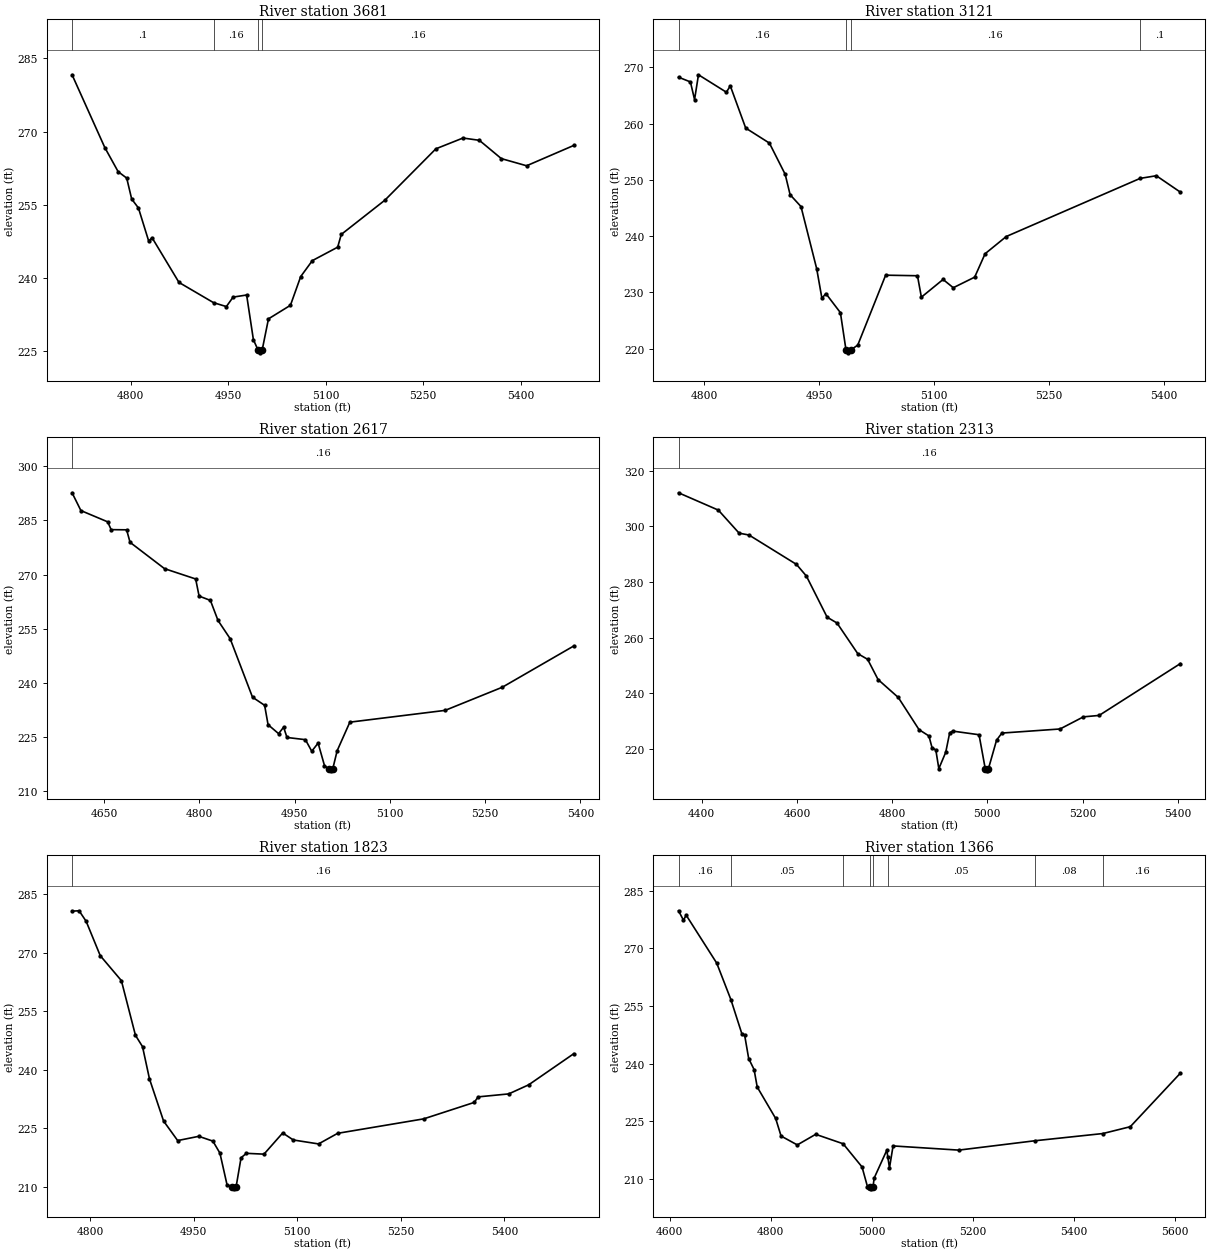
Type RM Length L Ch R = 1 ,3681    ,560,560,560
BEGIN DESCRIPTION:
Mapping XS 008a3896
END DESCRIPTION:
XS GIS Cut Line= 2
      3737727.14     10590762.03      3737514.35     10591504.23
#Sta/Elev= 30
  4709.6  281.64    4760  266.71  4780.5  261.77  4793.7  260.45  4801.3  256.17
  4811.7  254.33  4827.5  247.54  4832.7  248.23  4874.1  239.06  4927.4   234.9
    4947  234.11  4957.4  236.05  4978.2  236.48  4988.6  227.32    4996  225.12
  4998.7  224.62    5002  225.12  5011.8  231.59  5045.6  234.37  5061.4  240.26
  5079.3  243.53  5118.3  246.29  5123.8   248.9  5190.9  255.92  5269.4  266.46
  5311.1  268.67  5336.3   268.2  5370.1  264.45    5409  262.98  5481.7  267.16
#Mann= 4 ,-1 , 0
  4709.6      .1       0  4927.4     .16       0    4996     .07       0
    5002     .16       0
Bank Sta=4996,5002
XS Rating Curve= 0 ,0
Exp/Cntr=0.3,0.1

Type RM Length L Ch R = 1 ,3121    ,504,504,504
BEGIN DESCRIPTION:
Mapping XS ec35e22c
END DESCRIPTION:
XS GIS Cut Line= 2
      3737289.64     10590715.16      3737133.38     10591350.63
#Sta/Elev= 30
  4766.5  268.25    4782  267.41  4787.4  264.27  4792.5  268.68  4828.9  265.58
    4834  266.71  4854.1  259.21    4885  256.54  4905.6  250.99    4912  247.37
  4926.2  245.26  4946.7   234.2  4953.5  228.95  4958.6  229.81  4977.6  226.41
  4984.9  219.77  4987.7  219.27  4990.9  219.77  5000.2  220.64  5036.6  233.07
  5078.1  232.97  5083.2  229.16  5111.5  232.31  5124.8  230.84  5152.7  232.72
  5166.3  236.88  5193.9  239.94  5368.5  250.27  5389.6  250.74  5420.9  247.83
#Mann= 4 ,-1 , 0
  4766.5     .16       0  4984.9     .07       0  4990.9     .16       0
  5368.5      .1       0
Bank Sta=4984.9,4990.9
XS Rating Curve= 0 ,0
Exp/Cntr=0.3,0.1

Type RM Length L Ch R = 1 ,2617    ,304,304,304
BEGIN DESCRIPTION:
UNT 180 IN BOCR 4.0
END DESCRIPTION:
XS GIS Cut Line= 3
      3736966.71     10590517.28      3736836.51     10590850.61
      3736836.51     10591282.85
#Sta/Elev= 30
  4599.7  292.68  4613.6  287.74  4655.8  284.61  4661.2  282.45  4685.6   282.4
    4691  278.93  4745.3  271.62  4794.3  268.76  4799.7  264.01  4817.5  262.81
  4829.5  257.24  4848.6  252.19  4883.8  235.95  4902.9  233.69  4908.3  228.32
  4924.9  225.83  4932.8  227.62  4938.1  224.77  4967.1  224.16  4977.1  220.95
  4987.1  223.21  4997.1  216.99  5004.1  216.01  5006.9  215.51  5010.1  216.01
  5017.1  221.09  5037.1  229.02  5187.1  232.29  5277.1  238.71  5389.8  250.18
#Mann= 1 ,-1 , 0
  4599.7     .16       0
Bank Sta=5004.1,5010.1
XS Rating Curve= 0 ,0
Exp/Cntr=0.3,0.1

Type RM Length L Ch R = 1 ,2313    ,490,490,490
BEGIN DESCRIPTION:
UNT 180 IN BOCR 3.0
END DESCRIPTION:
XS GIS Cut Line= 3
      3736096.95     10590465.21      3736565.68     10590824.57
      3736669.56     10591276.45
#Sta/Elev= 30
  4351.2  312.05  4434.9  305.81  4478.5  297.53  4499.3  296.86    4599   286.3
  4619.8  282.12  4663.4  267.32  4684.2  265.22  4727.7  254.23  4748.5  252.17
  4770.4  244.91  4812.9  238.46  4856.5  226.89  4877.3  224.62  4883.8  220.42
  4891.8  219.57  4898.1  212.87  4912.6  218.75  4920.9  225.74  4927.2  226.37
  4982.6  225.06  4995.9  212.58  4998.7  212.08  5001.9  212.58  5019.4   223.1
  5030.6  225.66  5152.8  227.13  5201.9  231.49  5234.9     232  5405.5  250.63
#Mann= 1 ,-1 , 0
  4351.2     .16       0
Bank Sta=4995.9,5001.9
XS Rating Curve= 0 ,0
Exp/Cntr=0.3,0.1

Type RM Length L Ch R = 1 ,1823    ,457,457,457
BEGIN DESCRIPTION:
UNT 180 IN BOCR 2.0
END DESCRIPTION:
XS GIS Cut Line= 3
       3736199.6     10590710.22      3736149.61     10590960.19
       3736399.6     10591360.17
#Sta/Elev= 30
  4774.1  280.69  4784.3  280.78  4794.5  278.08  4814.9  269.28  4845.5  262.88
  4865.9  248.86  4876.1  245.97  4886.2  237.69  4906.6   226.9    4927  221.89
  4957.6  222.98    4978  221.75  4988.2  218.67  4998.4  210.63  5005.6  210.02
  5008.4  209.52  5011.6  210.02  5018.8  217.48  5026.5  218.62    5052  218.41
  5079.1  223.84  5094.5  222.04    5131  221.03  5158.7  223.75  5283.2  227.45
  5356.3  231.66  5362.2  233.09  5406.4  233.85  5435.3  236.18  5500.7  244.17
#Mann= 1 ,-1 , 0
  4774.1     .16       0
Bank Sta=5005.6,5011.6
XS Rating Curve= 0 ,0
Exp/Cntr=0.3,0.1

Type RM Length L Ch R = 1 ,1366    ,0,0,0
BEGIN DESCRIPTION:
UNT 180 IN BOCR 1.0
END DESCRIPTION:
XS GIS Cut Line= 3
      3735899.61     10590760.19      3735749.61     10591160.19
      3736149.62      10591560.2
#Sta/Elev= 30
  4617.6  279.74  4627.4  277.28  4632.7   278.6  4693.2  266.12  4721.2  256.64
  4743.1  247.68  4748.4  247.41  4756.4  241.31  4767.1  238.45  4773.3   233.9
  4809.8  225.73  4820.5  221.16  4852.6  218.85    4889  221.61  4943.3  219.15
  4980.7  213.12  4991.4  208.02  4996.4  207.93  4999.2  207.43  5002.4  207.93
  5004.7  210.23  5029.7  217.47  5031.8  215.64    5035  212.86  5042.1  218.59
  5172.1   217.5  5322.5  219.93  5457.2  221.81  5511.5  223.59  5610.5   237.5
#Mann= 8 ,-1 , 0
  4617.6     .16       0  4721.2     .05       0  4943.3     .16       0
  4996.4     .07       0  5002.4     .16       0  5031.8     .05       0
  5322.5     .08       0  5457.2     .16       0
Bank Sta=4996.4,5002.4
XS Rating Curve= 0 ,0
Exp/Cntr=0.3,0.1

Chan Stop Cuts=-1
Use User Specified Reach Order=0
Composite Channel Slope=5