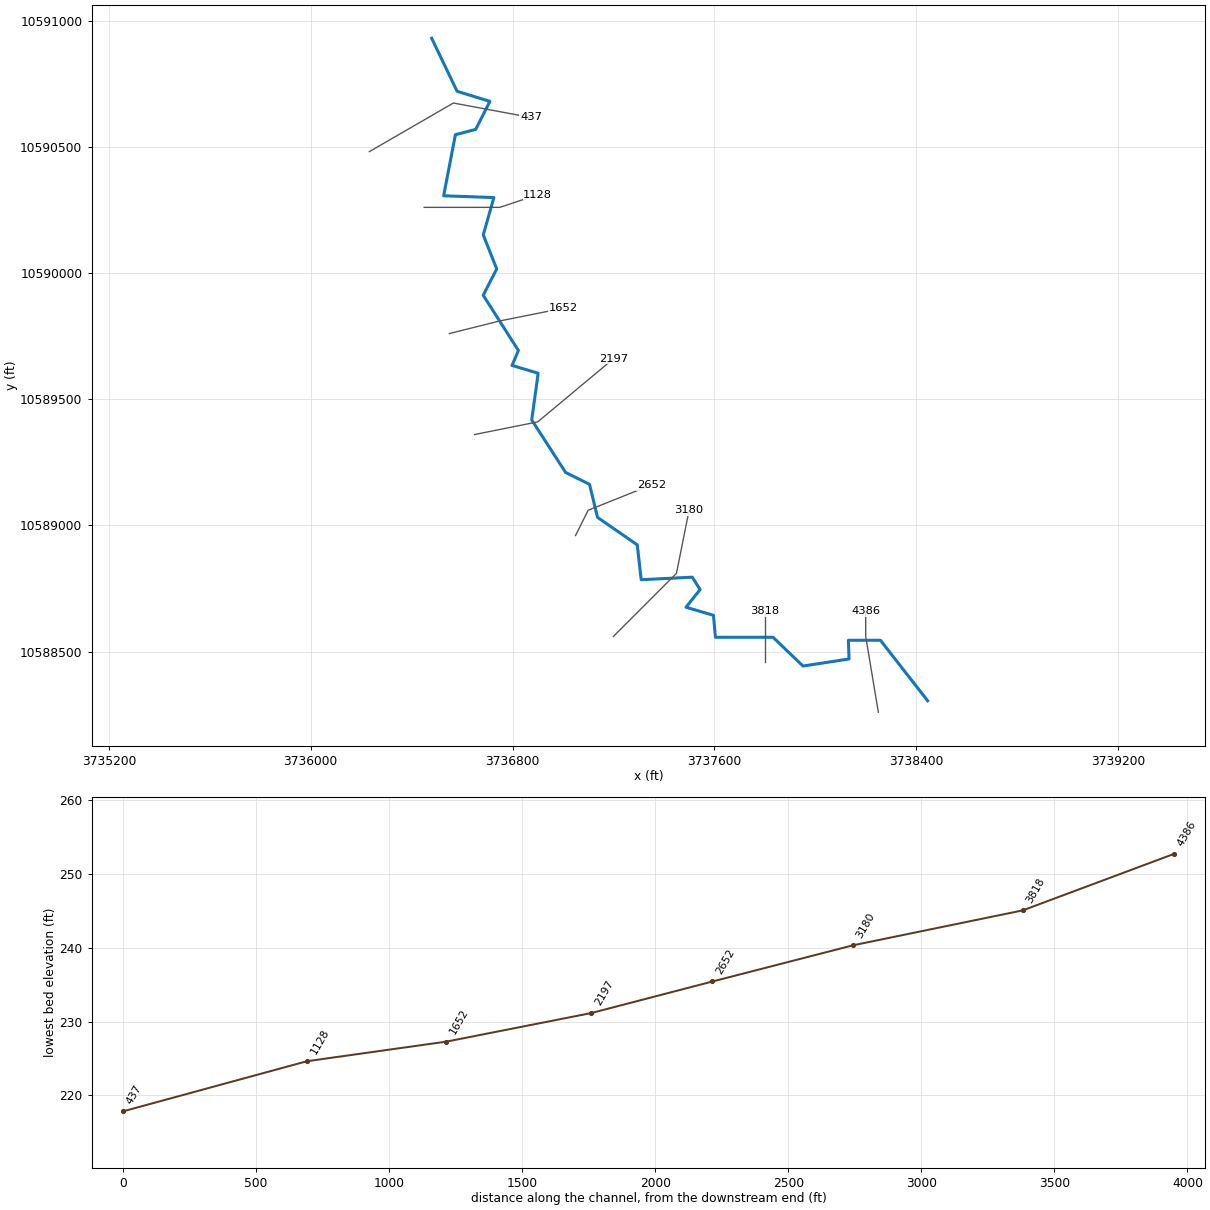
--- UNT 181 IN BOCR.prj (project) ---

Proj Title=UNT 181 IN BOCR Base Level Engineering
Current Plan=p01
Default Exp/Contr=0.3,0.1
English Units
Geom File=g01
Flow File=f01
Plan File=p01
Y Axis Title=Elevation
X Axis Title(PF)=Main Channel Distance
X Axis Title(XS)=Station
BEGIN DESCRIPTION:
UNT 181 IN BOCR
END DESCRIPTION:
DSS Export Rating Curves= 0
DSS Export Rating Curve Sorted= 0
DSS Export Volume Flow Curves= 0
DXF OffsetX= 0
DXF OffsetY= 0
DXF ScaleX= 1
DXF ScaleY= 10

--- UNT 181 IN BOCR.p01 (plan) ---

Plan Title=Multiple Run
Short Identifier=Multiple
Geom File=g01
Flow File=f01
Subcritical Flow
K Sum by GR= 0
Std Step Tol= 0.01
Critical Tol= 0.01
Num of Std Step Trials= 20
Max Error Tol= 0.3
Flow Tol Ratio= 0.001
Split Flow NTrial= 30
Split Flow Tol= 0.02
Split Flow Ratio= 0.02
Log Output Level= 0
Friction Slope Method= 1
Unsteady Friction Slope Method= 2
Unsteady Bridges Friction Slope Method= 1
Parabolic Critical Depth
Global Vel Dist=  1 , 1 , 1
Global Log Level= 0
CheckData=True
Encroach Param= -1, 0, 0, 0
BEGIN DESCRIPTION:
Multiple Run
END DESCRIPTION:

--- UNT 181 IN BOCR.f01 (steady flow) ---

Flow Title=Multiple
Program Version=4.10
Number of Profiles= 7
Profile Names=10-year,25-year,50-year,1pct_min,100-year,1pct_plu,500-year
River Rch & RM=UNT 181 IN BOCR,Reach-1         ,4386
     537     725     880     786    1063    1438    1556
Boundary for River Rch & Prof#=UNT 181 IN BOCR,Reach-1         , 1
Up Type= 0
Dn Type= 3
Dn Slope=0.01
Boundary for River Rch & Prof#=UNT 181 IN BOCR,Reach-1         , 2
Up Type= 0
Dn Type= 3
Dn Slope=0.01
Boundary for River Rch & Prof#=UNT 181 IN BOCR,Reach-1         , 3
Up Type= 0
Dn Type= 3
Dn Slope=0.01
Boundary for River Rch & Prof#=UNT 181 IN BOCR,Reach-1         , 4
Up Type= 0
Dn Type= 3
Dn Slope=0.01
Boundary for River Rch & Prof#=UNT 181 IN BOCR,Reach-1         , 5
Up Type= 0
Dn Type= 3
Dn Slope=0.01
Boundary for River Rch & Prof#=UNT 181 IN BOCR,Reach-1         , 6
Up Type= 0
Dn Type= 3
Dn Slope=0.01
Boundary for River Rch & Prof#=UNT 181 IN BOCR,Reach-1         , 7
Up Type= 0
Dn Type= 3
Dn Slope=0.01
DSS Import GetInterval= 0
DSS Import GetPeak= 0
DSS Import FillOption= 0

--- UNT 181 IN BOCR.g01 (geometry) ---

Geom Title=Existing Conditions
Program Version=4.10

River Reach=UNT 181 IN BOCR ,Reach-1
Reach XY= 30
      3738445.09      10588305.3        3738258.       10588545.
        3738131.       10588545.       3738133.5       10588471.
        3737951.       10588443.      3737832.25       10588557.
        3737604.       10588557.      3737596.25       10588644.
       3737487.5       10588676.      3737543.25       10588746.
      3737512.25       10588795.      3737309.75       10588785.
      3737294.25       10588923.      3737136.75       10589032.
        3737105.       10589163.      3737010.25       10589210.
        3736876.       10589418.       3736901.5       10589603.
        3736798.       10589634.      3736823.25       10589693.
      3736683.75       10589912.      3736737.25       10590016.
        3736684.       10590151.        3736726.       10590299.
        3736527.       10590306.       3736573.5       10590548.
        3736654.       10590569.      3736710.25       10590680.
      3736580.25       10590720.       3736479.5       10590930.

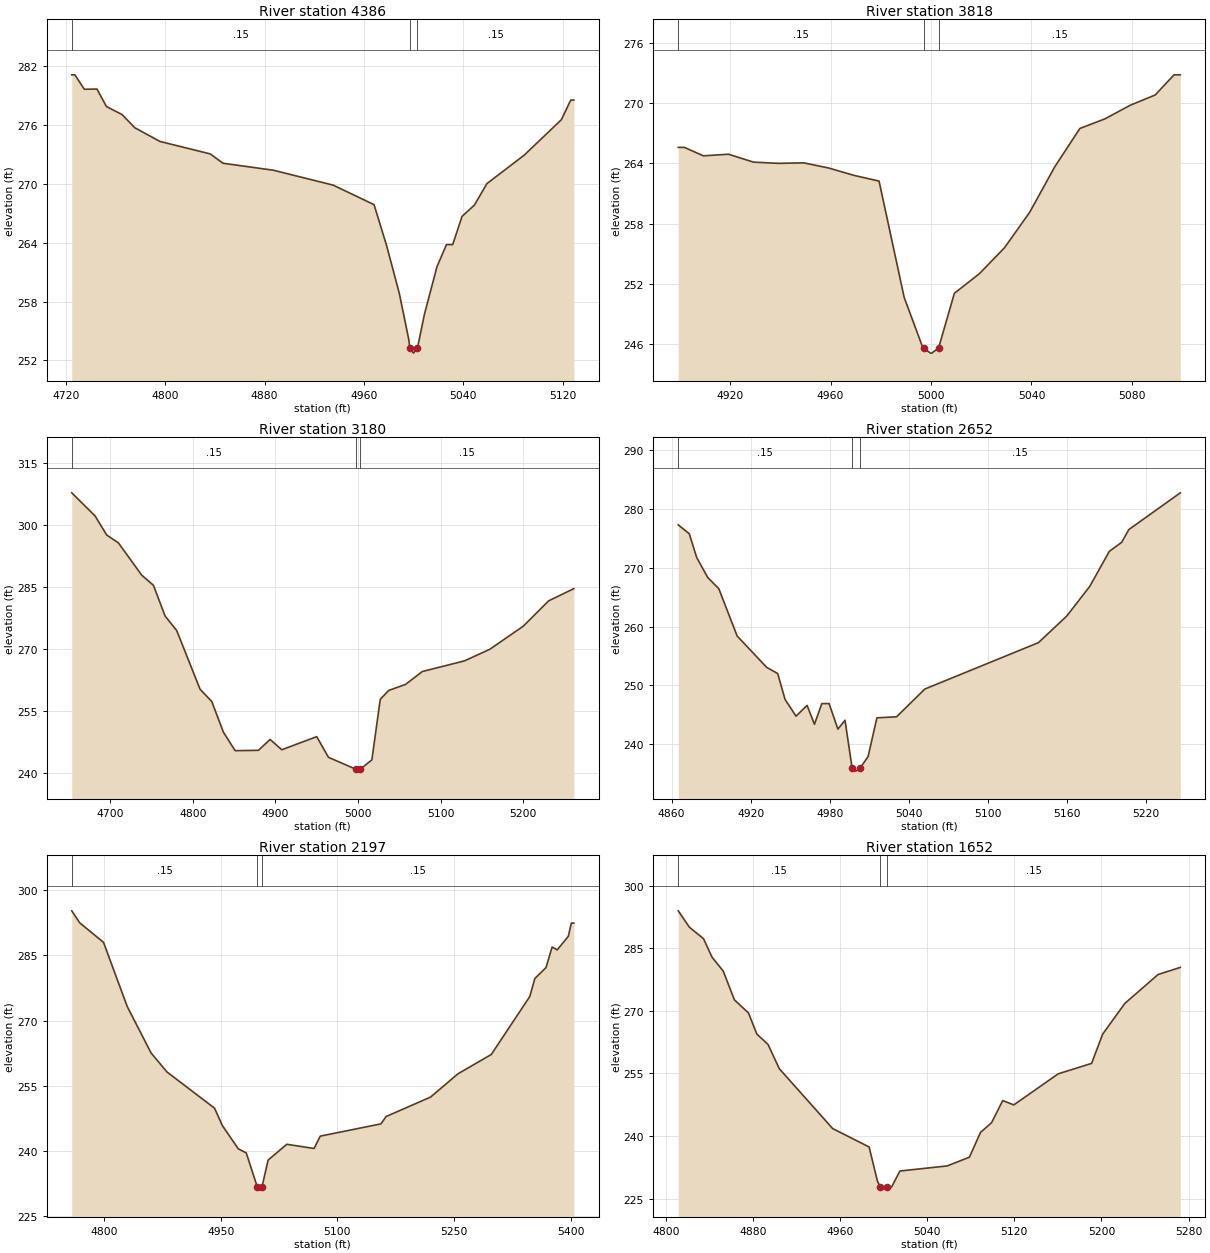
Type RM Length L Ch R = 1 ,4386    ,568,568,568
BEGIN DESCRIPTION:
UNT 181 IN BOCR 8.0
END DESCRIPTION:
XS GIS Cut Line= 3
      3738249.61     10588260.19      3738199.61     10588560.19
      3738199.61     10588660.15
#Sta/Elev= 30
  4724.8   281.1  4727.3   281.1  4734.9  279.63  4745.1  279.65  4752.7  277.87
  4765.3  277.05  4775.5  275.71  4795.8  274.31  4836.3  273.04  4846.5  272.09
    4887  271.38  4935.2  269.86  4968.1  267.87  4978.2   263.7  4988.4  258.84
    4996  254.16    4997  253.24  4999.8  252.74    5003  253.24  5008.7  256.73
  5018.8  261.57  5026.4   263.8  5031.4   263.8  5038.9  266.67  5048.9  267.83
  5058.9  270.01  5088.9  272.91  5118.9  276.53  5126.4  278.53  5128.9  278.53
#Mann= 3 ,-1 , 0
  4724.8     .15       0    4997     .05       0    5003     .15       0
Bank Sta=4997,5003
XS Rating Curve= 0 ,0
Exp/Cntr=0.3,0.1

Type RM Length L Ch R = 1 ,3818    ,638,638,638
BEGIN DESCRIPTION:
UNT 181 IN BOCR 7.0
END DESCRIPTION:
XS GIS Cut Line= 3
      3737799.61     10588460.18      3737799.61     10588560.19
      3737799.61     10588660.18
#Sta/Elev= 27
  4899.3   265.6  4901.8   265.6  4909.3  264.76  4919.3  264.92  4929.3  264.13
  4939.3  264.01  4949.3  264.06  4959.3  263.54  4969.3  262.81  4979.3  262.24
  4989.3  250.64  4996.8  245.58    4997  245.58  4999.8  245.08  5000.3  245.08
    5003  245.58  5009.3  251.05  5019.3  253.01  5029.3   255.6  5039.3  259.13
  5049.3  263.67  5059.3  267.49  5069.3  268.45  5079.3   269.8  5089.3  270.83
  5096.8  272.84  5099.3  272.84
#Mann= 3 ,-1 , 0
  4899.3     .15       0    4997     .05       0    5003     .15       0
Bank Sta=4997,5003
XS Rating Curve= 0 ,0
Exp/Cntr=0.3,0.1

Type RM Length L Ch R = 1 ,3180    ,528,528,528
BEGIN DESCRIPTION:
UNT 181 IN BOCR 6.0
END DESCRIPTION:
XS GIS Cut Line= 3
      3737199.64     10588560.21      3737449.61     10588810.19
      3737499.62     10589060.22
#Sta/Elev= 30
  4653.1  307.67  4681.3  302.09  4695.5  297.46  4709.6  295.57  4737.9  287.75
  4752.1  285.29  4766.2  277.87  4780.3  274.35  4808.6  260.15  4822.8  257.18
  4836.9  249.75  4851.1  245.29  4879.3  245.37  4893.5  248.01  4907.6  245.51
    4950  248.68  4964.2  243.68    4997  240.84  4999.8  240.34    5003  240.84
  5016.8  243.06    5027  257.71  5037.2  259.86  5057.6  261.32    5078  264.44
    5129  267.01  5159.6   269.8  5200.4  275.42    5231  281.53  5261.6  284.49
#Mann= 3 ,-1 , 0
  4653.1     .15       0    4997     .05       0    5003     .15       0
Bank Sta=4997,5003
XS Rating Curve= 0 ,0
Exp/Cntr=0.3,0.1

Type RM Length L Ch R = 1 ,2652    ,455,455,455
BEGIN DESCRIPTION:
UNT 181 IN BOCR 5.0
END DESCRIPTION:
XS GIS Cut Line= 3
      3737049.61     10588960.18      3737099.61     10589060.19
      3737349.64      10589160.2
#Sta/Elev= 30
    4865  277.28  4873.4  275.76    4879  271.74  4887.4  268.33  4895.8  266.43
  4909.7   258.4  4932.1  253.07  4940.5  252.01  4946.1  247.61  4954.4  244.77
  4962.8   246.6  4968.4  243.39    4974  246.91  4979.5  246.91  4986.2  242.57
  4991.6  244.07    4997  235.93  4999.8  235.43    5003  235.93  5009.1   237.9
  5015.8  244.49  5030.7  244.66  5052.2  249.38  5138.4  257.26  5159.9  261.78
  5177.4  266.83  5192.2  272.77  5201.6  274.31    5207  276.47  5246.1  282.72
#Mann= 3 ,-1 , 0
    4865     .15       0    4997     .05       0    5003     .15       0
Bank Sta=4997,5003
XS Rating Curve= 0 ,0
Exp/Cntr=0.3,0.1

Type RM Length L Ch R = 1 ,2197    ,545,545,545
BEGIN DESCRIPTION:
UNT 181 IN BOCR 4.0
END DESCRIPTION:
XS GIS Cut Line= 3
      3736649.63     10589360.19      3736899.61     10589410.19
      3737199.58     10589660.16
#Sta/Elev= 30
  4758.5  295.28  4768.7  292.52  4799.3  288.02  4829.9  273.19  4860.5  262.52
  4880.8  258.16    4942  249.81  4952.2  245.76  4972.6  240.43  4982.8   239.5
    4997  231.65  4999.8  231.15    5003  231.65  5010.9  237.84  5034.9  241.48
    5070  240.52  5077.9  243.36    5156  246.19  5162.5  247.87  5219.7  252.36
  5254.9  257.72  5297.8  262.18  5347.3  275.54  5353.8  279.69  5368.1   282.2
    5376  286.95  5382.5  286.28  5396.8  289.41  5400.7  292.45  5403.9  292.45
#Mann= 3 ,-1 , 0
  4758.5     .15       0    4997     .05       0    5003     .15       0
Bank Sta=4997,5003
XS Rating Curve= 0 ,0
Exp/Cntr=0.3,0.1

Type RM Length L Ch R = 1 ,1652    ,524,524,524
BEGIN DESCRIPTION:
UNT 181 IN BOCR 3.0
END DESCRIPTION:
XS GIS Cut Line= 3
      3736549.57     10589760.18      3736749.61     10589810.19
      3736999.57     10589860.18
#Sta/Elev= 30
  4811.3  293.97  4821.6  290.03  4834.5   287.3  4842.3  282.88  4852.6  279.54
  4862.9  272.63  4875.8   269.5  4883.5  264.43  4893.8  261.93  4904.1  256.14
  4953.1  241.79  4986.6  237.37  4994.3  229.12    4997  227.77  4999.8  227.27
    5003  227.77  5007.2  227.77  5014.9  231.61  5058.3  232.83  5078.7  234.92
  5088.9  240.86  5099.1   243.2  5109.3  248.49  5119.5  247.46  5160.3  254.91
  5190.9   257.4  5201.1  264.42  5221.5  271.79    5252  278.71  5272.4  280.41
#Mann= 3 ,-1 , 0
  4811.3     .15       0    4997     .05       0    5003     .15       0
Bank Sta=4997,5003
XS Rating Curve= 0 ,0
Exp/Cntr=0.3,0.1

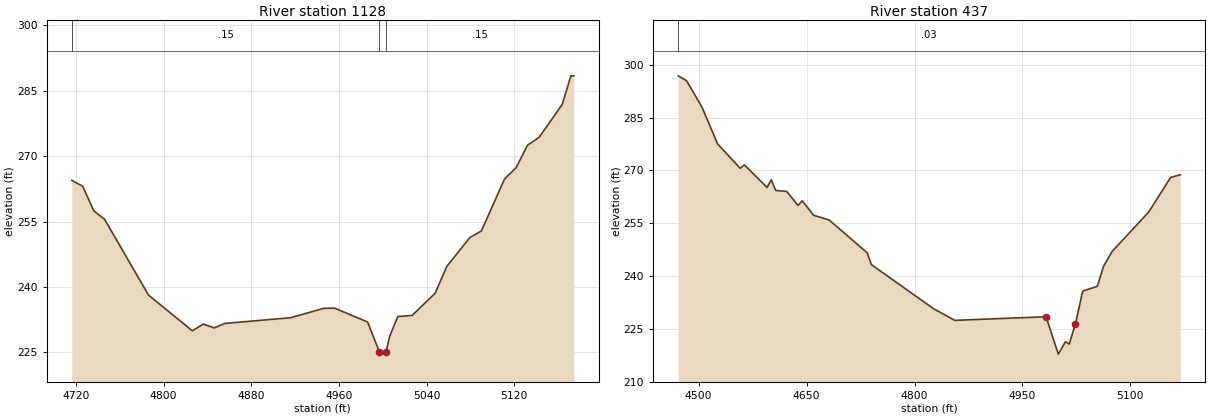
Type RM Length L Ch R = 1 ,1128    ,691,691,691
BEGIN DESCRIPTION:
UNT 181 IN BOCR 2.0
END DESCRIPTION:
XS GIS Cut Line= 3
      3736449.57     10590260.19      3736749.61     10590260.19
      3736899.65      10590310.2
#Sta/Elev= 30
  4716.2  264.46  4726.2  263.09  4736.2   257.5  4746.2   255.5  4786.2  238.16
  4826.2  229.96  4836.2  231.49  4846.2  230.63  4856.2  231.66  4916.2  232.96
  4946.2  235.12  4956.2  235.14  4986.2  231.97    4997  225.11  4999.8  224.61
    5003  225.11  5006.2  228.59  5013.7  233.22  5026.8  233.48  5047.9  238.59
  5058.4   244.7  5079.5  251.34    5090  252.84  5111.1  264.73  5121.7  267.36
  5132.2  272.52  5142.7  274.31  5163.8  281.85  5171.7  288.41  5174.4  288.41
#Mann= 3 ,-1 , 0
  4716.2     .15       0    4997     .05       0    5003     .15       0
Bank Sta=4997,5003
XS Rating Curve= 0 ,0
Exp/Cntr=0.3,0.1

Type RM Length L Ch R = 1 ,437     ,0,0,0
BEGIN DESCRIPTION:
UNT 181 IN BOCR 1.0
END DESCRIPTION:
XS GIS Cut Line= 3
      3736232.32      10590480.8      3736565.68     10590673.52
      3736872.92     10590616.24
#Sta/Elev= 30
  4471.7  296.86  4483.2  295.48  4504.7  287.97  4526.3  277.55  4557.8  270.58
  4563.6  271.57  4595.1  265.15  4600.9  267.32  4607.2  264.31  4622.4  264.02
  4638.2  260.05    4644  261.37  4659.7  257.26  4681.3  255.92  4734.2   246.6
  4740.1  243.23  4826.6  230.69  4856.1   227.4  4982.8  228.43  4999.8  217.81
  5009.8  221.34  5014.9  220.66  5023.5  226.31  5033.7  235.73    5054  237.06
  5062.5  242.68  5074.4  246.94  5125.4  258.17  5155.8  267.98  5169.3  268.78
#Mann= 1 ,-1 , 0
  4471.7     .03       0
Bank Sta=4982.8,5023.5
XS Rating Curve= 0 ,0
Exp/Cntr=0.3,0.1

Chan Stop Cuts=-1
Use User Specified Reach Order=0
Composite Channel Slope=5