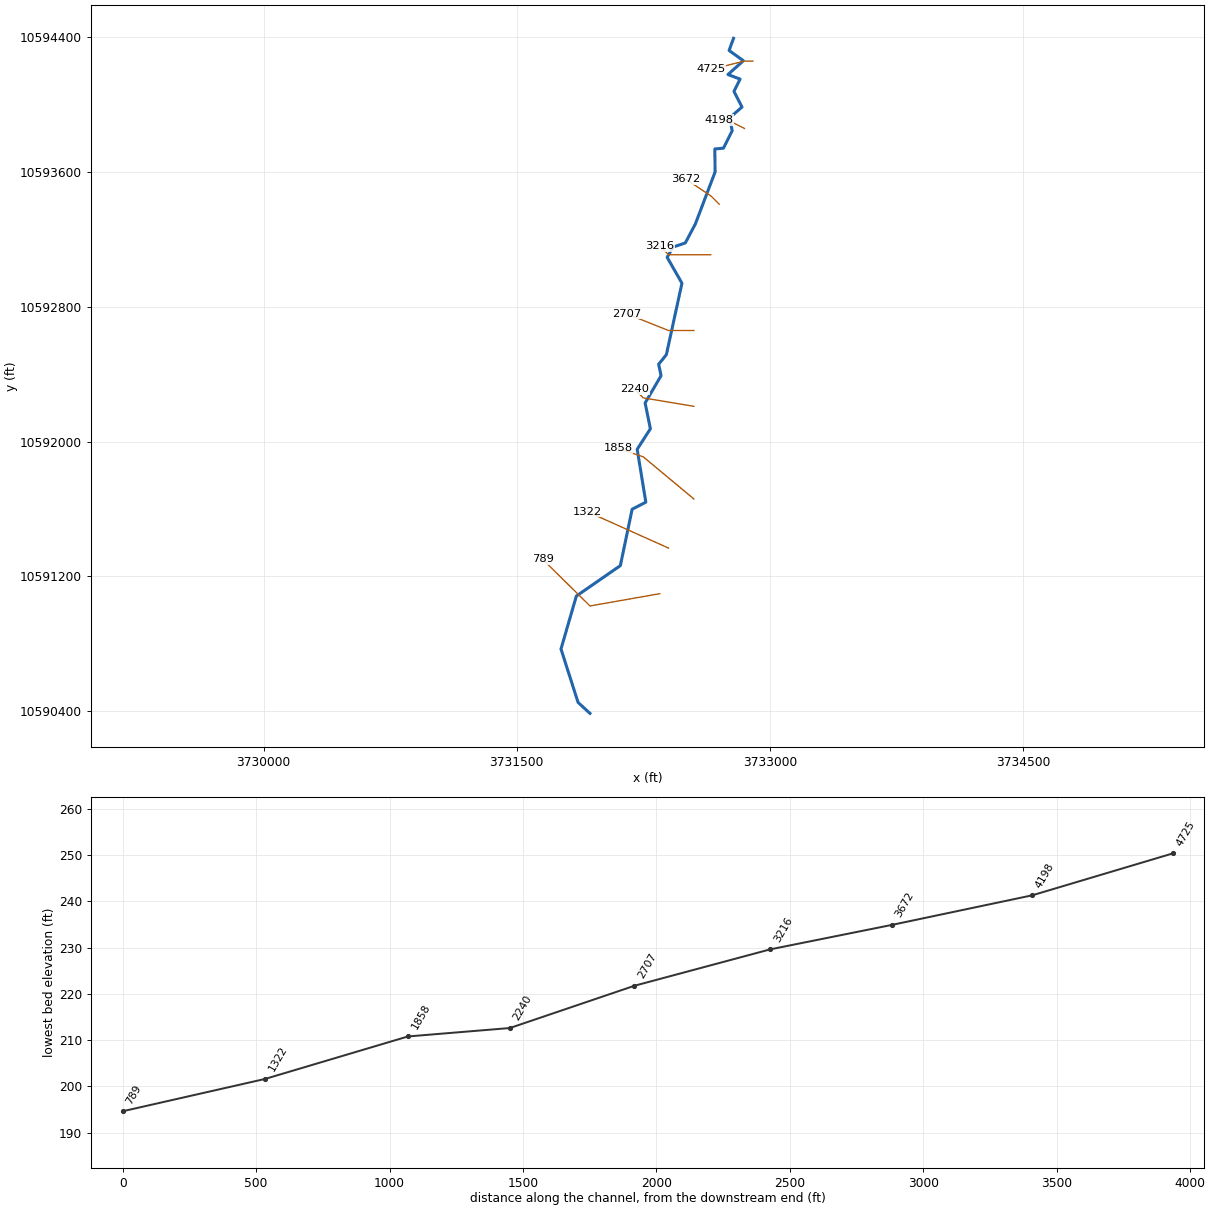
--- UNT 182 IN BOCR.prj (project) ---

Proj Title=UNT 182 IN BOCR Base Level Engineering
Current Plan=p01
Default Exp/Contr=0.3,0.1
English Units
Geom File=g01
Flow File=f01
Plan File=p01
BEGIN DESCRIPTION:
UNT 182 IN BOCR
END DESCRIPTION:

--- UNT 182 IN BOCR.p01 (plan) ---

Plan Title=Multiple Run
Short Identifier=Multiple
Geom File=g01
Flow File=f01
Subcritical Flow
K Sum by GR= 0
Std Step Tol= 0.01
Critical Tol= 0.01
Num of Std Step Trials= 20
Max Error Tol= 0.3
Flow Tol Ratio= 0.001
Split Flow NTrial= 30
Split Flow Tol= 0.02
Split Flow Ratio= 0.02
Log Output Level= 0
Friction Slope Method= 1
Unsteady Friction Slope Method= 2
Unsteady Bridges Friction Slope Method= 1
Parabolic Critical Depth
Global Vel Dist=  1 , 1 , 1
Global Log Level= 0
CheckData=True
Encroach Param= -1, 0, 0, 0
BEGIN DESCRIPTION:
Multiple Run
END DESCRIPTION:

--- UNT 182 IN BOCR.f01 (steady flow) ---

Flow Title=Multiple
Number of Profiles=7
Profile Names=10-year,25-year,50-year,1pct_min,100-year,1pct_plu,500-year
River Rch & RM= UNT 182 IN BOCR,Reach-1,4725
     276     358     424     371     501     678     701
Boundary for River Rch & Prof#=UNT 182 IN BOCR,Reach-1,1
Up Type=0
Dn Type=3
Dn Slope=0.005
Boundary for River Rch & Prof#=UNT 182 IN BOCR,Reach-1,2
Up Type=0
Dn Type=3
Dn Slope=0.005
Boundary for River Rch & Prof#=UNT 182 IN BOCR,Reach-1,3
Up Type=0
Dn Type=3
Dn Slope=0.005
Boundary for River Rch & Prof#=UNT 182 IN BOCR,Reach-1,4
Up Type=0
Dn Type=3
Dn Slope=0.005
Boundary for River Rch & Prof#=UNT 182 IN BOCR,Reach-1,5
Up Type=0
Dn Type=3
Dn Slope=0.005
Boundary for River Rch & Prof#=UNT 182 IN BOCR,Reach-1,6
Up Type=0
Dn Type=3
Dn Slope=0.005
Boundary for River Rch & Prof#=UNT 182 IN BOCR,Reach-1,7
Up Type=0
Dn Type=3
Dn Slope=0.005

--- UNT 182 IN BOCR.g01 (geometry) ---

Geom Title=Existing Conditions

River Reach=UNT 182 IN BOCR,Reach-1
Reach XY= 30
      3732784.50     10594395.00      3732758.50     10594323.00
      3732843.00     10594262.00      3732751.75     10594180.00
      3732823.50     10594153.00      3732787.25     10594080.00
      3732834.75     10593987.00      3732763.00     10593924.00
      3732776.50     10593846.00      3732725.00     10593743.00
      3732673.75     10593738.00      3732675.50     10593602.00
      3732557.75     10593291.00      3732498.75     10593180.00
      3732427.00     10593156.00      3732391.25     10593095.00
      3732479.00     10592941.00      3732386.75     10592517.00
      3732341.00     10592460.00      3732355.25     10592392.00
      3732260.75     10592230.00      3732292.00     10592077.00
      3732213.75     10591955.00      3732265.00     10591641.00
      3732183.75     10591599.00      3732114.00     10591264.29
      3731853.15     10591083.39      3731762.25     10590769.00
      3731863.50     10590452.00      3731934.00     10590387.00

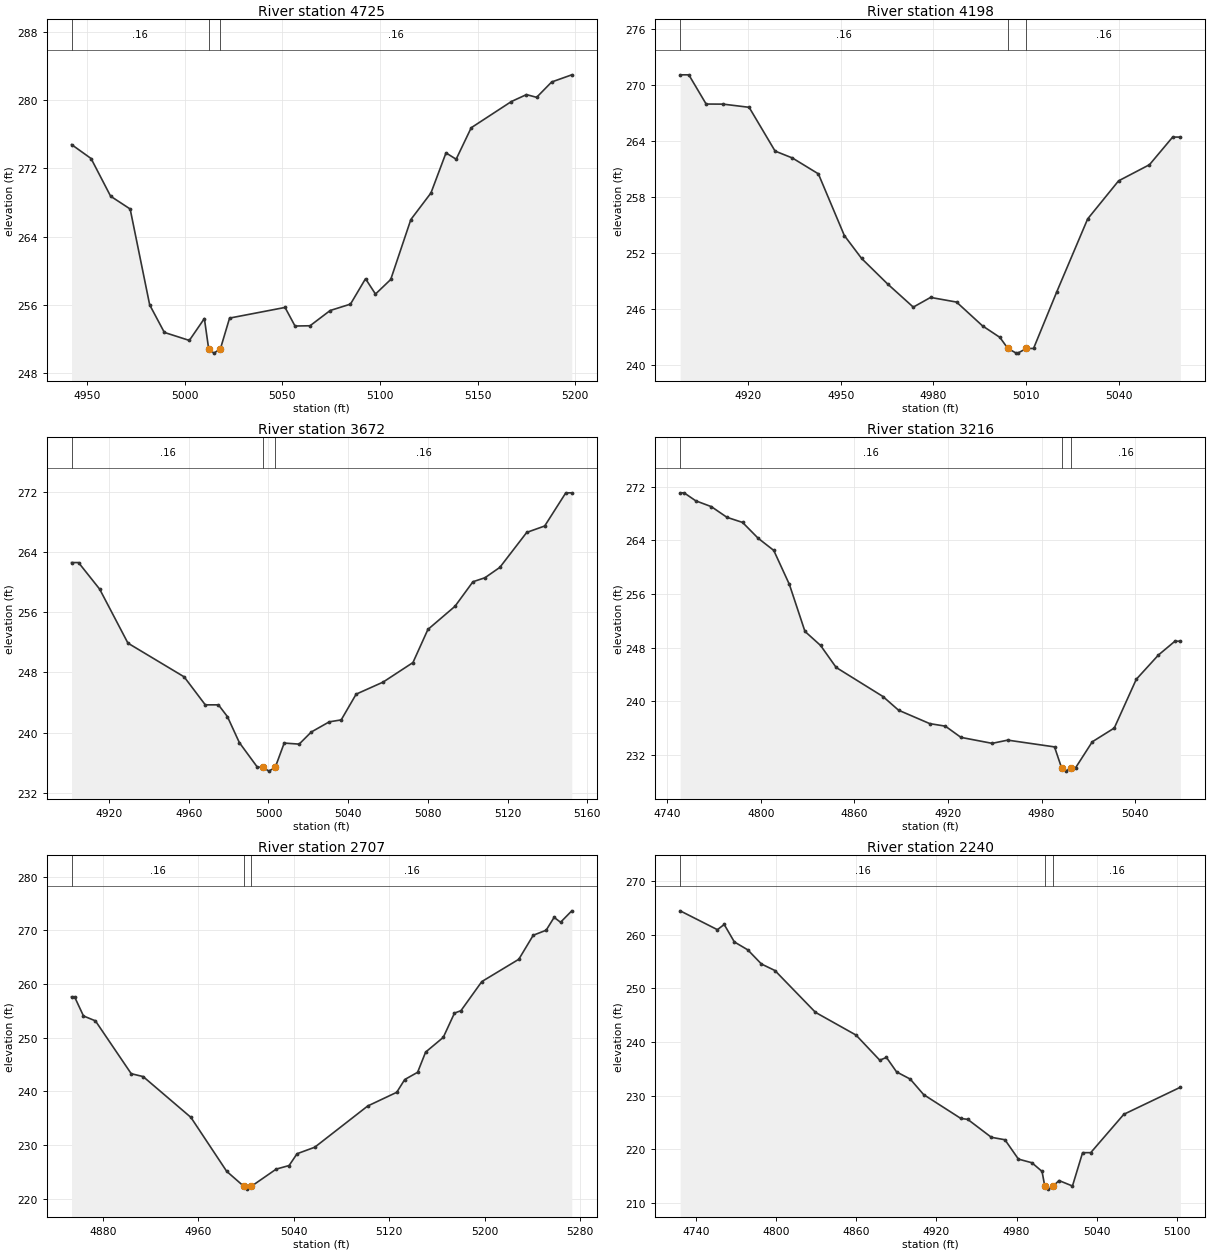
Type RM Length L Ch R = 1,4725,527,527,527
BEGIN DESCRIPTION:
UNT 182 IN BOCR 9.0
END DESCRIPTION:
XS GIS Cut Line= 3
      3732899.59     10594260.19      3732849.61     10594260.19
      3732649.64     10594210.20
#Sta/Elev= 30
  4942.1  274.80  4952.1  273.16  4962.1  268.74  4972.1  267.24  4982.1  255.99
  4989.6  252.76  5002.4  251.82  5010.1  254.39  5012.3  250.83  5015.0  250.33
  5018.3  250.83  5023.0  254.44  5051.4  255.69  5056.5  253.51  5064.2  253.54
  5074.5  255.33  5084.9  256.08  5092.6  259.06  5097.7  257.26  5105.5  258.97
  5115.8  266.00  5126.1  269.12  5133.8  273.82  5139.0  273.08  5146.7  276.77
  5167.3  279.85  5175.0  280.66  5180.2  280.34  5187.9  282.14  5198.2  282.98
#Mann=3,-1,0
  4942.1    0.16       0  5012.3    0.07       0  5018.3    0.16       0
Bank Sta=5012.3,5018.3
Exp/Cntr=0.3,0.1

Type RM Length L Ch R = 1,4198,526,526,526
BEGIN DESCRIPTION:
UNT 182 IN BOCR 8.0
END DESCRIPTION:
XS GIS Cut Line= 3
      3732849.59     10593860.20      3732749.61     10593910.19
      3732699.59     10593910.19
#Sta/Elev= 27
  4898.1  271.10  4900.9  271.10  4906.5  267.97  4912.0  267.96  4920.4  267.62
  4928.8  262.93  4934.4  262.19  4942.8  260.49  4951.2  253.88  4956.8  251.42
  4965.2  248.69  4973.5  246.21  4979.1  247.25  4987.5  246.75  4995.9  244.20
  5001.5  242.97  5004.1  241.78  5006.8  241.28  5007.3  241.28  5010.1  241.78
  5012.4  241.78  5019.9  247.84  5029.9  255.66  5039.9  259.74  5049.9  261.47
  5057.4  264.43  5059.9  264.43
#Mann=3,-1,0
  4898.1    0.16       0  5004.1    0.07       0  5010.1    0.16       0
Bank Sta=5004.1,5010.1
Exp/Cntr=0.3,0.1

Type RM Length L Ch R = 1,3672,456,456,456
BEGIN DESCRIPTION:
UNT 182 IN BOCR 7.0
END DESCRIPTION:
XS GIS Cut Line= 3
      3732699.59     10593410.21      3732649.61     10593460.19
      3732499.57     10593560.21
#Sta/Elev= 30
  4901.2  262.61  4904.7  262.61  4915.3  259.08  4929.5  251.90  4957.7  247.42
  4968.3  243.70  4974.9  243.70  4979.4  242.14  4985.4  238.68  4994.4  235.43
  4997.4  235.39  5000.2  234.89  5003.4  235.39  5007.9  238.62  5015.4  238.48
  5021.5  240.09  5030.5  241.44  5036.5  241.70  5044.0  245.12  5057.5  246.72
  5072.5  249.32  5080.0  253.72  5093.6  256.80  5102.6  260.06  5108.6  260.59
  5116.1  261.97  5129.6  266.62  5138.6  267.47  5149.2  271.88  5152.2  271.88
#Mann=3,-1,0
  4901.2    0.16       0  4997.4    0.07       0  5003.4    0.16       0
Bank Sta=4997.4,5003.4
Exp/Cntr=0.3,0.1

Type RM Length L Ch R = 1,3216,509,509,509
BEGIN DESCRIPTION:
UNT 182 IN BOCR 6.0
END DESCRIPTION:
XS GIS Cut Line= 3
      3732649.62     10593110.19      3732399.61     10593110.19
      3732349.63     10593160.17
#Sta/Elev= 30
  4748.3  271.08  4750.8  271.08  4758.3  269.89  4768.3  269.02  4778.3  267.43
  4788.3  266.67  4798.3  264.31  4808.3  262.50  4818.3  257.44  4828.3  250.43
  4838.3  248.34  4848.3  245.06  4878.3  240.73  4888.3  238.69  4908.3  236.69
  4918.3  236.31  4928.3  234.64  4948.3  233.75  4958.3  234.23  4988.3  233.22
  4992.8  230.11  4995.6  229.61  4998.8  230.11  5001.8  230.11  5012.5  233.98
  5026.6  236.03  5040.7  243.29  5054.9  246.91  5065.5  248.97  5069.0  248.97
#Mann=3,-1,0
  4748.3    0.16       0  4992.8    0.07       0  4998.8    0.16       0
Bank Sta=4992.8,4998.8
Exp/Cntr=0.3,0.1

Type RM Length L Ch R = 1,2707,467,467,467
BEGIN DESCRIPTION:
UNT 182 IN BOCR 5.0
END DESCRIPTION:
XS GIS Cut Line= 3
      3732549.58     10592660.19      3732399.61     10592660.19
      3732149.63     10592760.18
#Sta/Elev= 30
  4853.9  257.61  4856.4  257.61  4863.9  254.03  4873.9  253.12  4903.9  243.27
  4913.9  242.73  4953.9  235.13  4983.9  225.07  4998.4  222.25  5001.1  221.75
  5004.4  222.25  5025.4  225.48  5036.2  226.15  5042.9  228.35  5057.7  229.56
  5102.1  237.25  5126.4  239.80  5133.1  242.18  5143.9  243.53  5150.6  247.29
  5165.4  250.04  5174.8  254.57  5180.2  255.01  5197.7  260.44  5228.7  264.60
  5240.8  269.08  5251.6  270.01  5258.3  272.41  5263.7  271.50  5273.1  273.63
#Mann=3,-1,0
  4853.9    0.16       0  4998.4    0.07       0  5004.4    0.16       0
Bank Sta=4998.4,5004.4
Exp/Cntr=0.3,0.1

Type RM Length L Ch R = 1,2240,382,382,382
BEGIN DESCRIPTION:
UNT 182 IN BOCR 4.0
END DESCRIPTION:
XS GIS Cut Line= 3
      3732549.65     10592210.18      3732249.61     10592260.19
      3732199.60     10592310.20
#Sta/Elev= 30
  4727.9  264.43  4755.8  260.92  4760.9  261.89  4768.5  258.64  4778.6  257.16
  4788.8  254.53  4798.9  253.32  4829.3  245.53  4859.7  241.30  4877.5  236.62
  4882.5  237.14  4890.1  234.44  4900.3  233.11  4910.4  230.21  4938.3  225.77
  4943.4  225.61  4961.1  222.27  4971.3  221.81  4981.4  218.21  4991.5  217.53
  4999.1  215.92  5001.2  213.12  5003.9  212.62  5007.2  213.12  5011.8  214.22
  5021.9  213.20  5029.5  219.41  5035.6  219.41  5060.4  226.55  5102.8  231.59
#Mann=3,-1,0
  4727.9    0.16       0  5001.2    0.07       0  5007.2    0.16       0
Bank Sta=5001.2,5007.2
Exp/Cntr=0.3,0.1

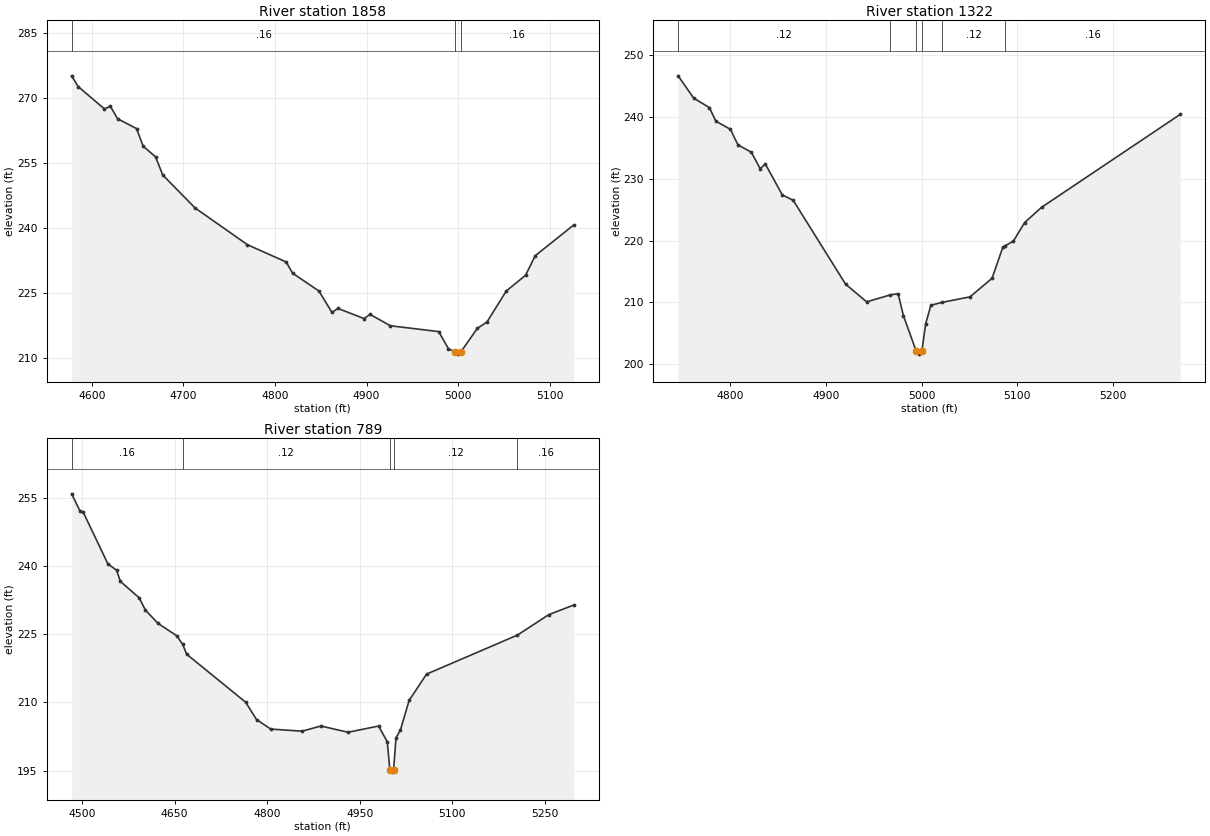
Type RM Length L Ch R = 1,1858,536,536,536
BEGIN DESCRIPTION:
UNT 182 IN BOCR 3.0
END DESCRIPTION:
XS GIS Cut Line= 3
      3732549.58     10591660.22      3732249.61     10591910.19
      3732099.59     10591960.19
#Sta/Elev= 30
  4577.9  275.07  4585.0  272.59  4613.7  267.43  4620.2  268.04  4628.0  265.18
  4648.8  262.88  4656.0  258.82  4669.6  256.35  4677.4  252.17  4712.6  244.58
  4769.9  236.07  4812.2  232.08  4819.3  229.49  4848.0  225.37  4862.3  220.43
  4868.8  221.35  4897.4  219.01  4903.9  219.98  4926.1  217.35  4978.9  216.00
  4989.5  212.05  4997.0  211.30  4999.7  210.80  5003.0  211.30  5021.1  216.75
  5031.6  218.21  5052.7  225.38  5073.8  229.02  5084.3  233.53  5126.5  240.64
#Mann=3,-1,0
  4577.9    0.16       0  4997.0    0.07       0  5003.0    0.16       0
Bank Sta=4997,5003
Exp/Cntr=0.3,0.1

Type RM Length L Ch R = 1,1322,533,533,533
BEGIN DESCRIPTION:
UNT 182 IN BOCR 2.0
END DESCRIPTION:
XS GIS Cut Line= 2
      3732399.46     10591368.49      3731920.30     10591583.77
#Sta/Elev= 30
  4745.3  246.66  4761.6  243.05  4778.0  241.52  4784.8  239.31  4800.0  238.01
  4807.9  235.48  4821.9  234.30  4831.1  231.64  4836.6  232.38  4854.3  227.38
  4865.7  226.51  4920.5  212.94  4942.5  210.08  4967.3  211.21  4975.4  211.40
  4981.0  207.83  4994.3  202.12  4997.0  201.62  5000.3  202.12  5004.2  206.51
  5009.7  209.52  5021.1  209.99  5050.5  210.88  5073.7  213.89  5085.0  218.95
  5087.3  219.15  5096.0  219.91  5107.8  222.92  5125.5  225.38  5270.6  240.43
#Mann=6,-1,0
  4745.3    0.12       0  4967.3    0.16       0  4994.3    0.07       0
  5000.3    0.16       0  5021.1    0.12       0  5087.3    0.16       0
Bank Sta=4994.3,5000.3
Exp/Cntr=0.3,0.1

Type RM Length L Ch R = 1,789,0,0,0
BEGIN DESCRIPTION:
UNT 182 IN BOCR 1.0
END DESCRIPTION:
XS GIS Cut Line= 3
      3732347.34     10591097.65      3731934.19     10591024.74
      3731653.75     10591301.72
#Sta/Elev= 30
  4483.2  255.95  4496.7  252.17  4501.8  251.95  4541.8  240.55  4556.0  239.11
  4562.1  236.68  4592.6  233.04  4602.8  230.32  4623.1  227.42  4653.5  224.68
  4663.2  222.77  4669.4  220.64  4765.2  210.04  4782.8  206.23  4805.8  204.13
  4856.6  203.67  4887.1  204.81  4931.0  203.43  4980.5  204.80  4994.6  201.34
  4998.8  195.15  5001.5  194.65  5004.8  195.15  5008.8  202.21  5015.9  203.92
  5030.0  210.44  5058.3  216.24  5205.5  224.83  5256.3  229.34  5296.9  231.46
#Mann=5,-1,0
  4483.2    0.16       0  4663.2    0.12       0  4998.8    0.07       0
  5004.8    0.12       0  5205.5    0.16       0
Bank Sta=4998.8,5004.8
Exp/Cntr=0.3,0.1

Chan Stop Cuts=-1