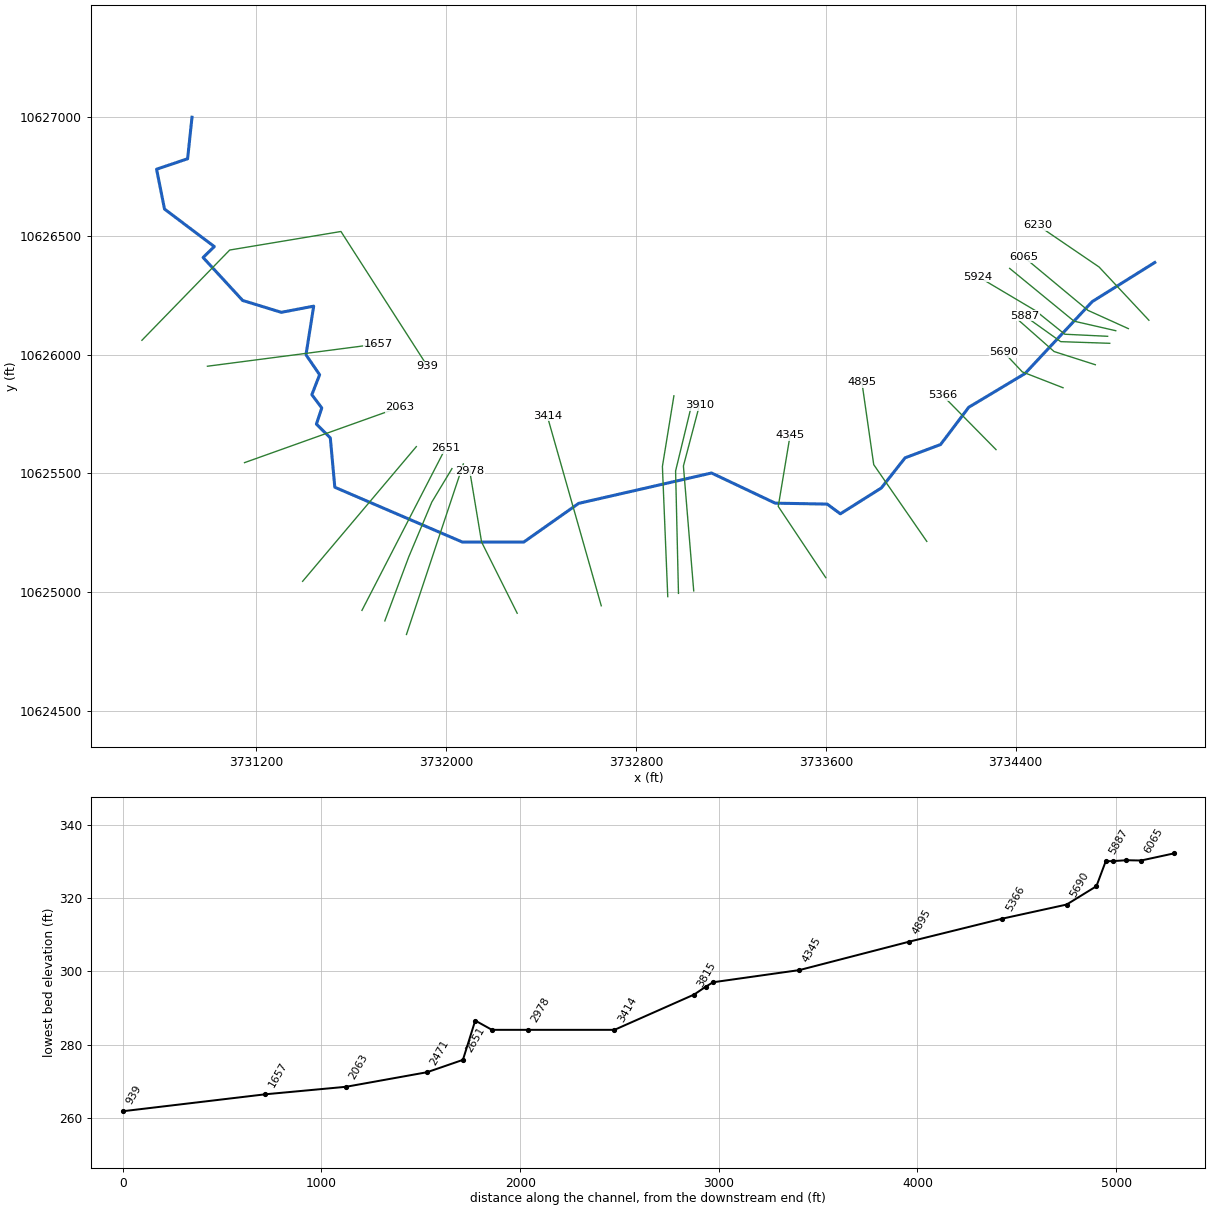
--- UNT 183 IN BOCR.prj (project) ---

Proj Title=UNT 183 IN BOCR Base Level Engineering
Current Plan=p01
Default Exp/Contr=0.3,0.1
English Units
Geom File=g01
Flow File=f01
Plan File=p01
BEGIN DESCRIPTION:
UNT 183 IN BOCR
END DESCRIPTION:

--- UNT 183 IN BOCR.p01 (plan) ---

Plan Title=Multiple Run
Short Identifier=Multiple
Geom File=g01
Flow File=f01
Subcritical Flow
K Sum by GR= 0
Std Step Tol= 0.01
Critical Tol= 0.01
Num of Std Step Trials= 20
Max Error Tol= 0.3
Flow Tol Ratio= 0.001
Split Flow NTrial= 30
Split Flow Tol= 0.02
Split Flow Ratio= 0.02
Log Output Level= 0
Friction Slope Method= 1
Unsteady Friction Slope Method= 2
Unsteady Bridges Friction Slope Method= 1
Parabolic Critical Depth
Global Vel Dist=  1 , 1 , 1
Global Log Level= 0
CheckData=True
Encroach Param= -1, 0, 0, 0
BEGIN DESCRIPTION:
Multiple Run
END DESCRIPTION:

--- UNT 183 IN BOCR.f01 (steady flow) ---

Flow Title=Multiple
Number of Profiles=7
Profile Names=10-year,25-year,50-year,1pct_min,100-year,1pct_plu,500-year
River Rch & RM= UNT 183 IN BOCR,Reach-1,6230
     349     456     542     475     642     869     902
Boundary for River Rch & Prof#=UNT 183 IN BOCR,Reach-1,1
Up Type=0
Dn Type=3
Dn Slope=0.005
Boundary for River Rch & Prof#=UNT 183 IN BOCR,Reach-1,2
Up Type=0
Dn Type=3
Dn Slope=0.005
Boundary for River Rch & Prof#=UNT 183 IN BOCR,Reach-1,3
Up Type=0
Dn Type=3
Dn Slope=0.005
Boundary for River Rch & Prof#=UNT 183 IN BOCR,Reach-1,4
Up Type=0
Dn Type=3
Dn Slope=0.005
Boundary for River Rch & Prof#=UNT 183 IN BOCR,Reach-1,5
Up Type=0
Dn Type=3
Dn Slope=0.005
Boundary for River Rch & Prof#=UNT 183 IN BOCR,Reach-1,6
Up Type=0
Dn Type=3
Dn Slope=0.005
Boundary for River Rch & Prof#=UNT 183 IN BOCR,Reach-1,7
Up Type=0
Dn Type=3
Dn Slope=0.005

--- UNT 183 IN BOCR.g01 (geometry) ---

Geom Title=Existing Conditions

River Reach=UNT 183 IN BOCR,Reach-1
Reach XY= 30
      3734986.00     10626388.00      3734722.25     10626223.00
      3734439.25     10625920.00      3734202.25     10625778.00
      3734083.50     10625621.00      3733934.00     10625565.00
      3733834.00     10625438.00      3733661.25     10625329.00
      3733605.75     10625370.00      3733386.75     10625374.00
      3733118.50     10625501.00      3732558.50     10625373.00
      3732327.25     10625210.00      3732068.75     10625210.00
      3731531.25     10625441.00      3731512.25     10625649.00
      3731453.75     10625707.00      3731476.25     10625775.00
      3731434.50     10625831.00      3731467.25     10625915.00
      3731409.75     10625999.00      3731442.25     10626204.00
      3731305.75     10626178.00      3731143.00     10626228.00
      3730976.25     10626409.00      3731023.50     10626455.00
      3730813.75     10626613.00      3730780.25     10626781.00
      3730911.00     10626825.00      3730929.50     10627000.00

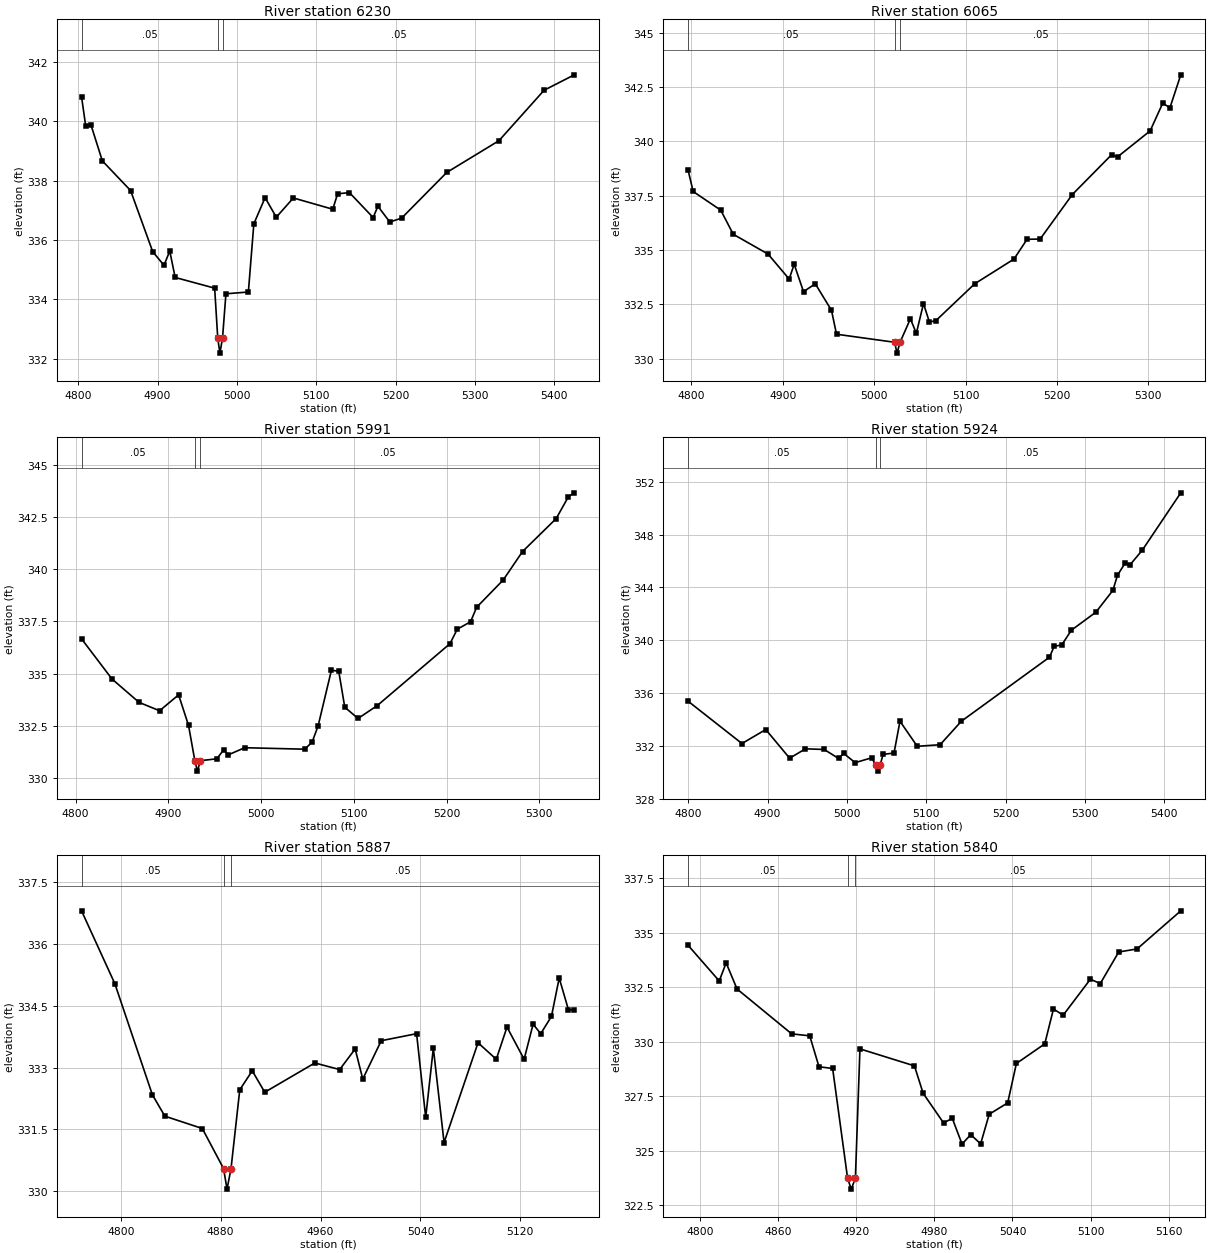
Type RM Length L Ch R = 1,6230,165,165,165
BEGIN DESCRIPTION:
UNT 183 IN BOCR 13.0
END DESCRIPTION:
XS GIS Cut Line= 3
      3734961.21     10626144.68      3734751.25     10626369.06
      3734491.77     10626545.73
#Sta/Elev= 30
  4804.2  340.83  4809.4  339.85  4816.2  339.87  4830.4  338.67  4866.0  337.67
  4893.9  335.61  4908.1  335.15  4915.4  335.63  4922.2  334.74  4972.0  334.38
  4975.9  332.69  4978.6  332.19  4981.9  332.69  4986.2  334.19  5014.5  334.25
  5021.4  336.55  5035.6  337.43  5049.7  336.77  5071.2  337.42  5120.9  337.04
  5127.0  337.56  5141.9  337.60  5171.8  336.76  5177.8  337.14  5192.8  336.61
  5207.7  336.74  5264.6  338.28  5330.4  339.35  5387.3  341.05  5425.4  341.57
#Mann=3,-1,0
  4804.2    0.05       0  4975.9    0.03       0  4981.9    0.05       0
Bank Sta=4975.9,4981.9
Exp/Cntr=0.3,0.1

Type RM Length L Ch R = 1,6065,74,74,74
BEGIN DESCRIPTION:
Mapping XS 489d70d4
END DESCRIPTION:
XS GIS Cut Line= 3
      3734874.72     10626109.28      3734704.39     10626186.30
      3734433.83     10626411.41
#Sta/Elev= 30
  4796.5  338.69  4802.1  337.69  4832.3  336.83  4846.0  335.72  4884.0  334.81
  4907.1  333.66  4912.6  334.34  4922.8  333.08  4935.7  333.44  4953.4  332.22
  4958.9  331.12  5022.4  330.75  5025.1  330.25  5028.4  330.75  5039.7  331.83
  5046.2  331.16  5054.0  332.53  5060.5  331.68  5067.7  331.75  5110.0  333.44
  5153.0  334.58  5167.3  335.49  5181.6  335.50  5216.8  337.55  5259.7  339.38
  5266.2  339.28  5301.9  340.48  5315.7  341.76  5323.5  341.54  5335.4  343.06
#Mann=3,-1,0
  4796.5    0.05       0  5022.4    0.03       0  5028.4    0.05       0
Bank Sta=5022.4,5028.4
Exp/Cntr=0.3,0.1

Type RM Length L Ch R = 1,5991,67,67,67
BEGIN DESCRIPTION:
Mapping XS d18a34b4
END DESCRIPTION:
XS GIS Cut Line= 3
      3734821.61     10626100.58      3734645.79     10626140.73
      3734374.56     10626363.14
#Sta/Elev= 30
  4806.5  336.66  4839.3  334.74  4868.5  333.62  4890.6  333.22  4911.1  333.98
  4921.8  332.52  4928.6  330.83  4931.4  330.33  4934.6  330.83  4952.2  330.92
  4959.6  331.34  4964.7  331.11  4982.3  331.45  5047.1  331.38  5055.0  331.72
  5061.5  332.50  5075.8  335.16  5083.7  335.11  5090.2  333.39  5104.5  332.85
  5125.3  333.47  5203.6  336.43  5211.4  337.12  5225.8  337.48  5232.3  338.17
  5261.0  339.48  5281.8  340.84  5318.1  342.42  5331.3  343.47  5337.6  343.65
#Mann=3,-1,0
  4806.5    0.05       0  4928.6    0.03       0  4934.6    0.05       0
Bank Sta=4928.6,4934.6
Exp/Cntr=0.3,0.1

Type RM Length L Ch R = 1,5924,37,37,37
BEGIN DESCRIPTION:
Mapping XS 2ea1c554
END DESCRIPTION:
XS GIS Cut Line= 4
      3734787.52     10626077.01      3734607.01     10626085.69
      3734484.27     10626184.47      3734240.96     10626328.84
#Sta/Elev= 30
  4799.7  335.39  4867.7  332.18  4897.7  333.24  4927.8  331.07  4947.8  331.78
  4971.4  331.73  4989.5  331.05  4996.0  331.43  5010.4  330.73  5031.2  331.10
  5036.1  330.59  5038.9  330.09  5042.1  330.59  5045.6  331.36  5059.4  331.46
  5066.9  333.87  5088.7  331.97  5117.5  332.09  5144.3  333.87  5255.4  338.72
  5261.2  339.53  5271.0  339.66  5282.9  340.76  5313.9  342.13  5335.3  343.78
  5341.1  344.92  5350.9  345.87  5356.7  345.70  5372.3  346.82  5420.9  351.17
#Mann=3,-1,0
  4799.7    0.05       0  5036.1    0.03       0  5042.1    0.05       0
Bank Sta=5036.1,5042.1
Exp/Cntr=0.3,0.1

Type RM Length L Ch R = 1,5887,47,47,47
BEGIN DESCRIPTION:
Mapping XS f3581dec
END DESCRIPTION:
XS GIS Cut Line= 3
      3734796.27     10626047.49      3734589.65     10626054.44
      3734436.89     10626163.80
#Sta/Elev= 30
  4768.6  336.80  4795.3  335.03  4825.3  332.34  4835.3  331.82  4865.3  331.52
  4882.3  330.55  4885.1  330.05  4888.3  330.55  4895.3  332.46  4905.3  332.92
  4915.3  332.40  4955.4  333.11  4975.3  332.95  4987.7  333.45  4993.8  332.72
  5008.6  333.65  5036.9  333.82  5044.2  331.79  5050.3  333.47  5058.9  331.18
  5086.1  333.60  5100.7  333.20  5109.3  333.98  5123.0  333.20  5130.2  334.05
  5136.3  333.82  5144.9  334.24  5151.1  335.17  5158.5  334.40  5163.2  334.40
#Mann=3,-1,0
  4768.6    0.05       0  4882.3    0.03       0  4888.3    0.05       0
Bank Sta=4882.3,4888.3
Exp/Cntr=0.3,0.1

Type RM Length L Ch R = 1,5840,150,150,150
BEGIN DESCRIPTION:
UNT 183 IN BOCR 12.0
END DESCRIPTION:
XS GIS Cut Line= 3
      3734735.47     10625957.22      3734561.87     10626012.77
      3734414.43     10626142.86
#Sta/Elev= 30
  4790.5  334.43  4814.5  332.79  4819.8  333.62  4828.2  332.42  4870.2  330.36
  4884.1  330.27  4891.2  328.85  4901.7  328.77  4913.2  323.73  4916.0  323.23
  4919.2  323.73  4922.7  329.67  4964.6  328.89  4971.3  327.63  4987.0  326.27
  4993.7  326.48  5001.2  325.30  5007.9  325.73  5015.5  325.31  5022.1  326.67
  5036.3  327.19  5043.0  329.00  5064.8  329.90  5071.5  331.50  5079.0  331.22
  5099.9  332.87  5107.5  332.67  5121.7  334.12  5135.8  334.26  5169.4  336.01
#Mann=3,-1,0
  4790.5    0.05       0  4913.2    0.03       0  4919.2    0.05       0
Bank Sta=4913.2,4919.2
Exp/Cntr=0.3,0.1

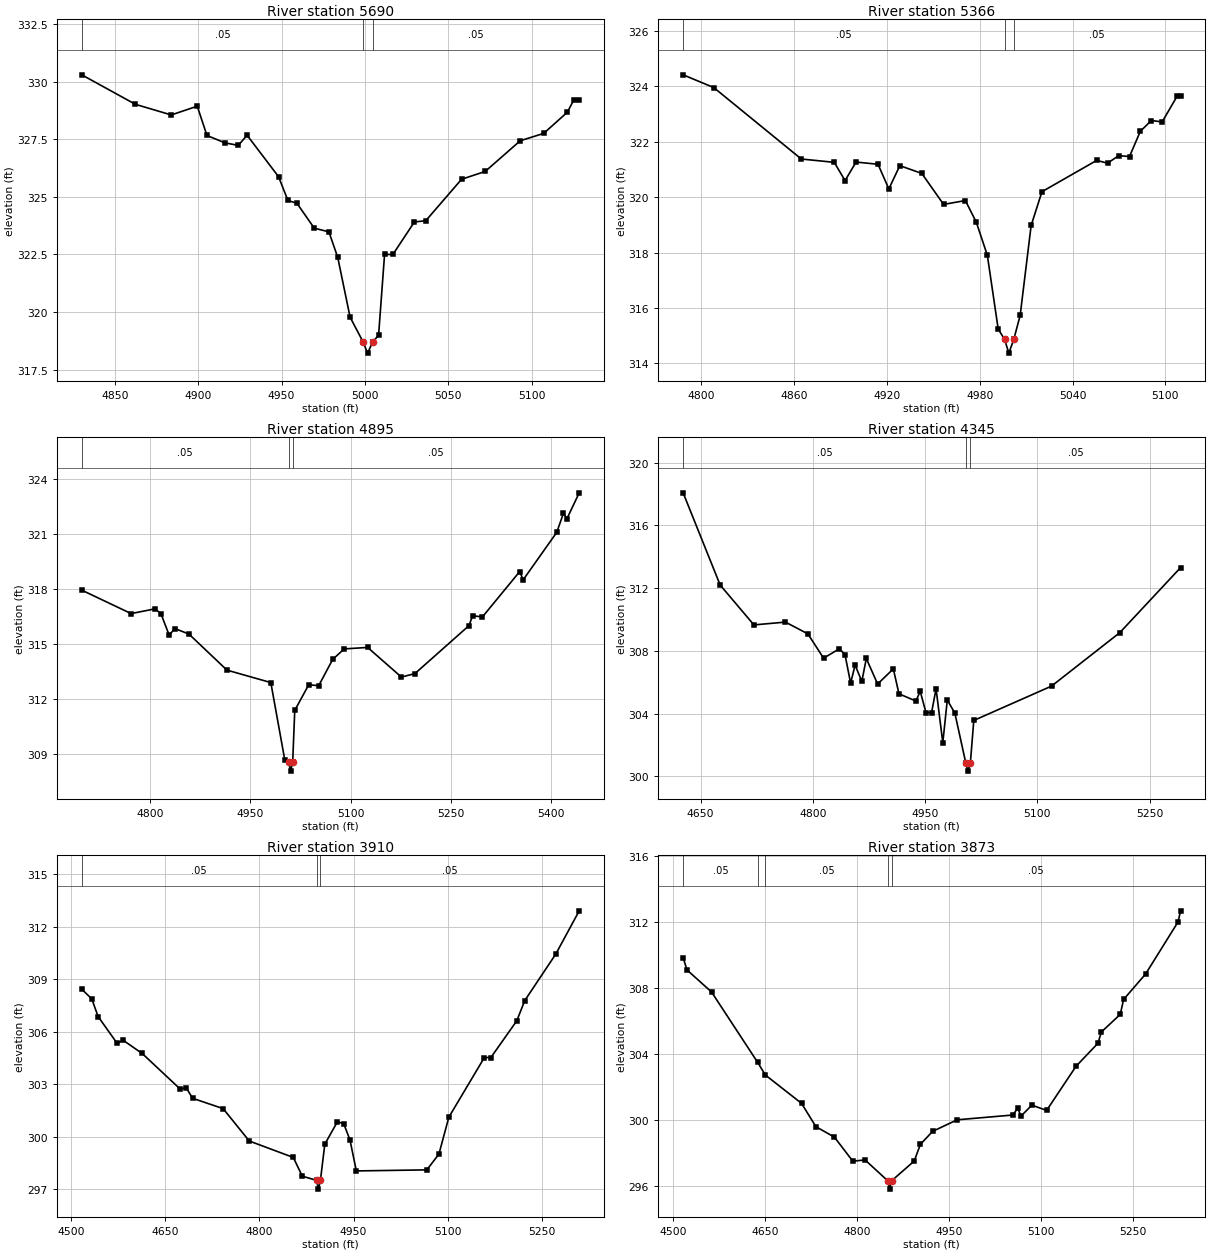
Type RM Length L Ch R = 1,5690,324,324,324
BEGIN DESCRIPTION:
UNT 183 IN BOCR 11.0
END DESCRIPTION:
XS GIS Cut Line= 3
      3734599.62     10625860.18      3734427.89     10625927.03
      3734349.60     10626010.20
#Sta/Elev= 30
  4830.1  330.29  4862.3  329.01  4883.8  328.55  4899.4  328.93  4905.2  327.66
  4916.0  327.34  4924.0  327.23  4929.3  327.67  4948.2  325.87  4953.8  324.84
  4959.2  324.72  4969.6  323.64  4978.4  323.48  4983.7  322.37  4991.1  319.78
  4998.8  318.72  5001.6  318.22  5004.8  318.72  5008.2  318.99  5011.8  322.50
  5016.8  322.50  5029.7  323.91  5036.5  323.96  5058.0  325.76  5072.2  326.10
  5093.2  327.43  5107.3  327.75  5121.5  328.67  5125.2  329.18  5128.6  329.18
#Mann=3,-1,0
  4830.1    0.05       0  4998.8    0.03       0  5004.8    0.05       0
Bank Sta=4998.8,5004.8
Exp/Cntr=0.3,0.1

Type RM Length L Ch R = 1,5366,471,471,471
BEGIN DESCRIPTION:
UNT 183 IN BOCR 10.0
END DESCRIPTION:
XS GIS Cut Line= 2
      3734317.08     10625599.57      3734091.42     10625828.71
#Sta/Elev= 30
  4788.2  324.42  4808.0  323.96  4864.6  321.38  4885.9  321.26  4892.9  320.60
  4900.0  321.27  4914.2  321.19  4921.2  320.30  4928.3  321.14  4942.5  320.86
  4956.6  319.74  4970.7  319.88  4977.8  319.09  4984.9  317.90  4991.9  315.24
  4996.0  314.87  4998.8  314.37  5002.0  314.87  5006.1  315.73  5013.2  318.98
  5020.2  320.20  5055.6  321.33  5062.6  321.23  5069.8  321.50  5076.8  321.47
  5083.8  322.38  5090.9  322.77  5097.9  322.72  5107.5  323.64  5109.8  323.64
#Mann=3,-1,0
  4788.2    0.05       0  4996.0    0.03       0  5002.0    0.05       0
Bank Sta=4996,5002
Exp/Cntr=0.3,0.1

Type RM Length L Ch R = 1,4895,550,550,550
BEGIN DESCRIPTION:
UNT 183 IN BOCR 9.0
END DESCRIPTION:
XS GIS Cut Line= 3
      3734025.44     10625212.82      3733801.89     10625536.21
      3733751.98     10625883.40
#Sta/Elev= 30
  4697.9  317.94  4771.7  316.66  4807.5  316.92  4816.3  316.65  4828.5  315.49
  4837.3  315.84  4858.2  315.54  4915.0  313.57  4980.6  312.89  5001.5  308.66
  5007.3  308.55  5010.1  308.05  5013.3  308.55  5016.4  311.37  5037.3  312.77
  5052.2  312.72  5073.2  314.16  5090.4  314.73  5125.4  314.81  5175.9  313.19
  5196.1  313.38  5276.9  316.00  5282.4  316.54  5297.1  316.48  5352.9  318.96
  5357.9  318.50  5408.2  321.10  5418.3  322.15  5423.4  321.84  5441.8  323.26
#Mann=3,-1,0
  4697.9    0.05       0  5007.3    0.03       0  5013.3    0.05       0
Bank Sta=5007.3,5013.3
Exp/Cntr=0.3,0.1

Type RM Length L Ch R = 1,4345,435,435,435
BEGIN DESCRIPTION:
UNT 183 IN BOCR 8.0
END DESCRIPTION:
XS GIS Cut Line= 3
      3733599.59     10625060.22      3733399.61     10625360.19
      3733449.62     10625660.23
#Sta/Elev= 30
  4626.7  318.07  4676.2  312.19  4721.3  309.65  4763.4  309.83  4793.4  309.08
  4814.4  307.53  4835.5  308.13  4843.0  307.76  4850.5  305.94  4856.5  307.09
  4865.5  306.05  4871.5  307.51  4886.6  305.88  4907.6  306.85  4915.1  305.26
  4937.6  304.80  4943.6  305.41  4951.2  304.06  4958.7  304.06  4964.7  305.58
  4973.7  302.14  4979.7  304.86  4989.8  304.03  5004.5  300.83  5007.2  300.33
  5010.5  300.83  5015.1  303.56  5119.0  305.75  5210.3  309.16  5291.4  313.30
#Mann=3,-1,0
  4626.7    0.05       0  5004.5    0.03       0  5010.5    0.05       0
Bank Sta=5004.5,5010.5
Exp/Cntr=0.3,0.1

Type RM Length L Ch R = 1,3910,37,37,37
BEGIN DESCRIPTION:
Mapping XS 233331b5
END DESCRIPTION:
XS GIS Cut Line= 3
      3733043.43     10625004.30      3733000.02     10625530.35
      3733067.46     10625786.28
#Sta/Elev= 30
  4517.0  308.42  4532.9  307.87  4543.0  306.86  4573.1  305.34  4583.1  305.50
  4613.2  304.75  4673.4  302.73  4683.5  302.79  4693.5  302.19  4742.2  301.60
  4783.8  299.75  4854.0  298.81  4868.3  297.74  4891.2  297.50  4893.9  297.00
  4897.2  297.50  4904.2  299.57  4924.3  300.85  4934.3  300.74  4944.3  299.81
  4954.4  298.04  5066.7  298.10  5086.0  299.00  5101.8  301.11  5158.4  304.52
  5168.8  304.52  5210.1  306.62  5222.7  307.77  5272.2  310.43  5309.5  312.90
#Mann=3,-1,0
  4517.0    0.05       0  4891.2    0.03       0  4897.2    0.05       0
Bank Sta=4891.2,4897.2
Exp/Cntr=0.3,0.1

Type RM Length L Ch R = 1,3873,58,58,58
BEGIN DESCRIPTION:
UNT 183 IN BOCR 7.0
END DESCRIPTION:
XS GIS Cut Line= 3
      3732979.19     10624993.92      3732967.04     10625509.52
      3733036.39     10625795.59
#Sta/Elev= 30
  4516.8  309.84  4523.1  309.09  4563.1  307.75  4638.3  303.47  4650.7  302.71
  4709.6  300.99  4733.1  299.57  4763.1  298.94  4793.1  297.48  4813.2  297.55
  4850.2  296.28  4852.9  295.78  4856.2  296.28  4893.2  297.49  4903.2  298.50
  4923.2  299.29  4963.2  299.99  5053.8  300.28  5061.8  300.70  5067.0  300.21
  5084.7  300.88  5108.8  300.56  5156.7  303.24  5192.4  304.64  5197.9  305.32
  5228.7  306.39  5234.2  307.30  5269.9  308.84  5322.9  312.01  5326.9  312.68
#Mann=5,-1,0
  4516.8    0.05       0  4638.3    0.08       0  4650.7    0.05       0
  4850.2    0.03       0  4856.2    0.05       0
Bank Sta=4850.2,4856.2
Exp/Cntr=0.3,0.1

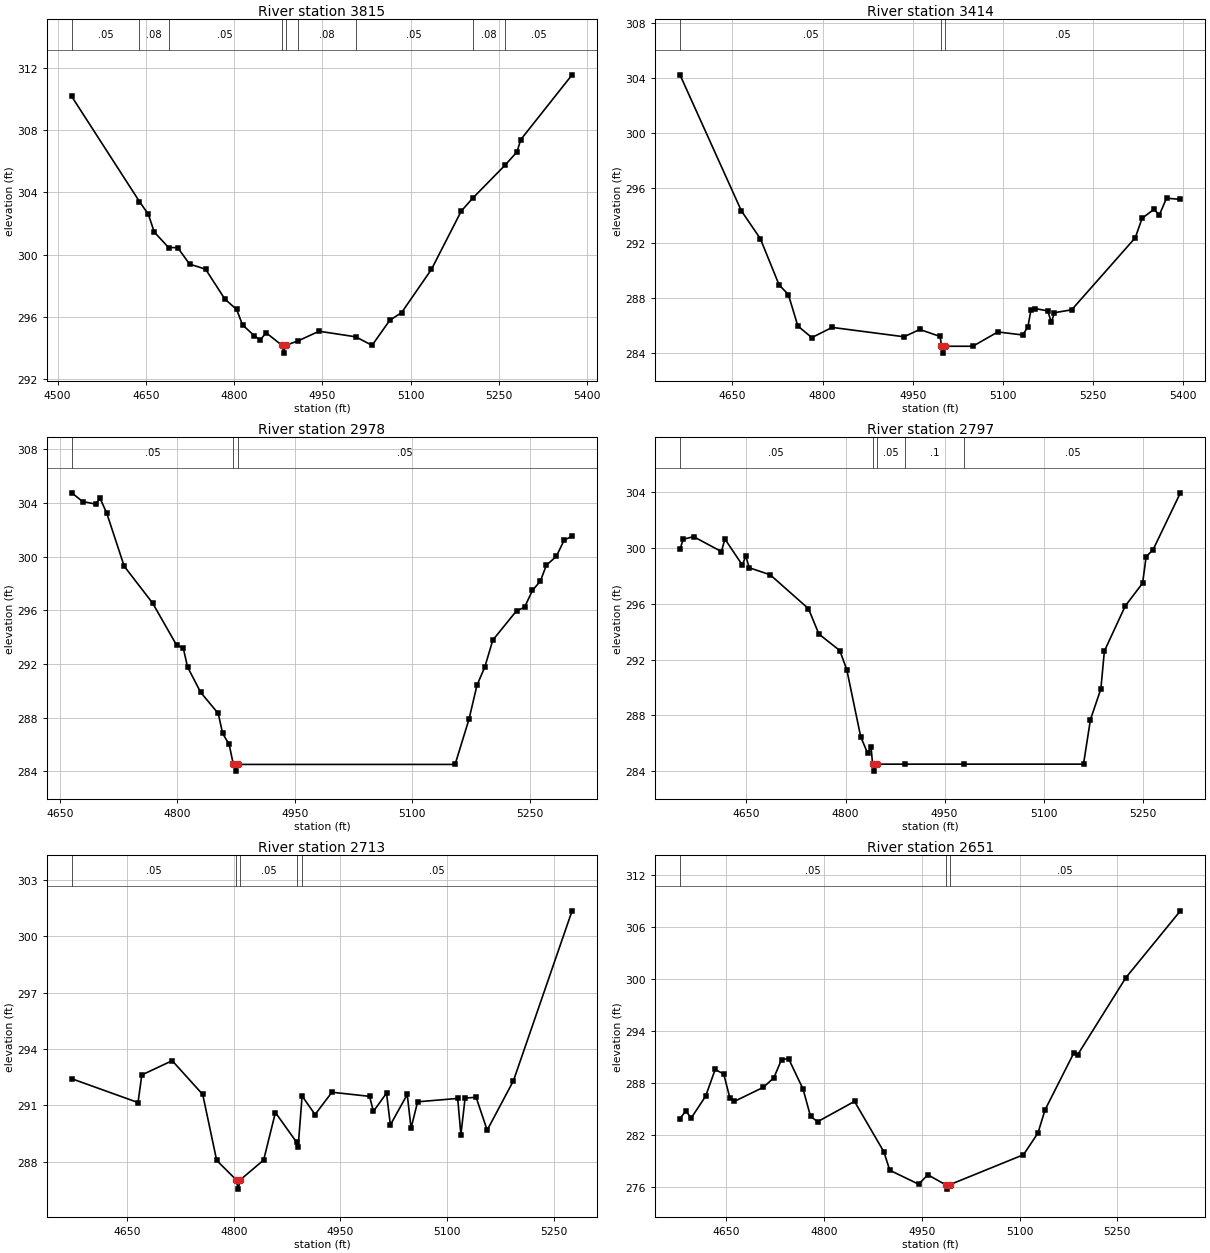
Type RM Length L Ch R = 1,3815,401,401,401
BEGIN DESCRIPTION:
Mapping XS 077b4545
END DESCRIPTION:
XS GIS Cut Line= 3
      3732934.05     10624980.00      3732911.48     10625528.61
      3732959.93     10625826.22
#Sta/Elev= 30
  4524.0  310.18  4639.2  303.41  4654.3  302.59  4664.3  301.45  4688.7  300.45
  4704.3  300.44  4724.4  299.38  4751.5  299.06  4784.4  297.13  4804.4  296.46
  4814.4  295.47  4834.4  294.77  4844.5  294.50  4854.5  294.96  4881.5  294.15
  4884.2  293.65  4887.5  294.15  4908.9  294.44  4944.5  295.06  5006.9  294.70
  5034.6  294.15  5064.6  295.76  5084.8  296.26  5135.5  299.04  5186.1  302.79
  5205.5  303.62  5260.6  305.75  5280.8  306.60  5287.4  307.40  5374.6  311.57
#Mann=9,-1,0
  4524.0    0.05       0  4639.2    0.08       0  4688.7    0.05       0
  4881.5    0.07       0  4887.5    0.05       0  4908.9    0.08       0
  5006.9    0.05       0  5205.5    0.08       0  5260.6    0.05       0
Bank Sta=4881.5,4887.5
Exp/Cntr=0.3,0.1

Type RM Length L Ch R = 1,3414,436,436,436
BEGIN DESCRIPTION:
UNT 183 IN BOCR 6.0
END DESCRIPTION:
XS GIS Cut Line= 2
      3732653.88     10624941.59      3732426.01     10625742.40
#Sta/Elev= 30
  4562.8  304.25  4664.9  294.36  4696.5  292.33  4727.7  288.97  4743.1  288.27
  4758.9  285.98  4782.1  285.14  4816.0  285.88  4935.6  285.20  4961.8  285.73
  4995.7  285.22  4997.9  284.51  5000.7  284.01  5003.9  284.51  5050.0  284.51
  5091.6  285.55  5133.2  285.33  5141.6  285.92  5146.8  287.15  5154.0  287.25
  5174.8  287.08  5180.6  286.25  5185.8  286.95  5214.5  287.16  5320.3  292.40
  5331.7  293.82  5351.5  294.47  5360.3  294.05  5372.3  295.28  5395.4  295.19
#Mann=3,-1,0
  4562.8    0.05       0  4997.9    0.03       0  5003.9    0.05       0
Bank Sta=4997.9,5003.9
Exp/Cntr=0.3,0.1

Type RM Length L Ch R = 1,2978,181,181,181
BEGIN DESCRIPTION:
UNT 183 IN BOCR 5.0
END DESCRIPTION:
XS GIS Cut Line= 3
      3732299.61     10624910.19      3732149.61     10625210.19
      3732099.62     10625510.14
#Sta/Elev= 30
  4664.8  304.76  4678.8  304.11  4695.5  303.92  4701.1  304.34  4709.5  303.26
  4731.9  299.29  4768.2  296.54  4799.0  293.39  4807.3  293.21  4812.9  291.77
  4829.7  289.88  4852.1  288.31  4857.7  286.82  4866.0  286.01  4871.4  284.51
  4874.2  284.01  4877.4  284.51  5154.8  284.51  5172.6  287.89  5182.7  290.40
  5192.8  291.78  5203.0  293.78  5233.4  295.97  5243.5  296.22  5253.7  297.49
  5263.8  298.18  5271.4  299.36  5284.1  300.02  5294.2  301.23  5304.3  301.53
#Mann=3,-1,0
  4664.8    0.05       0  4871.4   0.033       0  4877.4    0.05       0
Bank Sta=4871.4,4877.4
Exp/Cntr=0.3,0.1

Type RM Length L Ch R = 1,2797,84,84,84
BEGIN DESCRIPTION:
Mapping XS 0f413687
END DESCRIPTION:
XS GIS Cut Line= 2
      3731833.12     10624820.67      3732072.69     10625539.40
#Sta/Elev= 30
  4549.4  299.89  4554.1  300.62  4570.0  300.81  4612.1  299.74  4617.4  300.64
  4643.7  298.78  4649.0  299.41  4654.3  298.58  4685.9  298.08  4743.9  295.65
  4759.7  293.83  4791.3  292.65  4801.9  291.28  4823.0  286.47  4833.5  285.29
  4838.7  285.71  4841.0  284.51  4843.8  284.01  4847.0  284.51  4889.9  284.51
  4980.1  284.51  5160.3  284.51  5170.8  287.70  5186.6  289.90  5191.9  292.61
  5223.5  295.84  5249.8  297.48  5255.1  299.37  5265.7  299.88  5307.0  303.95
#Mann=5,-1,0
  4549.4    0.05       0  4841.0    0.03       0  4847.0    0.05       0
  4889.9     0.1       0  4980.1    0.05       0
Bank Sta=4841,4847
Exp/Cntr=0.3,0.1

Type RM Length L Ch R = 1,2713,62,62,62
BEGIN DESCRIPTION:
Mapping XS 6986f3e0
END DESCRIPTION:
XS GIS Cut Line= 4
      3731741.96     10624877.94      3731842.43     10625146.84
      3731939.91     10625378.47      3732024.83     10625519.52
#Sta/Elev= 30
  4572.4  292.42  4665.6  291.15  4670.9  292.62  4713.6  293.38  4756.5  291.58
  4776.1  288.07  4803.4  287.04  4806.2  286.54  4809.4  287.04  4842.1  288.09
  4858.6  290.62  4888.5  289.03  4890.5  288.76  4896.1  291.50  4914.3  290.51
  4938.0  291.70  4990.9  291.48  4996.3  290.68  5014.7  291.65  5020.1  289.96
  5043.8  291.58  5049.2  289.79  5058.4  291.19  5114.7  291.37  5119.2  289.44
  5125.1  291.39  5140.6  291.43  5156.1  289.68  5193.0  292.31  5275.4  301.36
#Mann=5,-1,0
  4572.4    0.05       0  4803.4    0.03       0  4809.4    0.05       0
  4888.5     0.1       0  4896.1    0.05       0
Bank Sta=4803.4,4809.4
Exp/Cntr=0.3,0.1

Type RM Length L Ch R = 1,2651,180,180,180
BEGIN DESCRIPTION:
Mapping XS 9e82fd77
END DESCRIPTION:
XS GIS Cut Line= 2
      3731645.61     10624922.22      3731997.20     10625604.57
#Sta/Elev= 30
  4579.2  283.93  4588.2  284.82  4596.3  283.98  4618.5  286.51  4633.2  289.59
  4646.3  289.05  4655.7  286.30  4662.8  285.92  4707.1  287.53  4723.2  288.63
  4734.9  290.72  4745.7  290.84  4768.0  287.32  4779.4  284.20  4790.2  283.57
  4846.9  285.91  4891.9  280.11  4901.0  277.98  4945.3  276.38  4959.4  277.46
  4986.7  276.31  4989.4  275.81  4992.7  276.31  5106.1  279.77  5128.3  282.27
  5139.2  284.94  5183.5  291.51  5189.2  291.28  5263.1  300.15  5346.8  307.85
#Mann=3,-1,0
  4579.2    0.05       0  4986.7    0.03       0  4992.7    0.05       0
Bank Sta=4986.7,4992.7
Exp/Cntr=0.3,0.1

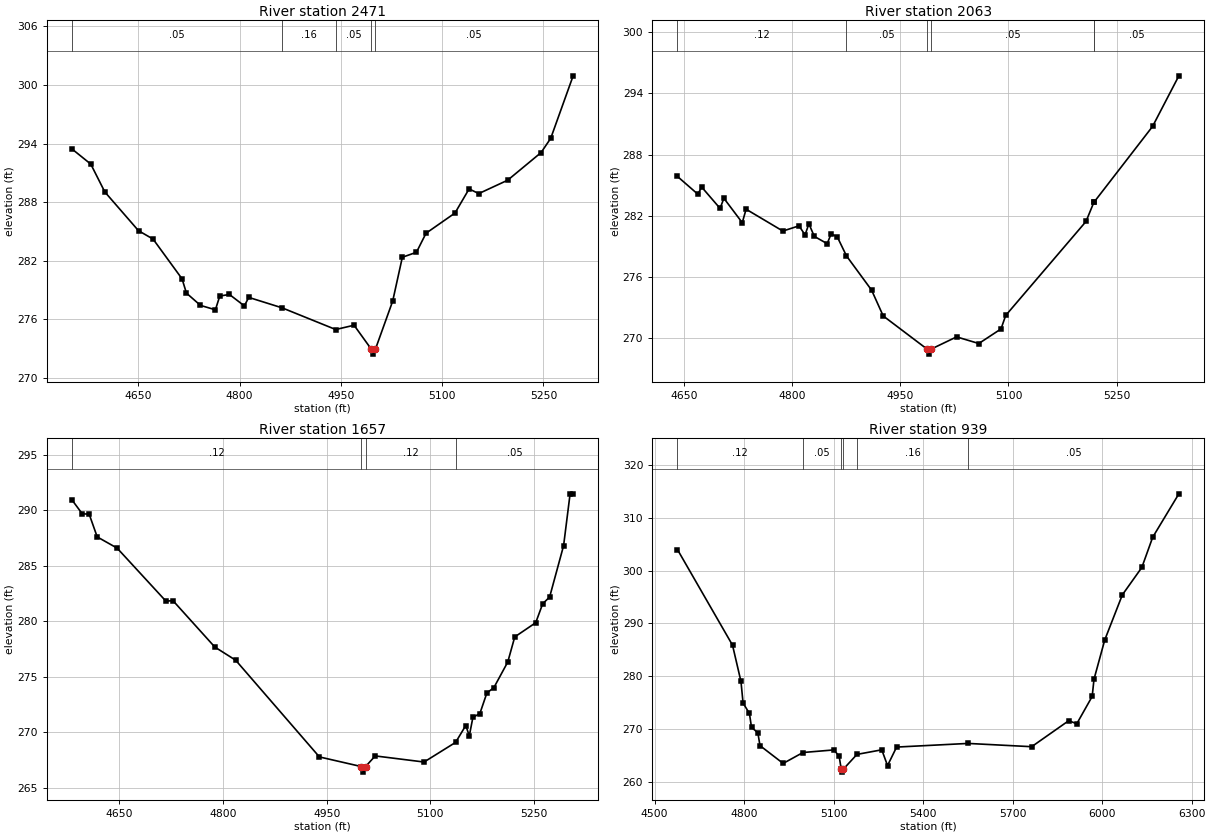
Type RM Length L Ch R = 1,2471,408,408,408
BEGIN DESCRIPTION:
Mapping XS 428d7232
END DESCRIPTION:
XS GIS Cut Line= 2
      3731395.63     10625044.65      3731874.67     10625612.21
#Sta/Elev= 30
  4551.3  293.47  4579.5  291.90  4600.3  289.05  4650.2  285.08  4671.8  284.22
  4714.7  280.15  4721.2  278.69  4742.0  277.43  4764.1  276.98  4770.6  278.39
  4784.9  278.55  4807.0  277.38  4813.5  278.25  4862.9  277.18  4942.3  274.96
  4969.5  275.40  4995.1  272.94  4997.9  272.44  5001.1  272.94  5026.7  277.87
  5041.0  282.36  5061.9  282.87  5076.1  284.82  5119.0  286.89  5139.9  289.36
  5154.2  288.88  5197.0  290.25  5246.5  293.08  5260.8  294.54  5294.0  300.94
#Mann=5,-1,0
  4551.3    0.05       0  4862.9    0.16       0  4942.3    0.05       0
  4995.1    0.03       0  5001.1    0.05       0
Bank Sta=4995.1,5001.1
Exp/Cntr=0.3,0.1

Type RM Length L Ch R = 1,2063,406,406,406
BEGIN DESCRIPTION:
Mapping XS afe9a7a6
END DESCRIPTION:
XS GIS Cut Line= 2
      3731150.85     10625544.64      3731805.83     10625778.56
#Sta/Elev= 30
  4640.9  285.87  4669.2  284.13  4674.5  284.83  4700.0  282.74  4705.3  283.73
  4730.8  281.34  4736.1  282.66  4787.1  280.52  4809.5  281.03  4817.9  280.14
  4823.2  281.23  4830.7  280.00  4848.6  279.28  4854.0  280.24  4862.6  279.95
  4875.3  278.09  4910.2  274.73  4926.3  272.20  4987.0  268.96  4989.8  268.46
  4993.0  268.96  5028.1  270.15  5058.9  269.50  5089.7  270.93  5096.2  272.25
  5207.6  281.46  5218.4  283.32  5218.5  283.33  5299.9  290.77  5336.4  295.73
#Mann=6,-1,0
  4640.9    0.12       0  4875.3    0.05       0  4987.0    0.03       0
  4993.0    0.05       0  5218.4    0.16       0  5218.5    0.05       0
Bank Sta=4987,4993
Exp/Cntr=0.3,0.1

Type RM Length L Ch R = 1,1657,718,718,718
BEGIN DESCRIPTION:
Mapping XS f20d8286
END DESCRIPTION:
XS GIS Cut Line= 2
      3730994.57     10625950.89      3731713.29     10626044.63
#Sta/Elev= 30
  4581.5  290.96  4596.7  289.68  4606.7  289.65  4618.3  287.60  4647.1  286.59
  4717.7  281.81  4727.8  281.86  4788.3  277.68  4818.5  276.49  4939.5  267.78
  5000.2  266.91  5003.0  266.41  5006.2  266.91  5020.2  267.87  5090.8  267.32
  5136.4  269.09  5151.1  270.61  5156.2  269.68  5161.4  271.34  5171.5  271.69
  5181.6  273.54  5191.7  274.02  5211.8  276.33  5221.9  278.59  5252.2  279.87
  5262.3  281.58  5272.3  282.18  5292.5  286.81  5301.9  291.48  5306.3  291.48
#Mann=4,-1,0
  4581.5    0.12       0  5000.2    0.07       0  5006.2    0.12       0
  5136.4    0.05       0
Bank Sta=5000.2,5006.2
Exp/Cntr=0.3,0.1

Type RM Length L Ch R = 1,939,0,0,0
BEGIN DESCRIPTION:
UNT 183 IN BOCR 1.0
END DESCRIPTION:
XS GIS Cut Line= 4
      3730718.56     10626060.29      3731088.33     10626440.47
      3731557.08     10626518.59      3731921.68     10625950.85
#Sta/Elev= 30
  4576.9  303.97  4761.4  285.85  4789.7  278.97  4796.8  274.87  4818.0  272.91
  4825.1  270.26  4846.3  269.25  4853.4  266.81  4931.1  263.43  4997.6  265.50
  5100.9  265.99  5118.7  264.81  5125.8  262.28  5128.6  261.78  5131.8  262.28
  5178.4  265.14  5261.6  266.01  5280.9  263.02  5311.3  266.53  5550.8  267.22
  5763.9  266.60  5888.1  271.53  5915.1  270.95  5966.7  276.13  5972.8  279.39
  6008.9  286.85  6067.8  295.39  6133.1  300.58  6169.5  306.31  6257.2  314.54
#Mann=6,-1,0
  4576.9    0.12       0  4997.6    0.05       0  5125.8    0.04       0
  5131.8    0.05       0  5178.4    0.16       0  5550.8    0.05       0
Bank Sta=5125.8,5131.8
Exp/Cntr=0.3,0.1

Chan Stop Cuts=-1