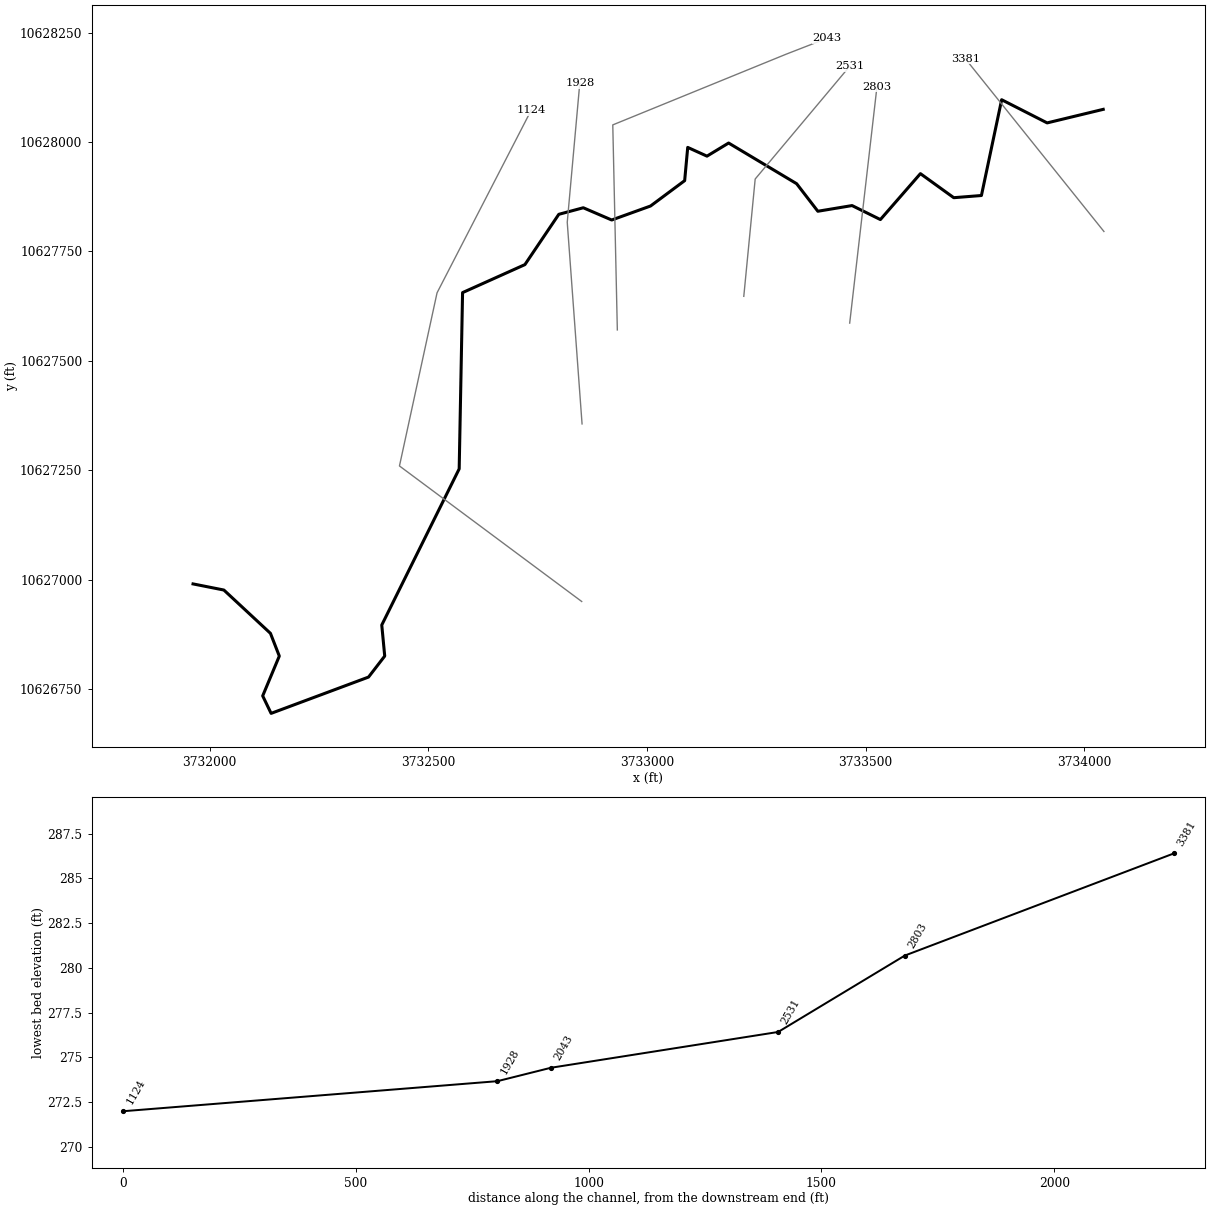
--- UNT 184 IN BOCR.prj (project) ---

Proj Title=UNT 184 IN BOCR Base Level Engineering
Current Plan=p01
Default Exp/Contr=0.3,0.1
English Units
Geom File=g01
Flow File=f01
Plan File=p01
BEGIN DESCRIPTION:
UNT 184 IN BOCR
END DESCRIPTION:

--- UNT 184 IN BOCR.p01 (plan) ---

Plan Title=Multiple Run
Short Identifier=Multiple
Geom File=g01
Flow File=f01
Subcritical Flow
K Sum by GR= 0
Std Step Tol= 0.01
Critical Tol= 0.01
Num of Std Step Trials= 20
Max Error Tol= 0.3
Flow Tol Ratio= 0.001
Split Flow NTrial= 30
Split Flow Tol= 0.02
Split Flow Ratio= 0.02
Log Output Level= 0
Friction Slope Method= 1
Unsteady Friction Slope Method= 2
Unsteady Bridges Friction Slope Method= 1
Parabolic Critical Depth
Global Vel Dist=  1 , 1 , 1
Global Log Level= 0
CheckData=True
Encroach Param= -1, 0, 0, 0
BEGIN DESCRIPTION:
Multiple Run
END DESCRIPTION:

--- UNT 184 IN BOCR.f01 (steady flow) ---

Flow Title=Multiple
Number of Profiles=7
Profile Names=10-year,25-year,50-year,1pct_min,100-year,1pct_plu,500-year
River Rch & RM= UNT 184 IN BOCR,Reach-1,3381
     327     424     501     436     589     797     817
Boundary for River Rch & Prof#=UNT 184 IN BOCR,Reach-1,1
Up Type=0
Dn Type=3
Dn Slope=0.005
Boundary for River Rch & Prof#=UNT 184 IN BOCR,Reach-1,2
Up Type=0
Dn Type=3
Dn Slope=0.005
Boundary for River Rch & Prof#=UNT 184 IN BOCR,Reach-1,3
Up Type=0
Dn Type=3
Dn Slope=0.005
Boundary for River Rch & Prof#=UNT 184 IN BOCR,Reach-1,4
Up Type=0
Dn Type=3
Dn Slope=0.005
Boundary for River Rch & Prof#=UNT 184 IN BOCR,Reach-1,5
Up Type=0
Dn Type=3
Dn Slope=0.005
Boundary for River Rch & Prof#=UNT 184 IN BOCR,Reach-1,6
Up Type=0
Dn Type=3
Dn Slope=0.005
Boundary for River Rch & Prof#=UNT 184 IN BOCR,Reach-1,7
Up Type=0
Dn Type=3
Dn Slope=0.005

--- UNT 184 IN BOCR.g01 (geometry) ---

Geom Title=Existing Conditions

River Reach=UNT 184 IN BOCR,Reach-1
Reach XY= 30
      3734043.00     10628075.00      3733914.75     10628044.00
      3733810.75     10628097.00      3733764.50     10627878.00
      3733701.25     10627873.00      3733625.00     10627928.00
      3733533.50     10627823.00      3733468.75     10627855.00
      3733390.50     10627842.00      3733342.00     10627905.00
      3733186.50     10627998.00      3733137.00     10627968.00
      3733093.00     10627988.00      3733086.00     10627912.00
      3733008.00     10627854.00      3732919.25     10627822.00
      3732854.25     10627850.00      3732798.25     10627835.00
      3732720.75     10627720.00      3732578.25     10627656.00
      3732570.50     10627253.00      3732393.50     10626896.00
      3732400.25     10626825.00      3732363.25     10626777.00
      3732140.50     10626694.00      3732121.25     10626734.00
      3732159.25     10626825.00      3732139.00     10626877.00
      3732032.50     10626976.00      3731962.00     10626990.00

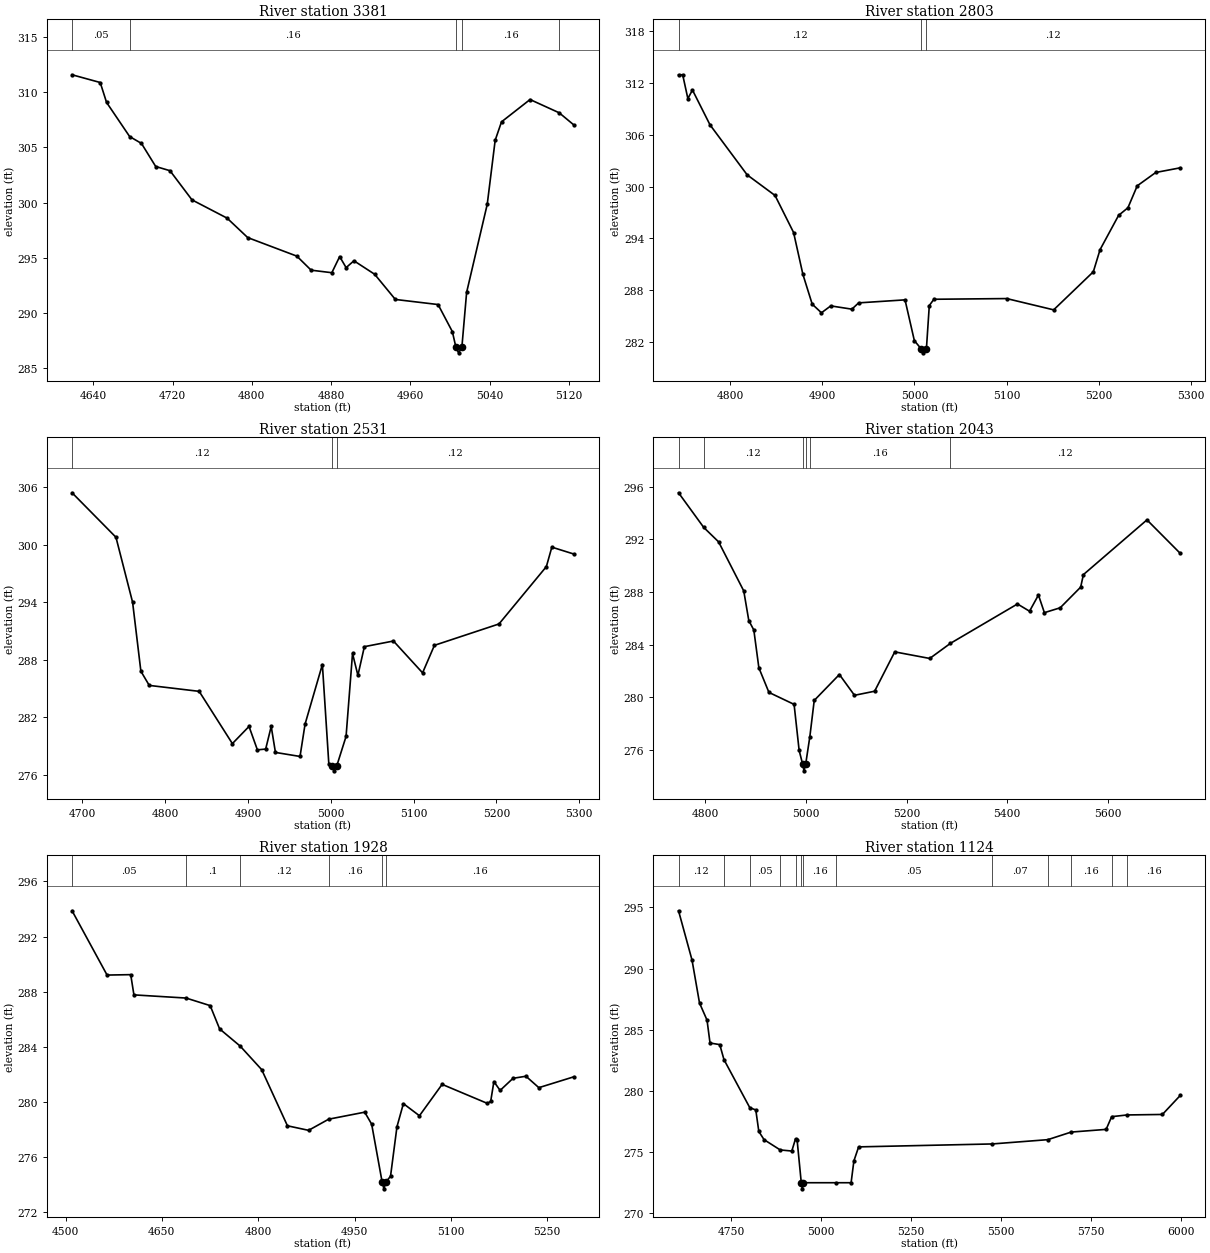
Type RM Length L Ch R = 1,3381,578,578,578
BEGIN DESCRIPTION:
UNT 184 IN BOCR 3.0
END DESCRIPTION:
XS GIS Cut Line= 2
      3734044.57     10627795.77      3733727.76     10628190.70
#Sta/Elev= 30
  4618.6  311.56  4647.0  310.86  4653.4  309.06  4676.7  305.97  4688.6  305.35
  4703.0  303.26  4717.4  302.88  4739.6  300.24  4775.0  298.59  4795.8  296.83
  4845.4  295.15  4859.8  293.88  4880.7  293.65  4888.6  295.11  4895.1  294.11
  4903.0  294.73  4923.9  293.51  4944.8  291.23  4987.9  290.77  5002.3  288.32
  5005.9  286.90  5008.6  286.40  5011.9  286.90  5016.7  291.87  5037.5  299.84
  5045.5  305.63  5051.9  307.30  5080.7  309.32  5110.1  308.12  5124.9  307.02
#Mann=5,-1,0
  4618.6    0.05       0  4676.7    0.16       0  5005.9    0.07       0
  5011.9    0.16       0  5110.1    0.12       0
Bank Sta=5005.9,5011.9
Exp/Cntr=0.3,0.1

Type RM Length L Ch R = 1,2803,272,272,272
BEGIN DESCRIPTION:
UNT 184 IN BOCR 2.0
END DESCRIPTION:
XS GIS Cut Line= 2
      3733463.32     10627586.29      3733525.67     10628126.60
#Sta/Elev= 30
  4744.3  312.97  4748.8  312.97  4754.4  310.21  4759.4  311.20  4778.4  307.16
  4818.7  301.35  4848.9  298.96  4869.0  294.66  4879.1  289.80  4889.2  286.34
  4899.2  285.34  4909.3  286.14  4932.2  285.76  4939.5  286.49  4989.8  286.84
  4999.9  282.11  5007.0  281.19  5009.7  280.69  5013.0  281.19  5016.1  286.18
  5021.1  286.91  5100.0  286.99  5150.9  285.68  5193.9  290.10  5201.2  292.67
  5221.3  296.65  5231.4  297.53  5241.5  300.08  5261.6  301.63  5288.2  302.17
#Mann=3,-1,0
  4744.3    0.12       0  5007.0    0.07       0  5013.0    0.12       0
Bank Sta=5007,5013
Exp/Cntr=0.3,0.1

Type RM Length L Ch R = 1,2531,488,488,488
BEGIN DESCRIPTION:
Mapping XS 29a529ec
END DESCRIPTION:
XS GIS Cut Line= 3
      3733221.20     10627647.45      3733247.25     10627915.71
      3733463.42     10628173.56
#Sta/Elev= 30
  4687.5  305.42  4740.5  300.78  4760.6  294.00  4770.6  286.81  4780.7  285.33
  4841.0  284.71  4881.1  279.26  4901.2  281.05  4911.3  278.61  4921.3  278.69
  4928.0  281.05  4933.1  278.34  4962.8  277.92  4968.9  281.30  4989.8  287.51
  4997.6  277.11  5001.1  276.92  5003.8  276.42  5007.1  276.92  5018.4  280.01
  5026.2  288.66  5032.7  286.38  5040.5  289.37  5075.6  289.96  5110.8  286.64
  5125.1  289.51  5203.1  291.74  5260.3  297.72  5266.9  299.75  5293.5  299.03
#Mann=3,-1,0
  4687.5    0.12       0  5001.1    0.07       0  5007.1    0.12       0
Bank Sta=5001.1,5007.1
Exp/Cntr=0.3,0.1

Type RM Length L Ch R = 1,2043,115,115,115
BEGIN DESCRIPTION:
UNT 184 IN BOCR 1.0
END DESCRIPTION:
XS GIS Cut Line= 4
      3732932.08     10627570.66      3732921.66     10628039.43
      3733317.49     10628200.89      3733411.27     10628237.35
#Sta/Elev= 30
  4746.9  295.55  4796.9  292.92  4826.5  291.82  4876.5  288.09  4886.5  285.84
  4896.5  285.12  4906.5  282.25  4926.5  280.38  4976.5  279.47  4986.5  275.98
  4993.5  274.92  4996.2  274.42  4999.5  274.92  5007.8  277.02  5016.5  279.77
  5066.5  281.74  5096.5  280.16  5136.5  280.47  5176.5  283.46  5246.0  282.96
  5287.2  284.11  5420.3  287.10  5444.3  286.55  5462.0  287.78  5473.8  286.44
  5505.2  286.81  5545.9  288.38  5551.3  289.33  5677.6  293.49  5743.9  290.94
#Mann=6,-1,0
  4746.9    0.05       0  4796.9    0.12       0  4993.5    0.07       0
  4999.5    0.12       0  5007.8    0.16       0  5287.2    0.12       0
Bank Sta=4993.5,4999.5
Exp/Cntr=0.3,0.1

Type RM Length L Ch R = 1,1928,804,804,804
BEGIN DESCRIPTION:
Mapping XS 8423f86d
END DESCRIPTION:
XS GIS Cut Line= 3
      3732851.42     10627355.81      3732817.56     10627816.75
      3732846.21     10628134.48
#Sta/Elev= 30
  4510.2  293.87  4564.7  289.20  4601.5  289.23  4606.5  287.76  4687.7  287.53
  4725.2  286.98  4739.9  285.29  4771.9  284.04  4805.4  282.33  4845.5  278.25
  4878.4  277.92  4909.7  278.73  4965.8  279.24  4976.6  278.37  4992.9  274.17
  4995.7  273.67  4998.9  274.17  5006.0  274.59  5016.0  278.18  5026.0  279.86
  5051.0  278.98  5086.3  281.26  5156.6  279.88  5161.9  280.02  5166.9  281.46
  5176.6  280.82  5196.7  281.70  5216.8  281.85  5236.9  281.02  5291.4  281.81
#Mann=6,-1,0
  4510.2    0.05       0  4687.7     0.1       0  4771.9    0.12       0
  4909.7    0.16       0  4992.9    0.07       0  4998.9    0.16       0
Bank Sta=4992.9,4998.9
Exp/Cntr=0.3,0.1

Type RM Length L Ch R = 1,1124,0,0,0
BEGIN DESCRIPTION:
Mapping XS f7b28bda
END DESCRIPTION:
XS GIS Cut Line= 4
      3732850.60     10626949.80      3732433.95     10627259.68
      3732519.89     10627655.52      3732735.34     10628073.44
#Sta/Elev= 30
  4604.3  294.72  4641.8  290.69  4662.6  287.18  4683.5  285.78  4691.8  283.91
  4718.9  283.78  4730.6  282.55  4802.4  278.62  4819.0  278.44  4827.4  276.68
  4842.0  276.01  4886.9  275.17  4919.1  275.08  4929.4  276.08  4933.7  276.02
  4945.4  272.49  4948.1  271.99  4951.4  272.49  5043.1  272.49  5083.9  272.49
  5091.6  274.27  5104.8  275.42  5476.2  275.66  5630.5  276.01  5695.5  276.63
  5792.6  276.85  5808.0  277.89  5851.1  278.03  5949.0  278.07  5998.8  279.63
#Mann=13,-1,0
  4604.3    0.12       0  4730.6    0.16       0  4802.4    0.05       0
  4886.9    0.12       0  4929.4    0.16       0  4945.4    0.07       0
  4951.4    0.16       0  5043.1    0.05       0  5476.2    0.07       0
  5630.5    0.05       0  5695.5    0.16       0  5808.0    0.12       0
  5851.1    0.16       0
Bank Sta=4945.4,4951.4
Exp/Cntr=0.3,0.1

Chan Stop Cuts=-1