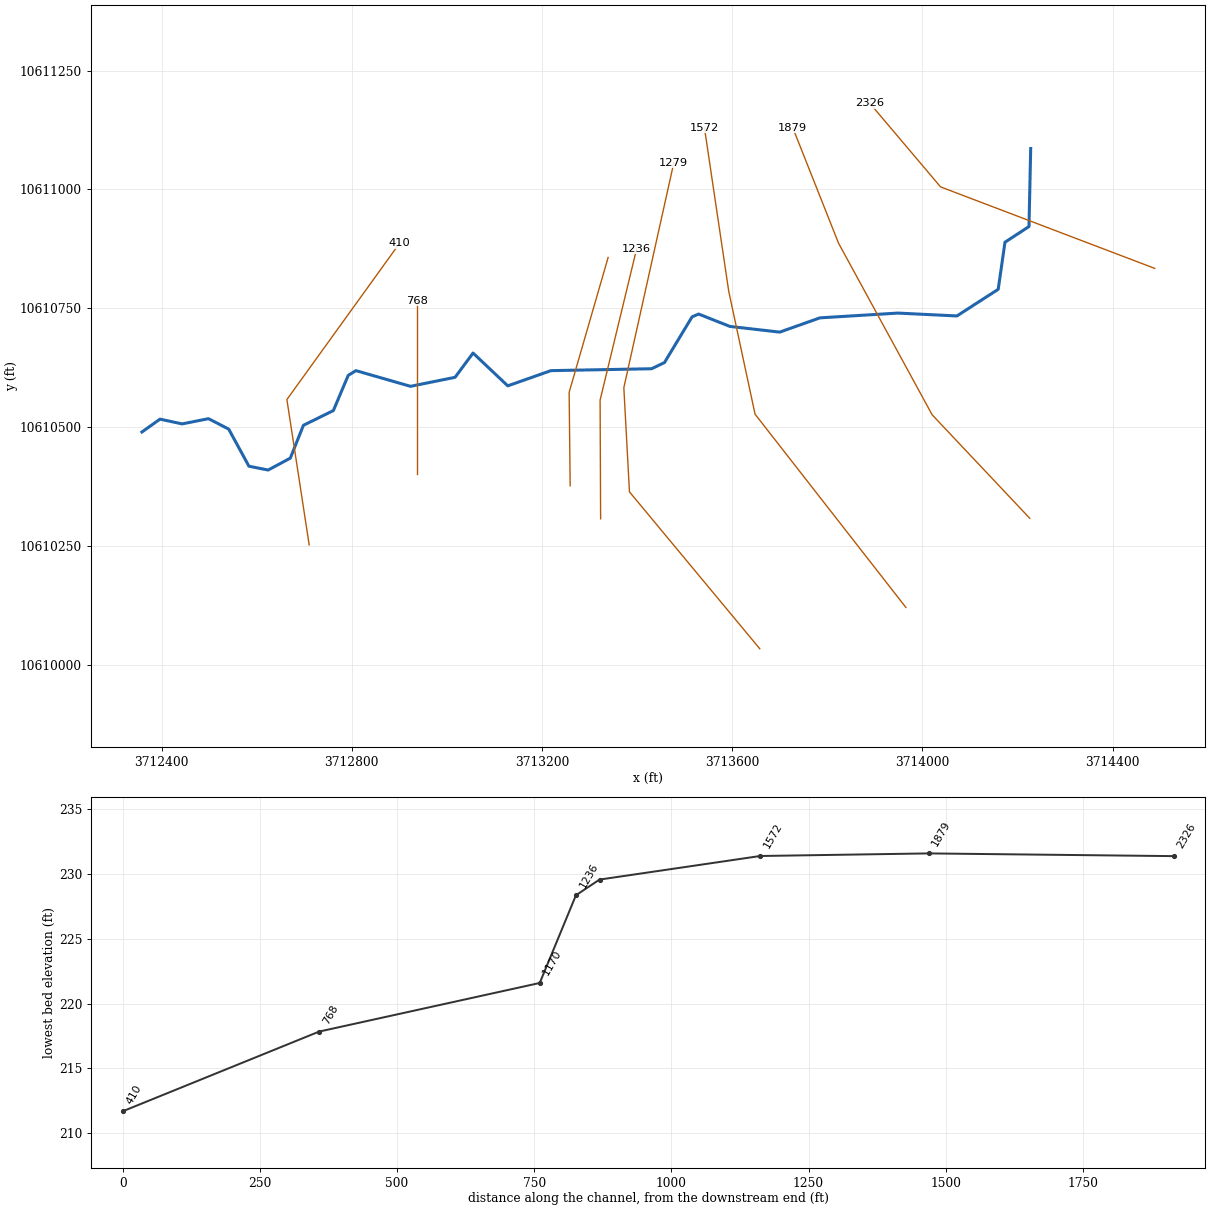
--- UNT 185 IN BOCR.prj (project) ---

Proj Title=UNT 185 IN BOCR Base Level Engineering
Current Plan=p01
Default Exp/Contr=0.3,0.1
English Units
Geom File=g01
Flow File=f01
Plan File=p01
Y Axis Title=Elevation
X Axis Title(PF)=Main Channel Distance
X Axis Title(XS)=Station
BEGIN DESCRIPTION:
UNT 185 IN BOCR
END DESCRIPTION:
DSS Export Rating Curves= 0
DSS Export Rating Curve Sorted= 0
DSS Export Volume Flow Curves= 0
DXF OffsetX= 0
DXF OffsetY= 0
DXF ScaleX= 1
DXF ScaleY= 10

--- UNT 185 IN BOCR.p01 (plan) ---

Plan Title=Multiple Run
Short Identifier=Multiple
Geom File=g01
Flow File=f01
Subcritical Flow
K Sum by GR= 0
Std Step Tol= 0.01
Critical Tol= 0.01
Num of Std Step Trials= 20
Max Error Tol= 0.3
Flow Tol Ratio= 0.001
Split Flow NTrial= 30
Split Flow Tol= 0.02
Split Flow Ratio= 0.02
Log Output Level= 0
Friction Slope Method= 1
Unsteady Friction Slope Method= 2
Unsteady Bridges Friction Slope Method= 1
Parabolic Critical Depth
Global Vel Dist=  1 , 1 , 1
Global Log Level= 0
CheckData=True
Encroach Param= -1, 0, 0, 0
BEGIN DESCRIPTION:
Multiple Run
END DESCRIPTION:

--- UNT 185 IN BOCR.f01 (steady flow) ---

Flow Title=Multiple
Program Version=4.10
Number of Profiles= 7
Profile Names=10-year,25-year,50-year,1pct_min,100-year,1pct_plu,500-year
River Rch & RM=UNT 185 IN BOCR,Reach-1         ,2326
     195     246     285     244     329     446     441
Boundary for River Rch & Prof#=UNT 185 IN BOCR,Reach-1         , 1
Up Type= 0
Dn Type= 3
Dn Slope=0.005
Boundary for River Rch & Prof#=UNT 185 IN BOCR,Reach-1         , 2
Up Type= 0
Dn Type= 3
Dn Slope=0.005
Boundary for River Rch & Prof#=UNT 185 IN BOCR,Reach-1         , 3
Up Type= 0
Dn Type= 3
Dn Slope=0.005
Boundary for River Rch & Prof#=UNT 185 IN BOCR,Reach-1         , 4
Up Type= 0
Dn Type= 3
Dn Slope=0.005
Boundary for River Rch & Prof#=UNT 185 IN BOCR,Reach-1         , 5
Up Type= 0
Dn Type= 3
Dn Slope=0.005
Boundary for River Rch & Prof#=UNT 185 IN BOCR,Reach-1         , 6
Up Type= 0
Dn Type= 3
Dn Slope=0.005
Boundary for River Rch & Prof#=UNT 185 IN BOCR,Reach-1         , 7
Up Type= 0
Dn Type= 3
Dn Slope=0.005
DSS Import GetInterval= 0
DSS Import GetPeak= 0
DSS Import FillOption= 0

--- UNT 185 IN BOCR.g01 (geometry) ---

Geom Title=Existing Conditions

River Reach=UNT 185 IN BOCR,Reach-1
Reach XY= 30
      3714227.57     10611085.99      3714224.00     10610922.00
      3714173.50     10610889.00      3714159.25     10610790.00
      3714072.50     10610734.00      3713948.25     10610740.00
      3713784.50     10610730.00      3713699.75     10610700.00
      3713595.00     10610712.00      3713529.25     10610738.00
      3713515.50     10610732.00      3713457.50     10610636.00
      3713430.50     10610623.00      3713218.75     10610619.00
      3713128.00     10610587.00      3713055.00     10610656.00
      3713017.25     10610605.00      3712923.50     10610586.00
      3712808.75     10610619.00      3712792.50     10610609.00
      3712761.25     10610535.00      3712698.25     10610504.00
      3712670.75     10610435.00      3712624.25     10610410.00
      3712583.75     10610418.00      3712541.25     10610496.00
      3712498.75     10610518.00      3712443.25     10610507.00
      3712396.75     10610517.00      3712358.75     10610490.00

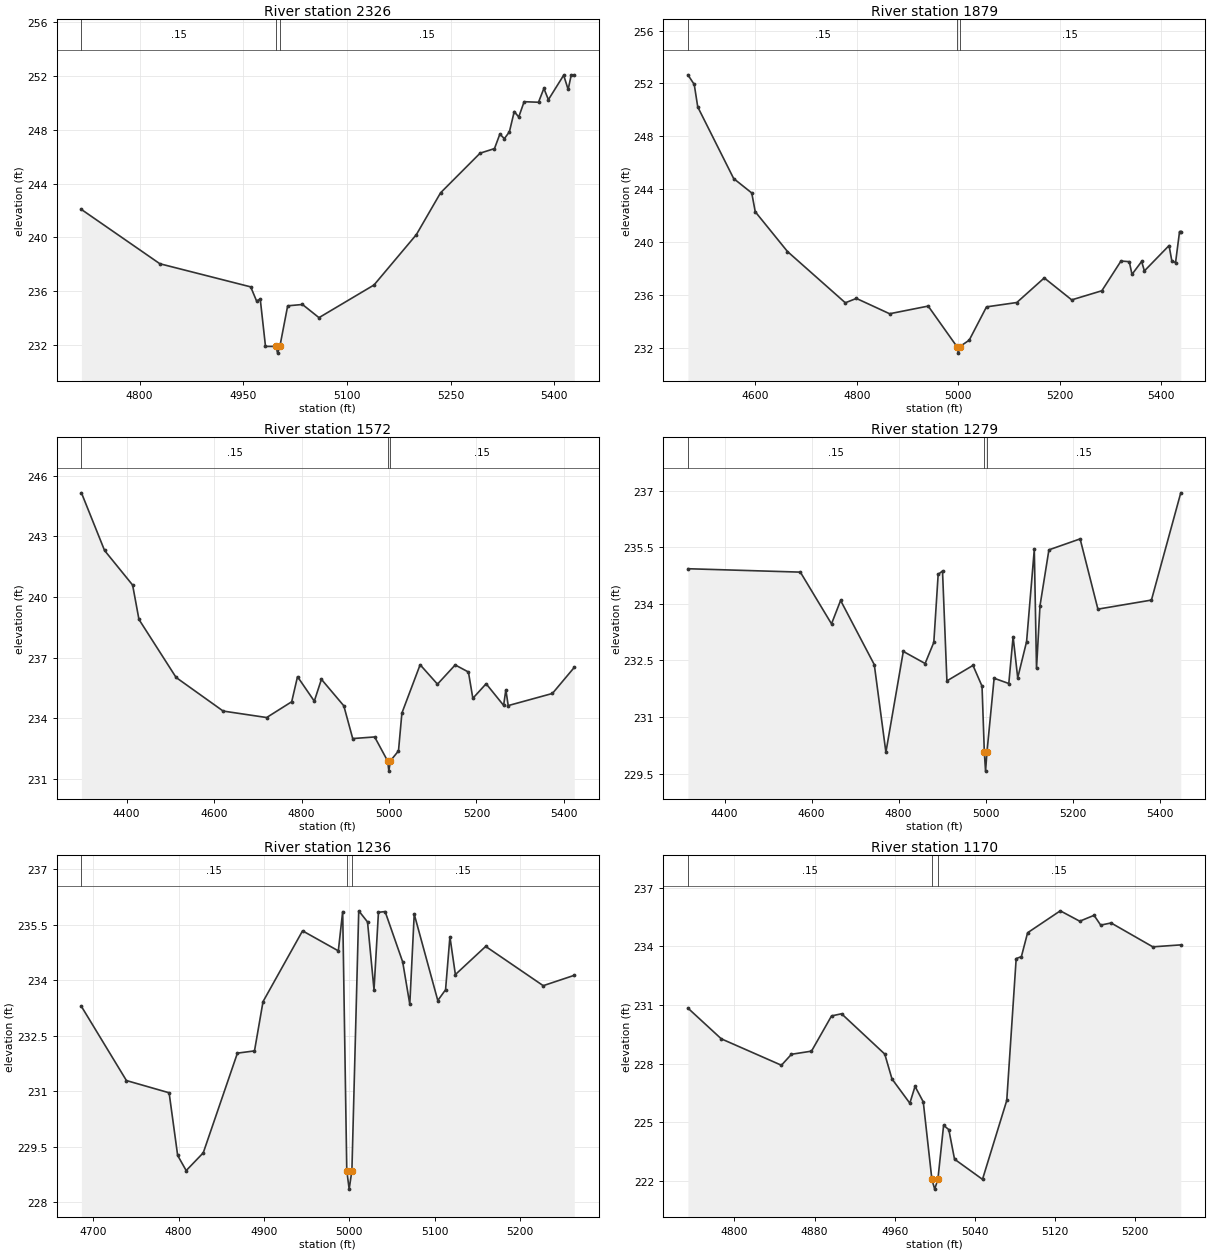
Type RM Length L Ch R = 1,2326,447,447,447
BEGIN DESCRIPTION:
UNT 185 IN BOCR 5.0
END DESCRIPTION:
XS GIS Cut Line= 3
      3714488.48     10610833.97      3714038.07     10611005.37
      3713888.74     10611181.84
#Sta/Elev= 30
  4715.9  242.07  4829.4  238.03  4960.8  236.31  4969.3  235.26  4974.6  235.41
  4982.2  231.88  4997.0  231.88  4999.8  231.38  5003.0  231.88  5014.3  234.90
  5035.7  235.00  5059.6  234.02  5139.2  236.45  5200.5  240.20  5235.5  243.31
  5292.7  246.26  5313.5  246.60  5321.3  247.68  5327.8  247.34  5335.1  247.85
  5342.1  249.36  5348.6  248.95  5356.4  250.09  5377.2  250.05  5385.0  251.08
  5391.5  250.24  5413.6  252.06  5420.1  251.00  5424.6  252.09  5429.0  252.09
#Mann=3,-1,0
  4715.9    0.15       0  4997.0    0.05       0  5003.0    0.15       0
Bank Sta=4997,5003
Exp/Cntr=0.3,0.1

Type RM Length L Ch R = 1,1879,307,307,307
BEGIN DESCRIPTION:
UNT 185 IN BOCR 4.0
END DESCRIPTION:
XS GIS Cut Line= 4
      3714225.54     10610308.58      3714020.35     10610526.15
      3713823.49     10610887.05      3713727.31     10611129.72
#Sta/Elev= 30
  4467.0  252.65  4479.5  251.92  4486.4  250.22  4557.2  244.80  4592.8  243.71
  4599.7  242.29  4663.2  239.28  4777.2  235.40  4799.0  235.73  4864.5  234.57
  4940.5  235.15  4997.0  232.09  4999.8  231.59  5003.0  232.09  5021.3  232.57
  5055.4  235.09  5115.1  235.42  5169.2  237.28  5223.3  235.62  5282.7  236.31
  5320.4  238.56  5336.7  238.51  5342.1  237.55  5361.1  238.53  5366.5  237.81
  5415.1  239.73  5420.5  238.59  5427.9  238.43  5435.8  240.79  5438.2  240.79
#Mann=3,-1,0
  4467.0    0.15       0  4997.0    0.05       0  5003.0    0.15       0
Bank Sta=4997,5003
Exp/Cntr=0.3,0.1

Type RM Length L Ch R = 1,1572,293,293,293
BEGIN DESCRIPTION:
UNT 185 IN BOCR 3.0
END DESCRIPTION:
XS GIS Cut Line= 4
      3713965.19     10610121.01      3713648.00     10610527.42
      3713592.64     10610785.77      3713541.54     10611129.74
#Sta/Elev= 30
  4296.5  245.15  4349.4  242.30  4413.6  240.59  4428.1  238.89  4513.1  236.02
  4620.7  234.36  4720.2  234.04  4777.5  234.82  4790.8  236.06  4829.2  234.85
  4845.5  235.93  4896.7  234.62  4917.1  233.00  4967.3  233.08  4997.0  231.89
  4999.8  231.39  5003.0  231.89  5021.8  232.39  5029.6  234.26  5071.3  236.65
  5111.0  235.69  5151.5  236.64  5181.8  236.29  5191.9  234.99  5222.3  235.71
  5262.3  234.64  5267.4  235.41  5272.8  234.63  5373.9  235.23  5424.0  236.52
#Mann=3,-1,0
  4296.5    0.15       0  4997.0    0.05       0  5003.0    0.15       0
Bank Sta=4997,5003
Exp/Cntr=0.3,0.1

Type RM Length L Ch R = 1,1279,43,43,43
BEGIN DESCRIPTION:
Mapping XS e7485aeb
END DESCRIPTION:
XS GIS Cut Line= 4
      3713657.89     10610034.21      3713383.90     10610364.12
      3713372.07     10610583.10      3713477.13     10611056.02
#Sta/Elev= 30
  4315.8  234.93  4574.2  234.84  4645.8  233.47  4666.7  234.09  4744.1  232.39
  4770.8  230.07  4810.8  232.74  4860.9  232.42  4880.9  232.98  4890.9  234.78
  4900.9  234.87  4911.0  231.96  4970.9  232.37  4991.7  231.82  4997.0  230.07
  4999.8  229.57  5003.0  230.07  5019.5  232.03  5053.2  231.89  5063.1  233.13
  5073.7  232.04  5094.1  233.00  5111.8  235.44  5116.9  232.29  5124.9  233.95
  5145.4  235.43  5217.1  235.72  5258.0  233.86  5381.0  234.10  5448.4  236.94
#Mann=3,-1,0
  4315.8    0.15       0  4997.0    0.05       0  5003.0    0.15       0
Bank Sta=4997,5003
Exp/Cntr=0.3,0.1

Type RM Length L Ch R = 1,1236,66,66,66
BEGIN DESCRIPTION:
Mapping XS 58051c1a
END DESCRIPTION:
XS GIS Cut Line= 3
      3713323.24     10610307.48      3713322.15     10610557.06
      3713399.08     10610875.62
#Sta/Elev= 30
  4686.2  233.29  4738.9  231.29  4788.9  230.96  4798.9  229.27  4808.9  228.86
  4828.9  229.34  4868.9  232.03  4888.9  232.09  4898.9  233.42  4945.2  235.33
  4987.1  234.79  4992.2  235.85  4997.0  228.86  4999.8  228.36  5003.0  228.86
  5011.0  235.87  5021.3  235.57  5028.9  233.74  5034.1  235.83  5041.9  235.85
  5062.5  234.49  5070.8  233.35  5076.0  235.78  5103.6  233.45  5112.7  233.74
  5117.8  235.17  5124.2  234.15  5159.7  234.91  5227.1  233.85  5263.5  234.13
#Mann=3,-1,0
  4686.2    0.15       0  4997.0    0.05       0  5003.0    0.15       0
Bank Sta=4997,5003
Exp/Cntr=0.3,0.1

Type RM Length L Ch R = 1,1170,402,402,402
BEGIN DESCRIPTION:
UNT 185 IN BOCR 2.0
END DESCRIPTION:
XS GIS Cut Line= 3
      3713259.22     10610376.91      3713257.05     10610573.34
      3713339.02     10610856.99
#Sta/Elev= 30
  4753.6  230.84  4786.9  229.27  4846.9  227.92  4856.9  228.48  4876.9  228.64
  4896.9  230.44  4906.9  230.55  4950.0  228.49  4957.2  227.22  4975.0  225.98
  4980.2  226.84  4988.4  226.05  4997.0  222.09  4999.8  221.59  5003.0  222.09
  5008.7  224.85  5013.9  224.63  5019.6  223.12  5047.5  222.09  5071.7  226.12
  5081.1  233.37  5086.3  233.47  5092.5  234.69  5125.1  235.81  5144.5  235.28
  5158.8  235.58  5165.4  235.08  5175.8  235.19  5217.4  233.97  5245.3  234.07
#Mann=3,-1,0
  4753.6    0.15       0  4997.0    0.05       0  5003.0    0.15       0
Bank Sta=4997,5003
Exp/Cntr=0.3,0.1

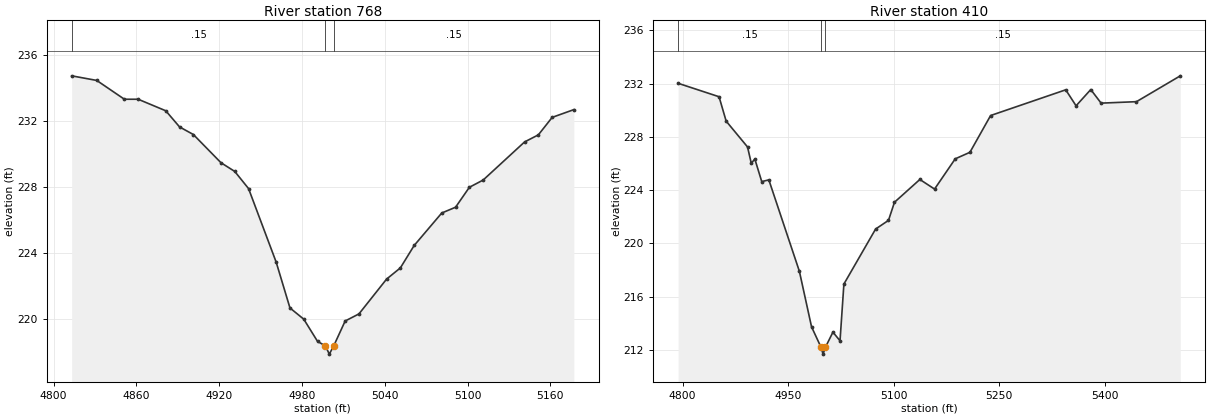
Type RM Length L Ch R = 1,768,358,358,358
BEGIN DESCRIPTION:
Mapping XS 4505d73b
END DESCRIPTION:
XS GIS Cut Line= 2
      3712937.86     10610401.97      3712937.86     10610765.87
#Sta/Elev= 30
  4813.1  234.72  4831.3  234.44  4851.3  233.30  4861.3  233.30  4881.3  232.60
  4891.3  231.62  4901.3  231.16  4921.3  229.45  4931.3  228.92  4941.3  227.88
  4961.3  223.42  4971.3  220.64  4981.3  219.96  4991.3  218.61  4997.0  218.34
  4999.8  217.84  5003.0  218.34  5011.3  219.85  5021.3  220.28  5041.3  222.39
  5051.3  223.07  5061.3  224.43  5081.3  226.40  5091.3  226.75  5101.3  227.96
  5111.3  228.40  5141.3  230.71  5151.3  231.14  5161.3  232.20  5177.0  232.67
#Mann=3,-1,0
  4813.1    0.15       0  4997.0    0.05       0  5003.0    0.15       0
Bank Sta=4997,5003
Exp/Cntr=0.3,0.1

Type RM Length L Ch R = 1,410,0,0,0
BEGIN DESCRIPTION:
UNT 185 IN BOCR 1.0
END DESCRIPTION:
XS GIS Cut Line= 3
      3712710.43     10610252.67      3712663.56     10610558.21
      3712900.36     10610886.63
#Sta/Elev= 30
  4793.7  232.02  4851.9  231.01  4862.0  229.18  4892.4  227.24  4897.7  226.02
  4902.8  226.33  4912.6  224.64  4922.7  224.77  4966.1  217.91  4983.4  213.74
  4997.0  212.19  4999.8  211.69  5003.0  212.19  5013.8  213.34  5023.9  212.69
  5029.4  216.95  5074.5  221.08  5092.8  221.73  5101.3  223.09  5137.4  224.80
  5158.3  224.08  5187.7  226.35  5208.6  226.84  5238.0  229.60  5344.8  231.53
  5359.5  230.33  5380.4  231.55  5395.1  230.53  5445.4  230.64  5507.7  232.58
#Mann=3,-1,0
  4793.7    0.15       0  4997.0    0.05       0  5003.0    0.15       0
Bank Sta=4997,5003
Exp/Cntr=0.3,0.1

Chan Stop Cuts=-1