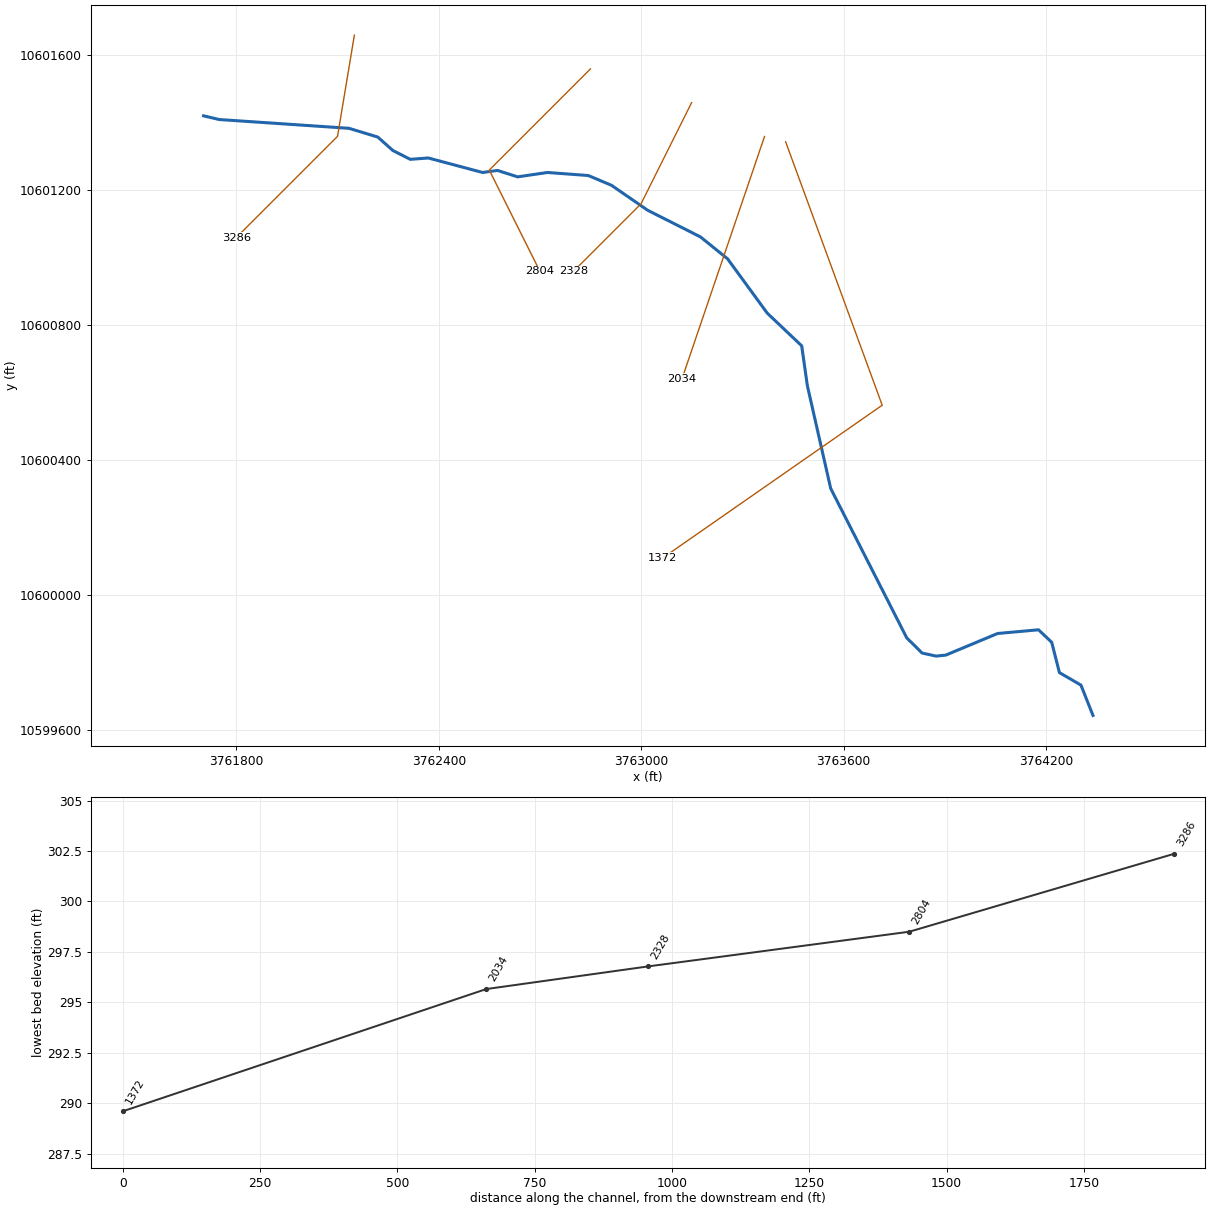
--- UNT 187 IN BOCR.prj (project) ---

Proj Title=UNT 187 IN BOCR Base Level Engineering
Current Plan=p01
Default Exp/Contr=0.3,0.1
English Units
Geom File=g01
Flow File=f01
Plan File=p01
Y Axis Title=Elevation
X Axis Title(PF)=Main Channel Distance
X Axis Title(XS)=Station
BEGIN DESCRIPTION:
UNT 187 IN BOCR
END DESCRIPTION:
DSS Export Rating Curves= 0
DSS Export Rating Curve Sorted= 0
DSS Export Volume Flow Curves= 0
DXF OffsetX= 0
DXF OffsetY= 0
DXF ScaleX= 1
DXF ScaleY= 10

--- UNT 187 IN BOCR.p01 (plan) ---

Plan Title=Multiple Run
Short Identifier=Multiple
Geom File=g01
Flow File=f01
Subcritical Flow
K Sum by GR= 0
Std Step Tol= 0.01
Critical Tol= 0.01
Num of Std Step Trials= 20
Max Error Tol= 0.3
Flow Tol Ratio= 0.001
Split Flow NTrial= 30
Split Flow Tol= 0.02
Split Flow Ratio= 0.02
Log Output Level= 0
Friction Slope Method= 1
Unsteady Friction Slope Method= 2
Unsteady Bridges Friction Slope Method= 1
Parabolic Critical Depth
Global Vel Dist=  1 , 1 , 1
Global Log Level= 0
CheckData=True
Encroach Param= -1, 0, 0, 0
BEGIN DESCRIPTION:
Multiple Run
END DESCRIPTION:

--- UNT 187 IN BOCR.f01 (steady flow) ---

Flow Title=Multiple
Program Version=4.10
Number of Profiles= 7
Profile Names=10-year,25-year,50-year,1pct_min,100-year,1pct_plu,500-year
River Rch & RM=UNT 187 IN BOCR,Reach-1         ,3286
     555     756     924     833    1126    1523    1675
Boundary for River Rch & Prof#=UNT 187 IN BOCR,Reach-1         , 1
Up Type= 0
Dn Type= 3
Dn Slope=0.005
Boundary for River Rch & Prof#=UNT 187 IN BOCR,Reach-1         , 2
Up Type= 0
Dn Type= 3
Dn Slope=0.005
Boundary for River Rch & Prof#=UNT 187 IN BOCR,Reach-1         , 3
Up Type= 0
Dn Type= 3
Dn Slope=0.005
Boundary for River Rch & Prof#=UNT 187 IN BOCR,Reach-1         , 4
Up Type= 0
Dn Type= 3
Dn Slope=0.005
Boundary for River Rch & Prof#=UNT 187 IN BOCR,Reach-1         , 5
Up Type= 0
Dn Type= 3
Dn Slope=0.005
Boundary for River Rch & Prof#=UNT 187 IN BOCR,Reach-1         , 6
Up Type= 0
Dn Type= 3
Dn Slope=0.005
Boundary for River Rch & Prof#=UNT 187 IN BOCR,Reach-1         , 7
Up Type= 0
Dn Type= 3
Dn Slope=0.005
DSS Import GetInterval= 0
DSS Import GetPeak= 0
DSS Import FillOption= 0

--- UNT 187 IN BOCR.g01 (geometry) ---

Geom Title=Existing Conditions

River Reach=UNT 187 IN BOCR,Reach-1
Reach XY= 30
      3761702.49     10601421.00      3761749.00     10601410.00
      3762133.50     10601384.00      3762219.00     10601358.00
      3762264.00     10601318.00      3762315.50     10601292.00
      3762368.75     10601296.00      3762529.75     10601253.00
      3762574.25     10601259.00      3762633.50     10601240.00
      3762722.00     10601253.00      3762843.25     10601244.00
      3762912.00     10601215.00      3763019.25     10601141.00
      3763175.75     10601062.00      3763256.25     10600997.00
      3763373.75     10600836.00      3763476.00     10600739.00
      3763492.75     10600621.00      3763562.00     10600316.00
      3763787.50     10599873.00      3763833.00     10599828.00
      3763874.50     10599819.00      3763903.25     10599822.00
      3764056.75     10599886.00      3764178.25     10599897.00
      3764217.25     10599860.00      3764240.25     10599770.00
      3764304.00     10599733.00      3764339.75     10599643.00

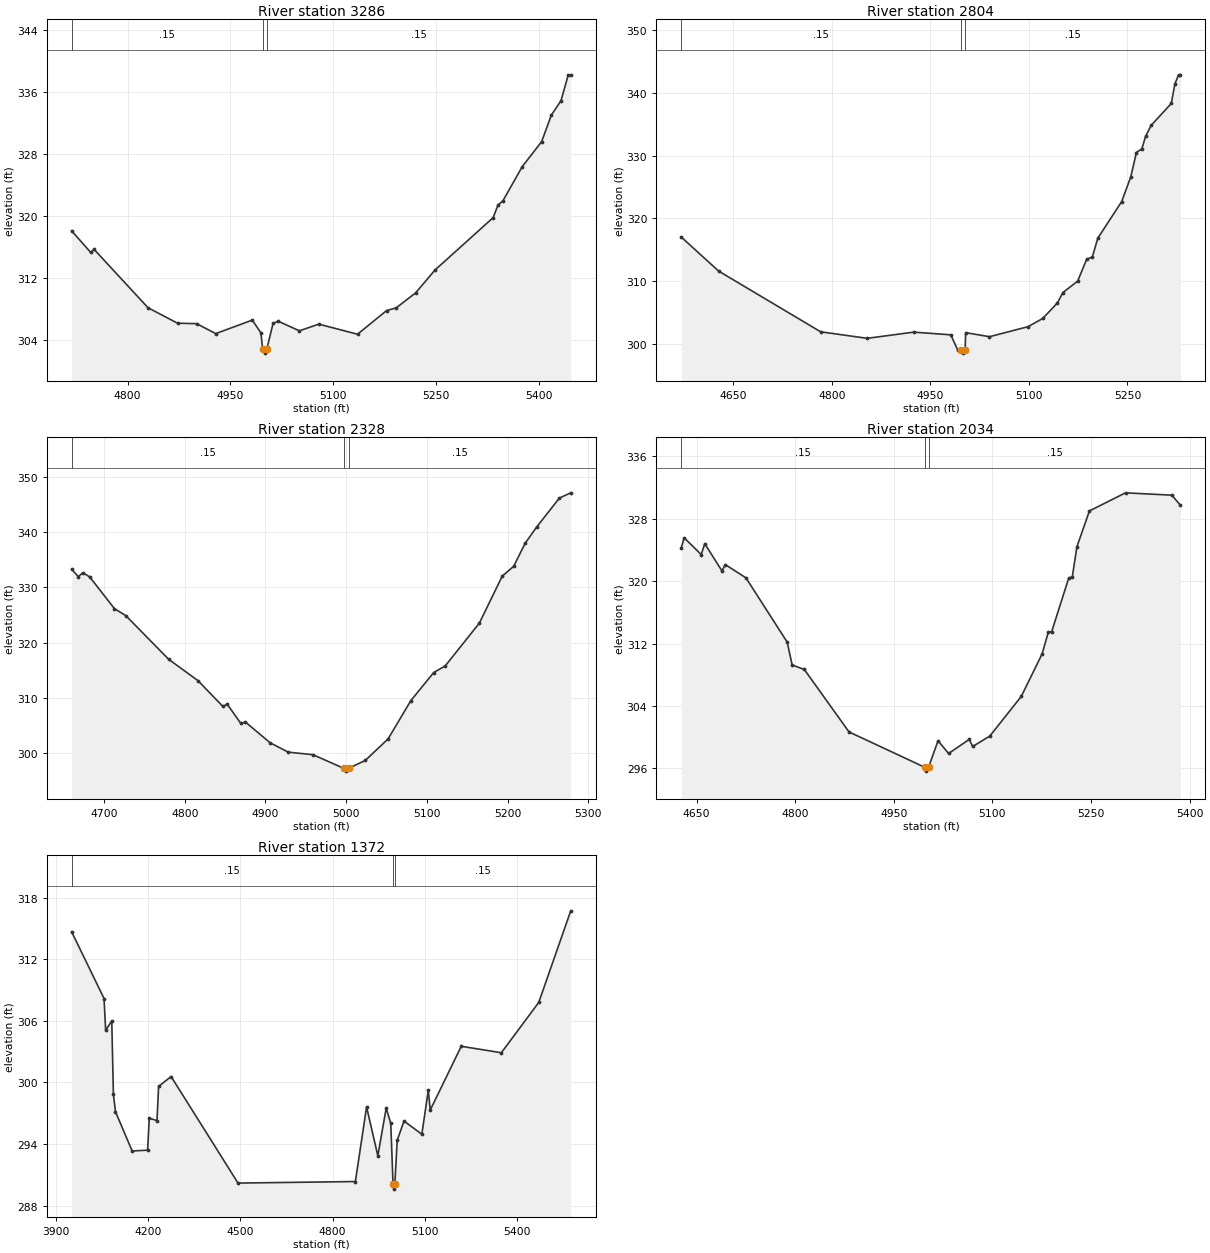
Type RM Length L Ch R = 1,3286,482,482,482
BEGIN DESCRIPTION:
UNT 187 IN BOCR 4.0
END DESCRIPTION:
XS GIS Cut Line= 3
      3762149.60     10601660.16      3762099.61     10601360.19
      3761799.59     10601060.17
#Sta/Elev= 30
  4718.2  318.10  4746.1  315.31  4751.1  315.70  4829.7  308.20  4872.8  306.21
  4900.7  306.15  4928.5  304.87  4981.8  306.61  4994.4  304.98  4997.0  302.86
  4999.8  302.36  5003.0  302.86  5012.2  306.20  5019.8  306.46  5050.6  305.23
  5078.9  306.09  5135.4  304.79  5177.9  307.84  5192.0  308.19  5220.3  310.12
  5248.6  313.06  5333.4  319.80  5340.5  321.42  5347.6  321.96  5375.9  326.37
  5404.1  329.57  5418.3  332.98  5432.4  334.85  5443.0  338.17  5446.6  338.17
#Mann=3,-1,0
  4718.2    0.15       0  4997.0    0.05       0  5003.0    0.15       0
Bank Sta=4997,5003
Exp/Cntr=0.3,0.1

Type RM Length L Ch R = 1,2804,476,476,476
BEGIN DESCRIPTION:
UNT 187 IN BOCR 3.0
END DESCRIPTION:
XS GIS Cut Line= 3
      3762849.62     10601560.20      3762549.61     10601260.19
      3762699.62     10600960.18
#Sta/Elev= 30
  4571.0  317.01  4627.6  311.60  4783.1  301.90  4853.9  300.86  4924.6  301.85
  4981.1  301.42  4991.7  299.00  4997.0  299.00  4999.8  298.50  5003.0  299.00
  5003.7  301.77  5040.0  301.12  5098.7  302.72  5121.1  304.03  5143.4  306.51
  5151.8  308.17  5174.2  309.98  5188.1  313.51  5196.5  313.81  5204.9  316.84
  5241.2  322.67  5255.2  326.66  5263.6  330.50  5272.0  331.11  5277.6  333.08
  5286.0  334.82  5316.7  338.33  5322.3  341.48  5327.9  342.90  5330.7  342.90
#Mann=3,-1,0
  4571.0    0.15       0  4997.0    0.05       0  5003.0    0.15       0
Bank Sta=4997,5003
Exp/Cntr=0.3,0.1

Type RM Length L Ch R = 1,2328,294,294,294
BEGIN DESCRIPTION:
UNT 187 IN BOCR 2.0
END DESCRIPTION:
XS GIS Cut Line= 3
      3763149.60     10601460.16      3762999.61     10601160.19
      3762799.63     10600960.21
#Sta/Elev= 30
  4659.9  333.27  4668.3  331.94  4673.8  332.66  4682.2  331.91  4713.0  326.15
  4727.0  324.90  4780.1  317.00  4816.4  313.14  4847.1  308.50  4852.7  308.87
  4869.5  305.40  4875.1  305.66  4905.8  301.90  4928.2  300.21  4958.9  299.75
  4997.0  297.28  4999.8  296.78  5003.0  297.28  5023.6  298.71  5051.9  302.61
  5080.1  309.54  5108.4  314.61  5122.6  315.80  5165.0  323.56  5193.3  332.05
  5207.4  333.81  5221.6  337.97  5235.7  340.88  5264.0  346.15  5278.1  347.10
#Mann=3,-1,0
  4659.9    0.15       0  4997.0    0.05       0  5003.0    0.15       0
Bank Sta=4997,5003
Exp/Cntr=0.3,0.1

Type RM Length L Ch R = 1,2034,662,662,662
BEGIN DESCRIPTION:
Mapping XS 3a2bcc2d
END DESCRIPTION:
XS GIS Cut Line= 2
      3763365.78     10601359.80      3763120.99     10600641.04
#Sta/Elev= 30
  4626.9  324.30  4631.2  325.55  4657.2  323.40  4662.5  324.80  4688.6  321.32
  4693.9  322.11  4725.2  320.42  4787.9  312.19  4795.5  309.25  4814.0  308.68
  4882.0  300.68  4997.0  296.16  4999.8  295.66  5003.0  296.16  5017.4  299.55
  5033.5  297.92  5064.8  299.72  5070.2  298.82  5096.2  300.15  5144.1  305.24
  5175.8  310.69  5185.0  313.42  5190.3  313.53  5216.3  320.41  5221.6  320.50
  5228.6  324.38  5247.7  328.99  5302.6  331.31  5373.1  331.01  5386.2  329.71
#Mann=3,-1,0
  4626.9    0.15       0  4997.0    0.05       0  5003.0    0.15       0
Bank Sta=4997,5003
Exp/Cntr=0.3,0.1

Type RM Length L Ch R = 1,1372,0,0,0
BEGIN DESCRIPTION:
UNT 187 IN BOCR 1.0
END DESCRIPTION:
XS GIS Cut Line= 3
      3763428.28     10601344.24      3763714.75     10600562.95
      3763064.17     10600110.15
#Sta/Elev= 30
  3950.7  314.70  4056.2  308.19  4061.5  305.09  4081.4  306.01  4086.7  298.84
  4093.5  297.15  4147.7  293.32  4198.1  293.40  4203.4  296.52  4228.6  296.28
  4233.9  299.62  4274.5  300.58  4492.4  290.19  4874.4  290.34  4910.9  297.61
  4947.5  292.85  4974.7  297.49  4989.6  296.02  4997.0  290.10  4999.8  289.60
  5003.0  290.10  5010.5  294.35  5032.8  296.24  5090.8  294.95  5111.8  299.24
  5118.1  297.31  5219.1  303.53  5349.6  302.90  5471.4  307.81  5575.5  316.74
#Mann=3,-1,0
  3950.7    0.15       0  4997.0    0.05       0  5003.0    0.15       0
Bank Sta=4997,5003
Exp/Cntr=0.3,0.1

Chan Stop Cuts=-1