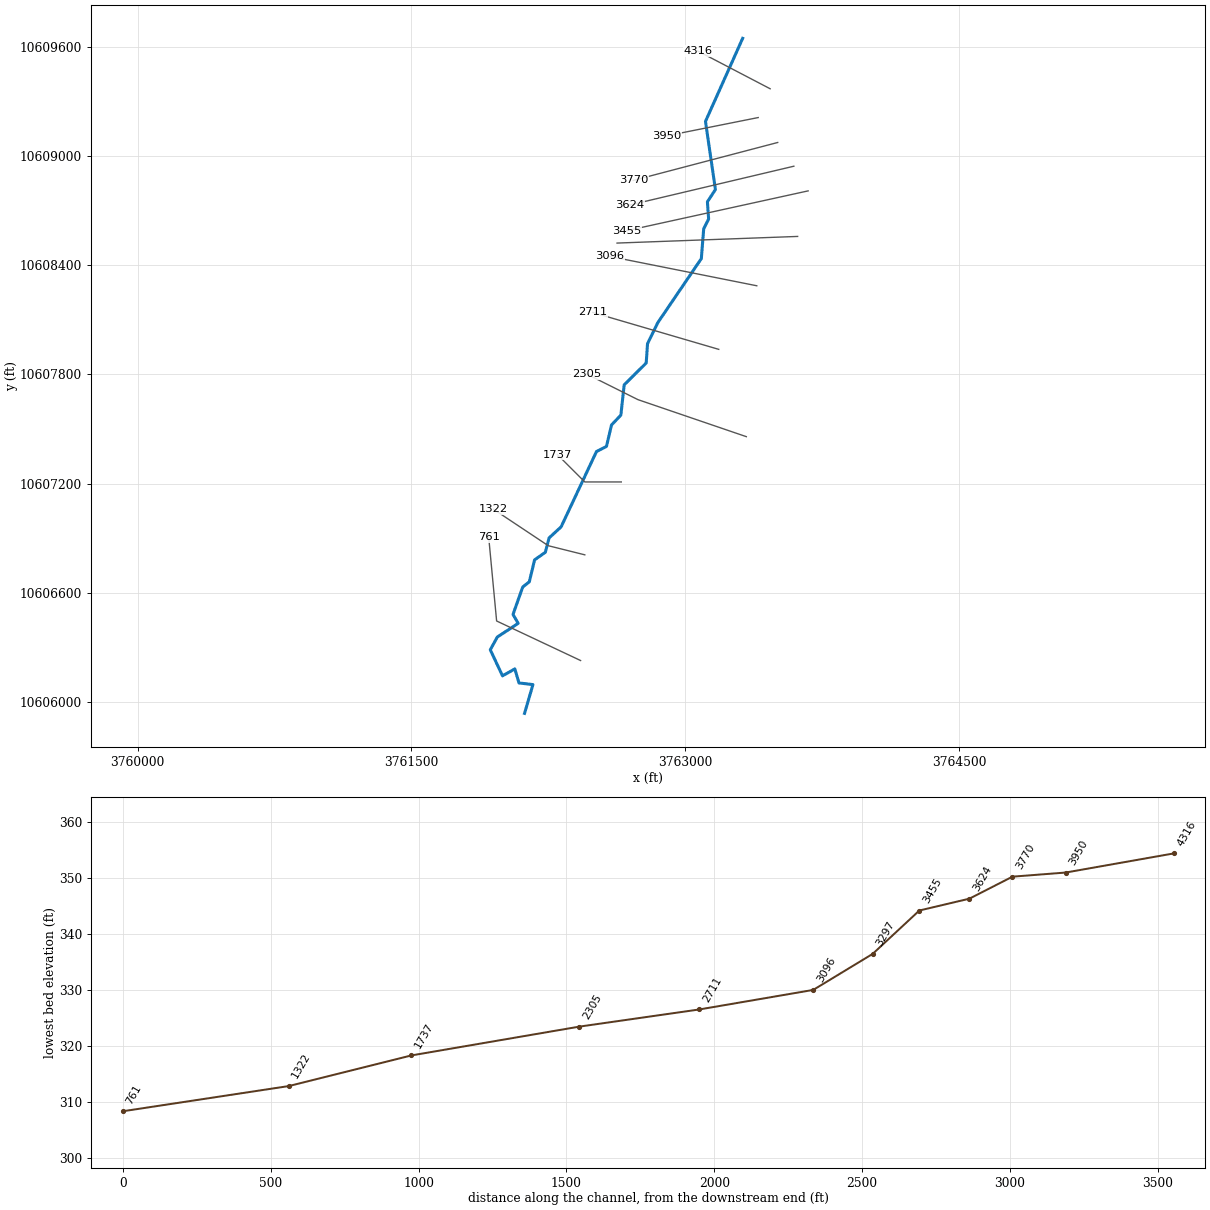
--- UNT 188 IN BOCR.prj (project) ---

Proj Title=UNT 188 IN BOCR Base Level Engineering
Current Plan=p01
Default Exp/Contr=0.3,0.1
English Units
Geom File=g01
Flow File=f01
Plan File=p01
BEGIN DESCRIPTION:
UNT 188 IN BOCR
END DESCRIPTION:

--- UNT 188 IN BOCR.p01 (plan) ---

Plan Title=Multiple Run
Short Identifier=Multiple
Geom File=g01
Flow File=f01
Subcritical Flow
K Sum by GR= 0
Std Step Tol= 0.01
Critical Tol= 0.01
Num of Std Step Trials= 20
Max Error Tol= 0.3
Flow Tol Ratio= 0.001
Split Flow NTrial= 30
Split Flow Tol= 0.02
Split Flow Ratio= 0.02
Log Output Level= 0
Friction Slope Method= 1
Unsteady Friction Slope Method= 2
Unsteady Bridges Friction Slope Method= 1
Parabolic Critical Depth
Global Vel Dist=  1 , 1 , 1
Global Log Level= 0
CheckData=True
Encroach Param= -1, 0, 0, 0
BEGIN DESCRIPTION:
Multiple Run
END DESCRIPTION:

--- UNT 188 IN BOCR.f01 (steady flow) ---

Flow Title=Multiple
Number of Profiles=7
Profile Names=10-year,25-year,50-year,1pct_min,100-year,1pct_plu,500-year
River Rch & RM= UNT 188 IN BOCR,Reach-1,4316
     266     344     405     353     478     646     664
Boundary for River Rch & Prof#=UNT 188 IN BOCR,Reach-1,1
Up Type=0
Dn Type=3
Dn Slope=0.005
Boundary for River Rch & Prof#=UNT 188 IN BOCR,Reach-1,2
Up Type=0
Dn Type=3
Dn Slope=0.005
Boundary for River Rch & Prof#=UNT 188 IN BOCR,Reach-1,3
Up Type=0
Dn Type=3
Dn Slope=0.005
Boundary for River Rch & Prof#=UNT 188 IN BOCR,Reach-1,4
Up Type=0
Dn Type=3
Dn Slope=0.005
Boundary for River Rch & Prof#=UNT 188 IN BOCR,Reach-1,5
Up Type=0
Dn Type=3
Dn Slope=0.005
Boundary for River Rch & Prof#=UNT 188 IN BOCR,Reach-1,6
Up Type=0
Dn Type=3
Dn Slope=0.005
Boundary for River Rch & Prof#=UNT 188 IN BOCR,Reach-1,7
Up Type=0
Dn Type=3
Dn Slope=0.005

--- UNT 188 IN BOCR.g01 (geometry) ---

Geom Title=Existing Conditions

River Reach=UNT 188 IN BOCR,Reach-1
Reach XY= 30
      3763314.50     10609645.00      3763110.75     10609189.00
      3763165.25     10608815.00      3763121.30     10608748.02
      3763128.00     10608653.00      3763101.00     10608600.00
      3763088.00     10608436.00      3762849.45     10608084.35
      3762793.25     10607969.00      3762786.00     10607863.00
      3762665.25     10607743.00      3762647.25     10607577.00
      3762596.00     10607523.00      3762568.22     10607405.14
      3762513.50     10607377.00      3762319.85     10606963.69
      3762254.00     10606903.00      3762233.25     10606824.00
      3762174.53     10606782.44      3762145.50     10606662.00
      3762109.43     10606633.35      3762056.25     10606483.00
      3762084.50     10606434.00      3761970.25     10606359.00
      3761931.75     10606289.00      3761998.75     10606146.00
      3762066.25     10606184.00      3762089.00     10606107.00
      3762165.50     10606098.00      3762119.50     10605940.00

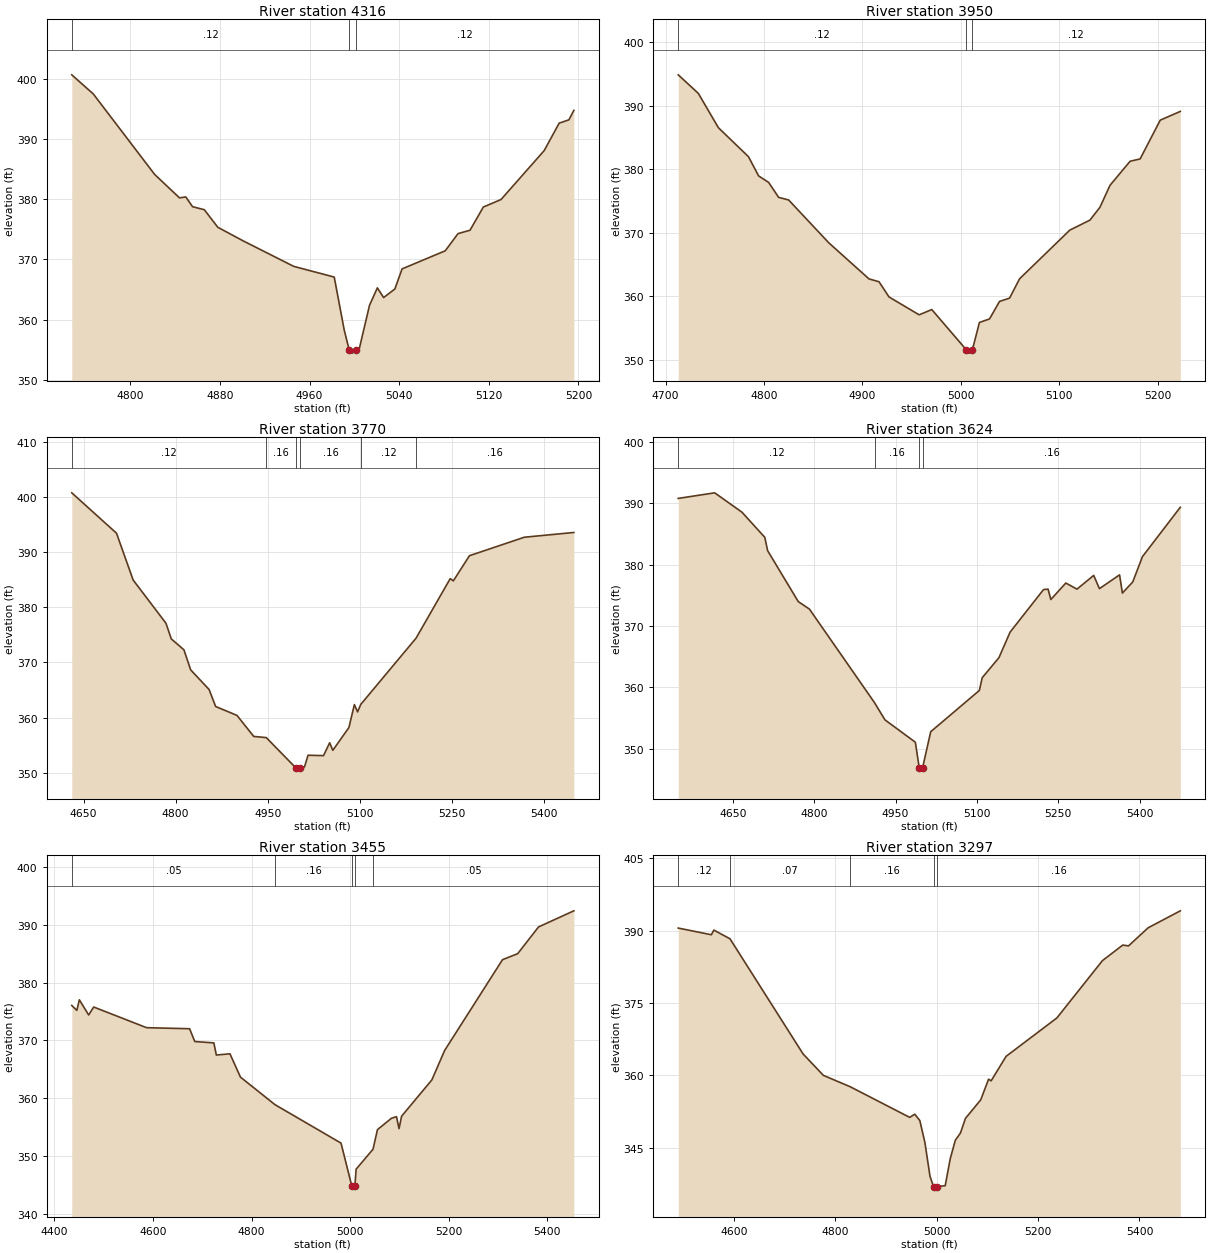
Type RM Length L Ch R = 1,4316,366,366,366
BEGIN DESCRIPTION:
UNT 188 IN BOCR 9.0
END DESCRIPTION:
XS GIS Cut Line= 2
      3763465.16     10609368.16      3763067.98     10609575.83
#Sta/Elev= 30
  4747.7  400.63  4766.9  397.46  4821.7  384.10  4843.9  380.21  4849.5  380.37
  4855.5  378.75  4866.0  378.25  4878.1  375.33  4900.7  373.08  4945.8  368.85
  4982.0  367.07  4990.9  358.30  4995.4  354.95  4998.2  354.45  5001.4  354.95
  5004.1  354.97  5013.5  362.39  5020.5  365.28  5026.1  363.67  5036.1  365.09
  5042.6  368.43  5081.1  371.43  5092.5  374.28  5103.2  374.84  5115.1  378.69
  5130.9  379.94  5169.4  388.05  5182.8  392.61  5191.5  393.16  5195.9  394.73
#Mann=3,-1,0
  4747.7    0.12       0  4995.4    0.07       0  5001.4    0.12       0
Bank Sta=4995.4,5001.4
Exp/Cntr=0.3,0.1

Type RM Length L Ch R = 1,3950,180,180,180
BEGIN DESCRIPTION:
UNT 188 IN BOCR 8.0
END DESCRIPTION:
XS GIS Cut Line= 3
      3763399.58     10609210.18      3763149.61     10609160.19
      3762899.58     10609110.18
#Sta/Elev= 30
  4712.9  394.85  4733.3  391.93  4753.7  386.52  4784.3  381.95  4794.5  378.94
  4804.7  377.91  4814.9  375.55  4825.0  375.15  4865.8  368.40  4906.6  362.72
  4916.8  362.27  4927.0  359.87  4957.6  357.06  4970.4  357.89  5005.6  351.53
  5008.4  351.03  5011.6  351.53  5018.8  355.86  5029.0  356.41  5039.2  359.17
  5049.4  359.69  5059.6  362.74  5110.6  370.40  5131.0  371.97  5141.2  374.00
  5151.4  377.45  5171.8  381.24  5182.0  381.61  5202.4  387.71  5222.8  389.09
#Mann=3,-1,0
  4712.9    0.12       0  5005.6    0.07       0  5011.6    0.12       0
Bank Sta=5005.6,5011.6
Exp/Cntr=0.3,0.1

Type RM Length L Ch R = 1,3770,146,146,146
BEGIN DESCRIPTION:
Mapping XS 47f69c0e
END DESCRIPTION:
XS GIS Cut Line= 2
      3763506.42     10609073.37      3762715.06     10608865.12
#Sta/Elev= 30
  4630.7  400.75  4703.6  393.43  4730.8  384.93  4784.2  377.11  4792.9  374.26
  4813.5  372.29  4824.5  368.65  4854.5  365.09  4865.2  362.01  4900.0  360.39
  4927.3  356.58  4947.7  356.37  4996.7  350.79  4999.4  350.29  5002.7  350.79
  5010.0  351.05  5015.8  353.17  5041.0  353.10  5051.0  355.43  5056.2  354.07
  5082.4  358.19  5091.3  362.35  5096.5  361.03  5101.8  362.40  5191.8  374.39
  5247.5  385.19  5252.6  384.79  5278.9  389.35  5368.4  392.70  5449.0  393.56
#Mann=6,-1,0
  4630.7    0.12       0  4947.7    0.16       0  4996.7    0.07       0
  5002.7    0.16       0  5101.8    0.12       0  5191.8    0.16       0
Bank Sta=4996.7,5002.7
Exp/Cntr=0.3,0.1

Type RM Length L Ch R = 1,3624,169,169,169
BEGIN DESCRIPTION:
Mapping XS 48af0744
END DESCRIPTION:
XS GIS Cut Line= 2
      3763594.99     10608943.17      3762694.24     10608729.70
#Sta/Elev= 30
  4549.2  390.80  4616.4  391.71  4666.6  388.56  4708.8  384.46  4714.0  382.29
  4770.5  373.98  4791.1  372.76  4911.1  357.51  4930.3  354.71  4986.4  351.06
  4993.6  346.85  4996.4  346.35  4999.6  346.85  5014.7  352.77  5104.4  359.50
  5109.7  361.58  5140.5  364.84  5161.1  369.01  5222.7  375.94  5231.1  376.01
  5236.2  374.32  5263.8  377.01  5284.4  376.01  5315.2  378.25  5325.8  376.09
  5362.9  378.34  5368.1  375.37  5387.2  377.18  5405.1  381.31  5474.9  389.36
#Mann=4,-1,0
  4549.2    0.12       0  4911.1    0.16       0  4993.6    0.07       0
  4999.6    0.16       0
Bank Sta=4993.6,4999.6
Exp/Cntr=0.3,0.1

Type RM Length L Ch R = 1,3455,158,158,158
BEGIN DESCRIPTION:
Mapping XS 5b3c4f25
END DESCRIPTION:
XS GIS Cut Line= 2
      3763673.07     10608807.74      3762678.33     10608589.01
#Sta/Elev= 30
  4435.3  376.05  4445.6  375.20  4450.7  377.03  4469.6  374.40  4479.8  375.78
  4587.1  372.20  4674.3  372.02  4684.9  369.80  4723.5  369.57  4728.6  367.46
  4756.2  367.68  4777.5  363.64  4847.7  358.86  4981.5  352.21  5003.5  344.74
  5006.3  344.24  5009.5  344.74  5012.2  347.70  5046.4  351.15  5055.4  354.54
  5083.9  356.52  5094.0  356.79  5099.2  354.72  5104.4  356.87  5165.8  363.16
  5191.8  368.27  5309.1  383.98  5339.9  385.02  5382.2  389.65  5453.8  392.44
#Mann=5,-1,0
  4435.3    0.05       0  4847.7    0.16       0  5003.5    0.07       0
  5009.5    0.16       0  5046.4    0.05       0
Bank Sta=5003.5,5009.5
Exp/Cntr=0.3,0.1

Type RM Length L Ch R = 1,3297,201,201,201
BEGIN DESCRIPTION:
Mapping XS 71134584
END DESCRIPTION:
XS GIS Cut Line= 2
      3763615.76     10608557.75      3762626.24     10608521.29
#Sta/Elev= 30
  4490.4  390.51  4555.7  389.13  4560.7  390.09  4592.5  388.29  4736.7  364.45
  4776.7  360.02  4829.4  357.68  4946.9  351.33  4956.9  351.99  4966.9  350.67
  4976.9  346.13  4986.9  339.16  4993.9  336.98  4996.6  336.48  4999.9  336.98
  5016.9  337.19  5026.9  342.79  5036.9  346.60  5046.9  348.08  5056.9  351.13
  5087.0  354.96  5102.5  359.24  5107.5  358.89  5137.0  363.96  5237.1  371.90
  5327.1  383.78  5367.1  386.99  5378.4  386.82  5417.2  390.57  5480.6  394.08
#Mann=5,-1,0
  4490.4    0.12       0  4592.5    0.07       0  4829.4    0.16       0
  4993.9    0.07       0  4999.9    0.16       0
Bank Sta=4993.9,4999.9
Exp/Cntr=0.3,0.1

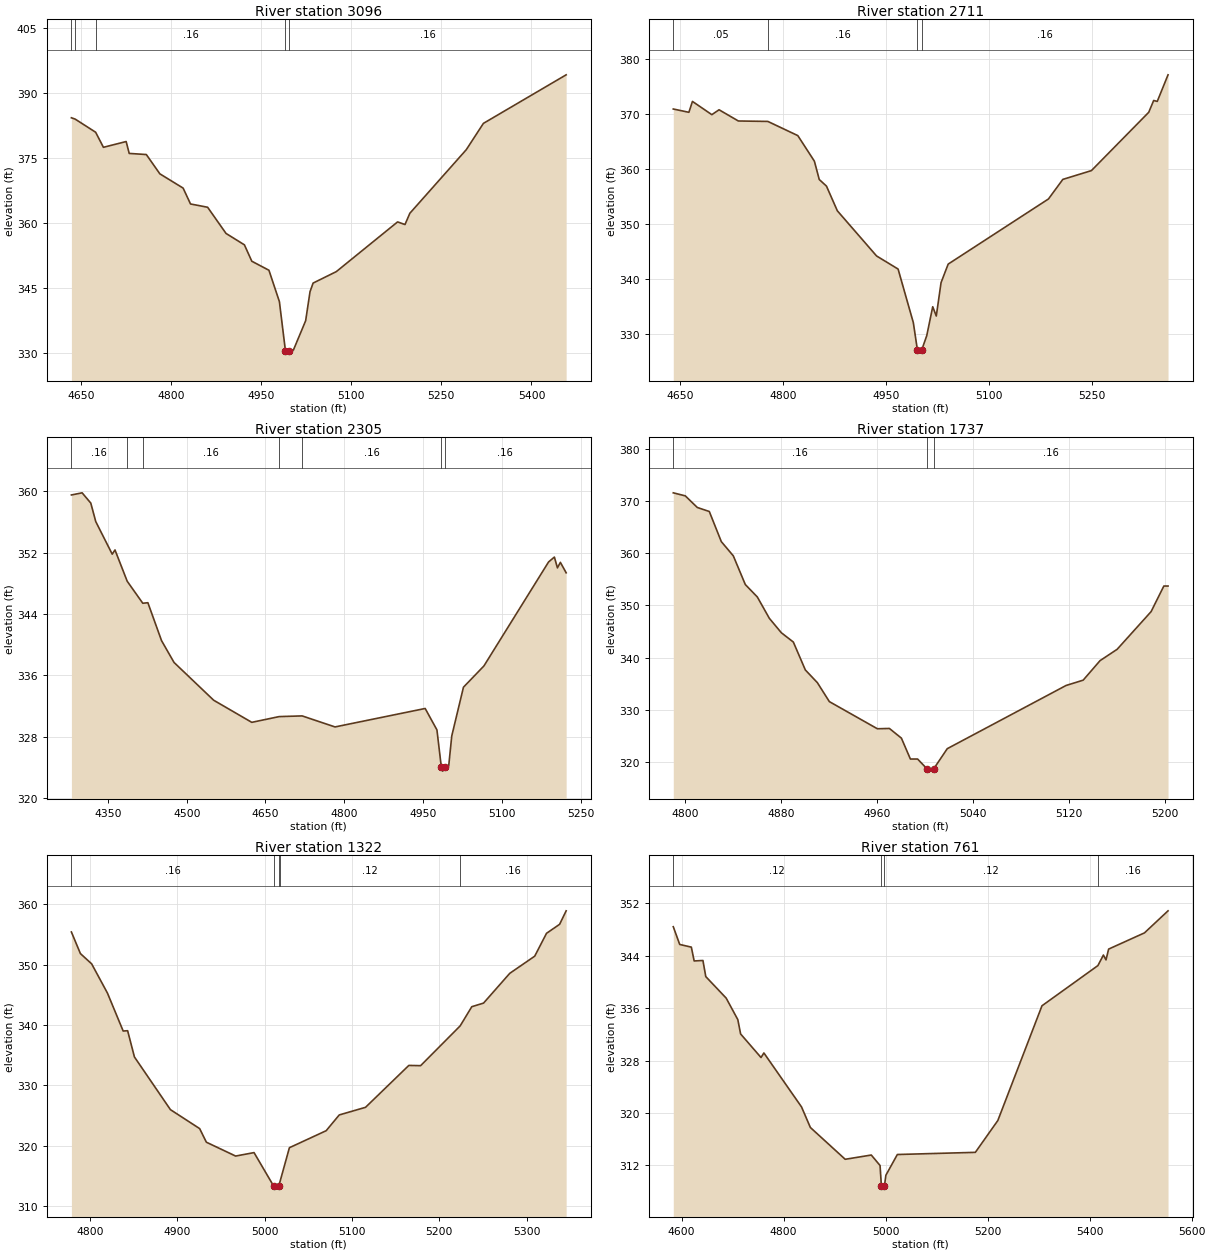
Type RM Length L Ch R = 1,3096,385,385,385
BEGIN DESCRIPTION:
Mapping XS 98c60416
END DESCRIPTION:
XS GIS Cut Line= 2
      3763391.88     10608286.90      3762584.57     10608448.37
#Sta/Elev= 30
  4634.4  384.33  4640.7  384.02  4674.7  381.00  4687.7  377.52  4725.5  378.85
  4730.6  376.11  4759.1  375.85  4781.6  371.40  4820.3  368.11  4832.6  364.45
  4861.1  363.69  4891.7  357.65  4922.3  355.02  4934.6  351.24  4963.1  349.16
  4980.5  341.94  4990.6  330.54  4993.4  330.04  4996.6  330.54  5003.8  330.74
  5024.2  337.51  5031.5  344.22  5036.6  346.20  5075.2  348.84  5177.2  360.31
  5189.5  359.70  5197.6  362.30  5291.5  376.97  5320.0  383.04  5457.7  394.24
#Mann=5,-1,0
  4634.4    0.07       0  4640.7    0.05       0  4674.7    0.16       0
  4990.6    0.07       0  4996.6    0.16       0
Bank Sta=4990.6,4996.6
Exp/Cntr=0.3,0.1

Type RM Length L Ch R = 1,2711,406,406,406
BEGIN DESCRIPTION:
Mapping XS 526c9123
END DESCRIPTION:
XS GIS Cut Line= 2
      3763183.47     10607937.96      3762492.66     10608140.53
#Sta/Elev= 30
  4640.4  370.97  4663.1  370.37  4668.3  372.35  4696.5  369.94  4707.0  370.83
  4735.1  368.79  4778.0  368.71  4821.6  366.13  4845.7  361.48  4852.8  358.14
  4863.3  356.94  4879.1  352.45  4936.2  344.23  4967.5  341.85  4989.7  332.09
  4995.7  327.05  4998.5  326.55  5001.7  327.05  5009.2  329.73  5017.9  334.99
  5023.1  333.30  5030.0  339.37  5040.4  342.75  5186.3  354.60  5207.2  358.16
  5248.8  359.76  5332.2  370.37  5339.4  372.52  5344.6  372.35  5360.3  377.19
#Mann=4,-1,0
  4640.4    0.05       0  4778.0    0.16       0  4995.7    0.07       0
  5001.7    0.16       0
Bank Sta=4995.7,5001.7
Exp/Cntr=0.3,0.1

Type RM Length L Ch R = 1,2305,568,568,568
BEGIN DESCRIPTION:
UNT 188 IN BOCR 4.0
END DESCRIPTION:
XS GIS Cut Line= 3
      3763334.50     10607458.80      3762740.79     10607661.91
      3762459.58     10607802.52
#Sta/Elev= 30
  4280.5  359.54  4300.9  359.82  4317.4  358.48  4326.9  356.06  4358.2  351.81
  4363.5  352.36  4386.7  348.28  4416.4  345.40  4426.1  345.47  4452.1  340.52
  4475.9  337.67  4551.3  332.74  4623.9  329.85  4676.0  330.60  4719.8  330.69
  4782.4  329.25  4954.0  331.66  4976.4  328.86  4984.8  323.98  4987.5  323.48
  4990.8  323.98  4998.8  324.15  5004.6  328.07  5026.9  334.44  5065.8  337.21
  5189.0  350.80  5200.0  351.43  5205.8  350.02  5211.4  350.74  5222.4  349.38
#Mann=7,-1,0
  4280.5    0.16       0  4386.7     0.1       0  4416.4    0.16       0
  4676.0    0.12       0  4719.8    0.16       0  4984.8    0.07       0
  4990.8    0.16       0
Bank Sta=4984.8,4990.8
Exp/Cntr=0.3,0.1

Type RM Length L Ch R = 1,1737,415,415,415
BEGIN DESCRIPTION:
UNT 188 IN BOCR 3.0
END DESCRIPTION:
XS GIS Cut Line= 3
      3762649.57     10607210.19      3762449.61     10607210.19
      3762299.61     10607360.19
#Sta/Elev= 30
  4790.3  371.54  4800.3  370.96  4810.3  368.74  4820.3  367.97  4830.3  362.21
  4840.3  359.49  4850.3  354.00  4860.3  351.63  4870.3  347.55  4880.3  344.79
  4890.3  343.01  4900.3  337.67  4910.3  335.25  4920.3  331.62  4960.3  326.43
  4970.3  326.49  4980.3  324.64  4987.8  320.64  4993.8  320.64  5001.4  318.83
  5004.2  318.33  5007.4  318.83  5018.5  322.62  5117.5  334.71  5131.7  335.72
  5145.8  339.46  5160.0  341.62  5188.3  348.83  5198.9  353.72  5202.4  353.72
#Mann=3,-1,0
  4790.3    0.16       0  5001.4    0.07       0  5007.4    0.16       0
Bank Sta=5001.4,5007.4
Exp/Cntr=0.3,0.1

Type RM Length L Ch R = 1,1322,561,561,561
BEGIN DESCRIPTION:
UNT 188 IN BOCR 2.0
END DESCRIPTION:
XS GIS Cut Line= 3
      3762449.63     10606810.18      3762249.61     10606860.19
      3761949.64     10607060.17
#Sta/Elev= 30
  4778.7  355.38  4789.0  351.81  4801.9  350.11  4820.0  345.27  4838.0  339.00
  4843.1  339.05  4850.9  334.71  4892.1  326.00  4925.6  322.86  4933.3  320.61
  4966.8  318.32  4987.9  318.89  5010.4  313.35  5013.2  312.85  5016.4  313.35
  5017.1  313.81  5028.4  319.70  5070.5  322.51  5085.5  325.12  5115.6  326.38
  5165.2  333.31  5178.7  333.27  5224.0  339.85  5237.3  343.02  5250.8  343.62
  5280.8  348.54  5309.4  351.38  5322.9  355.16  5337.9  356.65  5345.4  358.88
#Mann=5,-1,0
  4778.7    0.16       0  5010.4    0.07       0  5016.4    0.16       0
  5017.1    0.12       0  5224.0    0.16       0
Bank Sta=5010.4,5016.4
Exp/Cntr=0.3,0.1

Type RM Length L Ch R = 1,761,0,0,0
BEGIN DESCRIPTION:
UNT 188 IN BOCR 1.0
END DESCRIPTION:
XS GIS Cut Line= 3
      3762426.53     10606230.07      3761966.48     10606447.07
      3761923.17     10606906.18
#Sta/Elev= 30
  4583.9  348.45  4596.5  345.74  4619.3  345.33  4624.8  343.22  4642.0  343.29
  4647.6  340.83  4687.6  337.54  4710.4  334.25  4715.9  332.06  4755.9  328.46
  4761.5  329.16  4835.3  320.91  4852.6  317.77  4920.9  312.91  4972.0  313.56
  4989.2  311.96  4991.8  308.85  4994.5  308.35  4997.8  308.85  5000.6  310.47
  5023.1  313.64  5176.0  313.97  5220.1  318.84  5306.6  336.37  5416.2  342.51
  5427.0  344.12  5432.1  343.38  5437.2  345.03  5507.5  347.51  5553.7  350.88
#Mann=4,-1,0
  4583.9    0.12       0  4991.8    0.07       0  4997.8    0.12       0
  5416.2    0.16       0
Bank Sta=4991.8,4997.8
Exp/Cntr=0.3,0.1

Chan Stop Cuts=-1