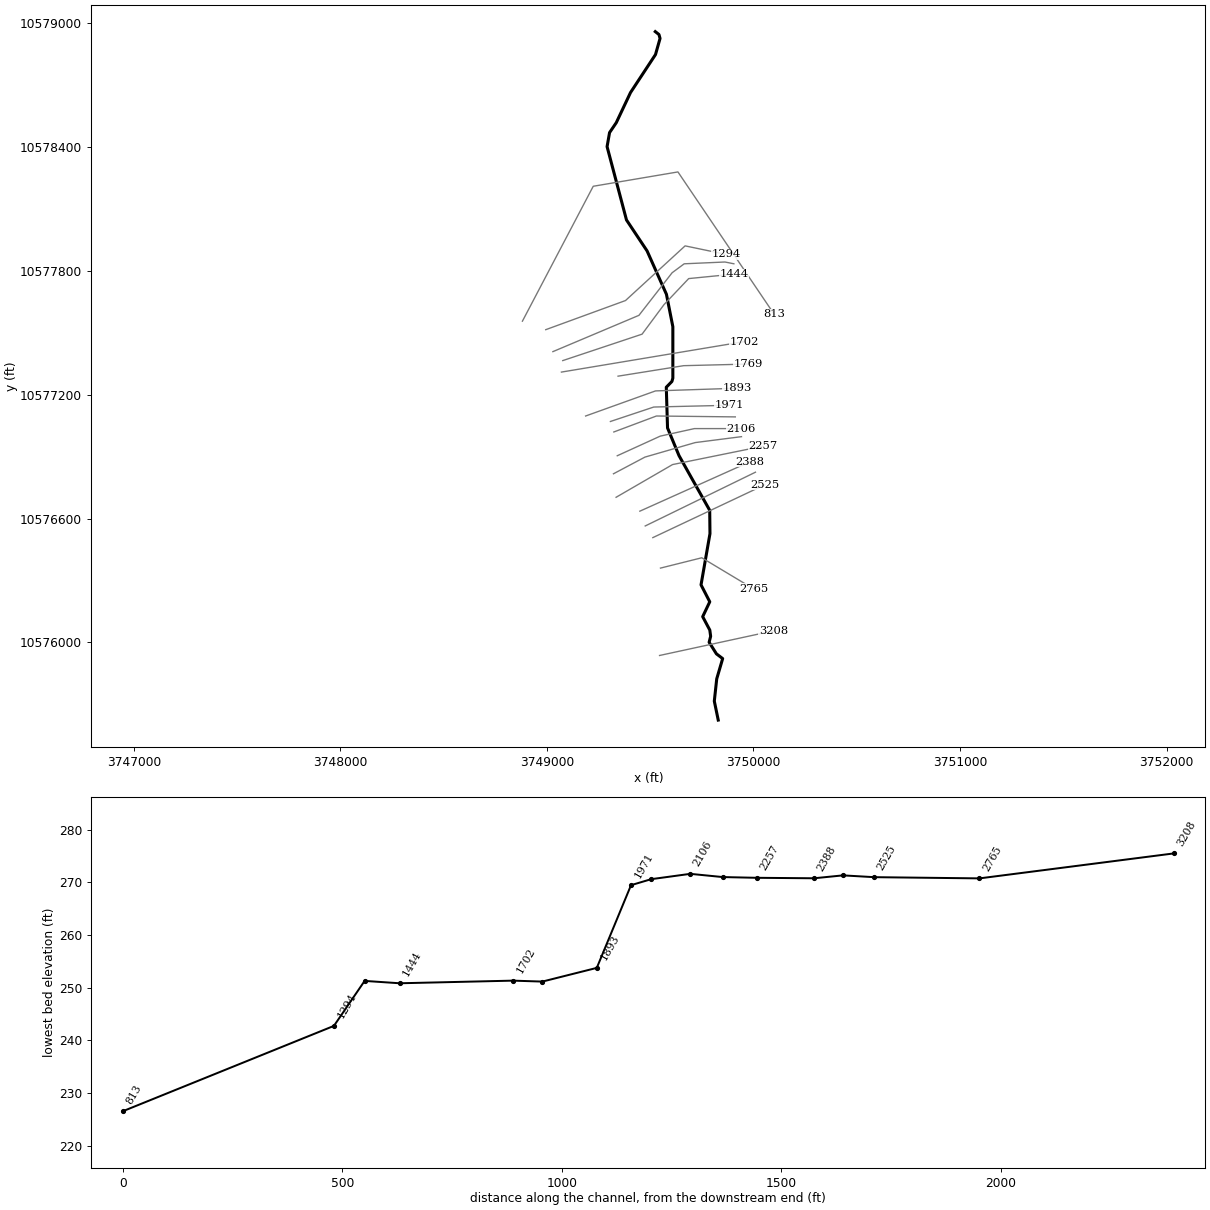
--- UNT 189 IN BOCR.prj (project) ---

Proj Title=UNT 189 IN BOCR Base Level Engineering
Current Plan=p01
Default Exp/Contr=0.3,0.1
English Units
Geom File=g01
Flow File=f01
Plan File=p01
Y Axis Title=Elevation
X Axis Title(PF)=Main Channel Distance
X Axis Title(XS)=Station
BEGIN DESCRIPTION:
UNT 189 IN BOCR
END DESCRIPTION:
DSS Export Rating Curves= 0
DSS Export Rating Curve Sorted= 0
DSS Export Volume Flow Curves= 0
DXF OffsetX= 0
DXF OffsetY= 0
DXF ScaleX= 1
DXF ScaleY= 10

--- UNT 189 IN BOCR.p01 (plan) ---

Plan Title=Multiple Run
Short Identifier=Multiple
Geom File=g01
Flow File=f01
Subcritical Flow
K Sum by GR= 0
Std Step Tol= 0.01
Critical Tol= 0.01
Num of Std Step Trials= 20
Max Error Tol= 0.3
Flow Tol Ratio= 0.001
Split Flow NTrial= 30
Split Flow Tol= 0.02
Split Flow Ratio= 0.02
Log Output Level= 0
Friction Slope Method= 1
Unsteady Friction Slope Method= 2
Unsteady Bridges Friction Slope Method= 1
Parabolic Critical Depth
Global Vel Dist=  1 , 1 , 1
Global Log Level= 0
CheckData=True
Encroach Param= -1, 0, 0, 0
BEGIN DESCRIPTION:
Multiple Run
END DESCRIPTION:

--- UNT 189 IN BOCR.f01 (steady flow) ---

Flow Title=Multiple
Program Version=4.10
Number of Profiles= 7
Profile Names=10-year,25-year,50-year,1pct_min,100-year,1pct_plu,500-year
River Rch & RM=UNT 189 IN BOCR,Reach-1         ,3208
     610     841    1037     941    1273    1721    1923
Boundary for River Rch & Prof#=UNT 189 IN BOCR,Reach-1         , 1
Up Type= 0
Dn Type= 3
Dn Slope=0.005
Boundary for River Rch & Prof#=UNT 189 IN BOCR,Reach-1         , 2
Up Type= 0
Dn Type= 3
Dn Slope=0.005
Boundary for River Rch & Prof#=UNT 189 IN BOCR,Reach-1         , 3
Up Type= 0
Dn Type= 3
Dn Slope=0.005
Boundary for River Rch & Prof#=UNT 189 IN BOCR,Reach-1         , 4
Up Type= 0
Dn Type= 3
Dn Slope=0.005
Boundary for River Rch & Prof#=UNT 189 IN BOCR,Reach-1         , 5
Up Type= 0
Dn Type= 3
Dn Slope=0.005
Boundary for River Rch & Prof#=UNT 189 IN BOCR,Reach-1         , 6
Up Type= 0
Dn Type= 3
Dn Slope=0.005
Boundary for River Rch & Prof#=UNT 189 IN BOCR,Reach-1         , 7
Up Type= 0
Dn Type= 3
Dn Slope=0.005
DSS Import GetInterval= 0
DSS Import GetPeak= 0
DSS Import FillOption= 0

--- UNT 189 IN BOCR.g01 (geometry) ---

Geom Title=Existing Conditions

River Reach=UNT 189 IN BOCR,Reach-1
Reach XY= 30
      3749829.27     10575624.21      3749810.25     10575716.00
      3749822.00     10575824.00      3749850.75     10575922.00
      3749820.50     10575945.00      3749785.25     10576001.00
      3749792.50     10576030.00      3749788.50     10576060.00
      3749754.00     10576125.00      3749788.25     10576197.00
      3749746.00     10576279.00      3749789.25     10576527.00
      3749788.00     10576640.00      3749639.25     10576905.00
      3749583.75     10577039.00      3749577.75     10577236.00
      3749605.00     10577264.00      3749609.50     10577280.00
      3749609.50     10577529.00      3749578.50     10577686.00
      3749484.75     10577896.00      3749385.00     10578046.00
      3749291.00     10578401.00      3749303.00     10578469.00
      3749335.50     10578517.00      3749404.50     10578663.00
      3749525.50     10578847.00      3749547.50     10578925.00
      3749542.25     10578944.00      3749524.50     10578958.00

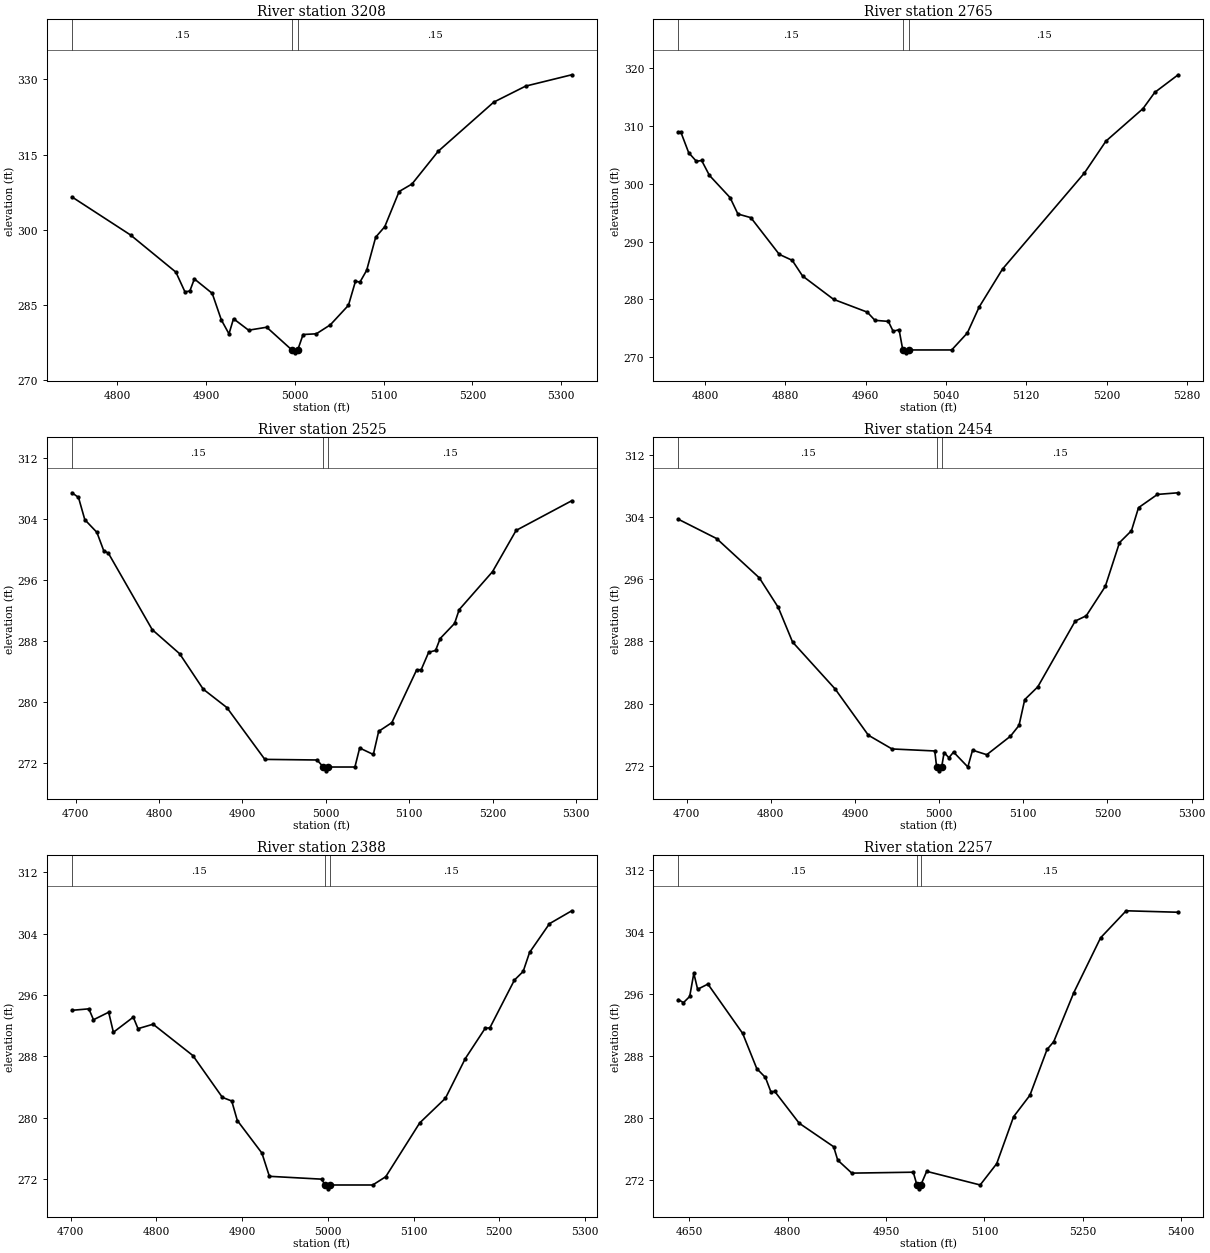
Type RM Length L Ch R = 1,3208,443,443,443
BEGIN DESCRIPTION:
UNT 189 IN BOCR 5.0
END DESCRIPTION:
XS GIS Cut Line= 2
      3749545.14     10575937.03      3750095.49     10576056.20
#Sta/Elev= 30
  4748.8  306.55  4814.8  298.97  4865.9  291.57  4876.1  287.64  4881.6  287.82
  4886.7  290.22  4906.8  287.35  4917.1  282.05  4925.7  279.28  4930.8  282.29
  4947.8  280.01  4968.2  280.60  4997.0  276.00  4999.8  275.50  5003.0  276.00
  5009.2  279.15  5024.1  279.29  5039.9  281.08  5060.3  284.97  5068.2  289.75
  5073.3  289.60  5080.8  291.93  5091.0  298.54  5101.2  300.62  5117.4  307.63
  5131.9  309.13  5161.4  315.64  5224.0  325.43  5259.9  328.62  5311.9  330.88
#Mann=3,-1,0
  4748.8    0.15       0  4997.0    0.05       0  5003.0    0.15       0
Bank Sta=4997,5003
Exp/Cntr=0.3,0.1

Type RM Length L Ch R = 1,2765,240,240,240
BEGIN DESCRIPTION:
UNT 189 IN BOCR 4.0
END DESCRIPTION:
XS GIS Cut Line= 3
      3749549.61     10576360.19      3749749.61     10576410.19
      3749999.61     10576260.19
#Sta/Elev= 30
  4773.5  308.88  4776.1  308.88  4783.8  305.37  4791.5  303.88  4796.7  304.03
  4804.4  301.46  4825.0  297.61  4832.8  294.77  4845.7  294.14  4874.0  287.79
  4886.9  286.76  4897.2  284.05  4928.1  280.01  4961.6  277.80  4969.3  276.38
  4982.6  276.20  4987.4  274.49  4993.3  274.77  4997.0  271.26  4999.8  270.76
  5003.0  271.26  5045.7  271.26  5061.3  274.20  5073.0  278.67  5096.3  285.25
  5177.9  301.87  5199.3  307.38  5236.2  313.00  5247.9  315.80  5271.2  318.85
#Mann=3,-1,0
  4773.5    0.15       0  4997.0    0.05       0  5003.0    0.15       0
Bank Sta=4997,5003
Exp/Cntr=0.3,0.1

Type RM Length L Ch R = 1,2525,71,71,71
BEGIN DESCRIPTION:
Mapping XS ac7a8ee4
END DESCRIPTION:
XS GIS Cut Line= 2
      3749512.57     10576507.76      3750054.89     10576763.74
#Sta/Elev= 30
  4695.4  307.39  4703.2  306.79  4710.8  303.87  4725.3  302.21  4733.5  299.81
  4739.1  299.48  4791.7  289.47  4824.6  286.32  4852.9  281.68  4881.2  279.28
  4926.8  272.49  4989.5  272.41  4997.0  271.49  4999.8  270.99  5003.0  271.49
  5034.9  271.49  5040.6  273.98  5057.0  273.13  5063.4  276.16  5079.2  277.30
  5108.9  284.19  5114.5  284.25  5123.4  286.51  5131.7  286.75  5137.2  288.31
  5154.5  290.29  5160.0  292.09  5200.0  297.06  5228.3  302.46  5295.1  306.35
#Mann=3,-1,0
  4695.4    0.15       0  4997.0    0.05       0  5003.0    0.15       0
Bank Sta=4997,5003
Exp/Cntr=0.3,0.1

Type RM Length L Ch R = 1,2454,66,66,66
BEGIN DESCRIPTION:
Mapping XS bc4b31e6
END DESCRIPTION:
XS GIS Cut Line= 2
      3749475.74     10576564.22      3750009.52     10576824.60
#Sta/Elev= 30
  4690.1  303.75  4735.6  301.26  4786.3  296.20  4808.8  292.39  4825.8  287.93
  4876.4  281.88  4915.9  275.92  4944.0  274.15  4994.8  273.89  4997.0  271.83
  4999.8  271.33  5003.0  271.83  5005.9  273.69  5011.6  273.02  5017.1  273.75
  5034.1  271.83  5039.7  273.99  5056.6  273.41  5084.7  275.79  5094.9  277.18
  5101.7  280.51  5117.2  282.15  5161.7  290.63  5174.8  291.31  5197.4  295.09
  5214.3  300.74  5228.5  302.27  5236.9  305.24  5259.4  306.95  5284.0  307.16
#Mann=3,-1,0
  4690.1    0.15       0  4997.0    0.05       0  5003.0    0.15       0
Bank Sta=4997,5003
Exp/Cntr=0.3,0.1

Type RM Length L Ch R = 1,2388,131,131,131
BEGIN DESCRIPTION:
Mapping XS cf82bf76
END DESCRIPTION:
XS GIS Cut Line= 2
      3749449.64     10576635.81      3749981.31     10576874.51
#Sta/Elev= 30
  4701.7  294.01  4721.4  294.20  4726.8  292.78  4744.5  293.76  4750.0  291.15
  4773.2  293.12  4778.7  291.62  4796.3  292.20  4842.7  288.12  4877.1  282.68
  4888.0  282.21  4894.5  279.67  4923.2  275.43  4931.9  272.41  4992.7  272.04
  4997.0  271.28  4999.8  270.78  5003.0  271.28  5052.4  271.28  5067.6  272.36
  5107.2  279.36  5137.2  282.57  5160.3  287.72  5183.5  291.67  5189.0  291.73
  5217.6  297.94  5227.8  299.06  5235.3  301.54  5258.5  305.28  5284.5  306.96
#Mann=3,-1,0
  4701.7    0.15       0  4997.0    0.05       0  5003.0    0.15       0
Bank Sta=4997,5003
Exp/Cntr=0.3,0.1

Type RM Length L Ch R = 1,2257,77,77,77
BEGIN DESCRIPTION:
UNT 189 IN BOCR 3.0
END DESCRIPTION:
XS GIS Cut Line= 3
      3749334.67     10576703.10      3749608.08     10576861.51
      3750045.57     10576950.31
#Sta/Elev= 30
  4633.1  295.32  4640.9  294.92  4650.4  295.72  4656.7  298.71  4662.5  296.65
  4678.2  297.32  4731.2  290.95  4752.8  286.39  4765.9  285.26  4774.3  283.39
  4780.1  283.46  4817.4  279.35  4870.0  276.31  4876.2  274.58  4897.7  272.90
  4991.5  273.02  4997.0  271.37  4999.8  270.87  5003.0  271.37  5011.9  273.13
  5093.5  271.37  5118.7  274.12  5144.5  280.19  5169.4  282.96  5195.5  288.87
  5205.7  289.88  5236.4  296.23  5277.2  303.30  5316.2  306.79  5395.5  306.60
#Mann=3,-1,0
  4633.1    0.15       0  4997.0    0.05       0  5003.0    0.15       0
Bank Sta=4997,5003
Exp/Cntr=0.3,0.1

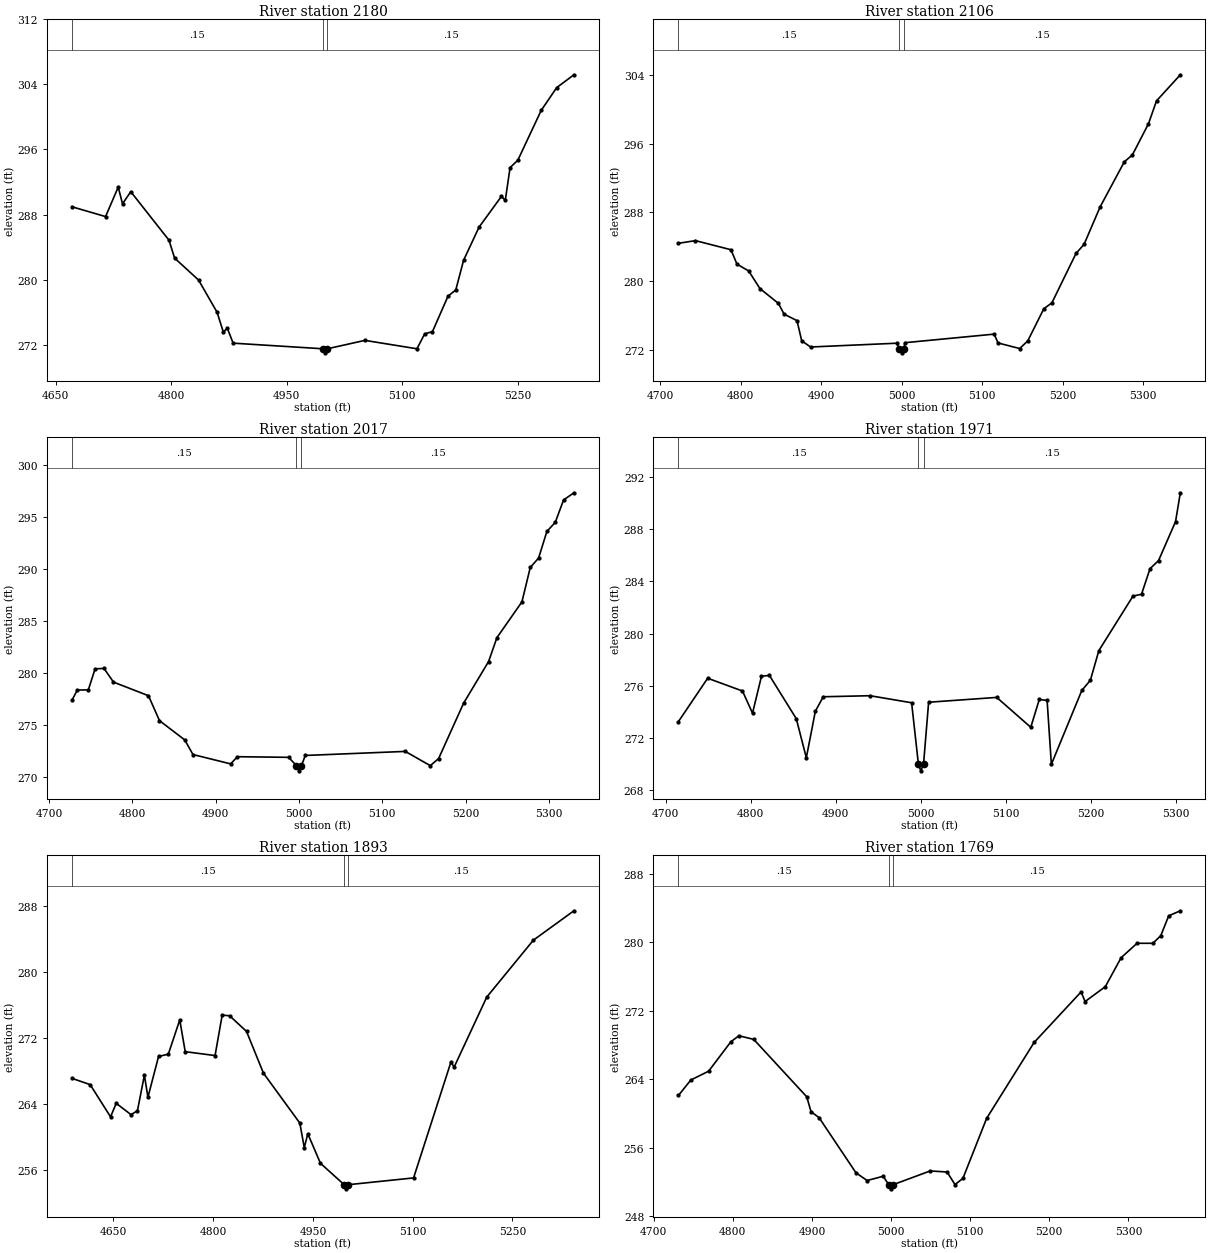
Type RM Length L Ch R = 1,2180,74,74,74
BEGIN DESCRIPTION:
Mapping XS 818f7e5c
END DESCRIPTION:
XS GIS Cut Line= 4
      3749322.03     10576816.97      3749474.36     10576897.69
      3749717.85     10576968.01      3749941.79     10576996.65
#Sta/Elev= 30
  4671.5  288.95  4715.0  287.75  4731.4  291.37  4737.0  289.32  4747.7  290.81
  4797.4  284.84  4804.6  282.65  4835.7  279.96  4859.8  275.99  4867.9  273.56
  4873.1  274.03  4880.6  272.20  4997.0  271.51  4999.8  271.01  5003.0  271.51
  5051.7  272.54  5119.3  271.51  5129.3  273.34  5139.4  273.61  5159.6  277.97
  5169.7  278.73  5179.8  282.37  5199.9  286.45  5228.9  290.22  5234.0  289.75
  5240.2  293.76  5250.3  294.68  5280.6  300.79  5300.7  303.59  5323.1  305.17
#Mann=3,-1,0
  4671.5    0.15       0  4997.0    0.05       0  5003.0    0.15       0
Bank Sta=4997,5003
Exp/Cntr=0.3,0.1

Type RM Length L Ch R = 1,2106,89,89,89
BEGIN DESCRIPTION:
Mapping XS cad5427a
END DESCRIPTION:
XS GIS Cut Line= 4
      3749340.28     10576904.22      3749548.58     10576999.26
      3749713.95     10577035.72      3749939.26     10577035.72
#Sta/Elev= 30
  4722.6  284.38  4743.7  284.69  4787.8  283.63  4795.3  281.95  4809.8  281.16
  4823.8  279.11  4846.8  277.38  4853.8  276.13  4869.9  275.37  4875.7  273.03
  4886.7  272.30  4993.6  272.74  4997.0  272.12  4999.8  271.62  5003.0  272.12
  5003.8  272.80  5114.9  273.80  5119.7  272.77  5146.6  272.12  5156.6  273.01
  5176.6  276.76  5186.6  277.44  5216.6  283.20  5226.6  284.26  5246.6  288.63
  5276.6  293.87  5286.6  294.67  5306.6  298.30  5316.6  300.97  5346.2  304.01
#Mann=3,-1,0
  4722.6    0.15       0  4997.0    0.05       0  5003.0    0.15       0
Bank Sta=4997,5003
Exp/Cntr=0.3,0.1

Type RM Length L Ch R = 1,2017,46,46,46
BEGIN DESCRIPTION:
UNT 189 IN BOCR 2.0
END DESCRIPTION:
XS GIS Cut Line= 3
      3749323.74     10577019.34      3749530.04     10577096.71
      3749911.99     10577092.37
#Sta/Elev= 30
  4727.7  277.42  4734.0  278.39  4747.2  278.40  4755.3  280.42  4766.0  280.47
  4777.4  279.15  4819.4  277.84  4832.6  275.44  4862.9  273.59  4872.8  272.18
  4918.0  271.28  4926.2  271.97  4987.6  271.91  4997.0  271.11  4999.8  270.61
  5003.0  271.11  5007.6  272.09  5127.6  272.48  5157.6  271.11  5167.6  271.79
  5197.6  277.12  5227.6  281.13  5237.6  283.43  5267.6  286.87  5277.6  290.18
  5287.6  291.09  5297.6  293.66  5307.6  294.52  5317.6  296.68  5330.0  297.37
#Mann=3,-1,0
  4727.7    0.15       0  4997.0    0.05       0  5003.0    0.15       0
Bank Sta=4997,5003
Exp/Cntr=0.3,0.1

Type RM Length L Ch R = 1,1971,78,78,78
BEGIN DESCRIPTION:
Mapping XS 8c50ea9a
END DESCRIPTION:
XS GIS Cut Line= 3
      3749307.10     10577070.13      3749517.02     10577140.11
      3749885.24     10577148.77
#Sta/Elev= 30
  4715.1  273.25  4749.4  276.57  4790.3  275.59  4802.1  273.89  4812.6  276.72
  4821.9  276.79  4853.5  273.47  4865.3  270.47  4875.9  274.04  4885.2  275.15
  4940.2  275.23  4989.0  274.69  4997.0  269.97  4999.8  269.47  5003.0  269.97
  5009.0  274.73  5089.0  275.10  5129.0  272.81  5139.0  274.94  5148.2  274.87
  5153.2  269.97  5189.0  275.64  5199.0  276.41  5209.0  278.69  5249.1  282.87
  5259.1  283.01  5269.1  284.97  5279.1  285.59  5299.1  288.58  5304.7  290.79
#Mann=3,-1,0
  4715.1    0.15       0  4997.0    0.05       0  5003.0    0.15       0
Bank Sta=4997,5003
Exp/Cntr=0.3,0.1

Type RM Length L Ch R = 1,1893,124,124,124
BEGIN DESCRIPTION:
Mapping XS 8f633400
END DESCRIPTION:
XS GIS Cut Line= 3
      3749187.12     10577096.69      3749525.70     10577218.23
      3749920.65     10577231.25
#Sta/Elev= 30
  4587.7  267.12  4614.9  266.37  4645.6  262.47  4654.1  264.11  4676.3  262.74
  4686.0  263.20  4696.5  267.51  4701.8  264.84  4717.8  269.77  4732.5  270.05
  4749.7  274.19  4757.9  270.35  4802.8  269.88  4813.5  274.77  4824.7  274.69
  4850.1  272.80  4875.6  267.75  4930.3  261.72  4937.0  258.75  4942.3  260.43
  4961.3  256.86  4997.0  254.27  4999.8  253.77  5003.0  254.27  5101.4  255.09
  5157.5  269.07  5162.5  268.50  5211.5  276.95  5281.5  283.82  5342.6  287.38
#Mann=3,-1,0
  4587.7    0.15       0  4997.0    0.05       0  5003.0    0.15       0
Bank Sta=4997,5003
Exp/Cntr=0.3,0.1

Type RM Length L Ch R = 1,1769,67,67,67
BEGIN DESCRIPTION:
Mapping XS 700f9e8f
END DESCRIPTION:
XS GIS Cut Line= 3
      3749344.17     10577289.62      3749661.86     10577340.40
      3749974.34     10577348.21
#Sta/Elev= 30
  4731.3  262.09  4746.9  263.89  4769.4  264.92  4797.6  268.37  4807.7  269.06
  4826.4  268.64  4893.5  261.92  4898.8  260.19  4909.0  259.49  4955.6  253.05
  4969.7  252.14  4990.0  252.64  4997.0  251.67  4999.8  251.17  5003.0  251.67
  5049.4  253.26  5070.8  253.14  5080.8  251.67  5090.8  252.39  5120.8  259.41
  5180.8  268.28  5240.2  274.19  5245.2  273.06  5270.8  274.80  5290.8  278.19
  5310.9  279.87  5330.9  279.87  5340.9  280.76  5350.9  283.08  5365.6  283.67
#Mann=3,-1,0
  4731.3    0.15       0  4997.0    0.05       0  5003.0    0.15       0
Bank Sta=4997,5003
Exp/Cntr=0.3,0.1

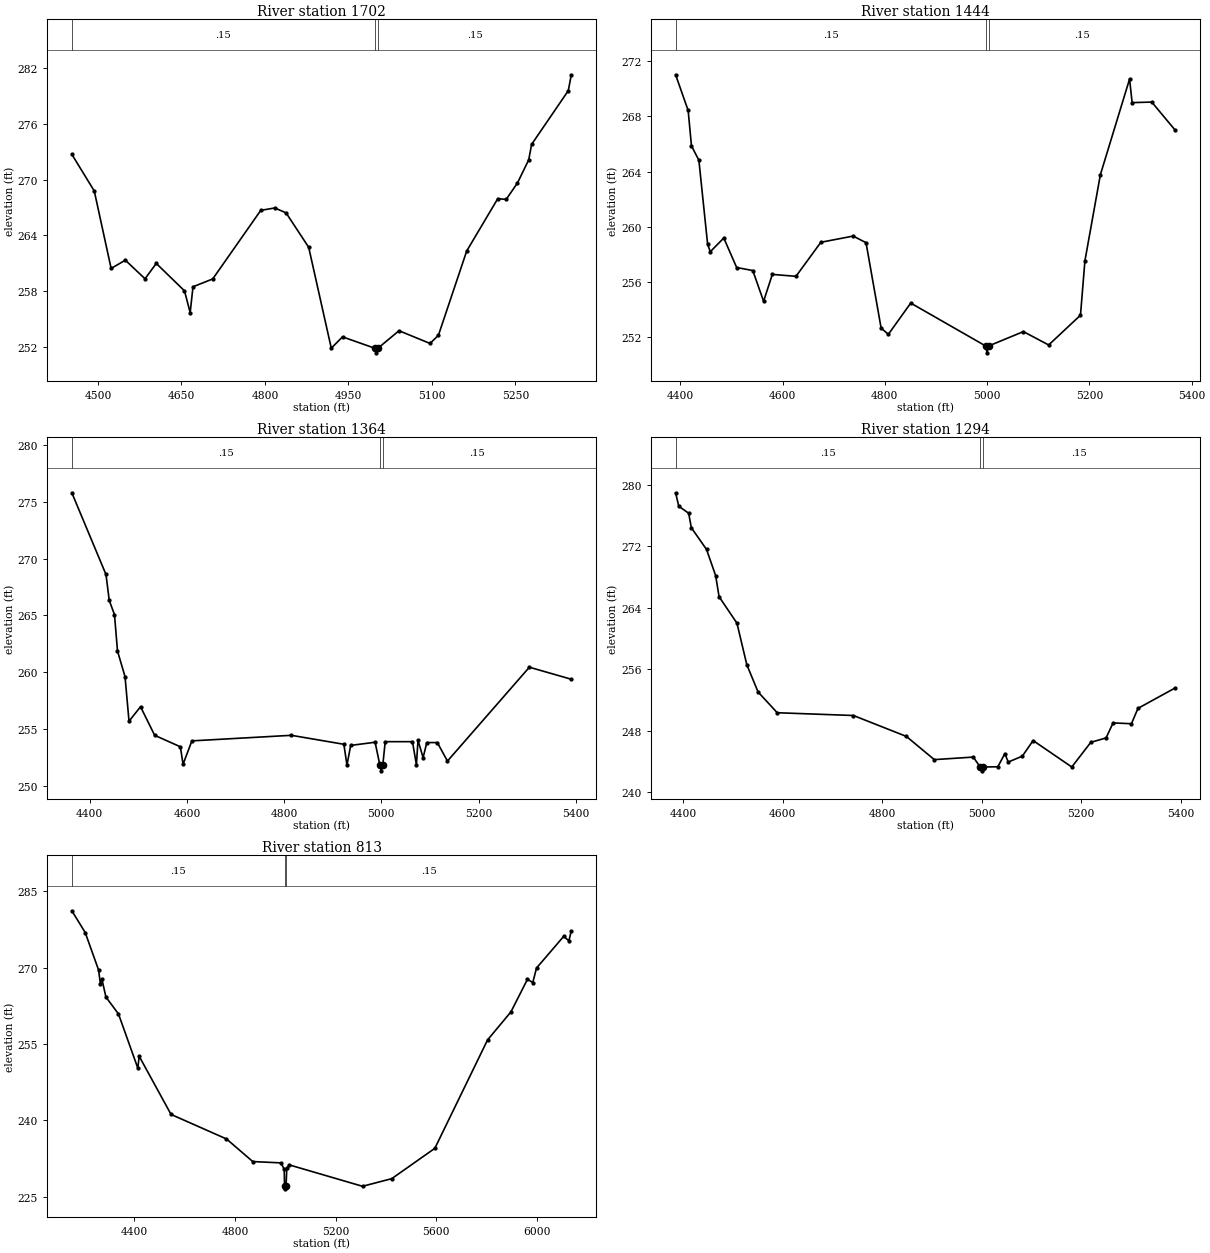
Type RM Length L Ch R = 1,1702,258,258,258
BEGIN DESCRIPTION:
Mapping XS 2f46c4c9
END DESCRIPTION:
XS GIS Cut Line= 2
      3749069.94     10577309.37      3749955.03     10577456.89
#Sta/Elev= 30
  4453.0  272.71  4493.3  268.77  4523.6  260.43  4549.1  261.32  4584.5  259.32
  4604.7  260.97  4655.4  258.02  4665.6  255.68  4670.7  258.46  4706.1  259.30
  4792.4  266.68  4817.6  266.94  4837.9  266.41  4878.5  262.71  4919.1  251.85
  4939.3  253.07  4997.0  251.85  4999.8  251.35  5003.0  251.85  5040.8  253.73
  5096.5  252.36  5111.6  253.24  5162.4  262.31  5218.2  267.94  5233.3  267.86
  5253.6  269.63  5273.8  272.12  5279.0  273.78  5344.9  279.56  5350.3  281.27
#Mann=3,-1,0
  4453.0    0.15       0  4997.0    0.05       0  5003.0    0.15       0
Bank Sta=4997,5003
Exp/Cntr=0.3,0.1

Type RM Length L Ch R = 1,1444,80,80,80
BEGIN DESCRIPTION:
Mapping XS 2b6c95f3
END DESCRIPTION:
XS GIS Cut Line= 5
      3749076.41     10577364.98      3749460.51     10577493.02
      3749566.85     10577636.25      3749686.21     10577762.12
      3749905.01     10577783.78
#Sta/Elev= 30
  4390.9  271.02  4415.4  268.43  4421.9  265.86  4436.4  264.82  4453.5  258.71
  4458.8  258.19  4485.1  259.18  4510.2  257.04  4541.8  256.82  4562.9  254.59
  4580.0  256.54  4626.2  256.40  4674.9  258.87  4738.1  259.32  4763.2  258.84
  4792.7  252.65  4806.8  252.19  4850.6  254.46  4997.0  251.35  4999.8  250.85
  5003.0  251.35  5070.9  252.39  5120.3  251.42  5182.5  253.58  5191.2  257.53
  5221.4  263.77  5278.5  270.71  5283.5  269.00  5321.9  269.04  5367.5  267.01
#Mann=3,-1,0
  4390.9    0.15       0  4997.0    0.05       0  5003.0    0.15       0
Bank Sta=4997,5003
Exp/Cntr=0.3,0.1

Type RM Length L Ch R = 1,1364,70,70,70
BEGIN DESCRIPTION:
Mapping XS bee44071
END DESCRIPTION:
XS GIS Cut Line= 6
      3749028.67     10577408.39      3749445.32     10577584.16
      3749605.91     10577790.33      3749664.50     10577833.73
      3749861.99     10577842.41      3749904.97     10577833.82
#Sta/Elev= 30
  4363.0  275.80  4433.3  268.60  4440.0  266.32  4450.8  265.06  4457.0  261.86
  4472.5  259.60  4480.7  255.67  4504.4  256.95  4533.5  254.43  4586.4  253.42
  4591.9  251.88  4610.1  253.94  4814.8  254.43  4922.9  253.64  4929.3  251.80
  4936.9  253.54  4987.2  253.82  4997.0  251.80  4999.8  251.30  5003.0  251.80
  5008.0  253.87  5064.1  253.87  5072.2  251.84  5075.5  253.99  5086.0  252.46
  5093.6  253.79  5115.3  253.79  5136.1  252.16  5304.7  260.43  5391.0  259.37
#Mann=3,-1,0
  4363.0    0.15       0  4997.0    0.05       0  5003.0    0.15       0
Bank Sta=4997,5003
Exp/Cntr=0.3,0.1

Type RM Length L Ch R = 1,1294,481,481,481
BEGIN DESCRIPTION:
Mapping XS 04182de4
END DESCRIPTION:
XS GIS Cut Line= 4
      3748993.95     10577514.73      3749380.22     10577655.78
      3749668.84     10577920.54      3749865.42     10577879.49
#Sta/Elev= 30
  4384.9  278.94  4391.2  277.19  4411.1  276.28  4416.5  274.39  4447.0  271.57
  4465.4  268.15  4472.2  265.42  4508.1  261.98  4528.0  256.56  4550.6  253.02
  4589.1  250.32  4742.2  249.96  4848.6  247.24  4904.7  244.22  4983.0  244.55
  4997.0  243.26  4999.8  242.76  5003.0  243.26  5032.4  243.29  5046.5  245.00
  5053.3  243.90  5081.7  244.68  5103.3  246.70  5181.0  243.26  5219.2  246.47
  5249.9  247.04  5264.0  249.00  5300.9  248.89  5314.0  250.89  5388.6  253.54
#Mann=3,-1,0
  4384.9    0.15       0  4997.0    0.05       0  5003.0    0.15       0
Bank Sta=4997,5003
Exp/Cntr=0.3,0.1

Type RM Length L Ch R = 1,813,0,0,0
BEGIN DESCRIPTION:
UNT 189 IN BOCR 1.0
END DESCRIPTION:
XS GIS Cut Line= 4
      3748881.07     10577555.92      3749223.97     10578209.16
      3749634.12     10578278.61      3750100.70     10577588.50
#Sta/Elev= 30
  4150.9  281.19  4204.1  276.92  4257.4  269.54  4264.6  266.79  4270.2  267.84
  4286.6  264.23  4336.4  260.93  4413.3  250.29  4418.9  252.60  4545.6  241.18
  4766.1  236.36  4870.7  231.92  4982.6  231.66  4995.8  230.41  4997.0  227.06
  4999.8  226.56  5003.0  227.06  5006.0  230.59  5016.1  231.26  5307.2  227.06
  5423.5  228.56  5594.9  234.52  5804.6  255.82  5897.5  261.32  5963.4  267.74
  5984.4  267.08  5999.3  269.94  6107.2  276.15  6128.2  275.30  6137.7  277.25
#Mann=3,-1,0
  4150.9    0.15       0  4997.0    0.05       0  5003.0    0.15       0
Bank Sta=4997,5003
Exp/Cntr=0.3,0.1

Chan Stop Cuts=-1