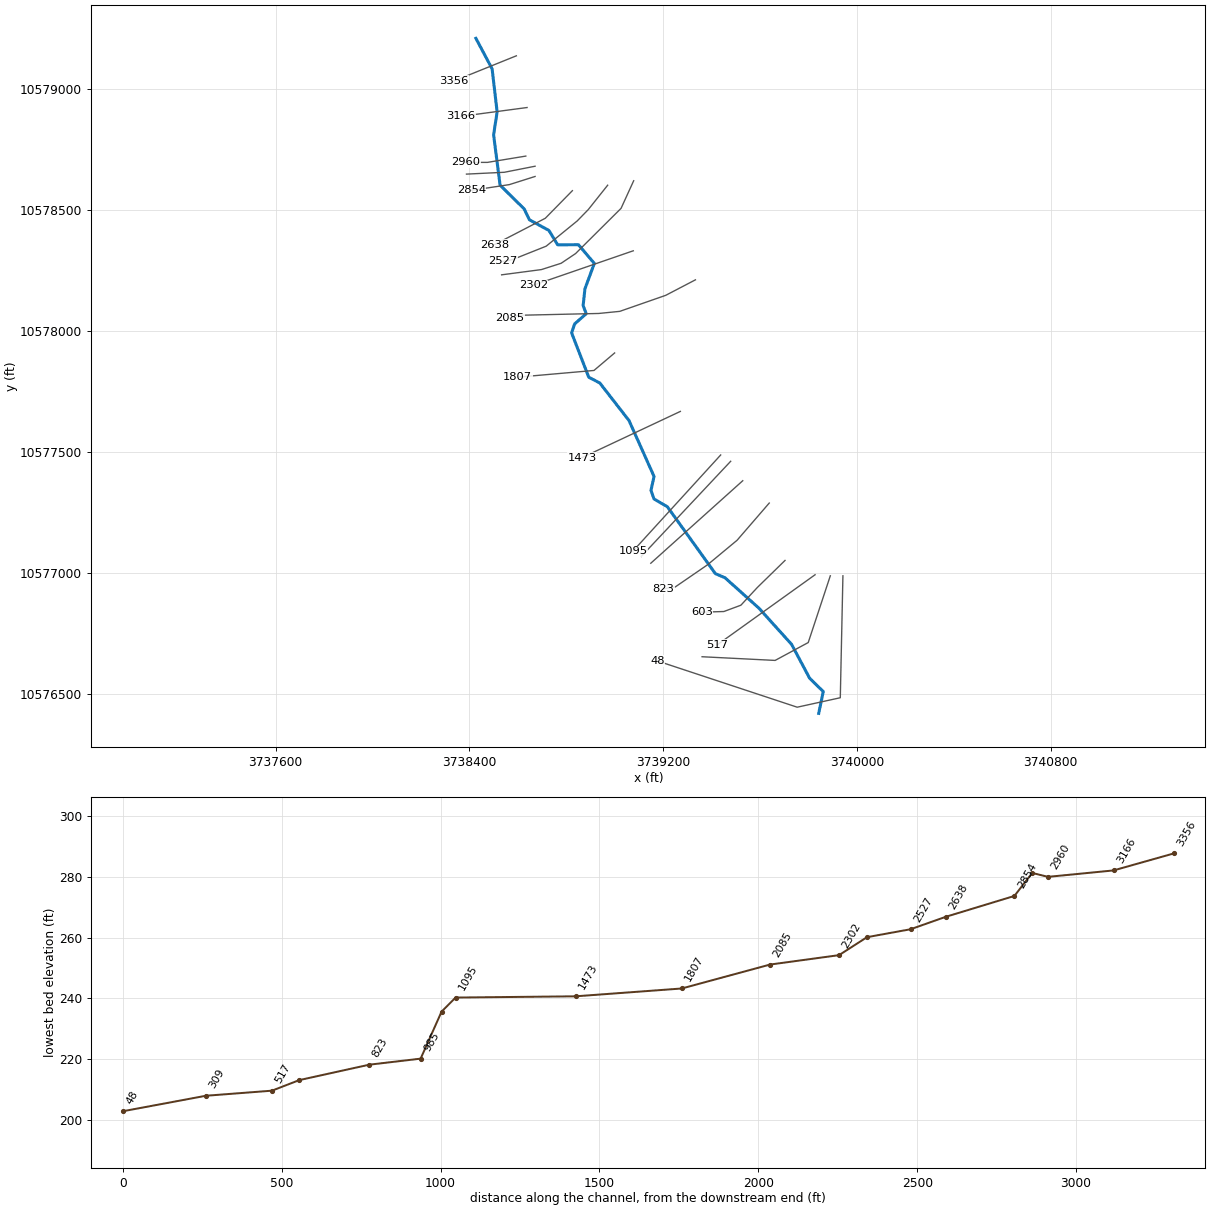
--- UNT 192 IN BOCR.prj (project) ---

Proj Title=UNT 192 IN BOCR Base Level Engineering
Current Plan=p01
Default Exp/Contr=0.3,0.1
English Units
Geom File=g01
Flow File=f01
Plan File=p01
Y Axis Title=Elevation
X Axis Title(PF)=Main Channel Distance
X Axis Title(XS)=Station
BEGIN DESCRIPTION:
UNT 192 IN BOCR
END DESCRIPTION:
DSS Export Rating Curves= 0
DSS Export Rating Curve Sorted= 0
DSS Export Volume Flow Curves= 0
DXF OffsetX= 0
DXF OffsetY= 0
DXF ScaleX= 1
DXF ScaleY= 10

--- UNT 192 IN BOCR.p01 (plan) ---

Plan Title=Multiple Run
Short Identifier=Multiple
Geom File=g01
Flow File=f01
Subcritical Flow
K Sum by GR= 0
Std Step Tol= 0.01
Critical Tol= 0.01
Num of Std Step Trials= 20
Max Error Tol= 0.3
Flow Tol Ratio= 0.001
Split Flow NTrial= 30
Split Flow Tol= 0.02
Split Flow Ratio= 0.02
Log Output Level= 0
Friction Slope Method= 1
Unsteady Friction Slope Method= 2
Unsteady Bridges Friction Slope Method= 1
Parabolic Critical Depth
Global Vel Dist=  1 , 1 , 1
Global Log Level= 0
CheckData=True
Encroach Param= -1, 0, 0, 0
BEGIN DESCRIPTION:
Multiple Run
END DESCRIPTION:

--- UNT 192 IN BOCR.f01 (steady flow) ---

Flow Title=Multiple
Number of Profiles=7
Profile Names=10-year,25-year,50-year,1pct_min,100-year,1pct_plu,500-year
River Rch & RM= UNT 192 IN BOCR,Reach-1,3356
     152     190     219     187     253     343     339
Boundary for River Rch & Prof#=UNT 192 IN BOCR,Reach-1,1
Up Type=0
Dn Type=3
Dn Slope=0.005
Boundary for River Rch & Prof#=UNT 192 IN BOCR,Reach-1,2
Up Type=0
Dn Type=3
Dn Slope=0.005
Boundary for River Rch & Prof#=UNT 192 IN BOCR,Reach-1,3
Up Type=0
Dn Type=3
Dn Slope=0.005
Boundary for River Rch & Prof#=UNT 192 IN BOCR,Reach-1,4
Up Type=0
Dn Type=3
Dn Slope=0.005
Boundary for River Rch & Prof#=UNT 192 IN BOCR,Reach-1,5
Up Type=0
Dn Type=3
Dn Slope=0.005
Boundary for River Rch & Prof#=UNT 192 IN BOCR,Reach-1,6
Up Type=0
Dn Type=3
Dn Slope=0.005
Boundary for River Rch & Prof#=UNT 192 IN BOCR,Reach-1,7
Up Type=0
Dn Type=3
Dn Slope=0.005

--- UNT 192 IN BOCR.g01 (geometry) ---

Geom Title=Existing Conditions
Program Version=4.10

River Reach=UNT 192 IN BOCR ,Reach-1
Reach XY= 30
      3738426.79     10579209.22      3738493.62      10579083.4
      3738514.45     10578905.62      3738499.87     10578810.48
      3738526.63     10578602.97        3738626.       10578505.
      3738647.75       10578460.      3738728.35     10578415.85
       3738764.5     10578356.65      3738850.01     10578357.09
      3738915.75       10578280.        3738877.       10578175.
       3738869.5       10578106.      3738882.25     10578072.18
       3738834.5       10578030.        3738822.       10577993.
      3738892.75       10577810.       3738938.5       10577786.
        3739059.       10577631.      3739162.28     10577400.38
      3739149.65     10577342.71      3739162.15      10577307.3
      3739217.26     10577275.19       3739415.5       10576999.
      3739455.25       10576982.      3739595.75       10576856.
      3739730.25       10576707.      3739804.75       10576567.
        3739861.       10576512.      3739842.25       10576422.

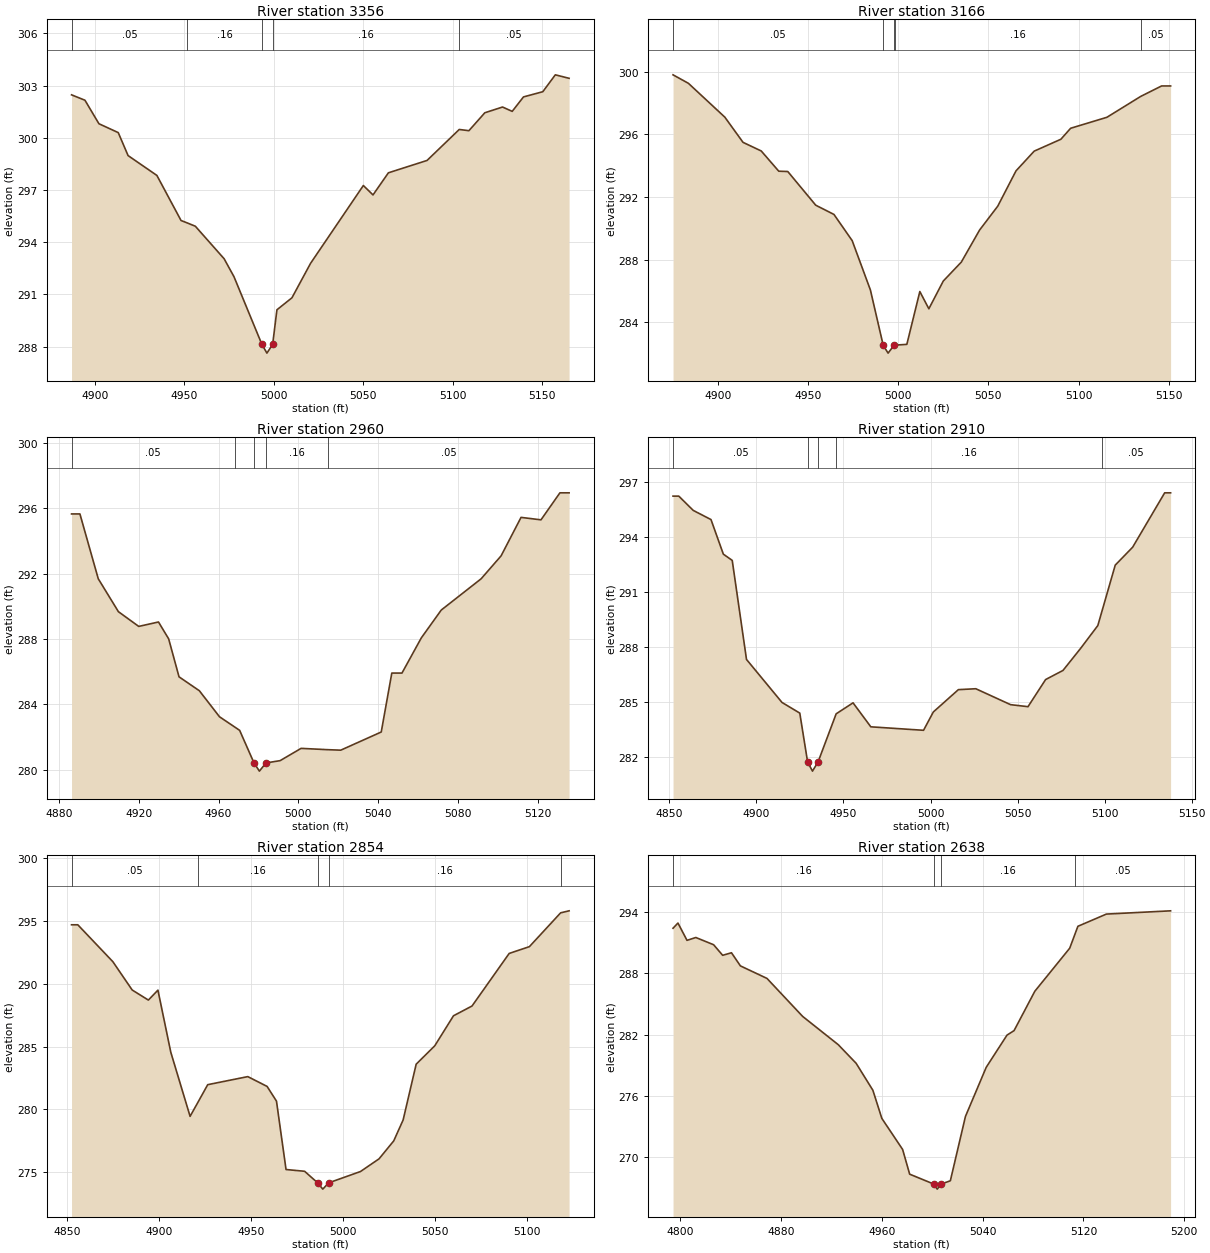
Type RM Length L Ch R = 1 ,3356    ,190,190,190
BEGIN DESCRIPTION:
UNT 192 IN BOCR 6.0
END DESCRIPTION:
XS GIS Cut Line= 2
      3738593.81      10579137.1      3738335.97     10579032.92
#Sta/Elev= 30
  4886.9  302.47  4894.4  302.16  4902.2  300.81    4913   300.3  4918.5  298.98
  4934.6  297.84  4948.1  295.25  4951.6  295.11  4956.1  294.92  4972.2  293.05
  4977.7  292.02  4993.3  288.13  4996.1  287.63  4999.3  288.13  5001.7  290.12
  5010.1  290.81  5020.5  292.79    5050  297.26  5055.4  296.72    5064  297.99
  5085.6   298.7  5103.6  300.48    5109  300.41  5117.9  301.44  5127.8  301.77
  5133.2  301.52  5139.5  302.35  5150.3  302.65  5157.3  303.62    5165  303.42
#Mann= 5 ,-1 , 0
  4886.9     .05       0  4951.6     .16       0  4993.3     .07       0
  4999.3     .16       0  5103.6     .05       0
Bank Sta=4993.3,4999.3
XS Rating Curve= 0 ,0
Exp/Cntr=0.3,0.1

Type RM Length L Ch R = 1 ,3166    ,206,206,206
BEGIN DESCRIPTION:
Mapping XS 7691de16
END DESCRIPTION:
XS GIS Cut Line= 2
      3738638.05     10578923.55      3738364.67      10578887.1
#Sta/Elev= 30
  4875.2   299.8  4883.7  299.26  4903.9   297.1    4914  295.49  4924.1  294.94
  4933.8  293.65  4938.8  293.63  4954.3  291.48  4964.4  290.89  4974.5  289.22
  4984.6  286.07  4991.7  282.54  4994.4  282.04  4997.7  282.54  4998.4  282.55
  5004.8   282.6    5012  285.97    5017  284.87    5025  286.64    5035  287.85
  5045.1  289.89  5055.2  291.42  5065.3  293.67  5075.4  294.93  5090.2  295.69
  5095.6  296.39  5115.7  297.09  5134.4  298.42    5146  299.09    5151  299.09
#Mann= 5 ,-1 , 0
  4875.2     .05       0  4991.7     .07       0  4997.7     .05       0
  4998.4     .16       0  5134.4     .05       0
Bank Sta=4991.7,4997.7
XS Rating Curve= 0 ,0
Exp/Cntr=0.3,0.1

Type RM Length L Ch R = 1 ,2960    ,50,50,50
BEGIN DESCRIPTION:
Mapping XS 508869ef
END DESCRIPTION:
XS GIS Cut Line= 3
      3738632.84     10578723.03      3738474.01     10578696.99
      3738385.46     10578696.99
#Sta/Elev= 30
  4886.3  295.64  4890.5  295.64  4899.7  291.68  4909.8  289.67    4920  288.77
  4929.9  289.04    4935  288.01  4940.2  285.69  4950.4  284.84  4960.5  283.25
  4968.3  282.61  4970.6  282.42  4977.8  280.43  4980.5  279.93  4983.8  280.43
  4990.9  280.57  5001.4  281.32  5014.8  281.24  5021.3  281.21  5041.6  282.32
  5046.9  285.92    5052  285.92  5061.7  288.07  5071.7  289.77  5091.7  291.68
  5101.7  293.08  5111.7  295.43  5121.7  295.28  5131.2  296.93  5135.8  296.93
#Mann= 5 ,-1 , 0
  4886.3     .05       0  4968.3     .16       0  4977.8     .07       0
  4983.8     .16       0  5014.8     .05       0
Bank Sta=4977.8,4983.8
XS Rating Curve= 0 ,0
Exp/Cntr=0.3,0.1

Type RM Length L Ch R = 1 ,2910    ,56,56,56
BEGIN DESCRIPTION:
Mapping XS 5a24e14e
END DESCRIPTION:
XS GIS Cut Line= 3
      3738671.03     10578681.15      3738544.11     10578656.19
      3738387.84      10578648.6
#Sta/Elev= 30
  4852.1  296.23  4855.4  296.23  4863.7  295.45  4873.9  294.95    4881  293.06
  4886.1  292.72  4894.3  287.31  4914.7  284.96  4924.9  284.38  4929.4  281.71
  4932.2  281.21  4935.4  281.71  4945.8  284.34  4955.5  284.94  4965.7  283.63
    4996  283.44  5001.6  284.44    5016  285.66    5026  285.71    5046  284.84
    5056  284.73  5066.1  286.21  5076.1  286.71  5086.1   287.9  5096.1  289.16
  5098.4  289.92  5106.1  292.46  5116.1  293.44  5134.5  296.41  5137.9  296.41
#Mann= 5 ,-1 , 0
  4852.1     .05       0  4929.4     .07       0  4935.4     .05       0
  4945.8     .16       0  5098.4     .05       0
Bank Sta=4929.4,4935.4
XS Rating Curve= 0 ,0
Exp/Cntr=0.3,0.1

Type RM Length L Ch R = 1 ,2854    ,216,216,216
BEGIN DESCRIPTION:
Mapping XS 7f8e9484
END DESCRIPTION:
XS GIS Cut Line= 3
      3738671.08     10578638.84      3738564.73      10578605.2
      3738407.37     10578581.32
#Sta/Elev= 30
  4852.4  294.69  4855.8  294.69  4874.9  291.75  4885.4   289.5  4894.2   288.7
  4899.4  289.49  4906.4  284.55  4916.9  279.45  4921.4  280.63  4926.5  281.97
  4948.3  282.61  4958.8  281.83  4963.9  280.66  4969.1  275.22  4979.2  275.08
  4986.3  274.16  4989.1  273.66  4992.3  274.16  5009.6  275.06  5019.7  276.07
  5027.7   277.5  5032.8  279.16  5039.9   283.6    5050  285.06  5060.2  287.45
  5070.3  288.23  5090.5  292.41  5101.5  292.95  5118.5  295.64  5123.1   295.8
#Mann= 5 ,-1 , 0
  4852.4     .05       0  4921.4     .16       0  4986.3     .07       0
  4992.3     .16       0  5118.5     .05       0
Bank Sta=4986.3,4992.3
XS Rating Curve= 0 ,0
Exp/Cntr=0.3,0.1

Type RM Length L Ch R = 1 ,2638    ,111,111,111
BEGIN DESCRIPTION:
UNT 192 IN BOCR 5.0
END DESCRIPTION:
XS GIS Cut Line= 3
      3738825.15     10578580.24      3738713.38     10578466.31
      3738504.28     10578357.97
#Sta/Elev= 30
  4794.1  292.44    4798  292.95  4805.2  291.25  4812.2  291.53  4826.3  290.82
  4833.5  289.78  4840.5  290.03  4847.6  288.74  4868.7  287.51    4897  283.78
  4925.3     281  4939.5  279.17  4952.8  276.52  4959.9  273.76  4976.4  270.71
    4982  268.28  5001.1  267.31  5003.9  266.81  5007.1  267.31  5014.3  267.63
  5026.3  273.95  5042.8  278.78  5059.3  281.94  5064.9  282.38  5081.4  286.25
  5109.1  290.48  5113.2  291.84  5115.6  292.63  5138.2  293.83  5189.2  294.15
#Mann= 4 ,-1 , 0
  4794.1     .16       0  5001.1     .07       0  5007.1     .16       0
  5113.2     .05       0
Bank Sta=5001.1,5007.1
XS Rating Curve= 0 ,0
Exp/Cntr=0.3,0.1

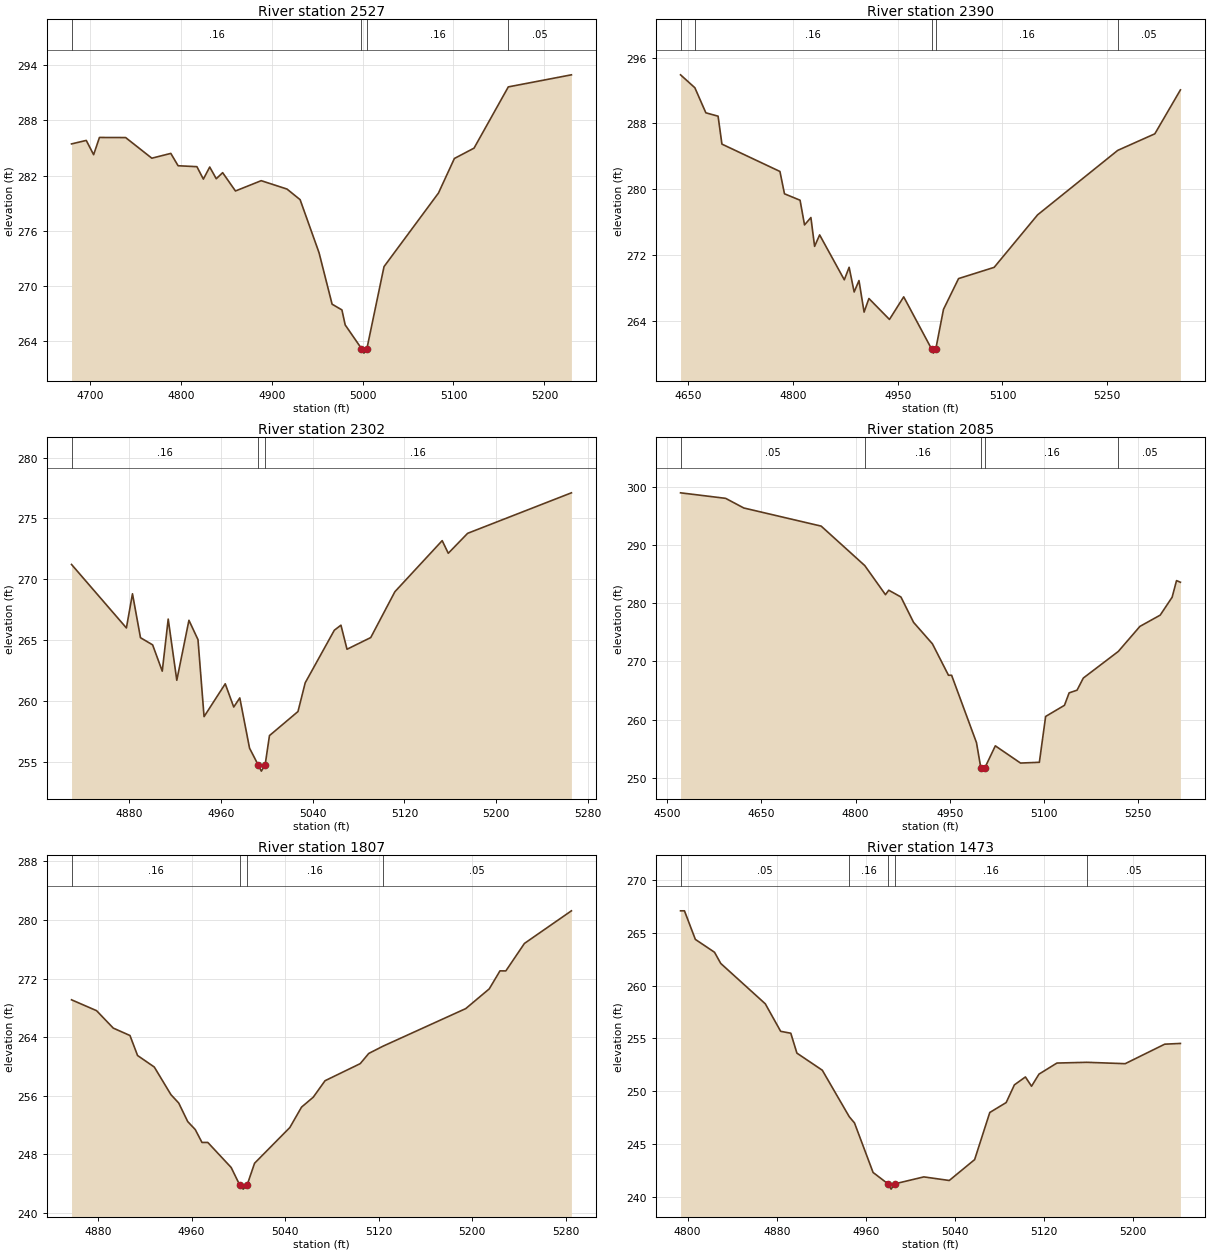
Type RM Length L Ch R = 1 ,2527    ,137,137,137
BEGIN DESCRIPTION:
Mapping XS 7677b0c3
END DESCRIPTION:
XS GIS Cut Line= 6
      3738970.84     10578602.78      3738890.52     10578501.83
      3738844.95     10578455.17      3738716.91       10578351.
      3738578.02     10578295.66      3738537.88     10578288.07
#Sta/Elev= 30
  4679.9  285.43  4696.1  285.81  4704.2  284.26  4710.6  286.13  4739.4  286.12
  4768.2  283.88  4789.1   284.4  4797.1  283.06  4817.8  282.96  4824.9  281.61
  4831.9  282.92  4839.1  281.65  4846.1  282.31  4860.2  280.32  4888.5  281.44
  4916.9  280.53  4931.3  279.38  4952.1  273.63  4966.5  268.03  4977.3  267.41
  4980.9  265.78  4998.8  263.22  5001.5  262.72  5004.8  263.22  5023.6  272.11
  5083.5   280.1    5101  283.85  5122.6  284.97  5160.3  291.62  5229.7  292.93
#Mann= 4 ,-1 , 0
  4679.9     .16       0  4998.8     .07       0  5004.8     .16       0
  5160.3     .05       0
Bank Sta=4998.8,5004.8
XS Rating Curve= 0 ,0
Exp/Cntr=0.3,0.1

Type RM Length L Ch R = 1 ,2390    ,88,88,88
BEGIN DESCRIPTION:
Mapping XS fd347a21
END DESCRIPTION:
XS GIS Cut Line= 6
      3739078.24     10578621.21      3739026.15     10578507.25
      3738838.43     10578320.62      3738778.76     10578280.47
      3738697.38     10578254.43      3738532.97     10578232.75
#Sta/Elev= 30
  4639.4   293.9  4659.9  292.33  4675.6  289.29  4693.1  288.88  4698.6  285.49
  4781.6  282.17  4788.1  279.46  4810.4  278.68  4816.8  275.68  4825.9  276.58
  4831.2  273.08  4838.4  274.47  4873.7  269.02  4880.6  270.54  4887.8  267.54
  4894.7  268.93    4902   265.1  4908.9  266.75  4938.3  264.21  4958.7  266.95
  4998.6  260.62  5001.3  260.12  5004.6  260.62  5015.6  265.43  5037.2  269.17
  5088.1  270.53  5150.2   276.9  5264.9  284.73    5318  286.74  5354.6  292.07
#Mann= 5 ,-1 , 0
  4639.4     .05       0  4659.9     .16       0  4998.6     .07       0
  5004.6     .16       0  5264.9     .05       0
Bank Sta=4998.6,5004.6
XS Rating Curve= 0 ,0
Exp/Cntr=0.3,0.1

Type RM Length L Ch R = 1 ,2302    ,217,217,217
BEGIN DESCRIPTION:
UNT 192 IN BOCR 4.0
END DESCRIPTION:
XS GIS Cut Line= 2
      3739076.52     10578331.98      3738663.93     10578189.82
#Sta/Elev= 30
  4829.4  271.21  4877.3  265.99  4882.6   268.8  4889.6  265.19  4900.2   264.6
  4908.6  262.44  4913.8  266.72  4921.3  261.69  4931.9  266.62  4939.8  265.03
  4945.1   258.7  4963.6   261.4    4971  259.49  4976.3  260.24  4984.8  256.11
  4992.4  254.72  4995.1  254.22  4998.4  254.72  5002.2  257.14  5027.1  259.12
  5033.4  261.48  5058.8   265.8  5064.6  266.22  5069.9  264.24  5090.6   265.2
  5111.7  268.97    5153  273.17  5158.3  272.13  5175.2  273.77  5265.8   277.1
#Mann= 3 ,-1 , 0
  4829.4     .16       0  4992.4     .07       0  4998.4     .16       0
Bank Sta=4992.4,4998.4
XS Rating Curve= 0 ,0
Exp/Cntr=0.3,0.1

Type RM Length L Ch R = 1 ,2085    ,278,278,278
BEGIN DESCRIPTION:
Mapping XS 5929a764
END DESCRIPTION:
XS GIS Cut Line= 6
      3739333.23     10578212.11      3739210.61      10578148.1
      3739020.73     10578081.91      3738933.92     10578073.23
      3738601.89     10578065.63      3738567.17     10578053.69
#Sta/Elev= 30
  4521.2  299.03    4593  298.08  4621.9  296.42  4745.1   293.3  4814.5  286.51
  4847.5   281.5  4852.7  282.27  4872.1   281.1  4892.2  276.74  4922.3  273.03
  4947.8  267.63  4952.8  267.63  4992.4  256.03  4999.4  251.63  5002.2  251.13
  5005.4  251.63  5022.4  255.48  5062.5  252.52  5092.5  252.65  5102.5  260.54
  5132.5  262.46  5139.9   264.6  5152.5  265.06  5162.5  267.15  5218.2  271.73
  5252.6  276.04  5284.9  277.98  5303.9  281.06  5310.9  283.92  5317.1  283.64
#Mann= 5 ,-1 , 0
  4521.2     .05       0  4814.5     .16       0  4999.4     .07       0
  5005.4     .16       0  5218.2     .05       0
Bank Sta=4999.4,5005.4
XS Rating Curve= 0 ,0
Exp/Cntr=0.3,0.1

Type RM Length L Ch R = 1 ,1807    ,334,334,334
BEGIN DESCRIPTION:
UNT 192 IN BOCR 3.0
END DESCRIPTION:
XS GIS Cut Line= 3
      3738999.58     10577910.16      3738914.32      10577837.9
       3738599.6     10577810.19
#Sta/Elev= 30
  4857.3   269.1  4878.7  267.62    4893  265.24  4907.3  264.23  4913.8   261.5
  4928.1  259.93  4942.4  256.15    4949  255.02  4956.7  252.49  4963.2  251.39
  4968.9  249.64  4973.9  249.64  4993.9  246.22  5001.4  243.77  5004.2  243.27
  5007.4  243.77  5013.9   246.8  5044.1  251.68  5054.1  254.46  5064.1  255.81
  5074.2  258.06  5104.3  260.39  5111.6  261.78  5123.9  262.78  5194.6   267.9
  5214.7  270.59  5223.9  273.05  5228.9  273.04  5244.8  276.79    5285  281.24
#Mann= 4 ,-1 , 0
  4857.3     .16       0  5001.4     .07       0  5007.4     .16       0
  5123.9     .05       0
Bank Sta=5001.4,5007.4
XS Rating Curve= 0 ,0
Exp/Cntr=0.3,0.1

Type RM Length L Ch R = 1 ,1473    ,378,378,378
BEGIN DESCRIPTION:
UNT 192 IN BOCR 2.0
END DESCRIPTION:
XS GIS Cut Line= 2
      3739270.97     10577668.78      3738864.72     10577477.81
#Sta/Elev= 30
  4793.6   267.1  4797.1   267.1  4806.9  264.39  4824.1  263.17  4829.7  262.11
  4869.7  258.28  4883.5  255.67  4892.6  255.49  4898.1   253.6  4920.9  251.98
  4945.1  247.57  4949.8  246.98  4966.5  242.28  4979.9   241.2  4982.7   240.7
  4985.9   241.2  5012.1  241.86  5034.9  241.52  5057.7   243.5  5071.3  247.97
    5086  248.91  5093.4  250.59  5103.3  251.34  5108.8  250.46  5115.5  251.61
  5131.6  252.66  5158.5  252.73  5192.9   252.6  5228.4  254.45  5242.5  254.52
#Mann= 5 ,-1 , 0
  4793.6     .05       0  4945.1     .16       0  4979.9     .07       0
  4985.9     .16       0  5158.5     .05       0
Bank Sta=4979.9,4985.9
XS Rating Curve= 0 ,0
Exp/Cntr=0.3,0.1

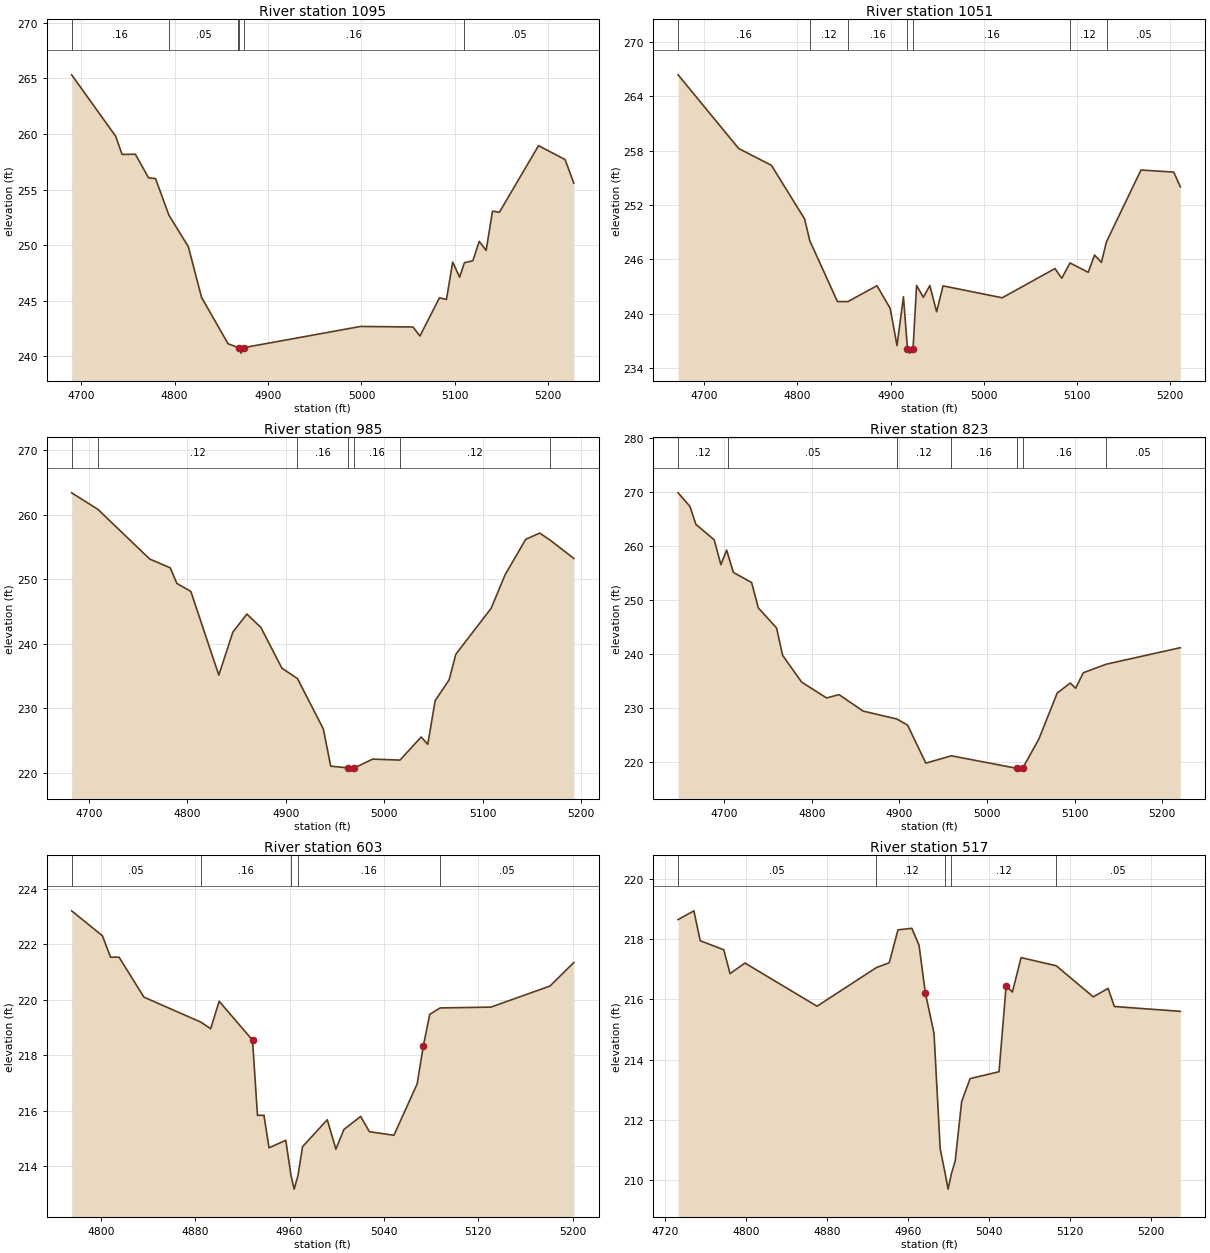
Type RM Length L Ch R = 1 ,1095    ,44,44,44
BEGIN DESCRIPTION:
Mapping XS dfd4740a
END DESCRIPTION:
XS GIS Cut Line= 2
      3739437.48     10577488.96      3739075.03     10577091.78
#Sta/Elev= 30
  4689.7  265.32  4736.9  259.79  4743.7  258.16  4757.9  258.18  4772.1  256.05
  4779.5  255.99  4793.9  252.69  4814.6  249.87  4828.8   245.3  4857.2  241.13
  4867.7  240.81  4868.4  240.79  4871.1  240.29  4874.4  240.79  4999.1  242.69
  5055.2  242.64  5062.6  241.83  5083.5  245.26    5091  245.12  5097.7  248.48
  5105.1  247.12  5110.2  248.42  5119.3   248.6  5126.1  250.34  5133.5  249.53
  5140.3  253.06  5147.7  252.96  5189.6  258.95    5218   257.7  5227.4  255.58
#Mann= 6 ,-1 , 0
  4689.7     .16       0  4793.9     .05       0  4867.7     .16       0
  4868.4     .07       0  4874.4     .16       0  5110.2     .05       0
Bank Sta=4868.4,4874.4
XS Rating Curve= 0 ,0
Exp/Cntr=0.3,0.1

Type RM Length L Ch R = 1 ,1051    ,66,66,66
BEGIN DESCRIPTION:
Mapping XS c55b69bf
END DESCRIPTION:
XS GIS Cut Line= 2
      3739478.72     10577462.92      3739109.78     10577070.11
#Sta/Elev= 30
  4671.9  266.35  4736.9  258.23    4772  256.38  4807.7  250.46  4813.2  248.07
  4842.9  241.36  4854.1  241.36  4885.3  243.11  4899.5   240.6  4906.8  236.51
  4913.7  241.89    4918  236.18  4920.7  235.68    4924  236.18  4927.8  243.14
  4935.1  241.83    4942  243.13  4949.3  240.24  4956.2  243.09  5019.7  241.78
  5076.3     245  5083.6  243.93  5092.4  245.62    5112  244.59  5118.8  246.49
  5126.1  245.68  5131.6  247.96  5168.6  255.86  5203.8  255.63  5210.8  254.01
#Mann= 7 ,-1 , 0
  4671.9     .16       0  4813.2     .12       0  4854.1     .16       0
    4918     .07       0    4924     .16       0  5092.4     .12       0
  5131.6     .05       0
Bank Sta=4918,4924
XS Rating Curve= 0 ,0
Exp/Cntr=0.3,0.1

Type RM Length L Ch R = 1 ,985     ,162,162,162
BEGIN DESCRIPTION:
Mapping XS 47f22bbe
END DESCRIPTION:
XS GIS Cut Line= 2
      3739528.63     10577382.62      3739148.87     10577041.92
#Sta/Elev= 30
  4682.4  263.36    4709  260.81  4761.7   253.1  4782.6  251.73  4789.3  249.32
  4803.5  248.08  4831.9  235.11  4846.2  241.78  4860.4  244.57  4874.6  242.51
    4896  236.19  4911.8  234.58  4938.1  226.77  4945.6     221  4963.5  220.73
  4966.3  220.23  4969.5  220.73  4988.2  222.09    5016  221.94  5037.5  225.52
  5044.2  224.38  5051.7  231.15  5065.9  234.38  5072.7  238.34  5108.6  245.47
  5122.8  250.67  5143.7  256.15  5157.9  257.12  5168.7  256.01  5192.6  253.19
#Mann= 7 ,-1 , 0
  4682.4     .16       0    4709     .12       0  4911.8     .16       0
  4963.5     .07       0  4969.5     .16       0    5016     .12       0
  5168.7     .05       0
Bank Sta=4963.5,4969.5
XS Rating Curve= 0 ,0
Exp/Cntr=0.3,0.1

Type RM Length L Ch R = 1 ,823     ,220,220,220
BEGIN DESCRIPTION:
Mapping XS 43904b20
END DESCRIPTION:
XS GIS Cut Line= 5
      3739637.99     10577290.42      3739505.21     10577136.81
      3739382.81     10577035.25        3739250.      10576944.1
      3739200.49     10576936.28
#Sta/Elev= 30
  4647.4  269.78  4660.9  267.27  4667.7  263.94  4688.6  261.08  4696.2  256.48
  4702.8  259.17  4704.5  258.26  4710.5  255.04  4731.3  253.17    4739  248.46
  4759.8  244.75  4766.7  239.68  4788.4  234.73  4816.9  231.79  4831.1  232.41
  4858.6  229.36  4897.2  227.89  4909.4  226.75  4930.2  219.72  4959.4  221.08
  5034.6  218.74  5037.4  218.24  5040.6  218.74  5059.2  224.17  5080.2  232.71
  5095.1  234.55  5101.2  233.58    5110  236.46  5136.1  238.04  5220.7   241.1
#Mann= 7 ,-1 , 0
  4647.4     .12       0  4704.5     .05       0  4897.2     .12       0
  4959.4     .16       0  5034.6     .07       0  5040.6     .16       0
  5136.1     .05       0
Bank Sta=5034.6,5040.6
XS Rating Curve= 0 ,0
Exp/Cntr=0.3,0.1

Type RM Length L Ch R = 1 ,603     ,86,86,86
BEGIN DESCRIPTION:
Mapping XS a50f6a4f
END DESCRIPTION:
XS GIS Cut Line= 5
      3739703.14     10577053.49      3739588.54      10576941.5
      3739520.83     10576868.58      3739450.52     10576842.54
      3739359.38     10576839.94
#Sta/Elev= 30
  4775.2  223.21  4801.3  222.31  4808.2  221.54  4815.4  221.54  4836.5   220.1
  4884.7   219.2  4893.1  218.96  4900.3  219.95  4928.6  218.55  4932.8  215.84
  4938.3  215.84  4942.6  214.67  4956.8  214.94  4961.2  213.68  4963.9  213.18
  4967.2  213.68    4971  214.71    4992  215.68  4999.3  214.62  5006.1  215.33
  5020.3   215.8  5027.7  215.25  5048.5  215.12  5068.2  216.97  5073.5  218.35
  5078.9  219.48  5087.7  219.71  5130.8  219.74  5180.9   220.5  5201.1  221.35
#Mann= 5 ,-1 , 0
  4775.2     .05       0  4884.7     .16       0  4961.2     .07       0
  4967.2     .16       0  5087.7     .05       0
Bank Sta=4928.6,5073.5
XS Rating Curve= 0 ,0
Exp/Cntr=0.3,0.1

Type RM Length L Ch R = 1 ,517     ,208,208,208
BEGIN DESCRIPTION:
Mapping XS 6966233f
END DESCRIPTION:
XS GIS Cut Line= 2
      3739827.18     10576994.39      3739424.09     10576705.55
#Sta/Elev= 30
  4733.2  218.64  4748.8  218.93    4755  217.94  4778.3  217.64  4784.5  216.85
  4799.2   217.2  4870.4  215.77    4929  217.05  4941.7  217.21  4950.3   218.3
    4964  218.35  4971.1  217.79  4977.3  216.22  4985.9  214.87    4992  211.05
    4997  210.21  4999.8  209.71    5003  210.21  5006.8  210.64  5013.2  212.61
  5021.5  213.37  5050.1   213.6  5057.1  216.44  5063.3  216.24  5071.9  217.38
  5106.6  217.11  5143.1  216.08  5157.8  216.36    5164  215.76  5229.1   215.6
#Mann= 5 ,-1 , 0
  4733.2     .05       0    4929     .12       0    4997     .07       0
    5003     .12       0  5106.6     .05       0
Bank Sta=4977.3,5057.1
XS Rating Curve= 0 ,0
Exp/Cntr=0.3,0.1

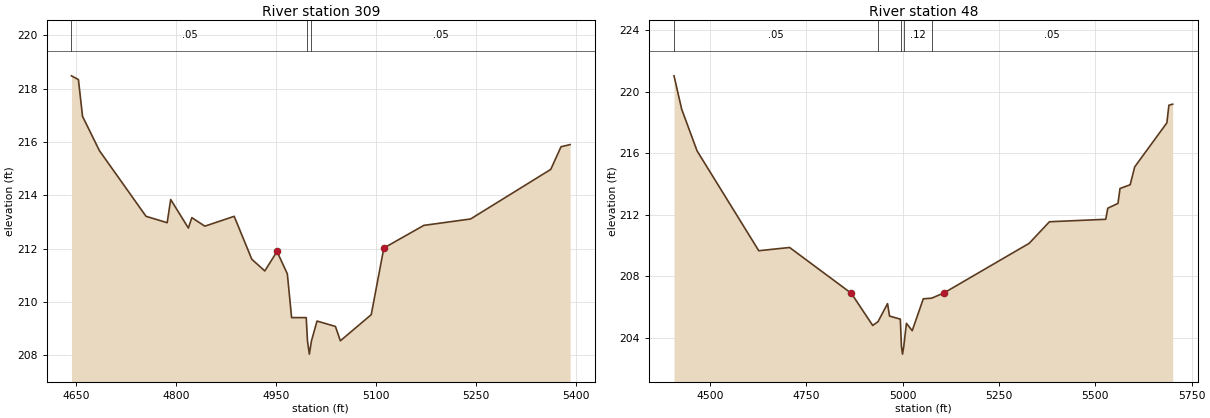
Type RM Length L Ch R = 1 ,309     ,261,261,261
BEGIN DESCRIPTION:
Mapping XS 9d354993
END DESCRIPTION:
XS GIS Cut Line= 4
      3739890.13     10576990.09      3739798.97     10576714.45
      3739662.25     10576640.66      3739360.62     10576655.85
#Sta/Elev= 30
  4643.1  218.48  4653.5  218.34  4659.7  216.96  4685.1  215.67  4754.9  213.21
  4786.6  212.97  4791.9  213.84  4818.4  212.77  4823.6  213.16  4843.1  212.84
  4887.1  213.21  4913.5   211.6    4933  211.16  4951.3  211.89  4966.8  211.05
  4973.2  209.41  4995.1  209.41    4997  208.54  4999.8  208.04    5003  208.54
  5011.3  209.28  5038.9  209.08  5046.3  208.54  5092.6  209.52  5111.5  212.02
  5171.5  212.87  5241.6  213.11  5361.8  214.97  5377.2  215.82  5390.8   215.9
#Mann= 3 ,-1 , 0
  4643.1     .05       0    4997     .03       0    5003     .05       0
Bank Sta=4951.3,5111.5
XS Rating Curve= 0 ,0
Exp/Cntr=0.3,0.1

Type RM Length L Ch R = 1 ,48      ,0,0,0
BEGIN DESCRIPTION:
UNT 192 IN BOCR 1.0
END DESCRIPTION:
XS GIS Cut Line= 4
       3739942.2     10576990.01      3739931.35     10576486.58
       3739753.4     10576447.52      3739176.11      10576638.5
#Sta/Elev= 30
  4406.9  221.02  4426.7  218.86  4466.7  216.15  4626.8  209.67  4706.8  209.88
  4866.8  206.91  4922.5  204.82  4936.3  205.07  4960.9  206.24  4966.1  205.43
  4994.1  205.23    4997  203.46  4999.8  202.96    5003  203.46  5009.9  204.96
  5024.9  204.48  5053.7  206.55  5075.3  206.59  5107.2  206.93  5328.4  210.15
    5381  211.55  5527.1  211.71  5532.4  212.43  5558.8  212.74  5564.1  213.71
  5590.5  213.95  5602.2  215.11  5685.7  217.97  5690.9  219.11  5700.7  219.18
#Mann= 5 ,-1 , 0
  4406.9     .05       0  4936.3     .12       0    4997     .07       0
    5003     .12       0  5075.3     .05       0
Bank Sta=4866.8,5107.2
XS Rating Curve= 0 ,0
Exp/Cntr=0.3,0.1

Chan Stop Cuts=-1
Use User Specified Reach Order=0
Composite Channel Slope=5