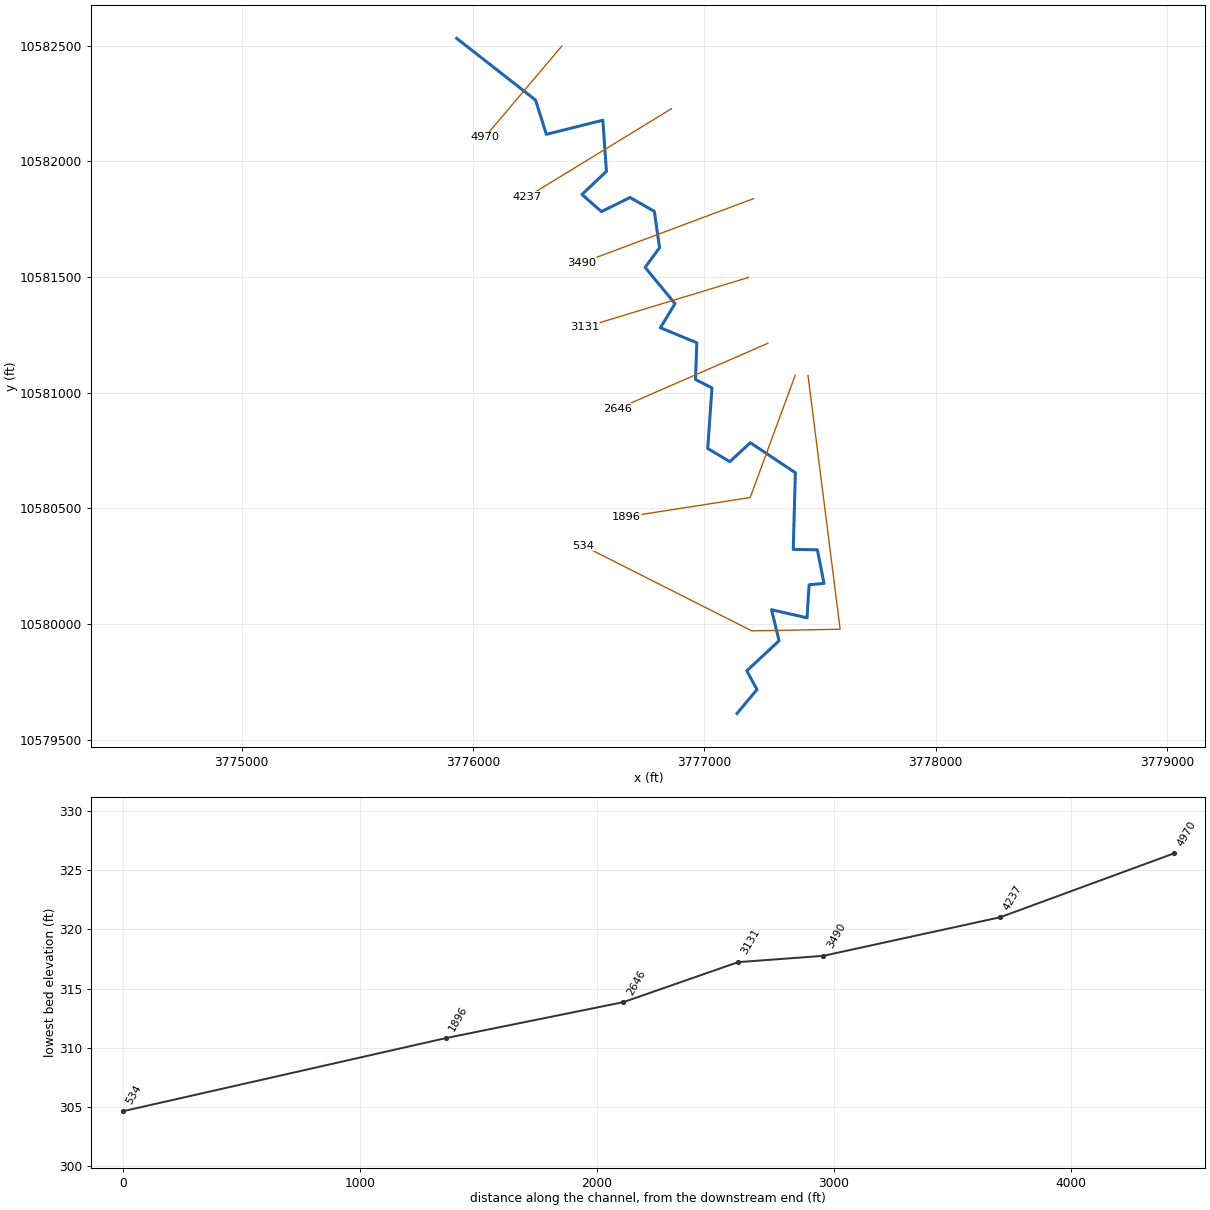
--- UNT 193 IN BOCR.prj (project) ---

Proj Title=UNT 193 IN BOCR Base Level Engineering
Current Plan=p01
Default Exp/Contr=0.3,0.1
English Units
Geom File=g01
Flow File=f01
Plan File=p01
Y Axis Title=Elevation
X Axis Title(PF)=Main Channel Distance
X Axis Title(XS)=Station
BEGIN DESCRIPTION:
UNT 193 IN BOCR
END DESCRIPTION:
DSS Export Rating Curves= 0
DSS Export Rating Curve Sorted= 0
DSS Export Volume Flow Curves= 0
DXF OffsetX= 0
DXF OffsetY= 0
DXF ScaleX= 1
DXF ScaleY= 10

--- UNT 193 IN BOCR.p01 (plan) ---

Plan Title=Multiple Run
Short Identifier=Multiple
Geom File=g01
Flow File=f01
Subcritical Flow
K Sum by GR= 0
Std Step Tol= 0.01
Critical Tol= 0.01
Num of Std Step Trials= 20
Max Error Tol= 0.3
Flow Tol Ratio= 0.001
Split Flow NTrial= 30
Split Flow Tol= 0.02
Split Flow Ratio= 0.02
Log Output Level= 0
Friction Slope Method= 1
Unsteady Friction Slope Method= 2
Unsteady Bridges Friction Slope Method= 1
Parabolic Critical Depth
Global Vel Dist=  1 , 1 , 1
Global Log Level= 0
CheckData=True
Encroach Param= -1, 0, 0, 0
BEGIN DESCRIPTION:
Multiple Run
END DESCRIPTION:

--- UNT 193 IN BOCR.f01 (steady flow) ---

Flow Title=Multiple
Program Version=4.10
Number of Profiles= 7
Profile Names=10-year,25-year,50-year,1pct_min,100-year,1pct_plu,500-year
River Rch & RM=UNT 193 IN BOCR,Reach-1         ,4970
     372     486     577     504     681     921     953
Boundary for River Rch & Prof#=UNT 193 IN BOCR,Reach-1         , 1
Up Type= 0
Dn Type= 3
Dn Slope=0.005
Boundary for River Rch & Prof#=UNT 193 IN BOCR,Reach-1         , 2
Up Type= 0
Dn Type= 3
Dn Slope=0.005
Boundary for River Rch & Prof#=UNT 193 IN BOCR,Reach-1         , 3
Up Type= 0
Dn Type= 3
Dn Slope=0.005
Boundary for River Rch & Prof#=UNT 193 IN BOCR,Reach-1         , 4
Up Type= 0
Dn Type= 3
Dn Slope=0.005
Boundary for River Rch & Prof#=UNT 193 IN BOCR,Reach-1         , 5
Up Type= 0
Dn Type= 3
Dn Slope=0.005
Boundary for River Rch & Prof#=UNT 193 IN BOCR,Reach-1         , 6
Up Type= 0
Dn Type= 3
Dn Slope=0.005
Boundary for River Rch & Prof#=UNT 193 IN BOCR,Reach-1         , 7
Up Type= 0
Dn Type= 3
Dn Slope=0.005
DSS Import GetInterval= 0
DSS Import GetPeak= 0
DSS Import FillOption= 0

--- UNT 193 IN BOCR.g01 (geometry) ---

Geom Title=Existing Conditions

River Reach=UNT 193 IN BOCR,Reach-1
Reach XY= 30
      3775929.75     10582531.00      3776270.75     10582264.00
      3776317.25     10582116.00      3776561.50     10582177.00
      3776577.00     10581956.00      3776471.25     10581856.00
      3776555.50     10581782.00      3776679.25     10581843.00
      3776784.00     10581783.00      3776806.75     10581626.00
      3776744.25     10581541.00      3776873.50     10581384.00
      3776810.25     10581280.00      3776967.75     10581215.00
      3776962.00     10581056.00      3777033.25     10581020.00
      3777014.75     10580758.00      3777110.50     10580701.00
      3777198.75     10580783.00      3777393.75     10580653.00
      3777384.50     10580322.00      3777489.00     10580320.00
      3777517.50     10580175.00      3777453.00     10580169.00
      3777444.25     10580026.00      3777290.75     10580061.00
      3777323.25     10579927.00      3777183.75     10579797.00
      3777227.75     10579716.00      3777141.75     10579613.00

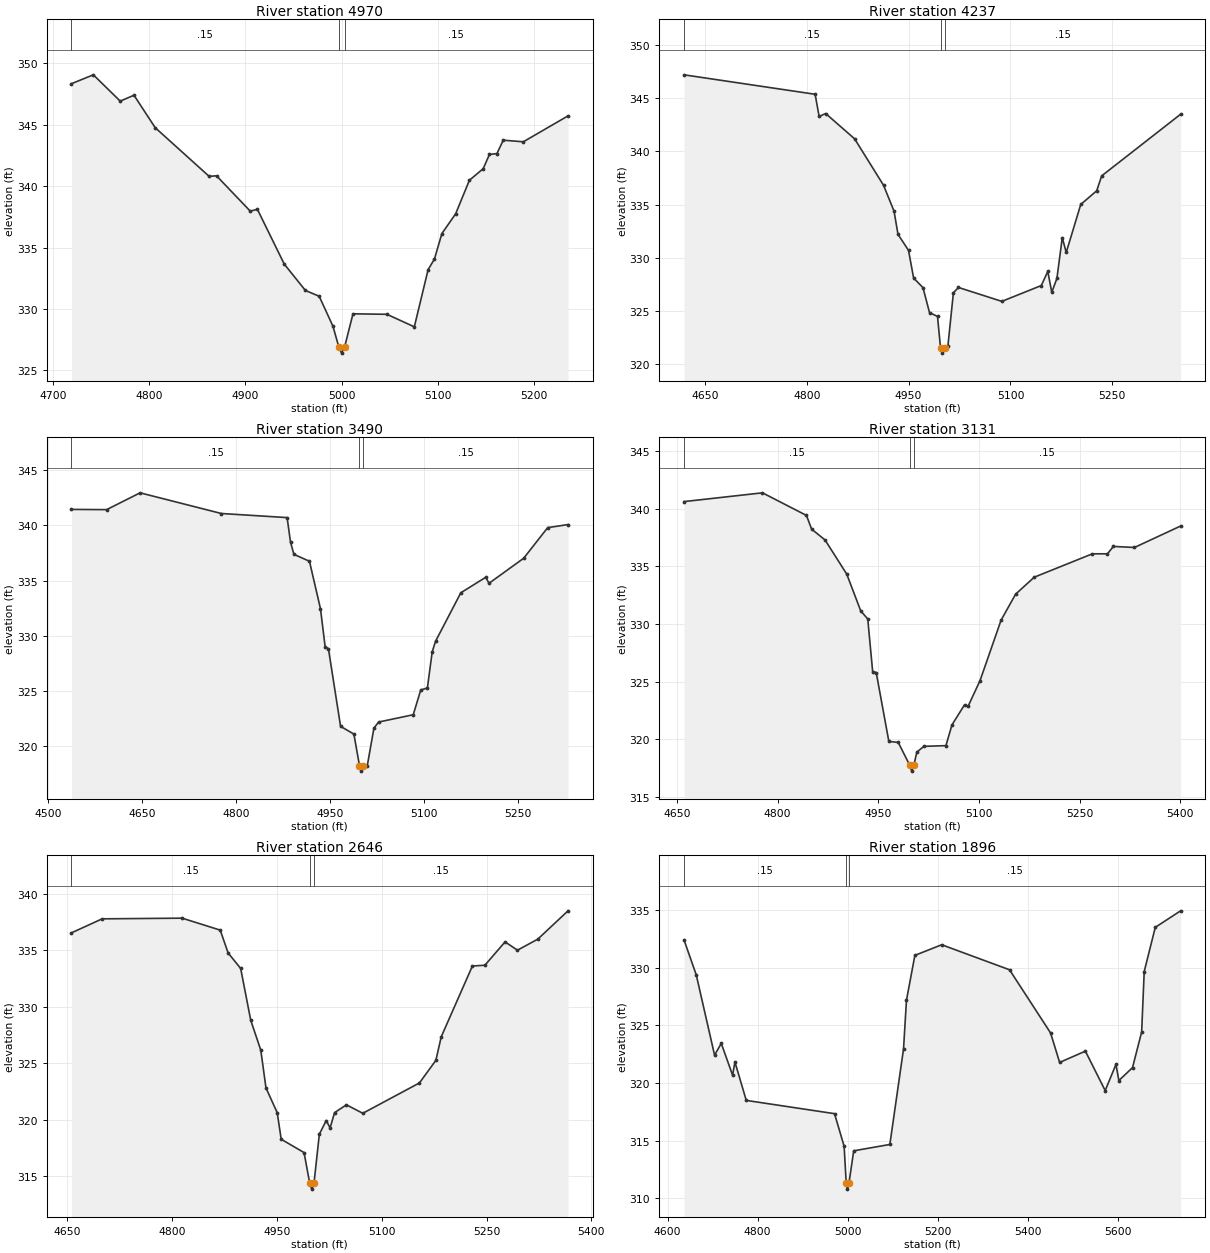
Type RM Length L Ch R = 1,4970,733,733,733
BEGIN DESCRIPTION:
UNT 193 IN BOCR 7.0
END DESCRIPTION:
XS GIS Cut Line= 2
      3776384.16     10582497.49      3776051.11     10582103.89
#Sta/Elev= 30
  4719.4  348.34  4742.1  349.06  4770.0  346.92  4784.3  347.40  4806.3  344.76
  4862.3  340.80  4870.0  340.84  4905.1  337.96  4912.4  338.12  4940.3  333.66
  4962.3  331.51  4976.6  331.04  4990.9  328.60  4997.0  326.91  4999.8  326.41
  5003.0  326.91  5011.7  329.61  5046.9  329.57  5075.4  328.55  5089.7  333.20
  5096.3  334.07  5104.0  336.14  5118.3  337.75  5132.6  340.48  5146.9  341.42
  5153.4  342.58  5161.2  342.65  5167.7  343.74  5188.6  343.61  5235.0  345.72
#Mann=3,-1,0
  4719.4    0.15       0  4997.0    0.05       0  5003.0    0.15       0
Bank Sta=4997,5003
Exp/Cntr=0.3,0.1

Type RM Length L Ch R = 1,4237,747,747,747
BEGIN DESCRIPTION:
Mapping XS e004c261
END DESCRIPTION:
XS GIS Cut Line= 2
      3776858.04     10582226.64      3776234.21     10581845.41
#Sta/Elev= 30
  4619.4  347.21  4812.4  345.38  4818.3  343.29  4827.9  343.57  4870.5  341.19
  4913.1  336.82  4928.6  334.38  4934.4  332.20  4949.9  330.69  4957.4  328.09
  4971.2  327.18  4980.8  324.84  4992.6  324.47  4997.0  321.52  4999.8  321.02
  5003.0  321.52  5007.9  321.70  5016.0  326.70  5023.4  327.20  5087.3  325.89
  5145.4  327.38  5155.0  328.71  5160.8  326.74  5168.4  328.05  5176.3  331.89
  5182.1  330.49  5203.5  335.01  5227.0  336.30  5234.3  337.70  5350.5  343.50
#Mann=3,-1,0
  4619.4    0.15       0  4997.0    0.05       0  5003.0    0.15       0
Bank Sta=4997,5003
Exp/Cntr=0.3,0.1

Type RM Length L Ch R = 1,3490,359,359,359
BEGIN DESCRIPTION:
Mapping XS f32c513d
END DESCRIPTION:
XS GIS Cut Line= 2
      3777212.25     10581837.78      3776469.18     10581559.99
#Sta/Elev= 30
  4536.9  341.43  4593.1  341.41  4646.5  342.93  4776.3  341.06  4881.4  340.69
  4886.8  338.48  4892.2  337.37  4917.1  336.74  4934.7  332.44  4942.1  329.03
  4947.4  328.83  4966.8  321.81  4988.1  321.11  4997.0  318.26  4999.8  317.76
  5003.0  318.26  5009.5  318.26  5020.1  321.65  5027.6  322.20  5082.9  322.86
  5094.9  325.10  5105.5  325.28  5113.2  328.55  5118.5  329.50  5158.9  333.89
  5198.7  335.29  5204.0  334.75  5259.3  337.01  5297.7  339.78  5330.2  340.06
#Mann=3,-1,0
  4536.9    0.15       0  4997.0    0.05       0  5003.0    0.15       0
Bank Sta=4997,5003
Exp/Cntr=0.3,0.1

Type RM Length L Ch R = 1,3131,485,485,485
BEGIN DESCRIPTION:
Mapping XS 560f0008
END DESCRIPTION:
XS GIS Cut Line= 2
      3777191.40     10581497.49      3776483.85     10581282.45
#Sta/Elev= 30
  4660.8  340.61  4777.6  341.37  4843.1  339.41  4850.8  338.22  4870.8  337.28
  4903.1  334.32  4924.0  331.12  4934.4  330.43  4941.7  325.86  4947.0  325.78
  4965.8  319.81  4979.8  319.72  4997.0  317.73  4999.8  317.23  5003.0  317.73
  5007.5  318.88  5018.0  319.38  5050.8  319.44  5059.8  321.24  5078.5  322.98
  5083.7  322.84  5101.6  325.08  5133.0  330.33  5154.6  332.58  5182.3  334.05
  5268.9  336.08  5291.4  336.08  5300.2  336.72  5331.6  336.63  5400.3  338.49
#Mann=3,-1,0
  4660.8    0.15       0  4997.0    0.05       0  5003.0    0.15       0
Bank Sta=4997,5003
Exp/Cntr=0.3,0.1

Type RM Length L Ch R = 1,2646,750,750,750
BEGIN DESCRIPTION:
Mapping XS a875fbf6
END DESCRIPTION:
XS GIS Cut Line= 2
      3777274.78     10581212.79      3776623.26     10580928.62
#Sta/Elev= 30
  4655.9  336.56  4699.8  337.80  4814.3  337.86  4868.8  336.80  4880.1  334.78
  4898.1  333.40  4912.5  328.81  4926.9  326.16  4934.3  322.82  4950.4  320.62
  4956.1  318.27  4988.8  317.09  4997.0  314.35  4999.8  313.85  5003.0  314.35
  5010.7  318.72  5020.6  319.93  5026.1  319.27  5032.5  320.63  5049.5  321.32
  5072.9  320.57  5154.0  323.26  5177.5  325.26  5185.2  327.35  5229.8  333.62
  5247.7  333.69  5276.6  335.76  5294.3  335.02  5323.4  336.00  5366.7  338.51
#Mann=3,-1,0
  4655.9    0.15       0  4997.0    0.05       0  5003.0    0.15       0
Bank Sta=4997,5003
Exp/Cntr=0.3,0.1

Type RM Length L Ch R = 1,1896,1362,1362,1362
BEGIN DESCRIPTION:
Mapping XS 031f5b91
END DESCRIPTION:
XS GIS Cut Line= 3
      3777392.79     10581073.84      3777198.36     10580546.11
      3776664.12     10580462.85
#Sta/Elev= 30
  4636.7  332.40  4663.8  329.38  4704.5  322.42  4719.4  323.44  4744.5  320.69
  4749.8  321.82  4774.9  318.50  4971.0  317.35  4992.3  314.53  4997.0  311.31
  4999.8  310.81  5003.0  311.31  5013.6  314.13  5093.9  314.68  5124.3  322.96
  5130.8  327.18  5149.5  331.07  5209.1  331.99  5359.8  329.82  5450.9  324.35
  5471.1  321.79  5528.3  322.77  5572.3  319.35  5596.2  321.62  5602.7  320.22
  5633.0  321.34  5653.3  324.43  5659.0  329.67  5683.6  333.50  5739.8  334.93
#Mann=3,-1,0
  4636.7    0.15       0  4997.0    0.05       0  5003.0    0.15       0
Bank Sta=4997,5003
Exp/Cntr=0.3,0.1

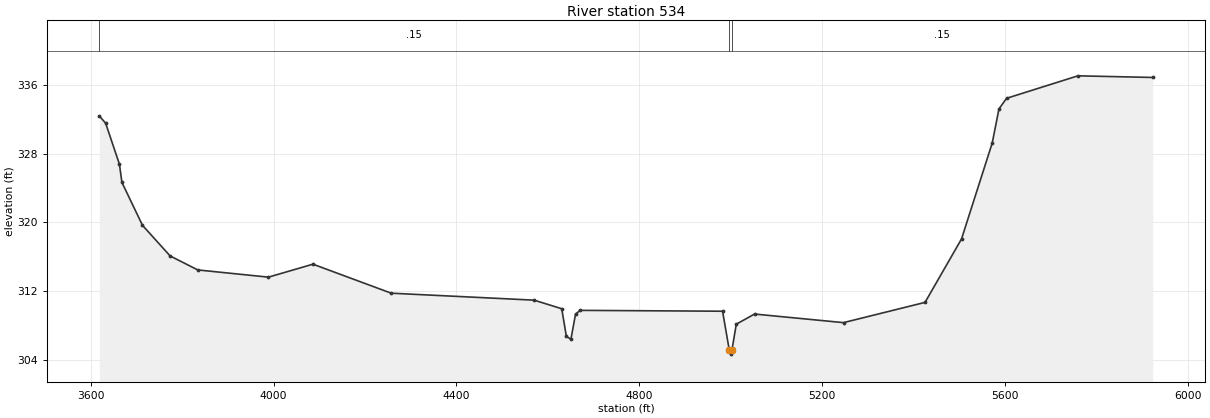
Type RM Length L Ch R = 1,534,0,0,0
BEGIN DESCRIPTION:
UNT 193 IN BOCR 1.0
END DESCRIPTION:
XS GIS Cut Line= 4
      3777448.36     10581073.86      3777587.25     10579976.66
      3777205.30     10579969.72      3776476.09     10580337.80
#Sta/Elev= 30
  3618.8  332.39  3632.6  331.55  3662.8  326.76  3668.2  324.65  3713.2  319.65
  3773.7  316.08  3834.2  314.45  3988.7  313.61  4086.2  315.12  4257.5  311.74
  4570.0  310.93  4630.5  309.93  4640.6  306.72  4650.6  306.37  4660.7  309.30
  4670.8  309.74  4982.4  309.64  4997.0  305.14  4999.8  304.64  5003.0  305.14
  5012.4  308.13  5052.4  309.31  5247.0  308.31  5425.4  310.67  5505.2  318.06
  5572.4  329.24  5587.1  333.21  5603.8  334.45  5759.9  337.07  5923.6  336.88
#Mann=3,-1,0
  3618.8    0.15       0  4997.0    0.05       0  5003.0    0.15       0
Bank Sta=4997,5003
Exp/Cntr=0.3,0.1

Chan Stop Cuts=-1