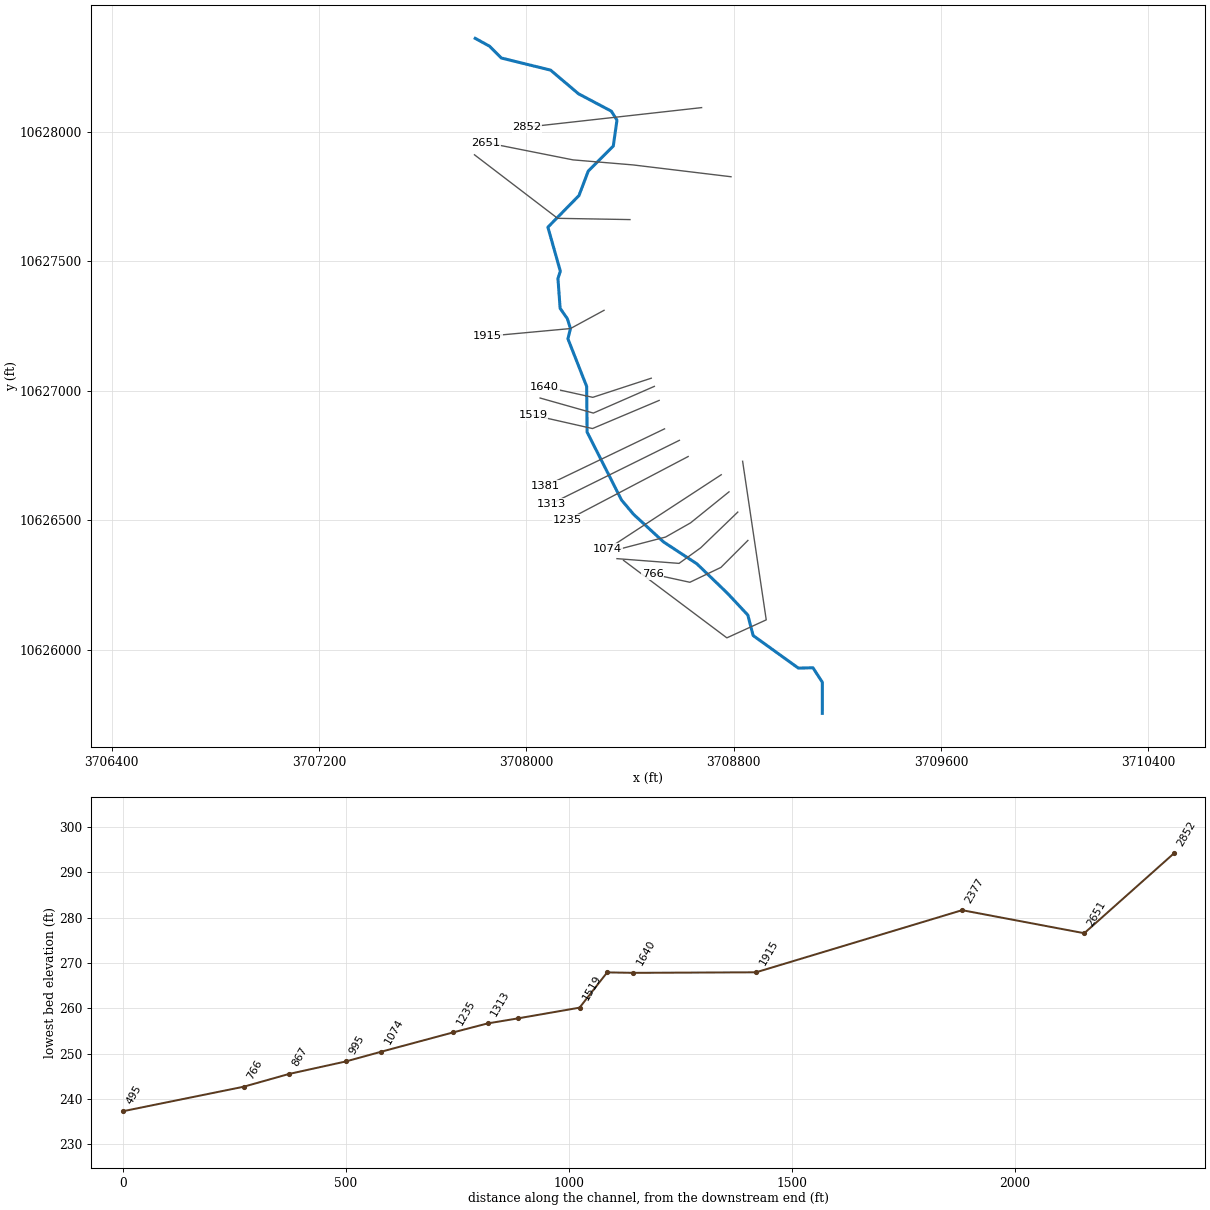
--- UNT 194 IN BOCR.prj (project) ---

Proj Title=UNT 194 IN BOCR Base Level Engineering
Current Plan=p01
Default Exp/Contr=0.3,0.1
English Units
Geom File=g01
Flow File=f01
Plan File=p01
Y Axis Title=Elevation
X Axis Title(PF)=Main Channel Distance
X Axis Title(XS)=Station
BEGIN DESCRIPTION:
UNT 194 IN BOCR
END DESCRIPTION:
DSS Export Rating Curves= 0
DSS Export Rating Curve Sorted= 0
DSS Export Volume Flow Curves= 0
DXF OffsetX= 0
DXF OffsetY= 0
DXF ScaleX= 1
DXF ScaleY= 10

--- UNT 194 IN BOCR.p01 (plan) ---

Plan Title=Multiple Run
Short Identifier=Multiple
Geom File=g01
Flow File=f01
Subcritical Flow
K Sum by GR= 0
Std Step Tol= 0.01
Critical Tol= 0.01
Num of Std Step Trials= 20
Max Error Tol= 0.3
Flow Tol Ratio= 0.001
Split Flow NTrial= 30
Split Flow Tol= 0.02
Split Flow Ratio= 0.02
Log Output Level= 0
Friction Slope Method= 1
Unsteady Friction Slope Method= 2
Unsteady Bridges Friction Slope Method= 1
Parabolic Critical Depth
Global Vel Dist=  1 , 1 , 1
Global Log Level= 0
CheckData=True
Encroach Param= -1, 0, 0, 0
BEGIN DESCRIPTION:
Multiple Run
END DESCRIPTION:

--- UNT 194 IN BOCR.f01 (steady flow) ---

Flow Title=Multiple
Program Version=4.10
Number of Profiles= 7
Profile Names=10-year,25-year,50-year,1pct_min,100-year,1pct_plu,500-year
River Rch & RM=UNT 194 IN BOCR,Reach-1         ,2852
      90     107     120      99     134     181     168
Boundary for River Rch & Prof#=UNT 194 IN BOCR,Reach-1         , 1
Up Type= 0
Dn Type= 3
Dn Slope=0.02
Boundary for River Rch & Prof#=UNT 194 IN BOCR,Reach-1         , 2
Up Type= 0
Dn Type= 3
Dn Slope=0.02
Boundary for River Rch & Prof#=UNT 194 IN BOCR,Reach-1         , 3
Up Type= 0
Dn Type= 3
Dn Slope=0.02
Boundary for River Rch & Prof#=UNT 194 IN BOCR,Reach-1         , 4
Up Type= 0
Dn Type= 3
Dn Slope=0.02
Boundary for River Rch & Prof#=UNT 194 IN BOCR,Reach-1         , 5
Up Type= 0
Dn Type= 3
Dn Slope=0.02
Boundary for River Rch & Prof#=UNT 194 IN BOCR,Reach-1         , 6
Up Type= 0
Dn Type= 3
Dn Slope=0.02
Boundary for River Rch & Prof#=UNT 194 IN BOCR,Reach-1         , 7
Up Type= 0
Dn Type= 3
Dn Slope=0.02
DSS Import GetInterval= 0
DSS Import GetPeak= 0
DSS Import FillOption= 0

--- UNT 194 IN BOCR.g01 (geometry) ---

Geom Title=Existing Conditions
Program Version=4.10

River Reach=UNT 194 IN BOCR ,Reach-1
Reach XY= 30
      3707802.44     10628359.52      3707857.78     10628329.14
      3707903.36     10628283.56      3708093.24     10628236.91
      3708200.66     10628145.76      3708327.62     10628078.49
      3708349.32     10628043.76      3708335.21     10627943.94
      3708238.64     10627847.37      3708202.83     10627752.96
      3708082.87     10627630.87      3708130.86     10627461.07
      3708121.71     10627432.85      3708130.02      10627317.9
       3708157.8     10627277.96      3708169.95     10627239.77
       3708160.2     10627200.05      3708232.45     10627016.46
      3708234.18     10626840.25        3708367.      10626578.1
      3708413.87     10626522.54      3708529.24     10626416.36
       3708657.8       10626332.      3708774.98     10626219.15
      3708854.19     10626134.52      3708874.81     10626055.31
      3709049.36     10625929.58      3709105.52     10625930.99
      3709141.86     10625874.98      3709141.75       10625755.

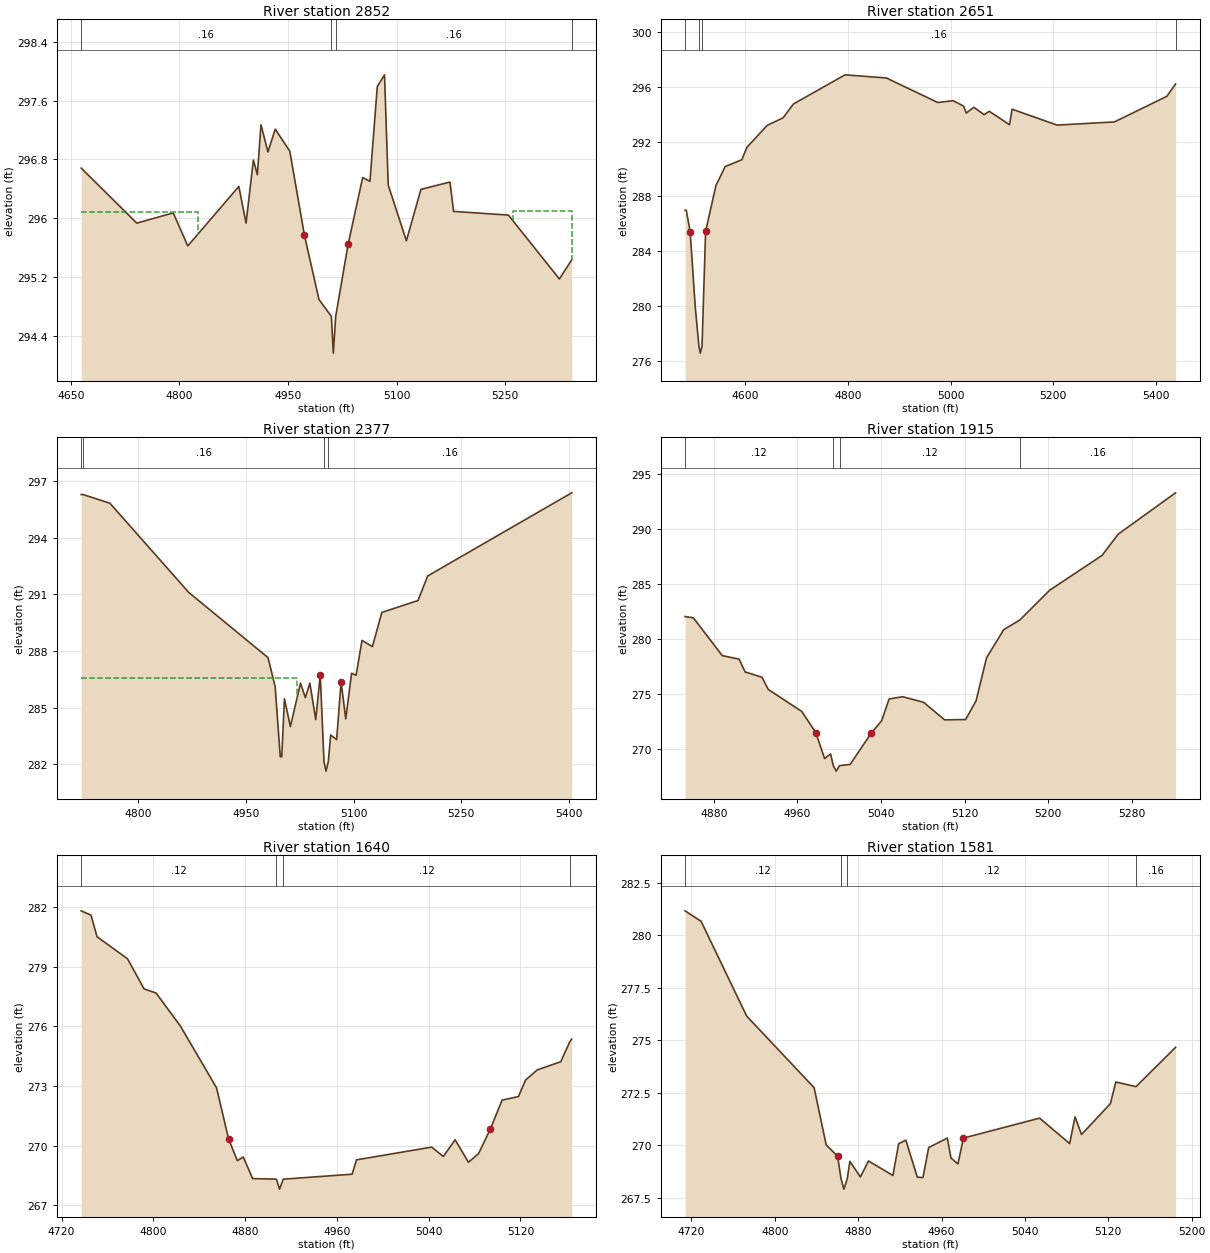
Type RM Length L Ch R = 1 ,2852    ,201,201,201
BEGIN DESCRIPTION:
UNT 194 IN BOCR 5.0
END DESCRIPTION:
XS GIS Cut Line= 2
      3708675.94     10628092.22      3708002.72     10628017.07
#Sta/Elev= 30
  4664.3  296.68  4741.1  295.93  4791.4  296.07  4811.5  295.62    4882  296.43
    4892  295.93  4902.1  296.79  4907.6  296.59  4912.6  297.27  4922.2   296.9
  4932.3  297.21  4952.4  296.91  4972.5  295.77  4992.7  294.89  5009.8  294.66
  5012.5  294.16  5015.8  294.66  5032.9  295.64    5053  296.55  5063.1   296.5
  5073.2  297.79  5083.2  297.95  5088.3  296.45  5113.4  295.69  5133.5  296.39
  5173.6  296.49  5178.6  296.09  5254.3  296.04  5324.7  295.17  5341.7  295.43
#Mann= 4 ,-1 , 0
  4664.3     .16       0  5009.8     .07       0  5015.8     .16       0
  5341.7     .16       0
#XS Ineff= 2 , 0
            4825  296.08 5260.45           296.1
Permanent Ineff=
       F       F
Bank Sta=4972.5,5032.9
XS Rating Curve= 0 ,0
Exp/Cntr=0.3,0.1

Type RM Length L Ch R = 1 ,2651    ,274,274,274
BEGIN DESCRIPTION:
Mapping XS c5098e19
END DESCRIPTION:
XS GIS Cut Line= 4
      3708789.47     10627825.49      3708411.88     10627871.06
      3708179.68     10627890.59      3707842.91     10627957.51
#Sta/Elev= 30
  4482.2  286.99  4484.6  286.99  4492.1  285.44  4502.2  279.89  4509.3  277.06
    4512  276.56  4515.3  277.06  4522.3  285.45  4542.5   288.8  4560.4  290.18
  4592.9  290.68  4602.9  291.59  4642.4  293.19  4673.4  293.74  4693.6  294.75
  4794.3  296.88  4874.8  296.65  4975.2  294.86  5005.3  294.99  5025.4   294.6
  5030.7  294.09  5045.4  294.51  5065.5  293.97  5075.5  294.22    5115  293.24
  5120.1  294.37  5207.8  293.21  5319.6  293.44  5421.9  295.31  5438.9  296.21
#Mann= 4 ,-1 , 0
  4482.2     .16       0  4509.3     .07       0  4515.3     .16       0
  5438.9     .16       0
Bank Sta=4492.1,4522.3
XS Rating Curve= 0 ,0
Exp/Cntr=0.3,0.1

Type RM Length L Ch R = 1 ,2377    ,462,462,462
BEGIN DESCRIPTION:
UNT 194 IN BOCR 4.0
END DESCRIPTION:
XS GIS Cut Line= 3
      3708399.63     10627660.19      3708120.37     10627665.07
       3707799.6     10627910.19
#Sta/Elev= 30
  4720.7  296.28  4723.2  296.28  4760.7  295.82  4870.7  291.09  4980.8  287.65
  4990.8  286.11  4997.9   282.4    5000   282.4  5003.7  285.47    5012     284
  5026.1   286.3  5032.8  285.53  5039.1   286.3  5047.3  284.37  5053.6  286.73
  5058.8  282.14  5061.6  281.64  5064.8  282.14  5068.1  283.55  5076.4  283.31
  5082.6  286.36  5089.1  284.41  5097.2  286.82  5103.5  286.71  5111.7  288.56
  5126.2  288.23  5139.4  290.04  5189.7  290.67  5203.2  291.97  5403.7  296.37
#Mann= 4 ,-1 , 0
  4720.7     .16       0  4723.2     .16       0  5058.8     .07       0
  5064.8     .16       0
#XS Ineff= 2 , 0
         5020.91  286.56
Permanent Ineff=
       F       F
Bank Sta=5053.6,5082.6
XS Rating Curve= 0 ,0
Exp/Cntr=0.3,0.1

Type RM Length L Ch R = 1 ,1915    ,275,275,275
BEGIN DESCRIPTION:
UNT 194 IN BOCR 3.0
END DESCRIPTION:
XS GIS Cut Line= 3
      3708299.57     10627310.17      3708169.95     10627239.77
      3707849.61     10627210.19
#Sta/Elev= 30
  4852.5  282.02  4860.5   281.9  4888.1  278.46  4904.2  278.14  4909.9  276.98
  4926.1  276.49  4932.1  275.38  4964.1  273.38  4977.6  271.44    4986  269.08
  4991.7  269.51  4994.3  268.44  4997.1  267.94  5000.3  268.44  5010.4  268.55
  5030.5  271.38  5040.5  272.52  5047.7  274.51  5060.6  274.72  5080.7  274.21
  5100.8  272.61  5120.9  272.64  5130.9  274.35  5140.9  278.26  5157.3  280.82
  5172.9  281.72  5201.2  284.41  5251.4  287.59  5266.9  289.53  5321.7  293.29
#Mann= 4 ,-1 , 0
  4852.5     .12       0  4994.3     .07       0  5000.3     .12       0
  5172.9     .16       0
Bank Sta=4977.6,5030.5
XS Rating Curve= 0 ,0
Exp/Cntr=0.3,0.1

Type RM Length L Ch R = 1 ,1640    ,59,59,59
BEGIN DESCRIPTION:
Mapping XS fc9a056c
END DESCRIPTION:
XS GIS Cut Line= 3
      3708481.72     10627048.19      3708256.02      10626974.4
      3708070.35     10627015.42
#Sta/Elev= 30
  4737.1   281.8  4745.7  281.58  4750.9   280.5  4777.5  279.39  4791.9  277.88
  4802.4  277.67  4823.5  276.02  4855.1  272.91  4865.6  270.34  4873.2  269.25
  4878.4  269.43  4886.6  268.35  4907.3  268.32    4910  267.82  4913.3  268.32
  4973.3  268.57  4977.1  269.29  5042.6  269.93  5052.8  269.46  5063.1   270.3
  5074.7  269.17  5083.5   269.6  5093.8  270.84    5104  272.29  5118.3  272.47
  5124.5   273.3  5134.7  273.81  5155.2  274.22    5163  275.22  5164.7  275.36
#Mann= 4 ,-1 , 0
  4737.1     .12       0  4907.3     .07       0  4913.3     .12       0
    5163     .16       0
Bank Sta=4865.6,5093.8
XS Rating Curve= 0 ,0
Exp/Cntr=0.3,0.1

Type RM Length L Ch R = 1 ,1581    ,62,62,62
BEGIN DESCRIPTION:
Mapping XS f21dec36
END DESCRIPTION:
XS GIS Cut Line= 3
      3708493.67     10627016.73      3708258.19     10626913.64
       3708052.8     10626971.71
#Sta/Elev= 30
    4714  281.17  4729.4  280.67  4773.1  276.16  4837.8  272.75  4849.4  270.02
  4860.3  269.49  4863.6  268.42  4866.4  267.92  4869.6  268.42  4872.1  269.24
  4882.2   268.5    4890  269.26  4913.4  268.57  4918.9  270.08  4925.8  270.25
  4936.8  268.49  4942.2  268.47  4947.7   269.9  4965.6  270.35  4969.1   269.4
  4975.8  269.12    4981  270.35  5054.1   271.3  5082.9  270.09  5088.1  271.36
  5094.3  270.52    5122  271.99  5127.2  273.02  5146.6   272.8  5184.5  274.67
#Mann= 4 ,-1 , 0
    4714     .12       0  4863.6     .07       0  4869.6     .12       0
  5146.6     .16       0
Bank Sta=4860.3,4981
XS Rating Curve= 0 ,0
Exp/Cntr=0.3,0.1

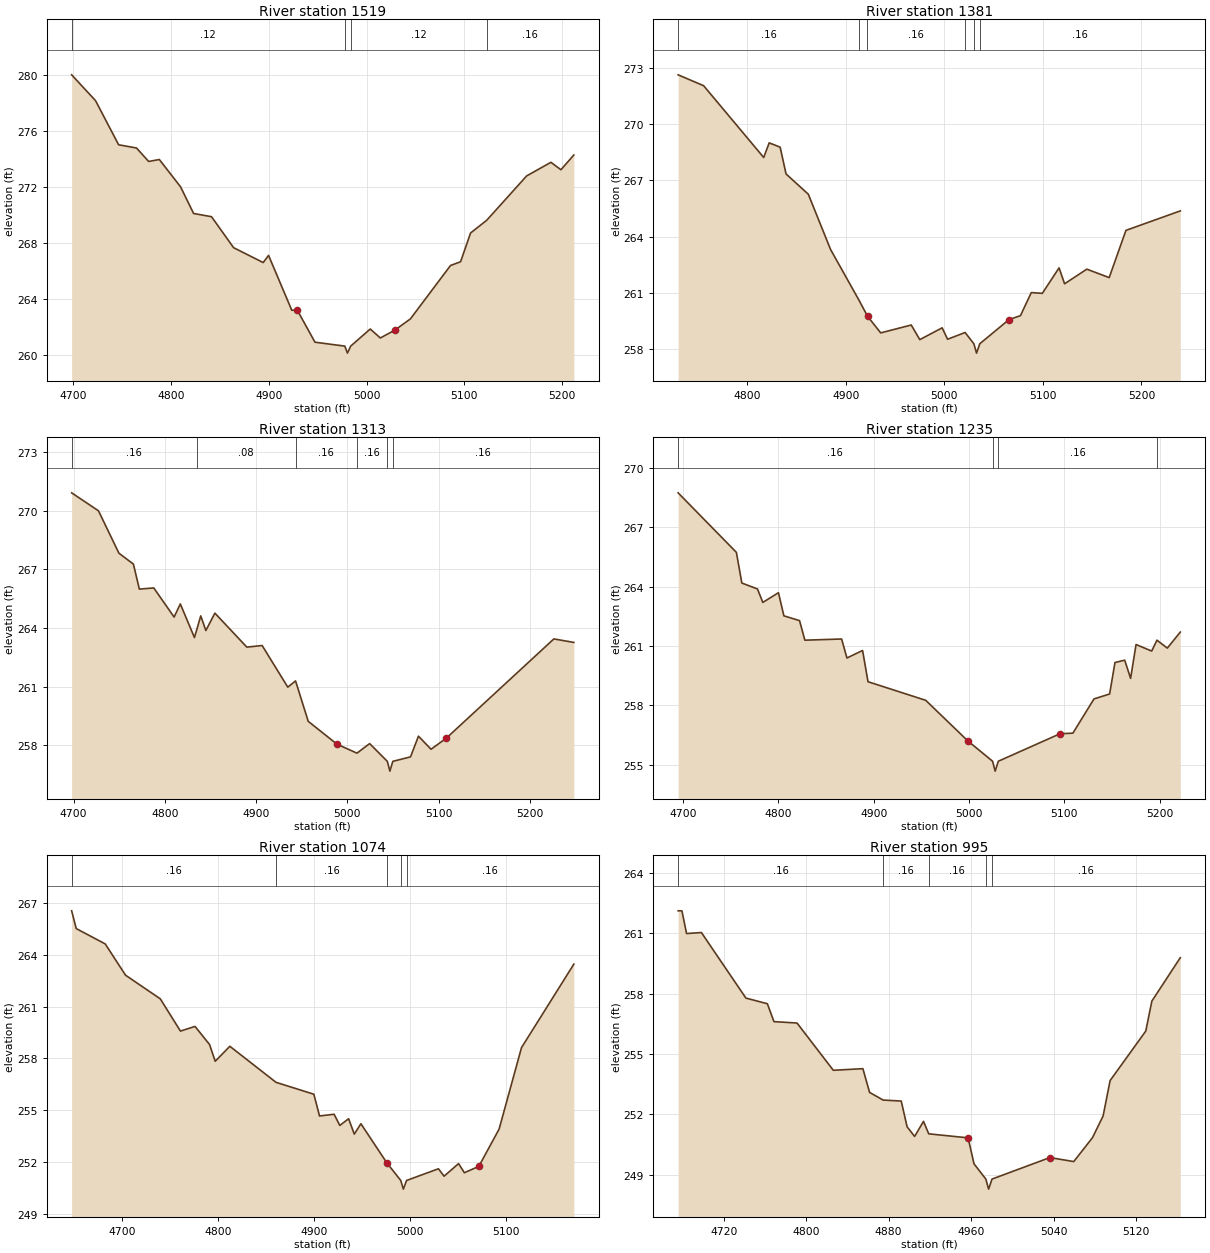
Type RM Length L Ch R = 1 ,1519    ,138,138,138
BEGIN DESCRIPTION:
UNT 194 IN BOCR 2.0
END DESCRIPTION:
XS GIS Cut Line= 3
      3708512.12     10626962.48      3708254.93     10626853.96
      3708026.75     10626905.62
#Sta/Elev= 30
  4698.7  279.99  4723.1  278.15  4746.7     275    4765  274.77  4777.4  273.81
  4788.3  273.95    4810     272  4823.3   270.1  4841.6  269.87  4864.2  267.66
  4894.4   266.6  4899.9  267.11  4923.6   263.2  4929.3   263.2  4947.3  260.92
  4977.8  260.64  4980.5  260.14  4983.8  260.64  5003.8  261.86  5014.1  261.22
  5029.1  261.79  5044.8  262.58  5085.8  266.39  5096.1  266.66  5106.3  268.71
  5122.7  269.61  5163.6  272.78  5188.4  273.75  5198.6  273.22  5211.8  274.27
#Mann= 4 ,-1 , 0
  4698.7     .12       0  4977.8     .07       0  4983.8     .12       0
  5122.7     .16       0
Bank Sta=4929.3,5029.1
XS Rating Curve= 0 ,0
Exp/Cntr=0.3,0.1

Type RM Length L Ch R = 1 ,1381    ,68,68,68
BEGIN DESCRIPTION:
Mapping XS c0d0f0fb
END DESCRIPTION:
XS GIS Cut Line= 2
      3708532.97      10626852.8      3708073.33     10626632.07
#Sta/Elev= 30
  4729.6  272.63  4755.5  272.05  4816.5  268.22  4822.1     269  4833.2  268.77
  4839.2  267.34  4861.8  266.26  4884.4  263.31  4913.2  260.61  4921.1  259.83
  4921.9  259.75  4935.3  258.86  4966.3  259.28    4975   258.5  4997.7  259.13
  5003.2  258.52    5021  258.88  5029.9  258.28  5032.6  257.78  5035.9  258.28
  5065.6  259.57  5077.2  259.78  5088.2  261.01  5099.4  260.97  5116.4  262.33
    5122  261.48  5144.6  262.26  5167.3  261.81  5184.3  264.33  5239.5  265.37
#Mann= 6 ,-1 , 0
  4729.6     .16       0  4913.2     .12       0  4921.1     .16       0
    5021     .16       0  5029.9     .07       0  5035.9     .16       0
Bank Sta=4921.9,5065.6
XS Rating Curve= 0 ,0
Exp/Cntr=0.3,0.1

Type RM Length L Ch R = 1 ,1313    ,78,78,78
BEGIN DESCRIPTION:
Mapping XS 3520dba0
END DESCRIPTION:
XS GIS Cut Line= 2
      3708590.29     10626808.54      3708096.96     10626564.47
#Sta/Elev= 30
  4697.8  270.92  4727.2     270  4749.6  267.83  4765.5  267.27    4772  265.99
  4787.8  266.05  4810.1  264.56  4816.9  265.23  4832.4  263.51  4834.9  263.91
  4839.3  264.62  4844.9  263.87  4854.8  264.76  4889.8  263.02  4906.6   263.1
  4934.7  260.97  4943.2  261.29  4957.1  259.22  4988.6  258.05  5010.5  257.59
  5024.4  258.08  5043.8  257.17  5046.6  256.67  5049.8  257.17  5069.2   257.4
  5077.9  258.46  5091.7  257.79  5108.5  258.36  5226.3  263.44  5248.2  263.26
#Mann= 6 ,-1 , 0
  4697.8     .16       0  4834.9     .08       0  4943.2     .16       0
  5010.5     .16       0  5043.8     .07       0  5049.8     .16       0
Bank Sta=4988.6,5108.5
XS Rating Curve= 0 ,0
Exp/Cntr=0.3,0.1

Type RM Length L Ch R = 1 ,1235    ,161,161,161
BEGIN DESCRIPTION:
Mapping XS c2bbf552
END DESCRIPTION:
XS GIS Cut Line= 2
      3708624.14     10626746.04        3708158.     10626501.25
#Sta/Elev= 30
    4695  268.74  4756.1  265.73  4761.8  264.18  4778.2  263.88  4783.8   263.2
  4800.2  263.69  4805.9  262.52  4822.3  262.28  4827.9  261.29  4866.4  261.35
    4872  260.39  4888.4  260.77  4894.1  259.19  4954.6  258.25  4998.7   256.2
  5024.7  255.17  5027.4  254.67  5030.7  255.17  5095.4  256.56  5108.9  256.59
    5131  258.32  5147.4  258.57    5153  260.16  5163.2  260.28  5169.4  259.36
  5175.1  261.07  5191.5  260.74    5197  261.29  5207.9  260.89  5221.5   261.7
#Mann= 4 ,-1 , 0
    4695     .16       0  5024.7     .04       0  5030.7     .16       0
    5197     .08       0
Bank Sta=4998.7,5095.4
XS Rating Curve= 0 ,0
Exp/Cntr=0.3,0.1

Type RM Length L Ch R = 1 ,1074    ,79,79,79
BEGIN DESCRIPTION:
Mapping XS 882beb9c
END DESCRIPTION:
XS GIS Cut Line= 2
      3708751.74     10626675.73      3708314.01     10626389.69
#Sta/Elev= 30
  4647.7  266.55  4652.5  265.52  4682.7  264.63  4703.8  262.82    4740  261.45
    4761  259.58  4776.2  259.85  4791.3   258.8  4797.2  257.83  4812.4   258.7
  4860.5  256.61  4899.9  255.92  4905.8  254.66    4921  254.76  4926.9  254.11
  4936.1   254.5    4942  253.61  4948.9  254.21  4975.8  251.95  4990.4  250.92
  4993.1  250.42  4996.4  250.92  5029.6   251.6  5035.5  251.17  5050.6   251.9
  5056.6  251.37  5071.7  251.74  5092.8   253.9  5116.1  258.62  5170.6  263.46
#Mann= 5 ,-1 , 0
  4647.7     .16       0  4860.5     .16       0  4975.8     .16       0
  4990.4     .07       0  4996.4     .16       0
Bank Sta=4975.8,5071.7
XS Rating Curve= 0 ,0
Exp/Cntr=0.3,0.1

Type RM Length L Ch R = 1 ,995     ,128,128,128
BEGIN DESCRIPTION:
Mapping XS f143b5a0
END DESCRIPTION:
XS GIS Cut Line= 4
      3708781.71      10626609.8      3708633.23     10626489.98
      3708536.88     10626435.29      3708357.18     10626388.42
#Sta/Elev= 30
  4675.7  262.12  4679.4  262.12  4683.9  260.99  4698.3  261.04  4741.5  257.78
  4762.3   257.5  4768.7  256.61  4791.1  256.54  4826.3  254.19    4855  254.27
  4861.5  253.09  4874.6  252.71  4892.2  252.66  4897.9  251.38  4905.2   250.9
  4913.8  251.65  4918.9  251.03  4957.1  250.83  4962.8  249.54  4974.3  248.78
    4977  248.28  4980.3  248.78  5036.5  249.85  5059.6  249.65  5077.8  250.84
  5088.1  251.92  5094.9  253.68  5129.5  256.14  5135.4  257.63    5163  259.79
#Mann= 5 ,-1 , 0
  4675.7     .16       0  4874.6     .16       0  4918.9     .16       0
  4974.3     .07       0  4980.3     .16       0
Bank Sta=4957.1,5036.5
XS Rating Curve= 0 ,0
Exp/Cntr=0.3,0.1

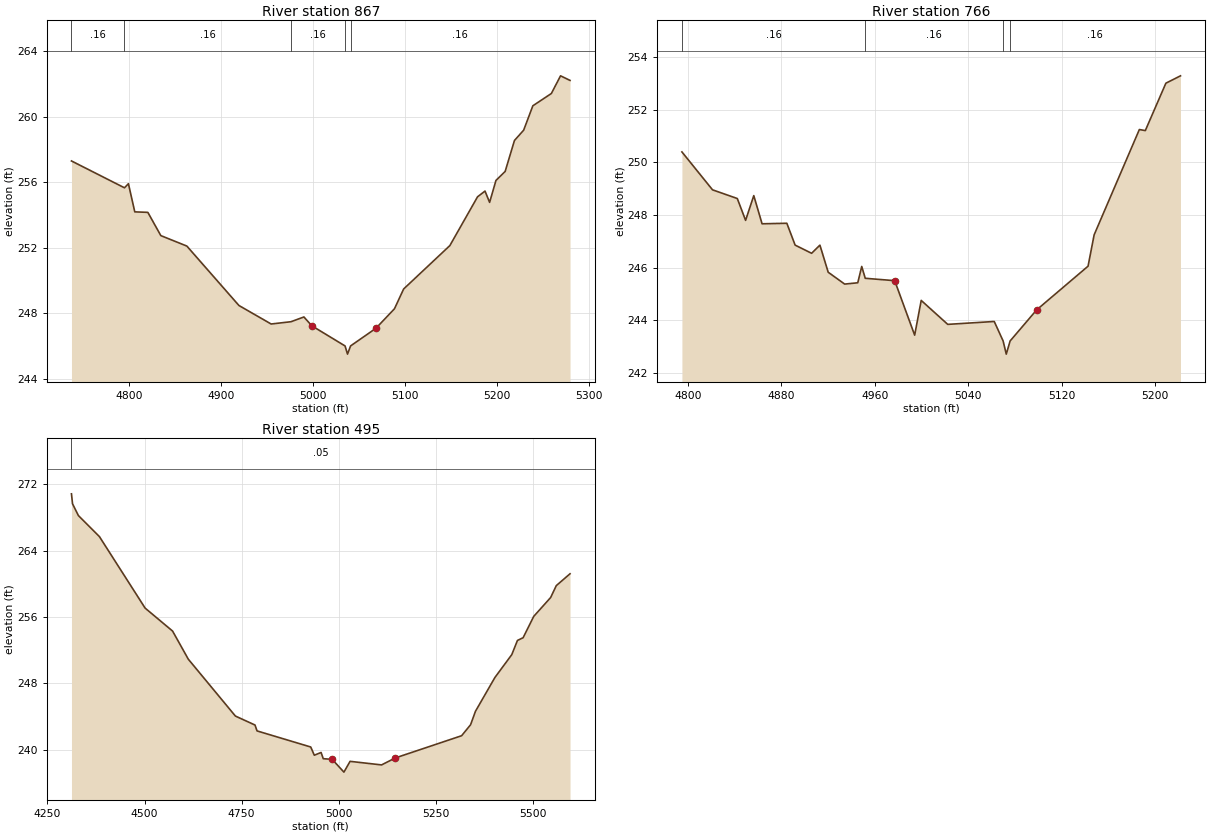
Type RM Length L Ch R = 1 ,867     ,101,101,101
BEGIN DESCRIPTION:
Mapping XS f2c7c54c
END DESCRIPTION:
XS GIS Cut Line= 4
      3708815.51     10626531.63       3708672.3     10626393.63
      3708588.96     10626333.73      3708349.36     10626351.96
#Sta/Elev= 30
  4737.4  257.31    4795  255.67  4799.3  255.92  4806.2   254.2  4820.4  254.17
  4834.5  252.75  4862.8  252.11  4919.4  248.48  4954.4  247.35    4976  247.49
    4990  247.78  4998.6  247.24  5034.7  246.01  5037.4  245.51  5040.7  246.01
  5068.3  247.09  5088.4  248.28  5098.4  249.49  5148.6  252.14  5178.7  255.12
  5186.8  255.47  5191.8  254.78  5198.7  256.12  5208.7  256.67  5218.8  258.56
  5228.8  259.19  5238.8  260.68  5258.9  261.43  5268.9  262.51  5279.2  262.23
#Mann= 5 ,-1 , 0
  4737.4     .16       0    4795     .16       0    4976     .16       0
  5034.7     .07       0  5040.7     .16       0
Bank Sta=4998.6,5068.3
XS Rating Curve= 0 ,0
Exp/Cntr=0.3,0.1

Type RM Length L Ch R = 1 ,766     ,271,271,271
BEGIN DESCRIPTION:
Mapping XS 578d7eb5
END DESCRIPTION:
XS GIS Cut Line= 4
      3708854.57     10626422.25      3708750.42     10626318.11
      3708630.63     10626260.82      3708487.37     10626292.07
#Sta/Elev= 30
  4794.8  250.39    4821  248.95  4842.2  248.62  4849.3  247.79  4856.3  248.73
  4863.4  247.66  4884.6  247.68  4891.7  246.85  4905.8  246.54  4912.9  246.85
    4920  245.82  4934.1  245.37  4945.3  245.42  4948.7  246.04  4951.7  245.59
  4976.9   245.5    4994  243.43  4999.6  244.75  5022.3  243.84  5062.1  243.95
  5069.7  243.21  5072.4  242.71  5075.7  243.21  5098.4  244.39  5142.4  246.05
  5147.6  247.24  5186.3  251.24  5191.4   251.2    5209     253  5221.5  253.28
#Mann= 4 ,-1 , 0
  4794.8     .16       0  4951.7     .16       0  5069.7     .07       0
  5075.7     .16       0
Bank Sta=4976.9,5098.4
XS Rating Curve= 0 ,0
Exp/Cntr=0.3,0.1

Type RM Length L Ch R = 1 ,495     ,0,0,0
BEGIN DESCRIPTION:
UNT 194 IN BOCR 1.0
END DESCRIPTION:
XS GIS Cut Line= 4
       3708834.2     10626727.78      3708925.34     10626115.82
      3708773.43     10626046.38      3708374.82     10626345.34
#Sta/Elev= 30
  4311.8  270.86  4314.5  269.66  4329.6  268.24  4383.8   265.7  4501.5  257.08
  4572.2  254.31  4612.7  250.92    4734  244.06  4784.5  242.98  4789.7  242.27
    4928  240.33  4937.2  239.34  4954.7  239.67  4960.2  238.92  4983.2  238.84
  5013.5   237.3  5029.3   238.6  5110.4  238.17  5145.8  239.01  5316.6  241.69
  5339.6  243.01  5352.3  244.64  5402.3  248.71  5445.8  251.47  5460.4  253.18
    5475  253.51  5502.3  256.08  5545.8  258.35  5560.4  259.79  5595.8  261.22
#Mann= 1 ,-1 , 0
  4311.8     .05       0
Bank Sta=4983.2,5145.8
XS Rating Curve= 0 ,0
Exp/Cntr=0.3,0.1

Chan Stop Cuts=-1
Use User Specified Reach Order=0
Composite Channel Slope=5