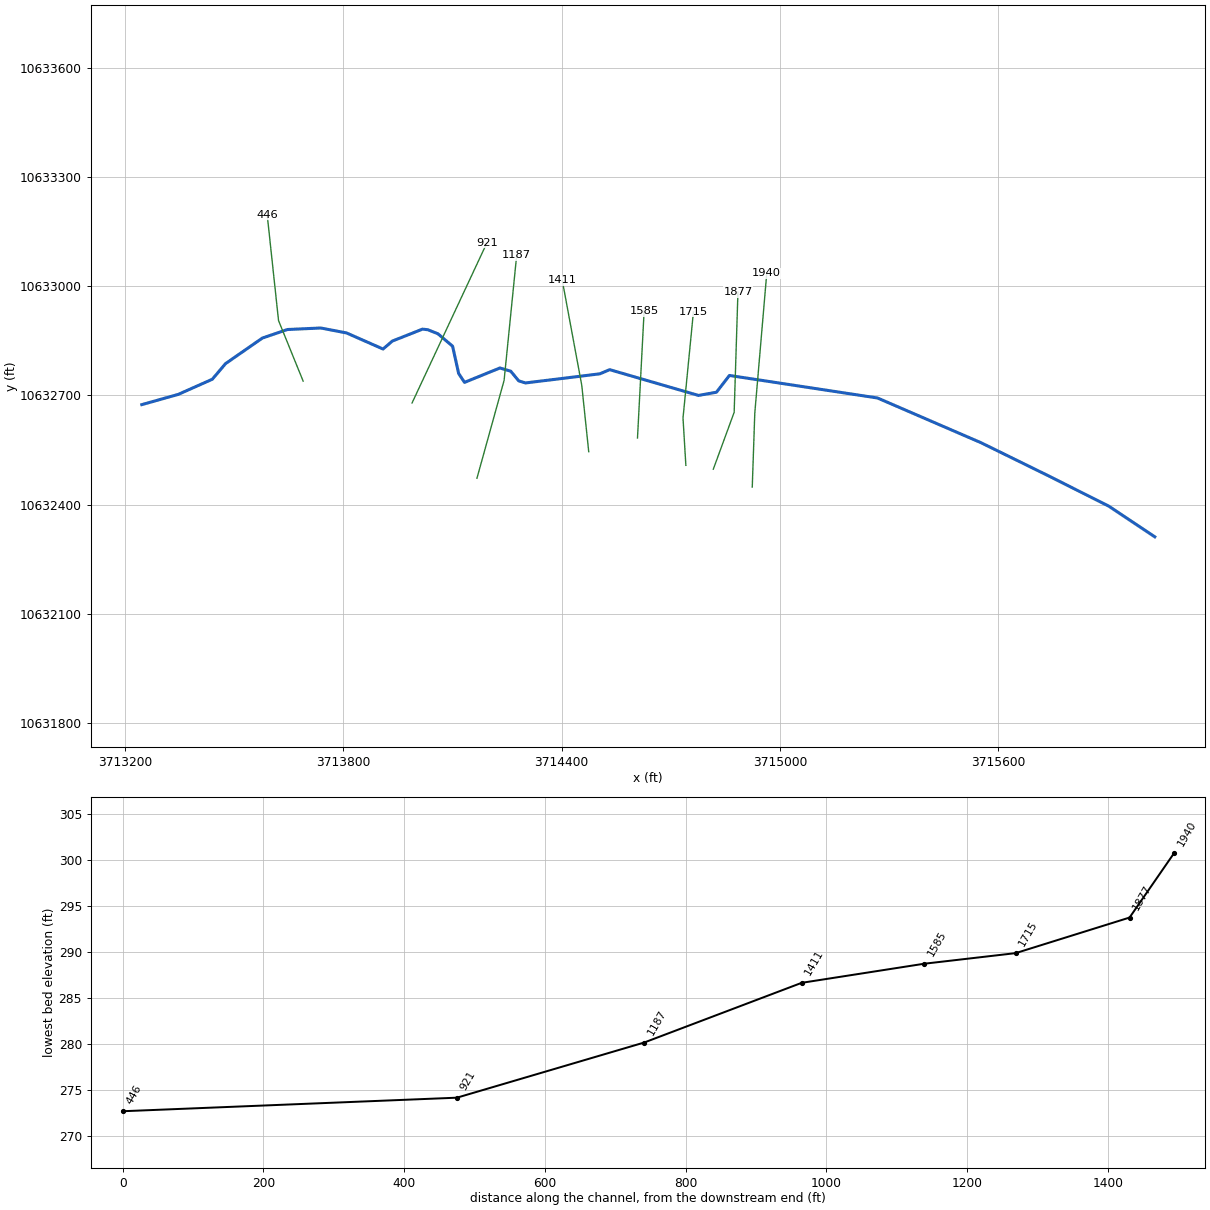
--- UNT 195 IN BOCR.prj (project) ---

Proj Title=UNT 195 IN BOCR Base Level Engineering
Current Plan=p01
Default Exp/Contr=0.3,0.1
English Units
Geom File=g01
Flow File=f01
Plan File=p01
Y Axis Title=Elevation
X Axis Title(PF)=Main Channel Distance
X Axis Title(XS)=Station
BEGIN DESCRIPTION:
UNT 195 IN BOCR
END DESCRIPTION:
DSS Export Rating Curves= 0
DSS Export Rating Curve Sorted= 0
DSS Export Volume Flow Curves= 0
DXF OffsetX= 0
DXF OffsetY= 0
DXF ScaleX= 1
DXF ScaleY= 10

--- UNT 195 IN BOCR.p01 (plan) ---

Plan Title=Multiple Run
Short Identifier=Multiple
Geom File=g01
Flow File=f01
Subcritical Flow
K Sum by GR= 0
Std Step Tol= 0.01
Critical Tol= 0.01
Num of Std Step Trials= 20
Max Error Tol= 0.3
Flow Tol Ratio= 0.001
Split Flow NTrial= 30
Split Flow Tol= 0.02
Split Flow Ratio= 0.02
Log Output Level= 0
Friction Slope Method= 1
Unsteady Friction Slope Method= 2
Unsteady Bridges Friction Slope Method= 1
Parabolic Critical Depth
Global Vel Dist=  1 , 1 , 1
Global Log Level= 0
CheckData=True
Encroach Param= -1, 0, 0, 0
BEGIN DESCRIPTION:
Multiple Run
END DESCRIPTION:

--- UNT 195 IN BOCR.f01 (steady flow) ---

Flow Title=Multiple
Program Version=4.10
Number of Profiles= 7
Profile Names=10-year,25-year,50-year,1pct_min,100-year,1pct_plu,500-year
River Rch & RM=UNT 195 IN BOCR,Reach-1         ,1940
      66      76      83      68      92     124     110
Boundary for River Rch & Prof#=UNT 195 IN BOCR,Reach-1         , 1
Up Type= 0
Dn Type= 3
Dn Slope=0.005
Boundary for River Rch & Prof#=UNT 195 IN BOCR,Reach-1         , 2
Up Type= 0
Dn Type= 3
Dn Slope=0.005
Boundary for River Rch & Prof#=UNT 195 IN BOCR,Reach-1         , 3
Up Type= 0
Dn Type= 3
Dn Slope=0.005
Boundary for River Rch & Prof#=UNT 195 IN BOCR,Reach-1         , 4
Up Type= 0
Dn Type= 3
Dn Slope=0.005
Boundary for River Rch & Prof#=UNT 195 IN BOCR,Reach-1         , 5
Up Type= 0
Dn Type= 3
Dn Slope=0.005
Boundary for River Rch & Prof#=UNT 195 IN BOCR,Reach-1         , 6
Up Type= 0
Dn Type= 3
Dn Slope=0.005
Boundary for River Rch & Prof#=UNT 195 IN BOCR,Reach-1         , 7
Up Type= 0
Dn Type= 3
Dn Slope=0.005
DSS Import GetInterval= 0
DSS Import GetPeak= 0
DSS Import FillOption= 0

--- UNT 195 IN BOCR.g01 (geometry) ---

Geom Title=Existing Conditions
Program Version=4.10

River Reach=UNT 195 IN BOCR ,Reach-1
Reach XY= 30
      3716030.99     10632311.38      3715904.18     10632395.91
      3715738.44      10632479.2      3715553.38     10632570.05
      3715268.54     10632693.11      3714861.47     10632754.99
      3714825.93     10632708.94      3714776.45     10632700.09
      3714532.26     10632770.93      3714505.09     10632759.46
      3714300.83     10632734.41      3714282.08     10632740.14
      3714260.21     10632766.71      3714230.52     10632775.56
      3714133.13     10632735.98      3714116.98     10632760.46
      3714100.31     10632835.46      3714059.69     10632869.83
      3714032.08     10632880.77       3714017.5     10632882.33
      3713934.69     10632849.52      3713909.17     10632827.64
      3713808.65     10632871.91      3713737.81     10632885.46
      3713646.15     10632881.29       3713577.4     10632857.85
      3713476.09     10632787.54      3713439.64     10632744.57
      3713345.89      10632702.9      3713245.84     10632674.79

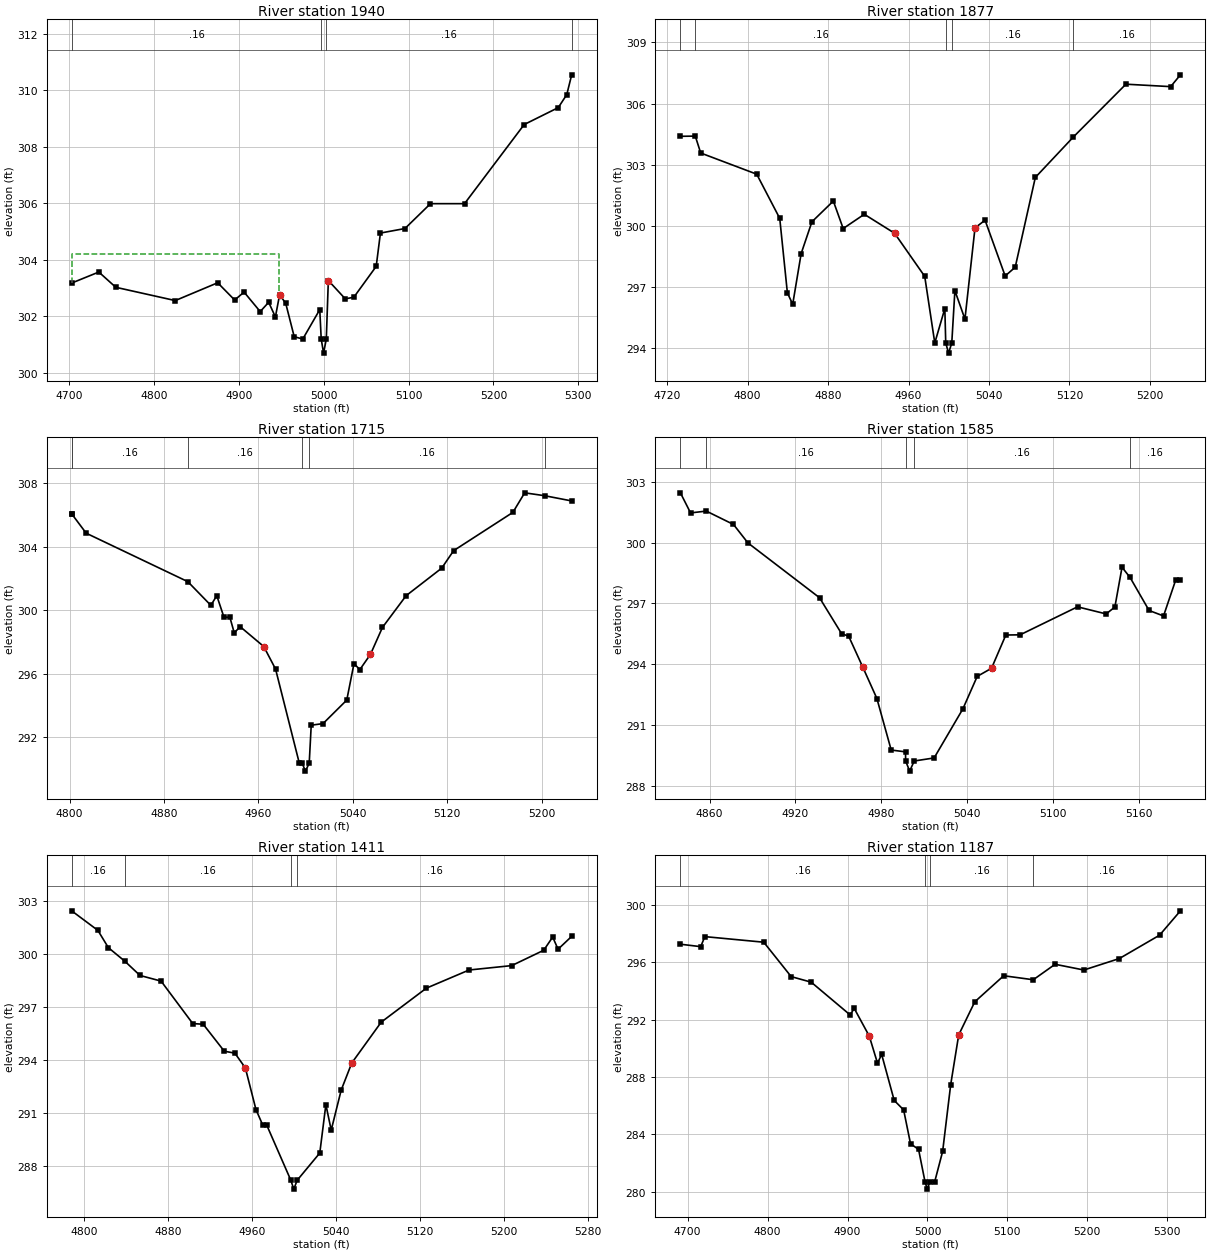
Type RM Length L Ch R = 1 ,1940    ,63,63,63
BEGIN DESCRIPTION:
Mapping XS 183f1a99
END DESCRIPTION:
XS GIS Cut Line= 3
      3714924.28     10632448.21      3714931.22      10632651.3
      3714964.15     10633035.98
#Sta/Elev= 30
  4702.9  303.18  4734.9  303.57  4754.9  303.03    4825  302.56    4875  303.19
    4895  302.58  4906.1  302.86  4925.1  302.17  4935.1   302.5    4943  301.98
    4948  302.77  4955.2  302.46  4965.2  301.28  4975.3   301.2  4995.3  302.24
    4997   301.2  4999.8   300.7    5003   301.2  5005.4  303.27  5025.4  302.62
  5035.5  302.68  5061.8  303.77  5066.8  304.95  5095.7  305.11  5125.8  305.99
  5165.9  305.99  5236.2  308.79  5276.4  309.39  5286.4  309.85  5292.2  310.55
#Mann= 4 ,-1 , 0
  4702.9     .16       0    4997     .16       0    5003     .16       0
  5292.2     .16       0
#XS Ineff= 2 , 0
          4947.5  304.21
Permanent Ineff=
       F       F
Bank Sta=4948,5005.4
XS Rating Curve= 0 ,0
Exp/Cntr=0.3,0.1

Type RM Length L Ch R = 1 ,1877    ,162,162,162
BEGIN DESCRIPTION:
Mapping XS ab92ec29
END DESCRIPTION:
XS GIS Cut Line= 3
      3714817.21     10632497.43      3714874.51      10632653.7
      3714884.93     10632984.39
#Sta/Elev= 30
  4733.1  304.39  4747.9   304.4  4753.3  303.57    4809  302.53  4831.9  300.36
  4839.5   296.7  4844.8  296.14  4853.2  298.63  4863.9  300.19  4885.2  301.21
    4895  299.86    4916  300.56  4946.1  299.63  4976.1  297.51  4986.1  294.24
  4996.1  295.93    4997  294.24  4999.8  293.74    5003  294.24  5006.1  296.81
  5016.1  295.41  5026.1  299.89  5036.1  300.27  5056.1  297.53  5066.1  297.96
  5086.1  302.37    5124  304.36  5176.2  306.95  5220.7  306.83  5230.4  307.41
#Mann= 5 ,-1 , 0
  4733.1     .16       0  4747.9     .16       0    4997     .16       0
    5003     .16       0    5124     .16       0
Bank Sta=4946.1,5026.1
XS Rating Curve= 0 ,0
Exp/Cntr=0.3,0.1

Type RM Length L Ch R = 1 ,1715    ,130,130,130
BEGIN DESCRIPTION:
Mapping XS a20bb0b7
END DESCRIPTION:
XS GIS Cut Line= 3
       3714741.7     10632507.89      3714733.89     10632638.08
      3714762.53     10632929.75
#Sta/Elev= 30
  4801.8  306.04  4802.1  306.04  4814.1  304.85  4900.2   301.8  4919.7  300.31
  4924.7  300.92  4930.8  299.56  4935.8  299.56  4939.5  298.58  4944.5  298.97
  4964.5  297.72  4974.5   296.3  4994.6  290.38    4997  290.38  4999.8  289.88
    5003  290.38  5004.7  292.77  5014.7  292.87  5034.8  294.35  5040.9  296.64
  5045.9  296.27  5054.9  297.23    5065  298.92  5085.1  300.92  5115.2  302.65
  5125.3  303.75  5175.5  306.16  5185.5  307.39  5202.3  307.21  5225.3  306.88
#Mann= 6 ,-1 , 0
  4801.8     .16       0  4802.1     .16       0  4900.2     .16       0
    4997     .16       0    5003     .16       0  5202.3     .16       0
Bank Sta=4964.5,5054.9
XS Rating Curve= 0 ,0
Exp/Cntr=0.3,0.1

Type RM Length L Ch R = 1 ,1585    ,174,174,174
BEGIN DESCRIPTION:
UNT 195 IN BOCR 3.0
END DESCRIPTION:
XS GIS Cut Line= 2
      3714608.72     10632583.09      3714626.94     10632932.01
#Sta/Elev= 30
  4839.6  302.45  4846.7  301.46  4857.7  301.55  4876.7  300.89  4886.8  299.98
  4936.8  297.28  4952.2  295.51  4957.2  295.38  4966.9  293.88  4976.9  292.31
  4986.9  289.77  4996.9  289.68    4997  289.23  4999.8  288.73    5003  289.23
  5016.9  289.38    5037   291.8    5047   293.4    5057   293.8    5067  295.44
    5077  295.45  5117.1  296.83  5137.1  296.48  5143.2  296.82  5148.2  298.78
  5153.8  298.28  5167.1  296.65  5177.2  296.38  5185.6  298.13    5189  298.13
#Mann= 5 ,-1 , 0
  4839.6     .16       0  4857.7     .16       0    4997     .16       0
    5003     .16       0  5153.8     .16       0
Bank Sta=4966.9,5057
XS Rating Curve= 0 ,0
Exp/Cntr=0.3,0.1

Type RM Length L Ch R = 1 ,1411    ,224,224,224
BEGIN DESCRIPTION:
Mapping XS 160069c7
END DESCRIPTION:
XS GIS Cut Line= 3
      3714474.63     10632545.35      3714455.53     10632727.69
      3714401.93     10633016.42
#Sta/Elev= 30
  4787.9  302.46  4812.9  301.35  4822.9  300.37  4838.6   299.6  4853.1  298.79
  4873.2  298.47  4903.4  296.06  4913.4  296.02  4933.5  294.49  4943.6  294.38
  4953.6  293.54  4963.7  291.18    4970  290.32  4973.8  290.32    4997  287.16
  4999.8  286.66    5003  287.16  5024.6  288.71  5030.4  291.46  5035.5  290.01
    5045  292.28  5055.1  293.82  5083.2  296.14  5126.3  298.07    5167   299.1
  5207.7  299.35  5238.2  300.22  5246.8  300.97  5251.9  300.28  5264.9  301.01
#Mann= 4 ,-1 , 0
  4787.9     .16       0  4838.6     .16       0    4997     .16       0
    5003     .16       0
Bank Sta=4953.6,5055.1
XS Rating Curve= 0 ,0
Exp/Cntr=0.3,0.1

Type RM Length L Ch R = 1 ,1187    ,266,266,266
BEGIN DESCRIPTION:
Mapping XS aebb38b8
END DESCRIPTION:
XS GIS Cut Line= 3
      3714167.33     10632472.46      3714241.99     10632741.58
      3714276.62     10633086.17
#Sta/Elev= 30
  4690.9  297.27  4716.3   297.1  4721.5   297.8  4795.2  297.41  4829.5  295.01
  4854.6  294.62  4903.2  292.34  4908.4  292.79  4927.2  290.86  4937.5  288.97
  4942.7  289.58  4958.4  286.37  4970.2  285.71  4978.8  283.35  4988.9  282.95
    4997  280.68  4999.8  280.18    5003  280.68    5009  280.68    5019  282.81
  5029.1  287.48  5039.1  290.94  5059.2  293.25  5095.4  295.07  5132.4  294.79
  5159.7  295.87  5195.7  295.47  5240.1  296.27  5290.4   297.9  5316.5   299.6
#Mann= 4 ,-1 , 0
  4690.9     .16       0    4997     .16       0    5003     .16       0
  5132.4     .16       0
Bank Sta=4927.2,5039.1
XS Rating Curve= 0 ,0
Exp/Cntr=0.3,0.1

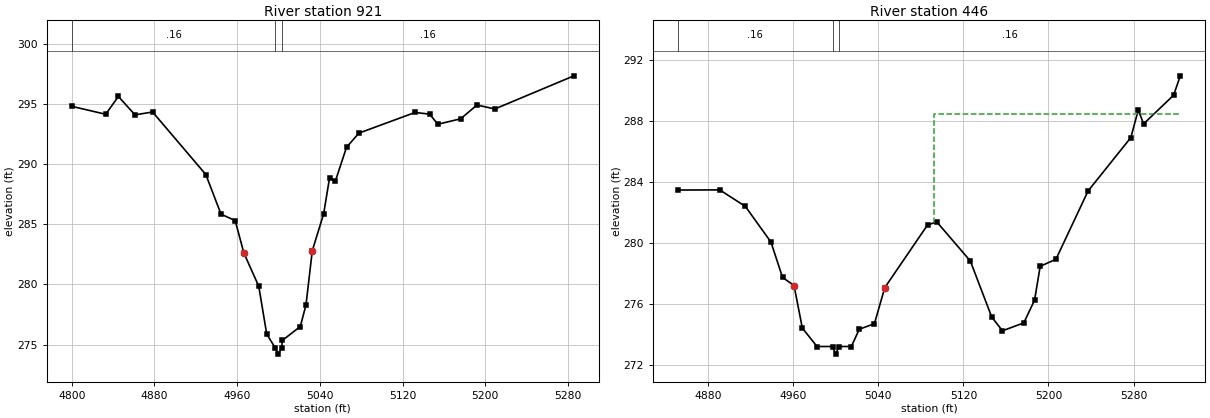
Type RM Length L Ch R = 1 ,921     ,475,475,475
BEGIN DESCRIPTION:
UNT 195 IN BOCR 2.0
END DESCRIPTION:
XS GIS Cut Line= 2
      3713988.91     10632679.37      3714194.63     10633119.46
#Sta/Elev= 30
    4800  294.83  4832.8  294.17  4845.1  295.65  4861.2  294.12  4878.2  294.36
  4929.7  289.15  4944.4  285.85  4958.1  285.32  4966.5  282.62  4980.9  279.85
  4988.6  275.87    4997   274.7  4999.8   274.2    5003   274.7  5003.7  275.34
  5021.1   276.5  5026.6   278.3  5032.7  282.81  5043.7  285.89  5049.4  288.88
    5055   288.6  5065.8  291.42  5077.8   292.6  5132.1  294.32  5146.3  294.18
  5154.1  293.34  5176.2  293.79    5192  294.94  5209.3  294.61  5285.8  297.37
#Mann= 3 ,-1 , 0
    4800     .16       0    4997     .16       0    5003     .16       0
Bank Sta=4966.5,5032.7
XS Rating Curve= 0 ,0
Exp/Cntr=0.3,0.1

Type RM Length L Ch R = 1 ,446     ,0,0,0
BEGIN DESCRIPTION:
UNT 195 IN BOCR 1.0
END DESCRIPTION:
XS GIS Cut Line= 3
      3713689.44     10632739.32      3713621.74     10632905.97
      3713590.62     10633196.43
#Sta/Elev= 30
  4851.9  283.49    4891   283.5    4915  282.42  4939.1  280.08    4950  277.76
  4960.8  277.23  4968.6  274.44  4982.4  273.23    4997  273.23  4999.8  272.73
    5003  273.23  5014.7  273.23  5022.1  274.36  5036.4  274.73  5046.1  277.09
  5086.3   281.2    5095   281.4  5126.5  278.84  5146.6  275.17  5156.7  274.26
  5176.8  274.78  5186.9  276.27  5192.2  278.49    5207  278.95  5237.2  283.43
  5277.4  286.93  5284.4  288.74  5289.4  287.83  5317.6  289.71  5323.9  290.98
#Mann= 3 ,-1 , 0
  4851.9     .16       0    4997     .16       0    5003     .16       0
#XS Ineff= 2 , 0
                         5092.47          288.48
Permanent Ineff=
       F       F
Bank Sta=4960.8,5046.1
XS Rating Curve= 0 ,0
Exp/Cntr=0.3,0.1

Chan Stop Cuts=-1
Use User Specified Reach Order=0
Composite Channel Slope=5