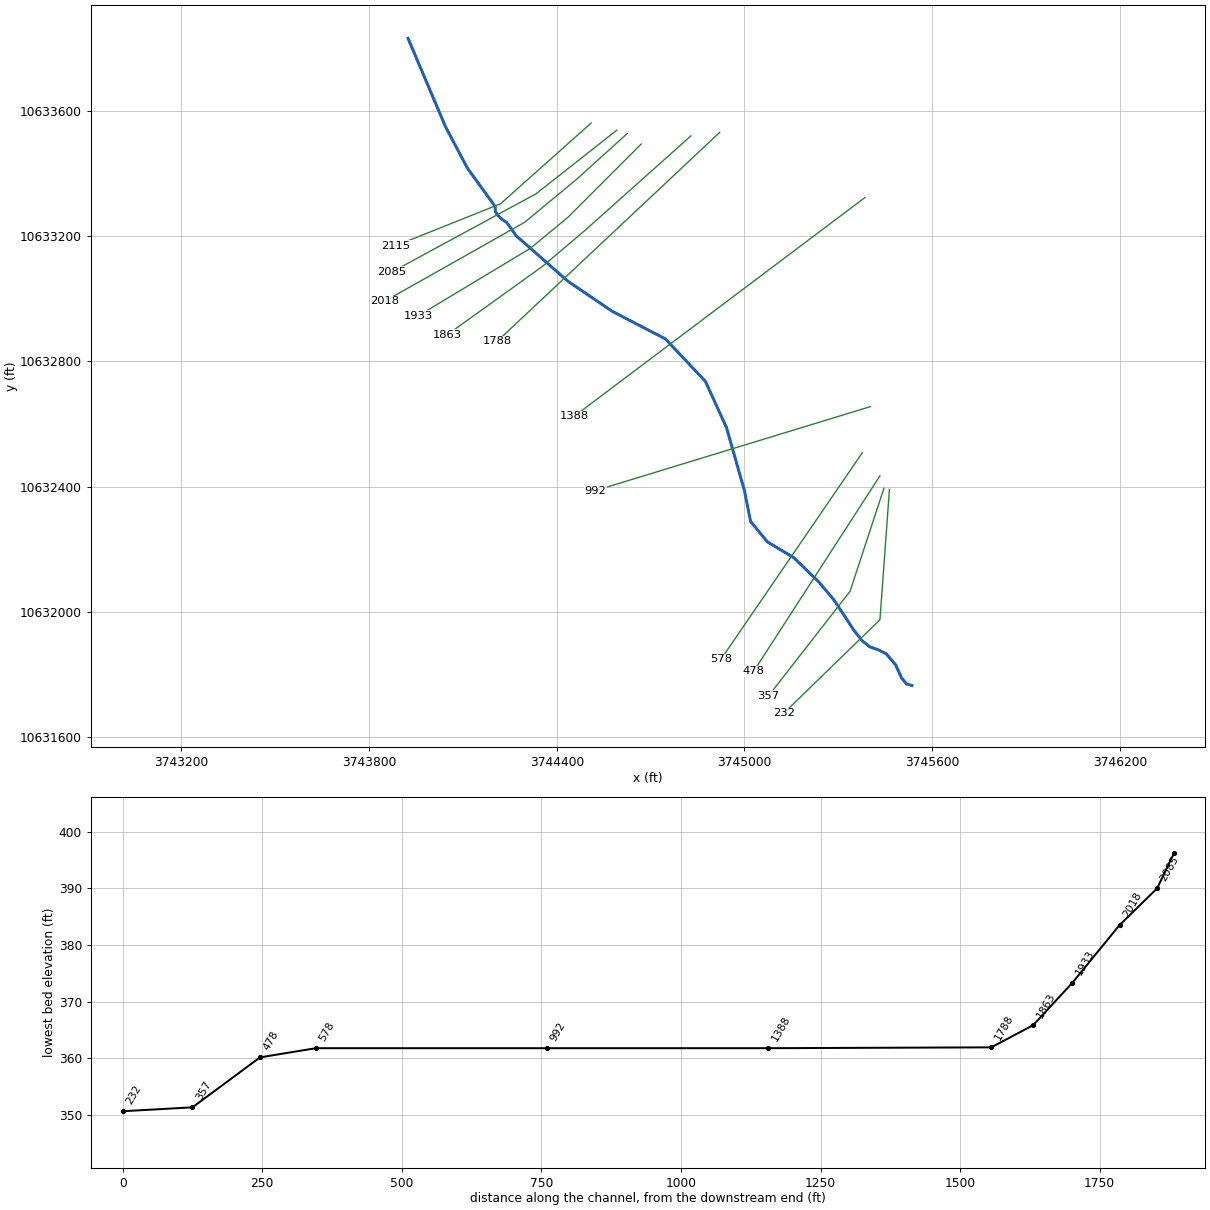
--- UNT 196 IN BOCR.prj (project) ---

Proj Title=UNT 196 IN BOCR Base Level Engineering
Current Plan=p01
Default Exp/Contr=0.3,0.1
English Units
Geom File=g01
Flow File=f01
Plan File=p01
Y Axis Title=Elevation
X Axis Title(PF)=Main Channel Distance
X Axis Title(XS)=Station
BEGIN DESCRIPTION:
UNT 196 IN BOCR
END DESCRIPTION:
DSS Export Rating Curves= 0
DSS Export Rating Curve Sorted= 0
DSS Export Volume Flow Curves= 0
DXF OffsetX= 0
DXF OffsetY= 0
DXF ScaleX= 1
DXF ScaleY= 10

--- UNT 196 IN BOCR.p01 (plan) ---

Plan Title=Multiple Run
Short Identifier=Multiple
Geom File=g01
Flow File=f01
Subcritical Flow
K Sum by GR= 0
Std Step Tol= 0.01
Critical Tol= 0.01
Num of Std Step Trials= 20
Max Error Tol= 0.3
Flow Tol Ratio= 0.001
Split Flow NTrial= 30
Split Flow Tol= 0.02
Split Flow Ratio= 0.02
Log Output Level= 0
Friction Slope Method= 1
Unsteady Friction Slope Method= 2
Unsteady Bridges Friction Slope Method= 1
Parabolic Critical Depth
Global Vel Dist=  1 , 1 , 1
Global Log Level= 0
CheckData=True
Encroach Param= -1, 0, 0, 0
BEGIN DESCRIPTION:
Multiple Run
END DESCRIPTION:

--- UNT 196 IN BOCR.f01 (steady flow) ---

Flow Title=Multiple
Number of Profiles=7
Profile Names=10-year,25-year,50-year,1pct_min,100-year,1pct_plu,500-year
River Rch & RM= UNT 196 IN BOCR,Reach-1,2115
     106     128     144     121     163     220     207
Boundary for River Rch & Prof#=UNT 196 IN BOCR,Reach-1,1
Up Type=0
Dn Type=3
Dn Slope=0.005
Boundary for River Rch & Prof#=UNT 196 IN BOCR,Reach-1,2
Up Type=0
Dn Type=3
Dn Slope=0.005
Boundary for River Rch & Prof#=UNT 196 IN BOCR,Reach-1,3
Up Type=0
Dn Type=3
Dn Slope=0.005
Boundary for River Rch & Prof#=UNT 196 IN BOCR,Reach-1,4
Up Type=0
Dn Type=3
Dn Slope=0.005
Boundary for River Rch & Prof#=UNT 196 IN BOCR,Reach-1,5
Up Type=0
Dn Type=3
Dn Slope=0.005
Boundary for River Rch & Prof#=UNT 196 IN BOCR,Reach-1,6
Up Type=0
Dn Type=3
Dn Slope=0.005
Boundary for River Rch & Prof#=UNT 196 IN BOCR,Reach-1,7
Up Type=0
Dn Type=3
Dn Slope=0.005

--- UNT 196 IN BOCR.g01 (geometry) ---

Geom Title=Existing Conditions
Program Version=4.10

River Reach=UNT 196 IN BOCR ,Reach-1
Reach XY= 30
      3743924.51      10633832.8       3744044.3     10633550.25
      3744114.61     10633417.44      3744202.99     10633295.19
       3744203.6     10633279.02       3744210.9     10633267.22
      3744226.52     10633252.98      3744239.89     10633244.14
      3744270.86     10633201.29      3744434.92     10633056.76
      3744576.85     10632960.41      3744747.42     10632871.87
      3744875.03     10632736.45      3744942.74     10632588.01
      3745000.03     10632386.19      3745019.56     10632288.53
      3745072.94     10632223.43      3745157.58     10632172.65
      3745237.01     10632095.83      3745285.18     10632038.53
      3745321.64     10631983.85      3745347.68     10631943.48
      3745376.33     10631907.02      3745401.07     10631887.49
      3745427.11     10631878.38      3745453.15     10631865.36
       3745483.1      10631830.2      3745502.63     10631787.23
      3745518.26       10631769.       3745535.5       10631764.

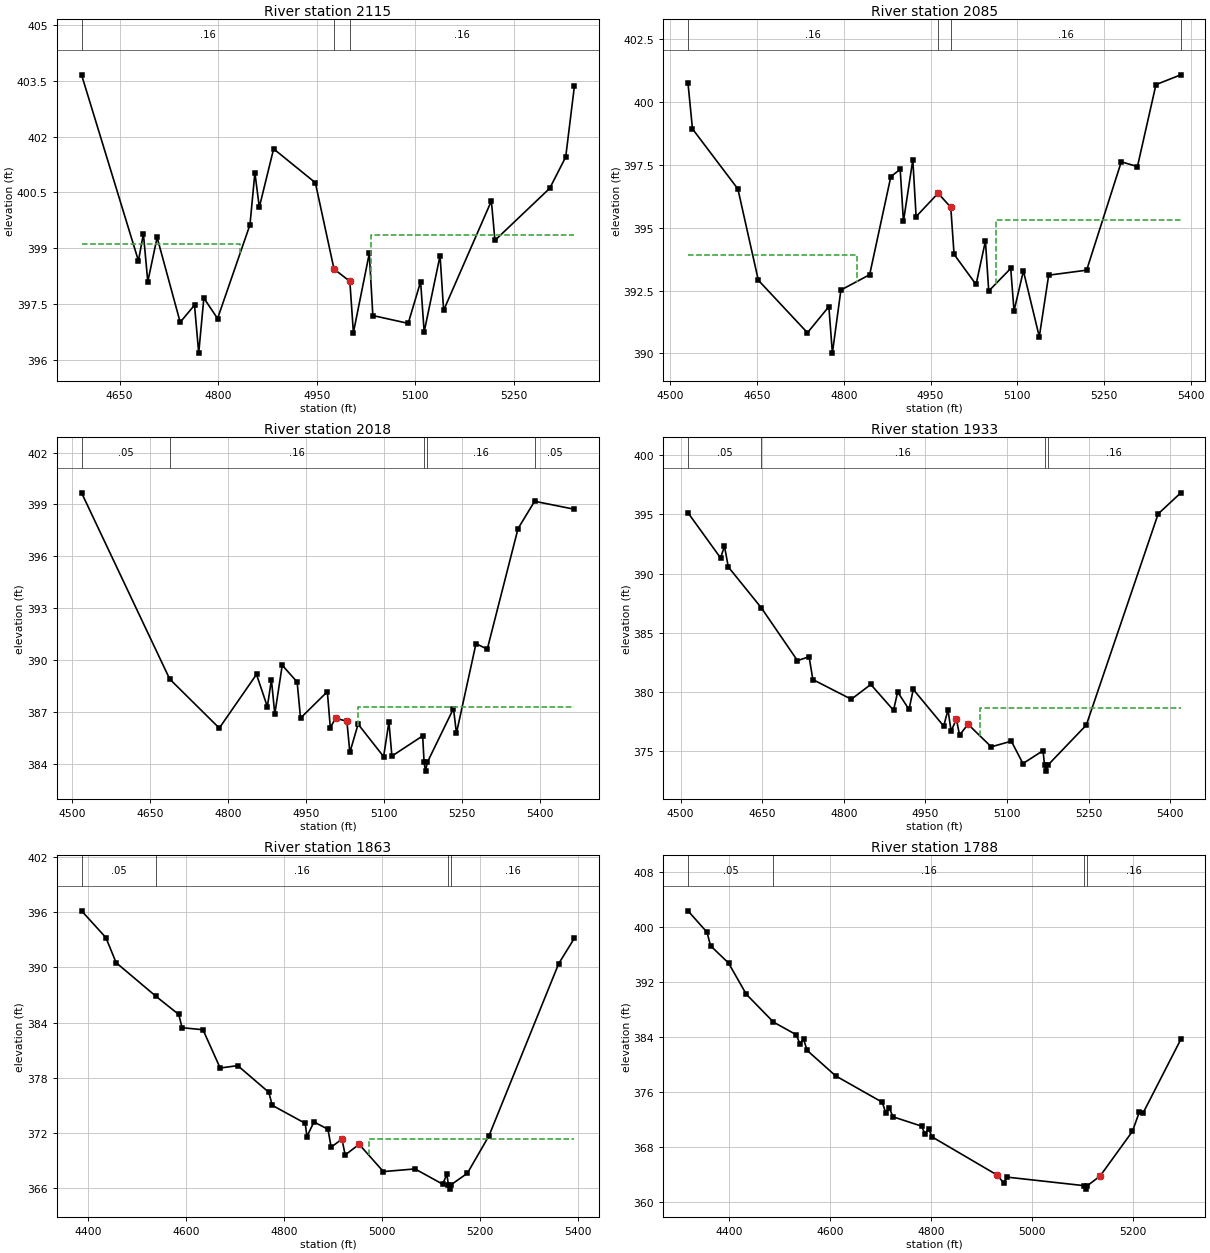
Type RM Length L Ch R = 1 ,2115    ,30,30,30
BEGIN DESCRIPTION:
UNT 196 IN BOCR 6.0
END DESCRIPTION:
XS GIS Cut Line= 3
      3744509.97     10633562.15      3744220.25      10633303.9
      3743884.25      10633169.5
#Sta/Elev= 30
  4592.2  403.66  4678.8  398.66  4686.3  399.39    4693   398.1  4707.2  399.29
  4742.3  397.01  4764.1  397.47  4770.5  396.18  4778.3  397.66  4799.2  397.11
  4848.5  399.63    4856  401.03  4862.7   400.1  4884.5  401.67    4948  400.76
  4976.4  398.44  5000.5  398.11  5005.9  396.73  5030.1  398.86  5035.5  397.19
  5089.3  396.98  5108.2   398.1  5113.6  396.75  5137.8   398.8  5143.2  397.33
  5215.9  400.27  5221.3  399.21  5304.7  400.61    5329  401.45  5342.2  403.35
#Mann= 3 , 0 , 0
  4592.2     .16       0  4976.4     .07       0  5000.5     .16       0
#XS Ineff= 2 , 0
         4832.95   399.1 5032.39          399.35
Permanent Ineff=
       F       F
Bank Sta=4976.4,5000.5
XS Rating Curve= 0 ,0
Exp/Cntr=0.3,0.1

Type RM Length L Ch R = 1 ,2085    ,67,67,67
BEGIN DESCRIPTION:
Mapping XS 98925328
END DESCRIPTION:
XS GIS Cut Line= 3
      3744591.78     10633539.14      3744333.94     10633335.99
      3743873.81     10633086.43
#Sta/Elev= 30
  4530.7  400.76  4538.5  398.93    4617  396.54  4652.3  392.91  4737.2  390.82
  4774.2  391.86  4780.3  390.01    4795  392.52  4844.7  393.13  4881.3  397.03
  4897.5  397.32  4903.1  395.25  4919.3   397.7    4925  395.44    4963  396.37
  4984.9  395.81  4990.6  393.94  5028.6  392.74  5044.8  394.47  5050.5  392.48
  5088.5  393.38  5094.2  391.69  5110.4  393.28  5137.9  390.66  5154.1  393.11
  5219.7  393.31  5279.6  397.62  5307.5  397.43  5339.5  400.69  5382.4  401.08
#Mann= 4 ,-1 , 0
  4530.7     .16       0    4963     .03       0  4984.9     .16       0
  5382.4     .05       0
#XS Ineff= 2 , 0
         4822.16   393.9  5062.5          395.29
Permanent Ineff=
       F       F
Bank Sta=4963,4984.9
XS Rating Curve= 0 ,0
Exp/Cntr=0.3,0.1

Type RM Length L Ch R = 1 ,2018    ,85,85,85
BEGIN DESCRIPTION:
Mapping XS b5ea7814
END DESCRIPTION:
XS GIS Cut Line= 4
      3744625.64     10633528.73      3744464.15     10633382.87
      3744297.48     10633244.85      3743849.61     10632992.27
#Sta/Elev= 30
  4518.6  399.67  4688.2  388.89  4783.6  386.05  4855.2  389.16  4876.1  387.29
  4883.9  388.85  4890.4  386.86  4904.7  389.69  4933.4  388.72  4939.9  386.63
  4991.5  388.16  4997.2  386.08  5007.4  386.62  5029.1  386.45  5034.8  384.64
  5050.7  386.28  5099.8   384.4    5110  386.41  5115.7  384.43  5174.9   385.6
  5177.7  384.06  5180.4  383.56  5183.7  384.06  5234.2  387.18  5239.9  385.76
  5277.5  390.94  5299.2  390.62  5358.4   397.6  5390.3  399.18  5466.8  398.72
#Mann= 5 ,-1 , 0
  4518.6     .05       0  4688.2     .16       0  5177.7     .07       0
  5183.7     .16       0  5390.3     .05       0
#XS Ineff= 2 , 0
                         5049.77          387.25
Permanent Ineff=
       F       F
Bank Sta=5007.4,5029.1
XS Rating Curve= 0 ,0
Exp/Cntr=0.3,0.1

Type RM Length L Ch R = 1 ,1933    ,70,70,70
BEGIN DESCRIPTION:
Mapping XS 6fdf1531
END DESCRIPTION:
XS GIS Cut Line= 4
      3744669.86     10633494.82      3744435.51     10633260.47
      3744315.71     10633161.52      3743956.31     10632945.35
#Sta/Elev= 30
  4513.4  395.14  4573.4  391.32  4580.5  392.32  4587.6  390.56  4648.3  387.11
  4714.8  382.65  4736.1  382.98  4743.1  381.05  4813.8  379.39  4849.6  380.64
  4891.4  378.46    4899     380  4919.9  378.53  4927.7  380.22  4983.7  377.12
  4991.5   378.5  4997.3   376.7    5007  377.71  5012.8  376.36  5028.4  377.28
  5071.1  375.37    5108  375.85  5129.4  373.96  5166.3  375.05  5169.1  373.82
  5171.9  373.32  5175.1  373.82  5245.9  377.21    5378  395.04  5419.6  396.82
#Mann= 4 ,-1 , 0
  4513.4     .05       0  4648.3     .16       0  5169.1     .07       0
  5175.1     .16       0
#XS Ineff= 2 , 0
                         5051.14          378.67
Permanent Ineff=
       F       F
Bank Sta=5007,5028.4
XS Rating Curve= 0 ,0
Exp/Cntr=0.3,0.1

Type RM Length L Ch R = 1 ,1863    ,75,75,75
BEGIN DESCRIPTION:
Mapping XS 1a218dad
END DESCRIPTION:
XS GIS Cut Line= 4
      3744828.77     10633520.92      3744490.19     10633218.81
      3744354.78     10633104.22      3744050.12     10632885.49
#Sta/Elev= 30
  4386.4  396.17  4436.1  393.25    4457  390.52  4538.8  386.84  4584.9  384.88
  4591.6  383.44  4634.3  383.22  4669.4  379.05  4705.3  379.31  4768.9   376.4
  4775.6  374.99    4843  373.03  4846.6  371.59  4860.9  373.18  4889.5  372.38
    4896  370.43  4918.1  371.31  4924.6  369.58  4953.2  370.74  5002.6  367.77
  5067.2  368.06  5123.7   366.4  5132.2  367.48  5135.4  366.36  5138.1  365.86
  5141.4  366.36    5174  367.58  5218.2  371.66  5360.6  390.42  5392.6  393.18
#Mann= 4 ,-1 , 0
  4386.4     .05       0  4538.8     .16       0  5135.4     .07       0
  5141.4     .16       0
#XS Ineff= 2 , 0
                          4972.5          371.35
Permanent Ineff=
       F       F
Bank Sta=4918.1,4953.2
XS Rating Curve= 0 ,0
Exp/Cntr=0.3,0.1

Type RM Length L Ch R = 1 ,1788    ,400,400,400
BEGIN DESCRIPTION:
Mapping XS a8f49954
END DESCRIPTION:
XS GIS Cut Line= 2
      3744920.89     10633532.28      3744209.77     10632864.52
#Sta/Elev= 30
  4318.9   402.4  4356.7  399.28  4363.6  397.32  4399.2  394.81  4434.4  390.27
  4488.2  386.22  4533.5  384.38  4540.4  383.06  4547.7  383.77  4554.6  382.12
  4611.2  378.41  4703.5  374.57  4710.4  373.05  4717.7  373.72  4724.5  372.46
  4781.2   371.1    4788  369.99  4795.3  370.69  4802.2  369.53  4929.7  364.04
  4943.8  362.88  4951.1  363.68  5103.5  362.44  5106.2  361.94  5109.5  362.44
  5134.8  363.85  5198.6  370.33  5212.5  373.17  5219.8  373.01  5294.4   383.7
#Mann= 4 ,-1 , 0
  4318.9     .05       0  4488.2     .16       0  5103.5     .07       0
  5109.5     .16       0
Bank Sta=4929.7,5134.8
XS Rating Curve= 0 ,0
Exp/Cntr=0.3,0.1

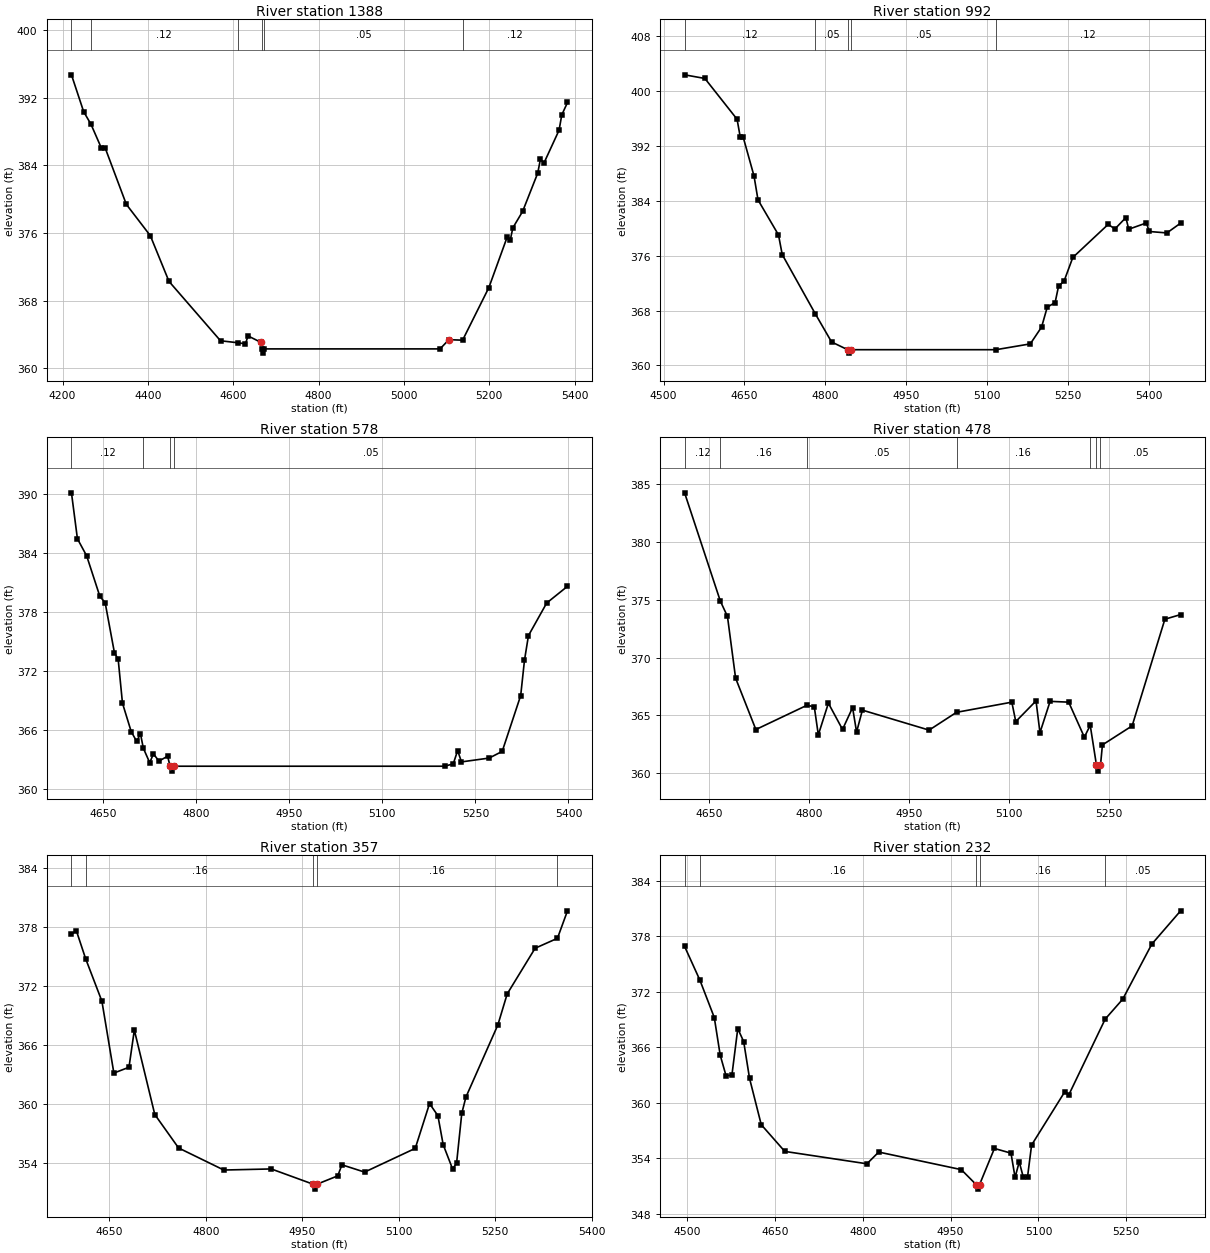
Type RM Length L Ch R = 1 ,1388    ,396,396,396
BEGIN DESCRIPTION:
Mapping XS c3292e84
END DESCRIPTION:
XS GIS Cut Line= 2
      3745385.34     10633323.98      3744456.47     10632625.15
#Sta/Elev= 30
  4220.9  394.68  4249.5  390.32  4266.6  388.84  4291.2     386  4299.5  386.09
  4349.5  379.37  4405.7  375.67  4449.4  370.27  4570.2  363.25  4610.4  363.02
  4628.5  362.89  4634.8  363.82  4663.9  363.09  4667.2  362.29  4669.9  361.79
  4673.2  362.29  5084.6  362.29  5105.4  363.38  5137.5  363.32  5199.1  369.54
  5241.7  375.47  5249.1  375.13  5255.3   376.6  5278.2  378.54  5313.6  383.07
  5319.9  384.71  5328.2  384.26  5363.6  388.14  5369.9  389.94  5383.3  391.41
#Mann= 6 ,-1 , 0
  4220.9     .16       0  4266.6     .12       0  4610.4     .05       0
  4667.2    .033       0  4673.2     .05       0  5137.5     .12       0
Bank Sta=4663.9,5105.4
XS Rating Curve= 0 ,0
Exp/Cntr=0.3,0.1

Type RM Length L Ch R = 1 ,992     ,414,414,414
BEGIN DESCRIPTION:
Mapping XS 1cbbf07f
END DESCRIPTION:
XS GIS Cut Line= 2
      3745402.68     10632655.55      3744523.09     10632386.91
#Sta/Elev= 30
    4539  402.38  4576.6  401.85  4636.3   395.9  4642.3  393.25  4647.5  393.33
  4667.7  387.63  4675.1  384.14  4713.1  379.03    4720  376.17  4781.5   367.5
  4811.5  363.42  4841.3  362.29    4844  361.79  4847.3  362.29  5116.3  362.29
    5180  363.14  5200.9  365.59  5211.4  368.49    5226  369.17  5232.3  371.53
  5242.8  372.34  5258.8  375.74  5324.4  380.57  5336.9   379.9  5357.2  381.56
  5362.5  379.86  5395.3  380.78  5400.5  379.53  5433.3  379.32  5458.7  380.75
#Mann= 5 ,-1 , 0
    4539     .12       0  4781.5     .05       0  4841.3    .033       0
  4847.3     .05       0  5116.3     .12       0
Bank Sta=4841.3,4847.3
XS Rating Curve= 0 ,0
Exp/Cntr=0.3,0.1

Type RM Length L Ch R = 1 ,578     ,100,100,100
BEGIN DESCRIPTION:
Mapping XS d815abdd
END DESCRIPTION:
XS GIS Cut Line= 2
      3745376.65     10632508.02      3744925.24     10631848.27
#Sta/Elev= 30
    4599  390.13  4608.6  385.45  4623.5  383.71  4644.8  379.58  4653.3  378.94
  4668.2  373.86  4674.3  373.16  4681.2  368.71  4695.3  365.81  4704.1  364.82
  4710.2   365.6  4714.8  364.13  4725.1  362.65  4731.1  363.55    4740  362.81
  4753.9  363.31    4758  362.29  4760.7  361.79    4764  362.29  5200.4  362.29
  5214.3  362.53  5221.4  363.89  5227.5  362.73  5272.2  363.12  5293.2   363.8
    5323  369.49  5329.1  373.08  5335.5  375.59  5364.9  378.91  5398.4  380.61
#Mann= 4 ,-1 , 0
    4599     .12       0  4714.8     .05       0    4758    .033       0
    4764     .05       0
Bank Sta=4758,4764
XS Rating Curve= 0 ,0
Exp/Cntr=0.3,0.1

Type RM Length L Ch R = 1 ,478     ,121,121,121
BEGIN DESCRIPTION:
Mapping XS 5ddcb14b
END DESCRIPTION:
XS GIS Cut Line= 2
      3745433.07     10632434.23      3745029.37     10631809.15
#Sta/Elev= 30
  4613.1  384.26  4666.7  374.89  4677.4  373.56  4689.6  368.22    4720  363.77
    4797  365.88  4807.7  365.72  4813.7  363.31  4828.8  366.05    4850  363.78
  4865.1  365.67  4871.1  363.55  4879.8  365.45  4979.9  363.72    5021  365.26
    5104  366.14  5109.9  364.46  5140.3  366.25  5146.2   363.5  5161.4  366.21
  5189.3  366.14  5212.8  363.11  5221.6  364.14    5231  360.67  5233.7  360.17
    5237  360.67  5239.9  362.44  5284.5  364.09  5333.6  373.32  5357.2  373.72
#Mann= 7 ,-1 , 0
  4613.1     .12       0  4666.7     .16       0    4797     .05       0
    5021     .16       0  5221.6     .05       0    5231    .033       0
    5237     .05       0
Bank Sta=5231,5237
XS Rating Curve= 0 ,0
Exp/Cntr=0.3,0.1

Type RM Length L Ch R = 1 ,357     ,125,125,125
BEGIN DESCRIPTION:
Mapping XS 4b033943
END DESCRIPTION:
XS GIS Cut Line= 3
      3745446.07     10632395.13      3745337.56     10632065.27
      3745077.16     10631731.09
#Sta/Elev= 30
  4591.2  377.24  4598.8   377.6  4613.2  374.76  4638.5  370.44  4657.1  363.14
  4680.6  363.73  4688.9  367.51  4720.7  358.93  4757.7  355.53    4828  353.29
  4901.7   353.4  4966.8  351.85  4969.6  351.35  4972.8  351.85  5005.1   352.7
  5011.5  353.82  5046.8  353.08  5125.5  355.49  5147.7  360.04  5160.7  358.81
  5168.9  355.87  5183.4  353.42  5189.7  353.96  5197.8  359.04  5204.2  360.69
  5253.9  368.03  5268.4  371.18  5311.8  375.82  5346.5  376.83  5362.1  379.62
#Mann= 5 ,-1 , 0
  4591.2     .12       0  4613.2     .16       0  4966.8     .07       0
  4972.8     .16       0  5346.5     .05       0
Bank Sta=4966.8,4972.8
XS Rating Curve= 0 ,0
Exp/Cntr=0.3,0.1

Type RM Length L Ch R = 1 ,232     ,0,0,0
BEGIN DESCRIPTION:
UNT 196 IN BOCR 1.0
END DESCRIPTION:
XS GIS Cut Line= 3
      3745463.43     10632390.79      3745433.05     10631974.12
      3745125.16     10631674.91
#Sta/Elev= 30
  4495.7  376.91  4521.9  373.25  4546.4  369.22  4556.5  365.15  4566.5  362.92
  4576.5  362.99  4586.5  368.02  4596.6  366.62  4606.6  362.64  4626.6  357.63
  4666.8  354.74  4807.1   353.4  4827.2  354.67  4968.2  352.77  4993.5  351.16
  4996.2  350.66  4999.5  351.16  5024.8  355.06  5053.1  354.55  5060.1  351.93
  5067.2  353.61  5074.2  351.93  5081.4     352  5088.3  355.43  5144.9  361.18
  5152.1  360.89    5214  369.05    5244  371.21  5293.6  377.16  5342.8  380.76
#Mann= 5 ,-1 , 0
  4495.7     .12       0  4521.9     .16       0  4993.5     .07       0
  4999.5     .16       0    5214     .05       0
Bank Sta=4993.5,4999.5
XS Rating Curve= 0 ,0
Exp/Cntr=0.3,0.1

Chan Stop Cuts=-1
Use User Specified Reach Order=0
Composite Channel Slope=5