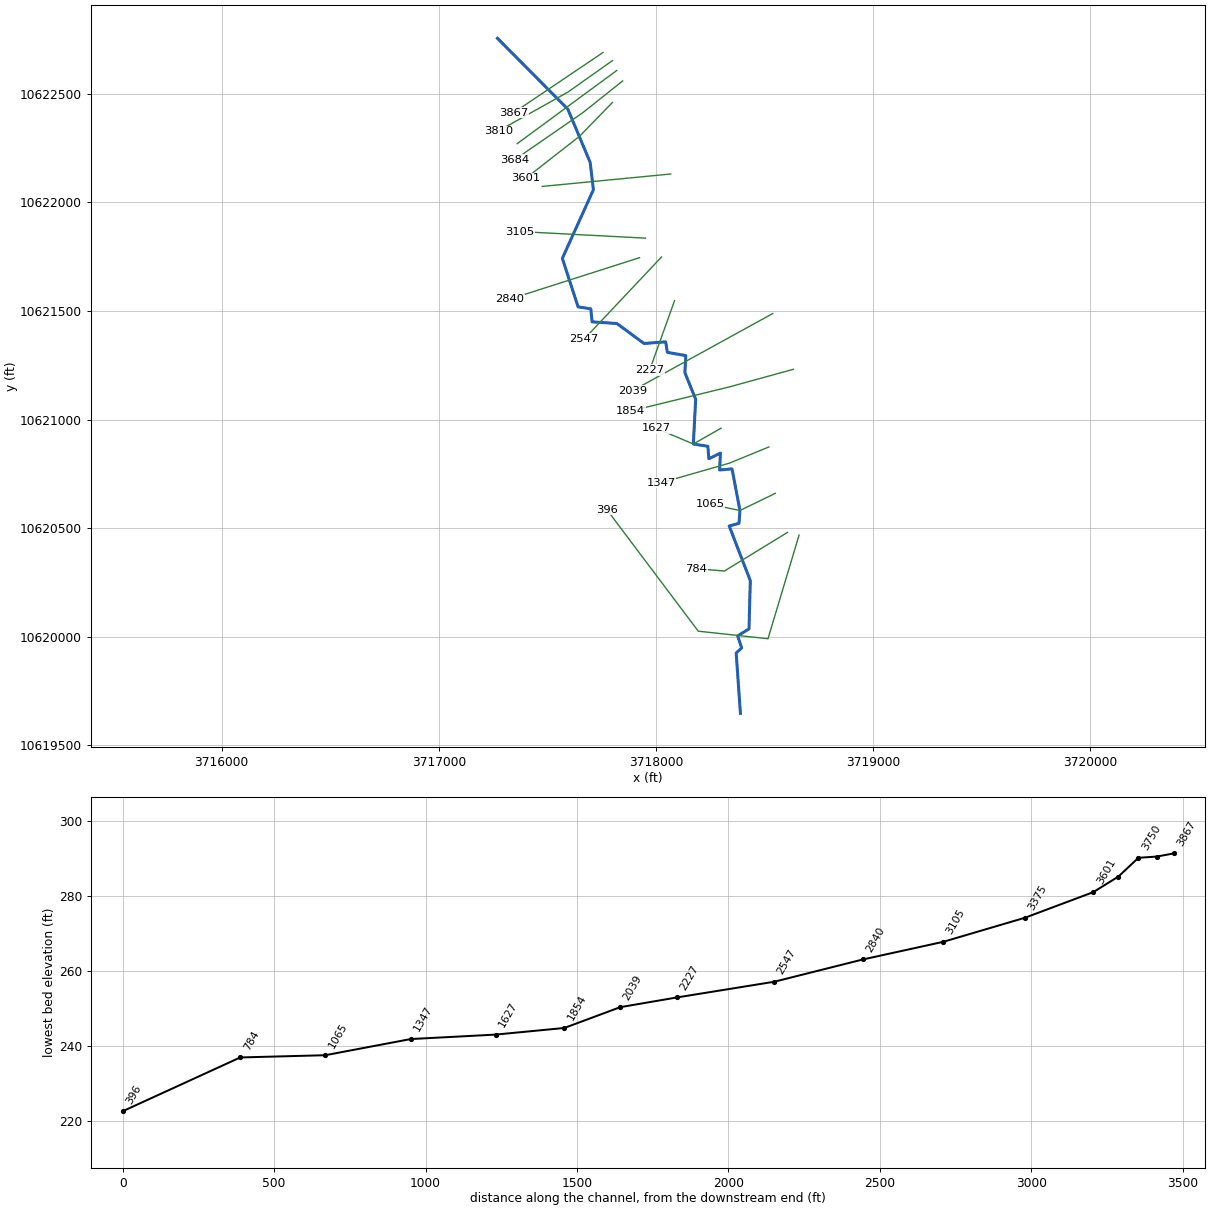
--- UNT 198 IN BOCR.prj (project) ---

Proj Title=UNT 198 IN BOCR Base Level Engineering
Current Plan=p01
Default Exp/Contr=0.3,0.1
English Units
Geom File=g01
Flow File=f01
Plan File=p01
BEGIN DESCRIPTION:
UNT 198 IN BOCR
END DESCRIPTION:

--- UNT 198 IN BOCR.p01 (plan) ---

Plan Title=Multiple Run
Short Identifier=Multiple
Geom File=g01
Flow File=f01
Subcritical Flow
K Sum by GR= 0
Std Step Tol= 0.01
Critical Tol= 0.01
Num of Std Step Trials= 20
Max Error Tol= 0.3
Flow Tol Ratio= 0.001
Split Flow NTrial= 30
Split Flow Tol= 0.02
Split Flow Ratio= 0.02
Log Output Level= 0
Friction Slope Method= 1
Unsteady Friction Slope Method= 2
Unsteady Bridges Friction Slope Method= 1
Parabolic Critical Depth
Global Vel Dist=  1 , 1 , 1
Global Log Level= 0
CheckData=True
Encroach Param= -1, 0, 0, 0
BEGIN DESCRIPTION:
Multiple Run
END DESCRIPTION:

--- UNT 198 IN BOCR.f01 (steady flow) ---

Flow Title=Multiple
Number of Profiles=7
Profile Names=10-year,25-year,50-year,1pct_min,100-year,1pct_plu,500-year
River Rch & RM= UNT 198 IN BOCR,Reach-1,3867
     126     153     174     145     196     266     252
Boundary for River Rch & Prof#=UNT 198 IN BOCR,Reach-1,1
Up Type=0
Dn Type=3
Dn Slope=0.005
Boundary for River Rch & Prof#=UNT 198 IN BOCR,Reach-1,2
Up Type=0
Dn Type=3
Dn Slope=0.005
Boundary for River Rch & Prof#=UNT 198 IN BOCR,Reach-1,3
Up Type=0
Dn Type=3
Dn Slope=0.005
Boundary for River Rch & Prof#=UNT 198 IN BOCR,Reach-1,4
Up Type=0
Dn Type=3
Dn Slope=0.005
Boundary for River Rch & Prof#=UNT 198 IN BOCR,Reach-1,5
Up Type=0
Dn Type=3
Dn Slope=0.005
Boundary for River Rch & Prof#=UNT 198 IN BOCR,Reach-1,6
Up Type=0
Dn Type=3
Dn Slope=0.005
Boundary for River Rch & Prof#=UNT 198 IN BOCR,Reach-1,7
Up Type=0
Dn Type=3
Dn Slope=0.005

--- UNT 198 IN BOCR.g01 (geometry) ---

Geom Title=Existing Conditions

River Reach=UNT 198 IN BOCR,Reach-1
Reach XY= 30
      3717270.24     10622755.53      3717594.14     10622429.61
      3717696.98     10622184.47      3717712.02     10622058.43
      3717568.92     10621742.37      3717641.40     10621518.93
      3717700.07     10621509.84      3717705.98     10621450.01
      3717820.22     10621442.37      3717944.87     10621350.35
      3718044.69     10621357.93      3718052.57     10621309.40
      3718137.57     10621294.56      3718133.23     10621216.43
      3718182.92     10621093.05      3718172.21     10620887.43
      3718239.00     10620876.90      3718243.69     10620819.61
      3718296.99     10620845.48      3718293.17     10620767.70
      3718350.31     10620772.95      3718386.77     10620581.11
      3718382.43     10620522.08      3718337.29     10620509.93
      3718434.51     10620258.19      3718428.43     10620035.97
      3718376.35     10620003.85      3718394.58     10619948.29
      3718369.41     10619924.86      3718389.00     10619647.00

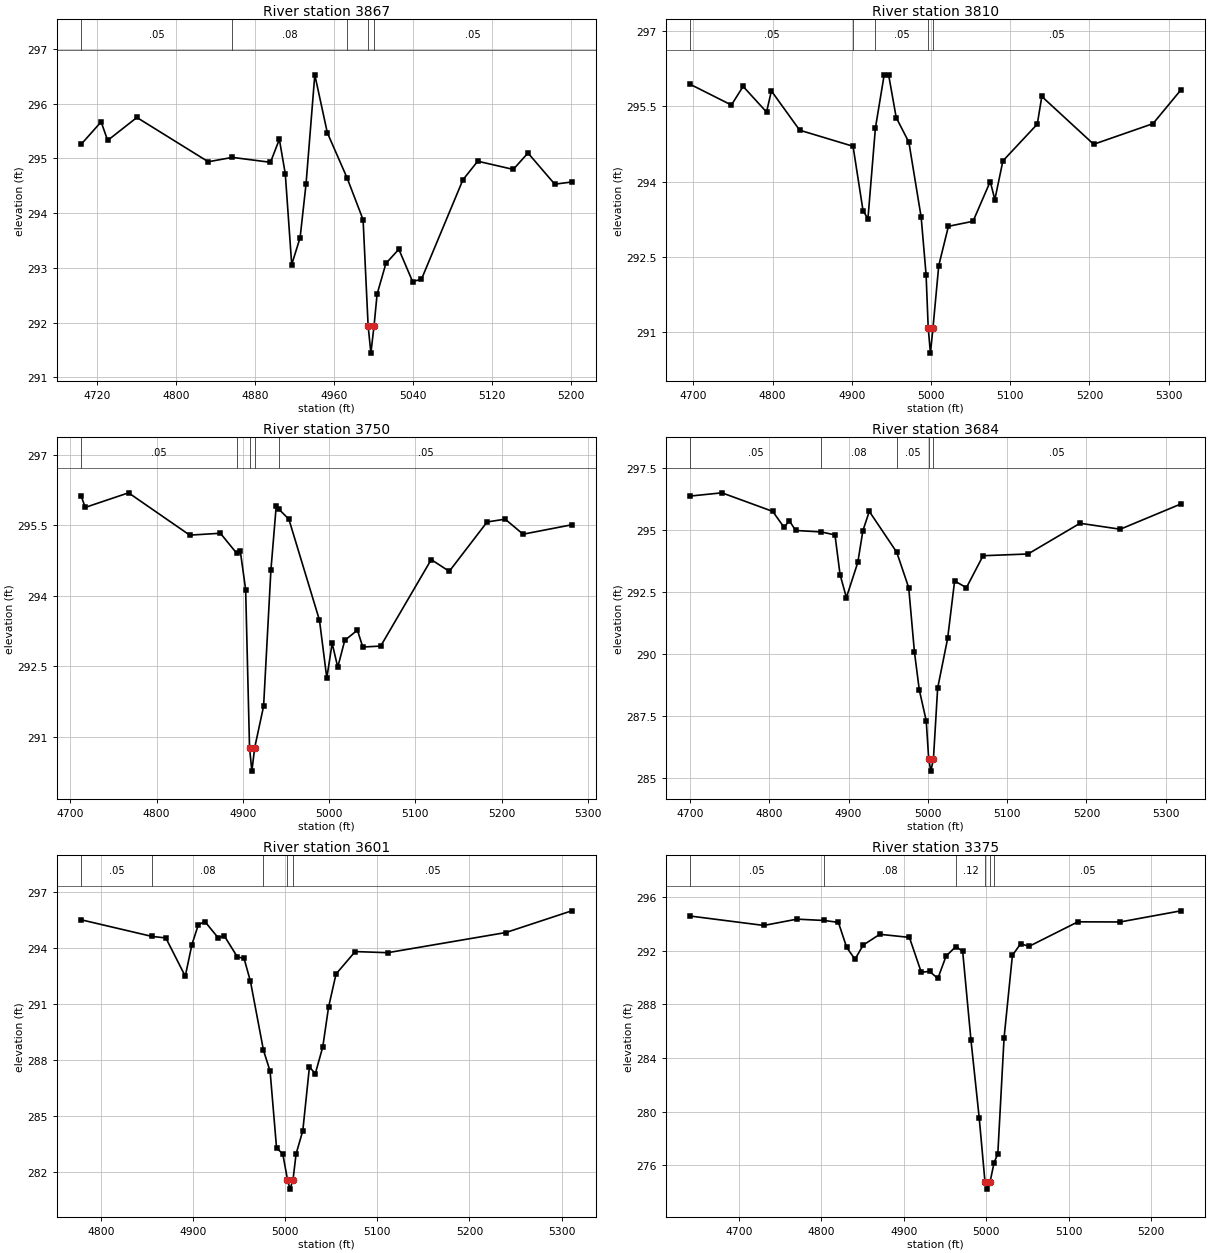
Type RM Length L Ch R = 1,3867,57,57,57
BEGIN DESCRIPTION:
UNT 198 IN BOCR 8.0
END DESCRIPTION:
XS GIS Cut Line= 2
      3717756.40     10622690.41      3717344.38     10622412.84
#Sta/Elev= 30
  4703.9  295.26  4724.1  295.67  4730.7  295.33  4760.3  295.75  4832.6  294.94
  4857.0  295.02  4895.6  294.93  4904.6  295.35  4910.6  294.72  4917.1  293.06
  4925.6  293.55  4931.6  294.53  4940.5  296.53  4953.2  295.47  4973.3  294.64
  4989.4  293.88  4994.5  291.94  4997.3  291.44  5000.5  291.94  5003.6  292.52
  5012.5  293.08  5025.6  293.34  5039.5  292.75  5048.5  292.79  5090.5  294.61
  5105.5  294.95  5141.5  294.80  5156.4  295.10  5183.5  294.53  5200.7  294.57
#Mann=5,-1,0
  4703.9    0.05       0  4857.0    0.08       0  4973.3    0.05       0
  4994.5    0.04       0  5000.5    0.05       0
Bank Sta=4994.5,5000.5
Exp/Cntr=0.3,0.1

Type RM Length L Ch R = 1,3810,60,60,60
BEGIN DESCRIPTION:
Mapping XS ceeac7b5
END DESCRIPTION:
XS GIS Cut Line= 3
      3717799.85     10622653.03      3717595.44     10622508.51
      3717273.58     10622328.12
#Sta/Elev= 30
  4696.2  295.93  4748.0  295.52  4762.8  295.89  4792.4  295.38  4798.5  295.80
  4834.2  295.02  4901.6  294.70  4914.2  293.42  4920.4  293.26  4929.8  295.06
  4940.9  296.12  4946.5  296.12  4956.1  295.27  4972.1  294.78  4987.6  293.29
  4993.8  292.15  4996.5  291.09  4999.3  290.59  5002.5  291.09  5009.8  292.33
  5022.0  293.11  5053.1  293.21  5074.8  294.00  5080.6  293.64  5090.8  294.41
  5134.2  295.14  5139.9  295.69  5205.4  294.74  5280.3  295.15  5315.5  295.82
#Mann=5,-1,0
  4696.2    0.05       0  4901.6    0.08       0  4929.8    0.05       0
  4996.5    0.04       0  5002.5    0.05       0
Bank Sta=4996.5,5002.5
Exp/Cntr=0.3,0.1

Type RM Length L Ch R = 1,3750,66,66,66
BEGIN DESCRIPTION:
Mapping XS 0d2c63c6
END DESCRIPTION:
XS GIS Cut Line= 2
      3717819.32     10622607.30      3717360.96     10622270.48
#Sta/Elev= 30
  4712.6  296.12  4717.3  295.88  4767.5  296.19  4838.5  295.29  4874.0  295.33
  4893.1  294.90  4897.1  294.95  4903.3  294.13  4907.8  290.77  4910.5  290.27
  4913.8  290.77  4924.1  291.65  4932.6  294.55  4938.8  295.92  4941.9  295.84
  4953.4  295.63  4988.9  293.48  4997.4  292.25  5003.6  292.99  5010.1  292.48
  5018.2  293.05  5032.9  293.27  5039.1  292.91  5059.9  292.93  5118.5  294.77
  5139.4  294.52  5183.3  295.57  5204.2  295.63  5225.0  295.31  5281.4  295.51
#Mann=5,-1,0
  4712.6    0.05       0  4893.1    0.08       0  4907.8    0.04       0
  4913.8    0.08       0  4941.9    0.05       0
Bank Sta=4907.8,4913.8
Exp/Cntr=0.3,0.1

Type RM Length L Ch R = 1,3684,83,83,83
BEGIN DESCRIPTION:
Mapping XS 04e32081
END DESCRIPTION:
XS GIS Cut Line= 3
      3717846.70     10622559.27      3717661.84     10622412.16
      3717347.07     10622194.94
#Sta/Elev= 30
  4700.5  296.37  4740.3  296.50  4804.4  295.75  4818.8  295.10  4825.2  295.38
  4833.3  294.98  4865.6  294.92  4882.9  294.80  4889.3  293.20  4897.3  292.27
  4911.7  293.69  4918.1  294.97  4926.2  295.75  4960.8  294.10  4975.9  292.67
  4983.1  290.08  4989.2  288.55  4998.0  287.29  5001.1  285.76  5003.8  285.26
  5007.1  285.76  5012.4  288.61  5025.0  290.62  5033.8  292.94  5048.7  292.67
  5069.7  293.96  5126.4  294.03  5192.0  295.27  5242.7  295.03  5319.2  296.05
#Mann=5,-1,0
  4700.5    0.05       0  4865.6    0.08       0  4960.8    0.05       0
  5001.1    0.03       0  5007.1    0.05       0
Bank Sta=5001.1,5007.1
Exp/Cntr=0.3,0.1

Type RM Length L Ch R = 1,3601,226,226,226
BEGIN DESCRIPTION:
UNT 198 IN BOCR 7.0
END DESCRIPTION:
XS GIS Cut Line= 3
      3717799.58     10622460.16      3717648.79     10622305.18
      3717399.64     10622110.21
#Sta/Elev= 30
  4778.4  295.50  4855.3  294.61  4870.3  294.53  4891.4  292.48  4898.6  294.17
  4905.6  295.24  4912.8  295.40  4926.9  294.55  4933.9  294.63  4948.0  293.51
  4955.2  293.44  4962.2  292.20  4976.3  288.52  4983.5  287.40  4990.5  283.30
  4997.3  282.97  5002.4  281.59  5005.1  281.09  5008.4  281.59  5011.7  282.97
  5019.0  284.21  5026.2  287.62  5032.6  287.27  5040.7  288.70  5047.0  290.83
  5055.1  292.60  5075.9  293.80  5111.2  293.74  5239.6  294.82  5311.0  295.98
#Mann=5,-1,0
  4778.4    0.05       0  4855.3    0.08       0  4976.3    0.05       0
  5002.4    0.03       0  5008.4    0.05       0
Bank Sta=5002.4,5008.4
Exp/Cntr=0.3,0.1

Type RM Length L Ch R = 1,3375,270,270,270
BEGIN DESCRIPTION:
Mapping XS 91cbcd42
END DESCRIPTION:
XS GIS Cut Line= 2
      3718068.27     10622130.84      3717476.24     10622073.55
#Sta/Elev= 30
  4641.1  294.58  4730.2  293.88  4770.4  294.35  4803.4  294.25  4820.6  294.11
  4830.6  292.25  4840.7  291.36  4850.7  292.42  4870.8  293.22  4906.7  292.99
  4921.1  290.39  4931.1  290.46  4941.2  289.93  4951.2  291.60  4963.1  292.31
  4971.3  291.95  4981.3  285.37  4991.4  279.51  4998.4  274.73  5001.2  274.23
  5004.4  274.73  5009.4  276.21  5013.9  276.86  5021.5  285.51  5031.6  291.65
  5041.6  292.52  5051.7  292.32  5111.0  294.15  5162.2  294.14  5235.9  294.97
#Mann=6,-1,0
  4641.1    0.05       0  4803.4    0.08       0  4963.1    0.12       0
  4998.4    0.07       0  5004.4    0.12       0  5009.4    0.05       0
Bank Sta=4998.4,5004.4
Exp/Cntr=0.3,0.1

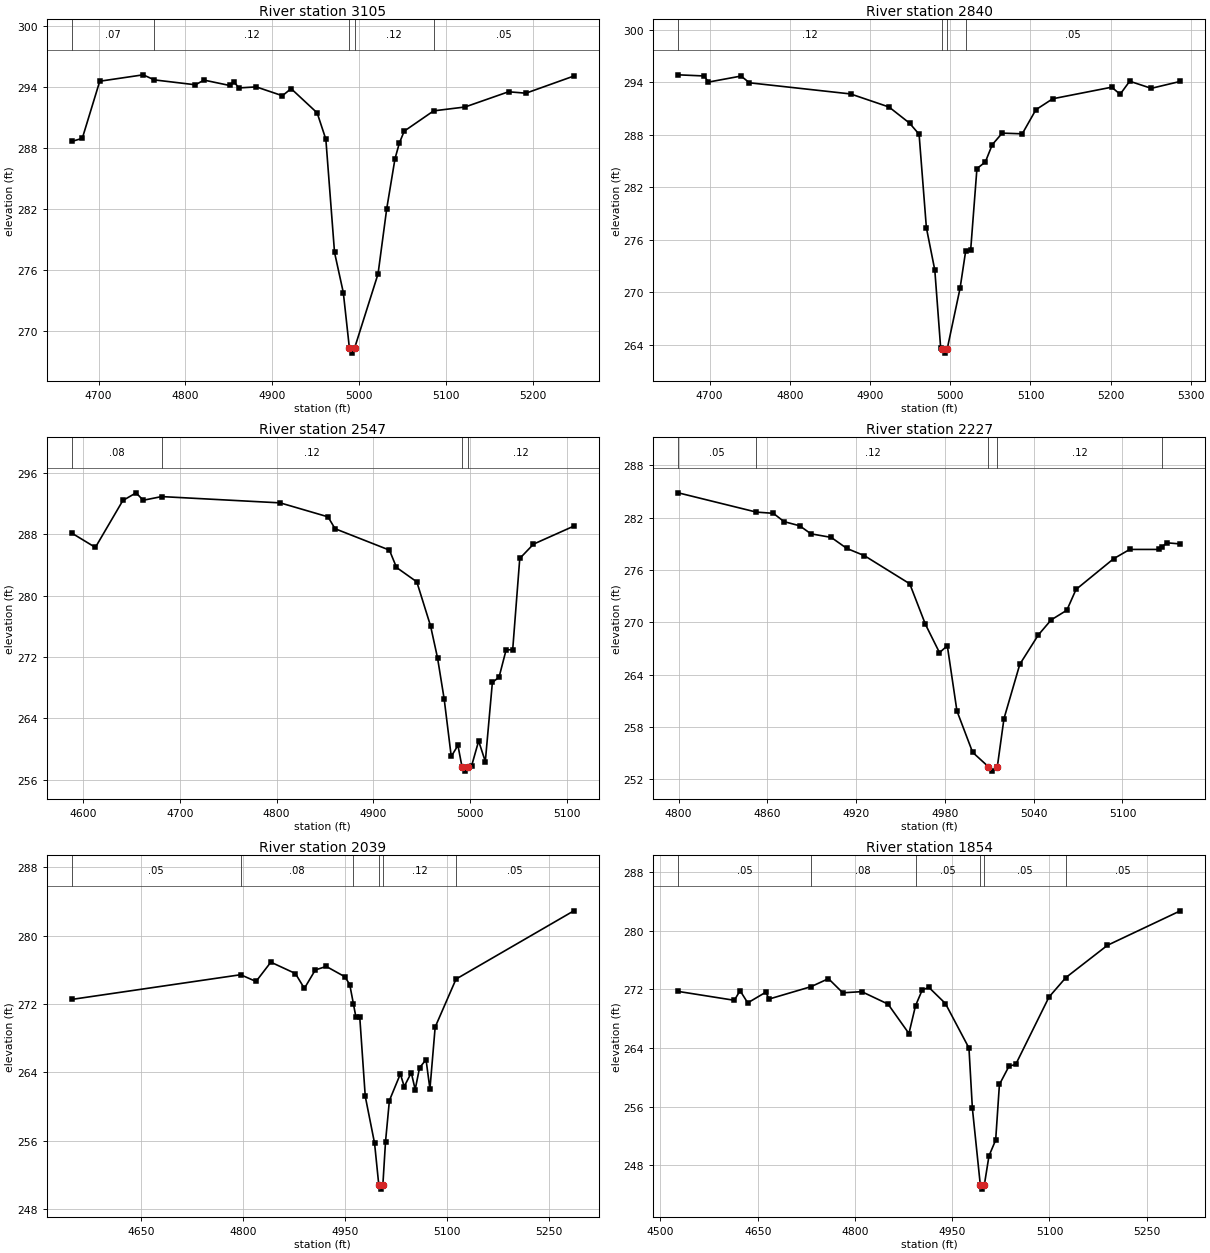
Type RM Length L Ch R = 1,3105,265,265,265
BEGIN DESCRIPTION:
Mapping XS 19626187
END DESCRIPTION:
XS GIS Cut Line= 2
      3717951.73     10621835.40      3717374.53     10621865.78
#Sta/Elev= 30
  4669.2  288.65  4681.3  288.95  4701.4  294.58  4751.4  295.21  4764.3  294.71
  4811.5  294.23  4821.5  294.69  4851.0  294.16  4856.0  294.51  4861.6  293.92
  4881.6  294.02  4911.7  293.15  4921.7  293.85  4951.7  291.46  4961.7  288.86
  4971.7  277.71  4981.8  273.76  4988.8  268.29  4991.5  267.79  4994.8  268.29
  5021.8  275.60  5031.8  282.03  5041.3  286.94  5046.3  288.48  5051.9  289.66
  5085.8  291.66  5121.9  292.04  5172.0  293.54  5192.0  293.40  5247.2  295.09
#Mann=5,-1,0
  4669.2    0.07       0  4764.3    0.12       0  4988.8    0.07       0
  4994.8    0.12       0  5085.8    0.05       0
Bank Sta=4988.8,4994.8
Exp/Cntr=0.3,0.1

Type RM Length L Ch R = 1,2840,293,293,293
BEGIN DESCRIPTION:
Mapping XS 34a26751
END DESCRIPTION:
XS GIS Cut Line= 2
      3717924.20     10621745.43      3717328.13     10621554.82
#Sta/Elev= 30
  4661.0  294.83  4693.3  294.70  4698.6  294.00  4739.3  294.69  4749.8  293.92
  4875.8  292.65  4923.7  291.16  4949.3  289.32  4961.2  288.05  4970.3  277.38
  4980.8  272.55  4988.1  263.67  4990.3  263.58  4993.1  263.08  4996.3  263.58
  5012.3  270.49  5019.3  274.75  5025.5  274.85  5033.3  284.13  5043.8  284.89
  5052.4  286.86  5064.8  288.18  5089.8  288.10  5106.8  290.85  5127.8  292.10
  5201.3  293.42  5211.8  292.61  5223.7  294.10  5250.6  293.29  5286.8  294.08
#Mann=4,-1,0
  4661.0    0.12       0  4990.3    0.07       0  4996.3    0.12       0
  5019.3    0.05       0
Bank Sta=4990.3,4996.3
Exp/Cntr=0.3,0.1

Type RM Length L Ch R = 1,2547,320,320,320
BEGIN DESCRIPTION:
Mapping XS faf8c190
END DESCRIPTION:
XS GIS Cut Line= 2
      3718025.52     10621748.59      3717669.61     10621370.98
#Sta/Elev= 30
  4588.4  288.16  4612.8  286.29  4641.2  292.41  4654.9  293.41  4662.2  292.44
  4681.3  292.92  4803.8  292.10  4853.2  290.28  4860.5  288.73  4916.7  285.94
  4924.0  283.68  4945.0  281.80  4959.2  276.06  4966.4  271.90  4973.3  266.51
  4980.6  259.03  4987.5  260.48  4991.8  257.62  4994.5  257.12  4997.8  257.62
  5001.6  257.79  5008.9  261.05  5015.8  258.37  5023.1  268.69  5030.0  269.37
  5037.3  272.93  5044.1  272.95  5051.4  284.85  5065.6  286.72  5107.3  289.07
#Mann=4,-1,0
  4588.4    0.08       0  4681.3    0.12       0  4991.8    0.07       0
  4997.8    0.12       0
Bank Sta=4991.8,4997.8
Exp/Cntr=0.3,0.1

Type RM Length L Ch R = 1,2227,188,188,188
BEGIN DESCRIPTION:
Mapping XS 16dda49b
END DESCRIPTION:
XS GIS Cut Line= 2
      3718085.66     10621547.50      3717971.06     10621228.03
#Sta/Elev= 30
  4799.7  284.85  4852.5  282.64  4864.0  282.50  4871.2  281.55  4881.8  281.07
  4889.4  280.15  4903.1  279.74  4913.7  278.47  4925.5  277.65  4956.2  274.42
  4966.8  269.77  4976.3  266.53  4981.6  267.31  4988.1  259.84  4998.7  255.10
  5009.4  253.44  5012.1  252.94  5015.4  253.44  5019.9  258.96  5030.6  265.19
  5043.1  268.55  5051.8  270.28  5062.4  271.39  5068.6  273.77  5094.0  277.29
  5104.9  278.36  5124.7  278.36  5127.0  278.69  5130.0  279.12  5139.1  278.99
#Mann=5,-1,0
  4799.7    0.05       0  4852.5    0.12       0  5009.4    0.07       0
  5015.4    0.12       0  5127.0    0.05       0
Bank Sta=5009.4,5015.4
Exp/Cntr=0.3,0.1

Type RM Length L Ch R = 1,2039,185,185,185
BEGIN DESCRIPTION:
Mapping XS df188973
END DESCRIPTION:
XS GIS Cut Line= 2
      3718537.68     10621488.18      3717890.95     10621132.26
#Sta/Elev= 30
  4548.0  272.54  4796.3  275.43  4818.9  274.64  4840.7  276.90  4876.8  275.57
  4890.0  273.83  4906.1  275.99  4922.2  276.40  4949.6  275.19  4956.7  274.28
  4962.2  271.98  4965.7  270.51  4971.4  270.51  4979.5  261.20  4993.2  255.70
  4999.4  250.83  5002.1  250.33  5005.4  250.83  5009.3  255.88  5015.0  260.70
  5031.1  263.81  5036.8  262.34  5047.2  263.96  5052.9  261.99  5059.4  264.55
  5068.9  265.48  5074.6  262.04  5082.3  269.30  5113.0  274.92  5286.2  282.91
#Mann=6,-1,0
  4548.0    0.05       0  4796.3    0.08       0  4962.2    0.12       0
  4999.4    0.07       0  5005.4    0.12       0  5113.0    0.05       0
Bank Sta=4999.4,5005.4
Exp/Cntr=0.3,0.1

Type RM Length L Ch R = 1,1854,227,227,227
BEGIN DESCRIPTION:
Mapping XS dcf667e5
END DESCRIPTION:
XS GIS Cut Line= 3
      3718632.98     10621231.44      3718336.12     10621149.85
      3717882.92     10621039.14
#Sta/Elev= 30
  4527.4  271.72  4613.9  270.51  4622.8  271.82  4634.6  270.16  4662.4  271.61
  4667.5  270.68  4732.3  272.37  4759.1  273.46  4781.2  271.53  4810.4  271.69
  4851.0  269.99  4883.2  265.98  4893.4  269.77  4903.7  271.91  4914.0  272.27
  4939.5  270.07  4975.8  264.00  4981.1  255.77  4993.4  245.26  4996.1  244.76
  4999.4  245.26  5006.7  249.29  5017.0  251.45  5022.8  259.03  5037.6  261.53
  5047.9  261.76  5099.3  270.96  5125.3  273.61  5189.4  278.01  5301.8  282.71
#Mann=6,-1,0
  4527.4    0.05       0  4732.3    0.08       0  4893.4    0.05       0
  4993.4    0.07       0  4999.4    0.05       0  5125.3    0.05       0
Bank Sta=4993.4,4999.4
Exp/Cntr=0.3,0.1

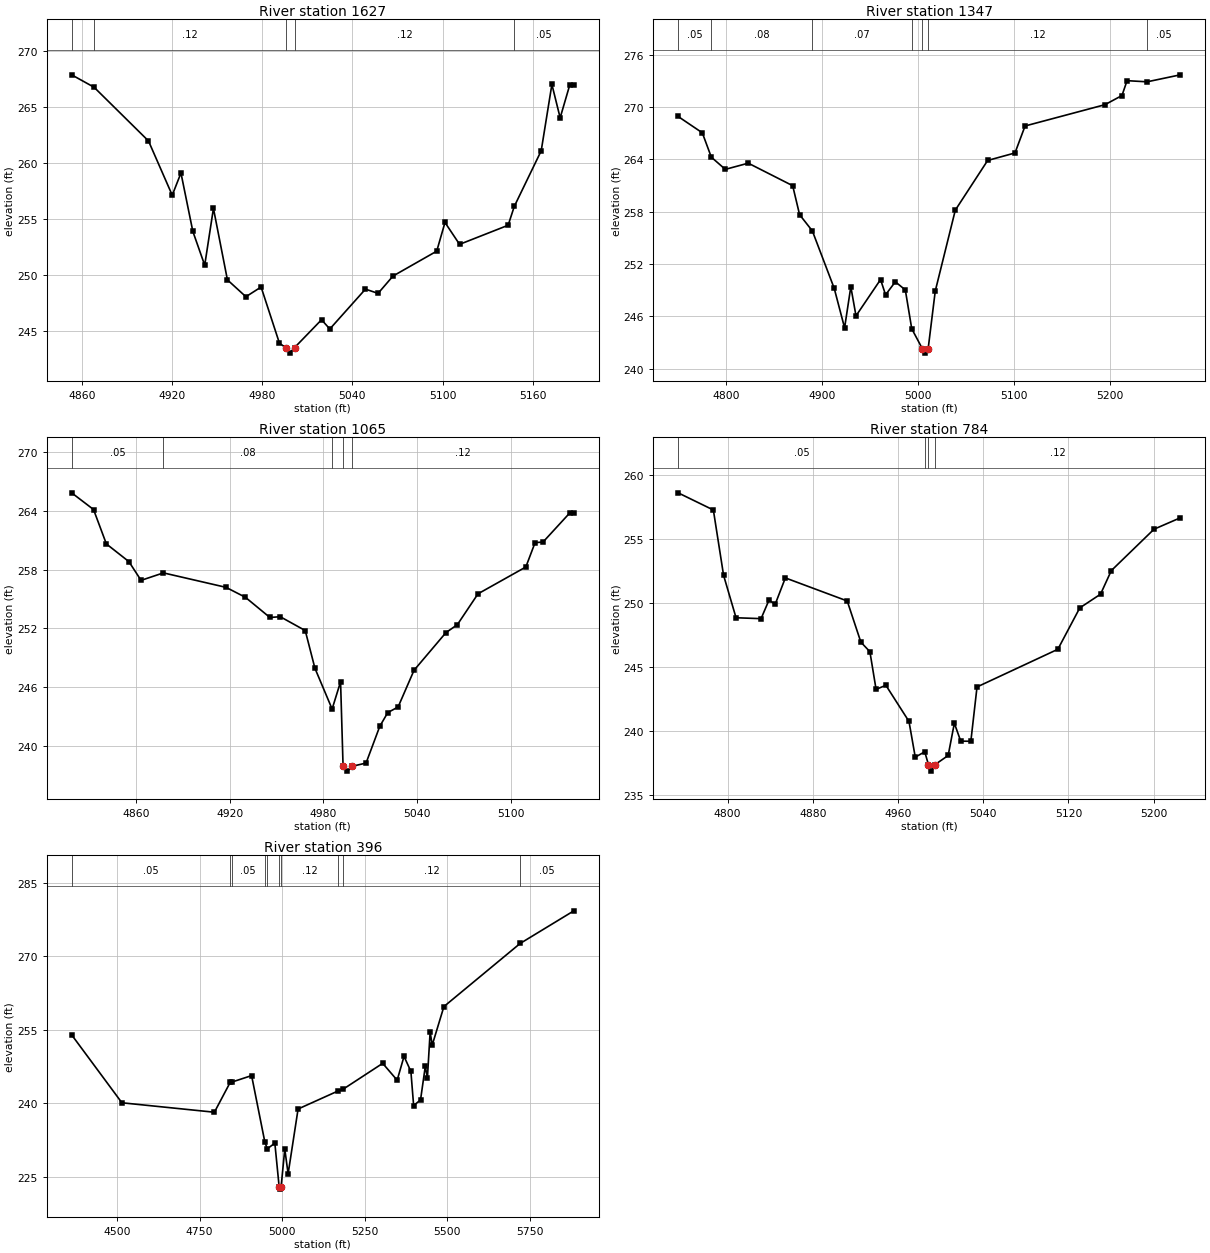
Type RM Length L Ch R = 1,1627,280,280,280
BEGIN DESCRIPTION:
UNT 198 IN BOCR 3.0
END DESCRIPTION:
XS GIS Cut Line= 3
      3718299.60     10620960.18      3718172.21     10620887.43
      3717999.62     10620960.18
#Sta/Elev= 30
  4853.3  267.91  4868.2  266.80  4904.4  261.99  4920.2  257.13  4926.0  259.12
  4933.9  253.89  4941.8  250.86  4947.6  255.95  4956.9  249.55  4969.2  248.04
  4979.3  248.91  4991.5  243.88  4995.6  243.49  4998.4  242.99  5001.6  243.49
  5019.5  245.98  5025.0  245.15  5048.7  248.72  5057.1  248.34  5067.0  249.89
  5096.1  252.12  5101.6  254.69  5111.3  252.73  5143.6  254.44  5147.7  256.13
  5165.6  261.11  5172.7  267.05  5178.2  264.06  5184.6  267.01  5187.3  267.01
#Mann=5,-1,0
  4853.3    0.07       0  4868.2    0.12       0  4995.6    0.07       0
  5001.6    0.12       0  5147.7    0.05       0
Bank Sta=4995.6,5001.6
Exp/Cntr=0.3,0.1

Type RM Length L Ch R = 1,1347,282,282,282
BEGIN DESCRIPTION:
Mapping XS 35ff6758
END DESCRIPTION:
XS GIS Cut Line= 3
      3718520.13     10620873.80      3718337.86     10620799.15
      3718024.12     10620709.02
#Sta/Elev= 30
  4750.3  268.91  4775.5  267.04  4784.9  264.25  4799.5  262.85  4823.4  263.56
  4869.7  260.98  4876.9  257.66  4890.2  255.80  4913.0  249.22  4923.8  244.69
  4930.3  249.40  4935.7  246.07  4961.3  250.23  4966.5  248.48  4976.7  249.97
  4987.1  249.04  4993.8  244.59  5004.9  242.30  5007.6  241.80  5010.9  242.30
  5018.3  248.91  5039.2  258.18  5072.9  263.87  5101.4  264.73  5111.9  267.82
  5195.2  270.26  5212.9  271.31  5218.2  273.01  5239.1  272.88  5273.7  273.68
#Mann=7,-1,0
  4750.3    0.05       0  4784.9    0.08       0  4890.2    0.07       0
  4993.8    0.12       0  5004.9    0.07       0  5010.9    0.12       0
  5239.1    0.05       0
Bank Sta=5004.9,5010.9
Exp/Cntr=0.3,0.1

Type RM Length L Ch R = 1,1065,281,281,281
BEGIN DESCRIPTION:
UNT 198 IN BOCR 2.0
END DESCRIPTION:
XS GIS Cut Line= 3
      3718549.58     10620660.18      3718386.77     10620581.11
      3718249.62     10620610.19
#Sta/Elev= 30
  4819.0  265.81  4833.0  264.11  4841.2  260.61  4855.6  258.81  4863.4  256.90
  4877.7  257.66  4917.7  256.19  4930.1  255.18  4945.8  253.12  4952.4  253.20
  4968.4  251.79  4974.6  247.95  4985.6  243.80  4991.0  246.58  4992.6  237.98
  4995.4  237.48  4998.6  237.98  5007.3  238.30  5016.1  242.05  5021.2  243.44
  5027.8  244.01  5038.0  247.75  5058.4  251.58  5065.7  252.39  5078.9  255.53
  5109.5  258.26  5115.4  260.74  5120.5  260.80  5137.7  263.78  5140.2  263.78
#Mann=5,-1,0
  4819.0    0.05       0  4877.7    0.08       0  4985.6    0.12       0
  4992.6    0.07       0  4998.6    0.12       0
Bank Sta=4992.6,4998.6
Exp/Cntr=0.3,0.1

Type RM Length L Ch R = 1,784,388,388,388
BEGIN DESCRIPTION:
Mapping XS a9721047
END DESCRIPTION:
XS GIS Cut Line= 3
      3718606.02     10620480.53      3718315.18     10620302.55
      3718185.00     10620313.40
#Sta/Elev= 30
  4753.5  258.60  4786.6  257.26  4796.2  252.16  4807.9  248.85  4831.4  248.78
  4838.8  250.22  4844.7  249.91  4854.2  251.96  4912.3  250.16  4925.1  246.95
  4933.6  246.20  4939.4  243.26  4948.6  243.58  4970.3  240.76  4976.2  237.97
  4985.1  238.39  4988.6  237.38  4991.4  236.88  4994.6  237.38  5007.1  238.10
  5012.9  240.62  5018.9  239.22  5028.4  239.21  5034.2  243.45  5110.1  246.39
  5130.7  249.62  5150.2  250.69  5160.3  252.53  5200.4  255.76  5225.1  256.65
#Mann=4,-1,0
  4753.5    0.05       0  4985.1    0.12       0  4988.6    0.07       0
  4994.6    0.12       0
Bank Sta=4988.6,4994.6
Exp/Cntr=0.3,0.1

Type RM Length L Ch R = 1,396,0,0,0
BEGIN DESCRIPTION:
UNT 198 IN BOCR 1.0
END DESCRIPTION:
XS GIS Cut Line= 4
      3718659.19     10620468.18      3718515.97     10619990.78
      3718194.79     10620025.50      3717774.26     10620584.76
#Sta/Elev= 30
  4362.6  254.00  4514.8  240.13  4795.0  238.20  4843.5  244.38  4847.7  244.35
  4907.7  245.68  4947.7  232.15  4955.2  230.73  4978.1  231.89  4991.1  223.00
  4993.9  222.50  4997.1  223.00  5008.2  230.68  5018.3  225.62  5048.5  238.86
  5169.6  242.54  5184.4  242.88  5304.8  248.18  5348.6  244.74  5369.4  249.60
  5390.2  246.54  5398.5  239.57  5419.4  240.71  5433.9  247.60  5440.2  245.15
  5448.5  254.59  5454.8  251.90  5490.2  259.77  5721.0  272.65  5883.8  279.32
#Mann=10,-1,0
  4362.6    0.05       0  4843.5    0.07       0  4847.7    0.05       0
  4947.7    0.07       0  4955.2    0.12       0  4991.1    0.07       0
  4997.1    0.12       0  5169.6    0.16       0  5184.4    0.12       0
  5721.0    0.05       0
Bank Sta=4991.1,4997.1
Exp/Cntr=0.3,0.1

Chan Stop Cuts=-1