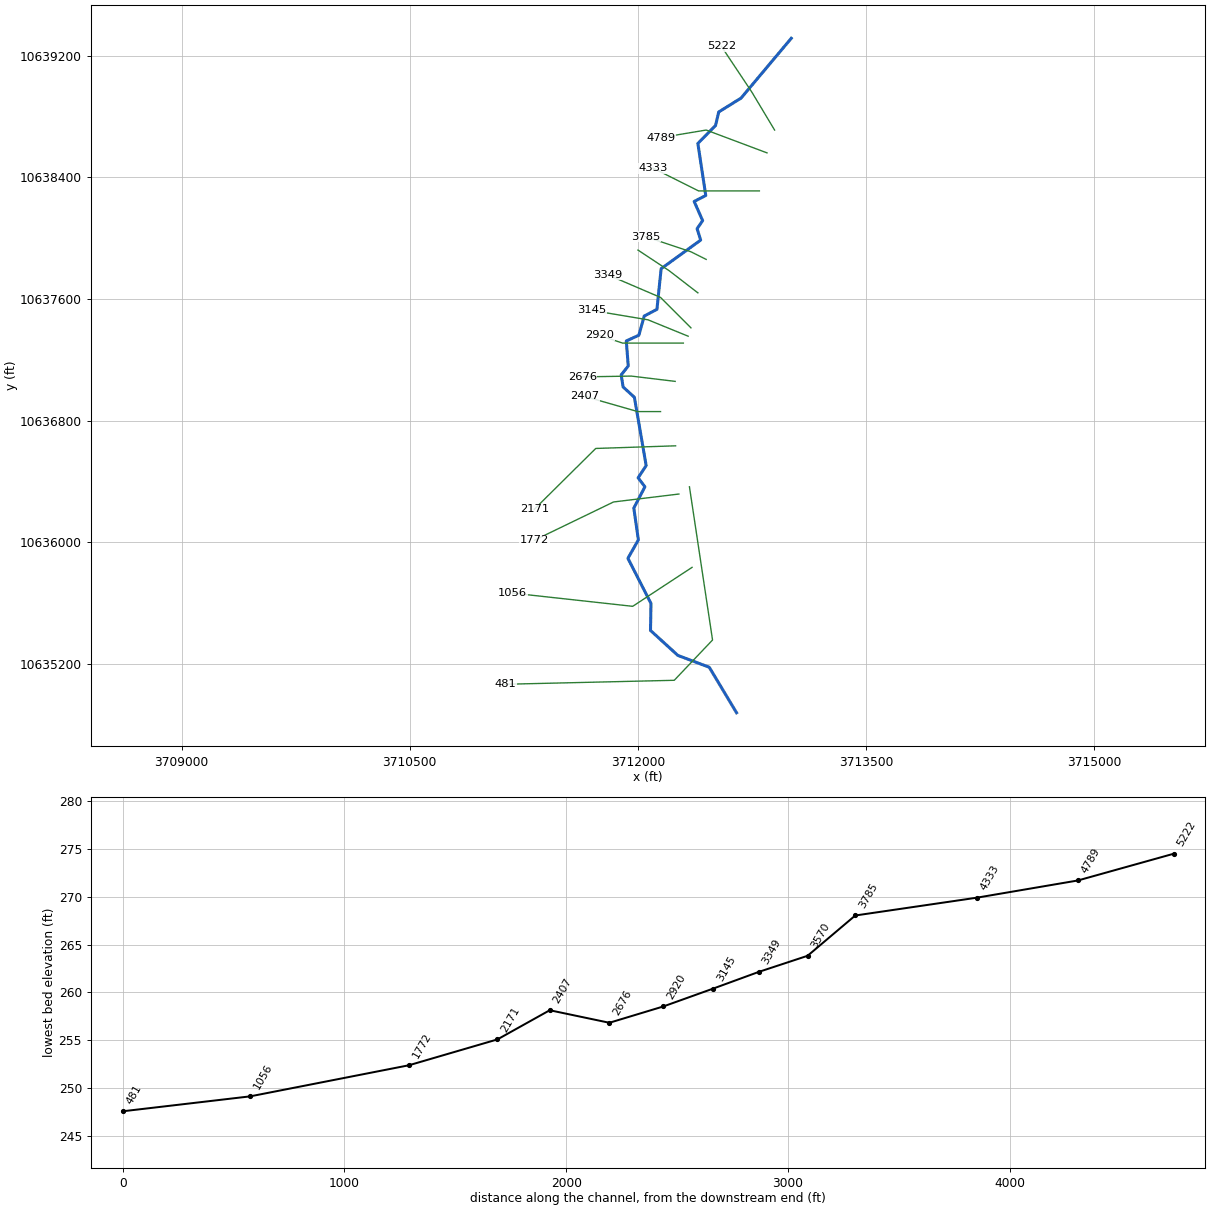
--- UNT 203 IN BOCR.prj (project) ---

Proj Title=UNT 203 IN BOCR Base Level Engineering
Current Plan=p01
Default Exp/Contr=0.3,0.1
English Units
Geom File=g01
Flow File=f01
Plan File=p01
Y Axis Title=Elevation
X Axis Title(PF)=Main Channel Distance
X Axis Title(XS)=Station
BEGIN DESCRIPTION:
UNT 203 IN BOCR
END DESCRIPTION:
DSS Export Rating Curves= 0
DSS Export Rating Curve Sorted= 0
DSS Export Volume Flow Curves= 0
DXF OffsetX= 0
DXF OffsetY= 0
DXF ScaleX= 1
DXF ScaleY= 10

--- UNT 203 IN BOCR.p01 (plan) ---

Plan Title=Multiple Run
Short Identifier=Multiple
Geom File=g01
Flow File=f01
Subcritical Flow
K Sum by GR= 0
Std Step Tol= 0.01
Critical Tol= 0.01
Num of Std Step Trials= 20
Max Error Tol= 0.3
Flow Tol Ratio= 0.001
Split Flow NTrial= 30
Split Flow Tol= 0.02
Split Flow Ratio= 0.02
Log Output Level= 0
Friction Slope Method= 1
Unsteady Friction Slope Method= 2
Unsteady Bridges Friction Slope Method= 1
Parabolic Critical Depth
Global Vel Dist=  1 , 1 , 1
Global Log Level= 0
CheckData=True
Encroach Param= -1, 0, 0, 0
BEGIN DESCRIPTION:
Multiple Run
END DESCRIPTION:

--- UNT 203 IN BOCR.f01 (steady flow) ---

Flow Title=Multiple
Program Version=4.10
Number of Profiles= 7
Profile Names=10-year,25-year,50-year,1pct_min,100-year,1pct_plu,500-year
River Rch & RM=UNT 203 IN BOCR,Reach-1         ,5222
     627     850    1035     926    1252    1693    1839
River Rch & RM=UNT 203 IN BOCR,Reach-1         ,2171
     875    1209    1490    1347    1822    2464    2738
River Rch & RM=UNT 203 IN BOCR,Reach-1         ,1056
     875    1209    1490    1347    1822    2464    2738
Boundary for River Rch & Prof#=UNT 203 IN BOCR,Reach-1         , 1
Up Type= 0
Dn Type= 3
Dn Slope=0.005
Boundary for River Rch & Prof#=UNT 203 IN BOCR,Reach-1         , 2
Up Type= 0
Dn Type= 3
Dn Slope=0.005
Boundary for River Rch & Prof#=UNT 203 IN BOCR,Reach-1         , 3
Up Type= 0
Dn Type= 3
Dn Slope=0.005
Boundary for River Rch & Prof#=UNT 203 IN BOCR,Reach-1         , 4
Up Type= 0
Dn Type= 3
Dn Slope=0.005
Boundary for River Rch & Prof#=UNT 203 IN BOCR,Reach-1         , 5
Up Type= 0
Dn Type= 3
Dn Slope=0.005
Boundary for River Rch & Prof#=UNT 203 IN BOCR,Reach-1         , 6
Up Type= 0
Dn Type= 3
Dn Slope=0.005
Boundary for River Rch & Prof#=UNT 203 IN BOCR,Reach-1         , 7
Up Type= 0
Dn Type= 3
Dn Slope=0.005
DSS Import GetInterval= 0
DSS Import GetPeak= 0
DSS Import FillOption= 0

--- UNT 203 IN BOCR.g01 (geometry) ---

Geom Title=Existing Conditions

River Reach=UNT 203 IN BOCR,Reach-1
Reach XY= 30
      3713009.25     10639313.00      3712679.00     10638920.00
      3712532.25     10638829.00      3712511.25     10638740.00
      3712395.00     10638622.00      3712447.00     10638280.00
      3712370.75     10638241.00      3712426.50     10638115.00
      3712390.00     10638062.00      3712413.50     10637987.00
      3712153.50     10637799.00      3712125.75     10637532.00
      3712042.25     10637488.00      3712007.00     10637362.00
      3711924.25     10637324.00      3711937.25     10637160.00
      3711890.75     10637101.00      3711903.25     10637022.00
      3711977.50     10636954.00      3712055.00     10636505.00
      3712002.00     10636425.00      3712046.75     10636366.00
      3711973.75     10636226.00      3712003.75     10636017.00
      3711935.00     10635896.00      3712086.75     10635599.00
      3712083.50     10635422.00      3712263.25     10635258.00
      3712470.00     10635180.00      3712649.50     10634881.00

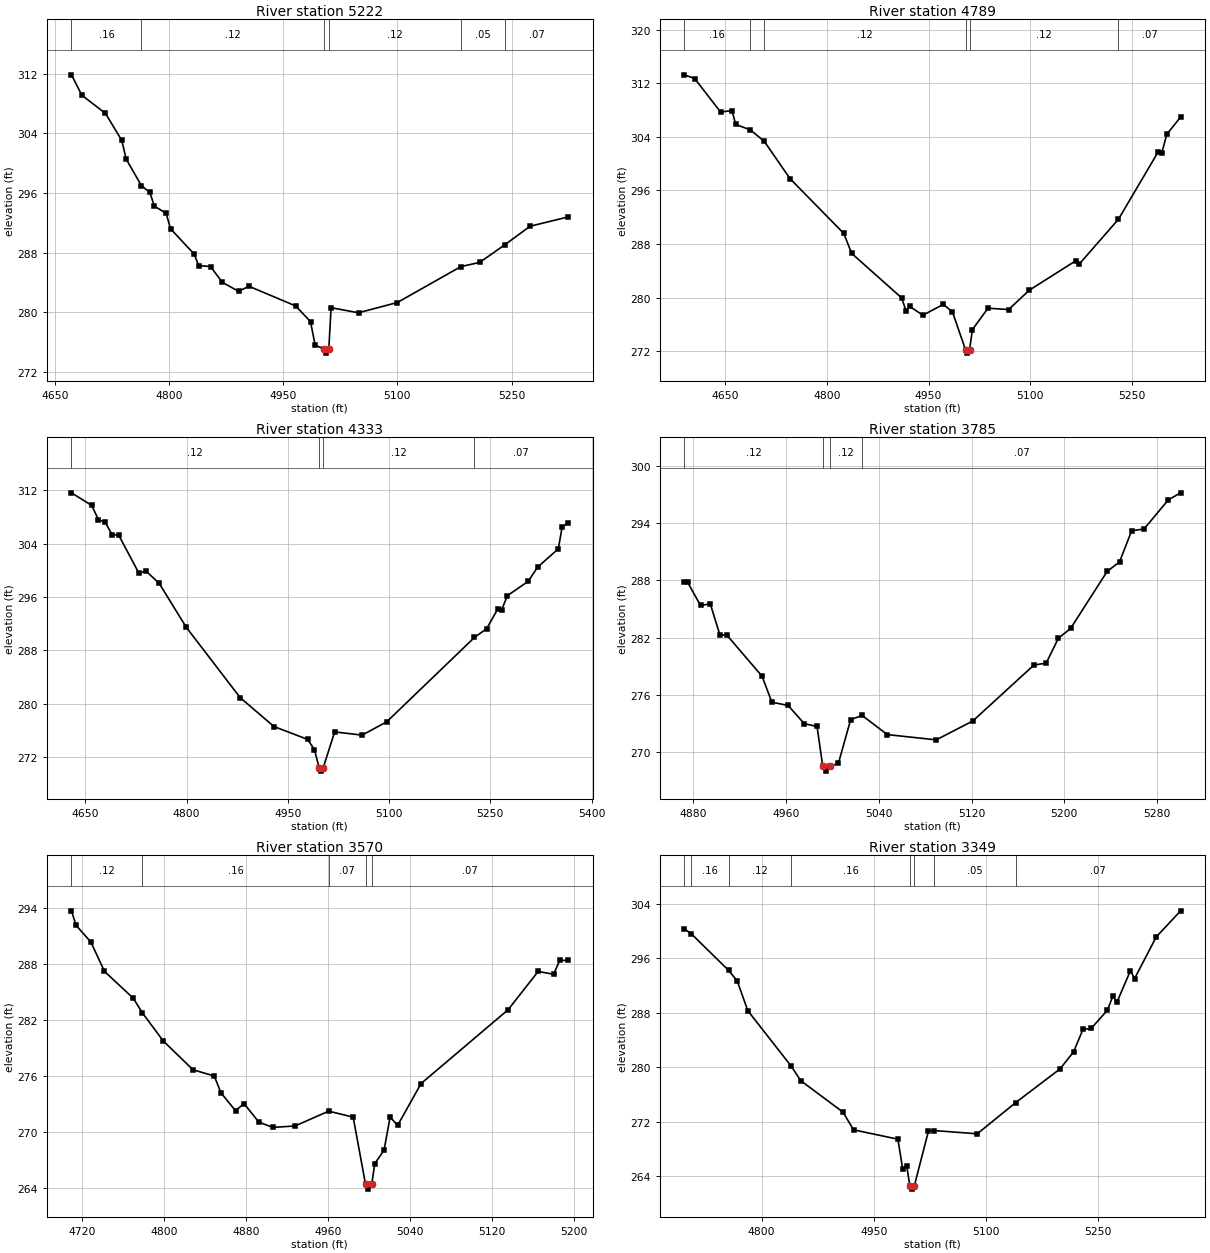
Type RM Length L Ch R = 1,5222,433,433,433
BEGIN DESCRIPTION:
UNT 203 IN BOCR 8.0
END DESCRIPTION:
XS GIS Cut Line= 3
      3712899.60     10638710.20      3712749.61     10638960.19
      3712549.60     10639260.20
#Sta/Elev= 30
  4671.8  311.88  4685.4  309.14  4716.5  306.70  4737.9  303.06  4743.7  300.55
  4763.8  296.98  4774.8  296.09  4780.6  294.26  4796.2  293.27  4802.0  291.20
  4833.1  287.79  4838.9  286.26  4854.5  286.13  4870.0  284.01  4891.4  282.80
  4905.0  283.48  4966.3  280.84  4985.9  278.73  4991.9  275.60  5003.9  275.00
  5006.7  274.50  5009.9  275.00  5012.9  280.60  5049.0  279.92  5100.0  281.30
  5183.4  286.12  5208.2  286.69  5241.5  289.07  5274.3  291.54  5323.9  292.78
#Mann=6,-1,0
  4671.8    0.16       0  4763.8    0.12       0  5003.9    0.07       0
  5009.9    0.12       0  5183.4    0.05       0  5241.5    0.07       0
Bank Sta=5003.9,5009.9
Exp/Cntr=0.3,0.1

Type RM Length L Ch R = 1,4789,456,456,456
BEGIN DESCRIPTION:
UNT 203 IN BOCR 7.0
END DESCRIPTION:
XS GIS Cut Line= 3
      3712849.64     10638560.18      3712449.61     10638710.19
      3712149.58     10638660.18
#Sta/Elev= 30
  4590.0  313.27  4605.2  312.72  4643.4  307.72  4660.3  307.92  4665.7  305.86
  4687.4  305.04  4707.8  303.34  4745.8  297.76  4825.0  289.58  4836.6  286.60
  4910.4  279.94  4916.7  278.00  4922.0  278.68  4941.6  277.37  4971.8  278.98
  4985.2  277.85  5004.4  272.20  5007.2  271.70  5010.4  272.20  5014.6  275.22
  5037.5  278.41  5067.9  278.21  5098.3  281.09  5166.8  285.49  5171.8  284.97
  5229.8  291.70  5288.4  301.77  5293.5  301.55  5301.1  304.39  5321.4  306.96
#Mann=6,-1,0
  4590.0    0.16       0  4687.4    0.05       0  4707.8    0.12       0
  5004.4    0.07       0  5010.4    0.12       0  5229.8    0.07       0
Bank Sta=5004.4,5010.4
Exp/Cntr=0.3,0.1

Type RM Length L Ch R = 1,4333,548,548,548
BEGIN DESCRIPTION:
UNT 203 IN BOCR 6.0
END DESCRIPTION:
XS GIS Cut Line= 3
      3712799.60     10638310.19      3712399.61     10638310.19
      3712099.61     10638460.19
#Sta/Elev= 30
  4629.3  311.63  4659.3  309.74  4669.3  307.60  4679.3  307.20  4689.3  305.38
  4699.3  305.28  4729.3  299.56  4739.3  299.94  4759.3  298.05  4799.3  291.48
  4879.3  280.92  4929.3  276.59  4979.3  274.65  4989.3  273.13  4996.3  270.40
  4999.0  269.90  5002.3  270.40  5019.3  275.78  5060.0  275.30  5096.4  277.29
  5226.5  289.95  5244.5  291.25  5261.3  294.27  5266.9  294.13  5275.3  296.22
  5306.0  298.35  5320.0  300.48  5350.7  303.23  5356.3  306.46  5364.7  307.13
#Mann=4,-1,0
  4629.3    0.12       0  4996.3    0.07       0  5002.3    0.12       0
  5226.5    0.07       0
Bank Sta=4996.3,5002.3
Exp/Cntr=0.3,0.1

Type RM Length L Ch R = 1,3785,215,215,215
BEGIN DESCRIPTION:
UNT 203 IN BOCR 5.0
END DESCRIPTION:
XS GIS Cut Line= 3
      3712449.65     10637860.17      3712349.61     10637910.19
      3712049.59     10638010.20
#Sta/Elev= 30
  4872.2  287.80  4875.0  287.80  4886.2  285.37  4894.6  285.54  4903.0  282.24
  4908.6  282.31  4939.3  277.96  4947.7  275.25  4961.7  274.91  4975.7  273.00
  4986.7  272.71  4991.6  268.54  4994.3  268.04  4997.6  268.54  5005.1  268.85
  5015.7  273.43  5025.6  273.86  5047.3  271.86  5089.5  271.31  5121.1  273.29
  5173.8  279.14  5184.3  279.33  5194.9  281.94  5205.4  282.96  5237.0  288.94
  5247.6  289.92  5258.1  293.19  5268.7  293.36  5289.7  296.41  5300.3  297.15
#Mann=4,-1,0
  4872.2    0.12       0  4991.6    0.07       0  4997.6    0.12       0
  5025.6    0.07       0
Bank Sta=4991.6,4997.6
Exp/Cntr=0.3,0.1

Type RM Length L Ch R = 1,3570,221,221,221
BEGIN DESCRIPTION:
Mapping XS 19f5c509
END DESCRIPTION:
XS GIS Cut Line= 3
      3712395.15     10637640.22      3712205.89     10637786.07
      3712001.04     10637921.48
#Sta/Elev= 30
  4709.5  293.67  4713.9  292.12  4728.4  290.33  4741.7  287.18  4770.0  284.28
  4778.5  282.76  4799.1  279.72  4828.1  276.63  4848.9  275.96  4855.4  274.16
  4869.7  272.23  4877.9  273.01  4892.4  271.02  4905.9  270.45  4927.7  270.60
  4960.6  272.19  4984.5  271.55  4996.6  264.33  4999.3  263.83  5002.6  264.33
  5005.6  266.57  5014.6  267.99  5020.6  271.56  5027.9  270.66  5050.8  275.15
  5135.8  283.07  5165.1  287.17  5180.2  286.87  5186.2  288.36  5194.0  288.35
#Mann=5,-1,0
  4709.5    0.12       0  4778.5    0.16       0  4960.6    0.07       0
  4996.6    0.07       0  5002.6    0.07       0
Bank Sta=4996.6,5002.6
Exp/Cntr=0.3,0.1

Type RM Length L Ch R = 1,3349,204,204,204
BEGIN DESCRIPTION:
UNT 203 IN BOCR 4.0
END DESCRIPTION:
XS GIS Cut Line= 3
      3712349.62     10637410.18      3712149.61     10637610.19
      3711799.65     10637760.17
#Sta/Elev= 30
  4696.7  300.27  4706.0  299.57  4755.8  294.21  4767.4  292.66  4781.6  288.29
  4839.5  280.18  4852.3  278.04  4908.8  273.43  4923.0  270.83  4982.3  269.46
  4988.6  265.14  4994.1  265.48  4998.3  262.64  5001.1  262.14  5004.3  262.64
  5023.1  270.63  5030.1  270.73  5088.4  270.25  5139.6  274.81  5199.0  279.75
  5217.1  282.25  5229.8  285.56  5240.7  285.69  5262.4  288.36  5269.7  290.42
  5275.1  289.52  5293.3  294.18  5298.7  292.99  5327.7  299.10  5360.3  302.93
#Mann=8,-1,0
  4696.7    0.05       0  4706.0    0.16       0  4755.8    0.12       0
  4839.5    0.16       0  4998.3    0.07       0  5004.3    0.16       0
  5030.1    0.05       0  5139.6    0.07       0
Bank Sta=4998.3,5004.3
Exp/Cntr=0.3,0.1

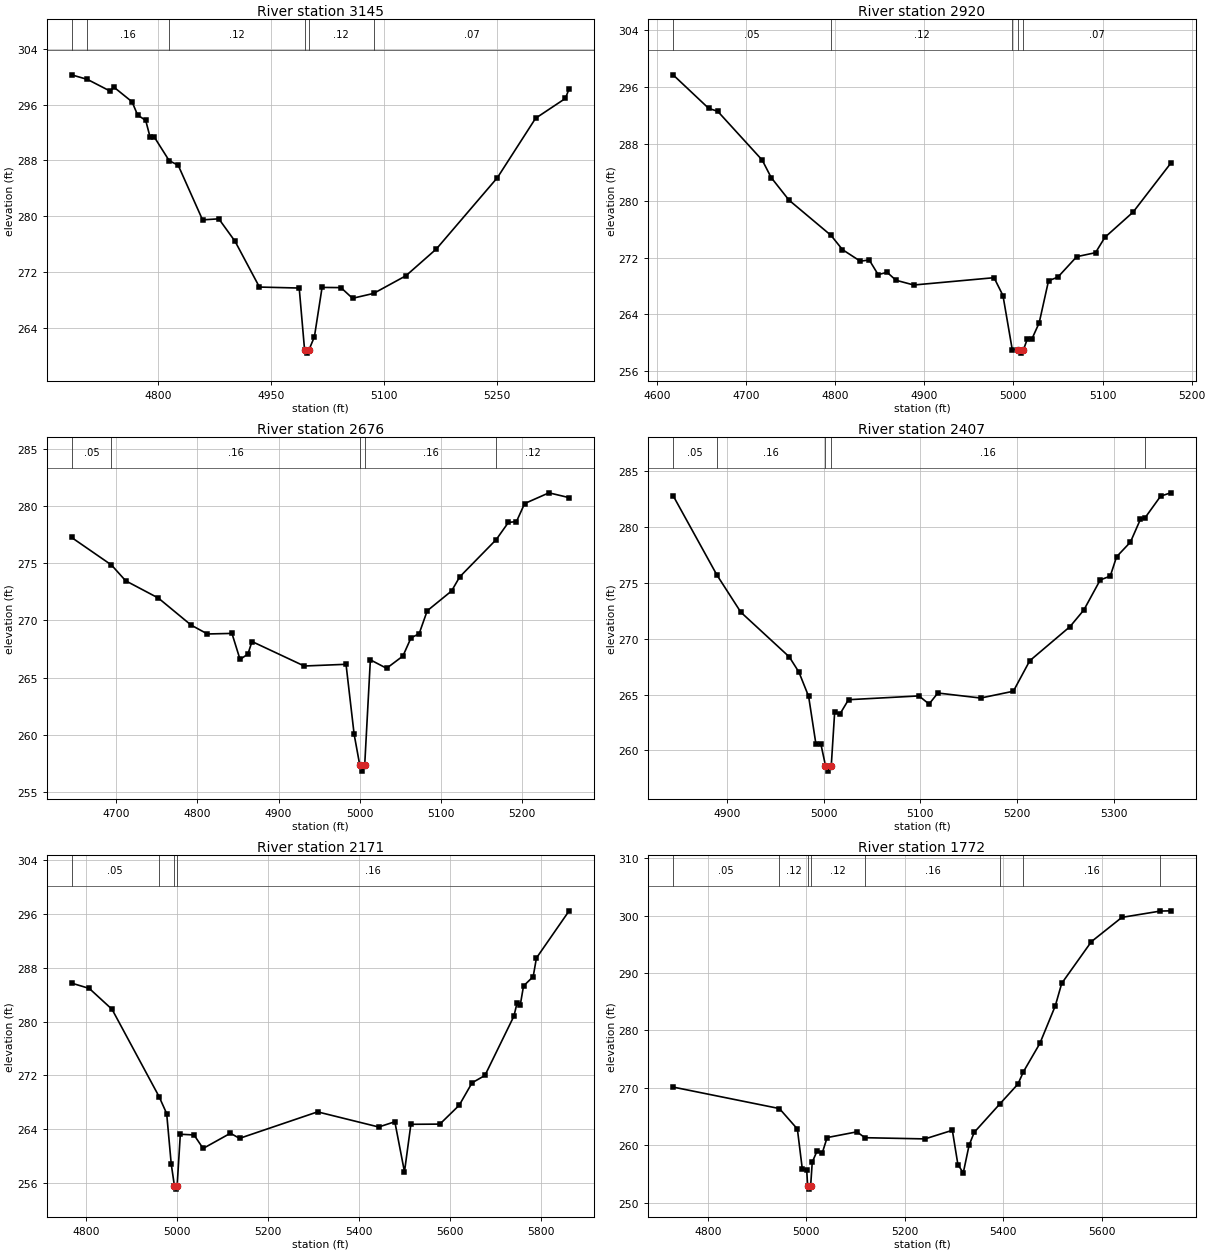
Type RM Length L Ch R = 1,3145,225,225,225
BEGIN DESCRIPTION:
Mapping XS 7f3f940d
END DESCRIPTION:
XS GIS Cut Line= 3
      3712330.92     10637355.50      3712067.00     10637463.16
      3711695.60     10637525.34
#Sta/Elev= 30
  4684.8  300.26  4706.0  299.60  4735.9  297.94  4741.3  298.48  4765.3  296.39
  4772.6  294.51  4783.4  293.73  4789.3  291.31  4794.7  291.37  4814.6  287.97
  4826.6  287.31  4859.0  279.49  4880.6  279.64  4902.2  276.42  4934.6  269.87
  4987.5  269.73  4994.6  260.91  4997.4  260.41  5000.6  260.91  5007.7  262.75
  5017.9  269.82  5043.0  269.79  5058.4  268.26  5086.4  268.96  5129.4  271.49
  5170.0  275.34  5251.1  285.55  5301.8  294.04  5341.4  296.88  5346.4  298.28
#Mann=6,-1,0
  4684.8    0.05       0  4706.0    0.16       0  4814.6    0.12       0
  4994.6    0.07       0  5000.6    0.12       0  5086.4    0.07       0
Bank Sta=4994.6,5000.6
Exp/Cntr=0.3,0.1

Type RM Length L Ch R = 1,2920,244,244,244
BEGIN DESCRIPTION:
UNT 203 IN BOCR 3.0
END DESCRIPTION:
XS GIS Cut Line= 3
      3712299.62     10637310.19      3711899.61     10637310.19
      3711749.63     10637360.18
#Sta/Elev= 30
  4618.3  297.72  4658.3  292.99  4668.3  292.59  4718.3  285.71  4728.3  283.26
  4748.3  280.08  4795.4  275.12  4808.3  273.11  4828.3  271.48  4838.3  271.66
  4848.3  269.59  4858.3  269.92  4868.3  268.80  4888.3  268.13  4978.3  269.16
  4988.3  266.64  4998.7  259.04  5005.3  259.04  5008.1  258.54  5011.3  259.04
  5015.8  260.58  5020.9  260.58  5028.9  262.80  5039.4  268.73  5049.9  269.24
  5071.0  272.12  5092.1  272.68  5102.6  274.84  5134.3  278.40  5176.4  285.26
#Mann=5,-1,0
  4618.3    0.05       0  4795.4    0.12       0  4998.7    0.07       0
  5005.3    0.07       0  5011.3    0.07       0
Bank Sta=5005.3,5011.3
Exp/Cntr=0.3,0.1

Type RM Length L Ch R = 1,2676,269,269,269
BEGIN DESCRIPTION:
Mapping XS 57253923
END DESCRIPTION:
XS GIS Cut Line= 3
      3712245.86     10637058.64      3711957.63     10637093.36
      3711634.69     10637088.15
#Sta/Elev= 30
  4644.8  277.26  4694.0  274.85  4711.5  273.47  4751.8  271.96  4792.1  269.60
  4812.3  268.82  4842.5  268.87  4852.5  266.59  4862.2  267.07  4867.2  268.16
  4931.6  266.02  4983.1  266.17  4993.1  260.05  5000.1  257.33  5002.9  256.83
  5006.1  257.33  5013.1  266.56  5033.1  265.82  5053.2  266.89  5063.2  268.48
  5073.2  268.84  5083.2  270.85  5113.2  272.58  5123.2  273.81  5168.2  277.07
  5183.2  278.57  5193.2  278.65  5203.2  280.22  5233.2  281.16  5258.1  280.74
#Mann=5,-1,0
  4644.8    0.05       0  4694.0    0.16       0  5000.1    0.07       0
  5006.1    0.16       0  5168.2    0.12       0
Bank Sta=5000.1,5006.1
Exp/Cntr=0.3,0.1

Type RM Length L Ch R = 1,2407,236,236,236
BEGIN DESCRIPTION:
UNT 203 IN BOCR 2.0
END DESCRIPTION:
XS GIS Cut Line= 3
      3712149.59     10636860.19      3711999.61     10636860.19
      3711649.59     10636960.19
#Sta/Elev= 30
  4844.5  282.83  4889.8  275.71  4914.5  272.38  4964.5  268.38  4974.5  267.01
  4984.5  264.84  4992.0  260.59  4997.1  260.59  5001.9  258.64  5004.6  258.14
  5007.9  258.64  5011.4  263.42  5016.6  263.22  5025.7  264.54  5098.5  264.88
  5108.9  264.15  5118.0  265.14  5162.2  264.69  5196.0  265.30  5212.9  268.03
  5254.5  271.09  5268.8  272.58  5285.7  275.27  5296.1  275.62  5302.6  277.35
  5316.9  278.66  5327.3  280.72  5332.0  280.84  5348.1  282.78  5358.5  283.08
#Mann=5,-1,0
  4844.5    0.05       0  4889.8    0.16       0  5001.9    0.07       0
  5007.9    0.16       0  5332.0    0.12       0
Bank Sta=5001.9,5007.9
Exp/Cntr=0.3,0.1

Type RM Length L Ch R = 1,2171,399,399,399
BEGIN DESCRIPTION:
Mapping XS 2058b02b
END DESCRIPTION:
XS GIS Cut Line= 3
      3712248.52     10636635.14      3711723.30     10636617.78
      3711319.64     10636218.46
#Sta/Elev= 30
  4768.7  285.73  4807.6  284.94  4857.7  281.83  4961.0  268.85  4977.7  266.33
  4987.7  258.84  4994.7  255.59  4997.5  255.09  5000.7  255.59  5007.7  263.25
  5037.8  263.15  5057.8  261.14  5117.8  263.40  5137.8  262.64  5309.3  266.58
  5443.6  264.33  5479.0  265.11  5500.2  257.66  5514.3  264.73  5578.0  264.76
  5620.4  267.56  5648.7  270.90  5677.0  272.00  5740.6  280.81  5747.7  282.81
  5754.7  282.51  5761.8  285.31  5783.0  286.69  5790.1  289.46  5862.0  296.48
#Mann=4,-1,0
  4768.7    0.05       0  4961.0    0.16       0  4994.7    0.07       0
  5000.7    0.16       0
Bank Sta=4994.7,5000.7
Exp/Cntr=0.3,0.1

Type RM Length L Ch R = 1,1772,716,716,716
BEGIN DESCRIPTION:
Mapping XS 4ac10a47
END DESCRIPTION:
XS GIS Cut Line= 3
      3712270.15     10636318.29      3711840.49     10636266.21
      3711320.36     10636014.82
#Sta/Elev= 30
  4729.5  270.15  4945.4  266.41  4981.9  262.85  4991.9  255.90  5000.8  255.75
  5002.8  252.89  5005.6  252.39  5008.8  252.89  5012.1  257.08  5022.2  259.09
  5032.2  258.62  5042.3  261.36  5102.8  262.36  5119.0  261.34  5241.0  261.13
  5296.6  262.63  5307.9  256.66  5318.8  255.22  5330.5  259.99  5341.0  262.27
  5393.2  267.23  5429.8  270.67  5441.1  272.84  5474.3  277.74  5505.7  284.29
  5518.7  288.20  5579.0  295.46  5640.9  299.68  5719.2  300.78  5740.0  300.82
#Mann=8,-1,0
  4729.5    0.05       0  4945.4    0.12       0  5002.8    0.07       0
  5008.8    0.12       0  5119.0    0.16       0  5393.2    0.12       0
  5441.1    0.16       0  5719.2    0.05       0
Bank Sta=5002.8,5008.8
Exp/Cntr=0.3,0.1

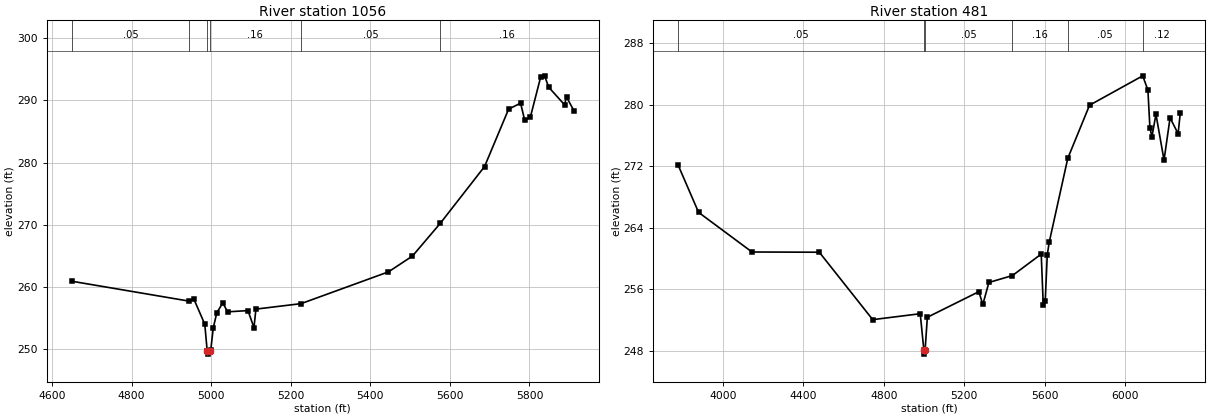
Type RM Length L Ch R = 1,1056,575,575,575
BEGIN DESCRIPTION:
Mapping XS d9e67f3f
END DESCRIPTION:
XS GIS Cut Line= 3
      3712356.95     10635836.51      3711966.35     10635580.45
      3711176.45     10635667.25
#Sta/Elev= 30
  4649.9  260.88  4945.3  257.67  4957.0  257.96  4984.1  253.96  4990.2  249.64
  4992.9  249.14  4996.2  249.64  4999.2  249.83  5005.4  253.36  5014.3  255.80
  5029.4  257.40  5041.3  255.95  5092.6  256.15  5107.7  253.41  5112.6  256.39
  5226.0  257.27  5445.7  262.39  5506.0  264.94  5576.0  270.22  5687.1  279.35
  5747.5  288.59  5777.6  289.56  5787.7  286.88  5802.0  287.26  5827.9  293.72
  5838.0  293.96  5848.1  292.14  5888.0  289.30  5893.0  290.54  5911.6  288.35
#Mann=6,-1,0
  4649.9    0.05       0  4945.3    0.16       0  4990.2    0.07       0
  4996.2    0.16       0  5226.0    0.05       0  5576.0    0.16       0
Bank Sta=4990.2,4996.2
Exp/Cntr=0.3,0.1

Type RM Length L Ch R = 1,481,0,0,0
BEGIN DESCRIPTION:
UNT 203 IN BOCR 1.0
END DESCRIPTION:
XS GIS Cut Line= 4
      3712339.62     10636366.06      3712491.53     10635359.10
      3712239.79     10635094.34      3711128.69     10635068.30
#Sta/Elev= 30
  3778.8  272.13  3880.1  266.00  4145.6  260.85  4480.1  260.82  4745.5  252.06
  4981.6  252.83  4999.7  248.08  5002.4  247.58  5005.7  248.08  5016.9  252.37
  5272.7  255.69  5292.7  254.03  5322.7  256.89  5439.8  257.79  5582.8  260.58
  5592.8  254.02  5602.8  254.52  5612.8  260.49  5622.8  262.16  5714.7  273.02
  5822.9  279.92  6087.1  283.74  6112.9  281.89  6122.9  276.96  6132.9  275.83
  6152.9  278.75  6193.0  272.78  6223.0  278.28  6263.0  276.22  6273.9  278.96
#Mann=6,-1,0
  3778.8    0.05       0  4999.7    0.03       0  5005.7    0.05       0
  5439.8    0.16       0  5714.7    0.05       0  6087.1    0.12       0
Bank Sta=4999.7,5005.7
Exp/Cntr=0.3,0.1

Chan Stop Cuts=-1