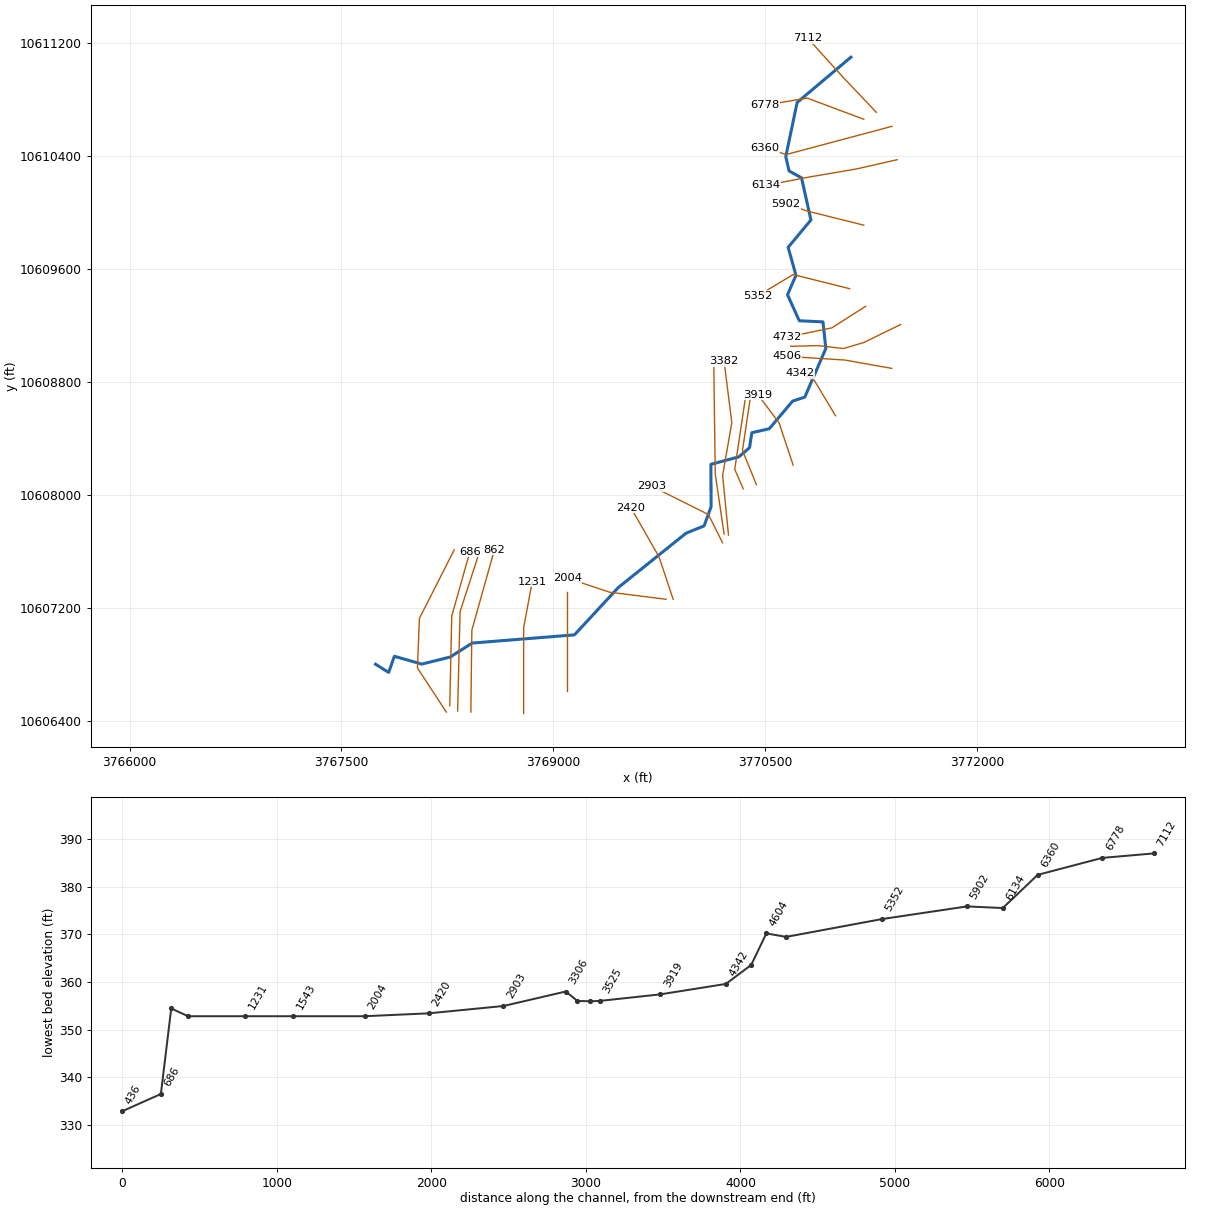
--- UNT 341 IN BOCR.prj (project) ---

Proj Title=UNT 341 IN BOCR Base Level Engineering
Current Plan=p01
Default Exp/Contr=0.3,0.1
English Units
Geom File=g01
Flow File=f01
Plan File=p01
Y Axis Title=Elevation
X Axis Title(PF)=Main Channel Distance
X Axis Title(XS)=Station
BEGIN DESCRIPTION:
UNT 341 IN BOCR
END DESCRIPTION:
DSS Export Rating Curves= 0
DSS Export Rating Curve Sorted= 0
DSS Export Volume Flow Curves= 0
DXF OffsetX= 0
DXF OffsetY= 0
DXF ScaleX= 1
DXF ScaleY= 10

--- UNT 341 IN BOCR.p01 (plan) ---

Plan Title=Multiple Run
Short Identifier=Multiple
Geom File=g01
Flow File=f01
Subcritical Flow
K Sum by GR= 0
Std Step Tol= 0.01
Critical Tol= 0.01
Num of Std Step Trials= 20
Max Error Tol= 0.3
Flow Tol Ratio= 0.001
Split Flow NTrial= 30
Split Flow Tol= 0.02
Split Flow Ratio= 0.02
Log Output Level= 0
Friction Slope Method= 1
Unsteady Friction Slope Method= 2
Unsteady Bridges Friction Slope Method= 1
Parabolic Critical Depth
Global Vel Dist=  1 , 1 , 1
Global Log Level= 0
CheckData=True
Encroach Param= -1, 0, 0, 0
BEGIN DESCRIPTION:
Multiple Run
END DESCRIPTION:

--- UNT 341 IN BOCR.f01 (steady flow) ---

Flow Title=Multiple
Program Version=4.10
Number of Profiles= 7
Profile Names=10-year,25-year,50-year,1pct_min,100-year,1pct_plu,500-year
River Rch & RM=UNT 341 IN BOCR,Reach-1         ,7112
    1083    1524    1904    1746    2361    3193    3646
Boundary for River Rch & Prof#=UNT 341 IN BOCR,Reach-1         , 1
Up Type= 0
Dn Type= 3
Dn Slope=0.011
Boundary for River Rch & Prof#=UNT 341 IN BOCR,Reach-1         , 2
Up Type= 0
Dn Type= 3
Dn Slope=0.011
Boundary for River Rch & Prof#=UNT 341 IN BOCR,Reach-1         , 3
Up Type= 0
Dn Type= 3
Dn Slope=0.011
Boundary for River Rch & Prof#=UNT 341 IN BOCR,Reach-1         , 4
Up Type= 0
Dn Type= 3
Dn Slope=0.011
Boundary for River Rch & Prof#=UNT 341 IN BOCR,Reach-1         , 5
Up Type= 0
Dn Type= 3
Dn Slope=0.011
Boundary for River Rch & Prof#=UNT 341 IN BOCR,Reach-1         , 6
Up Type= 0
Dn Type= 3
Dn Slope=0.011
Boundary for River Rch & Prof#=UNT 341 IN BOCR,Reach-1         , 7
Up Type= 0
Dn Type= 3
Dn Slope=0.011
DSS Import GetInterval= 0
DSS Import GetPeak= 0
DSS Import FillOption= 0

--- UNT 341 IN BOCR.g01 (geometry) ---

Geom Title=Existing Conditions
Program Version=4.10

River Reach=UNT 341 IN BOCR ,Reach-1
Reach XY= 30
      3771108.75       10611100.      3770727.75       10610779.
      3770647.25       10610395.        3770671.       10610294.
        3770759.       10610245.       3770825.5       10609947.
        3770664.       10609753.       3770719.5       10609555.
      3770659.75       10609417.        3770743.       10609233.
      3770910.75       10609225.      3770931.25       10609037.
        3770782.       10608692.        3770696.       10608664.
        3770530.       10608468.        3770407.       10608440.
       3770390.5       10608334.       3770315.5       10608269.
        3770117.       10608216.      3770118.25       10607916.
        3770069.       10607780.       3769940.5       10607728.
      3769460.75       10607343.      3769150.25       10607008.
      3768426.25       10606950.      3768270.25       10606851.
       3768069.5       10606801.      3767874.75       10606856.
       3767834.5       10606742.       3767741.5       10606800.

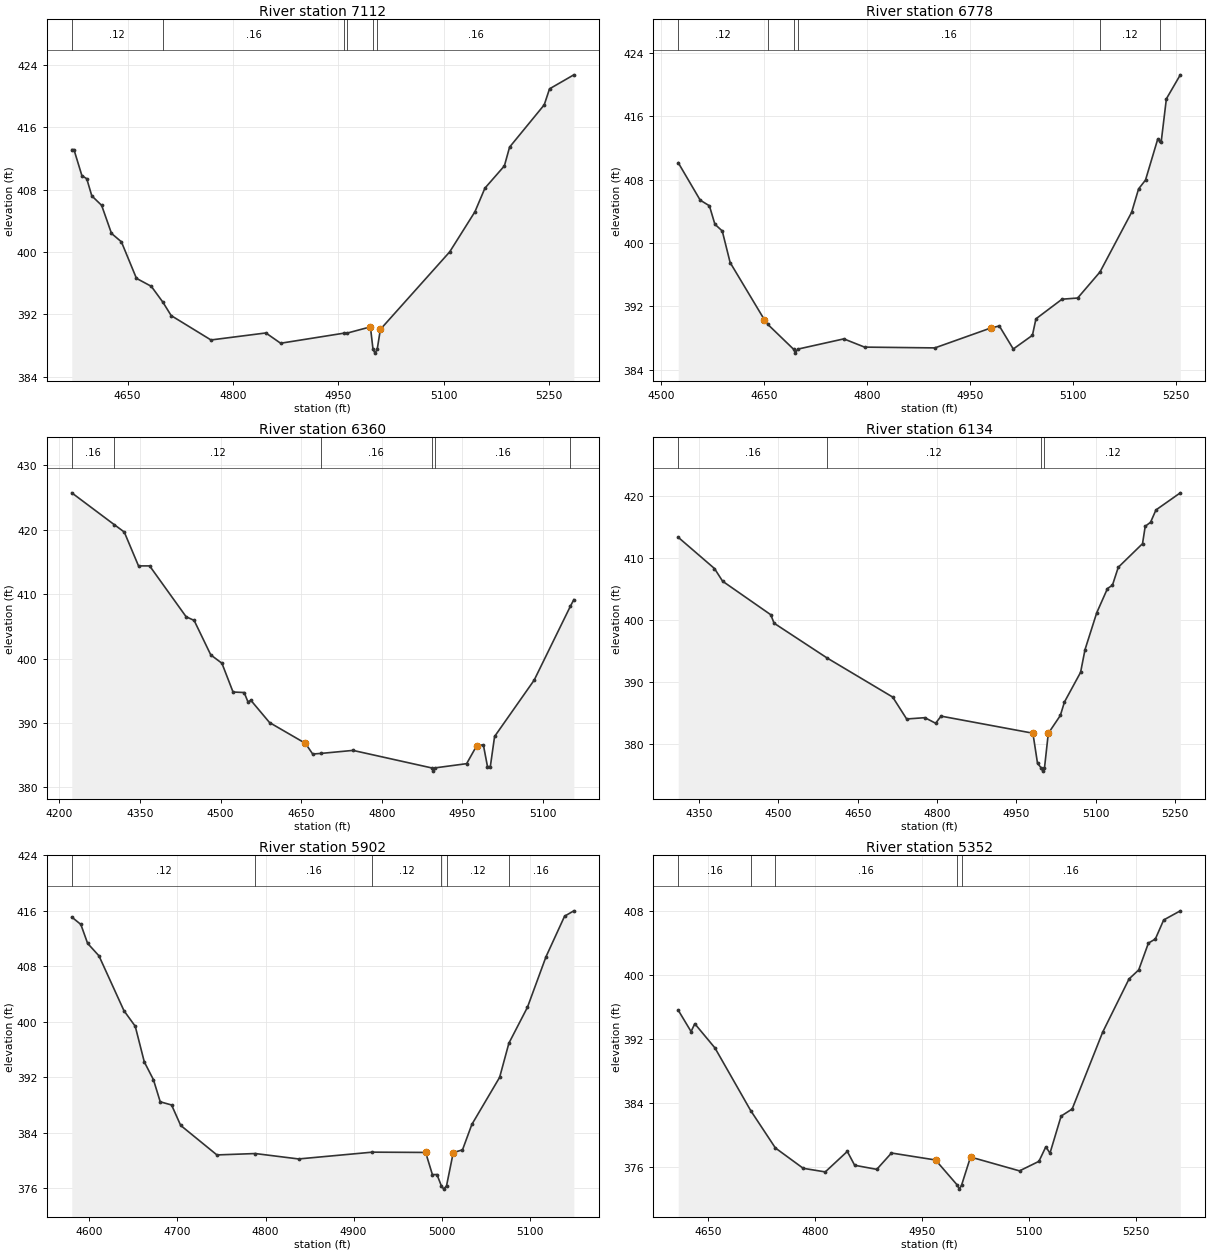
Type RM Length L Ch R = 1 ,7112    ,334,334,334
BEGIN DESCRIPTION:
UNT 341 IN BOCR 15.0
END DESCRIPTION:
XS GIS Cut Line= 3
      3771288.85     10610709.36      3771050.17     10610961.06
      3770803.72     10611233.45
#Sta/Elev= 30
  4570.7  413.15  4573.8  413.15  4585.1  409.81    4592  409.41  4599.2  407.21
  4613.2  405.99  4627.2  402.39  4641.3  401.31  4662.7  396.62  4683.8   395.6
  4700.4  393.55  4712.1  391.84  4768.7  388.71  4846.8  389.61  4867.8  388.29
  4957.7  389.58    4962  389.58  4995.5  390.39  4999.2  387.52    5002  387.02
  5005.2  387.52  5009.7  390.07  5108.3  400.02  5144.2  405.17  5158.4   408.2
  5186.1  411.06  5193.5  413.47  5242.8   418.9  5250.3  420.95  5284.9  422.75
#Mann= 6 ,-1 , 0
  4570.7     .12       0  4700.4     .16       0  4957.7     .12       0
    4962     .16       0  4999.2     .07       0  5005.2     .16       0
Bank Sta=4995.5,5009.7
XS Rating Curve= 0 ,0
Exp/Cntr=0.3,0.1

Type RM Length L Ch R = 1 ,6778    ,418,418,418
BEGIN DESCRIPTION:
UNT 341 IN BOCR 14.0
END DESCRIPTION:
XS GIS Cut Line= 3
       3771199.6     10610660.19      3770799.61     10610810.19
      3770499.63     10610760.19
#Sta/Elev= 30
  4524.8  410.13  4556.8   405.4  4570.2  404.69  4578.2  402.36  4588.9  401.51
  4600.4  397.52  4650.3   390.3  4655.4   389.7  4692.7  386.58  4695.4  386.08
  4698.7  386.58    4766  387.88  4796.2  386.84  4898.6  386.74  4979.9  389.25
  4992.5  389.51  5012.8   386.6  5040.7  388.33  5045.8  390.41  5083.8  392.89
  5106.6  393.04  5139.1  396.33  5185.2  403.87  5195.3  406.82  5205.4  407.94
  5223.2  413.11  5226.5  412.85  5228.2  412.72  5235.8   418.2  5256.1  421.23
#Mann= 6 ,-1 , 0
  4524.8     .12       0  4655.4     .16       0  4692.7     .07       0
  4698.7     .16       0  5139.1     .12       0  5226.5     .16       0
Bank Sta=4650.3,4979.9
XS Rating Curve= 0 ,0
Exp/Cntr=0.3,0.1

Type RM Length L Ch R = 1 ,6360    ,226,226,226
BEGIN DESCRIPTION:
UNT 341 IN BOCR 13.0
END DESCRIPTION:
XS GIS Cut Line= 3
      3771399.62     10610610.19      3770649.61     10610410.19
      3770499.64     10610460.18
#Sta/Elev= 30
    4223  425.75  4301.7  420.83  4320.7  419.66  4347.2   414.4  4367.9   414.4
  4435.8   406.5  4450.7  405.93  4481.7  400.57  4502.4  399.28  4523.1  394.81
  4543.8  394.73    4551  393.25  4556.1  393.54  4591.1  390.06  4657.7  386.84
  4671.3  385.18  4686.7  385.27  4746.3  385.74  4892.7  383.02  4895.5  382.52
  4898.7  383.02  4957.8  383.68  4976.6  386.48  4988.9  386.61  4996.6  383.23
  5001.9  383.23  5009.8   387.9  5083.5  396.66  5150.9  408.14  5157.3  409.16
#Mann= 6 ,-1 , 0
    4223     .16       0  4301.7     .12       0  4686.7     .16       0
  4892.7     .07       0  4898.7     .16       0  5150.9     .12       0
Bank Sta=4657.7,4976.6
XS Rating Curve= 0 ,0
Exp/Cntr=0.3,0.1

Type RM Length L Ch R = 1 ,6134    ,232,232,232
BEGIN DESCRIPTION:
Mapping XS 41ad400c
END DESCRIPTION:
XS GIS Cut Line= 4
      3771436.46     10610373.91       3771155.2     10610309.67
      3770801.04      10610248.9      3770504.35     10610191.65
#Sta/Elev= 30
  4310.4  413.35    4379   408.3  4394.4  406.25  4485.5  400.83  4491.8  399.46
  4591.9  393.85  4716.2  387.52  4742.6  383.98  4777.1  384.19  4797.4  383.29
  4807.7  384.44  4981.5  381.68  4990.2  376.82  4997.4  376.05  5000.2  375.55
  5003.4  376.05  5010.6  381.65  5033.4  384.55  5041.2  386.73  5071.7  391.52
  5080.1   395.2  5102.3  401.16  5122.6  405.07    5132  405.61    5143   408.5
  5188.9  412.32    5194  415.13  5204.1  415.78  5214.3  417.77  5260.4  420.54
#Mann= 4 ,-1 , 0
  4310.4     .16       0  4591.9     .12       0  4997.4     .07       0
  5003.4     .12       0
Bank Sta=4981.5,5010.6
XS Rating Curve= 0 ,0
Exp/Cntr=0.3,0.1

Type RM Length L Ch R = 1 ,5902    ,550,550,550
BEGIN DESCRIPTION:
UNT 341 IN BOCR 12.0
END DESCRIPTION:
XS GIS Cut Line= 3
      3771199.59     10609910.19      3770799.61     10610010.19
      3770649.62     10610060.19
#Sta/Elev= 30
  4579.9  415.11  4590.2  414.05  4597.9  411.32  4610.8  409.52  4639.2  401.61
    4652  399.37  4662.3  394.23  4672.7  391.66  4680.4  388.48  4693.3  388.02
  4703.6  385.08  4744.8  380.82  4788.3  381.02  4837.6  380.24  4921.3  381.22
  4981.9  381.18  4989.6  377.99  4994.8  377.99  4999.7  376.39  5002.5  375.89
  5005.7  376.39  5013.3  381.16  5023.8  381.55  5034.4  385.21    5066  392.01
  5076.5  396.93  5097.6  402.11  5118.7   409.4  5139.8  415.24  5150.3  416.01
#Mann= 6 ,-1 , 0
  4579.9     .12       0  4788.3     .16       0  4921.3     .12       0
  4999.7     .07       0  5005.7     .12       0  5076.5     .16       0
Bank Sta=4981.9,5013.3
XS Rating Curve= 0 ,0
Exp/Cntr=0.3,0.1

Type RM Length L Ch R = 1 ,5352    ,620,620,620
BEGIN DESCRIPTION:
UNT 341 IN BOCR 11.0
END DESCRIPTION:
XS GIS Cut Line= 3
      3771099.57      10609460.2      3770699.61     10609560.19
      3770449.63      10609410.2
#Sta/Elev= 30
  4608.2  395.58  4626.2  392.91  4631.4  393.89  4659.7  390.86  4709.7  383.05
  4744.4  378.37  4783.4  375.83  4814.3  375.38  4845.2  377.94  4855.5  376.21
  4886.5   375.7  4907.1  377.74  4968.9  376.87  4999.4  373.73  5002.2  373.23
  5005.4  373.73  5017.9  377.24  5086.6  375.51  5113.8   376.7  5123.5  378.52
  5129.3  377.72  5144.9  382.35  5160.4  383.24  5203.2  392.84  5240.1  399.48
  5253.7  400.61  5267.3  403.96    5277  404.47  5288.7  406.85    5312  407.99
#Mann= 5 ,-1 , 0
  4608.2     .16       0  4709.7     .12       0  4744.4     .16       0
  4999.4     .07       0  5005.4     .16       0
Bank Sta=4968.9,5017.9
XS Rating Curve= 0 ,0
Exp/Cntr=0.3,0.1

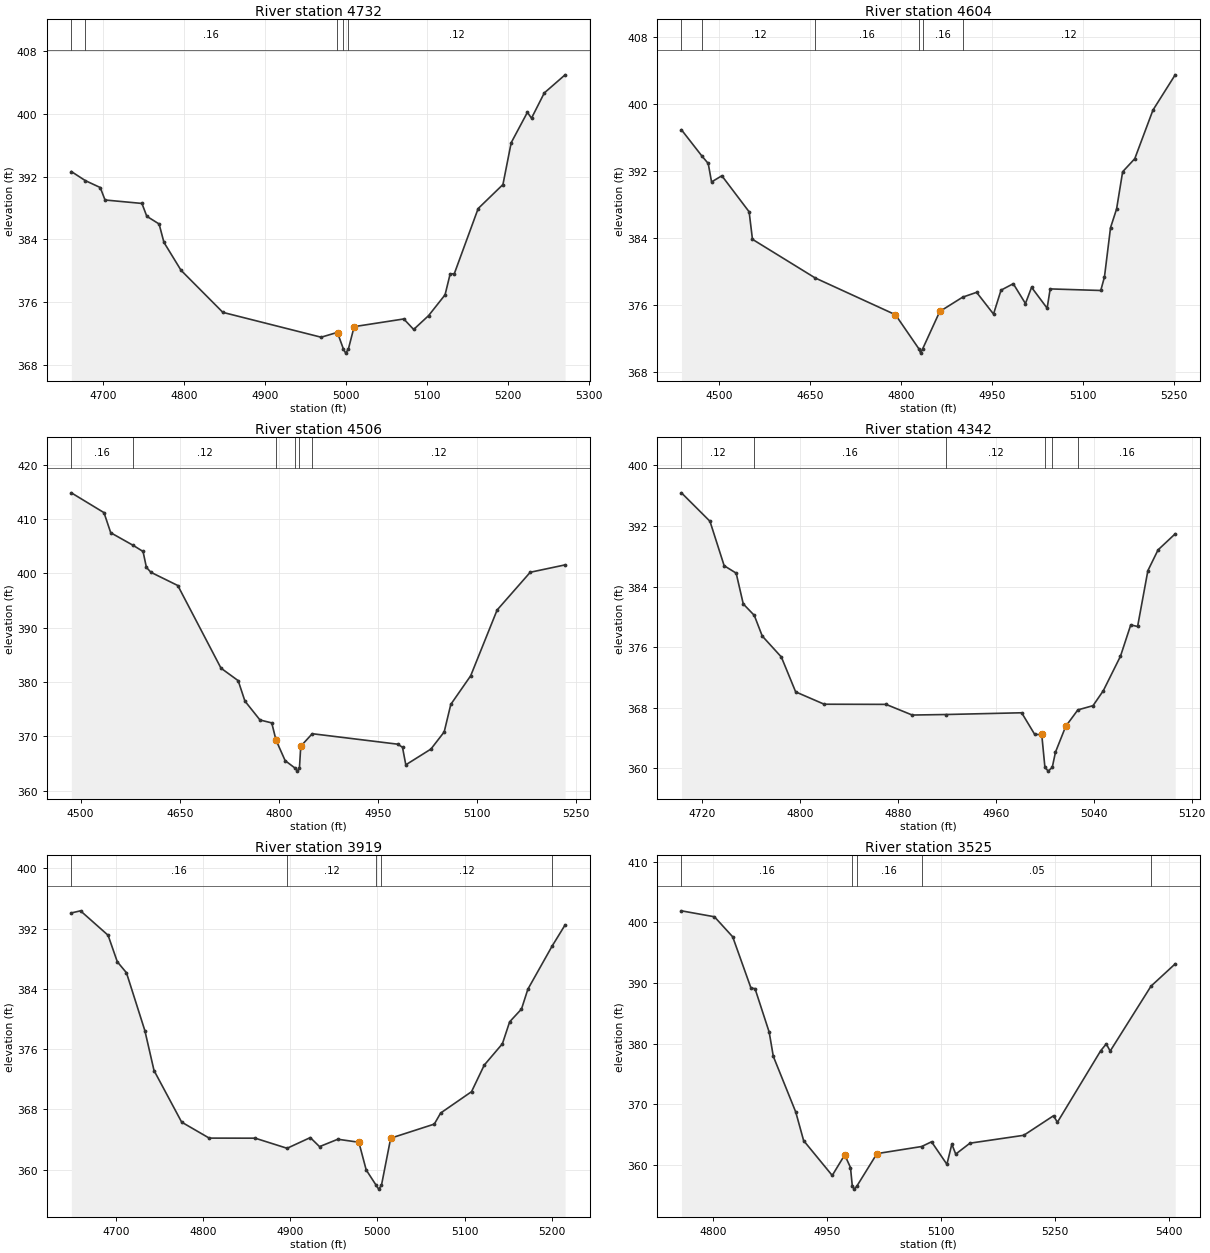
Type RM Length L Ch R = 1 ,4732    ,128,128,128
BEGIN DESCRIPTION:
UNT 341 IN BOCR 10.0
END DESCRIPTION:
XS GIS Cut Line= 3
       3771213.1     10609335.38      3770973.56     10609182.62
       3770654.4     10609116.71
#Sta/Elev= 30
  4660.7  392.66    4678   391.5  4696.4  390.62  4702.3  389.03  4747.9  388.59
  4753.9  386.95  4769.1  385.97  4775.1  383.62  4796.2  380.06  4847.9  374.69
  4969.3  371.52  4988.5  372.11  4989.7  372.04  4996.9  369.99  4999.6  369.49
  5002.9  369.99  5010.1  372.87  5071.4  373.85  5083.6  372.51    5102  374.27
  5122.4  376.93  5128.7   379.6  5133.8  379.62  5163.3  387.94  5193.9     391
  5204.1  396.34  5224.1  400.21  5229.2  399.47    5245  402.69  5270.7     405
#Mann= 5 ,-1 , 0
  4660.7     .12       0    4678     .16       0  4988.5     .12       0
  4996.9     .07       0  5002.9     .12       0
Bank Sta=4989.7,5010.1
XS Rating Curve= 0 ,0
Exp/Cntr=0.3,0.1

Type RM Length L Ch R = 1 ,4604    ,98,98,98
BEGIN DESCRIPTION:
Mapping XS 92ae37d3
END DESCRIPTION:
XS GIS Cut Line= 5
      3771460.74     10609206.36      3771202.08     10609079.63
      3771056.25     10609036.23      3770877.43     10609057.06
      3770682.92      10609051.9
#Sta/Elev= 30
  4437.6  396.93  4471.6  393.77  4481.8   392.9  4487.3  390.69  4504.3  391.43
  4549.3  387.12  4554.8  383.83  4658.3  379.21  4790.8  374.81  4829.6  370.72
  4832.3  370.22  4835.6  370.72  4863.9   375.2  4901.6  376.91  4924.7  377.49
  4952.6  374.89    4965  377.75  4985.2  378.52  5005.3  376.15  5015.4  378.09
  5041.1  375.59  5046.1   377.9  5129.6  377.71  5135.7  379.34  5145.7  385.22
  5155.7  387.46  5165.7  391.91  5185.7  393.47  5215.7  399.28  5252.4   403.5
#Mann= 6 ,-1 , 0
  4437.6     .16       0  4471.6     .12       0  4658.3     .16       0
  4829.6     .07       0  4835.6     .16       0  4901.6     .12       0
Bank Sta=4790.8,4863.9
XS Rating Curve= 0 ,0
Exp/Cntr=0.3,0.1

Type RM Length L Ch R = 1 ,4506    ,164,164,164
BEGIN DESCRIPTION:
Mapping XS 5ebd5e8d
END DESCRIPTION:
XS GIS Cut Line= 3
      3771398.22     10608895.61      3771066.66     10608954.63
      3770656.96     10608980.67
#Sta/Elev= 30
  4485.9  414.85  4535.3   411.2  4545.5   407.5  4579.7  405.16  4594.4  404.05
  4599.5  401.12  4606.4  400.21    4647  397.78  4712.4  382.56  4738.4  380.26
  4748.6   376.5  4771.4  373.02  4789.2  372.48  4795.7   369.3  4809.5  365.53
  4825.1   364.1  4827.8   363.6  4831.1   364.1  4833.1  368.18  4850.5  370.49
    4980  368.56  4987.1  367.99  4992.1  364.76  5030.1  367.66  5050.2  370.82
  5060.2  375.89  5090.3  381.16  5130.3  393.27  5180.4  400.22  5233.2  401.58
#Mann= 6 ,-1 , 0
  4485.9     .16       0  4579.7     .12       0  4795.7     .16       0
  4825.1     .07       0  4831.1     .16       0  4850.5     .12       0
Bank Sta=4795.7,4833.1
XS Rating Curve= 0 ,0
Exp/Cntr=0.3,0.1

Type RM Length L Ch R = 1 ,4342    ,423,423,423
BEGIN DESCRIPTION:
UNT 341 IN BOCR 9.0
END DESCRIPTION:
XS GIS Cut Line= 3
      3770999.59     10608560.22      3770849.61     10608810.19
      3770749.62     10608860.18
#Sta/Elev= 30
  4703.2  396.38  4726.5  392.62  4738.1  386.75  4747.9  385.77  4753.7   381.7
  4762.7  380.19  4769.2  377.46  4784.8  374.69  4796.5  370.08  4819.8  368.45
  4870.3  368.43  4891.7  367.02  4919.2  367.09  4981.1  367.32  4991.8  364.45
  4997.5  364.45  5000.1  360.11  5002.8  359.61  5006.1  360.11  5008.7  362.11
  5017.1  365.53    5027   367.7  5039.4  368.26  5047.8  370.24  5061.8  374.79
  5070.2  378.93  5075.8  378.72  5084.2   386.1  5092.5  388.84  5106.5  390.96
#Mann= 6 ,-1 , 0
  4703.2     .12       0  4762.7     .16       0  4919.2     .12       0
  5000.1     .07       0  5006.1     .12       0    5027     .16       0
Bank Sta=4997.5,5017.1
XS Rating Curve= 0 ,0
Exp/Cntr=0.3,0.1

Type RM Length L Ch R = 1 ,3919    ,394,394,394
BEGIN DESCRIPTION:
UNT 341 IN BOCR 8.0
END DESCRIPTION:
XS GIS Cut Line= 3
       3770699.6     10608210.22      3770599.61     10608510.19
       3770449.6      10608710.2
#Sta/Elev= 30
  4649.1  394.08  4659.6  394.36  4691.2  391.12  4701.8   387.6  4712.3  386.14
  4733.4  378.46  4743.9  373.17  4775.6  366.32  4807.2   364.2  4859.9  364.19
  4896.5  362.85  4923.1  364.27  4933.7  363.07  4954.7  364.05  4978.8  363.65
  4987.2  359.98  4998.7  357.93  5001.5  357.43  5004.7  357.93  5015.3  364.19
  5065.3  366.06  5072.6  367.53    5108  370.36  5122.6  373.89  5143.4  376.72
  5151.7  379.63  5165.3  381.33  5172.6  383.96  5200.3  389.66  5215.3  392.49
#Mann= 5 ,-1 , 0
  4649.1     .16       0  4896.5     .12       0  4998.7     .07       0
  5004.7     .12       0  5200.3     .16       0
Bank Sta=4978.8,5015.3
XS Rating Curve= 0 ,0
Exp/Cntr=0.3,0.1

Type RM Length L Ch R = 1 ,3525    ,63,63,63
BEGIN DESCRIPTION:
Mapping XS defd7636
END DESCRIPTION:
XS GIS Cut Line= 3
      3770439.56     10608071.46      3770340.58     10608313.69
      3770397.58     10608697.11
#Sta/Elev= 30
  4758.9  401.89  4802.3  400.91  4826.3  397.61  4850.3  389.18  4855.7  389.06
  4874.3   381.9  4879.7  377.92  4909.2  368.75  4919.6  364.03  4957.2  358.29
  4973.6  361.68  4981.2   359.6  4983.6  356.54  4986.4  356.04  4989.6  356.54
    5016  361.89  5074.8  363.06  5087.8  363.84    5108  360.13  5114.5  363.45
  5119.6  361.81  5138.3  363.61  5209.1  364.91  5248.2  368.13  5253.3  367.05
  5310.2  378.83  5317.6  379.97  5322.7  378.78  5376.4  389.48  5408.2  393.15
#Mann= 5 ,-1 , 0
  4758.9     .16       0  4983.6     .07       0  4989.6     .16       0
  5074.8     .05       0  5376.4     .16       0
Bank Sta=4973.6,5016
XS Rating Curve= 0 ,0
Exp/Cntr=0.3,0.1

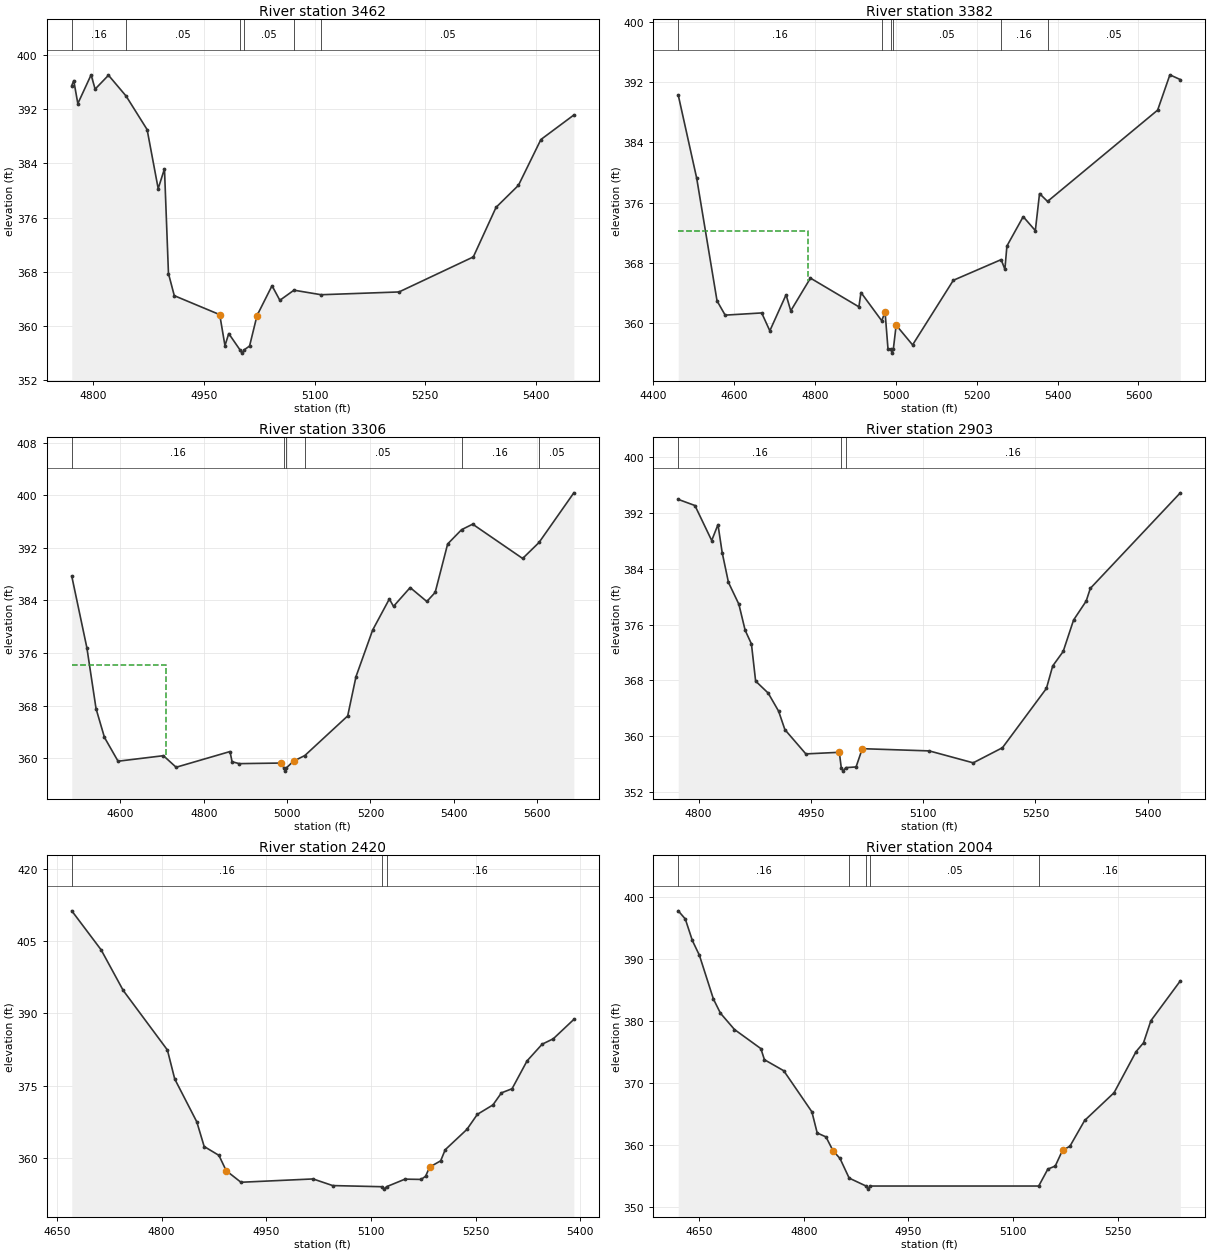
Type RM Length L Ch R = 1 ,3462    ,80,80,80
BEGIN DESCRIPTION:
UNT 341 IN BOCR 7.0
END DESCRIPTION:
XS GIS Cut Line= 3
      3770345.78     10608042.87      3770285.89     10608180.88
      3770364.02     10608704.34
#Sta/Elev= 30
  4771.3  395.47    4774  396.21  4779.5  392.81  4797.5  397.06  4802.9  394.95
    4821     397  4844.9  393.92  4873.3  388.98  4888.3  380.26  4896.8  383.19
  4902.2  367.73  4910.1  364.46  4971.6  361.66  4978.7  357.08  4983.8  358.87
  4998.9  356.48  5001.7  355.98  5004.9  356.48    5012  357.03  5022.1  361.53
  5042.4  365.93    5053  363.78  5072.1  365.27  5108.9   364.6  5214.3  365.01
  5314.9  370.18  5345.7   377.5    5376  380.75  5406.4  387.51    5451  391.13
#Mann= 6 ,-1 , 0
  4771.3     .16       0  4844.9     .05       0  4998.9     .04       0
  5004.9     .05       0  5072.1     .16       0  5108.9     .05       0
Bank Sta=4971.6,5022.1
XS Rating Curve= 0 ,0
Exp/Cntr=0.3,0.1

Type RM Length L Ch R = 1 ,3382    ,76,76,76
BEGIN DESCRIPTION:
Mapping XS 9b19a525
END DESCRIPTION:
XS GIS Cut Line= 4
      3770241.63      10607714.7      3770199.96     10608136.61
      3770265.06     10608511.61      3770210.46     10608945.81
#Sta/Elev= 30
  4461.4  390.26  4507.1  379.22  4557.4  362.96  4577.5  361.07  4667.9  361.36
    4688  358.99  4728.2  363.77  4739.8  361.64  4788.5  365.98  4908.4  362.17
  4913.5  364.07  4964.9  360.32  4973.1   361.5  4980.3  356.64  4987.5  356.53
  4990.2  356.03  4993.5  356.53  5000.6  359.74  5041.2  357.12    5142  365.69
  5260.3  368.43  5269.6  367.15  5274.6  370.24  5314.9  374.13  5344.9  372.28
  5355.3  377.19  5375.1  376.15  5647.5  388.26  5677.8  392.94  5703.6  392.31
#Mann= 6 ,-1 , 0
  4461.4     .16       0  4964.9     .05       0  4987.5     .04       0
  4993.5     .05       0  5260.3     .16       0  5375.1     .05       0
#XS Ineff= 2 , 0
         4783.66  372.17
Permanent Ineff=
       F       F
Bank Sta=4973.1,5000.6
XS Rating Curve= 0 ,0
Exp/Cntr=0.3,0.1

Type RM Length L Ch R = 1 ,3306    ,403,403,403
BEGIN DESCRIPTION:
Mapping XS 4bc0797b
END DESCRIPTION:
XS GIS Cut Line= 3
      3770210.38      10607722.5      3770147.87     10608147.02
      3770137.46     10608923.05
#Sta/Elev= 30
  4483.2  387.69  4519.5  376.79  4541.5  367.52  4561.7  363.15  4594.3  359.53
  4703.2  360.37  4733.7  358.61    4863     361    4868  359.45  4885.2  359.16
  4985.5  359.25  4992.5  358.52  4995.2  358.02  4998.5  358.52  5015.5  359.54
  5042.6  360.39  5145.5  366.42  5165.5  372.41  5205.5   379.5  5245.5  384.22
  5255.5   383.1  5295.5  385.96  5335.5  383.84  5355.5  385.22  5385.5   392.6
  5418.9  394.77  5445.5  395.61  5565.5  390.39  5604.8  392.82  5688.4  400.38
#Mann= 6 ,-1 , 0
  4483.2     .16       0  4992.5     .07       0  4998.5     .16       0
  5042.6     .05       0  5418.9     .16       0  5604.8     .05       0
#XS Ineff= 2 , 0
         4708.38  374.19
Permanent Ineff=
       F       F
Bank Sta=4985.5,5015.5
XS Rating Curve= 0 ,0
Exp/Cntr=0.3,0.1

Type RM Length L Ch R = 1 ,2903    ,483,483,483
BEGIN DESCRIPTION:
UNT 341 IN BOCR 6.0
END DESCRIPTION:
XS GIS Cut Line= 3
       3770199.6     10607660.21      3770099.61     10607860.19
      3769699.61     10608060.19
#Sta/Elev= 30
  4772.8  393.95  4795.1  393.07  4817.5  388.05  4825.9  390.33  4831.5  386.33
  4839.9  382.04  4853.8  378.92  4862.2  375.18  4870.6  373.22  4876.2  367.89
    4893  366.17  4906.9  363.58  4915.3  360.93  4943.3  357.45    4988  357.68
  4990.6  355.48  4993.3  354.98  4996.6  355.48  5010.4  355.58  5018.7   358.2
  5108.2  357.88  5166.9  356.17    5206  358.34  5264.7  366.84  5273.1  370.06
  5287.1  372.14    5301  376.65  5317.8  379.36  5323.4  381.19  5443.6  394.89
#Mann= 3 ,-1 , 0
  4772.8     .16       0  4990.6     .07       0  4996.6     .16       0
Bank Sta=4988,5018.7
XS Rating Curve= 0 ,0
Exp/Cntr=0.3,0.1

Type RM Length L Ch R = 1 ,2420    ,416,416,416
BEGIN DESCRIPTION:
UNT 341 IN BOCR 5.0
END DESCRIPTION:
XS GIS Cut Line= 3
      3769849.59     10607260.23      3769749.61     10607560.19
      3769549.61     10607910.19
#Sta/Elev= 30
  4671.3  411.37  4713.4  403.24    4745   394.8  4808.3   382.4  4818.8  376.37
  4850.4  367.45    4861  362.31  4882.1  360.47  4892.6  357.27  4913.7  354.87
    5017  355.56  5045.1  354.18  5116.2  353.94    5119  353.44  5122.2  353.94
  5148.7  355.52  5171.8  355.46  5178.2  356.12    5184  358.03  5199.8  359.33
  5206.3  361.64  5237.3  365.86  5252.4  369.01  5274.7  370.97  5286.9  373.48
  5302.1  374.34  5323.6  380.14  5345.2  383.61  5361.1  384.73  5390.6  388.77
#Mann= 3 ,-1 , 0
  4671.3     .16       0  5116.2     .07       0  5122.2     .16       0
Bank Sta=4892.6,5184
XS Rating Curve= 0 ,0
Exp/Cntr=0.3,0.1

Type RM Length L Ch R = 1 ,2004    ,461,461,461
BEGIN DESCRIPTION:
UNT 341 IN BOCR 4.0
END DESCRIPTION:
XS GIS Cut Line= 3
      3769799.63     10607260.19      3769399.61     10607310.19
      3769099.57      10607410.2
#Sta/Elev= 30
  4620.2  397.71  4630.3   396.4  4640.4  392.93  4650.5  390.55  4670.6  383.49
  4680.7   381.2  4700.8  378.57  4738.6  375.49  4743.7   373.7  4771.4  371.92
  4811.7   365.3  4819.3  361.89  4831.9  361.25  4841.9  359.04    4852  357.77
  4865.1  354.61  4889.3  353.33  4892.1  352.83  4895.3  353.33  5136.7  353.33
  5149.8  356.06  5160.4  356.55  5170.9  359.11  5181.4  359.74  5202.5   363.9
  5244.7  368.38  5276.3  375.02  5286.9  376.43  5297.4  379.98  5339.6  386.41
#Mann= 5 ,-1 , 0
  4620.2     .16       0  4865.1     .05       0  4889.3    .033       0
  4895.3     .05       0  5136.7     .16       0
Bank Sta=4841.9,5170.9
XS Rating Curve= 0 ,0
Exp/Cntr=0.3,0.1

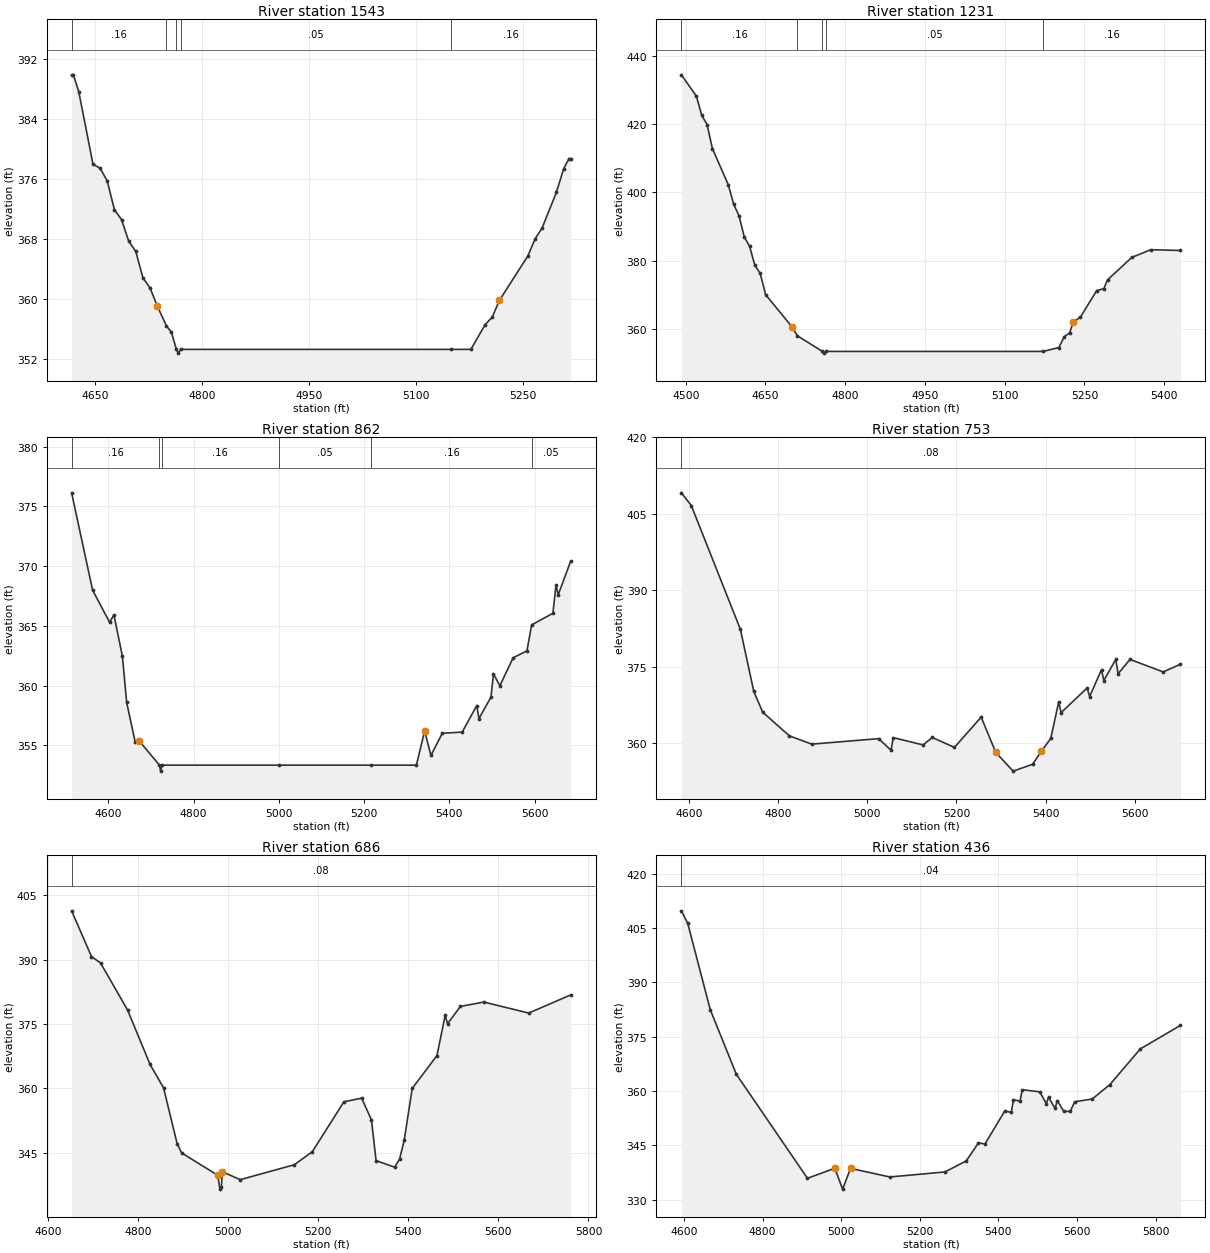
Type RM Length L Ch R = 1 ,1543    ,312,312,312
BEGIN DESCRIPTION:
UNT 341 IN BOCR 3.0
END DESCRIPTION:
XS GIS Cut Line= 3
      3769099.61     10606610.17      3769099.61     10607010.19
      3769099.61     10607310.17
#Sta/Elev= 30
  4616.6  389.95  4619.1  389.95  4626.6  387.71  4646.6  378.02  4656.6  377.49
  4666.6  375.78  4676.6  371.97  4686.6  370.64  4696.6  367.79  4706.6  366.39
  4716.6  362.88  4726.6  361.53  4736.6  359.14  4749.6  356.47  4756.6  355.59
  4763.6  353.33  4766.4  352.83  4769.6  353.33  5148.9  353.33  5176.6  353.33
  5196.6  356.63  5206.6  357.63  5216.6  359.87  5256.6   365.8  5266.6  368.05
  5276.6  369.54  5296.6  374.29  5306.6  377.39  5314.1  378.77  5316.6  378.77
#Mann= 5 ,-1 , 0
  4616.6     .16       0  4749.6     .05       0  4763.6    .033       0
  4769.6     .05       0  5148.9     .16       0
Bank Sta=4736.6,5216.6
XS Rating Curve= 0 ,0
Exp/Cntr=0.3,0.1

Type RM Length L Ch R = 1 ,1231    ,369,369,369
BEGIN DESCRIPTION:
UNT 341 IN BOCR 2.0
END DESCRIPTION:
XS GIS Cut Line= 3
      3768790.62      10606451.9      3768790.62     10607059.59
      3768851.38     10607385.08
#Sta/Elev= 30
  4491.9  434.51  4520.2  428.24  4530.2  422.62  4540.2   419.9  4550.2  412.88
  4580.2  402.22  4590.2  396.57  4600.2  393.16  4610.2  386.95  4620.2  384.18
  4630.2  378.55  4640.2  376.23  4650.2  370.03  4700.2  360.49  4710.2  357.91
  4757.2  353.33  4759.9  352.83  4763.2  353.33  5172.4  353.33  5201.9  354.47
  5212.1  357.65  5222.3  358.83  5228.8   361.9  5242.6  363.41  5273.1  371.19
  5286.6  371.75  5293.5  374.33  5339.3  380.94  5374.9  383.18  5430.7  382.96
#Mann= 5 ,-1 , 0
  4491.9     .16       0  4710.2     .05       0  4757.2    .033       0
  4763.2     .05       0  5172.4     .16       0
Bank Sta=4700.2,5228.8
XS Rating Curve= 0 ,0
Exp/Cntr=0.3,0.1

Type RM Length L Ch R = 1 ,862     ,109,109,109
BEGIN DESCRIPTION:
Mapping XS df311776
END DESCRIPTION:
XS GIS Cut Line= 3
      3768416.71     10606461.01      3768423.65     10607040.86
      3768583.37     10607610.29
#Sta/Elev= 30
  4513.6  376.14  4562.8  367.99  4602.8  365.29  4612.8  365.93  4632.8  362.45
  4642.8  358.58  4662.8  355.27  4672.8  355.33  4719.8  353.33  4722.5  352.83
  4725.8  353.33  4999.6  353.33  5217.1  353.33  5322.8  353.33  5342.1   356.2
  5356.9  354.14  5383.6     356  5430.3   356.1  5464.4  358.32  5469.6  357.23
  5497.8  359.03  5503.7  360.98  5518.6  359.98  5549.8  362.32  5582.3  362.91
  5593.2  365.08  5643.2  366.05  5650.4   368.4  5655.6   367.6  5684.9  370.42
#Mann= 6 ,-1 , 0
  4513.6     .16       0  4719.8    .033       0  4725.8     .16       0
  4999.6     .05       0  5217.1     .16       0  5593.2     .05       0
Bank Sta=4672.8,5342.1
XS Rating Curve= 0 ,0
Exp/Cntr=0.3,0.1

Type RM Length L Ch R = 1 ,753     ,67,67,67
BEGIN DESCRIPTION:
Mapping XS ded0d03a
END DESCRIPTION:
XS GIS Cut Line= 3
      3768322.96     10606467.95      3768340.32      10607172.8
      3768468.23      10607566.9
#Sta/Elev= 30
  4583.1  409.11  4605.3  406.62  4715.4  382.31  4745.4  370.15  4765.4  366.04
  4825.4  361.38  4875.4  359.76  5025.5  360.84  5053.3  358.56  5058.3  361.04
  5125.5   359.6  5145.5  361.08  5195.5  359.12  5255.5  365.07  5288.2  358.14
  5327.2  354.46  5370.8   355.8  5390.6  358.36  5411.6  360.88  5429.5  368.09
  5434.7  365.94  5493.4  370.81  5498.7  369.11  5525.4  374.38  5530.6  372.25
  5557.4   376.4  5562.6  373.58  5589.3   376.4  5663.9  373.94  5702.5  375.46
#Mann= 1 ,-1 , 0
  4583.1     .08       0
Bank Sta=5288.2,5390.6
XS Rating Curve= 0 ,0
Exp/Cntr=0.3,0.1

Type RM Length L Ch R = 1 ,686     ,250,250,250
BEGIN DESCRIPTION:
Mapping XS ffeb3f9a
END DESCRIPTION:
XS GIS Cut Line= 3
       3768267.4     10606506.11      3768281.29     10607141.55
      3768409.59     10607595.78
#Sta/Elev= 30
  4652.9  401.38    4697  390.71    4717  389.24    4777  378.27    4827  365.57
    4857  360.09    4887  347.12    4897  344.95  4977.1  339.73  4982.1   336.5
  4985.3     337  4987.3  340.54  5027.1  338.71  5147.1  342.18  5187.1  345.22
  5257.1  356.85  5296.5  357.71  5318.3  352.66  5328.6  343.15  5369.6  341.62
  5380.6  343.45    5391  347.86  5408.8  359.98  5463.7  367.64    5482  377.05
  5487.2  375.06  5515.7  379.09  5567.6  380.11  5667.5  377.55  5760.5  381.78
#Mann= 1 ,-1 , 0
  4652.9     .08       0
Bank Sta=4977.1,4987.3
XS Rating Curve= 0 ,0
Exp/Cntr=0.3,0.1

Type RM Length L Ch R = 1 ,436     ,0,0,0
BEGIN DESCRIPTION:
UNT 341 IN BOCR 1.0
END DESCRIPTION:
XS GIS Cut Line= 4
      3768243.07     10606461.04      3768038.24      10606773.5
      3768052.13     10607124.19      3768298.64     10607610.27
#Sta/Elev= 30
  4593.5  409.71  4609.7  406.23  4666.9  382.43  4733.3  364.58  4914.2  335.87
  4983.8  338.64  5003.6  332.88  5023.9  338.61  5123.5  336.24    5264  337.62
  5318.1  340.66  5349.3  345.65  5365.9  345.35  5416.1  354.44  5432.7  354.07
  5438.3  357.56    5455  357.19  5460.6  360.32  5505.1  359.74  5521.8  356.48
  5527.4  358.26  5544.1  355.17  5549.7  357.33  5566.3  354.34  5582.7  354.35
  5594.2  356.99  5638.8  357.77  5683.6  361.75  5761.1   371.6  5863.1  378.09
#Mann= 1 ,-1 , 0
  4593.5     .04       0
Bank Sta=4983.8,5023.9
XS Rating Curve= 0 ,0
Exp/Cntr=0.3,0.1

Chan Stop Cuts=-1
Use User Specified Reach Order=0
Composite Channel Slope=5