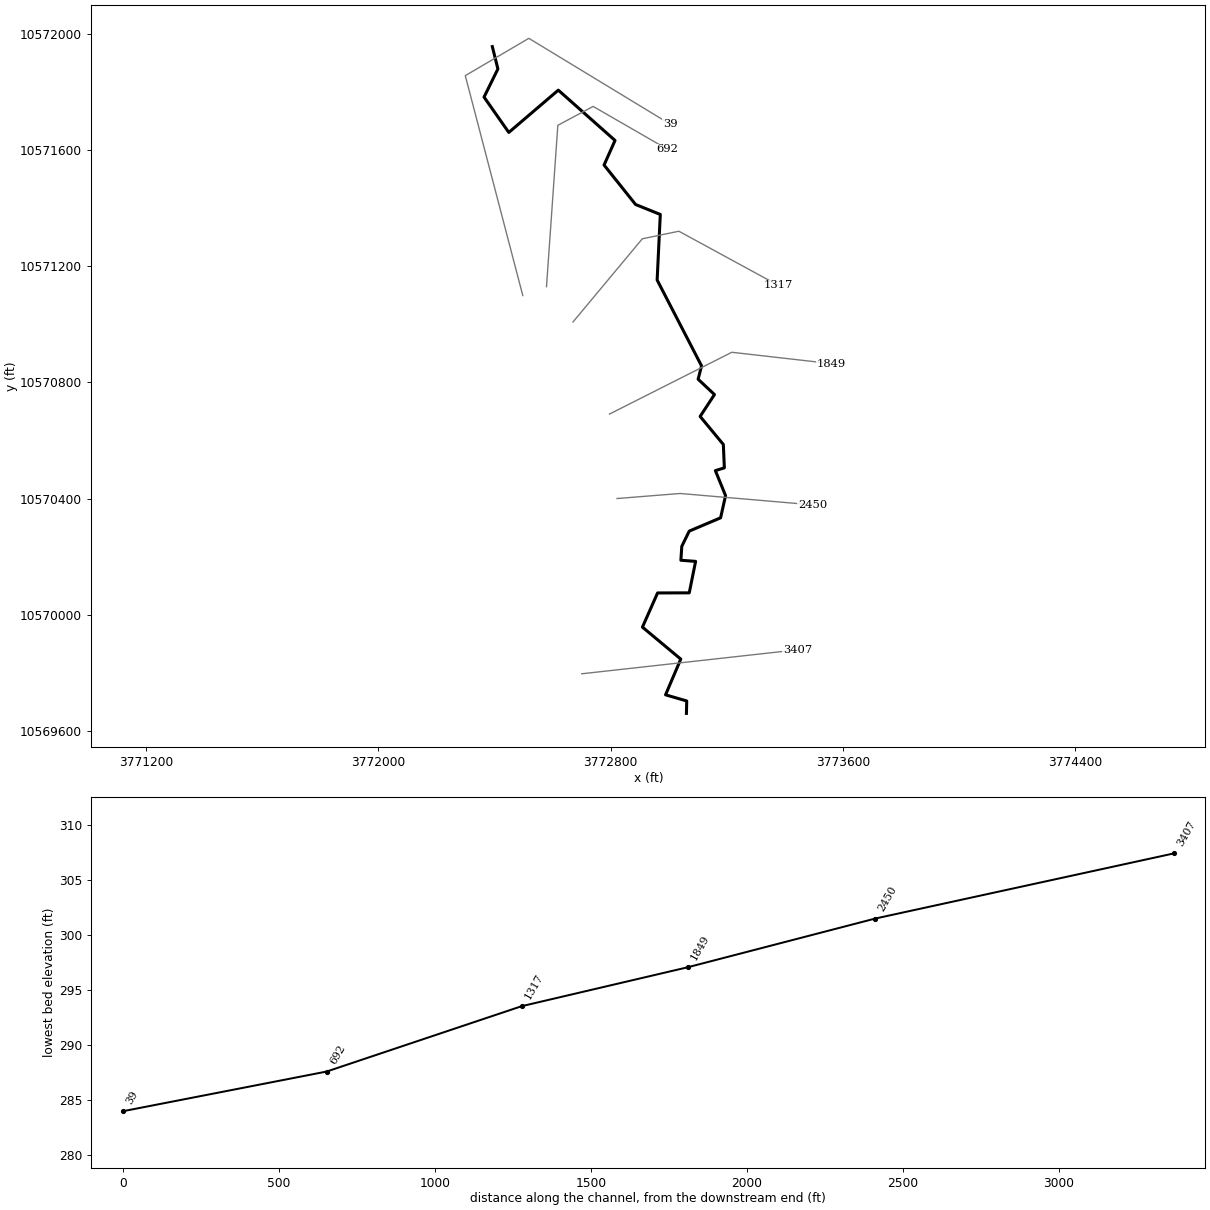
--- UNT 342 IN BOCR.prj (project) ---

Proj Title=UNT 342 IN BOCR Base Level Engineering
Current Plan=p01
Default Exp/Contr=0.3,0.1
English Units
Geom File=g01
Flow File=f01
Plan File=p01
Y Axis Title=Elevation
X Axis Title(PF)=Main Channel Distance
X Axis Title(XS)=Station
BEGIN DESCRIPTION:
UNT 342 IN BOCR
END DESCRIPTION:
DSS File=dss
DSS Export Rating Curves= 0
DSS Export Rating Curve Sorted= 0
DSS Export Volume Flow Curves= 0
DXF OffsetX= 0
DXF OffsetY= 0
DXF ScaleX= 1
DXF ScaleY= 10

--- UNT 342 IN BOCR.p01 (plan) ---

Plan Title=Multiple Run
Program Version=4.10
Short Identifier=Multiple Run
Geom File=g01
Flow File=f01
Subcritical Flow
K Sum by GR= 0
Std Step Tol= 0.01
Critical Tol= 0.01
Num of Std Step Trials= 20
Max Error Tol= 0.3
Flow Tol Ratio= 0.001
Split Flow NTrial= 30
Split Flow Tol= 0.02
Split Flow Ratio= 0.02
Log Output Level= 0
Friction Slope Method= 1
Unsteady Friction Slope Method= 2
Unsteady Bridges Friction Slope Method= 1
Parabolic Critical Depth
Global Vel Dist= 1 , 1 , 1
Global Log Level= 0
CheckData=True
Encroach Param=-1 ,0,0, 0
BEGIN DESCRIPTION:
Multiple Run
END DESCRIPTION:
Computation Interval=1HOUR
Output Interval=1HOUR
Run HTab= 0
Run UNet= 0
Run PostProcess= 0
Run WQNet= 0
UNET Theta= 1
UNET Theta Warmup= 1
UNET ZTol= 0.02
UNET ZSATol= 0.05
UNET MxIter= 20
UNET MaxInSteps= 0
UNET DtIC= 0
UNET DtMin= 0
UNET MaxCRTS= 20
UNET WFStab= 2
UNET SFStab= 1
UNET WFX= 1
UNET SFX= 1
UNET DSS MLevel= 4
UNET DZMax Abort= 100
UNET Convert EG Bridges= 0
UNET Use Existing IB Tables=-1
UNET Froude Reduction=False
UNET Froude Limit= 1
UNET Froude Power= 10
UNET Time Slicing=0,0, 5
UNET Junction Losses=0
Instantaneous Interval=1HOUR
DSS File=dss
Write IC File= 0
Write IC File at Sim End=0
Echo Input=False
Echo Parameters=False
Echo Output=False
Write Detailed= 0
WQ AD Non Conservative
WQ ULTIMATE=-1
WQ Max Comp Step=1HOUR
WQ Output Interval=15MIN
WQ Output Selected Increments= 0
WQ Output face flow=0
WQ Output face velocity=0
WQ Output face area=0
WQ Output face dispersion=0
WQ Output cell volume=0
WQ Output cell surface area=0
WQ Output cell continuity=0
WQ Output cumulative cell continuity=0
WQ Output face conc=0
WQ Output face dconc_dx=0
WQ Output face courant=0
WQ Output face peclet=0
WQ Output face adv mass=0
WQ Output face disp mass=0
WQ Output cell mass=0
WQ Output cell source sink temp=0
WQ Output cell source sink nsm=0
WQ Output MaxMinRange=-1
WQ Daily Max Min Mean=-1
WQ Daily Range=0
WQ Daily Time=0
WQ Create Restart=0
WQ Fixed Restart=0
WQ System Summary=0
WQ Use Fixed Temperature=0
Sorting and Armoring Iterations= 10
XS Update Threshold= 0.02
Hydraulics Update Threshold= 0.02
Energy Slope Method= 1
Volume Change Method= 0
XS Weighting Method= 0
Number of US Weighted Cross Sections= 1
Number of DS Weighted Cross Sections= 1
Upstream XS Weight=0.25
Main XS Weight=0.5
Downstream XS Weight=0.25
Number of DS XS's Weighted with US Boundary= 1
Upstream Boundary Weight= 1
Weight of XSs Associated with US Boundary= 0
Number of US XS's Weighted with DS Boundary= 1
Downstream Boundary Weight= 0.5
Weight of XSs Associated with DS Boundary= 0.5
Sediment Output Level= 4
Mass or Volume Output= 0
Output Increment Type= 1
Profile and TS Output Increment= 10
XS Output Flag= 0
XS Output Increment= 10
Disregard all LS=0
Disregard all Conn=0
Disregard all Breaches=0
Disregard all Pumps=0

--- UNT 342 IN BOCR.f01 (steady flow) ---

Flow Title=Multiple
Number of Profiles=7
Profile Names=10-year,25-year,50-year,1pct_min,100-year,1pct_plu,500-year
River Rch & RM= UNT 342 IN BOCR,Reach-1,3407
     246     316     371     323     436     590     603
Boundary for River Rch & Prof#=UNT 342 IN BOCR,Reach-1,1
Up Type=0
Dn Type=3
Dn Slope=0.005
Boundary for River Rch & Prof#=UNT 342 IN BOCR,Reach-1,2
Up Type=0
Dn Type=3
Dn Slope=0.005
Boundary for River Rch & Prof#=UNT 342 IN BOCR,Reach-1,3
Up Type=0
Dn Type=3
Dn Slope=0.005
Boundary for River Rch & Prof#=UNT 342 IN BOCR,Reach-1,4
Up Type=0
Dn Type=3
Dn Slope=0.005
Boundary for River Rch & Prof#=UNT 342 IN BOCR,Reach-1,5
Up Type=0
Dn Type=3
Dn Slope=0.005
Boundary for River Rch & Prof#=UNT 342 IN BOCR,Reach-1,6
Up Type=0
Dn Type=3
Dn Slope=0.005
Boundary for River Rch & Prof#=UNT 342 IN BOCR,Reach-1,7
Up Type=0
Dn Type=3
Dn Slope=0.005

--- UNT 342 IN BOCR.g01 (geometry) ---

Geom Title=Existing Conditions
Program Version=4.10

River Reach=UNT 342 IN BOCR ,Reach-1
Reach XY= 30
      3773061.07      10569660.3      3773062.11     10569703.01
       3772989.2     10569724.19      3773041.63      10569847.1
      3772909.68     10569957.17      3772961.77     10570074.88
       3773070.8     10570075.23      3773092.67     10570183.56
      3773041.98     10570187.38       3773045.1      10570235.3
       3773070.8     10570287.73      3773178.78     10570333.56
       3773195.8     10570409.95      3773160.73     10570496.06
      3773191.63     10570505.44      3773188.16     10570585.99
       3773108.3     10570682.52       3773157.6     10570757.87
      3773101.35     10570810.65      3773113.16     10570856.48
      3772960.27     10571152.14      3772971.12     10571377.83
      3772886.05     10571412.12      3772777.54     10571547.97
       3772815.3     10571632.61      3772619.99     10571805.78
      3772449.61     10571660.19      3772364.35     10571781.91
      3772412.09      10571878.7      3772392.89     10571955.69

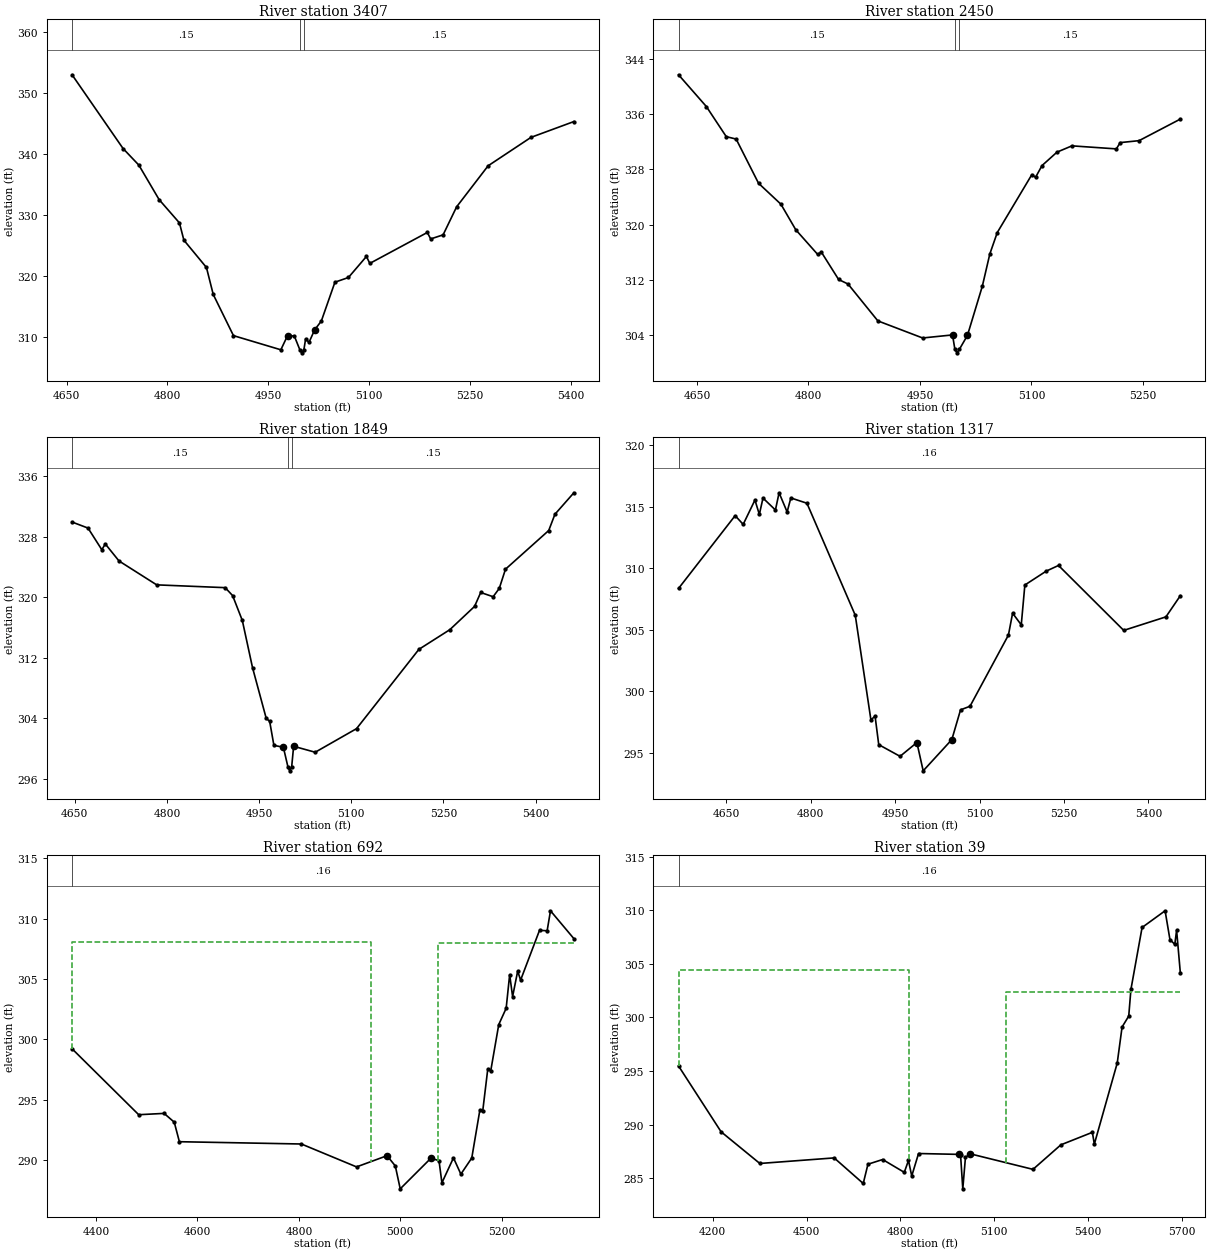
Type RM Length L Ch R = 1 ,3407    ,957,957,957
BEGIN DESCRIPTION:
UNT 342 IN BOCR 5.0
END DESCRIPTION:
XS GIS Cut Line= 2
      3772700.84     10569796.62      3773443.07     10569879.09
#Sta/Elev= 30
    4658  352.96  4733.9  340.87  4757.4  338.15  4787.6  332.49  4817.8  328.68
  4824.4  325.85    4858  321.37  4868.1  316.95  4898.2   310.2  4968.7  307.88
  4978.7   310.2  4988.8  310.13    4997  307.88  4999.8  307.38    5003  307.88
  5005.6  309.68  5010.6  309.09    5019  311.14    5029   312.6  5049.2  318.96
  5069.3  319.73  5096.1  323.18  5101.1  322.04  5186.7  327.11  5191.7  326.05
  5210.2  326.72  5230.3  331.31  5277.2  338.04    5341   342.7  5404.8  345.29
#Mann= 3 ,-1 , 0
    4658     .15       0    4997     .05       0    5003     .15       0
Bank Sta=4978.7,5019
XS Rating Curve= 0 ,0
Exp/Cntr=0.3,0.1

Type RM Length L Ch R = 1 ,2450    ,601,601,601
BEGIN DESCRIPTION:
UNT 342 IN BOCR 4.0
END DESCRIPTION:
XS GIS Cut Line= 3
      3772822.36     10570399.92      3773039.41     10570417.29
       3773494.9     10570378.25
#Sta/Elev= 30
  4625.3  341.69  4662.7   337.1  4689.5  332.74  4702.8  332.39  4732.9     326
    4763  322.97    4783  319.27  4812.4  315.71  4817.4  316.04  4840.6  312.08
  4853.3  311.42  4893.4  306.09  4953.6  303.62  4993.8  304.06    4997  301.97
  4999.8  301.47    5003  301.97  5013.9     304  5033.9  311.11    5044  315.78
    5054  318.87  5100.5  327.25  5105.5  326.86  5114.2  328.56  5134.3   330.5
  5154.4  331.41  5214.2  330.97  5219.3  331.88  5244.7  332.16  5300.2  335.28
#Mann= 3 ,-1 , 0
  4625.3     .15       0    4997     .05       0    5003     .15       0
Bank Sta=4993.8,5013.9
XS Rating Curve= 0 ,0
Exp/Cntr=0.3,0.1

Type RM Length L Ch R = 1 ,1849    ,532,532,532
BEGIN DESCRIPTION:
UNT 342 IN BOCR 3.0
END DESCRIPTION:
XS GIS Cut Line= 3
      3772796.39     10570690.74      3773217.37      10570903.4
       3773560.2     10570864.34
#Sta/Elev= 30
  4645.6  329.96  4671.6  329.16    4694   326.3  4699.7  327.06    4722  324.81
  4783.3  321.65  4894.8  321.28  4906.9  320.23  4922.7  316.94  4939.3   310.7
  4961.6  303.99  4967.2   303.6  4974.1  300.42  4989.5  300.17    4997  297.55
  4999.8  297.05    5003  297.55  5006.2   300.3  5041.3  299.51  5108.6  302.63
  5210.1  313.12  5260.4  315.72  5300.7   318.8  5310.7  320.64  5330.9  320.08
  5340.9  321.18    5351  323.72  5421.4  328.84  5431.5  330.99  5462.3  333.83
#Mann= 3 ,-1 , 0
  4645.6     .15       0    4997     .05       0    5003     .15       0
Bank Sta=4989.5,5006.2
XS Rating Curve= 0 ,0
Exp/Cntr=0.3,0.1

Type RM Length L Ch R = 1 ,1317    ,625,625,625
BEGIN DESCRIPTION:
UNT 342 IN BOCR 2.0
END DESCRIPTION:
XS GIS Cut Line= 4
      3772670.47     10571007.55      3772909.21     10571294.02
      3773035.07     10571320.07      3773377.93     10571133.45
#Sta/Elev= 30
    4565  308.35  4665.6  314.27  4679.9  313.56  4700.8  315.54  4708.6  314.37
  4715.1   315.7  4737.2  314.73  4743.7  316.13    4758  314.57  4764.6  315.71
  4793.2  315.28  4879.1  306.17  4906.9  297.66  4914.3  297.97  4920.8  295.65
  4958.7   294.7  4988.6  295.82  4999.8  293.52  5050.7  296.06  5066.2  298.48
    5083  298.77  5151.3  304.56  5158.7  306.34  5174.1  305.39  5180.5  308.63
  5218.5  309.76  5240.3  310.22  5356.2  304.94  5431.2  306.04  5456.8  307.76
#Mann= 1 ,-1 , 0
    4565     .16       0
Bank Sta=4988.6,5050.7
XS Rating Curve= 0 ,0
Exp/Cntr=0.3,0.1

Type RM Length L Ch R = 1 ,692     ,653,653,653
BEGIN DESCRIPTION:
Mapping XS 4c74082b
END DESCRIPTION:
XS GIS Cut Line= 4
      3772579.35     10571129.14      3772618.41     10571684.65
      3772739.93     10571749.75      3772995.31     10571602.59
#Sta/Elev= 30
  4352.7  299.21  4484.1  293.74  4534.2  293.85  4554.2  293.12  4564.3   291.5
  4804.9  291.31  4913.7  289.41  4973.8  290.34  4990.1  289.49  4999.8  287.59
  5060.5  290.14  5076.3  289.92    5082  288.09  5104.8  290.16  5119.4  288.81
  5140.9  290.15  5156.7  294.09  5162.5  294.05  5172.5  297.55  5178.3  297.38
  5194.1  301.22  5208.7  302.57  5215.6  305.36  5221.4  303.54  5231.4  305.65
  5237.2  304.91  5274.5  309.04  5289.5     309  5296.1  310.66  5342.2  308.35
#Mann= 1 ,-1 , 0
  4352.7     .16       0
#XS Ineff= 2 , 0
         4942.24  308.09 5075.27          307.98
Permanent Ineff=
       F       F
Bank Sta=4973.8,5060.5
XS Rating Curve= 0 ,0
Exp/Cntr=0.3,0.1

Type RM Length L Ch R = 1 ,39      ,0,0,0
BEGIN DESCRIPTION:
UNT 342 IN BOCR 1.0
END DESCRIPTION:
XS GIS Cut Line= 4
      3772497.76     10571098.67      3772299.83     10571855.66
      3772518.58     10571984.13      3773004.68       10571689.
#Sta/Elev= 30
  4090.7  295.47  4226.8  289.32  4350.7  286.36  4588.4  286.88  4681.4  284.49
  4696.5  286.29  4743.5  286.73  4812.7  285.53  4826.1  286.64  4836.5  285.19
  4858.3  287.29  4986.9  287.21  4992.7  287.14  4999.8  283.99  5008.3  286.93
  5023.6  287.26  5224.3  285.81  5313.4   288.1  5414.2  289.27  5420.5  288.17
  5493.7  295.74  5509.2  299.11  5530.5  300.13  5537.5  302.62  5573.2  308.41
  5646.8  309.97  5662.3  307.28  5677.8  306.83  5683.6  308.15  5695.5  304.18
#Mann= 1 ,-1 , 0
  4090.7     .16       0
#XS Ineff= 2 , 0
         4826.83  304.44 5139.32          302.38
Permanent Ineff=
       F       F
Bank Sta=4986.9,5023.6
XS Rating Curve= 0 ,0
Exp/Cntr=0.3,0.1

Chan Stop Cuts=-1
Use User Specified Reach Order=0
Composite Channel Slope=5