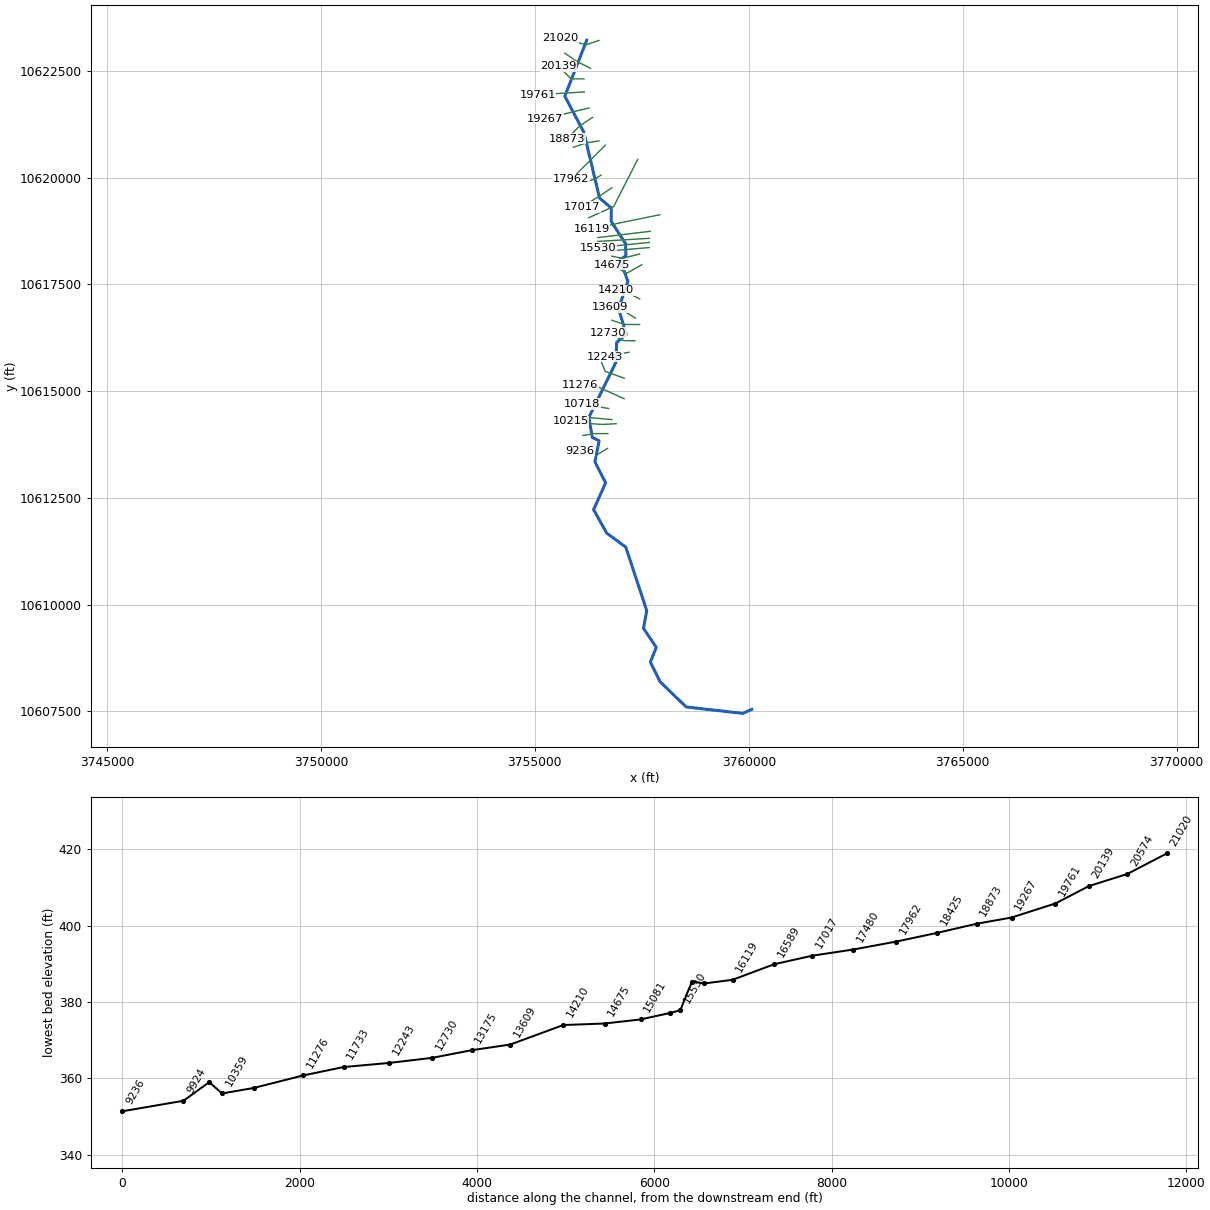
--- WILLOW SLOUGH.prj (project) ---

Proj Title=WILLOW SLOUGH Base Level Engineering
Current Plan=p01
Default Exp/Contr=0.3,0.1
English Units
Geom File=g01
Flow File=f01
Plan File=p01
Y Axis Title=Elevation
X Axis Title(PF)=Main Channel Distance
X Axis Title(XS)=Station
BEGIN DESCRIPTION:
WILLOW SLOUGH
END DESCRIPTION:
DSS Export Rating Curves= 0
DSS Export Rating Curve Sorted= 0
DSS Export Volume Flow Curves= 0
DXF OffsetX= 0
DXF OffsetY= 0
DXF ScaleX= 1
DXF ScaleY= 10

--- WILLOW SLOUGH.p01 (plan) ---

Plan Title=Multiple Run
Short Identifier=Multiple
Geom File=g01
Flow File=f01
Subcritical Flow
K Sum by GR= 0
Std Step Tol= 0.01
Critical Tol= 0.01
Num of Std Step Trials= 20
Max Error Tol= 0.3
Flow Tol Ratio= 0.001
Split Flow NTrial= 30
Split Flow Tol= 0.02
Split Flow Ratio= 0.02
Log Output Level= 0
Friction Slope Method= 1
Unsteady Friction Slope Method= 2
Unsteady Bridges Friction Slope Method= 1
Parabolic Critical Depth
Global Vel Dist=  1 , 1 , 1
Global Log Level= 0
CheckData=True
Encroach Param= -1, 0, 0, 0
BEGIN DESCRIPTION:
Multiple Run
END DESCRIPTION:

--- WILLOW SLOUGH.f01 (steady flow) ---

Flow Title=Multiple
Program Version=4.10
Number of Profiles= 7
Profile Names=10-year,25-year,50-year,1pct_min,100-year,1pct_plu,500-year
River Rch & RM=WILLOW SLOUGH,Reach-1         ,21020
     729    1006    1241    1126    1523    2059    2300
River Rch & RM=WILLOW SLOUGH,Reach-1         ,17962
     987    1380    1714    1565    2116    2862    3235
River Rch & RM=WILLOW SLOUGH,Reach-1         ,10718
    1239    1747    2183    2002    2707    3661    4180
River Rch & RM=WILLOW SLOUGH,Reach-1         ,5919
    1494    2123    2667    2457    3322    4493    5177
River Rch & RM=WILLOW SLOUGH,Reach-1         ,2999
    1798    2574    3250    3007    4067    5500    6394
Boundary for River Rch & Prof#=WILLOW SLOUGH,Reach-1         , 1
Up Type= 0
Dn Type= 3
Dn Slope=0.004
Boundary for River Rch & Prof#=WILLOW SLOUGH,Reach-1         , 2
Up Type= 0
Dn Type= 3
Dn Slope=0.004
Boundary for River Rch & Prof#=WILLOW SLOUGH,Reach-1         , 3
Up Type= 0
Dn Type= 3
Dn Slope=0.004
Boundary for River Rch & Prof#=WILLOW SLOUGH,Reach-1         , 4
Up Type= 0
Dn Type= 3
Dn Slope=0.004
Boundary for River Rch & Prof#=WILLOW SLOUGH,Reach-1         , 5
Up Type= 0
Dn Type= 3
Dn Slope=0.004
Boundary for River Rch & Prof#=WILLOW SLOUGH,Reach-1         , 6
Up Type= 0
Dn Type= 3
Dn Slope=0.004
Boundary for River Rch & Prof#=WILLOW SLOUGH,Reach-1         , 7
Up Type= 0
Dn Type= 3
Dn Slope=0.004
DSS Import GetInterval= 0
DSS Import GetPeak= 0
DSS Import FillOption= 0

--- WILLOW SLOUGH.g01 (geometry) ---

Geom Title=Existing Conditions
Program Version=4.10

River Reach=WILLOW SLOUGH   ,Reach-1
Reach XY= 30
      3756212.09      10623216.9        3755701.       10621906.
       3756146.5       10621059.        3756512.       10619521.
        3756786.       10619288.       3756784.5       10618973.
      3757121.25       10618452.        3757128.       10618166.
        3756991.       10618081.       3757174.5       10617568.
      3756956.25       10616933.        3757136.       10616327.
      3756911.75       10616141.        3756896.       10615678.
        3756262.       10614383.       3756343.5       10613916.
        3756502.       10613838.      3756403.75       10613346.
       3756653.5       10612854.      3756373.25       10612227.
      3756679.25       10611676.       3757125.5       10611349.
      3757615.25       10609859.      3757539.05      10609447.3
       3757838.5       10609000.       3757699.5       10608659.
      3757928.25       10608196.      3758536.75       10607606.
      3759860.25       10607456.       3760069.5       10607550.

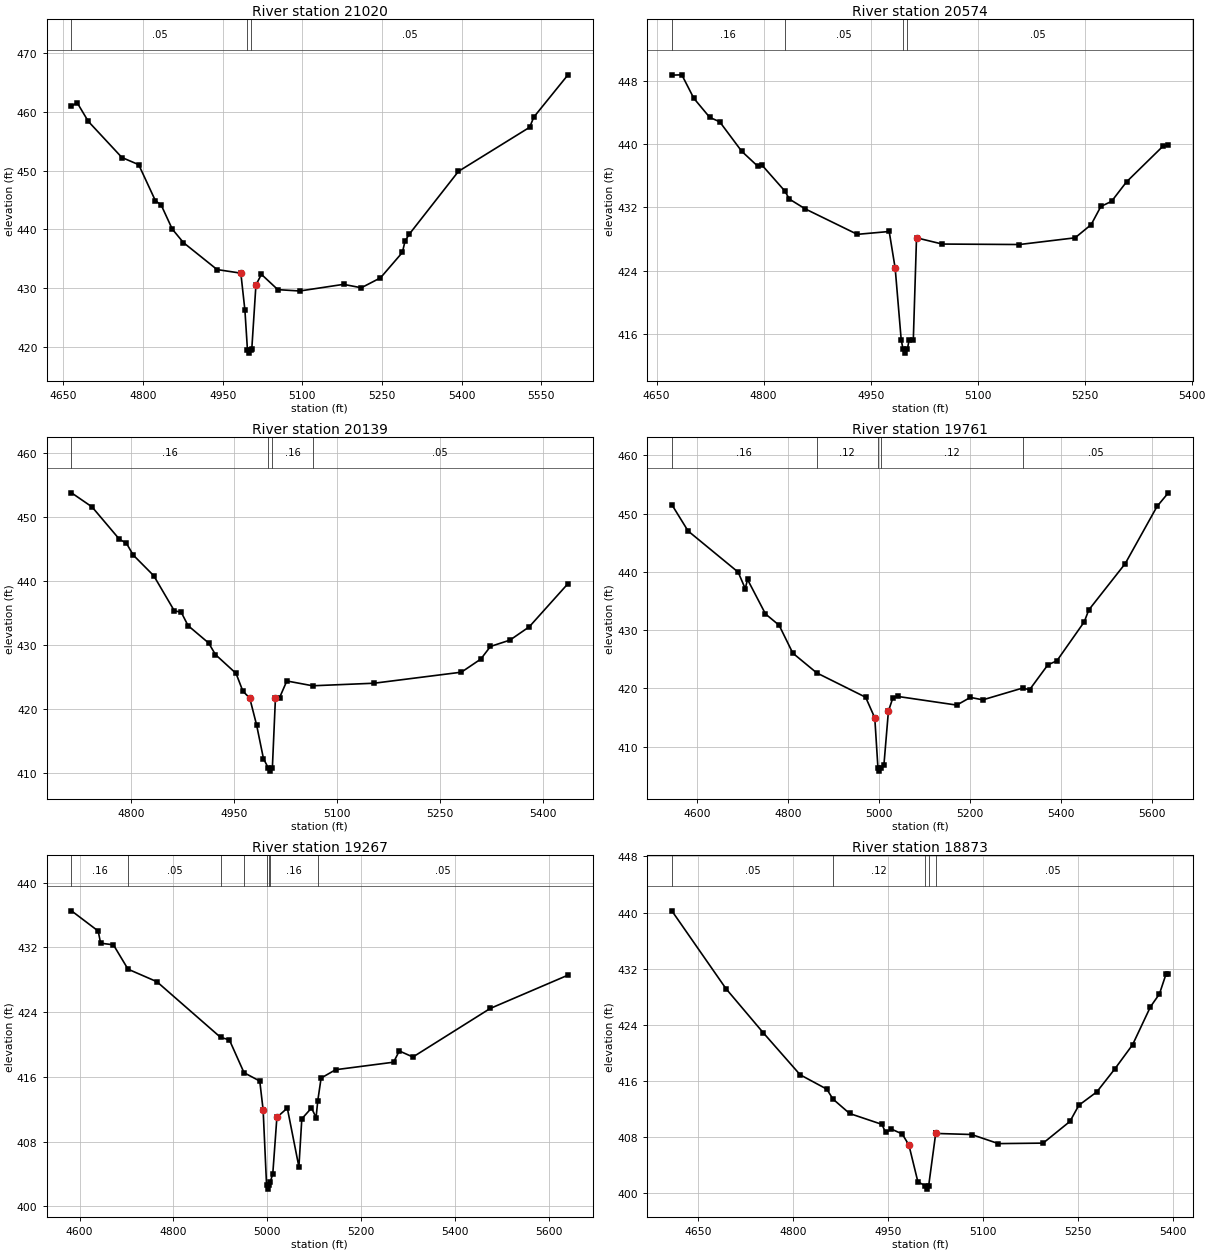
Type RM Length L Ch R = 1 ,21020   ,446,446,446
BEGIN DESCRIPTION:
WILLOW SLOUGH 45.0
END DESCRIPTION:
XS GIS Cut Line= 3
      3756499.62     10623210.19      3756199.61     10623110.19
      3755599.61     10623260.19
#Sta/Elev= 30
  4665.4     461    4676  461.61    4697  458.42  4760.3  452.26  4791.9  451.04
  4823.5  444.87  4834.1  444.19  4855.1  440.06  4876.2  437.75  4939.5  433.16
  4984.2  432.55  4991.9   426.2  4996.7  419.42  4999.4  418.92  5002.7  419.42
  5004.8  419.59  5012.6  430.52  5022.9  432.35  5053.8  429.74    5095  429.51
  5177.5  430.64    5211  430.06  5247.1  431.75  5288.3  436.08  5293.4  438.04
  5301.2  439.18  5393.9   449.9  5527.9  457.41  5535.7  459.14  5600.1  466.35
#Mann= 3 ,-1 , 0
  4665.4     .05       0  4996.7     .03       0  5002.7     .05       0
Bank Sta=4984.2,5012.6
XS Rating Curve= 0 ,0
Exp/Cntr=0.3,0.1

Type RM Length L Ch R = 1 ,20574   ,435,435,435
BEGIN DESCRIPTION:
WILLOW SLOUGH 44.0
END DESCRIPTION:
XS GIS Cut Line= 3
      3756299.64     10622560.17      3755999.61     10622710.19
      3755699.61     10622910.19
#Sta/Elev= 30
  4671.3  448.76  4685.3   448.8  4702.1  445.83  4724.4  443.41  4738.4  442.85
  4769.2  439.12  4791.5  437.24  4797.1  437.42  4829.5   434.1  4836.2  433.05
  4858.6   431.8  4931.3  428.59    4976  428.95  4984.4  424.28  4992.8  415.26
  4995.4  414.04  4998.1  413.54  5001.4  414.04    5004   415.2  5009.8   415.2
  5014.3  428.15  5050.3  427.36  5158.5   427.3  5236.6  428.15  5259.1  429.82
  5272.7  432.12  5287.7  432.77  5308.7  435.24  5359.8  439.76  5367.3  439.88
#Mann= 4 ,-1 , 0
  4671.3     .16       0  4829.5     .05       0  4995.4     .03       0
  5001.4     .05       0
Bank Sta=4984.4,5014.3
XS Rating Curve= 0 ,0
Exp/Cntr=0.3,0.1

Type RM Length L Ch R = 1 ,20139   ,378,378,378
BEGIN DESCRIPTION:
WILLOW SLOUGH 43.0
END DESCRIPTION:
XS GIS Cut Line= 3
      3756149.58     10622310.19      3755849.61     10622310.19
      3755549.63     10622610.17
#Sta/Elev= 30
  4712.9  453.72  4742.9  451.52  4782.9  446.47  4792.9  445.88  4802.9  444.03
  4832.9   440.8  4862.9  435.33  4872.9  435.12  4882.9  433.03  4912.9  430.32
  4922.9  428.51  4952.9  425.58  4962.9  422.81  4972.9  421.73  4982.9  417.54
  4992.9   412.3  4999.9  410.85  5002.6  410.35  5005.9  410.85  5010.4   421.8
  5016.4   421.8    5027   424.4  5064.6  423.65  5154.3  424.05  5281.6  425.77
  5309.9  427.81    5324  429.78  5352.3  430.76  5380.6  432.84  5437.1  439.57
#Mann= 4 ,-1 , 0
  4712.9     .16       0  4999.9     .07       0  5005.9     .16       0
  5064.6     .05       0
Bank Sta=4972.9,5010.4
XS Rating Curve= 0 ,0
Exp/Cntr=0.3,0.1

Type RM Length L Ch R = 1 ,19761   ,494,494,494
BEGIN DESCRIPTION:
Mapping XS bbccaee5
END DESCRIPTION:
XS GIS Cut Line= 2
      3756155.24     10622004.46      3755064.93     10621941.96
#Sta/Elev= 30
  4543.7  451.56  4579.4  447.04  4689.6  439.97  4705.2  437.13  4710.2  438.71
  4749.7  432.79  4779.7  430.85  4809.8  426.06  4862.4  422.67    4970  418.49
  4990.1  414.94  4997.1   406.3  4999.8   405.8  5003.1   406.3  5010.1  406.77
  5020.1   416.1  5030.1  418.43  5040.1  418.63  5170.4  417.14  5200.4  418.46
  5227.7  418.04  5315.1  420.06  5330.6  419.78  5370.7  424.04  5390.7  424.75
  5450.8  431.43  5460.8  433.48    5541  441.44  5611.1  451.27  5635.8  453.59
#Mann= 5 ,-1 , 0
  4543.7     .16       0  4862.4     .12       0  4997.1     .07       0
  5003.1     .12       0  5315.1     .05       0
Bank Sta=4990.1,5020.1
XS Rating Curve= 0 ,0
Exp/Cntr=0.3,0.1

Type RM Length L Ch R = 1 ,19267   ,394,394,394
BEGIN DESCRIPTION:
Mapping XS a932f2eb
END DESCRIPTION:
XS GIS Cut Line= 2
      3756266.38     10621629.47      3755238.55     10621379.46
#Sta/Elev= 30
  4582.9  436.53  4639.8  434.03  4644.9  432.53  4672.2  432.33  4703.3  429.32
  4764.8  427.77  4900.7  420.88  4919.2  420.59  4950.5  416.52    4984  415.49
  4991.2  411.91  4998.5  402.63  5001.3  402.13  5004.5  402.63  5006.7  403.06
  5011.8  404.06  5020.5     411  5042.7  412.15  5067.4  404.88  5073.6  410.82
  5094.2  412.16    5104  410.98  5107.6  413.06  5114.7  415.86  5145.6  416.89
  5269.1  417.82  5281.3  419.21  5310.3  418.46  5474.9  424.46  5640.7  428.58
#Mann= 8 ,-1 , 0
  4582.9     .16       0  4703.3     .05       0  4900.7     .16       0
  4950.5     .12       0  4998.5     .07       0  5004.5     .12       0
  5006.7     .16       0  5107.6     .05       0
Bank Sta=4991.2,5020.5
XS Rating Curve= 0 ,0
Exp/Cntr=0.3,0.1

Type RM Length L Ch R = 1 ,18873   ,448,448,448
BEGIN DESCRIPTION:
WILLOW SLOUGH 40.0
END DESCRIPTION:
XS GIS Cut Line= 3
      3756349.63      10621410.2      3756049.61     10621210.19
      3755749.64     10620910.22
#Sta/Elev= 30
    4608  440.24  4693.7  429.11  4752.2  422.86  4810.8  416.83  4852.9  414.78
  4862.7  413.36    4889   411.3    4940  409.75    4946  408.59  4955.1  409.07
  4972.1  408.38  4982.7   406.8  4996.9  401.55    5008     401  5010.8   400.5
    5014     401  5025.1  408.46  5026.1  408.45  5081.7   408.3  5124.1     407
  5194.9  407.07  5237.3  410.17  5251.4  412.48  5279.7  414.38    5308  417.64
  5336.3  421.12  5364.6  426.55  5378.7  428.36  5389.3  431.25  5392.8  431.25
#Mann= 5 ,-1 , 0
    4608     .05       0  4862.7     .12       0    5008     .07       0
    5014     .12       0  5026.1     .05       0
Bank Sta=4982.7,5025.1
XS Rating Curve= 0 ,0
Exp/Cntr=0.3,0.1

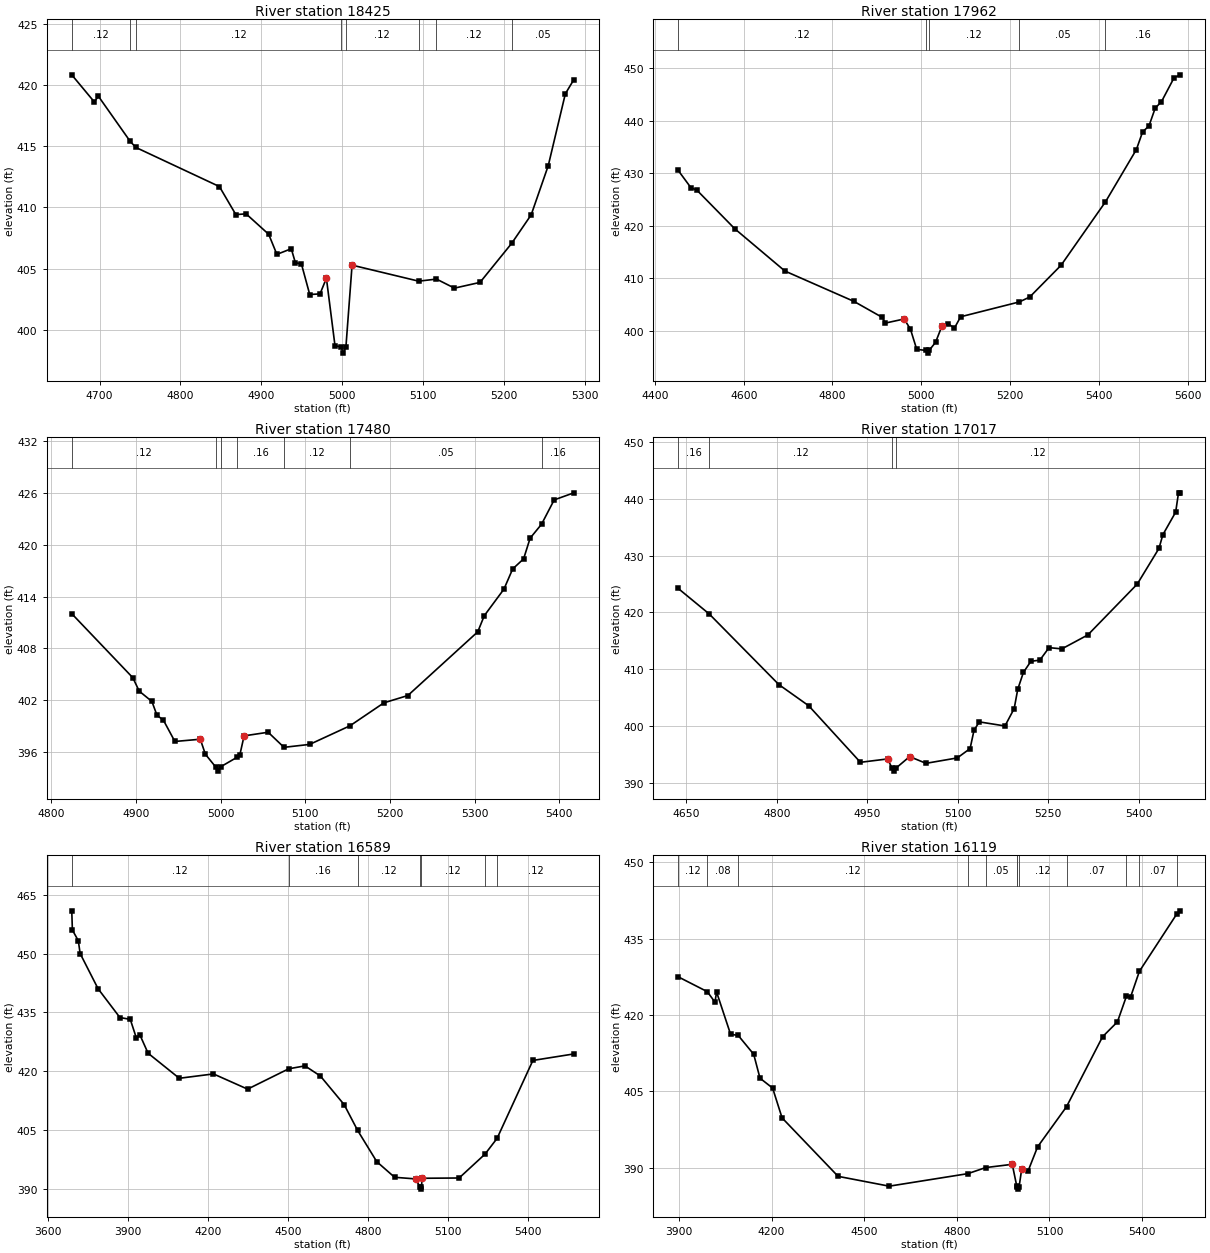
Type RM Length L Ch R = 1 ,18425   ,463,463,463
BEGIN DESCRIPTION:
WILLOW SLOUGH 39.0
END DESCRIPTION:
XS GIS Cut Line= 3
      3756499.57     10620860.18      3756199.61     10620810.19
      3755899.64      10620710.2
#Sta/Elev= 30
  4665.7  420.84  4693.5  418.63  4698.6  419.09  4737.8  415.41  4744.8  414.91
  4848.1  411.71  4868.4  409.42  4881.1  409.48    4909  407.81  4919.1  406.17
  4936.9  406.63  4941.9   405.5  4949.5  405.37  4959.7  402.89  4972.4  402.94
  4980.3  404.22  4990.9  398.71  4998.4   398.6  5001.2   398.1  5004.4   398.6
    5012  405.29  5094.3  403.98  5116.3  404.15  5138.5  403.41  5170.1  403.88
  5209.2  407.07  5233.3   409.4  5254.4  413.42  5275.5  419.29    5286  420.45
#Mann= 8 ,-1 , 0
  4665.7     .12       0  4737.8     .05       0  4744.8     .12       0
  4998.4     .07       0  5004.4     .12       0  5094.3     .16       0
  5116.3     .12       0  5209.2     .05       0
Bank Sta=4980.3,5012
XS Rating Curve= 0 ,0
Exp/Cntr=0.3,0.1

Type RM Length L Ch R = 1 ,17962   ,482,482,482
BEGIN DESCRIPTION:
WILLOW SLOUGH 38.0
END DESCRIPTION:
XS GIS Cut Line= 3
      3756649.63     10620760.21      3756249.61     10620360.19
      3755849.61     10619960.19
#Sta/Elev= 30
  4452.4  430.52  4480.7  427.28  4494.9  426.74  4579.7  419.45  4692.8  411.41
  4848.4  405.64    4912  402.61  4919.1  401.52  4961.5   402.3  4975.7  400.35
  4989.8  396.53  5011.6  396.31  5014.3  395.81  5017.6  396.31  5032.3  397.87
  5046.4  400.91  5060.5  401.41  5074.7  400.56  5088.8  402.72    5221  405.54
  5244.4  406.47  5315.1  412.51  5415.2  424.57  5484.8   434.5  5498.9  437.87
  5513.1  438.97  5527.2  442.37  5541.4  443.61  5569.7  448.14  5583.8   448.7
#Mann= 5 ,-1 , 0
  4452.4     .12       0  5011.6     .07       0  5017.6     .12       0
    5221     .05       0  5415.2     .16       0
Bank Sta=4961.5,5046.4
XS Rating Curve= 0 ,0
Exp/Cntr=0.3,0.1

Type RM Length L Ch R = 1 ,17480   ,463,463,463
BEGIN DESCRIPTION:
WILLOW SLOUGH 37.0
END DESCRIPTION:
XS GIS Cut Line= 3
      3756549.59     10620060.17      3756399.61     10619960.19
      3755999.57     10619860.18
#Sta/Elev= 30
  4824.4  412.01  4896.5  404.58    4904  403.03    4919  401.83    4925  400.22
  4932.5  399.67  4946.1  397.19  4976.1  397.45  4982.1  395.71  4994.1  394.25
  4996.9  393.75  5000.1  394.25  5019.9  395.38  5022.7   395.6  5027.8  397.84
  5056.2  398.26  5074.9  396.51  5105.2  396.85  5152.8  399.01  5192.8  401.67
  5221.1  402.52  5303.6  409.91  5311.3  411.78  5334.5  414.86  5344.8   417.2
  5357.7  418.37  5365.4  420.77  5378.9  422.39  5393.8  425.21    5417  426.03
#Mann= 7 ,-1 , 0
  4824.4     .12       0  4994.1     .07       0  5000.1     .12       0
  5019.9     .16       0  5074.9     .12       0  5152.8     .05       0
  5378.9     .16       0
Bank Sta=4976.1,5027.8
XS Rating Curve= 0 ,0
Exp/Cntr=0.3,0.1

Type RM Length L Ch R = 1 ,17017   ,428,428,428
BEGIN DESCRIPTION:
WILLOW SLOUGH 36.0
END DESCRIPTION:
XS GIS Cut Line= 3
      3756799.61     10619760.19      3756499.61     10619560.19
      3756099.57     10619310.17
#Sta/Elev= 30
  4636.7  424.21  4688.1  419.73  4803.5  407.33    4853  403.61  4938.7  393.68
  4983.7  394.27  4991.3  392.63    4994  392.13  4997.3  392.63  5020.3  394.68
  5047.4   393.5  5099.3  394.45  5120.5  396.09    5127   399.3  5135.8  400.78
  5178.3  400.06  5193.6  403.12  5199.5   406.5  5208.9  409.47  5221.3  411.42
  5236.1  411.62  5251.4  413.82  5272.6   413.6  5315.7  416.05  5397.6  424.98
  5433.6  431.25  5440.1  433.66  5461.3  437.62    5466  441.01    5469  441.01
#Mann= 4 ,-1 , 0
  4636.7     .16       0  4688.1     .12       0  4991.3     .07       0
  4997.3     .12       0
Bank Sta=4983.7,5020.3
XS Rating Curve= 0 ,0
Exp/Cntr=0.3,0.1

Type RM Length L Ch R = 1 ,16589   ,470,470,470
BEGIN DESCRIPTION:
WILLOW SLOUGH 35.0
END DESCRIPTION:
XS GIS Cut Line= 3
      3757405.22     10620428.04      3756842.74     10619323.91
       3756259.4     10619060.01
#Sta/Elev= 30
  3690.7   460.9    3693  456.01  3715.2  453.27    3722  450.01  3789.3  441.01
  3870.9  433.68  3909.7  433.21    3932  428.56  3946.4  429.14  3976.4  424.57
  4093.2  418.18  4221.1  419.29  4348.9  415.41  4502.8   420.6  4563.7  421.34
  4621.3  418.76  4710.3  411.46  4760.9  404.86  4832.5   396.9  4899.2  392.92
    4979   392.5  4993.6   390.4  4996.3   389.9  4999.6   390.4  5002.1  392.67
  5140.7  392.74  5237.5  398.82  5282.8  402.85  5416.8  422.73  5570.1  424.39
#Mann= 7 ,-1 , 0
  3690.7     .12       0  4502.8     .16       0  4760.9     .12       0
  4993.6     .07       0  4999.6     .12       0  5237.5     .07       0
  5282.8     .12       0
Bank Sta=4979,5002.1
XS Rating Curve= 0 ,0
Exp/Cntr=0.3,0.1

Type RM Length L Ch R = 1 ,16119   ,317,317,317
BEGIN DESCRIPTION:
WILLOW SLOUGH 34.0
END DESCRIPTION:
XS GIS Cut Line= 3
      3757919.09     10619129.46      3756967.74     10618935.02
      3756328.89     10618789.19
#Sta/Elev= 30
  3897.6   427.5  3991.7  424.59  4016.6  422.52  4021.7  424.53  4067.1  416.23
  4091.9  415.99    4142   412.3  4162.4   407.6  4203.3  405.66  4233.9  399.81
  4415.4  388.33  4580.9   386.4  4835.8  388.86  4893.4  390.05  4979.5  390.69
    4994  386.45  4995.8  386.32  4998.5  385.82  5001.8  386.32  5010.3  389.83
  5030.8  389.38  5061.6  394.12  5155.3     402  5272.1  415.74  5320.2  418.66
  5349.2  423.67  5363.2  423.61  5391.4  428.59  5512.8  439.87  5523.9  440.46
#Mann= 12 ,-1 , 0
  3897.6     .12       0  3991.7     .08       0  4091.9     .12       0
  4835.8     .07       0  4893.4     .05       0    4994     .12       0
  4995.8     .07       0  5001.8     .12       0  5155.3     .07       0
  5349.2     .05       0  5391.4     .07       0  5512.8     .05       0
Bank Sta=4979.5,5010.3
XS Rating Curve= 0 ,0
Exp/Cntr=0.3,0.1

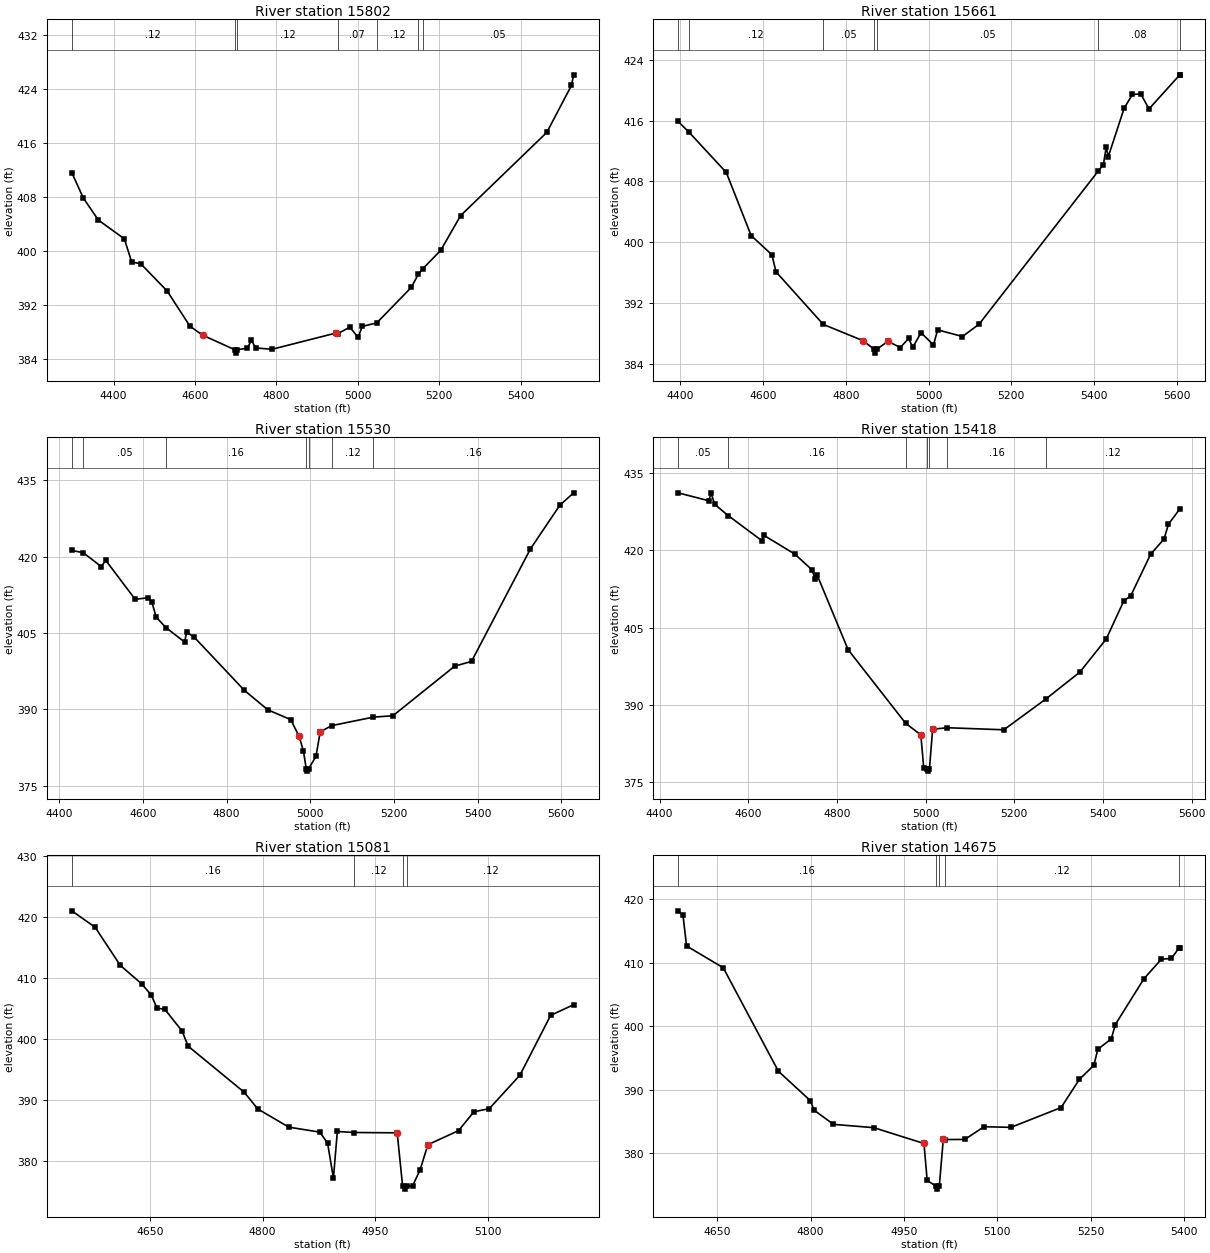
Type RM Length L Ch R = 1 ,15802   ,141,141,141
BEGIN DESCRIPTION:
Mapping XS becae3ad
END DESCRIPTION:
XS GIS Cut Line= 2
      3757697.76     10618743.18      3756474.22     10618595.66
#Sta/Elev= 30
  4297.5  411.62  4325.9  407.85  4362.7  404.59  4426.6   401.8  4444.7  398.37
  4466.9  398.11  4531.8  394.07  4587.7  388.86  4618.9  387.53    4698  385.37
  4700.7  384.87    4704  385.37  4728.8  385.61  4738.8  386.79  4748.9  385.64
  4789.2  385.44  4947.2  387.86  4950.2  387.75  4980.6  388.71  5000.7  387.19
  5010.8  388.83  5046.5  389.35  5131.6  394.63  5148.7  396.59  5159.8  397.39
  5203.4  400.09  5252.5  405.25    5464  417.57  5524.5  424.52  5529.9   426.1
#Mann= 7 ,-1 , 0
  4297.5     .12       0    4698     .07       0    4704     .12       0
  4950.2     .07       0  5046.5     .12       0  5148.7     .07       0
  5159.8     .05       0
Bank Sta=4618.9,4947.2
XS Rating Curve= 0 ,0
Exp/Cntr=0.3,0.1

Type RM Length L Ch R = 1 ,15661   ,131,131,131
BEGIN DESCRIPTION:
WILLOW SLOUGH 33.0
END DESCRIPTION:
XS GIS Cut Line= 2
      3757676.06     10618578.25      3756465.11     10618504.46
#Sta/Elev= 30
  4394.2  415.92  4420.8  414.48  4510.9  409.18    4571  400.87  4621.1  398.34
  4631.1  396.09  4745.4  389.16  4841.5  387.02  4868.5  385.88  4871.3  385.38
  4874.5  385.88  4901.6  386.93  4931.6  386.12  4951.7  387.31  4961.7  386.14
  4981.7  388.08  5011.8  386.45  5021.8  388.44  5081.9  387.57    5122  389.19
  5409.5  409.33  5422.6  410.21  5429.3  412.54  5434.3  411.25  5472.7  417.65
  5492.7  419.45  5512.7  419.53  5532.8  417.55  5607.2  422.04  5607.4  422.04
#Mann= 7 ,-1 , 0
  4394.2      .1       0  4420.8     .12       0  4745.4     .05       0
  4868.5     .04       0  4874.5     .05       0  5409.5     .08       0
  5607.2     .05       0
Bank Sta=4841.5,4901.6
XS Rating Curve= 0 ,0
Exp/Cntr=0.3,0.1

Type RM Length L Ch R = 1 ,15530   ,112,112,112
BEGIN DESCRIPTION:
Mapping XS 26580174
END DESCRIPTION:
XS GIS Cut Line= 2
      3757680.42     10618482.76      3756486.79     10618361.23
#Sta/Elev= 30
    4430  421.24  4457.3   420.8  4500.5  418.08  4511.2   419.3  4581.6  411.64
  4611.7  411.93  4621.8  411.02  4631.9  408.11  4655.4  406.06  4699.7  403.24
  4704.7  405.18  4722.3  404.23  4842.9  393.72  4898.9   389.9  4953.5  387.99
  4973.6  384.69  4983.7  381.86  4990.5  378.36  4993.3  377.86  4996.5  378.36
  5013.8  380.75  5023.9  385.59  5051.6  386.81  5150.6  388.47  5197.8  388.75
  5345.5   398.5  5385.7  399.43  5526.5  421.54  5596.8  430.13  5629.8  432.57
#Mann= 7 ,-1 , 0
    4430     .08       0  4457.3     .05       0  4655.4     .16       0
  4990.5     .07       0  4996.5     .16       0  5051.6     .12       0
  5150.6     .16       0
Bank Sta=4973.6,5023.9
XS Rating Curve= 0 ,0
Exp/Cntr=0.3,0.1

Type RM Length L Ch R = 1 ,15418   ,337,337,337
BEGIN DESCRIPTION:
Mapping XS c3d510c2
END DESCRIPTION:
XS GIS Cut Line= 2
      3757671.75     10618361.23      3756543.98     10618265.81
#Sta/Elev= 30
  4441.7  431.16  4511.2  429.62  4516.3  431.14  4524.1  428.95  4554.6  426.76
  4630.8  421.88  4635.8  422.89  4704.8  419.29  4744.9  416.14  4750.3   414.4
  4755.3  415.25  4825.2  400.74  4955.1  386.44  4989.3  384.19  4995.8  377.86
  5002.8  377.66  5005.6  377.16  5008.8  377.66  5015.9  385.29  5049.3  385.58
  5176.5  385.18  5271.3  391.16  5347.9  396.37  5407.3  402.78  5447.4  410.25
  5462.4  411.13  5507.6  419.25  5537.7   422.2  5547.8  425.08  5573.5  428.05
#Mann= 7 ,-1 , 0
  4441.7     .05       0  4554.6     .16       0  4955.1     .12       0
  5002.8     .07       0  5008.8     .12       0  5049.3     .16       0
  5271.3     .12       0
Bank Sta=4989.3,5015.9
XS Rating Curve= 0 ,0
Exp/Cntr=0.3,0.1

Type RM Length L Ch R = 1 ,15081   ,406,406,406
BEGIN DESCRIPTION:
WILLOW SLOUGH 32.0
END DESCRIPTION:
XS GIS Cut Line= 3
      3757449.64      10618210.2      3757049.61     10618110.19
       3756799.6     10618160.19
#Sta/Elev= 30
  4546.3  421.01  4577.3  418.33  4610.8  412.08  4639.1  409.07    4652  407.23
  4659.7  405.07    4670  404.89  4693.2  401.29  4700.9  398.86  4775.7  391.29
  4793.7  388.56  4834.9  385.59  4876.2  384.77  4886.5  382.95  4894.2  377.22
  4899.4  384.88  4922.2  384.71    4979  384.66  4986.2  375.94    4989  375.44
  4992.2  375.94  4999.4  375.95  5009.6  378.65  5019.8  382.71  5060.6  385.02
    5081  388.11  5101.4  388.61  5142.2   394.1    5183  403.89  5213.6  405.64
#Mann= 4 ,-1 , 0
  4546.3     .16       0  4922.2     .12       0  4986.2     .07       0
  4992.2     .12       0
Bank Sta=4979,5019.8
XS Rating Curve= 0 ,0
Exp/Cntr=0.3,0.1

Type RM Length L Ch R = 1 ,14675   ,465,465,465
BEGIN DESCRIPTION:
WILLOW SLOUGH 31.0
END DESCRIPTION:
XS GIS Cut Line= 3
      3757499.64      10617960.2      3757149.61     10617760.19
      3756799.57     10617960.21
#Sta/Elev= 30
  4587.1  418.17  4595.1  417.48  4600.8  412.65  4659.8  409.21  4748.4  392.93
  4799.5  388.32    4806  386.78  4836.9  384.57  4901.7  384.05  4982.3  381.56
  4987.4  375.76  5000.9  374.88  5003.7  374.38  5006.9  374.88  5013.3  382.22
  5015.7  382.18  5047.8   382.2  5078.8   384.2    5122   384.1  5202.6  387.22
  5232.1  391.67  5255.1  393.85  5261.6  396.39  5283.2  398.02  5289.7  400.28
  5335.8   407.5  5363.8  410.57  5379.7  410.67  5391.7  412.28  5393.4  412.28
#Mann= 5 ,-1 , 0
  4587.1     .16       0  5000.9     .07       0  5006.9     .16       0
  5015.7     .12       0  5391.7     .16       0
Bank Sta=4982.3,5013.3
XS Rating Curve= 0 ,0
Exp/Cntr=0.3,0.1

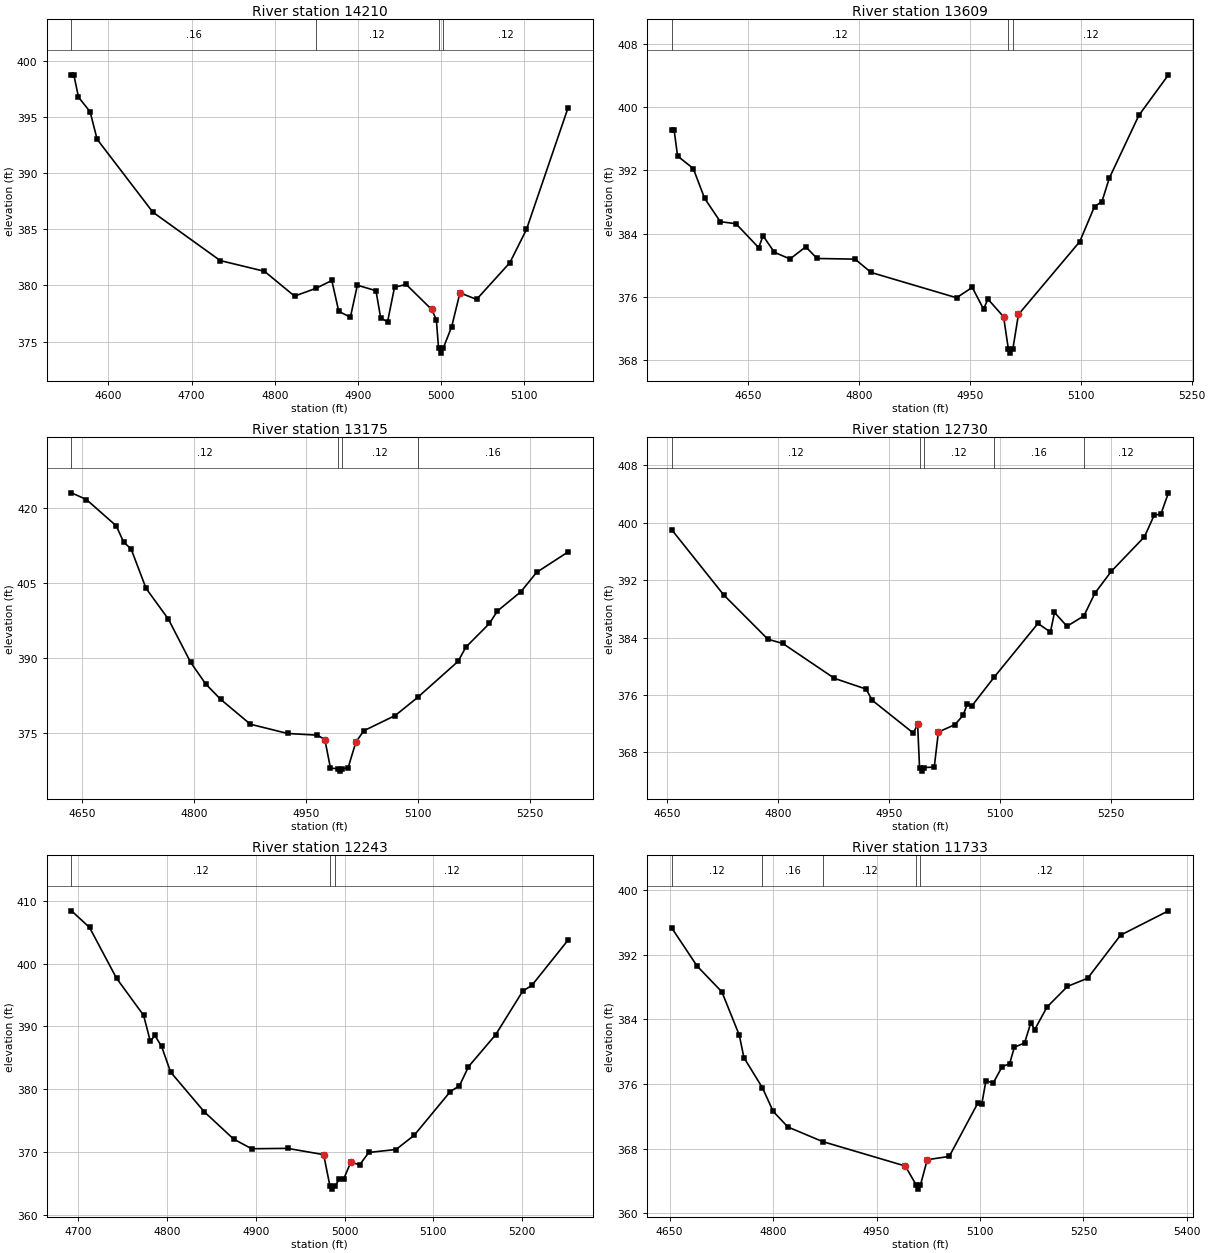
Type RM Length L Ch R = 1 ,14210   ,601,601,601
BEGIN DESCRIPTION:
WILLOW SLOUGH 30.0
END DESCRIPTION:
XS GIS Cut Line= 3
      3757449.62     10617160.18      3757049.61     10617360.19
      3756899.63     10617360.19
#Sta/Elev= 30
  4555.6  398.73  4558.4  398.73    4564  396.75    4578  395.44  4586.4     393
  4653.4  386.52  4734.5  382.21  4787.6  381.26  4823.9  379.05  4849.5  379.74
  4868.7  380.44    4877   377.7    4891  377.17  4899.4  380.02  4921.8  379.53
  4927.4  377.13  4935.7  376.75  4944.1  379.84  4958.1  380.09  4988.8  377.86
  4994.4  376.95    4997  374.48  4999.8  373.98    5003  374.48  5012.8  376.32
  5022.8  379.34  5042.8  378.76  5082.8  382.02  5102.8  384.98  5152.8   395.8
#Mann= 4 ,-1 , 0
  4555.6     .16       0  4849.5     .12       0    4997     .07       0
    5003     .12       0
Bank Sta=4988.8,5022.8
XS Rating Curve= 0 ,0
Exp/Cntr=0.3,0.1

Type RM Length L Ch R = 1 ,13609   ,434,434,434
BEGIN DESCRIPTION:
WILLOW SLOUGH 29.0
END DESCRIPTION:
XS GIS Cut Line= 3
      3757349.65     10616710.17      3756949.61     10616960.19
      3756749.65     10616960.19
#Sta/Elev= 30
  4546.8  397.11  4549.8  397.11  4554.5  393.81  4575.7  392.23  4591.1  388.45
  4612.3   385.5  4633.5  385.24  4664.2  382.21  4670.1  383.71  4685.4  381.63
  4706.6  380.78  4727.9  382.32  4743.2  380.84  4794.5  380.76  4816.3  379.07
  4931.9  375.87  4953.1  377.18  4968.4  374.44  4974.3   375.7  4995.5  373.46
    5002  369.36  5004.7  368.86    5008  369.36  5015.6  373.75  5098.5  382.97
  5118.5  387.42  5128.5  388.03  5138.5  391.01  5178.5  398.96  5218.5  404.09
#Mann= 3 ,-1 , 0
  4546.8     .12       0    5002     .07       0    5008     .12       0
Bank Sta=4995.5,5015.6
XS Rating Curve= 0 ,0
Exp/Cntr=0.3,0.1

Type RM Length L Ch R = 1 ,13175   ,445,445,445
BEGIN DESCRIPTION:
WILLOW SLOUGH 28.0
END DESCRIPTION:
XS GIS Cut Line= 3
      3757449.63     10616560.19      3757099.61     10616560.19
      3756799.56      10616660.2
#Sta/Elev= 30
  4635.4  422.98  4655.4  421.64  4695.4  416.39  4705.4  413.13  4715.4  411.77
  4735.4  403.91  4765.4  397.75  4795.4  389.09  4815.4  384.82  4835.4  381.75
  4875.4  376.76  4925.4  374.91  4965.4  374.57  4975.4  373.69  4982.9  367.97
    4993  367.89  4995.7  367.39    4999  367.89  5006.5  368.03    5017  373.18
  5027.6  375.45  5069.8   378.5    5100  382.13  5154.1  389.31  5164.6  392.16
  5196.2  396.88  5206.8  399.36  5238.4  403.22  5259.5  407.09  5301.7  411.17
#Mann= 4 ,-1 , 0
  4635.4     .12       0    4993     .07       0    4999     .12       0
    5100     .16       0
Bank Sta=4975.4,5017
XS Rating Curve= 0 ,0
Exp/Cntr=0.3,0.1

Type RM Length L Ch R = 1 ,12730   ,487,487,487
BEGIN DESCRIPTION:
WILLOW SLOUGH 27.0
END DESCRIPTION:
XS GIS Cut Line= 3
      3757339.46     10616179.01      3757079.01     10616183.35
      3756710.53     10616365.42
#Sta/Elev= 30
    4656  398.99  4725.9  389.96  4785.9  383.76  4805.9  383.18  4875.9  378.31
  4918.6  376.82    4927  375.25  4982.7  370.68  4988.3  371.95  4990.9  365.89
  4993.7  365.39  4996.9  365.89  5010.8  365.95  5016.4  370.84  5038.8  371.87
  5049.7  373.15  5055.7   374.8  5061.2  374.41  5091.6  378.45    5151  385.96
  5167.9  384.77  5173.4   387.5  5190.3  385.57  5213.2  387.02  5228.1  390.19
  5250.4  393.24  5295.1  398.04  5308.1  401.02  5317.4  401.23  5327.5  404.16
#Mann= 5 ,-1 , 0
    4656     .12       0  4990.9     .07       0  4996.9     .12       0
  5091.6     .16       0  5213.2     .12       0
Bank Sta=4988.3,5016.4
XS Rating Curve= 0 ,0
Exp/Cntr=0.3,0.1

Type RM Length L Ch R = 1 ,12243   ,510,510,510
BEGIN DESCRIPTION:
WILLOW SLOUGH 26.0
END DESCRIPTION:
XS GIS Cut Line= 3
      3757199.66      10615910.2      3756899.61     10615860.19
      3756649.64      10615810.2
#Sta/Elev= 30
  4692.6  408.44  4712.9  405.79  4743.3  397.69  4773.8  391.77  4781.4   387.6
  4786.4  388.57    4794  386.83  4804.2  382.72  4842.2  376.37  4875.1  372.04
  4895.4  370.49    4936  370.55  4976.5  369.55  4983.6  364.55  4986.4  364.05
  4989.6  364.55  4994.3  365.74  4999.3  365.74    5007  368.31  5017.2  367.95
  5027.4   369.9    5058  370.37  5078.4  372.63  5119.2  379.62  5129.4  380.53
  5139.6  383.58  5170.2  388.68  5200.7  395.64  5210.9  396.54  5251.7  403.77
#Mann= 3 ,-1 , 0
  4692.6     .12       0  4983.6     .07       0  4989.6     .12       0
Bank Sta=4976.5,5007
XS Rating Curve= 0 ,0
Exp/Cntr=0.3,0.1

Type RM Length L Ch R = 1 ,11733   ,457,457,457
BEGIN DESCRIPTION:
WILLOW SLOUGH 25.0
END DESCRIPTION:
XS GIS Cut Line= 3
      3757087.72     10615302.26      3756644.99     10615462.86
      3756549.51     10615692.87
#Sta/Elev= 30
  4653.3  395.28  4689.9  390.59  4725.8   387.4  4751.1  382.03  4757.7  379.27
  4784.6  375.53  4800.2  372.61  4821.5  370.68    4872  368.87  4991.7  365.85
  5007.7  363.49  5010.5  362.99  5013.7  363.49  5023.6  366.63  5055.5  367.04
  5097.3   373.7  5102.6  373.48  5108.7  376.43  5119.1   376.1  5132.2  378.15
    5143  378.51  5149.9  380.55  5164.7  381.08  5173.8   383.6  5179.2   382.7
  5197.2  385.52  5226.9  388.08  5256.2  389.09  5303.9  394.42  5373.3  397.43
#Mann= 5 ,-1 , 0
  4653.3     .12       0  4784.6     .16       0    4872     .12       0
  5007.7     .07       0  5013.7     .12       0
Bank Sta=4991.7,5023.6
XS Rating Curve= 0 ,0
Exp/Cntr=0.3,0.1

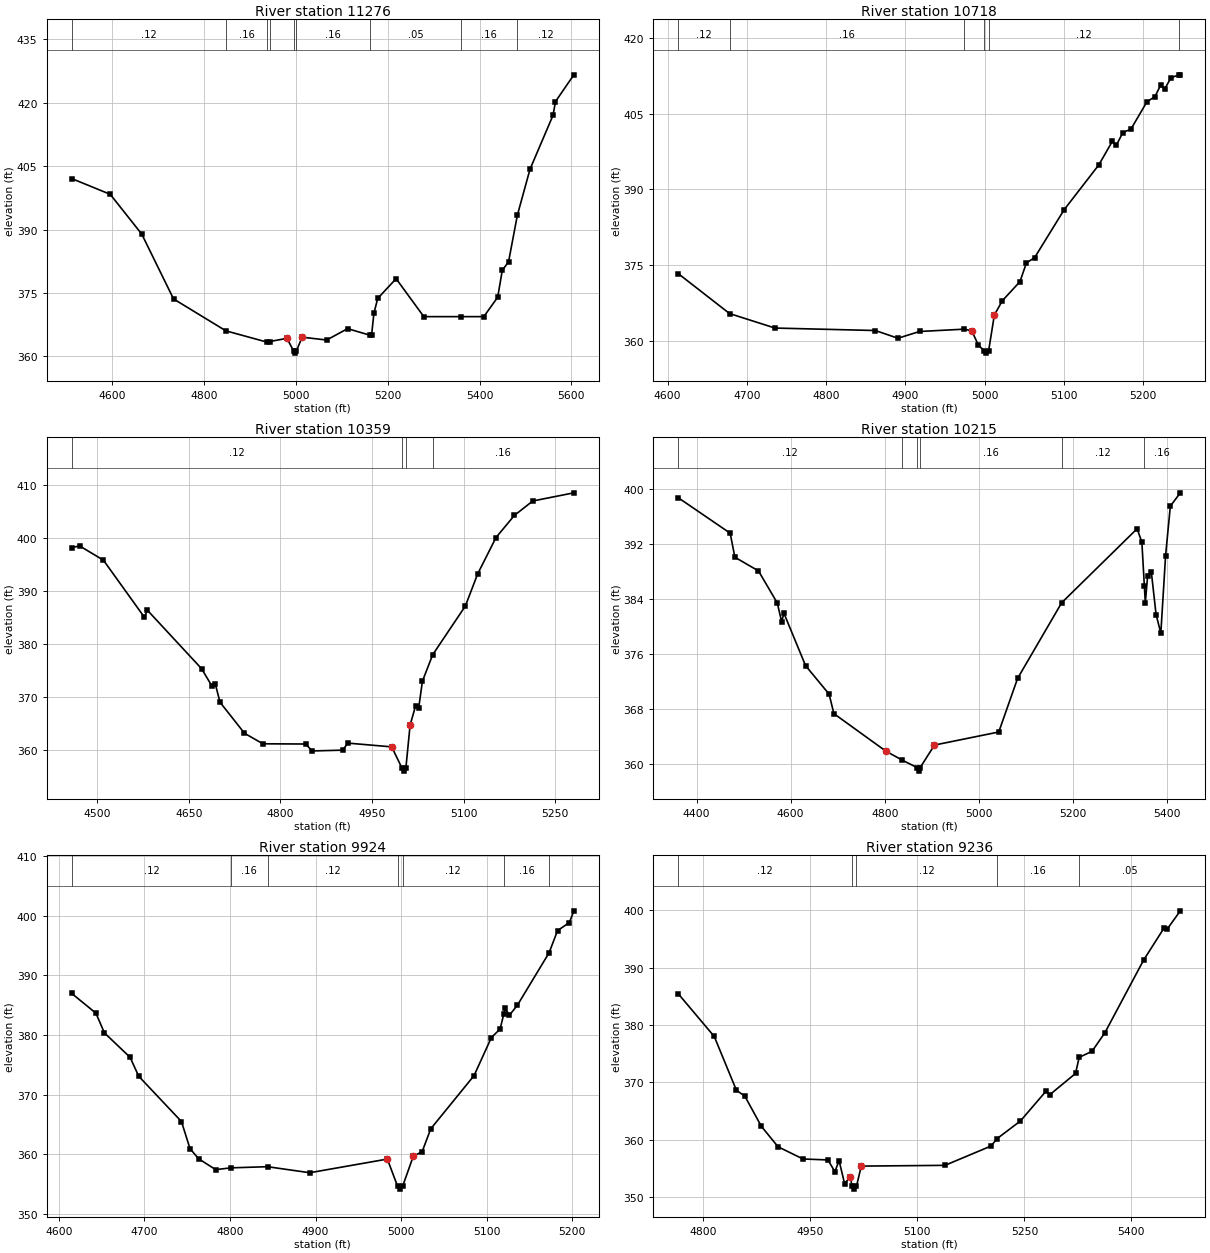
Type RM Length L Ch R = 1 ,11276   ,558,558,558
BEGIN DESCRIPTION:
WILLOW SLOUGH 24.0
END DESCRIPTION:
XS GIS Cut Line= 3
      3757085.77     10614823.05       3756485.1     10615097.34
      3756054.55     10615139.01
#Sta/Elev= 30
  4512.4  402.07  4596.1  398.35  4664.8  388.93  4733.9  373.61  4847.9  366.06
  4937.9  363.38  4943.3  363.53  4980.9  364.29  4995.2  361.29    4998  360.79
  5001.2  361.29  5013.9  364.56  5067.3  363.89  5112.8  366.58  5161.1  365.04
  5164.9  364.96  5170.1   370.2  5178.3  373.72  5218.4   378.4  5278.7  369.42
  5360.1  369.42  5409.3  369.42  5439.5     374  5449.5  380.36  5463.2   382.4
  5482.3  393.39  5509.8  404.26    5560  417.05  5565.3  420.28  5605.3  426.61
#Mann= 9 ,-1 , 0
  4512.4     .12       0  4847.9     .16       0  4937.9     .12       0
  4943.3     .16       0  4995.2     .07       0  5001.2     .16       0
  5161.1     .05       0  5360.1     .16       0  5482.3     .12       0
Bank Sta=4980.9,5013.9
XS Rating Curve= 0 ,0
Exp/Cntr=0.3,0.1

Type RM Length L Ch R = 1 ,10718   ,359,359,359
BEGIN DESCRIPTION:
WILLOW SLOUGH 23.0
END DESCRIPTION:
XS GIS Cut Line= 2
      3756723.15      10614594.8      3756098.07     10614698.98
#Sta/Elev= 30
  4613.4  373.27  4678.2  365.35  4735.5  362.48  4862.2  361.99  4890.7  360.46
    4918   361.8  4974.5  362.26  4983.9  361.93  4992.1  359.13  4999.2  358.01
    5002  357.51  5005.2  358.01  5012.4  365.07  5022.5   367.9  5044.7  371.68
  5052.9  375.41  5063.1  376.41  5100.5  385.94  5144.2  394.81  5161.3  399.49
  5166.4  398.73  5174.6  401.23  5184.7  401.89    5205  407.33  5215.1  408.36
  5222.1  410.57  5227.2  409.83  5235.4   412.1  5245.6  412.67  5247.1  412.67
#Mann= 6 ,-1 , 0
  4613.4     .12       0  4678.2     .16       0  4974.5     .12       0
  4999.2     .07       0  5005.2     .12       0  5245.6     .16       0
Bank Sta=4983.9,5012.4
XS Rating Curve= 0 ,0
Exp/Cntr=0.3,0.1

Type RM Length L Ch R = 1 ,10359   ,144,144,144
BEGIN DESCRIPTION:
WILLOW SLOUGH 22.0
END DESCRIPTION:
XS GIS Cut Line= 2
      3756801.22     10614334.39      3755982.72     10614408.01
#Sta/Elev= 30
  4458.6  398.26  4471.4  398.59  4510.4  395.89  4577.4  385.13  4582.4  386.44
  4671.1   375.4  4688.4  372.05  4693.4  372.58  4701.2  369.08  4741.3  363.21
  4771.5  361.22  4841.7  361.18  4851.8  359.87    4902  360.02  4910.5  361.35
  4982.3  360.64  4999.4  356.56  5002.1  356.06  5005.4  356.56  5012.4  364.77
  5021.5  368.44  5026.5  368.01  5032.5  373.02  5049.3  378.03  5102.8  387.23
  5122.9  393.28    5153  400.17  5183.1  404.35  5213.2  407.07  5280.4  408.61
#Mann= 4 ,-1 , 0
  4458.6     .12       0  4999.4     .07       0  5005.4     .12       0
  5049.3     .16       0
Bank Sta=4982.3,5012.4
XS Rating Curve= 0 ,0
Exp/Cntr=0.3,0.1

Type RM Length L Ch R = 1 ,10215   ,291,291,291
BEGIN DESCRIPTION:
Mapping XS e857eaae
END DESCRIPTION:
XS GIS Cut Line= 6
      3756899.81     10614238.05      3756598.13     10614220.68
       3756346.4     10614235.87      3756114.19     10614244.55
      3755955.77     10614279.28      3755838.57     10614294.47
#Sta/Elev= 30
  4361.1  398.79  4471.5  393.63  4481.5  390.13  4531.6  388.15  4571.7  383.47
  4580.8  380.78  4585.8  381.98  4631.8  374.36  4681.8  370.22  4691.9  367.39
  4802.1  361.95  4835.7  360.68  4869.2  359.53  4871.9  359.03  4875.2  359.53
  4905.7  362.82  5042.3  364.72  5082.4  372.52  5176.1  383.52  5336.4  394.28
  5346.5  392.32  5351.8  385.93  5353.8  383.52  5358.8  387.44  5366.7  387.93
  5376.7   381.8  5386.8   379.1  5396.9  390.37    5407  397.57  5428.2   399.5
#Mann= 6 ,-1 , 0
  4361.1     .12       0  4835.7     .16       0  4869.2     .07       0
  4875.2     .16       0  5176.1     .12       0  5351.8     .16       0
Bank Sta=4802.1,4905.7
XS Rating Curve= 0 ,0
Exp/Cntr=0.3,0.1

Type RM Length L Ch R = 1 ,9924    ,688,688,688
BEGIN DESCRIPTION:
WILLOW SLOUGH 21.0
END DESCRIPTION:
XS GIS Cut Line= 3
      3756707.82     10614006.62      3756395.28     10614006.62
      3756124.51     10613962.36
#Sta/Elev= 30
    4615  386.96  4643.2  383.66  4653.2  380.35  4683.2  376.25  4693.2  373.09
  4743.2  365.49  4753.2  360.94  4763.2  359.25  4783.2  357.42  4801.2  357.72
  4843.8  357.91  4893.2   356.9  4983.9  359.19  4995.8  354.65  4998.5  354.15
  5001.8  354.65  5014.3   359.7  5024.5   360.4  5034.6  364.26  5085.3   373.2
  5105.5  379.57  5115.7     381    5120  383.51  5121.6  384.45  5126.6  383.31
  5135.9  384.99  5172.9  393.77  5182.9  397.51  5196.7  398.85  5201.9  400.82
#Mann= 7 ,-1 , 0
    4615     .12       0  4801.2     .16       0  4843.8     .12       0
  4995.8     .07       0  5001.8     .12       0    5120     .16       0
  5172.9     .05       0
Bank Sta=4983.9,5014.3
XS Rating Curve= 0 ,0
Exp/Cntr=0.3,0.1

Type RM Length L Ch R = 1 ,9236    ,435,435,435
BEGIN DESCRIPTION:
WILLOW SLOUGH 20.0
END DESCRIPTION:
XS GIS Cut Line= 3
      3756699.62     10613660.19      3756449.61     10613510.19
      3756049.58      10613610.2
#Sta/Elev= 30
  4764.7  385.43  4815.2  377.99  4846.3  368.61    4858  367.62  4881.3  362.33
  4904.7  358.78  4939.6  356.66  4974.6  356.49  4984.3  354.45  4990.2  356.37
  4997.9  352.38  5005.7   353.5  5008.6  351.91  5011.3  351.41  5014.6  351.91
  5021.3  355.42  5138.7  355.55  5203.1  358.91  5211.9  360.22  5244.4  363.27
  5280.4  368.48  5285.6  367.85  5321.7  371.55  5326.8  374.35  5344.9  375.42
  5362.9  378.65    5417  391.26  5445.4   396.8  5450.5  396.74  5468.6  399.87
#Mann= 5 ,-1 , 0
  4764.7     .12       0  5008.6     .07       0  5014.6     .12       0
  5211.9     .16       0  5326.8     .05       0
Bank Sta=5005.7,5021.3
XS Rating Curve= 0 ,0
Exp/Cntr=0.3,0.1