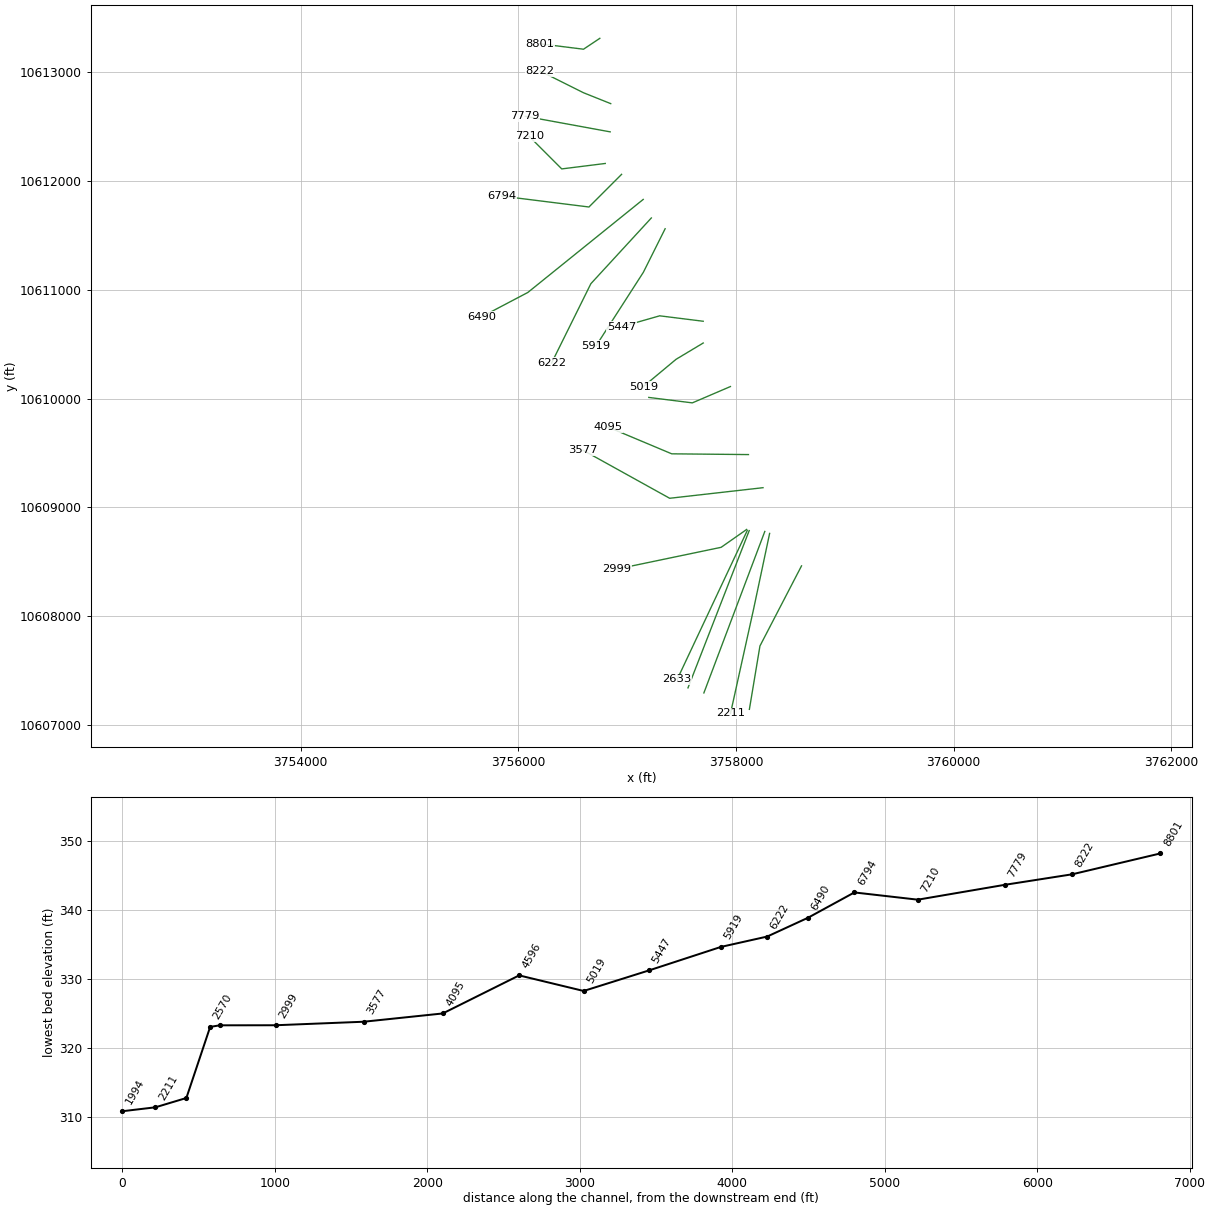
HEC-RAS study WILLOW SLOUGH.prj: WILLOW SLOUGH Base Level Engineering

--- WILLOW SLOUGH.g01 (geometry) --- (continued)

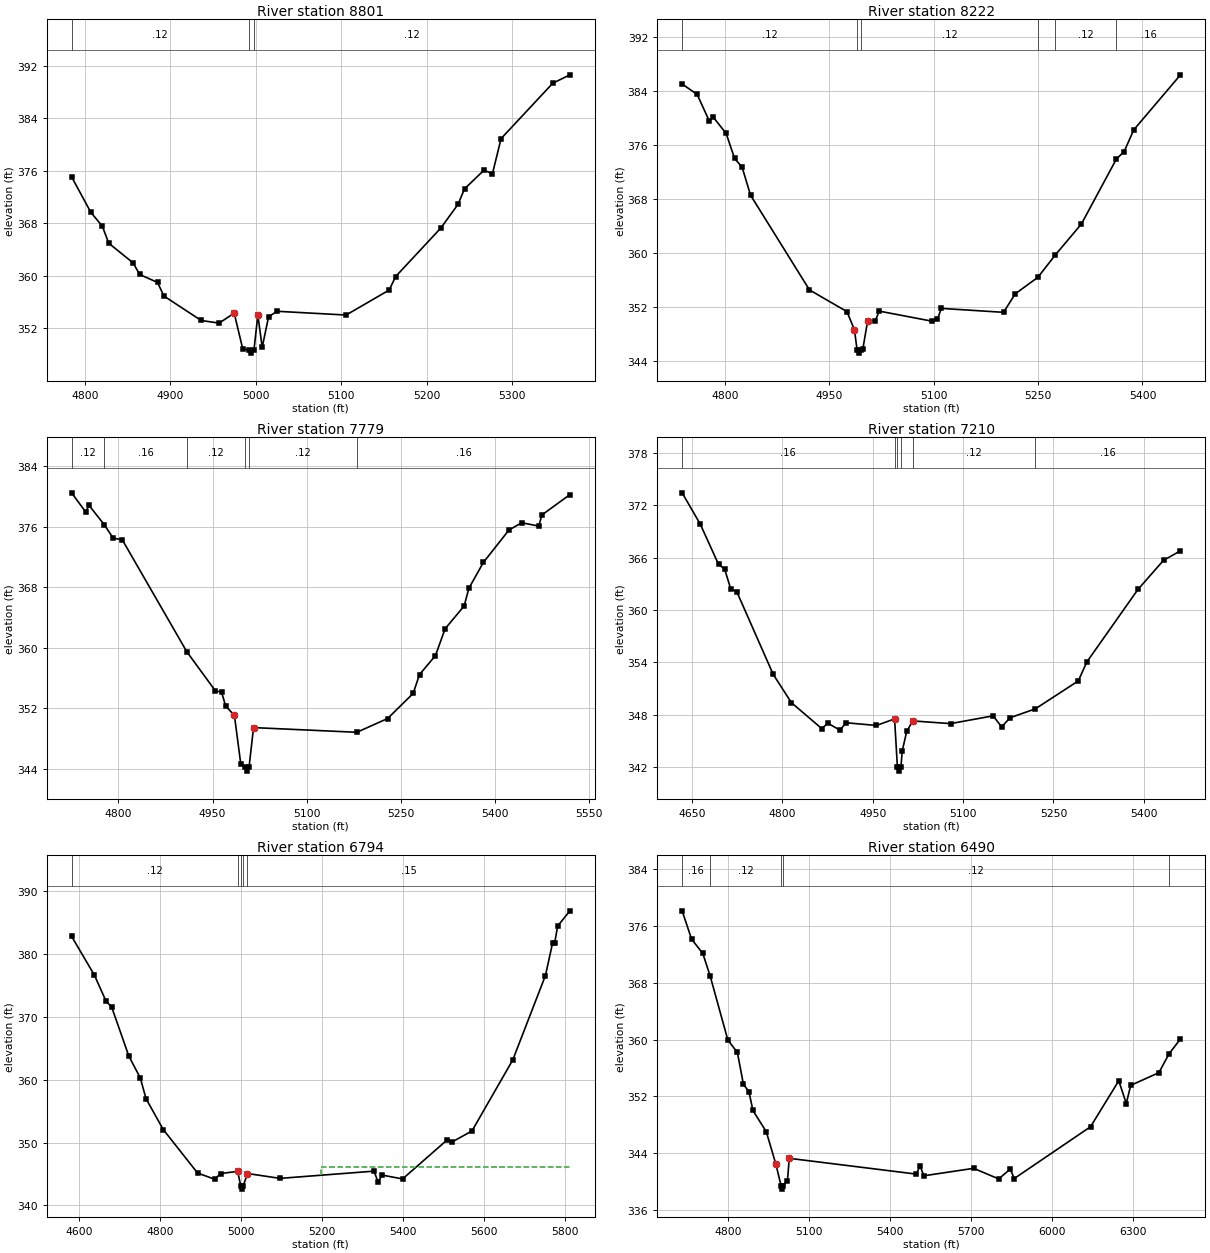
Type RM Length L Ch R = 1 ,8801    ,579,579,579
BEGIN DESCRIPTION:
WILLOW SLOUGH 19.0
END DESCRIPTION:
XS GIS Cut Line= 3
      3756749.57     10613310.16      3756599.61     10613210.19
      3756199.65     10613260.18
#Sta/Elev= 30
  4784.4  375.09  4806.9  369.69  4820.4  367.57  4827.9  364.98  4856.5  361.98
    4864  360.23    4885  359.01  4892.5  356.94  4936.1  353.22  4957.1  352.82
  4974.7  354.34  4984.8  348.86  4991.9  348.75  4994.6  348.25  4997.9  348.75
  5002.4  354.05  5007.5  349.14    5015   353.8  5025.1  354.62  5105.7  354.05
  5156.1  357.85  5163.7  359.91  5216.6   367.3  5236.7   370.9  5244.3  373.26
    5267  376.09    5277  375.57  5287.1  380.91  5347.6  389.34  5367.7  390.62
#Mann= 3 ,-1 , 0
  4784.4     .12       0  4991.9     .07       0  4997.9     .12       0
Bank Sta=4974.7,5002.4
XS Rating Curve= 0 ,0
Exp/Cntr=0.3,0.1

Type RM Length L Ch R = 1 ,8222    ,443,443,443
BEGIN DESCRIPTION:
WILLOW SLOUGH 18.0
END DESCRIPTION:
XS GIS Cut Line= 3
      3756849.64     10612710.18      3756599.61     10612810.19
      3756199.61     10613010.19
#Sta/Elev= 30
  4738.2  384.99  4759.8  383.45  4777.3  379.51  4782.7  380.13  4801.5  377.68
  4813.6  373.99  4824.4  372.71  4836.5  368.57  4921.3  354.56  4975.2  351.35
  4985.9  348.67  4989.7  345.72  4992.4  345.22  4995.7  345.72  4998.1  345.89
  5004.8  349.91  5015.9  349.99  5021.5  351.43  5096.9  349.95  5105.3  350.26
  5110.9  351.83  5200.3  351.25  5217.1  353.98  5249.7  356.43  5274.8  359.74
  5312.2   364.3  5362.5   373.9  5373.6     375  5387.6  378.23  5454.7  386.35
#Mann= 6 ,-1 , 0
  4738.2     .12       0  4989.7     .07       0  4995.7     .12       0
  5249.7     .16       0  5274.8     .12       0  5362.5     .16       0
Bank Sta=4985.9,5004.8
XS Rating Curve= 0 ,0
Exp/Cntr=0.3,0.1

Type RM Length L Ch R = 1 ,7779    ,569,569,569
BEGIN DESCRIPTION:
WILLOW SLOUGH 17.0
END DESCRIPTION:
XS GIS Cut Line= 2
      3756844.65     10612450.71      3756063.96     10612593.84
#Sta/Elev= 30
  4725.5  380.45  4748.1  377.91  4753.2   378.8  4777.5  376.25  4791.6  374.48
  4806.3  374.24  4909.1  359.45  4954.3  354.32  4964.5  354.11  4970.8  352.29
  4984.8  351.06    4995  344.61  5002.1  344.19  5004.9  343.69  5008.1  344.19
  5015.3  349.44  5179.8  348.82  5228.8  350.64  5269.5  353.95  5279.6  356.45
    5305  358.95  5320.3  362.48  5350.8  365.52  5358.1  367.82  5381.3  371.25
    5422  375.53  5442.3   376.5  5469.5  376.06  5474.6  377.53  5519.2  380.22
#Mann= 6 ,-1 , 0
  4725.5     .12       0  4777.5     .16       0  4909.1     .12       0
  5002.1     .07       0  5008.1     .12       0  5179.8     .16       0
Bank Sta=4984.8,5015.3
XS Rating Curve= 0 ,0
Exp/Cntr=0.3,0.1

Type RM Length L Ch R = 1 ,7210    ,416,416,416
BEGIN DESCRIPTION:
WILLOW SLOUGH 16.0
END DESCRIPTION:
XS GIS Cut Line= 3
      3756799.58     10612160.19      3756399.61     10612110.19
      3756099.64     10612410.15
#Sta/Elev= 30
  4633.6  373.41  4663.8  369.81    4694  365.22  4704.1  364.69  4714.2  362.42
  4724.3  362.09  4784.7  352.63    4815  349.38  4865.4  346.41  4875.4  347.03
  4895.6  346.23  4905.7  347.08  4956.1  346.77  4986.3  347.52  4990.9  342.04
  4993.6  341.54  4996.9  342.04  4998.9  343.84  5006.5  346.11  5016.5  347.29
  5079.1  346.98  5149.8  347.87    5164  346.61  5178.1  347.66  5219.9  348.67
  5291.2  351.87  5305.4  354.04  5390.2  362.34  5432.7  365.68  5460.9  366.77
#Mann= 6 ,-1 , 0
  4633.6     .16       0  4986.3     .12       0  4990.9     .07       0
  4996.9     .07       0  5016.5     .12       0  5219.9     .16       0
Bank Sta=4986.3,5016.5
XS Rating Curve= 0 ,0
Exp/Cntr=0.3,0.1

Type RM Length L Ch R = 1 ,6794    ,304,304,304
BEGIN DESCRIPTION:
WILLOW SLOUGH 15.0
END DESCRIPTION:
XS GIS Cut Line= 3
      3756949.59     10612060.17      3756649.61     10611760.19
      3755849.58     10611860.19
#Sta/Elev= 30
  4581.1  382.79  4637.6  376.59  4665.9  372.52  4680.1  371.53  4722.5  363.74
  4750.8  360.26  4764.9  356.97  4807.4  352.07  4892.2  345.15  4934.6  344.16
  4948.8  345.06  4991.2  345.42  4998.8  343.09  5001.6  342.59  5004.8  343.09
  5015.4  345.07    5096   344.3  5327.8  345.45  5337.9  343.73    5348  344.82
  5398.4  344.21  5509.2  350.46  5519.3  350.04  5569.7  351.84  5670.5  363.14
  5751.1  376.55  5768.7  381.71  5773.8  381.72  5781.3  384.42  5811.6  386.84
#Mann= 5 ,-1 , 0
  4581.1     .12       0  4991.2     .15       0  4998.8     .07       0
  5004.8     .07       0  5015.4     .15       0
#XS Ineff= 2 , 0
                          5196.4          346.14
Permanent Ineff=
       F       F
Bank Sta=4991.2,5015.4
XS Rating Curve= 0 ,0
Exp/Cntr=0.3,0.1

Type RM Length L Ch R = 1 ,6490    ,268,268,268
BEGIN DESCRIPTION:
WILLOW SLOUGH 14.0
END DESCRIPTION:
XS GIS Cut Line= 3
      3757148.26     10611829.96      3756088.54     10610975.03
      3755660.45     10610749.81
#Sta/Elev= 30
  4630.1  378.13    4665  374.14  4706.6  372.13  4734.2   368.9  4799.4  359.92
  4834.6  358.18  4856.9  353.71  4877.7  352.62  4892.1     350  4941.7  347.01
  4976.9  342.47  4996.3  339.42    4999  338.92  5002.3  339.42  5020.1  340.11
  5026.7  343.26  5496.7  341.04  5511.1  342.17  5525.4   340.8  5709.4  341.85
  5802.2  340.36  5845.3  341.75  5859.7  340.41  6142.3  347.71  6246.9  354.19
  6274.6  350.98    6291  353.54  6395.5  355.33  6432.8  357.97  6475.4  360.09
#Mann= 5 ,-1 , 0
  4630.1     .16       0  4734.2     .12       0  4996.3     .07       0
  5002.3     .12       0  6432.8     .16       0
Bank Sta=4976.9,5026.7
XS Rating Curve= 0 ,0
Exp/Cntr=0.3,0.1

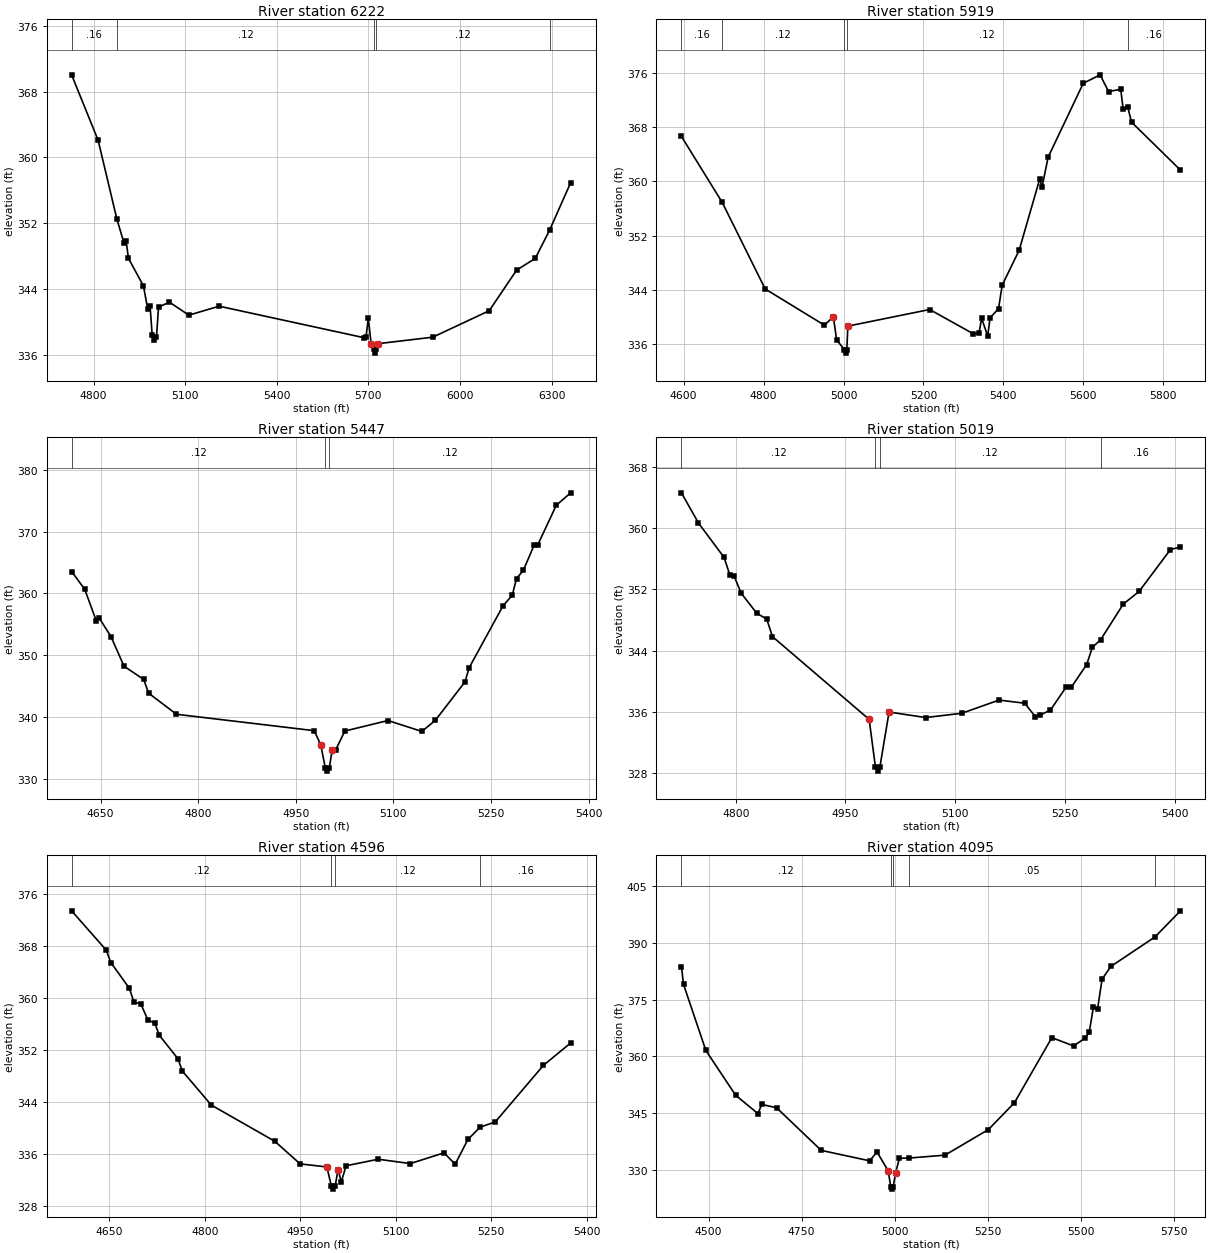
Type RM Length L Ch R = 1 ,6222    ,303,303,303
BEGIN DESCRIPTION:
Mapping XS 6ef41c71
END DESCRIPTION:
XS GIS Cut Line= 3
      3757222.91     10611659.51      3756667.36     10611055.35
      3756306.27     10610326.22
#Sta/Elev= 30
  4728.1  370.05  4814.9  362.09    4876  352.55  4899.9  349.54  4906.7  349.85
  4914.1  347.74  4963.4  344.36  4977.6   341.5    4985  341.97  4991.8  338.45
  4998.9  337.73    5006  338.13  5012.8  341.79  5048.5  342.39    5112  340.81
  5211.3   341.9  5686.6  338.06  5692.2  338.11  5699.7  340.45    5709  337.33
    5719  336.69  5721.7  336.19    5725  336.69  5731.5  337.34  5910.9  338.13
  6095.8  341.35  6185.5  346.29  6246.5  347.71  6293.4  351.14  6362.5  356.92
#Mann= 5 ,-1 , 0
  4728.1     .16       0    4876     .12       0    5719     .07       0
    5725     .12       0  6293.4     .16       0
Bank Sta=5709,5731.5
XS Rating Curve= 0 ,0
Exp/Cntr=0.3,0.1

Type RM Length L Ch R = 1 ,5919    ,472,472,472
BEGIN DESCRIPTION:
WILLOW SLOUGH 13.0
END DESCRIPTION:
XS GIS Cut Line= 3
      3757349.61     10611560.19      3757149.61     10611160.19
      3756715.97     10610485.91
#Sta/Elev= 30
  4594.4  366.64  4696.4  356.92    4804  344.15  4952.2  338.81  4974.5  340.05
  4982.9  336.63  5002.3  335.19    5005  334.69  5008.3  335.19  5010.9  338.67
  5215.6  341.12  5324.6  337.55  5338.9   337.6  5345.7  339.82  5360.9  337.21
  5366.9  339.89    5388  341.25  5397.2  344.72  5439.5  349.84    5491  360.34
    5497   359.2  5512.1  363.58    5600  374.47  5642.2  375.72  5663.4  373.25
  5693.8   373.6  5699.7  370.73  5711.5  370.93  5720.8  368.75  5843.3  361.67
#Mann= 5 ,-1 , 0
  4594.4     .16       0  4696.4     .12       0  5002.3     .07       0
  5008.3     .12       0  5711.5     .16       0
Bank Sta=4974.5,5010.9
XS Rating Curve= 0 ,0
Exp/Cntr=0.3,0.1

Type RM Length L Ch R = 1 ,5447    ,428,428,428
BEGIN DESCRIPTION:
WILLOW SLOUGH 12.0
END DESCRIPTION:
XS GIS Cut Line= 3
       3757699.6     10610710.19      3757299.61     10610760.19
      3756949.62     10610660.19
#Sta/Elev= 30
  4605.4  363.55  4625.5  360.69  4643.2  355.61  4648.2  355.98  4665.9  353.02
    4686  348.24  4716.2   346.1  4723.8  343.88  4766.6  340.47  4978.3  337.82
  4988.3  335.55  4995.4  331.78  4998.2  331.28  5001.4  331.78    5006  334.67
  5011.1  334.67  5025.4  337.76  5091.7  339.46  5143.7   337.7  5164.5  339.49
    5210   345.7  5216.5     348  5268.5  357.99  5282.8  359.73  5289.3  362.42
  5299.7  363.72  5316.6  367.87  5321.8  367.83  5350.4  374.25  5372.5  376.27
#Mann= 3 ,-1 , 0
  4605.4     .12       0  4995.4     .07       0  5001.4     .12       0
Bank Sta=4988.3,5006
XS Rating Curve= 0 ,0
Exp/Cntr=0.3,0.1

Type RM Length L Ch R = 1 ,5019    ,423,423,423
BEGIN DESCRIPTION:
WILLOW SLOUGH 11.0
END DESCRIPTION:
XS GIS Cut Line= 3
      3757699.62      10610510.2      3757449.61     10610360.19
      3757149.59     10610110.17
#Sta/Elev= 30
  4725.8  364.61  4749.1  360.67  4784.1  356.18  4791.9  353.91  4797.7  353.77
  4807.5  351.51  4828.8  348.89  4842.4  348.14  4850.2  345.85  4982.4  335.05
    4991   328.8  4993.8   328.3    4997   328.8  5009.6  336.01  5059.7  335.29
  5109.1  335.85  5159.9  337.57    5195  337.16  5209.4  335.42  5215.9  335.61
  5230.2  336.26  5251.7  339.28  5258.8  339.26  5279.7   342.2  5287.5  344.46
  5298.8  345.44  5329.8   350.1  5351.3  351.74  5394.2  357.21  5407.9  357.54
#Mann= 4 ,-1 , 0
  4725.8     .12       0    4991     .07       0    4997     .12       0
  5298.8     .16       0
Bank Sta=4982.4,5009.6
XS Rating Curve= 0 ,0
Exp/Cntr=0.3,0.1

Type RM Length L Ch R = 1 ,4596    ,501,501,501
BEGIN DESCRIPTION:
WILLOW SLOUGH 10.0
END DESCRIPTION:
XS GIS Cut Line= 3
       3757949.6     10610110.19      3757599.61     10609960.19
      3757199.61     10610010.19
#Sta/Elev= 30
  4590.8  373.46  4645.2   367.4  4652.4  365.49  4681.5  361.52  4688.7   359.4
  4699.6   359.1  4710.5  356.65  4721.4  356.14  4728.6  354.27  4757.6  350.69
  4764.9  348.74  4810.2  343.52  4909.9  337.94  4949.8  334.45  4991.7  333.98
  4998.8  331.06  5001.6  330.56  5004.8  331.06  5009.4  333.56  5014.4  331.68
    5022  334.16  5072.4  335.17  5122.8   334.5  5175.7  336.15  5193.3  334.41
  5213.5  338.24  5232.5  340.11  5256.3  340.92  5331.9  349.64  5374.7  353.09
#Mann= 4 ,-1 , 0
  4590.8     .12       0  4998.8     .07       0  5004.8     .12       0
  5232.5     .16       0
Bank Sta=4991.7,5009.4
XS Rating Curve= 0 ,0
Exp/Cntr=0.3,0.1

Type RM Length L Ch R = 1 ,4095    ,518,518,518
BEGIN DESCRIPTION:
WILLOW SLOUGH 9.0
END DESCRIPTION:
XS GIS Cut Line= 3
       3758115.2       10609485.      3757410.32     10609491.94
      3756824.07     10609738.24
#Sta/Elev= 30
  4427.1  383.69  4432.7  378.99  4492.7  361.58  4572.7  349.79  4632.7  344.93
  4642.7  347.36  4682.7  346.48  4802.7  335.25  4932.7   332.5  4952.7  334.82
  4982.7  329.85  4989.7  325.54  4992.5  325.04  4995.7  325.54  5002.7  329.36
  5012.7  333.17  5038.7  333.23  5135.1  333.99  5252.1  340.75  5321.9  347.82
  5422.3  364.95  5480.7  362.78  5512.4  364.86  5522.8  366.42  5534.1  373.06
    5545  372.43  5557.4   380.4  5581.1  383.73  5699.6   391.5  5767.9  398.37
#Mann= 5 ,-1 , 0
  4427.1     .12       0  4989.7     .07       0  4995.7     .12       0
  5038.7     .05       0  5699.6     .16       0
Bank Sta=4982.7,5002.7
XS Rating Curve= 0 ,0
Exp/Cntr=0.3,0.1

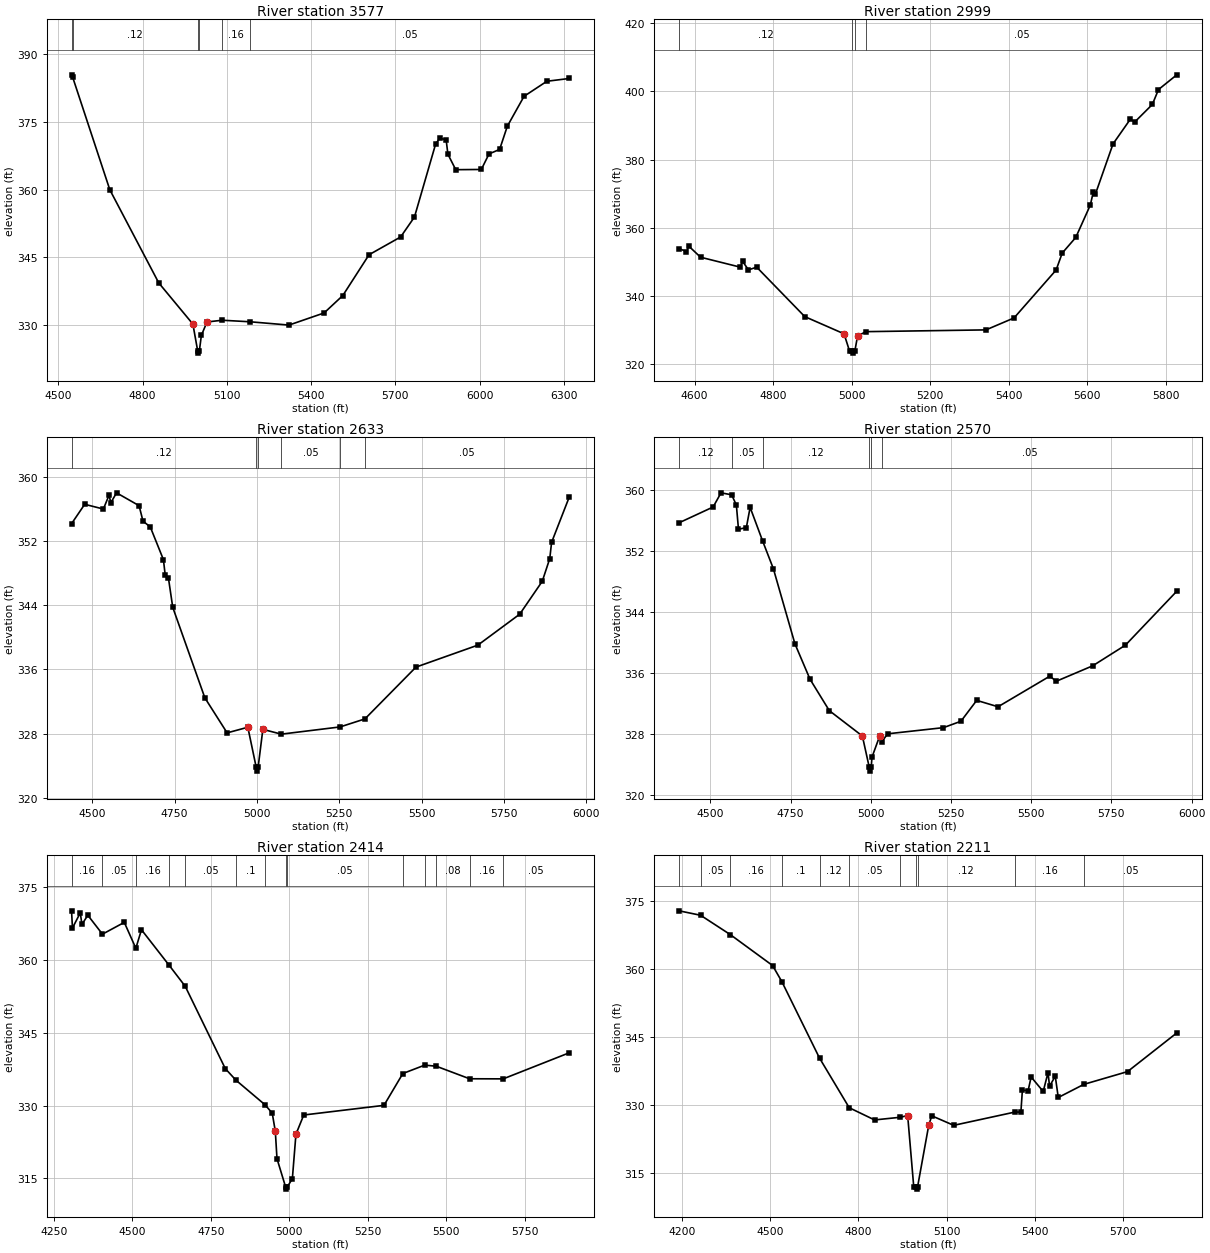
Type RM Length L Ch R = 1 ,3577    ,578,578,578
BEGIN DESCRIPTION:
WILLOW SLOUGH 8.0
END DESCRIPTION:
XS GIS Cut Line= 3
      3758248.95     10609180.67      3757391.35     10609083.46
      3756596.23     10609524.41
#Sta/Elev= 30
  4547.1  385.36  4550.7  384.91  4683.4  359.95  4857.8  339.35  4979.2  330.26
  4996.3  324.34  4999.1  323.84  5002.3  324.34  5009.4  327.76  5029.5  330.73
  5083.7  331.11  5182.9  330.77  5321.4  330.04  5446.5  332.72  5513.1  336.57
  5606.6  345.59  5719.1  349.52  5768.3  353.93  5843.9  370.11  5858.1   371.3
    5881  371.05  5887.4  367.81  5915.3  364.39  6006.4  364.44  6033.9  367.88
  6071.6  368.87  6099.1  374.01  6158.6  380.61  6239.9  383.94  6319.4  384.55
#Mann= 6 ,-1 , 0
  4547.1     .05       0  4550.7     .12       0  4996.3     .07       0
  5002.3     .12       0  5083.7     .16       0  5182.9     .05       0
Bank Sta=4979.2,5029.5
XS Rating Curve= 0 ,0
Exp/Cntr=0.3,0.1

Type RM Length L Ch R = 1 ,2999    ,366,366,366
BEGIN DESCRIPTION:
WILLOW SLOUGH 7.0
END DESCRIPTION:
XS GIS Cut Line= 3
      3758098.73     10608796.88      3757864.32     10608632.79
      3756904.04      10608432.4
#Sta/Elev= 30
  4560.6  353.97  4579.4  353.06  4585.5  354.65  4615.2  351.43  4716.3  348.52
  4722.4  350.19  4737.2  347.72  4758.1  348.52  4880.5  334.03  4980.5  328.99
  4994.6  323.92  5001.8  323.83  5004.5  323.33  5007.8  323.83    5015  328.34
  5036.1  329.62  5341.9  330.14  5413.4  333.64  5520.5  347.68    5536  352.64
  5570.5  357.22  5607.5  366.69  5615.4  370.65  5620.5  369.91  5665.4  384.63
  5709.6  391.89  5720.6  391.04  5765.5  396.19  5781.1  400.55  5827.7  404.87
#Mann= 4 ,-1 , 0
  4560.6     .12       0  5001.8     .07       0  5007.8     .12       0
  5036.1     .05       0
Bank Sta=4980.5,5015
XS Rating Curve= 0 ,0
Exp/Cntr=0.3,0.1

Type RM Length L Ch R = 1 ,2633    ,63,63,63
BEGIN DESCRIPTION:
Mapping XS 7269018b
END DESCRIPTION:
XS GIS Cut Line= 2
      3758103.89     10608786.42      3757460.68     10607419.27
#Sta/Elev= 30
  4437.3  354.17  4477.2  356.59  4533.9     356  4551.1  357.72  4556.6  356.79
  4573.9  358.02  4642.3  356.42  4654.2  354.49  4676.3  353.77  4716.2  349.69
  4721.7  347.74  4731.5  347.38  4744.5  343.75    4842  332.46  4909.6  328.09
  4972.5  328.79  4997.8  323.82  5000.6  323.32  5003.8  323.82  5018.1  328.53
  5074.1  327.93  5252.5  328.83    5328  329.83    5483  336.29  5670.9  339.03
    5798  342.89  5866.4  346.99  5889.2  349.83  5894.7  351.84  5948.2  357.48
#Mann= 6 ,-1 , 0
  4437.3     .12       0  4997.8     .07       0  5003.8     .12       0
  5074.1     .05       0  5252.5      .1       0    5328     .05       0
Bank Sta=4972.5,5018.1
XS Rating Curve= 0 ,0
Exp/Cntr=0.3,0.1

Type RM Length L Ch R = 1 ,2570    ,156,156,156
BEGIN DESCRIPTION:
WILLOW SLOUGH 6.0
END DESCRIPTION:
XS GIS Cut Line= 2
      3758122.13     10608786.43      3757559.63     10607341.13
#Sta/Elev= 30
  4402.8   355.7  4508.8  357.77  4533.4  359.63  4566.5  359.37  4581.2  358.03
  4587.8  354.85  4612.3  355.06  4624.1  357.72  4663.1   353.3  4696.5  349.67
  4763.6  339.82  4810.7  335.16  4870.9  331.03  4973.9   327.7  4995.4  323.59
  4998.2  323.09  5001.4  323.59  5003.8  324.91  5028.3  327.75  5034.9  326.98
  5052.8  327.99  5226.7   328.8  5281.1  329.64  5330.2  332.38  5396.7  331.54
  5558.5  335.57  5577.7  334.88  5691.8  336.92  5793.7  339.63  5953.7  346.71
#Mann= 6 ,-1 , 0
  4402.8     .12       0  4566.5     .05       0  4663.1     .12       0
  4995.4     .07       0  5001.4     .12       0  5034.9     .05       0
Bank Sta=4973.9,5028.3
XS Rating Curve= 0 ,0
Exp/Cntr=0.3,0.1

Type RM Length L Ch R = 1 ,2414    ,203,203,203
BEGIN DESCRIPTION:
WILLOW SLOUGH 5.0
END DESCRIPTION:
XS GIS Cut Line= 2
      3758265.36     10608778.62      3757705.63     10607294.68
#Sta/Elev= 30
    4306  370.15  4308.9   366.6  4333.8  369.74  4339.1  367.35  4357.8  369.24
  4404.5  365.34  4474.1  367.77  4510.9  362.43  4528.8  366.25  4617.3   358.9
  4668.3  354.59    4796  337.62    4830  335.23  4922.7  330.16  4945.6  328.44
  4955.4  324.69  4960.7  319.06  4987.9  313.28  4990.7  312.78  4993.9  313.28
  5009.7  314.92  5021.1  324.09    5046  328.06  5301.7  330.05  5361.8  336.61
  5431.4  338.34  5468.2  338.12  5574.5  335.53  5681.7  335.51    5892  340.88
#Mann= 14 ,-1 , 0
    4306     .16       0  4404.5     .05       0  4510.9     .16       0
  4617.3      .1       0  4668.3     .05       0    4830      .1       0
  4922.7     .05       0  4987.9     .04       0  4993.9     .05       0
  5361.8     .16       0  5431.4     .05       0  5468.2     .08       0
  5574.5     .16       0  5681.7     .05       0
Bank Sta=4955.4,5021.1
XS Rating Curve= 0 ,0
Exp/Cntr=0.3,0.1

Type RM Length L Ch R = 1 ,2211    ,217,217,217
BEGIN DESCRIPTION:
Mapping XS 0722b08e
END DESCRIPTION:
XS GIS Cut Line= 3
      3758309.63     10608760.41      3758161.19     10608059.87
      3757950.25     10607106.72
#Sta/Elev= 30
  4190.6  372.81  4263.7  371.83  4364.8  367.56  4508.5  360.74  4539.9   357.2
    4668  340.34  4769.1  329.38  4855.3  326.69  4942.6  327.28  4967.8  327.65
  4988.4  311.99  4995.5  311.93  4998.3  311.43  5001.5  311.93  5039.5  325.54
  5049.8   327.6  5124.4   325.5  5332.7  328.43  5352.8  328.42  5357.9  333.24
  5377.5  333.18  5387.7  336.16  5428.7  332.97  5445.1  337.13  5450.3  334.11
  5469.7  336.35  5479.9  331.64    5567  334.54  5715.5  337.35  5882.9  345.88
#Mann= 11 ,-1 , 0
  4190.6     .16       0  4263.7     .05       0  4364.8     .16       0
  4539.9      .1       0    4668     .12       0  4769.1     .05       0
  4942.6     .12       0  4995.5     .07       0  5001.5     .12       0
  5332.7     .16       0    5567     .05       0
Bank Sta=4967.8,5039.5
XS Rating Curve= 0 ,0
Exp/Cntr=0.3,0.1

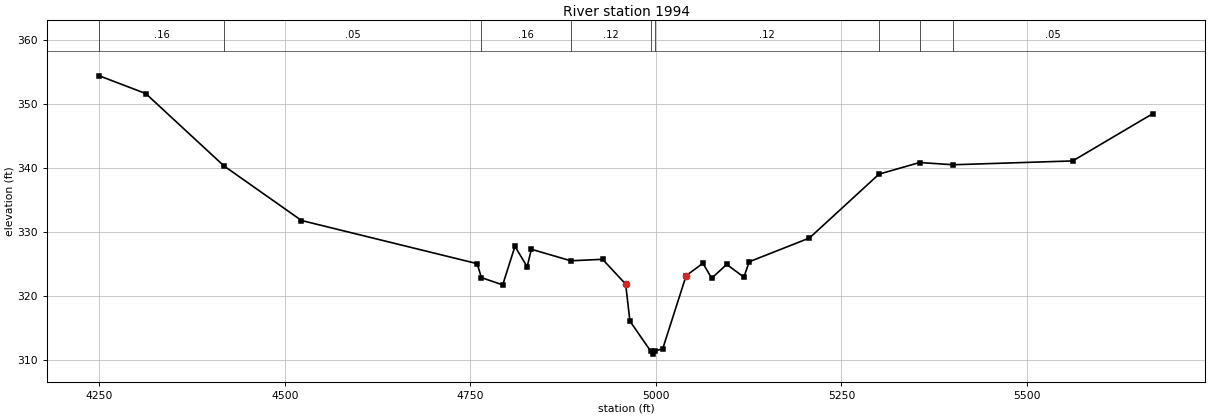
Type RM Length L Ch R = 1 ,1994    ,201,201,201
BEGIN DESCRIPTION:
Mapping XS f5d7a1d7
END DESCRIPTION:
XS GIS Cut Line= 3
      3758602.65     10608462.06      3758220.71     10607725.95
       3758123.7     10607143.88
#Sta/Elev= 30
    4250  354.39  4312.5  351.62  4417.8  340.31  4522.4  331.76  4759.1  325.01
  4764.8  322.83  4793.5  321.69    4810  327.71  4826.5  324.53  4832.1  327.26
  4885.3  325.46  4928.1  325.69  4959.2  321.81  4964.9  316.03  4992.7  311.36
  4995.4  310.86  4998.7  311.36  5009.1  311.69  5040.7  323.14  5063.3  325.07
  5075.1  322.73  5095.3  324.89  5118.5  322.91  5125.7  325.31  5206.8  329.02
  5300.5  339.01  5355.3  340.83  5400.6  340.48  5561.6  341.08  5669.4  348.47
#Mann= 9 ,-1 , 0
    4250     .16       0  4417.8     .05       0  4764.8     .16       0
  4885.3     .12       0  4992.7     .07       0  4998.7     .12       0
  5300.5     .05       0  5355.3     .12       0  5400.6     .05       0
Bank Sta=4959.2,5040.7
XS Rating Curve= 0 ,0
Exp/Cntr=0.3,0.1