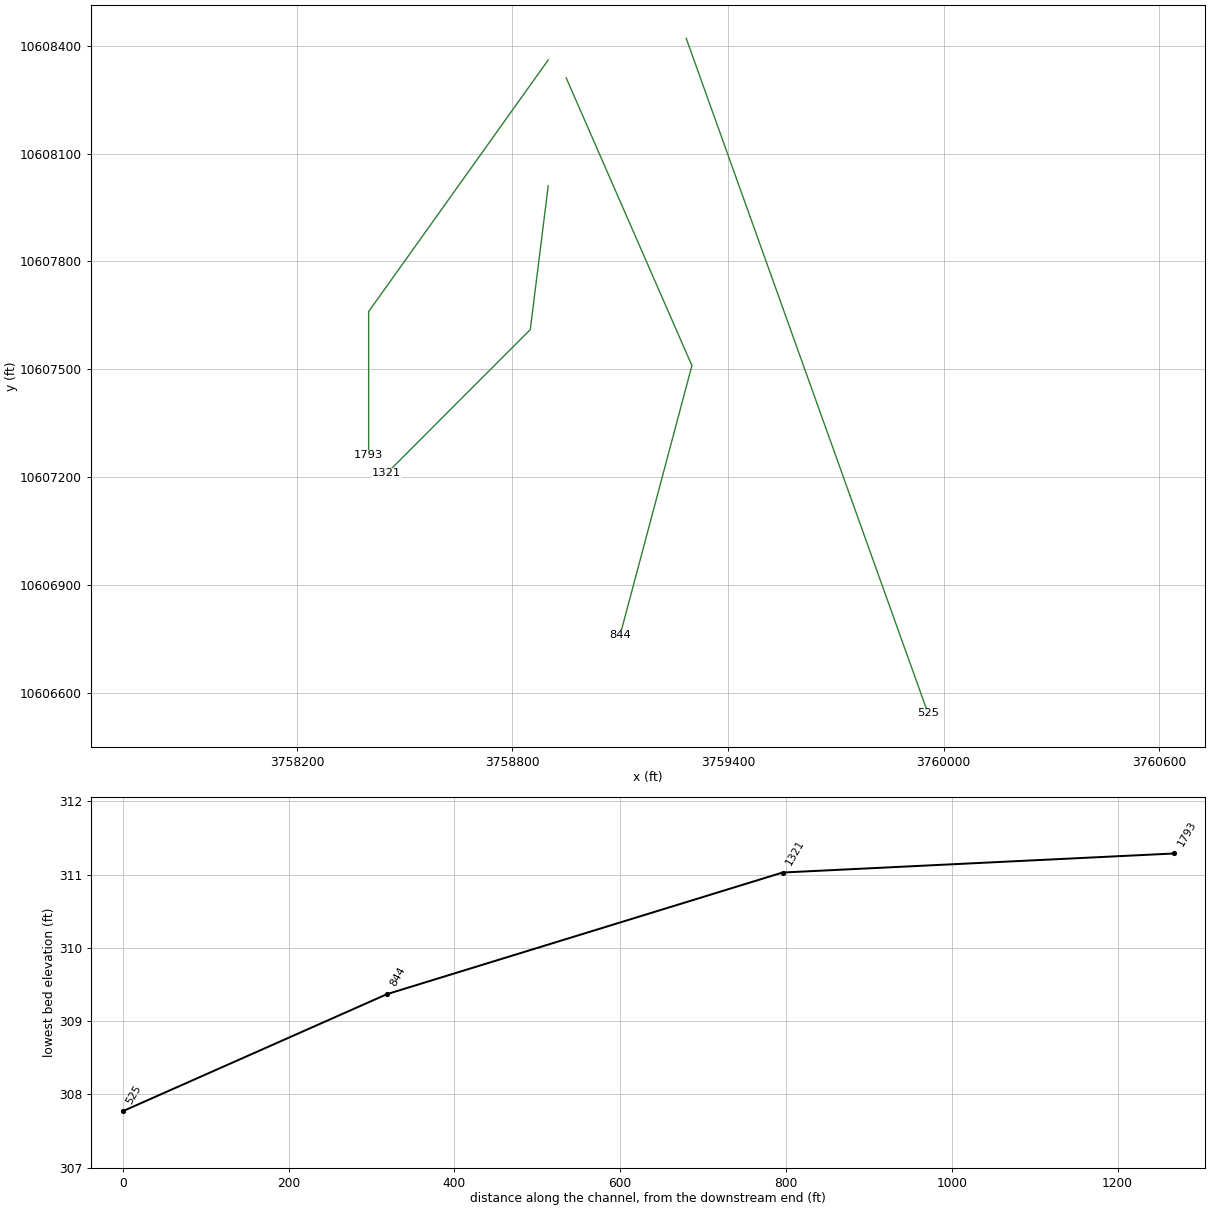
HEC-RAS study WILLOW SLOUGH.prj: WILLOW SLOUGH Base Level Engineering

--- WILLOW SLOUGH.g01 (geometry) --- (continued)

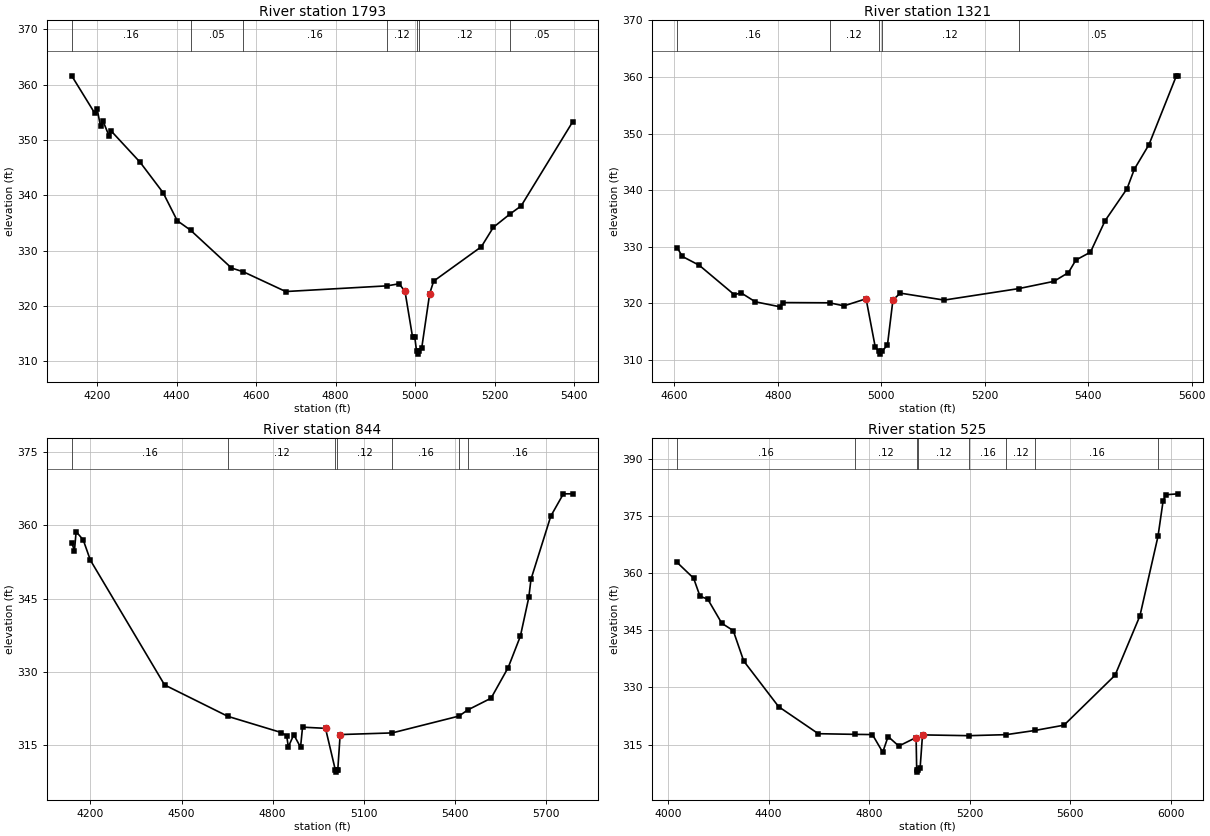
Type RM Length L Ch R = 1 ,1793    ,472,472,472
BEGIN DESCRIPTION:
WILLOW SLOUGH 4.0
END DESCRIPTION:
XS GIS Cut Line= 3
      3758899.59     10608360.17      3758399.61     10607660.19
      3758399.61     10607260.19
#Sta/Elev= 30
  4136.4  361.58  4194.1  354.85  4200.3  355.59  4208.9  352.43    4215  353.44
  4229.8  350.79  4235.9  351.59  4308.4  345.96  4366.2  340.46  4401.8   335.4
  4435.2  333.69  4538.2  326.85  4568.2  326.16  4674.6   322.6  4929.5  323.63
  4959.7     324  4974.5  322.64  4993.5  314.39  4999.1  314.39  5003.6  311.79
  5006.4  311.29  5009.6  311.79  5016.6  312.41  5036.6  322.23  5046.6  324.48
  5166.6   330.7  5196.6   334.2  5238.8  336.62  5266.6  338.07  5396.6  353.32
#Mann= 7 ,-1 , 0
  4136.4     .16       0  4435.2     .05       0  4568.2     .16       0
  4929.5     .12       0  5003.6     .07       0  5009.6     .12       0
  5238.8     .05       0
Bank Sta=4974.5,5036.6
XS Rating Curve= 0 ,0
Exp/Cntr=0.3,0.1

Type RM Length L Ch R = 1 ,1321    ,477,477,477
BEGIN DESCRIPTION:
WILLOW SLOUGH 3.0
END DESCRIPTION:
XS GIS Cut Line= 3
      3758899.61     10608010.17      3758849.61     10607610.19
      3758449.59     10607210.17
#Sta/Elev= 30
  4605.3  329.86  4615.4  328.29  4648.1  326.73  4716.1  321.51  4728.7  321.87
  4756.4  320.28  4804.3  319.39  4809.4  320.14  4899.9   320.1  4927.8  319.56
  4970.6  320.81  4988.2  312.34  4995.3  311.53  4998.1  311.03  5001.3  311.53
  5011.9  312.62  5022.5  320.59  5036.7  321.81  5121.5  320.58  5265.7  322.61
  5333.7  323.89  5361.9  325.44  5376.1  327.65  5404.4  329.05  5432.7  334.61
  5475.1  340.26  5489.2  343.71  5517.5  348.05  5570.5  360.21  5574.1  360.21
#Mann= 5 ,-1 , 0
  4605.3     .16       0  4899.9     .12       0  4995.3     .07       0
  5001.3     .12       0  5265.7     .05       0
Bank Sta=4970.6,5022.5
XS Rating Curve= 0 ,0
Exp/Cntr=0.3,0.1

Type RM Length L Ch R = 1 ,844     ,319,319,319
BEGIN DESCRIPTION:
WILLOW SLOUGH 2.0
END DESCRIPTION:
XS GIS Cut Line= 3
      3758949.59     10608310.23      3759299.61     10607510.19
       3759099.6     10606760.15
#Sta/Elev= 30
  4138.6  356.49  4147.6  354.83  4153.1  358.74  4176.5  357.04  4199.8   352.9
  4444.3  327.27  4652.6  320.82  4828.2   317.5  4846.2  316.82  4851.6  314.56
  4869.6  317.05  4891.8  314.48  4898.4   318.6    4974  318.36  5006.1  309.87
  5008.9  309.37  5012.1  309.87  5014.4  309.87  5022.2  317.08  5193.4  317.42
  5413.6  320.88  5441.5  322.11    5519  324.55  5575.3  330.84  5615.4  337.27
  5643.2  345.25  5650.3  348.95  5715.6  361.93    5757   366.5  5788.1   366.5
#Mann= 7 ,-1 , 0
  4138.6     .16       0  4652.6     .12       0  5006.1     .07       0
  5012.1     .12       0  5193.4     .16       0  5413.6     .05       0
  5441.5     .16       0
Bank Sta=4974,5022.2
XS Rating Curve= 0 ,0
Exp/Cntr=0.3,0.1

Type RM Length L Ch R = 1 ,525     ,0,0,0
BEGIN DESCRIPTION:
WILLOW SLOUGH 1.0
END DESCRIPTION:
XS GIS Cut Line= 2
      3759283.69      10608420.3       3759956.7     10606543.52
#Sta/Elev= 30
  4036.2  362.83  4101.8  358.69  4127.2  353.95    4158  353.19  4214.1  346.84
  4259.4  344.94  4301.1  336.95    4440  324.96  4597.9  317.86  4742.6  317.69
  4813.2  317.63  4854.3     313  4875.6  317.12  4918.1  314.62    4987  316.86
  4989.4  308.27  4992.2  307.77  4995.4  308.27  5003.1  308.96  5012.5  317.55
  5196.9  317.34  5345.7  317.61  5459.7  318.71  5575.4   320.1  5778.6  333.21
  5877.6  348.82  5949.4  369.67  5969.8  378.99  5980.4  380.61    6030  380.85
#Mann= 8 ,-1 , 0
  4036.2     .16       0  4742.6     .12       0  4989.4     .07       0
  4995.4     .12       0  5196.9     .16       0  5345.7     .12       0
  5459.7     .16       0  5949.4      .1       0
Bank Sta=4987,5012.5
XS Rating Curve= 0 ,0
Exp/Cntr=0.3,0.1

Chan Stop Cuts=-1
Use User Specified Reach Order=0
Composite Channel Slope=5