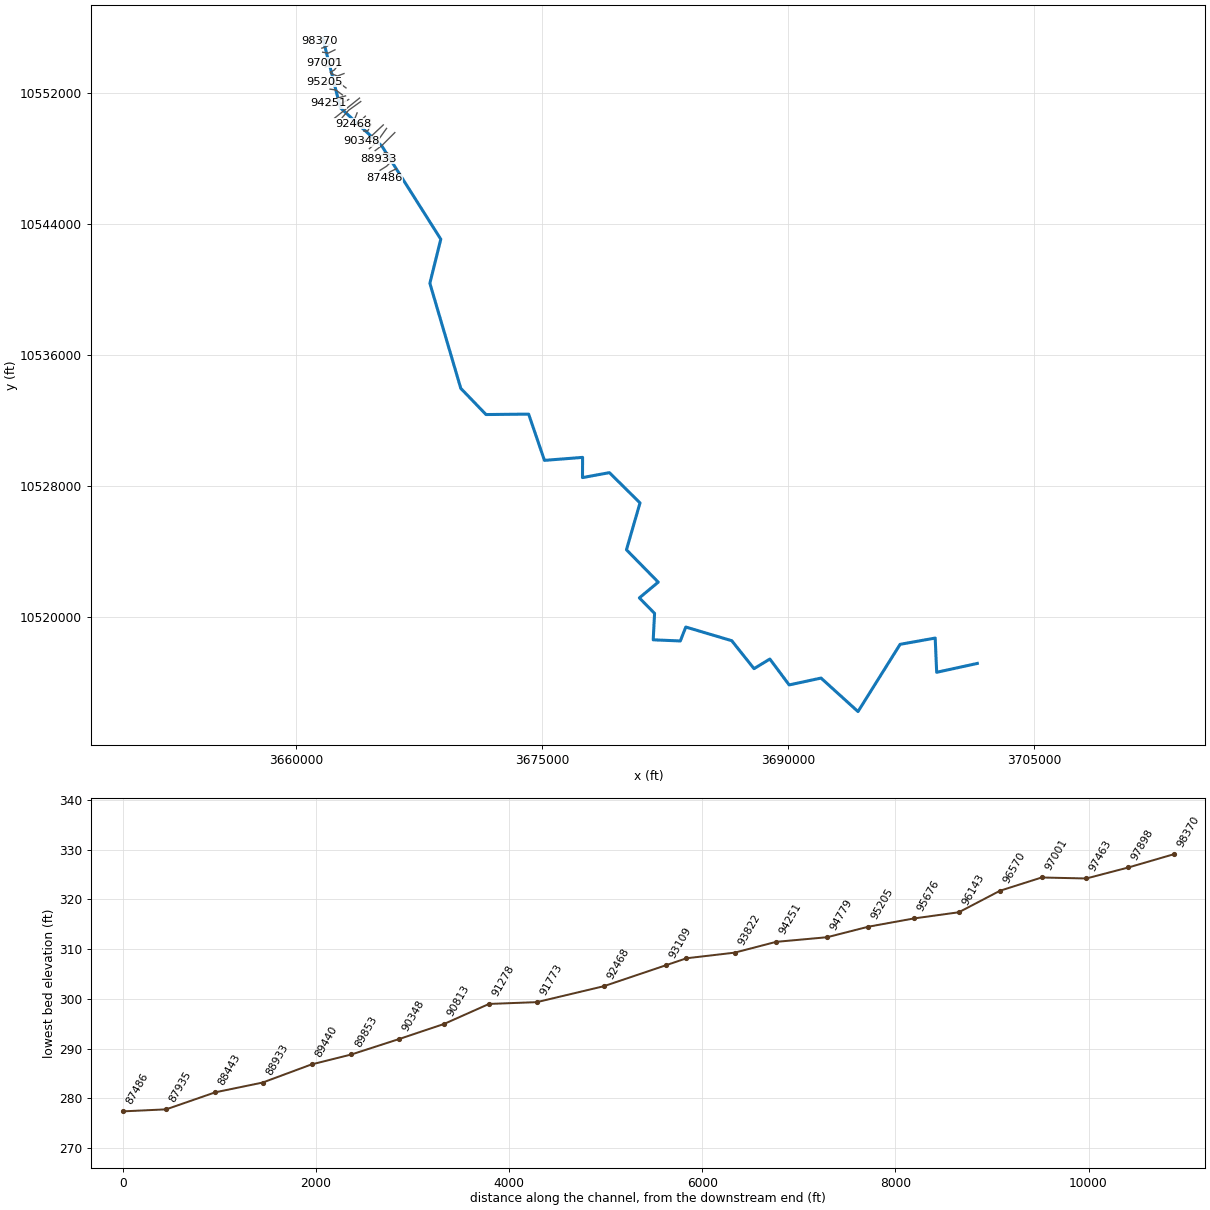
--- ALLIGATOR BRANCH.prj (project) ---

Proj Title=ALLIGATOR BRANCH Base Level Engineering
Current Plan=p01
Default Exp/Contr=0.3,0.1
English Units
Geom File=g01
Flow File=f01
Plan File=p01
Y Axis Title=Elevation
X Axis Title(PF)=Main Channel Distance
X Axis Title(XS)=Station
BEGIN DESCRIPTION:
ALLIGATOR BRANCH
END DESCRIPTION:
DSS Export Rating Curves= 0
DSS Export Rating Curve Sorted= 0
DSS Export Volume Flow Curves= 0
DXF OffsetX= 0
DXF OffsetY= 0
DXF ScaleX= 1
DXF ScaleY= 10

--- ALLIGATOR BRANCH.p01 (plan) ---

Plan Title=Multiple Run
Program Version=4.10
Short Identifier=Multiple
Geom File=g01
Flow File=f01
Subcritical Flow
K Sum by GR= 0
Std Step Tol= 0.01
Critical Tol= 0.01
Num of Std Step Trials= 20
Max Error Tol= 0.3
Flow Tol Ratio= 0.001
Split Flow NTrial= 30
Split Flow Tol= 0.02
Split Flow Ratio= 0.02
Log Output Level= 0
Friction Slope Method= 1
Unsteady Friction Slope Method= 2
Unsteady Bridges Friction Slope Method= 1
Parabolic Critical Depth
Global Vel Dist= 1 , 1 , 1
Global Log Level= 0
CheckData=True
Encroach Param=-1 ,0,0, 0
BEGIN DESCRIPTION:
Multiple Run
END DESCRIPTION:
Computation Interval=1HOUR
Output Interval=1HOUR
Run HTab= 0
Run UNet= 0
Run PostProcess= 0
Run WQNet= 0
UNET Theta= 1
UNET Theta Warmup= 1
UNET ZTol= 0.02
UNET ZSATol= 0.05
UNET MxIter= 20
UNET MaxInSteps= 0
UNET DtIC= 0
UNET DtMin= 0
UNET MaxCRTS= 20
UNET WFStab= 2
UNET SFStab= 1
UNET WFX= 1
UNET SFX= 1
UNET DSS MLevel= 4
UNET DZMax Abort= 100
UNET Convert EG Bridges= 0
UNET Use Existing IB Tables=-1
UNET Froude Reduction=False
UNET Froude Limit= 1
UNET Froude Power= 10
UNET Time Slicing=0,0, 5
UNET Junction Losses=0
Instantaneous Interval=1HOUR
Write IC File= 0
Write IC File at Sim End=0
Echo Input=False
Echo Parameters=False
Echo Output=False
Write Detailed= 0
WQ AD Non Conservative
WQ ULTIMATE=-1
WQ Max Comp Step=1HOUR
WQ Output Interval=15MIN
WQ Output Selected Increments= 0
WQ Output face flow=0
WQ Output face velocity=0
WQ Output face area=0
WQ Output face dispersion=0
WQ Output cell volume=0
WQ Output cell surface area=0
WQ Output cell continuity=0
WQ Output cumulative cell continuity=0
WQ Output face conc=0
WQ Output face dconc_dx=0
WQ Output face courant=0
WQ Output face peclet=0
WQ Output face adv mass=0
WQ Output face disp mass=0
WQ Output cell mass=0
WQ Output cell source sink temp=0
WQ Output cell source sink nsm=0
WQ Output MaxMinRange=-1
WQ Daily Max Min Mean=-1
WQ Daily Range=0
WQ Daily Time=0
WQ Create Restart=0
WQ Fixed Restart=0
WQ System Summary=0
WQ Use Fixed Temperature=0
Sorting and Armoring Iterations= 10
XS Update Threshold= 0.02
Hydraulics Update Threshold= 0.02
Energy Slope Method= 1
Volume Change Method= 0
XS Weighting Method= 0
Number of US Weighted Cross Sections= 1
Number of DS Weighted Cross Sections= 1
Upstream XS Weight=0.25
Main XS Weight=0.5
Downstream XS Weight=0.25
Number of DS XS's Weighted with US Boundary= 1
Upstream Boundary Weight= 1
Weight of XSs Associated with US Boundary= 0
Number of US XS's Weighted with DS Boundary= 1
Downstream Boundary Weight= 0.5
Weight of XSs Associated with DS Boundary= 0.5
Sediment Output Level= 4
Mass or Volume Output= 0
Output Increment Type= 1
Profile and TS Output Increment= 10
XS Output Flag= 0
XS Output Increment= 10
Disregard all LS=0
Disregard all Conn=0
Disregard all Breaches=0
Disregard all Pumps=0

--- ALLIGATOR BRANCH.f01 (steady flow) ---

Flow Title=Multiple
Program Version=4.10
Number of Profiles= 7
Profile Names=10-year,25-year,50-year,1pct_min,100-year,1pct_plu,500-year
River Rch & RM=ALLIGATOR BRANCH,Reach-1         ,98370
     632     876    1082     983    1330    1798    2017
River Rch & RM=ALLIGATOR BRANCH,Reach-1         ,97898
     962    1356    1695    1555    2102    2843    3253
River Rch & RM=ALLIGATOR BRANCH,Reach-1         ,93109
    1187    1685    2114    1945    2631    3557    4096
River Rch & RM=ALLIGATOR BRANCH,Reach-1         ,84606
    1717    2476    3141    2918    3947    5337    6266
River Rch & RM=ALLIGATOR BRANCH,Reach-1         ,84075
    1717    2476    3141    2918    3947    5337    6266
River Rch & RM=ALLIGATOR BRANCH,Reach-1         ,81708
    2026    2943    3751    3500    4733    6401    7580
River Rch & RM=ALLIGATOR BRANCH,Reach-1         ,81160
    2141    3110    3963    3696    4999    6761    7998
River Rch & RM=ALLIGATOR BRANCH,Reach-1         ,78266
    3200    4718    6073    5716    7730   10453   12592
River Rch & RM=ALLIGATOR BRANCH,Reach-1         ,77778
    3200    4718    6073    5716    7730   10453   12592
River Rch & RM=ALLIGATOR BRANCH,Reach-1         ,75159
    3246    4776    6139    5768    7801   10550   12666
River Rch & RM=ALLIGATOR BRANCH,Reach-1         ,70699
    3172    4643    5945    5564    7524   10176   12119
River Rch & RM=ALLIGATOR BRANCH,Reach-1         ,63189
    3269    4770    6094    5689    7694   10405   12329
River Rch & RM=ALLIGATOR BRANCH,Reach-1         ,62479
    3269    4770    6094    5689    7694   10405   12329
River Rch & RM=ALLIGATOR BRANCH,Reach-1         ,60944
   22434   32988   42329   39308   53159   71892   83575
River Rch & RM=ALLIGATOR BRANCH,Reach-1         ,53244
   22434   32988   42329   39308   53159   71892   83575
River Rch & RM=ALLIGATOR BRANCH,Reach-1         ,45323
   22643   33261   42662   39622   53584   72467   84306
River Rch & RM=ALLIGATOR BRANCH,Reach-1         ,42984
   22471   32973   42261   39221   53042   71733   83329
River Rch & RM=ALLIGATOR BRANCH,Reach-1         ,34034
   22386   32835   42076   39039   52796   71401   82907
River Rch & RM=ALLIGATOR BRANCH,Reach-1         ,31521
   22280   32656   41826   38791   52460   70946   82312
River Rch & RM=ALLIGATOR BRANCH,Reach-1         ,25671
   22289   32645   41794   38749   52403   70869   82176
River Rch & RM=ALLIGATOR BRANCH,Reach-1         ,21482
   22053   32261   41269   38231   51704   69923   80954
River Rch & RM=ALLIGATOR BRANCH,Reach-1         ,14998
   22180   32434   41485   38433   51976   70291   81396
Boundary for River Rch & Prof#=ALLIGATOR BRANCH,Reach-1         , 1
Up Type= 0
Dn Type= 3
Dn Slope=0.0014
Boundary for River Rch & Prof#=ALLIGATOR BRANCH,Reach-1         , 2
Up Type= 0
Dn Type= 3
Dn Slope=0.0014
Boundary for River Rch & Prof#=ALLIGATOR BRANCH,Reach-1         , 3
Up Type= 0
Dn Type= 3
Dn Slope=0.0014
Boundary for River Rch & Prof#=ALLIGATOR BRANCH,Reach-1         , 4
Up Type= 0
Dn Type= 3
Dn Slope=0.0014
Boundary for River Rch & Prof#=ALLIGATOR BRANCH,Reach-1         , 5
Up Type= 0
Dn Type= 3
Dn Slope=0.0014
Boundary for River Rch & Prof#=ALLIGATOR BRANCH,Reach-1         , 6
Up Type= 0
Dn Type= 3
Dn Slope=0.0014
Boundary for River Rch & Prof#=ALLIGATOR BRANCH,Reach-1         , 7
Up Type= 0
Dn Type= 3
Dn Slope=0.0014
DSS Import GetInterval= 0
DSS Import GetPeak= 0
DSS Import FillOption= 0

--- ALLIGATOR BRANCH.g01 (geometry) ---

Geom Title=Existing Conditions
Program Version=4.10

River Reach=ALLIGATOR BRANCH,Reach-1
Reach XY= 30
       3661607.5       10555314.      3662678.25       10551074.
       3665214.5       10548733.      3668802.75       10543057.
      3668136.25       10540370.      3670021.75       10533960.
        3671561.       10532363.        3674159.       10532389.
       3675123.5       10529568.       3677449.5       10529750.
      3677443.25       10528518.       3679084.5       10528819.
       3680950.5       10526974.       3680123.5       10524115.
      3682062.25       10522140.      3680910.75       10521180.
        3681838.       10520237.      3681755.75       10518623.
      3683408.25       10518553.      3683741.75       10519403.
        3686544.       10518569.       3687902.5       10516864.
       3688867.5       10517450.        3690046.       10515872.
      3691989.25       10516290.        3694244.       10514247.
        3696811.       10518348.      3698950.25       10518730.
      3699040.75       10516643.      3701518.75       10517183.

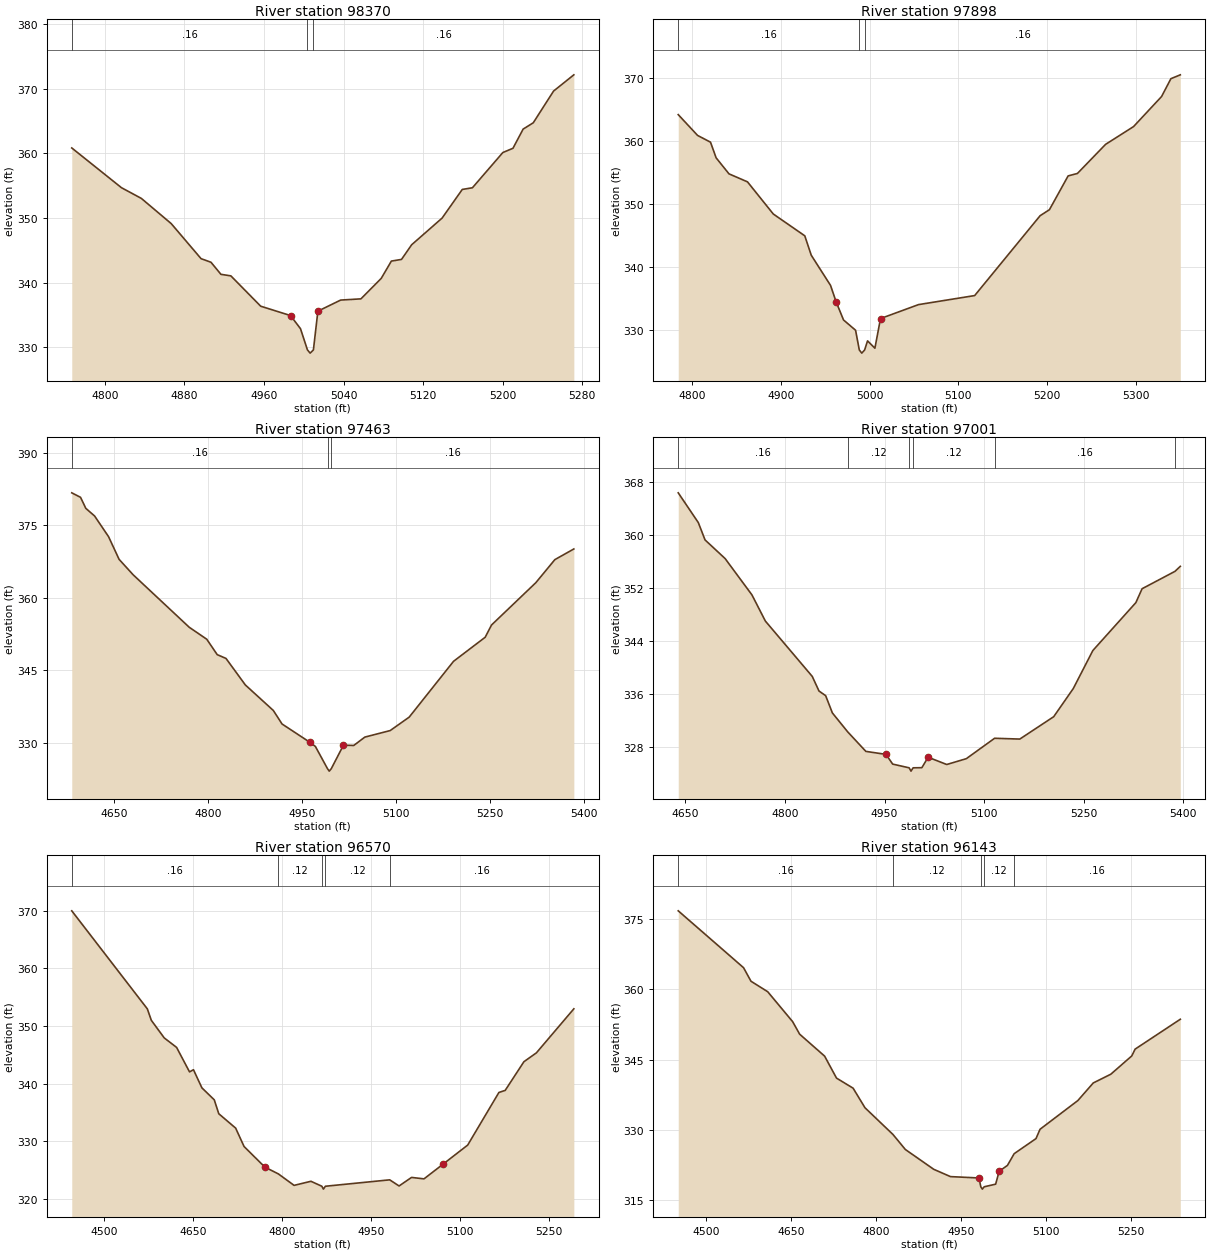
Type RM Length L Ch R = 1 ,98370   ,472,472,472
BEGIN DESCRIPTION:
ALLIGATOR BRANCH 100.0
END DESCRIPTION:
XS GIS Cut Line= 3
      3661899.58     10555210.19      3661649.61     10555210.19
      3661399.63     10555160.19
#Sta/Elev= 30
  4766.7  360.85  4816.7  354.69  4836.7  353.03  4866.7  349.13  4896.7   343.7
  4906.7  343.14  4916.7  341.27  4926.7  341.03  4956.7  336.33  4986.7  334.88
  4996.7  332.85  5003.7  329.56  5006.4  329.06  5009.7  329.56  5014.2  335.56
  5037.1  337.28  5057.5  337.47  5077.9  340.64  5088.1  343.32  5098.3  343.58
  5108.5  345.85  5139.1  349.98  5159.4  354.42  5169.6  354.68  5200.2  360.14
  5210.4   360.8  5220.6  363.77  5230.8  364.75  5251.2  369.66  5271.6  372.18
#Mann= 3 ,-1 , 0
  4766.7     .16       0  5003.7     .07       0  5009.7     .16       0
Bank Sta=4986.7,5014.2
XS Rating Curve= 0 ,0
Exp/Cntr=0.3,0.1

Type RM Length L Ch R = 1 ,97898   ,435,435,435
BEGIN DESCRIPTION:
ALLIGATOR BRANCH 99.0
END DESCRIPTION:
XS GIS Cut Line= 3
      3662049.57     10554960.16      3661849.61     10554810.19
      3661549.59     10554710.18
#Sta/Elev= 30
  4784.2  364.14    4806  360.85  4820.6  359.78  4826.9  357.31  4841.4  354.77
  4862.3   353.5  4891.4  348.41  4926.9  344.96  4934.2  341.89    4956   337.1
  4962.3  334.49  4970.6  331.64  4984.2  330.01  4988.4  326.89  4991.2  326.39
  4994.4  326.89  4997.7  328.33    5006  327.17  5012.3  331.86  5055.2  334.07
  5118.5   335.5  5192.3  348.14  5202.8  349.09  5223.9  354.44  5234.4  354.83
  5266.1  359.43  5297.7  362.25  5329.3  367.01  5339.8  369.83  5350.4  370.44
#Mann= 3 ,-1 , 0
  4784.2     .16       0  4988.4     .07       0  4994.4     .16       0
Bank Sta=4962.3,5012.3
XS Rating Curve= 0 ,0
Exp/Cntr=0.3,0.1

Type RM Length L Ch R = 1 ,97463   ,462,462,462
BEGIN DESCRIPTION:
ALLIGATOR BRANCH 98.0
END DESCRIPTION:
XS GIS Cut Line= 3
      3662349.64      10554610.2      3661949.61     10554410.19
      3661599.61     10554460.19
#Sta/Elev= 30
  4582.6  381.74  4596.6  380.81    4605  378.53    4619  376.95  4641.3  372.67
  4658.1  367.98  4680.5  364.79  4769.9  353.94  4797.9  351.46  4814.6  348.27
  4828.6  347.49  4859.4  342.01  4904.1  336.72    4918  333.93  4962.8  330.11
  4971.2  329.28  4990.5  324.68  4993.3  324.18  4996.5  324.68  5015.9  329.54
  5032.4  329.49  5050.1  331.22  5090.5  332.57  5120.8  335.35  5191.5  346.89
    5242  351.87  5252.1   354.4  5322.8  363.16  5353.1  367.92  5383.4  370.13
#Mann= 3 ,-1 , 0
  4582.6     .16       0  4990.5     .07       0  4996.5     .16       0
Bank Sta=4962.8,5015.9
XS Rating Curve= 0 ,0
Exp/Cntr=0.3,0.1

Type RM Length L Ch R = 1 ,97001   ,431,431,431
BEGIN DESCRIPTION:
ALLIGATOR BRANCH 97.0
END DESCRIPTION:
XS GIS Cut Line= 3
       3662399.6     10554060.19      3662049.61     10554010.19
      3661699.57     10553810.17
#Sta/Elev= 30
  4639.1   366.4  4669.4   361.9  4679.5  359.29  4709.8  356.47  4750.2  350.99
  4770.4  347.04  4841.1  338.68  4851.2  336.48  4861.3  335.77  4871.4  333.17
  4894.5  330.31  4921.9  327.36  4952.2  326.91  4962.3  325.44  4987.1  324.88
  4989.9  324.38  4993.1  324.88  5006.3   324.9  5015.7  326.48  5043.8  325.38
  5073.3  326.26  5115.9  329.34  5153.9  329.22    5205   332.6  5234.5  336.85
    5264  342.59  5328.8  349.82  5338.2  351.92  5387.7  354.54  5395.8   355.3
#Mann= 6 ,-1 , 0
  4639.1     .16       0  4894.5     .12       0  4987.1     .07       0
  4993.1     .12       0  5115.9     .16       0  5387.7     .05       0
Bank Sta=4952.2,5015.7
XS Rating Curve= 0 ,0
Exp/Cntr=0.3,0.1

Type RM Length L Ch R = 1 ,96570   ,427,427,427
BEGIN DESCRIPTION:
ALLIGATOR BRANCH 96.0
END DESCRIPTION:
XS GIS Cut Line= 3
       3662449.6     10554010.18      3662049.61     10553660.19
      3661749.63      10553560.2
#Sta/Elev= 30
  4444.8  369.97  4572.4  352.97  4579.1  350.99  4600.9  347.94  4621.8  346.29
  4643.6  342.05  4650.3  342.42  4664.5  339.28  4685.4   337.2    4693  334.79
  4721.5   332.3  4735.7  329.11  4770.8  325.54  4793.6  324.36  4820.2  322.37
  4848.6  323.08    4867  322.22  4869.7  321.72    4873  322.22  4981.6  323.33
  4997.4  322.27  5018.5  323.75  5039.5   323.5  5071.2  326.01  5113.3  329.36
    5166  338.48  5176.6  338.84  5208.2  343.81  5229.3  345.35  5292.5  352.98
#Mann= 5 ,-1 , 0
  4444.8     .16       0  4793.6     .12       0    4867     .07       0
    4873     .12       0  4981.6     .16       0
Bank Sta=4770.8,5071.2
XS Rating Curve= 0 ,0
Exp/Cntr=0.3,0.1

Type RM Length L Ch R = 1 ,96143   ,467,467,467
BEGIN DESCRIPTION:
ALLIGATOR BRANCH 95.0
END DESCRIPTION:
XS GIS Cut Line= 3
      3662666.91     10553863.21      3662317.98     10553384.07
      3662067.99     10553233.04
#Sta/Elev= 30
  4451.5  376.76  4566.6  364.63  4579.7  361.74  4609.1  359.51  4653.1  353.12
  4665.5  350.44  4709.5  345.76  4730.4  341.08  4759.7  338.92  4780.6  334.75
    4830  329.04  4851.7  325.85  4901.9  321.61  4931.3  320.06  4981.5  319.77
  4984.7  317.89  4987.4  317.39  4990.7  317.89  5010.9  318.45    5017  321.18
  5031.7  322.46  5043.5  324.95    5082  328.17  5089.1  330.16  5155.7  336.28
  5182.9  340.04  5213.9  341.91  5250.8  345.81  5256.6  347.25  5336.3  353.63
#Mann= 5 ,-1 , 0
  4451.5     .16       0    4830     .12       0  4984.7     .07       0
  4990.7     .12       0  5043.5     .16       0
Bank Sta=4981.5,5017
XS Rating Curve= 0 ,0
Exp/Cntr=0.3,0.1

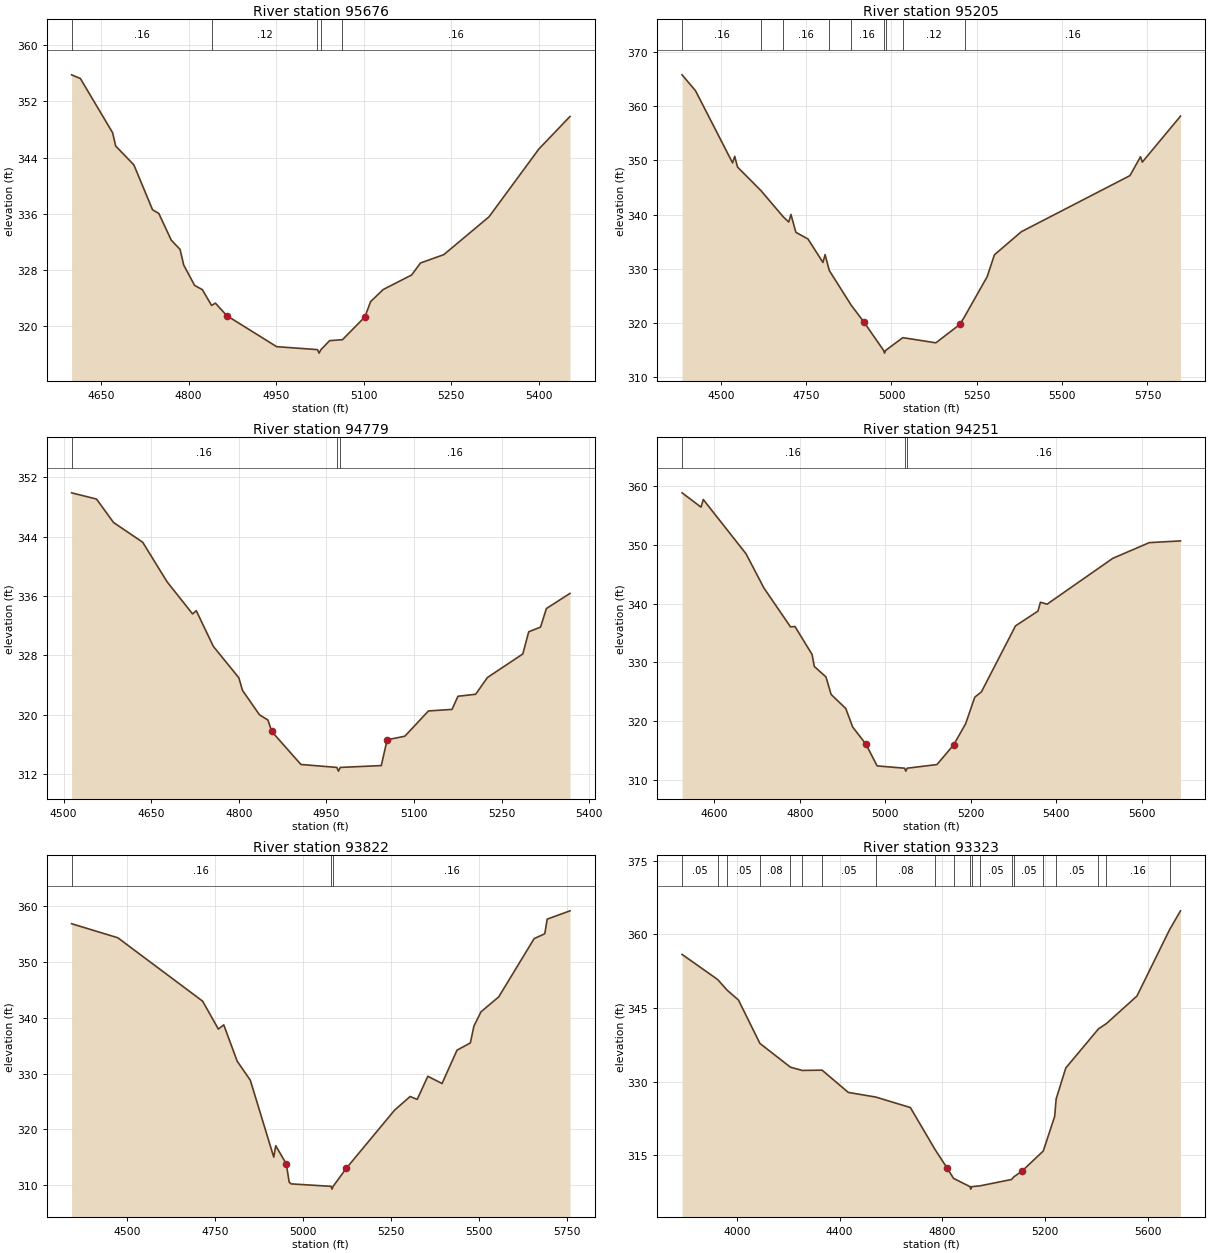
Type RM Length L Ch R = 1 ,95676   ,471,471,471
BEGIN DESCRIPTION:
ALLIGATOR BRANCH 94.0
END DESCRIPTION:
XS GIS Cut Line= 3
      3662899.58     10553160.18      3662499.61     10553010.19
      3662099.58      10553160.2
#Sta/Elev= 30
  4599.5  355.78  4614.6  355.25  4669.8  347.54  4675.1  345.64  4706.3  342.95
  4738.3  336.56    4749  336.04  4770.4  332.23  4785.5  330.91  4791.7  328.69
  4810.4  325.79  4823.8  325.17  4839.5  322.93    4846  323.26  4865.6  321.48
    4951  317.06    5021  316.64  5023.8  316.14    5027  316.64  5041.8  317.92
  5063.8  318.05  5102.3   321.3  5112.1  323.48  5133.5  325.19  5182.4  327.27
  5197.6  328.98  5237.6  330.17    5315  335.55  5400.5  345.21  5453.9  349.85
#Mann= 5 ,-1 , 0
  4599.5     .16       0  4839.5     .12       0    5021     .07       0
    5027     .12       0  5063.8     .16       0
Bank Sta=4865.6,5102.3
XS Rating Curve= 0 ,0
Exp/Cntr=0.3,0.1

Type RM Length L Ch R = 1 ,95205   ,426,426,426
BEGIN DESCRIPTION:
ALLIGATOR BRANCH 93.0
END DESCRIPTION:
XS GIS Cut Line= 4
      3663021.08     10552285.13      3662651.31     10552561.16
       3662021.1      10552524.7      3661683.58     10552670.09
#Sta/Elev= 30
  4386.5  365.75    4426  362.81  4534.4  349.53  4540.7  350.74    4549  348.76
  4618.3  344.37  4683.2  339.57  4699.1  338.63  4705.4  340.03    4720  336.73
  4755.4  335.51  4799.2  331.19  4805.5  332.63  4817.9  329.69  4881.8  323.33
  4919.8  320.16  4976.9  314.98  4979.6  314.48  4982.9  314.98  5033.1  317.33
  5130.1  316.38  5200.2  319.77    5214  321.19  5280.4  328.57  5301.5  332.59
  5380.5  336.85  5698.6  347.18  5729.5  350.66  5734.9  349.68  5846.7  358.14
#Mann= 9 ,-1 , 0
  4386.5     .16       0  4618.3     .05       0  4683.2     .16       0
  4817.9     .12       0  4881.8     .16       0  4976.9     .07       0
  4982.9     .16       0  5033.1     .12       0    5214     .16       0
Bank Sta=4919.8,5200.2
XS Rating Curve= 0 ,0
Exp/Cntr=0.3,0.1

Type RM Length L Ch R = 1 ,94779   ,528,528,528
BEGIN DESCRIPTION:
ALLIGATOR BRANCH 92.0
END DESCRIPTION:
XS GIS Cut Line= 3
      3662799.58     10551860.21      3662399.61     10552160.19
      3662049.62     10552210.19
#Sta/Elev= 30
  4513.6  349.92  4556.3  349.08  4585.4  345.92  4635.4  343.25  4677.1  337.92
  4720.8  333.58  4727.1  334.02  4756.3  329.21    4800  324.97  4806.3  323.26
  4835.4  319.97    4850  319.25  4856.3  317.73  4906.3  313.27  4967.8  312.87
  4970.6  312.37  4973.8  312.87  5043.9  313.12    5054   316.6  5084.3  317.08
  5124.7  320.49  5165.1   320.7  5175.2  322.47  5205.5  322.74  5225.7     325
  5286.3  328.18  5296.4  331.17  5316.6   331.8  5326.7  334.31  5367.1  336.35
#Mann= 3 ,-1 , 0
  4513.6     .16       0  4967.8     .07       0  4973.8     .16       0
Bank Sta=4856.3,5054
XS Rating Curve= 0 ,0
Exp/Cntr=0.3,0.1

Type RM Length L Ch R = 1 ,94251   ,429,429,429
BEGIN DESCRIPTION:
ALLIGATOR BRANCH 91.0
END DESCRIPTION:
XS GIS Cut Line= 3
      3662993.92     10551798.14      3662379.32     10551626.26
      3661926.17     10551355.41
#Sta/Elev= 30
  4524.6   358.9    4569  356.46  4574.2  357.76  4674.4  348.49    4716  342.68
  4778.3  336.04  4788.7  336.11  4828.8  331.33    4834  329.29  4861.3   327.5
  4873.3  324.52  4907.5  322.13  4923.7  318.97  4954.8  316.04  4980.9  312.33
  5045.3  311.94    5048  311.44  5051.3  311.94  5120.9  312.56    5160  315.92
    5188  319.52  5209.4  324.05  5224.9  324.95  5304.7  336.21  5357.2  338.73
    5363  340.24  5378.6  339.91  5532.3  347.73  5617.9  350.41  5690.7   350.7
#Mann= 3 ,-1 , 0
  4524.6     .16       0  5045.3     .07       0  5051.3     .16       0
Bank Sta=4954.8,5160
XS Rating Curve= 0 ,0
Exp/Cntr=0.3,0.1

Type RM Length L Ch R = 1 ,93822   ,499,499,499
BEGIN DESCRIPTION:
ALLIGATOR BRANCH 90.0
END DESCRIPTION:
XS GIS Cut Line= 3
      3663186.58     10551579.37      3662577.24     10551251.26
      3661858.51     10551167.93
#Sta/Elev= 30
  4343.2  356.87  4474.5  354.35  4715.4  342.98    4760  337.98  4775.4  338.73
  4813.6  332.21  4850.8   328.8  4917.4  315.01  4923.1  317.06  4953.1  313.78
  4961.2  310.51  4966.9  310.21  5080.1  309.77  5082.8  309.27  5086.1  309.77
  5123.5  313.01  5260.5  323.43  5304.7  325.88  5324.8  325.36    5355  329.51
  5395.3  328.21  5437.9  334.19  5475.8  335.49  5485.9  338.51    5506  341.07
  5556.4  343.75    5657   354.2  5687.2  355.07    5694  357.69  5758.8  359.18
#Mann= 3 ,-1 , 0
  4343.2     .16       0  5080.1     .07       0  5086.1     .16       0
Bank Sta=4953.1,5123.5
XS Rating Curve= 0 ,0
Exp/Cntr=0.3,0.1

Type RM Length L Ch R = 1 ,93323   ,214,214,214
BEGIN DESCRIPTION:
ALLIGATOR BRANCH 89.0
END DESCRIPTION:
XS GIS Cut Line= 2
      3663845.82     10551662.58      3662333.28     10550448.38
#Sta/Elev= 30
  3787.2  355.92  3925.4  350.82    3963  348.62  4006.7  346.63  4090.1   337.8
    4209  332.96  4254.8   332.3    4332  332.36    4434  327.83  4540.9  326.88
  4675.6  324.75  4771.7   316.2    4818  312.48  4843.6  310.33  4907.8  308.64
  4910.6  308.14  4913.8  308.64  4946.8  308.81  5069.8  310.11  5078.2  310.64
  5109.2  311.77  5192.8   315.9  5237.2  322.95  5242.9  326.49  5280.4   332.8
  5407.6  340.76  5438.7  341.85  5557.3  347.44  5684.6  360.98  5726.8  364.79
#Mann= 20 ,-1 , 0
  3787.2     .05       0  3925.4     .08       0    3963     .05       0
  4090.1     .08       0    4209     .05       0  4254.8     .08       0
    4332     .05       0  4540.9     .08       0  4771.7     .16       0
  4843.6     .08       0  4907.8     .03       0  4913.8     .08       0
  4946.8     .05       0  5069.8     .12       0  5078.2     .05       0
  5192.8     .12       0  5242.9     .05       0  5407.6     .08       0
  5438.7     .16       0  5684.6     .08       0
Bank Sta=4818,5109.2
XS Rating Curve= 0 ,0
Exp/Cntr=0.3,0.1

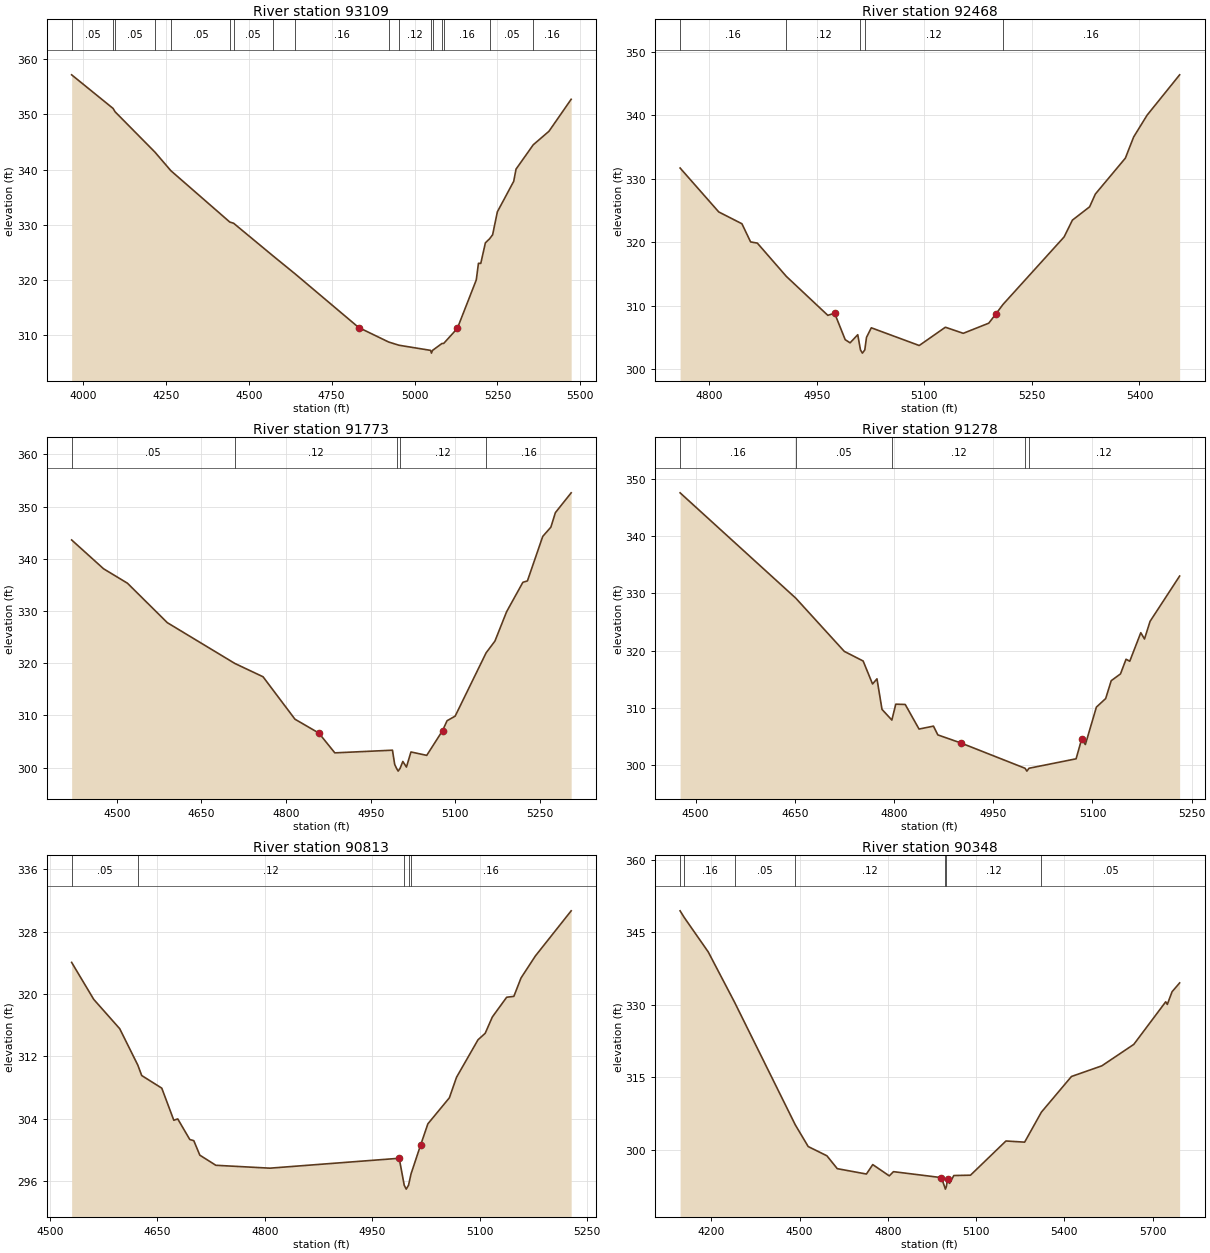
Type RM Length L Ch R = 1 ,93109   ,641,641,641
BEGIN DESCRIPTION:
ALLIGATOR BRANCH 88.0
END DESCRIPTION:
XS GIS Cut Line= 3
      3663922.18     10551454.22      3663179.13     10550919.51
      3662790.31     10550475.15
#Sta/Elev= 30
  3966.2  357.17  4091.1  351.08  4097.2  350.47  4217.5  343.15  4265.4  339.79
  4442.9  330.49  4454.5  330.27    4573  324.37    4641  321.04  4831.6  311.37
  4921.7  308.75    4953  308.16  5048.2  307.23  5050.9  306.73  5054.2  307.23
  5082.4  308.47  5087.9  308.49    5129  311.22    5186  319.99  5192.6  323.01
  5199.6  322.99  5213.5  326.72  5226.1  327.45  5235.3  328.18  5249.6  332.34
  5298.9  337.87  5305.9  340.08  5357.8  344.49  5405.2  346.94  5472.1  352.74
#Mann= 17 ,-1 , 0
  3966.2     .05       0  4091.1     .08       0  4097.2     .05       0
  4217.5      .1       0  4265.4     .05       0  4442.9     .08       0
  4454.5     .05       0    4573     .08       0    4641     .16       0
  4921.7     .08       0    4953     .12       0  5048.2     .07       0
  5054.2     .12       0  5082.4     .08       0  5087.9     .16       0
  5226.1     .05       0  5357.8     .16       0
Bank Sta=4831.6,5129
XS Rating Curve= 0 ,0
Exp/Cntr=0.3,0.1

Type RM Length L Ch R = 1 ,92468   ,695,695,695
BEGIN DESCRIPTION:
ALLIGATOR BRANCH 87.0
END DESCRIPTION:
XS GIS Cut Line= 3
      3663699.62     10550760.21      3663599.61     10550510.19
       3663449.6     10550110.17
#Sta/Elev= 30
  4759.5  331.69  4813.4  324.77  4845.7  322.91  4857.8  320.05  4867.2  319.86
  4907.7  314.61  4965.5  308.48  4974.9  308.83  4989.7  304.65  4996.5  304.15
  5007.2  305.43    5011  303.03  5013.7  302.53    5017  303.03  5019.4  305.01
  5026.1  306.52  5092.9  303.73  5129.4  306.61  5154.3  305.65  5189.9  307.25
  5199.7  308.69  5209.8  310.21  5294.9  320.83  5306.5  323.48  5330.5  325.58
  5338.5  327.59  5380.3  333.24  5391.9  336.58  5410.6  340.01    5456  346.37
#Mann= 5 ,-1 , 0
  4759.5     .16       0  4907.7     .12       0    5011     .07       0
    5017     .12       0  5209.8     .16       0
Bank Sta=4974.9,5199.7
XS Rating Curve= 0 ,0
Exp/Cntr=0.3,0.1

Type RM Length L Ch R = 1 ,91773   ,495,495,495
BEGIN DESCRIPTION:
ALLIGATOR BRANCH 86.0
END DESCRIPTION:
XS GIS Cut Line= 3
       3664199.6     10550560.18      3663799.61     10550160.19
      3663549.63      10549960.2
#Sta/Elev= 30
  4419.8  343.61  4476.4  338.09  4518.8  335.32  4589.5  327.76  4709.2  319.95
  4759.2   317.4  4815.8  309.27  4858.2  306.61  4886.5  302.82  4988.7  303.33
  4992.7  300.59  4996.1  299.82  4998.8  299.32  5002.1  299.82  5007.1  301.17
  5013.5   300.1  5021.5  302.99  5049.5  302.34  5077.5  307.07  5085.5  308.97
  5099.9  309.86  5154.8  321.99  5170.4  324.23  5191.2  329.88    5220   335.5
    5228  335.76  5255.2  344.29  5269.6  346.06  5277.6  348.84  5305.6  352.64
#Mann= 5 ,-1 , 0
  4419.8     .05       0  4709.2     .12       0  4996.1     .07       0
  5002.1     .12       0  5154.8     .16       0
Bank Sta=4858.2,5077.5
XS Rating Curve= 0 ,0
Exp/Cntr=0.3,0.1

Type RM Length L Ch R = 1 ,91278   ,465,465,465
BEGIN DESCRIPTION:
ALLIGATOR BRANCH 85.0
END DESCRIPTION:
XS GIS Cut Line= 3
      3664499.62      10550360.2      3664099.61     10550010.19
      3663999.62     10549810.21
#Sta/Elev= 30
  4476.7  347.51  4651.6  329.13  4724.9  319.85  4753.4  318.17  4767.6  314.16
  4774.3  315.06  4781.9  309.73  4796.8  307.87  4802.7  310.64    4817  310.59
  4837.9   306.3  4859.7  306.81  4866.3  305.28  4901.9  303.84  4998.1  299.46
  5000.9  298.96  5004.1  299.46  5075.3  301.11  5083.7  304.55  5089.3   303.6
    5106  310.13    5120  311.62  5128.4  314.74  5142.4  315.92  5150.8  318.48
  5156.4  318.13  5173.1  323.11  5178.7  322.01  5187.1  325.09  5231.8  332.99
#Mann= 5 ,-1 , 0
  4476.7     .16       0  4651.6     .05       0  4796.8     .12       0
  4998.1     .07       0  5004.1     .12       0
Bank Sta=4901.9,5083.7
XS Rating Curve= 0 ,0
Exp/Cntr=0.3,0.1

Type RM Length L Ch R = 1 ,90813   ,465,465,465
BEGIN DESCRIPTION:
ALLIGATOR BRANCH 84.0
END DESCRIPTION:
XS GIS Cut Line= 3
      3664549.61      10550060.2      3664349.61     10549660.19
      3664099.63     10549660.19
#Sta/Elev= 30
  4530.4  324.04  4561.2   319.3  4597.5  315.53  4622.7  310.87  4628.2  309.52
  4656.2   307.9    4673  303.78  4678.5  303.95  4695.3  301.31  4700.9  301.16
  4709.3   299.3  4731.7     298  4807.1  297.63  4987.6   298.9  4994.6  295.44
  4997.4  294.94  5000.6  295.44  5004.1   296.9  5017.6  300.63  5027.6  303.32
  5057.6  306.66  5067.6   309.3  5097.6  314.11  5107.6  314.94  5117.6  317.04
  5137.6  319.57  5147.6  319.68  5157.6  322.04  5177.6  324.86  5227.6  330.66
#Mann= 5 ,-1 , 0
  4530.4     .05       0  4622.7     .12       0  4994.6     .07       0
  5000.6     .12       0  5004.1     .16       0
Bank Sta=4987.6,5017.6
XS Rating Curve= 0 ,0
Exp/Cntr=0.3,0.1

Type RM Length L Ch R = 1 ,90348   ,495,495,495
BEGIN DESCRIPTION:
ALLIGATOR BRANCH 83.0
END DESCRIPTION:
XS GIS Cut Line= 3
      3665296.88      10550028.2      3664433.14     10549216.54
      3663955.68      10549029.9
#Sta/Elev= 30
  4093.7  349.43  4107.8  348.05  4189.3  340.94  4278.8  330.54  4485.1  305.21
  4529.1  300.71  4592.7   298.8  4627.9  296.14    4727  295.03  4748.5  296.98
  4804.7  294.65  4818.9  295.52  4981.9  294.29  4992.7  292.41  4995.4  291.91
  4998.7  292.41    5003  294.07  5009.8   293.1    5024  294.72  5080.7  294.79
  5201.3  301.86  5264.8  301.62  5321.6  307.81  5423.9  315.19  5527.1  317.39
  5635.7  321.82  5744.3  330.63  5749.7  330.08  5765.9  332.71  5791.6  334.53
#Mann= 7 ,-1 , 0
  4093.7     .05       0  4107.8     .16       0  4278.8     .05       0
  4485.1     .12       0  4992.7     .07       0  4998.7     .12       0
  5321.6     .05       0
Bank Sta=4981.9,5003
XS Rating Curve= 0 ,0
Exp/Cntr=0.3,0.1

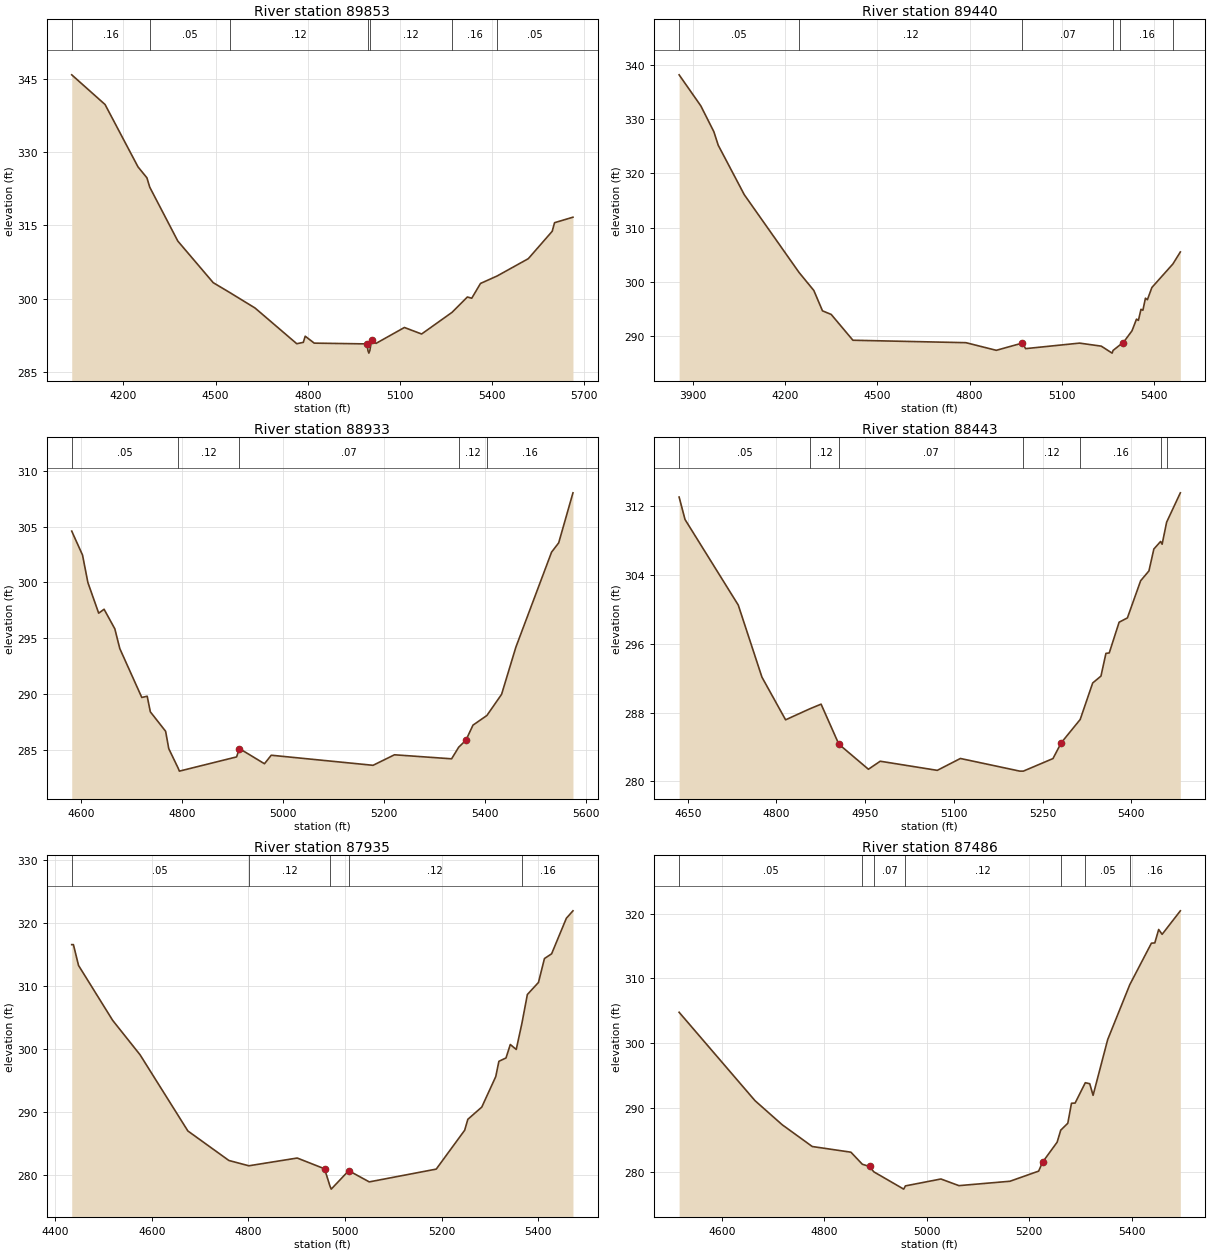
Type RM Length L Ch R = 1 ,89853   ,413,413,413
BEGIN DESCRIPTION:
ALLIGATOR BRANCH 82.0
END DESCRIPTION:
XS GIS Cut Line= 3
       3665496.5     10549815.48      3664875.85     10548951.78
      3664446.19     10548578.54
#Sta/Elev= 30
  4031.4  345.88    4140  339.79  4247.3     327  4276.3  324.76  4285.6  322.83
    4377  311.78  4492.3  303.25  4546.9   301.2  4628.6  298.05  4764.4  290.73
  4785.8  291.01  4791.9  292.27  4821.4  290.85  4993.3  290.69  4996.4   289.3
  4999.2   288.8  5002.4   289.3    5008  291.41  5022.7   290.8  5115.1  294.06
  5171.1  292.72  5269.9  297.15  5320.1  300.31  5334.4  300.06  5362.9  303.09
  5417.3  304.63  5518.6  308.17  5596.5  313.79  5604.1  315.55  5664.1  316.68
#Mann= 7 ,-1 , 0
  4031.4     .16       0  4285.6     .05       0  4546.9     .12       0
  4996.4     .07       0  5002.4     .12       0  5269.9     .16       0
  5417.3     .05       0
Bank Sta=4993.3,5008
XS Rating Curve= 0 ,0
Exp/Cntr=0.3,0.1

Type RM Length L Ch R = 1 ,89440   ,507,507,507
BEGIN DESCRIPTION:
ALLIGATOR BRANCH 81.0
END DESCRIPTION:
XS GIS Cut Line= 3
      3665999.62      10549560.2      3665199.61     10548760.19
      3664799.59     10548460.18
#Sta/Elev= 30
  3854.5  338.21  3925.2  332.47  3967.6   327.7  3981.8  325.21  4066.6  316.07
  4244.9   301.7  4292.9  298.38  4321.2  294.61  4349.5  293.95  4420.2  289.18
  4787.9  288.73  4886.9  287.32  4971.7  288.66  4982.3  287.63  5157.8  288.65
  5228.6  288.09  5263.8   286.8    5267   287.3  5290.4  288.36  5299.4  288.69
  5328.6  290.93  5343.2  293.08  5349.4  292.85  5357.8  294.89    5364  294.72
  5372.3  296.95  5378.6  296.66  5393.2  298.92  5461.6  303.27  5485.9  305.49
#Mann= 6 ,-1 , 0
  3854.5     .05       0  4244.9     .12       0  4971.7     .07       0
    5267     .12       0  5290.4     .16       0  5461.6     .05       0
Bank Sta=4971.7,5299.4
XS Rating Curve= 0 ,0
Exp/Cntr=0.3,0.1

Type RM Length L Ch R = 1 ,88933   ,490,490,490
BEGIN DESCRIPTION:
ALLIGATOR BRANCH 80.0
END DESCRIPTION:
XS GIS Cut Line= 3
      3665799.61     10548210.19      3665399.61     10548360.19
       3664999.6     10547960.18
#Sta/Elev= 30
  4581.1  304.59  4602.5  302.45  4613.1     300  4634.5  297.26  4645.2  297.61
  4666.5  295.86  4676.3   294.1  4719.9  289.73  4730.6  289.84  4736.8  288.45
  4767.1  286.71  4773.3  285.16    4792  283.41  4794.4  283.15  4907.7  284.42
  4913.1  285.17  4962.9  283.81  4976.3  284.57    5178  283.67  5220.4  284.61
  5333.6  284.25  5347.7  285.29  5361.9  285.91    5376  287.26  5403.5  288.12
  5432.6  290.01  5460.8  294.21  5531.6  302.71  5545.7  303.54    5574  308.01
#Mann= 5 ,-1 , 0
  4581.1     .05       0    4792     .12       0  4913.1     .07       0
  5347.7     .12       0  5403.5     .16       0
Bank Sta=4913.1,5361.9
XS Rating Curve= 0 ,0
Exp/Cntr=0.3,0.1

Type RM Length L Ch R = 1 ,88443   ,508,508,508
BEGIN DESCRIPTION:
ALLIGATOR BRANCH 79.0
END DESCRIPTION:
XS GIS Cut Line= 3
      3665849.65     10547960.19      3665449.61     10547960.19
      3665049.57     10547760.17
#Sta/Elev= 30
  4635.4  313.03  4645.4  310.42  4735.4  300.48  4775.4  292.11  4815.4  287.15
  4856.7  288.44  4875.4  288.97  4905.4  284.32  4955.4  281.41  4975.4  282.34
  5071.8  281.28  5110.9  282.66  5211.3  281.19  5217.3  281.19  5267.4  282.65
  5281.4  284.49  5313.4  287.19  5334.5  291.43  5348.5  292.23  5356.9  294.87
  5362.5  294.92  5379.2  298.49  5393.2  298.99  5415.6  303.31  5429.6  304.45
  5437.9  306.99  5449.3  307.87  5451.9  307.55  5459.5  310.11  5482.7  313.52
#Mann= 7 ,-1 , 0
  4635.4     .05       0  4856.7     .12       0  4905.4     .07       0
  5217.3     .12       0  5313.4     .16       0  5449.3     .12       0
  5459.5     .16       0
Bank Sta=4905.4,5281.4
XS Rating Curve= 0 ,0
Exp/Cntr=0.3,0.1

Type RM Length L Ch R = 1 ,87935   ,449,449,449
BEGIN DESCRIPTION:
ALLIGATOR BRANCH 78.0
END DESCRIPTION:
XS GIS Cut Line= 3
       3665899.6     10547910.18      3665499.61     10547510.19
      3665099.59     10547260.18
#Sta/Elev= 30
  4434.5  316.62    4438  316.62  4448.6  313.31  4519.3  304.58  4575.9  299.12
  4674.9  287.01  4759.8  282.32  4801.1  281.48  4901.2  282.71  4957.8     281
  4968.9  278.27  4971.6  277.77  5007.8   280.7  5050.3  278.92  5188.9  280.95
  5247.8  287.13  5254.3  288.86  5283.2  290.81  5312.1  295.65  5318.6  298.08
  5333.3  298.61  5342.2  300.75  5354.5  299.96  5366.3  304.14  5377.5  308.69
  5400.5  310.61  5412.9  314.41  5427.7  315.16  5458.3  320.82  5471.9  321.99
#Mann= 5 ,-1 , 0
  4434.5     .05       0  4801.1     .12       0  4968.9     .07       0
  5007.8     .12       0  5366.3     .16       0
Bank Sta=4957.8,5007.8
XS Rating Curve= 0 ,0
Exp/Cntr=0.3,0.1

Type RM Length L Ch R = 1 ,87486   ,480,480,480
BEGIN DESCRIPTION:
ALLIGATOR BRANCH 77.0
END DESCRIPTION:
XS GIS Cut Line= 3
      3666099.65     10547360.21      3665699.61     10547160.19
      3665349.58     10546760.16
#Sta/Elev= 30
  4516.6  304.75  4664.8  291.06  4717.9  287.33  4776.6  283.96  4852.1  283.08
  4874.4  281.21  4888.4  280.87  4896.8  280.04  4955.2  277.36  4958.5  277.86
  5027.9  278.93    5063   277.9  5162.7  278.58  5218.7  280.15  5226.3  281.53
  5254.8  284.63  5261.8  286.49  5275.6  287.56  5282.8  290.66  5289.9  290.69
  5309.8  293.84  5318.4  293.69    5325  291.89  5353.5  300.52  5396.7  309.03
  5438.9  315.45  5445.5  315.49  5453.1  317.57  5459.8  316.82  5495.4  320.46
#Mann= 7 ,-1 , 0
  4516.6     .05       0  4874.4     .12       0  4896.8     .07       0
  4958.5     .12       0  5261.8     .16       0  5309.8     .05       0
  5396.7     .16       0
Bank Sta=4888.4,5226.3
XS Rating Curve= 0 ,0
Exp/Cntr=0.3,0.1