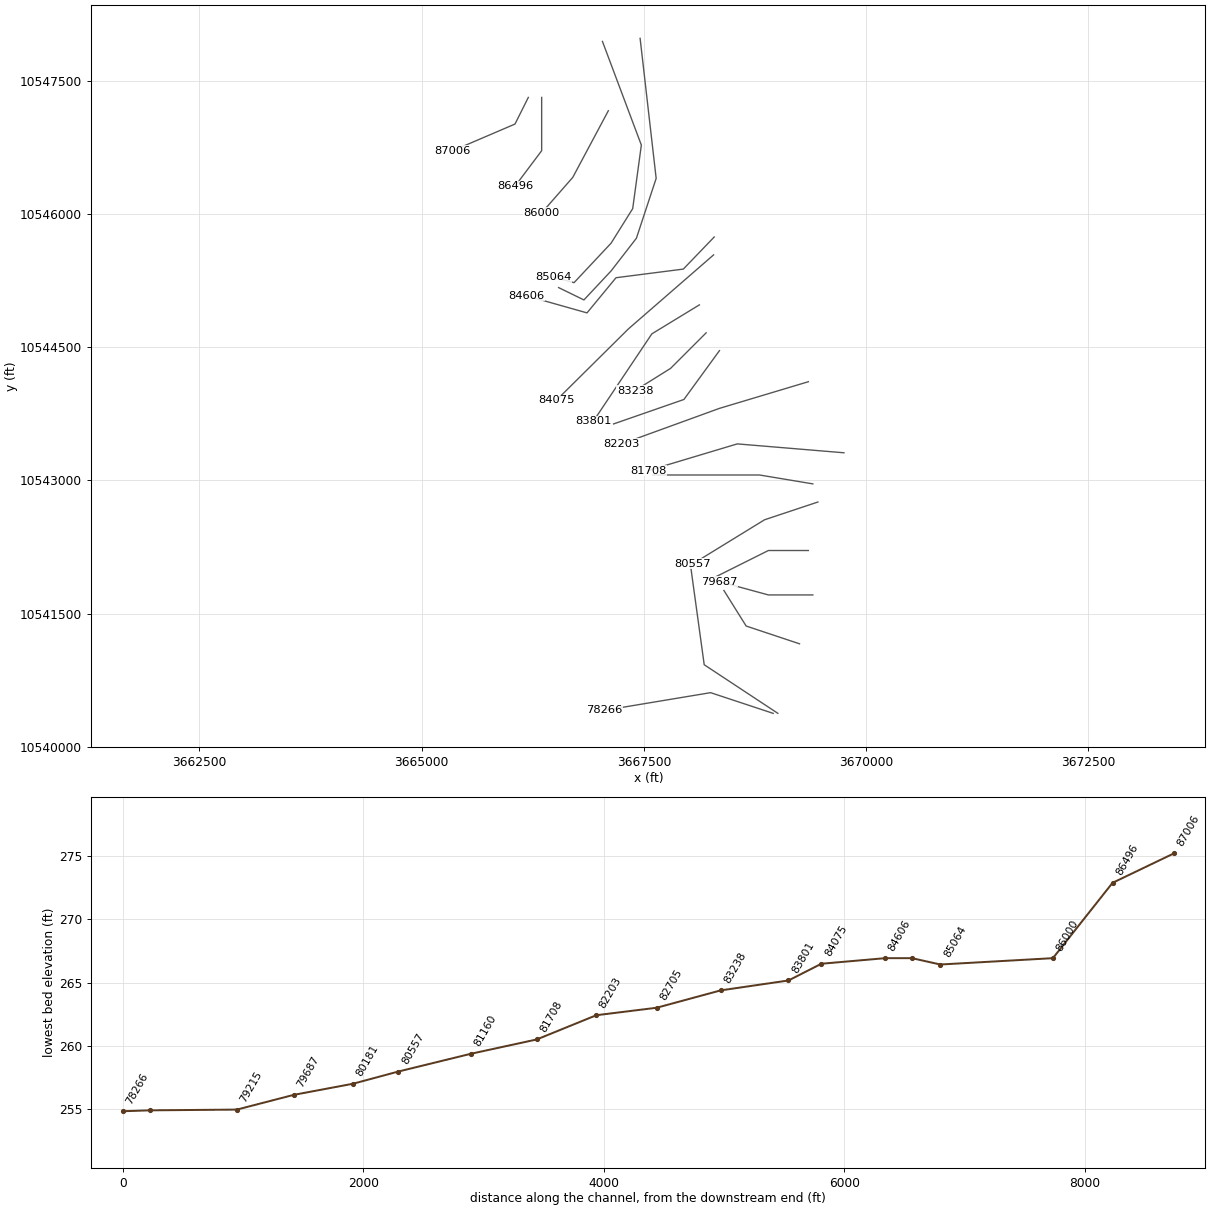
HEC-RAS study ALLIGATOR BRANCH.prj: ALLIGATOR BRANCH Base Level Engineering

--- ALLIGATOR BRANCH.g01 (geometry) --- (continued)

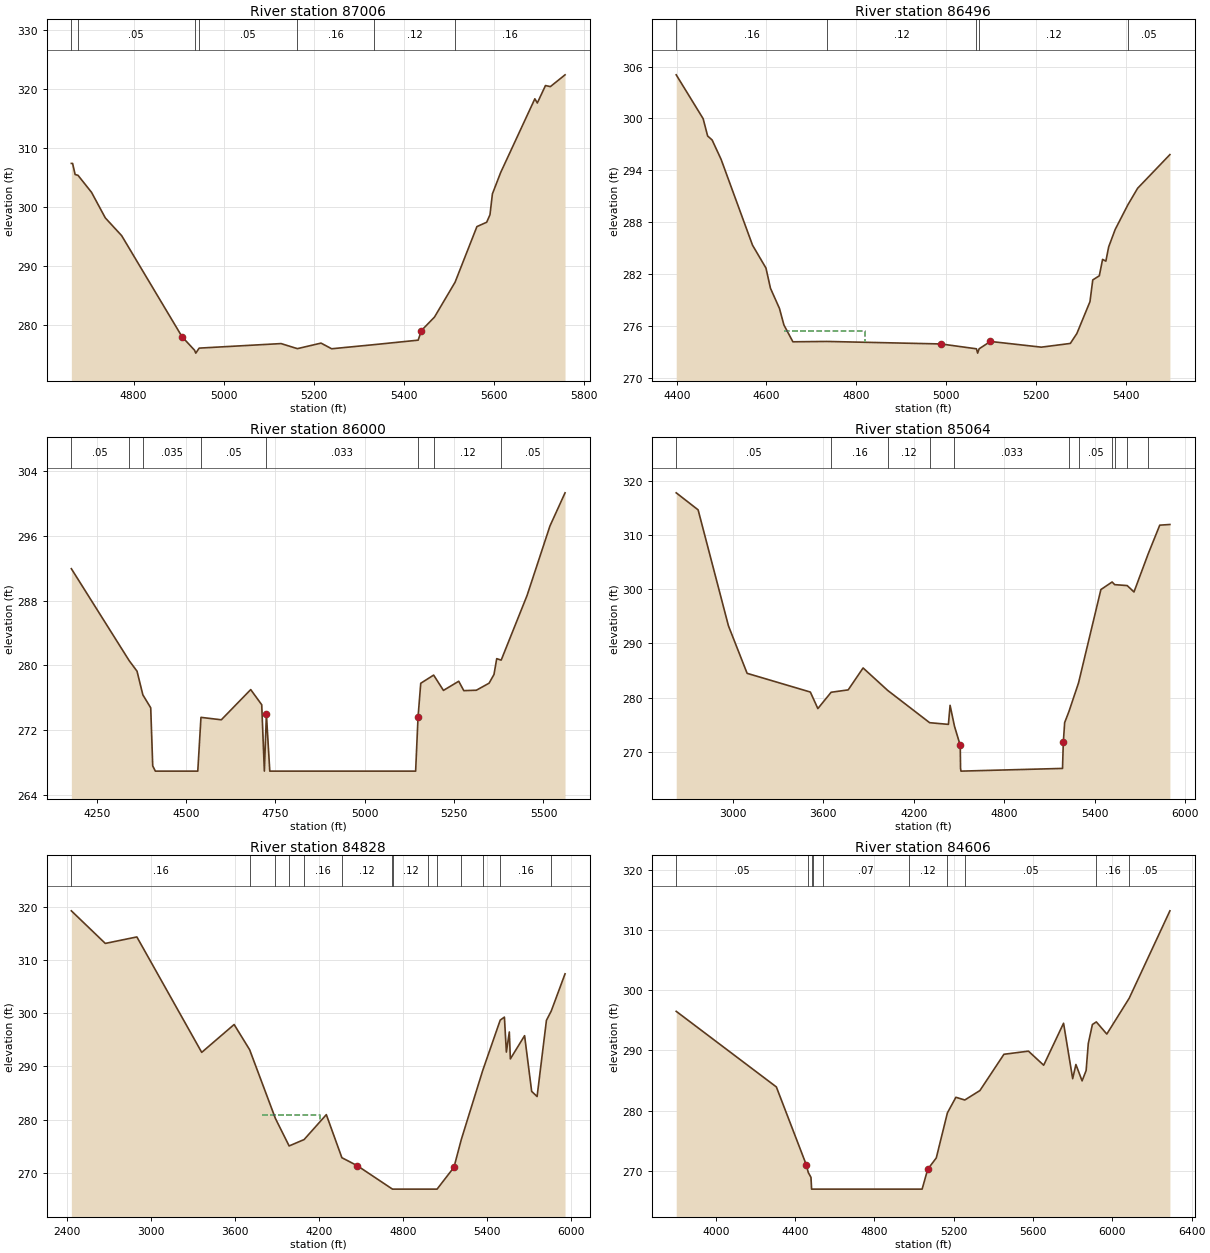
Type RM Length L Ch R = 1 ,87006   ,510,510,510
BEGIN DESCRIPTION:
ALLIGATOR BRANCH 76.0
END DESCRIPTION:
XS GIS Cut Line= 3
      3666199.62     10547310.22      3666049.61     10547010.19
      3665349.63      10546710.2
#Sta/Elev= 30
  4661.8  307.39  4664.6  307.39  4670.2  305.51  4676.6  305.37  4706.6  302.49
  4737.3  298.14  4773.6  295.13  4907.8  277.97  4935.5  275.69  4938.3  275.19
  4945.8  276.04  5127.8  276.81  5164.1  275.95  5216.6  276.89  5240.2  275.93
  5334.5  276.63  5432.4  277.39  5439.7  279.03  5468.7  281.31  5514.4  287.22
    5563  296.67  5584.7  297.41    5592  298.68  5597.4  302.22  5615.6  305.82
  5691.7  318.36  5697.2  317.65  5715.3  320.61  5726.2  320.43  5758.8  322.43
#Mann= 7 ,-1 , 0
  4661.8     .16       0  4676.6     .05       0  4935.5     .07       0
  4945.8     .05       0  5164.1     .16       0  5334.5     .12       0
  5514.4     .16       0
Bank Sta=4907.8,5439.7
XS Rating Curve= 0 ,0
Exp/Cntr=0.3,0.1

Type RM Length L Ch R = 1 ,86496   ,496,496,496
BEGIN DESCRIPTION:
ALLIGATOR BRANCH 75.0
END DESCRIPTION:
XS GIS Cut Line= 3
      3666349.61     10547310.17      3666349.61     10546710.19
       3666049.6     10546310.17
#Sta/Elev= 30
  4398.9  305.04  4458.9  299.97  4468.9  297.97  4478.9  297.51  4498.9  295.27
  4568.9  285.35  4598.9   282.7  4608.9  280.37  4628.9  278.04  4638.9  276.12
  4658.9  274.18    4735  274.22  4988.9  273.93  5067.8  273.37  5070.5  272.87
  5073.8  273.37  5098.9  274.22  5212.4  273.56    5277  273.99  5291.6  275.14
  5320.8  278.82    5327  281.33  5341.6  281.81  5348.9  283.71  5356.2   283.5
  5362.4  285.14    5377  287.17  5405.3  290.02    5427  291.93  5498.9  295.82
#Mann= 5 ,-1 , 0
  4398.9     .16       0    4735     .12       0  5067.8     .07       0
  5073.8     .12       0  5405.3     .05       0
#XS Ineff= 1 ,-1
 4637.94 4818.51  275.39
Permanent Ineff=
       F
Bank Sta=4988.9,5098.9
XS Rating Curve= 0 ,0
Exp/Cntr=0.3,0.1

Type RM Length L Ch R = 1 ,86000   ,936,936,936
BEGIN DESCRIPTION:
ALLIGATOR BRANCH 74.0
END DESCRIPTION:
XS GIS Cut Line= 3
      3667099.61     10547160.19      3666699.61     10546410.19
      3666349.61     10546010.19
#Sta/Elev= 30
  4178.9  291.93  4340.8  280.57  4362.7  279.27    4379  276.35    4401  274.75
  4406.6  267.58  4413.9  266.93  4532.7  266.93  4541.6  273.57  4598.6  273.27
  4680.8     277  4711.6  275.13    4719  266.93  4724.7  273.95  4734.2  266.93
  5142.3  266.93    5149  273.57  5156.6  277.78  5192.7  278.79  5220.1   276.9
  5262.9  278.03  5277.1  276.87  5312.2  276.92  5347.8  277.79  5361.6  278.87
  5369.2  280.82  5381.7  280.64  5454.1  288.62  5518.2  297.21  5560.4   301.3
#Mann= 8 ,-1 , 0
  4178.9     .05       0  4340.8     .16       0    4379    .035       0
  4541.6     .05       0  4724.7    .033       0    5149     .05       0
  5192.7     .12       0  5381.7     .05       0
#XS Ineff= 1 ,-1
 4347.27 4624.55  274.11
Permanent Ineff=
       F
Bank Sta=4724.7,5149
XS Rating Curve= 0 ,0
Exp/Cntr=0.3,0.1

Type RM Length L Ch R = 1 ,85064   ,236,236,236
BEGIN DESCRIPTION:
ALLIGATOR BRANCH 73.0
END DESCRIPTION:
XS GIS Cut Line= 6
       3667033.3     10547940.33       3667470.8     10546773.68
      3667373.58      10546058.4      3667130.52     10545669.51
      3666713.85     10545225.06      3666484.68     10545287.57
#Sta/Elev= 30
  2624.2  317.74  2769.4   314.6  2970.6  293.21  3094.3  284.46  3513.5  281.01
  3563.3  277.96  3651.2  280.97  3764.4  281.41  3863.2  285.45    4026  281.32
  4304.4  275.36  4428.8  275.05  4439.9  278.56  4469.1  274.71  4507.3  271.18
  4509.3  266.93  4512.1  266.43  5185.4  266.93 5190.62  271.71  5199.6  275.38
  5227.9  277.42  5291.4  282.68  5439.9  299.91  5514.2   301.3  5531.4  300.81
  5614.2  300.64  5659.2  299.46  5753.3  306.48  5830.1  311.78  5897.4   311.9
#Mann= 11 ,-1 , 0
  2624.2     .05       0  3651.2     .16       0    4026     .12       0
  4304.4     .16       0  4469.1    .033       0  5227.9     .16       0
  5291.4     .05       0  5514.2     .08       0  5531.4     .05       0
  5614.2     .16       0  5753.3     .05       0
Bank Sta=4507.3,5190.62
XS Rating Curve= 0 ,0
Exp/Cntr=0.3,0.1

Type RM Length L Ch R = 1 ,84828   ,222,222,222
BEGIN DESCRIPTION:
ALLIGATOR BRANCH 72.0
END DESCRIPTION:
XS GIS Cut Line= 6
      3667456.91     10547975.08      3667637.46     10546398.68
      3667415.24     10545725.06      3667130.52     10545357.01
      3666824.96     10545030.62       3666540.2     10545169.53
#Sta/Elev= 30
  2433.6  319.27  2676.1  313.14  2901.5  314.36  3364.5  292.65    3596  297.89
  3706.7  293.15  3890.3  280.25  3988.6  275.05  4095.5  276.25  4254.3  280.94
  4365.3  272.84  4476.5  271.32  4726.6  266.93  4732.6  266.93  4978.9  266.93
  5045.1  266.93  5165.6  271.04  5218.3  276.28  5370.6  289.21  5496.1  298.72
  5525.9  299.28    5540  292.71    5561  296.49  5568.4  291.42    5670  295.79
  5720.6  285.31  5759.3  284.35    5826  298.67  5860.7  300.45  5958.9  307.42
#Mann= 14 ,-1 , 0
  2433.6     .16       0  3706.7     .05       0  3890.3     .16       0
  3988.6     .12       0  4095.5     .16       0  4365.3     .12       0
  4726.6     .07       0  4732.6     .12       0  4978.9     .07       0
  5045.1     .12       0  5218.3     .16       0  5370.6     .05       0
  5496.1     .16       0  5860.7     .05       0
#XS Ineff= 1 ,-1
 3797.73 4206.82  280.95
Permanent Ineff=
       F
Bank Sta=4476.5,5165.6
XS Rating Curve= 0 ,0
Exp/Cntr=0.3,0.1

Type RM Length L Ch R = 1 ,84606   ,531,531,531
BEGIN DESCRIPTION:
ALLIGATOR BRANCH 71.0
END DESCRIPTION:
XS GIS Cut Line= 5
      3668290.22     10545738.93      3667943.02     10545377.84
      3667186.08     10545280.62      3666859.69     10544884.79
      3666173.35      10545078.9
#Sta/Elev= 30
  3799.9  296.49  4305.1  283.92  4455.5  271.02  4466.2  269.69  4479.7  268.88
  4482.8  266.93  4488.8  266.93  4538.2  266.93  4973.2  266.93  5040.3  266.93
  5068.7  270.24  5111.7  272.11  5167.9  279.61  5210.7   282.2  5255.6  281.75
  5331.9  283.32  5453.1  289.35  5576.8  289.87  5653.5  287.53  5753.8  294.51
  5799.8  285.29  5816.1  287.65  5847.3  284.93  5867.7  286.65  5878.5  291.13
  5899.3   294.3  5919.2  294.73    5972  292.71    6085  298.67  6290.3   313.2
#Mann= 10 ,-1 , 0
  3799.9     .05       0  4466.2     .12       0  4482.8     .07       0
  4488.8     .12       0  4538.2     .07       0  4973.2     .12       0
  5167.9     .07       0  5255.6     .05       0  5919.2     .16       0
    6085     .05       0
Bank Sta=4455.5,5068.7
XS Rating Curve= 0 ,0
Exp/Cntr=0.3,0.1

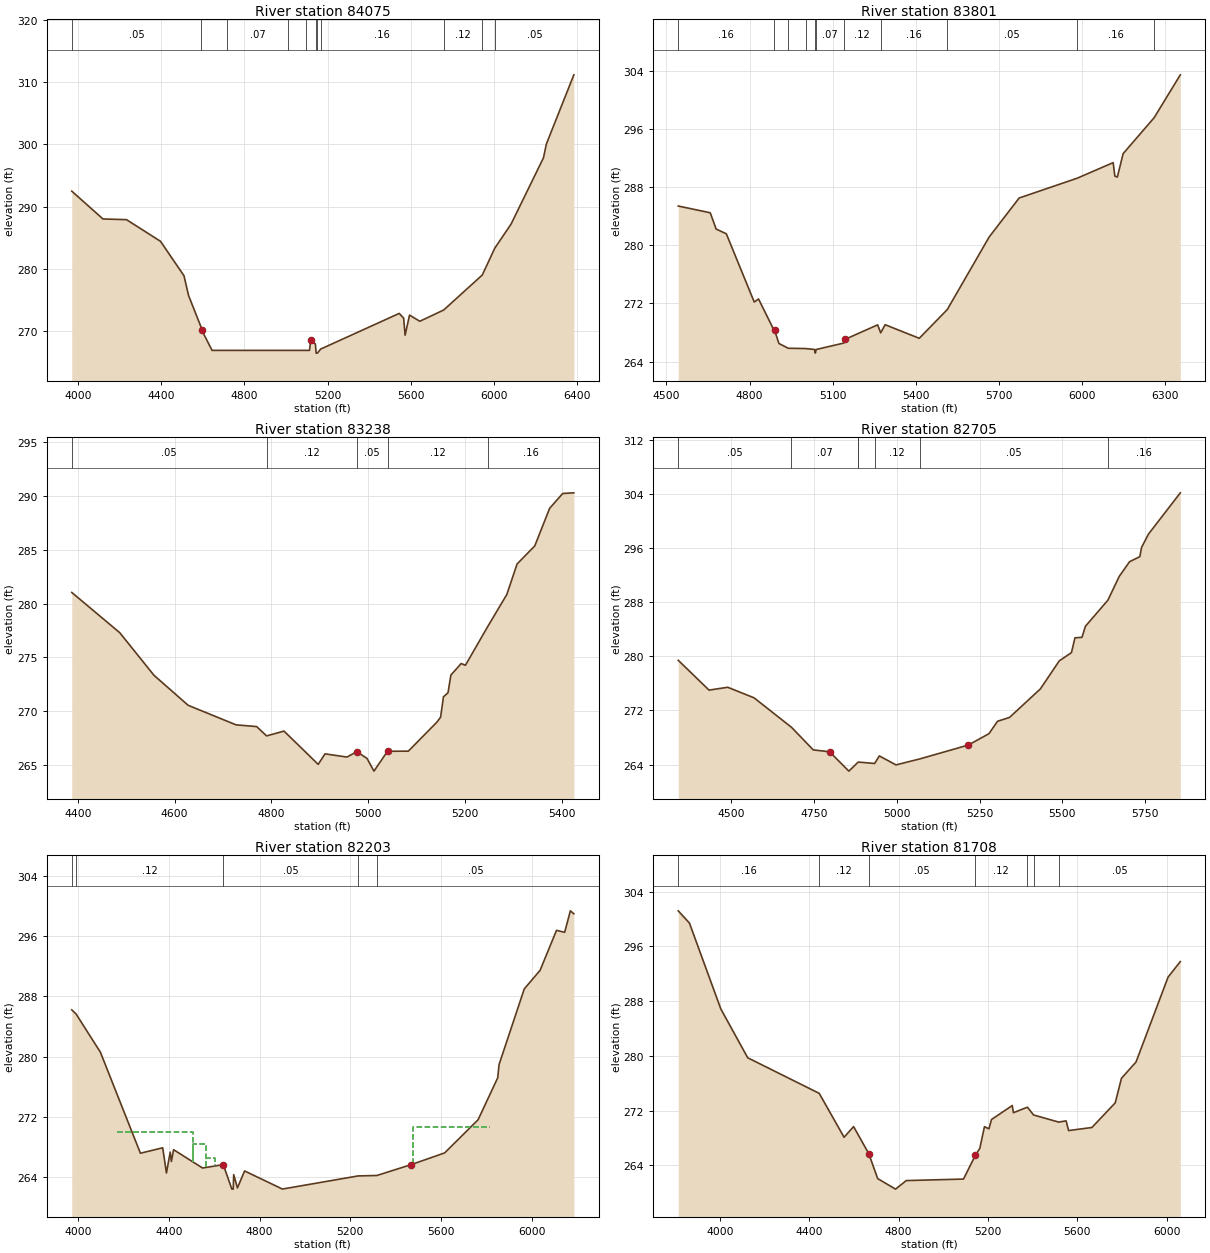
Type RM Length L Ch R = 1 ,84075   ,274,274,274
BEGIN DESCRIPTION:
ALLIGATOR BRANCH 70.0
END DESCRIPTION:
XS GIS Cut Line= 3
      3668283.27     10545537.54      3667324.96     10544704.23
      3666513.52     10543899.72
#Sta/Elev= 30
    3971  292.47    4121  288.01    4234   287.9  4397.3  284.43  4510.3   278.9
  4532.1  275.75  4591.7  270.72  4595.7  270.18  4645.1  266.93  4718.4  266.93
  5010.6  266.93  5098.7  266.93  5113.2  266.93  5119.8  268.61  5141.7  267.94
  5145.3  266.49  5151.3  266.49  5167.1  267.14  5544.5  272.86  5565.8   272.1
  5572.8  269.37  5594.1  272.59  5643.5   271.6  5758.4  273.41  5943.6  279.02
  6003.8  283.33    6082  287.19  6237.5  297.81  6251.7  300.04  6383.6  311.13
#Mann= 11 ,-1 , 0
    3971     .05       0  4591.7     .12       0  4718.4     .07       0
  5010.6     .12       0  5098.7     .05       0  5145.3     .07       0
  5151.3     .05       0  5167.1     .16       0  5758.4     .12       0
  5943.6     .16       0  6003.8     .05       0
Bank Sta=4595.7,5119.8
XS Rating Curve= 0 ,0
Exp/Cntr=0.3,0.1

Type RM Length L Ch R = 1 ,83801   ,563,563,563
BEGIN DESCRIPTION:
ALLIGATOR BRANCH 69.0
END DESCRIPTION:
XS GIS Cut Line= 3
       3668123.6     10544975.08      3667588.85     10544648.68
      3666929.98     10543663.84
#Sta/Elev= 30
  4542.6  285.41  4658.1  284.48  4679.4  282.24  4716.1  281.59  4816.8   272.2
  4832.3  272.62    4889  268.26  4890.4  268.31  4905.8   266.5  4939.3  265.84
  5002.1   265.8  5034.4  265.67  5037.2  265.17  5040.4  265.67  5140.4  266.56
  5144.8  267.07  5262.1  269.06    5273  267.96  5289.1  269.08  5412.2  267.21
  5513.2  271.16  5664.4  281.15  5772.5  286.51  5982.2  289.24  6111.8  291.38
  6117.8  289.53  6126.8  289.39  6147.8  292.62  6259.6  297.56    6354  303.46
#Mann= 11 ,-1 , 0
  4542.6     .16       0    4889     .07       0  4939.3     .12       0
  5002.1     .07       0  5034.4     .07       0  5040.4     .07       0
  5140.4     .12       0    5273     .16       0  5513.2     .05       0
  5982.2     .16       0  6259.6     .05       0
Bank Sta=4890.4,5144.8
XS Rating Curve= 0 ,0
Exp/Cntr=0.3,0.1

Type RM Length L Ch R = 1 ,83238   ,533,533,533
BEGIN DESCRIPTION:
ALLIGATOR BRANCH 68.0
END DESCRIPTION:
XS GIS Cut Line= 3
      3668199.64     10544660.22      3667799.61     10544260.19
      3667399.63      10544010.2
#Sta/Elev= 30
  4387.7  281.03  4486.7  277.29  4557.5  273.32  4628.2  270.52  4727.2   268.7
  4769.6  268.54  4790.3  267.67  4826.2  268.12  4896.9  265.02    4911     266
  4956.4   265.7  4976.4   266.2  4997.7  265.58  5012.1  264.39  5040.1  266.24
  5083.1  266.25  5142.1  268.95  5149.8  269.42  5155.7  271.31  5165.1  271.69
    5171  273.33  5192.2  274.41  5201.1  274.25  5246.7  277.82  5286.6  280.84
  5307.8  283.68  5344.4  285.37    5375  288.86  5402.1  290.25  5425.1  290.31
#Mann= 5 ,-1 , 0
  4387.7     .05       0  4790.3     .12       0  4976.4     .05       0
  5040.1     .12       0  5246.7     .16       0
Bank Sta=4976.4,5040.1
XS Rating Curve= 0 ,0
Exp/Cntr=0.3,0.1

Type RM Length L Ch R = 1 ,82705   ,502,502,502
BEGIN DESCRIPTION:
ALLIGATOR BRANCH 67.0
END DESCRIPTION:
XS GIS Cut Line= 3
       3668349.6     10544460.17      3667949.61     10543910.19
      3667158.88     10543634.99
#Sta/Elev= 30
  4339.4  279.41  4432.5     275  4488.9  275.42  4568.5  273.86  4681.5  269.51
  4747.4  266.16  4796.9  265.88    4855  263.02  4883.4  264.36  4932.9  264.15
  4947.2  265.27  4997.4  263.94  5069.8  264.83  5216.3  266.88  5278.5  268.56
  5304.3  270.39  5340.6  270.96  5433.9  275.18  5490.8  279.32  5527.7  280.54
  5538.3  282.73  5559.5   282.8    5570  284.44  5637.9   288.3  5672.1  291.81
  5703.2  293.98  5734.3  294.73  5739.6  296.09  5760.1  298.04  5856.7  304.17
#Mann= 7 ,-1 , 0
  4339.4     .05       0  4681.5     .07       0  4883.4     .12       0
  4883.4     .05       0  4932.9     .12       0  5069.8     .05       0
  5637.9     .16       0
Bank Sta=4796.9,5216.3
XS Rating Curve= 0 ,0
Exp/Cntr=0.3,0.1

Type RM Length L Ch R = 1 ,82203   ,495,495,495
BEGIN DESCRIPTION:
ALLIGATOR BRANCH 66.0
END DESCRIPTION:
XS GIS Cut Line= 3
      3669349.63      10544110.2      3668349.61     10543810.19
      3667249.63      10543410.2
#Sta/Elev= 30
  3971.9   286.2  3990.7  285.66  4098.1  280.59  4274.7  267.19    4373  267.91
  4389.5  264.57  4406.1  267.34  4411.3   266.1  4420.9  267.66  4548.8  265.23
  4640.1  265.68    4678  262.43    4684  262.43  4686.2  264.35  4702.7  262.59
  4734.1  264.84  4901.1  262.44  5234.8  264.18  5317.9  264.24  5468.8  265.68
  5616.5  267.23  5764.1  271.63  5850.6  277.19  5856.6  278.95  5967.6  288.97
  6037.5  291.44  6109.9  296.74  6145.9  296.48  6171.1  299.33  6186.4  298.94
#Mann= 5 ,-1 , 0
  3971.9     .16       0  3990.7     .12       0  4640.1     .05       0
  5234.8     .12       0  5317.9     .05       0
#XS Ineff= 4 ,-1
 4169.89 4505.68  269.96 4505.68 4565.34268.3594 4565.34 4602.84266.6103
 5475.57 5818.18  270.61
Permanent Ineff=
       F       F       F       F
Bank Sta=4640.1,5468.8
XS Rating Curve= 0 ,0
Exp/Cntr=0.3,0.1

Type RM Length L Ch R = 1 ,81708   ,548,548,548
BEGIN DESCRIPTION:
ALLIGATOR BRANCH 65.0
END DESCRIPTION:
XS GIS Cut Line= 3
      3669749.64     10543310.19      3668549.61     10543410.19
      3667549.63      10543110.2
#Sta/Elev= 30
  3813.1   301.2  3863.3  299.41  4003.8  286.86  4124.2  279.72  4444.4  274.52
  4555.7   268.1  4598.3  269.66  4666.1  265.72  4706.2  262.06  4786.2  260.52
  4834.2  261.77  5090.4  261.99  5143.4  265.45  5163.5  266.48  5184.3  269.65
  5204.4  269.33  5215.7  270.69  5308.8  272.74    5314  271.69  5376.7   272.5
  5404.2  271.36  5516.7  270.32  5549.8   270.5  5561.1  269.08  5665.5  269.53
  5769.9  273.13  5797.7  276.72    5863   279.1  6006.5  291.51  6061.3  293.78
#Mann= 7 ,-1 , 0
  3813.1     .16       0  4444.4     .12       0  4666.1     .05       0
  5143.4     .12       0  5376.7     .05       0  5404.2     .12       0
  5516.7     .05       0
#XS Ineff= 1 ,-1
 4490.34 4594.32  269.39
Permanent Ineff=
       F
Bank Sta=4666.1,5143.4
XS Rating Curve= 0 ,0
Exp/Cntr=0.3,0.1

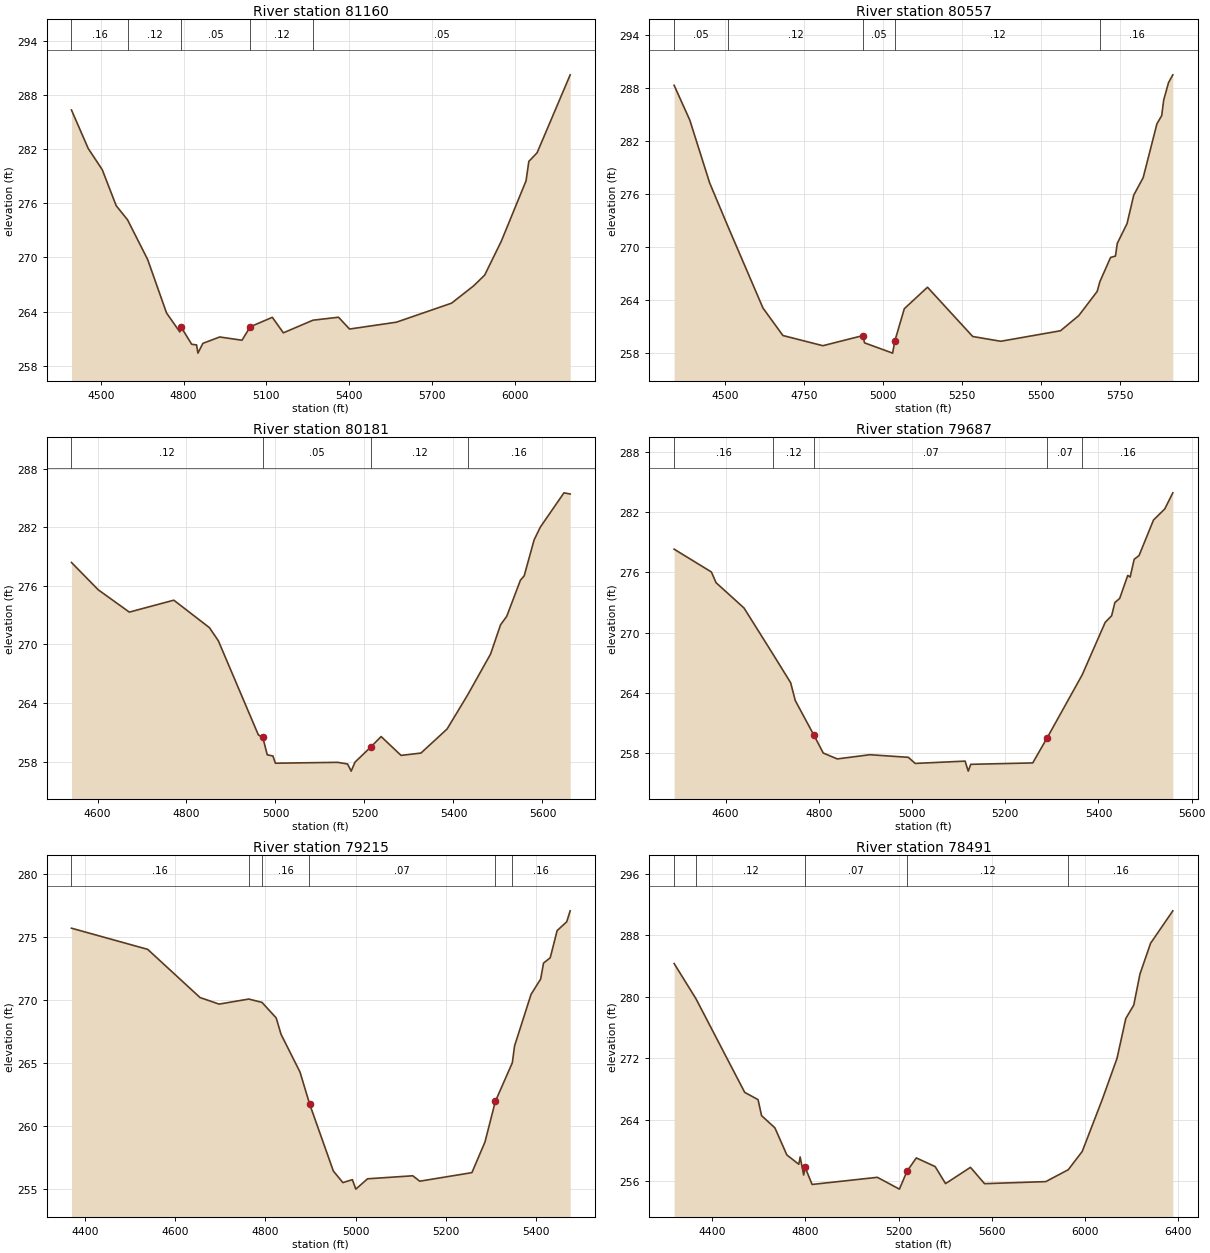
Type RM Length L Ch R = 1 ,81160   ,603,603,603
BEGIN DESCRIPTION:
ALLIGATOR BRANCH 64.0
END DESCRIPTION:
XS GIS Cut Line= 3
      3669399.57     10542960.19      3668799.61     10543060.19
      3667599.65     10543060.19
#Sta/Elev= 30
  4393.2  286.34    4454  282.07  4504.7  279.73  4555.4  275.73  4596.5  274.17
  4669.4  269.77  4737.9  263.84    4786  261.74  4791.1  262.26  4829.1  260.37
  4846.8   260.3  4851.7  259.39  4869.6  260.47  4930.5  261.18  5011.4  260.82
  5041.4  262.31  5121.4  263.36  5161.4  261.64  5268.8  263.04  5361.4  263.37
  5401.4  262.06  5571.4  262.82  5771.4  264.93  5851.4  266.85  5891.4  268.04
  5951.4  271.78  6041.4  278.49  6051.4  280.64  6081.4   281.6  6201.4  290.24
#Mann= 5 ,-1 , 0
  4393.2     .16       0  4596.5     .12       0  4791.1     .05       0
  5041.4     .12       0  5268.8     .05       0
Bank Sta=4791.1,5041.4
XS Rating Curve= 0 ,0
Exp/Cntr=0.3,0.1

Type RM Length L Ch R = 1 ,80557   ,376,376,376
BEGIN DESCRIPTION:
ALLIGATOR BRANCH 63.0
END DESCRIPTION:
XS GIS Cut Line= 3
      3669456.56     10542756.03      3668856.55     10542556.02
      3668049.58     10542060.17
#Sta/Elev= 30
  4338.7  288.27  4388.2  284.35  4451.4  277.22  4510.4  272.21  4620.1  263.09
  4683.3  259.98  4809.8  258.83  4936.3  259.97  4941.9  259.15  5030.8  257.99
    5038  259.39  5067.8  263.01  5141.2  265.44  5284.5  259.87  5373.2  259.33
  5562.6  260.52  5620.6  262.24  5678.6  264.96  5687.5  266.09  5721.2  268.81
  5736.6  268.96  5742.4   270.4  5773.3  272.63  5794.6  275.86  5824.4  277.83
    5868  283.92  5883.1  284.84  5889.3  286.59  5904.7  288.57  5918.3  289.45
#Mann= 5 ,-1 , 0
  4338.7     .05       0  4510.4     .12       0  4936.3     .05       0
    5038     .12       0  5687.5     .16       0
Bank Sta=4936.3,5038
XS Rating Curve= 0 ,0
Exp/Cntr=0.3,0.1

Type RM Length L Ch R = 1 ,80181   ,494,494,494
BEGIN DESCRIPTION:
ALLIGATOR BRANCH 62.0
END DESCRIPTION:
XS GIS Cut Line= 3
      3669349.57     10542210.19      3668899.61     10542210.19
       3668299.6     10541910.18
#Sta/Elev= 30
  4541.5  278.39  4601.5   275.6  4671.5  273.31  4771.5  274.53  4851.5  271.72
  4871.5  270.38  4961.5  260.74  4971.5  260.48  4981.5   258.7  4994.3  258.58
  4999.8  257.84  5139.6  257.93    5162  257.76  5170.1  257.03  5178.7  257.95
  5215.1  259.54  5237.4  260.57  5282.2  258.64  5326.9  258.88  5385.6  261.34
  5431.7  264.82  5483.4  269.02  5505.8  272.01  5519.7  272.88  5550.5  276.58
  5558.9  277.02  5581.2   280.7  5595.2  282.01  5648.3  285.52  5662.3   285.4
#Mann= 4 ,-1 , 0
  4541.5     .12       0  4971.5     .05       0  5215.1     .12       0
  5431.7     .16       0
Bank Sta=4971.5,5215.1
XS Rating Curve= 0 ,0
Exp/Cntr=0.3,0.1

Type RM Length L Ch R = 1 ,79687   ,472,472,472
BEGIN DESCRIPTION:
ALLIGATOR BRANCH 61.0
END DESCRIPTION:
XS GIS Cut Line= 3
      3669399.63     10541710.19      3668899.61     10541710.19
      3668349.62     10541860.19
#Sta/Elev= 30
  4489.5  278.33  4569.5  276.05  4579.5  274.98  4639.5  272.45  4702.7  267.76
  4739.5  264.99  4749.5   263.2  4789.5  259.74  4809.5  257.96  4839.5  257.37
  4909.5  257.79  4992.1  257.53  5006.8  256.92  5113.9  257.15  5120.6  256.15
    5126  256.83    5259  256.97  5290.1  259.49  5365.1  265.77  5414.5  271.02
  5428.3  271.68  5435.2  272.99  5445.6  273.41  5462.9  275.71    5468  275.54
  5476.7  277.32  5487.1  277.69  5518.1  281.24  5542.3  282.35  5559.6  283.96
#Mann= 5 ,-1 , 0
  4489.5     .16       0  4702.7     .12       0  4789.5     .07       0
  5290.1     .07       0  5365.1     .16       0
Bank Sta=4789.5,5290.1
XS Rating Curve= 0 ,0
Exp/Cntr=0.3,0.1

Type RM Length L Ch R = 1 ,79215   ,724,724,724
BEGIN DESCRIPTION:
ALLIGATOR BRANCH 60.0
END DESCRIPTION:
XS GIS Cut Line= 3
      3669249.66     10541160.17      3668649.61     10541360.19
      3668399.61     10541760.19
#Sta/Elev= 30
  4370.6  275.72  4539.3  274.04  4655.3  270.21  4697.4  269.69  4763.1  270.09
  4792.3  269.83  4823.9  268.59  4834.5   267.3  4876.6  264.29  4896.4  261.93
  4897.7  261.77  4950.4  256.43  4971.5  255.51  4992.6  255.74  5000.2  254.99
  5026.1  255.81  5126.3  256.05  5141.7  255.62  5257.2   256.3  5286.1  258.73
  5309.1  261.96  5346.7  265.03  5351.6  266.36  5388.1  270.46  5409.4  271.68
  5415.8  272.95  5430.6  273.37  5445.9  275.53  5467.1  276.23  5474.8   277.1
#Mann= 6 ,-1 , 0
  4370.6     .16       0  4763.1     .12       0  4792.3     .16       0
  4896.4     .07       0  5309.1     .12       0  5346.7     .16       0
Bank Sta=4897.7,5309.1
XS Rating Curve= 0 ,0
Exp/Cntr=0.3,0.1

Type RM Length L Ch R = 1 ,78491   ,225,225,225
BEGIN DESCRIPTION:
ALLIGATOR BRANCH 59.0
END DESCRIPTION:
XS GIS Cut Line= 3
      3669006.05     10540377.56      3668177.89     10540924.46
      3668021.64     10542059.91
#Sta/Elev= 30
  4237.2  284.34  4330.9  279.75    4540  267.54  4597.1   266.6  4612.2  264.51
  4669.4  262.92  4720.6  259.39  4771.8  258.17  4777.7  259.12  4792.8  256.77
  4798.8  257.78  4828.9  255.54  5108.8  256.47  5203.4  254.93  5235.4  257.23
  5275.8     259  5356.6  257.87  5401.2  255.65    5508  257.77  5568.5  255.64
    5831  255.91  5927.4  257.46  5987.3  259.84  6073.2  266.62  6136.4  271.97
  6174.2  277.18  6208.4  278.93  6234.8  282.96  6280.4  286.98  6375.8  291.21
#Mann= 5 ,-1 , 0
  4237.2     .16       0  4330.9     .12       0  4798.8     .07       0
  5235.4     .12       0  5927.4     .16       0
Bank Sta=4798.8,5235.4
XS Rating Curve= 0 ,0
Exp/Cntr=0.3,0.1

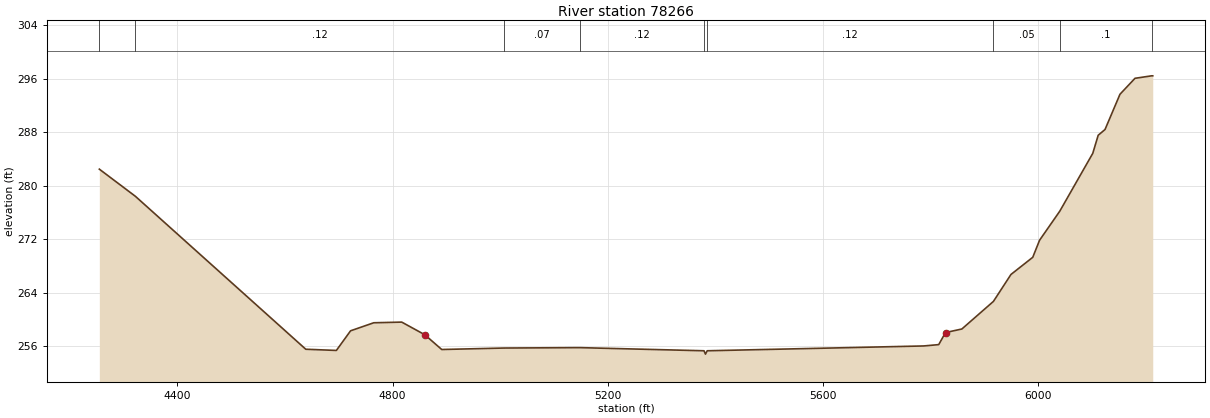
Type RM Length L Ch R = 1 ,78266   ,488,488,488
BEGIN DESCRIPTION:
ALLIGATOR BRANCH 58.0
END DESCRIPTION:
XS GIS Cut Line= 3
      3668953.93     10540377.01      3668249.61     10540610.19
      3667049.58     10540410.18
#Sta/Elev= 30
  4254.9  282.47  4321.9  278.42  4638.7  255.59  4695.6  255.41    4722  258.34
  4765.1  259.54  4817.1  259.64  4859.9  257.76  4891.5  255.55  5007.7  255.77
  5147.8  255.83  5379.1  255.36  5381.8  254.86  5385.1  255.36  5787.6  256.08
  5815.5  256.28  5828.1  258.08  5858.5  258.61  5917.2  262.73  5949.8  266.75
  5990.3  269.31    6003  271.86  6040.6   276.2  6101.9  284.83    6112  287.53
  6124.7  288.39  6152.5  293.65  6180.4  296.03  6211.2   296.4  6213.4   296.4
#Mann= 9 ,-1 , 0
  4254.9     .16       0  4321.9     .12       0  5007.7     .07       0
  5147.8     .12       0  5379.1     .07       0  5385.1     .12       0
  5917.2     .05       0  6040.6      .1       0  6211.2     .16       0
Bank Sta=4859.9,5828.1
XS Rating Curve= 0 ,0
Exp/Cntr=0.3,0.1