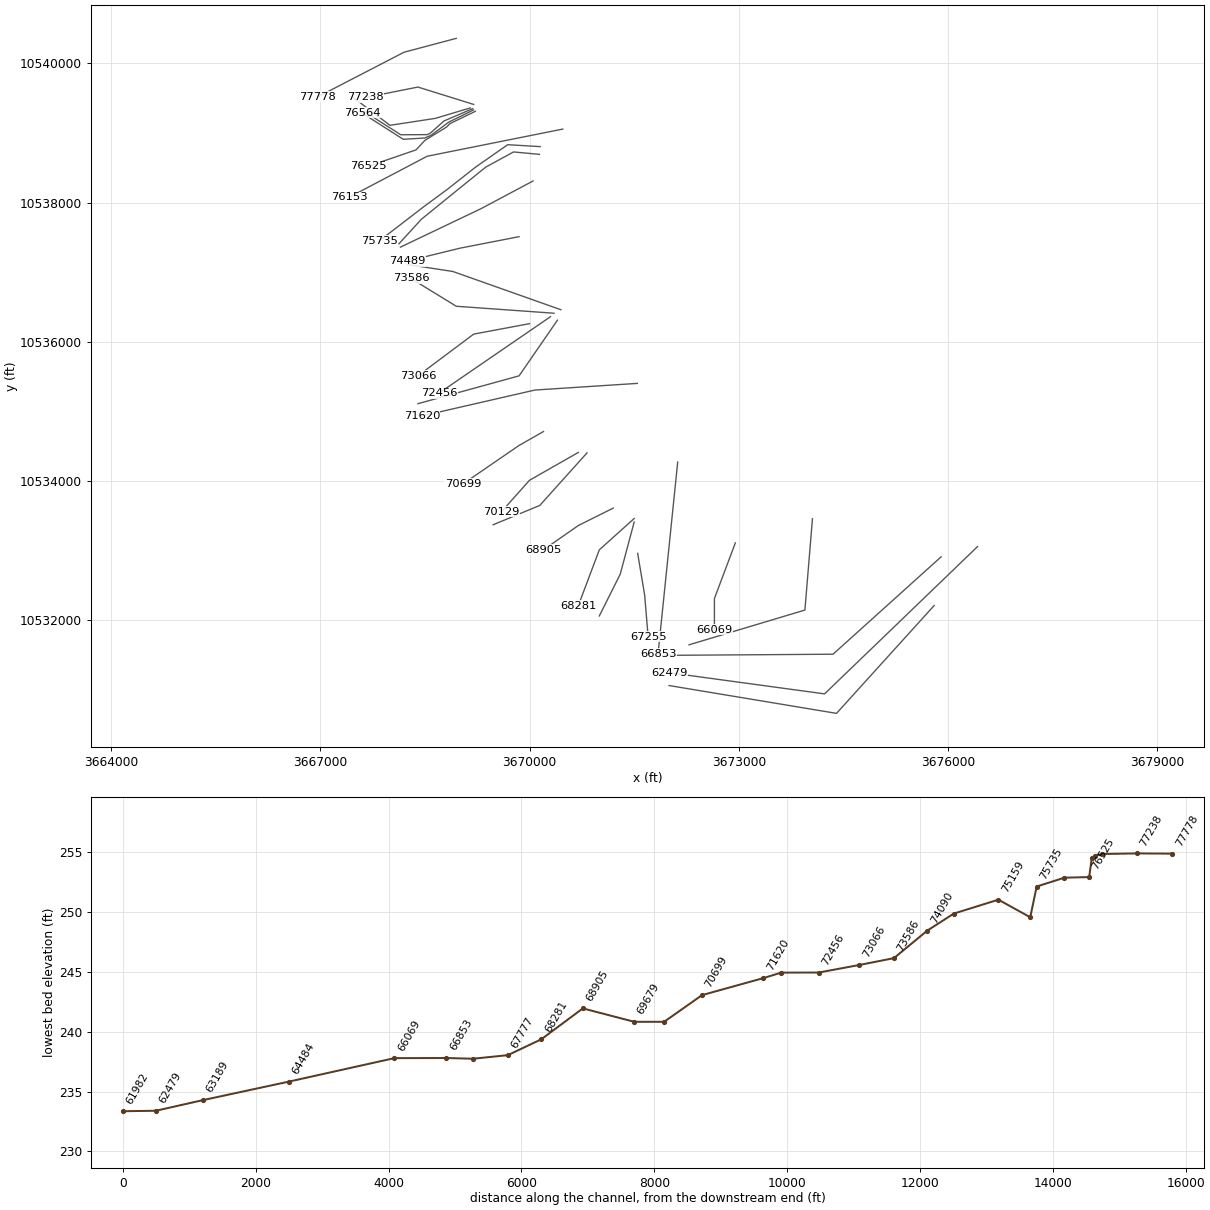
HEC-RAS study ALLIGATOR BRANCH.prj: ALLIGATOR BRANCH Base Level Engineering

--- ALLIGATOR BRANCH.g01 (geometry) --- (continued)

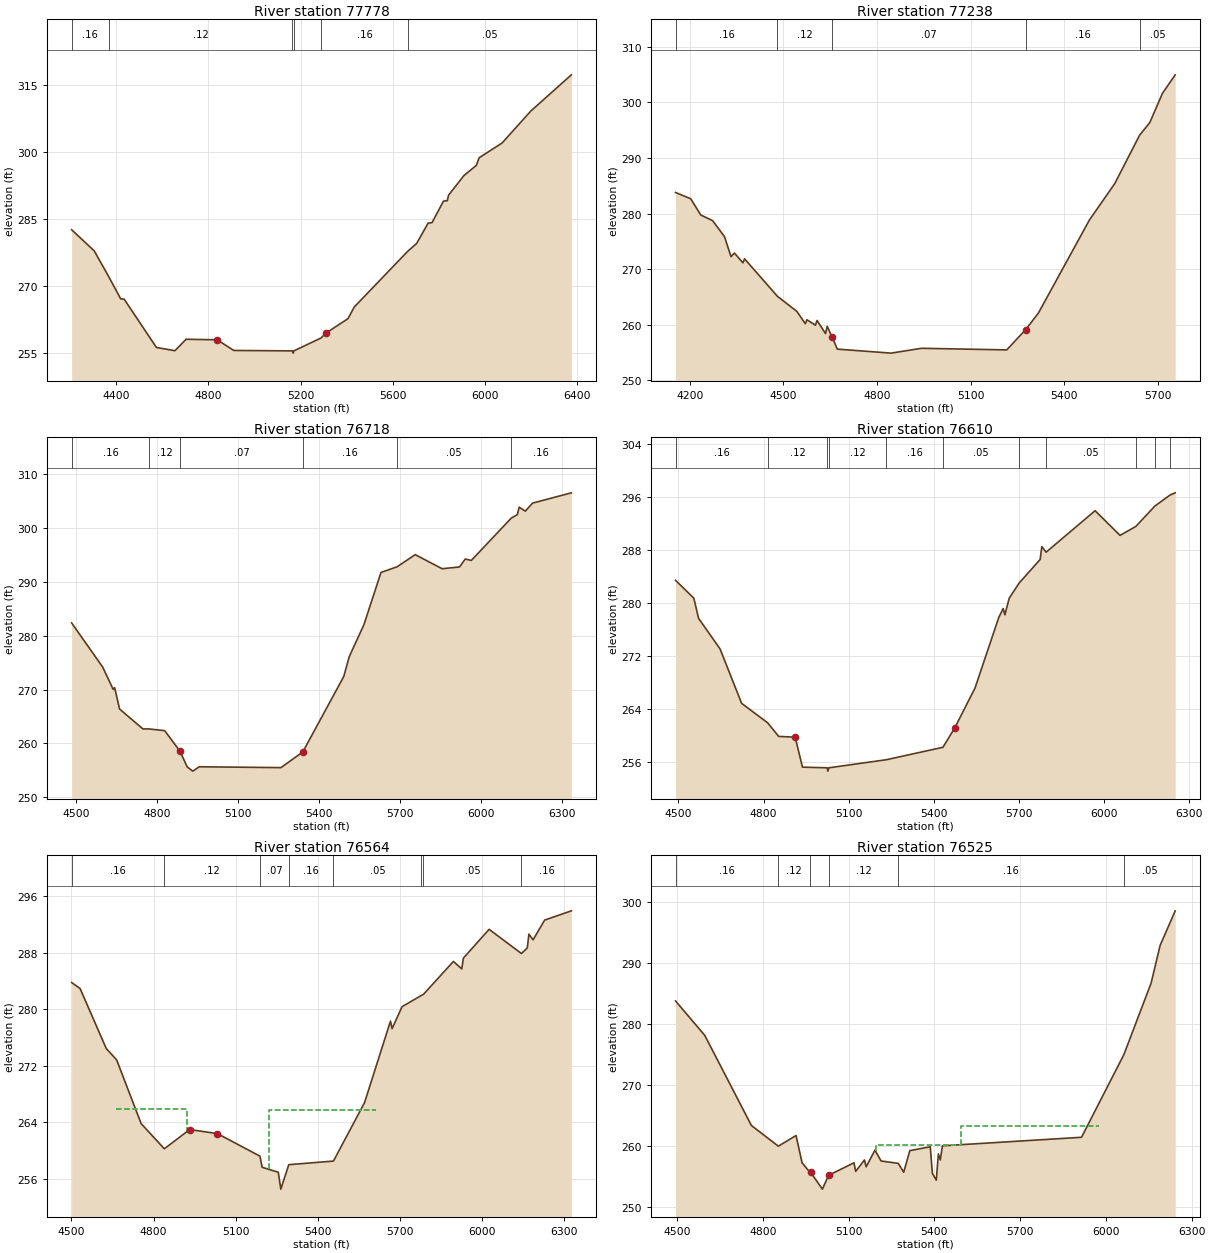
Type RM Length L Ch R = 1 ,77778   ,540,540,540
BEGIN DESCRIPTION:
ALLIGATOR BRANCH 57.0
END DESCRIPTION:
XS GIS Cut Line= 3
      3668949.61     10540360.19      3668199.61     10540160.19
      3666963.57      10539518.7
#Sta/Elev= 30
  4206.3  282.53    4304  277.82  4366.3  272.12  4419.1  267.05    4434  266.99
  4574.4  256.15  4654.6  255.43  4703.1     258  4837.6  257.88  4910.1  255.49
  5164.7  255.39  5167.5  254.89  5170.7  255.39  5288.4  258.27  5309.2  259.35
  5405.4   262.6  5433.2  265.24  5665.4  277.73  5703.6  279.45  5753.7  284.04
  5770.2  284.11  5820.1  288.94  5836.6  289.04  5842.2  290.28  5908.6  294.66
  5962.7  296.95  5974.9  298.66  6074.3  301.96  6199.3  309.13  6375.1  317.24
#Mann= 6 ,-1 , 0
  4206.3     .16       0  4366.3     .12       0  5164.7     .07       0
  5170.7     .12       0  5288.4     .16       0  5665.4     .05       0
Bank Sta=4837.6,5309.2
XS Rating Curve= 0 ,0
Exp/Cntr=0.3,0.1

Type RM Length L Ch R = 1 ,77238   ,520,520,520
BEGIN DESCRIPTION:
ALLIGATOR BRANCH 56.0
END DESCRIPTION:
XS GIS Cut Line= 3
      3669199.57      10539410.2      3668399.61     10539660.19
      3667649.58     10539510.18
#Sta/Elev= 30
  4153.7  283.81  4202.4  282.68  4234.9  279.75  4272.6  278.75  4310.8  275.87
  4331.8  272.26  4342.8  272.91    4370  271.15  4375.2  271.88  4480.5  265.14
  4542.9  262.42  4570.1  260.21  4575.4  260.91  4602.6  259.93  4607.8  260.78
  4635.1  258.42  4640.3  259.73  4656.6  257.75  4672.8  255.63  4845.4  254.91
  4943.1  255.78  5216.2  255.49  5277.4  259.16  5318.2  262.15  5481.3  278.84
  5562.9  285.42  5642.6  294.12  5675.1  296.38  5715.9  301.65  5756.7  304.97
#Mann= 5 ,-1 , 0
  4153.7     .16       0  4480.5     .12       0  4656.6     .07       0
  5277.4     .16       0  5642.6     .05       0
Bank Sta=4656.6,5277.4
XS Rating Curve= 0 ,0
Exp/Cntr=0.3,0.1

Type RM Length L Ch R = 1 ,76718   ,108,108,108
BEGIN DESCRIPTION:
ALLIGATOR BRANCH 55.0
END DESCRIPTION:
XS GIS Cut Line= 4
      3669149.57     10539360.18      3668649.61     10539210.19
      3667999.61     10539110.19      3667465.31     10539515.74
#Sta/Elev= 30
  4483.3  282.39  4598.1   274.2  4637.3  270.03  4642.5  270.38  4660.7   266.4
  4746.9  262.71  4771.1  262.69  4827.8  262.38  4884.3  258.58  4911.3  255.64
  4931.9  254.86  4955.7  255.67  5258.2  255.51  5339.2  258.42  5490.9  272.43
  5511.2  276.12  5565.5  282.05  5628.8  291.77  5688.5  292.82  5755.5  295.08
  5855.3  292.46  5919.8  292.79  5940.6  294.26  5963.4  294.01  6110.8  301.84
    6134  302.53  6140.3   303.9  6163.1  303.15  6190.2  304.65  6333.7  306.56
#Mann= 6 ,-1 , 0
  4483.3     .16       0  4771.1     .12       0  4884.3     .07       0
  5339.2     .16       0  5688.5     .05       0  6110.8     .16       0
Bank Sta=4884.3,5339.2
XS Rating Curve= 0 ,0
Exp/Cntr=0.3,0.1

Type RM Length L Ch R = 1 ,76610   ,46,46,46
BEGIN DESCRIPTION:
Mapping XS cb3e94e3
END DESCRIPTION:
XS GIS Cut Line= 6
      3669184.57     10539349.78      3668773.12      10539172.7
       3668575.2     10538995.62       3668531.8     10538976.52
      3668153.33     10538974.79      3667630.74     10539309.87
#Sta/Elev= 30
  4489.7  283.44  4554.2  280.75  4570.9  277.72  4646.7   273.1  4722.6  264.91
  4814.5  261.97  4853.1  259.93  4911.3  259.81  4936.9   255.3  5023.8   255.2
  5026.6   254.7  5029.8   255.2  5232.8  256.42  5431.8  258.29  5472.9  261.17
  5544.7   267.2  5628.6  277.86    5644  279.19    5650  278.24  5665.2  280.74
  5700.5  283.04  5774.2  286.57  5780.1  288.52  5795.3  287.67  5967.8  293.92
  6055.7   290.2  6111.4  291.55  6178.1  294.61  6231.9  296.28    6250  296.61
#Mann= 11 ,-1 , 0
  4489.7     .16       0  4814.5     .12       0  5023.8     .07       0
  5029.8     .12       0  5232.8     .16       0  5431.8     .05       0
  5700.5     .16       0  5795.3     .05       0  6111.4     .16       0
  6178.1     .05       0  6231.9     .16       0
Bank Sta=4911.3,5472.9
XS Rating Curve= 0 ,0
Exp/Cntr=0.3,0.1

Type RM Length L Ch R = 1 ,76564   ,39,39,39
BEGIN DESCRIPTION:
Mapping XS 2e191667
END DESCRIPTION:
XS GIS Cut Line= 6
      3669197.21     10539331.45        3668843.     10539156.95
      3668587.79     10538966.84      3668496.65     10538927.78
      3668189.35     10538909.55      3667595.58     10539289.77
#Sta/Elev= 30
  4500.6  283.75  4531.4  282.91    4627  274.42  4665.1   272.8  4754.3   263.8
  4839.1  260.23  4931.7  262.95  5032.8  262.38  5188.3  259.19  5196.4  257.61
  5255.4  256.91  5264.6  254.52  5293.8  257.98  5456.9  258.49  5570.5  266.76
  5665.2  278.29  5671.2  277.23  5707.5  280.34  5777.6  281.91  5785.8  282.09
  5895.2  286.74  5925.6  285.69  5931.6  287.21  6025.4  291.28  6143.6  287.86
  6164.9  288.65  6170.9   290.6  6186.1   289.8  6228.4  292.59  6325.9   293.9
#Mann= 8 ,-1 , 0
  4500.6     .16       0  4839.1     .12       0  5188.3     .07       0
  5293.8     .16       0  5456.9     .05       0  5777.6     .16       0
  5785.8     .05       0  6143.6     .16       0
#XS Ineff= 2 ,-1
 4661.36 4922.73265.8279 5222.73 5611.36  265.71
Permanent Ineff=
       F       F
Bank Sta=4931.7,5032.8
XS Rating Curve= 0 ,0
Exp/Cntr=0.3,0.1

Type RM Length L Ch R = 1 ,76525   ,372,372,372
BEGIN DESCRIPTION:
Mapping XS ff6e3cef
END DESCRIPTION:
XS GIS Cut Line= 6
      3669222.81     10539311.61      3668858.19     10539134.51
      3668811.32      10539085.9      3668500.55     10538894.92
      3668373.82     10538757.77       3667689.8     10538521.67
#Sta/Elev= 30
  4494.5  283.82  4596.7  278.18  4760.1  263.37  4854.3  259.98  4916.1  261.73
  4937.2  257.26    4965  255.67  4967.4  255.67  5008.4  252.93    5030   255.2
  5118.8  257.25  5124.7  255.84  5155.5  257.72  5161.4  256.59  5192.2  259.33
  5213.5  257.55  5273.6  257.16  5292.8   255.7  5314.1  259.25  5385.7  259.88
    5393  255.52  5406.7   254.4    5414  258.71  5420.8  257.72  5428.2  260.04
  5914.8  261.44  6062.7  274.98  6158.1  286.73  6189.8  292.95  6242.5  298.61
#Mann= 6 ,-1 , 0
  4494.5     .16       0  4854.3     .12       0    4965     .07       0
    5030     .12       0  5273.6     .16       0  6062.7     .05       0
#XS Ineff= 2 ,-1
 5194.32 5492.05  260.14 5492.05 5977.27  263.33
Permanent Ineff=
       F       F
Bank Sta=4967.4,5030
XS Rating Curve= 0 ,0
Exp/Cntr=0.3,0.1

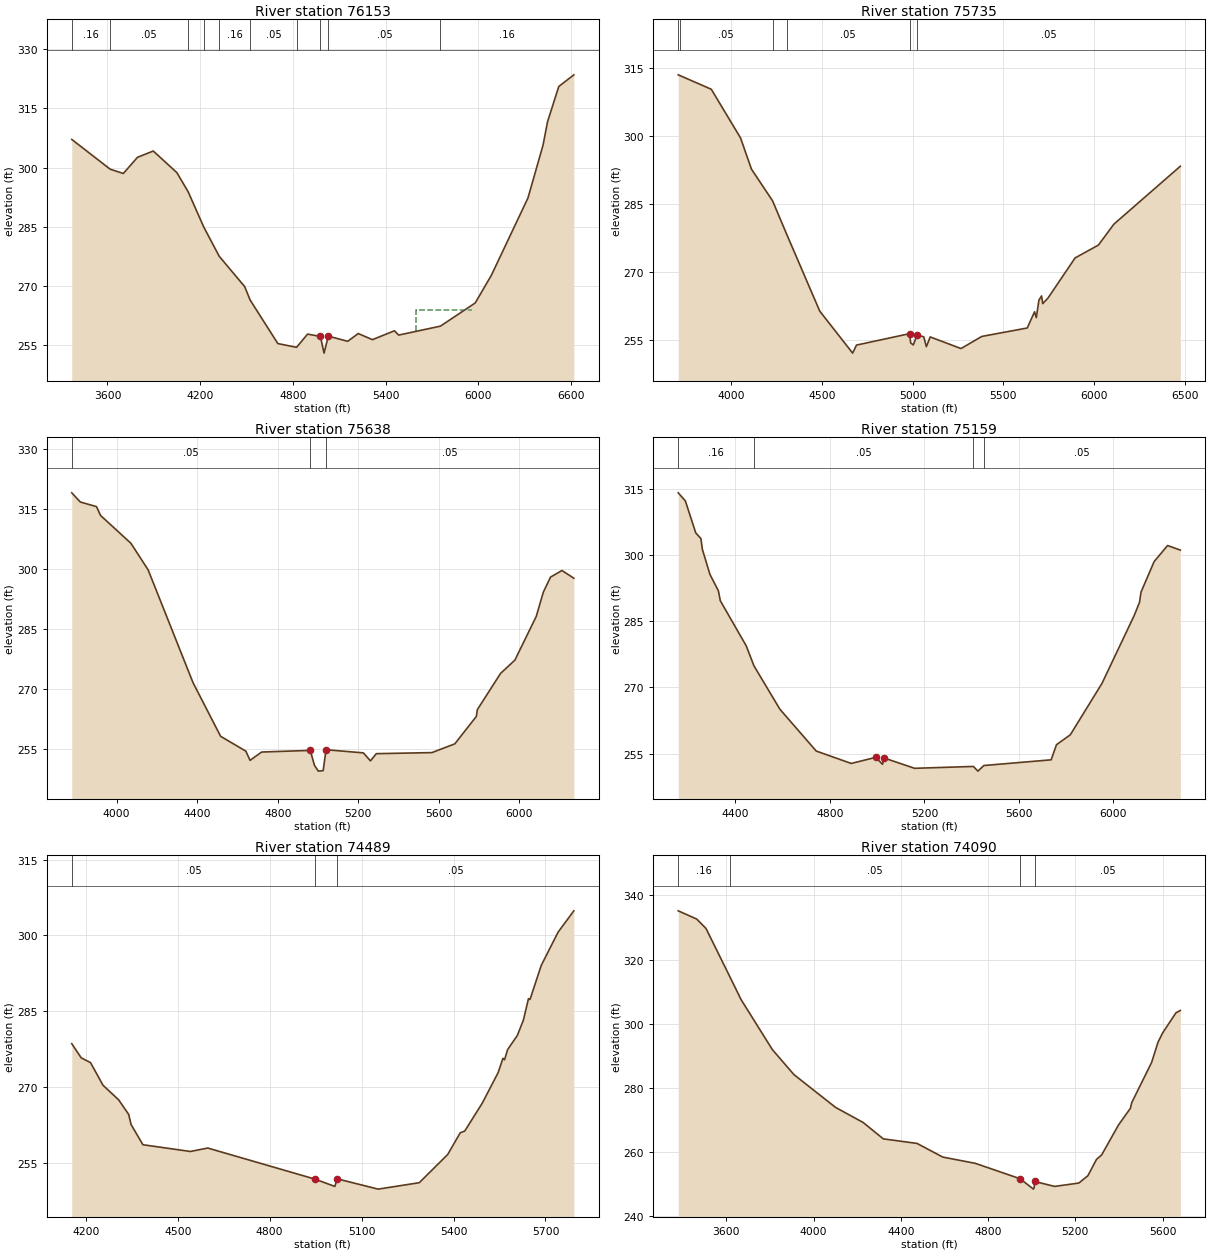
Type RM Length L Ch R = 1 ,76153   ,418,418,418
BEGIN DESCRIPTION:
ALLIGATOR BRANCH 54.0
END DESCRIPTION:
XS GIS Cut Line= 3
      3670476.47     10539056.39      3668532.06     10538665.78
      3667413.42     10538076.11
#Sta/Elev= 30
  3369.2  307.13  3617.9  299.57  3702.6  298.48  3794.4  302.59  3896.4  304.19
  4049.4  298.69  4122.7  293.79  4222.8  284.91  4322.9  277.48  4487.6  269.77
    4523  266.37  4702.2  255.31  4823.2  254.35  4894.7  257.71  4977.6  257.11
  5001.3  252.88  5028.6   257.2  5154.2  255.88  5222.4  257.85  5314.2   256.3
  5456.1  258.55  5483.8  257.46    5754  259.73  5979.1  265.62  6083.6  272.65
  6320.2  292.27  6417.8  305.69  6446.8  311.61  6519.6  320.57    6617  323.53
#Mann= 10 ,-1 , 0
  3369.2     .16       0  3617.9     .05       0  4122.7     .16       0
  4222.8     .12       0  4322.9     .16       0    4523     .05       0
  4823.2     .12       0  4977.6     .05       0  5028.6     .05       0
    5754     .16       0
#XS Ineff= 1 ,-1
 5593.18 5959.09  263.82
Permanent Ineff=
       F
Bank Sta=4977.6,5028.6
XS Rating Curve= 0 ,0
Exp/Cntr=0.3,0.1

Type RM Length L Ch R = 1 ,75735   ,97,97,97
BEGIN DESCRIPTION:
ALLIGATOR BRANCH 53.0
END DESCRIPTION:
XS GIS Cut Line= 6
      3670152.36     10538804.08      3669687.04     10538831.86
      3669225.23     10538508.94       3668829.4     10538196.44
      3668482.18      10537939.5      3667846.74      10537449.9
#Sta/Elev= 30
  3707.2  313.48  3714.6  313.35  3889.4   310.3  4050.6  299.59  4110.7  292.71
  4227.1  285.73    4306  278.26  4487.6  261.39  4668.8  252.14  4689.9  253.91
  4982.4  256.43  4988.7  254.38  5003.2  253.94  5024.3  256.18  5060.9  255.73
  5075.3  253.56  5096.2  255.71  5266.1  253.15  5380.9  255.82  5631.4  257.68
  5671.6  261.25  5681.4  259.97  5695.9  263.84  5710.4  264.75  5716.8  263.05
  5745.8  264.28  5895.2  273.12  6023.9  275.96    6109  280.56  6475.3  293.33
#Mann= 6 ,-1 , 0
  3707.2     .16       0  3714.6     .05       0  4227.1     .16       0
    4306     .05       0  4982.4     .03       0  5024.3     .05       0
Bank Sta=4982.4,5024.3
XS Rating Curve= 0 ,0
Exp/Cntr=0.3,0.1

Type RM Length L Ch R = 1 ,75638   ,479,479,479
BEGIN DESCRIPTION:
Mapping XS a4615864
END DESCRIPTION:
XS GIS Cut Line= 6
      3670141.88     10538692.97      3669770.37     10538727.69
      3669371.07     10538508.94      3669006.48      10538213.8
      3668447.46     10537758.94      3668127.99     10537408.23
#Sta/Elev= 30
  3777.5  318.96    3820  316.67  3900.3  315.52  3920.4  313.32    4071  306.39
  4156.5  299.77  4379.3  271.65  4516.4  258.26  4641.8  254.55  4662.6  252.26
  4720.2  254.33  4961.6  254.74  4982.4     251  5001.7  249.57  5025.5  249.69
  5039.9  254.91  5225.2  254.12  5260.4  252.13  5289.2  253.92  5565.6  254.19
  5679.1  256.37  5786.1  263.21  5791.1  264.91  5906.4  273.94  5977.4  277.25
  6083.5  288.15  6118.7  294.21  6154.4  297.95  6211.2  299.59  6270.1  297.67
#Mann= 3 , 0 , 0
  3777.5     .05       0  4961.6     .03       0  5039.9     .05       0
Bank Sta=4961.6,5039.9
XS Rating Curve= 0 ,0
Exp/Cntr=0.3,0.1

Type RM Length L Ch R = 1 ,75159   ,670,670,670
BEGIN DESCRIPTION:
ALLIGATOR BRANCH 52.0
END DESCRIPTION:
XS GIS Cut Line= 3
       3670049.6     10538310.18      3669299.61     10537910.19
      3668149.65     10537360.21
#Sta/Elev= 30
  4158.1  314.09  4188.2  312.27  4232.1  305.03  4254.1  303.71  4260.1  301.31
  4292.3  295.61  4328.1  291.88  4336.2  289.64    4446  279.41  4478.6  274.89
  4588.4  265.06  4742.1  255.59  4890.2  252.78  4994.3  254.17  5022.2  252.59
  5030.3     254  5158.2  251.68  5407.1   252.1  5426.3  251.04  5451.5  252.31
  5736.2   253.6  5758.8  257.03  5817.3  259.27  5951.3  270.92  6087.4  286.26
    6110  289.26  6116.6  291.61    6172  298.51  6228.9  302.15  6282.8  301.12
#Mann= 4 ,-1 , 0
  4158.1     .16       0  4478.6     .05       0  5407.1     .03       0
  5451.5     .05       0
Bank Sta=4994.3,5030.3
XS Rating Curve= 0 ,0
Exp/Cntr=0.3,0.1

Type RM Length L Ch R = 1 ,74489   ,399,399,399
BEGIN DESCRIPTION:
ALLIGATOR BRANCH 51.0
END DESCRIPTION:
XS GIS Cut Line= 3
      3669849.66      10537510.2      3669009.49     10537346.33
      3668249.65      10537160.2
#Sta/Elev= 30
  4154.2  278.62  4185.1  275.82  4215.4  274.88  4256.1  270.41  4307.1  267.53
  4339.9  264.64  4347.8  262.64  4386.4  258.65  4541.2  257.32  4597.9     258
  4948.9  251.84  5012.6  250.41  5020.4  251.91    5154  249.88  5288.1  251.15
  5380.7  256.71  5421.9  261.02  5436.3  261.34    5494   266.9  5545.5  272.91
  5561.1  275.73  5566.3  275.42  5576.3  277.44  5607.9  280.22  5627.8  283.26
  5644.4  287.51  5649.5  287.35    5686  294.07  5741.1  300.66  5792.5  304.87
#Mann= 3 , 0 , 0
  4154.2     .05       0  4948.9     .03       0  5020.4     .05       0
Bank Sta=4948.9,5020.4
XS Rating Curve= 0 ,0
Exp/Cntr=0.3,0.1

Type RM Length L Ch R = 1 ,74090   ,504,504,504
BEGIN DESCRIPTION:
ALLIGATOR BRANCH 50.0
END DESCRIPTION:
XS GIS Cut Line= 3
      3670449.58      10536460.2      3668899.61     10537010.19
      3668249.62     10537110.19
#Sta/Elev= 30
  3379.3   335.2  3464.2  332.63  3506.6  329.71  3616.6  314.58  3667.2  307.57
  3810.9  291.95  3909.8  284.16  4100.8  273.93  4227.2  269.23  4319.8  264.12
  4474.1  262.71  4592.3  258.45  4741.3   256.5  4946.8  251.71  5008.3  248.46
  5011.5  248.96  5013.8  250.85  5104.9  249.31  5216.2  250.35  5257.9  252.65
  5297.1  257.71  5321.2  259.15  5398.3  268.47  5452.7  273.65    5459  275.43
  5550.1  287.96  5579.2  294.23  5600.7  297.15  5661.4   303.4  5681.6  304.14
#Mann= 4 ,-1 , 0
  3379.3     .16       0  3616.6     .05       0  4946.8     .03       0
  5013.8     .05       0
Bank Sta=4946.8,5013.8
XS Rating Curve= 0 ,0
Exp/Cntr=0.3,0.1

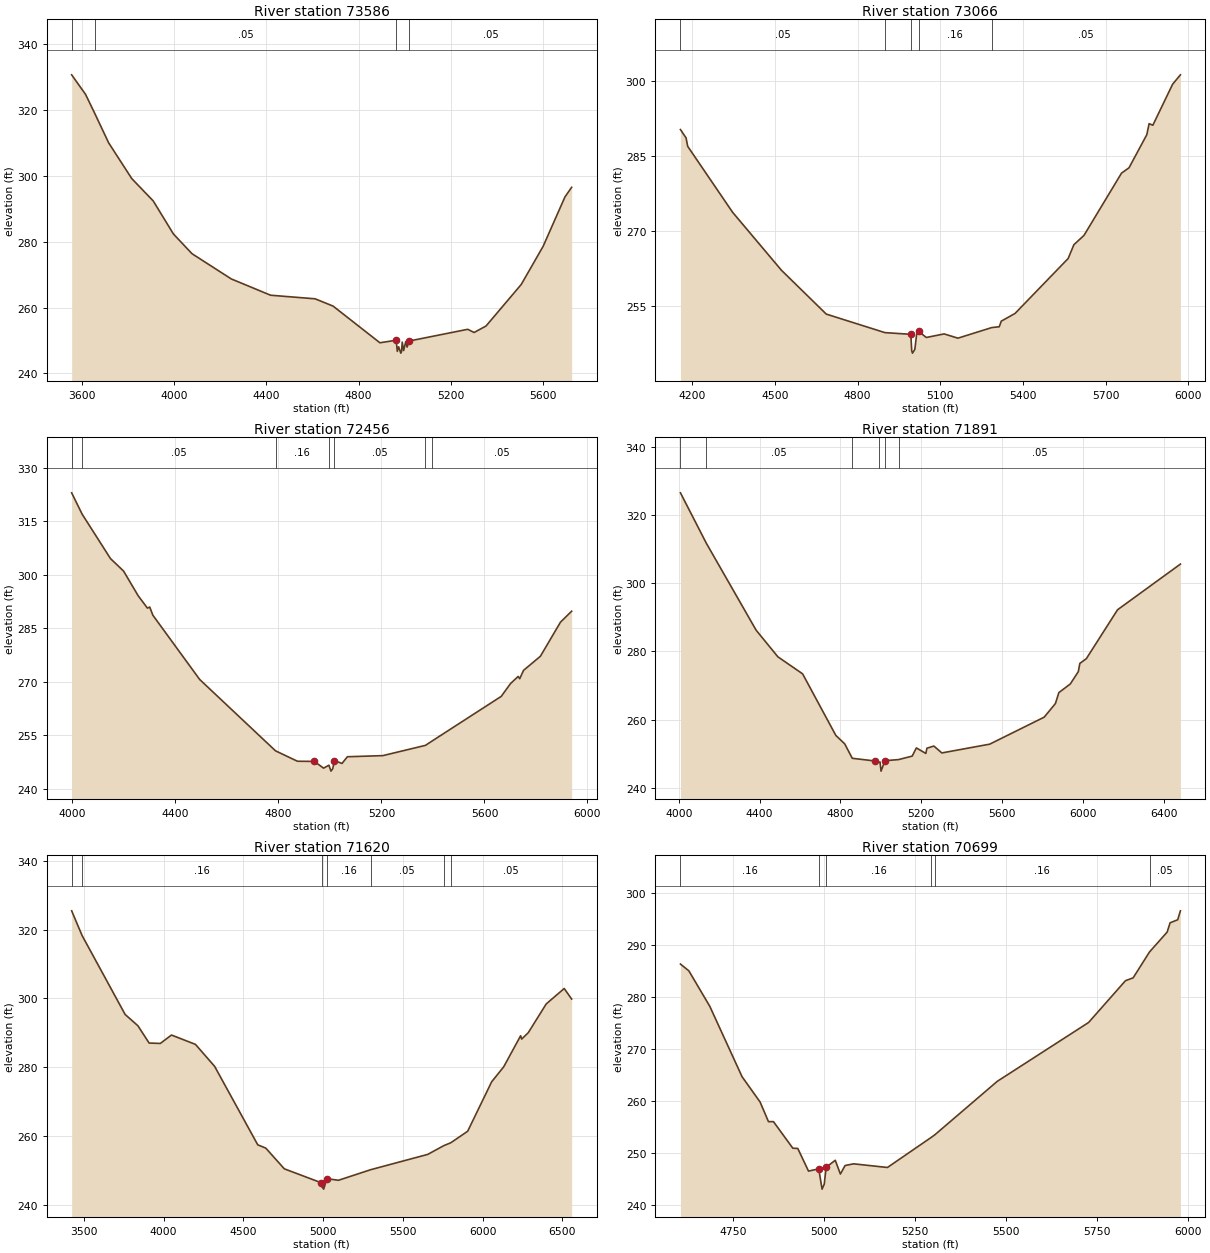
Type RM Length L Ch R = 1 ,73586   ,520,520,520
BEGIN DESCRIPTION:
ALLIGATOR BRANCH 49.0
END DESCRIPTION:
XS GIS Cut Line= 3
      3670349.64     10536410.19      3668949.61     10536510.19
      3668299.62     10536910.18
#Sta/Elev= 30
  3556.4  330.74  3616.6   324.8    3656  319.09  3716.8  310.06  3817.1  299.18
  3909.8  292.42  3997.5  282.36  4077.8  276.38  4248.2   268.7  4418.6  263.75
  4611.6  262.66  4689.3  260.45  4892.3   249.3  4962.9  250.07  4967.7  246.69
  4973.6  248.07  4982.9  246.15  4986.1  246.65    4989  249.51  4995.2  246.94
  5004.4  249.65  5010.3  247.99  5018.7  249.83    5273  253.39  5300.5  252.42
  5352.2  254.39  5504.9  267.03  5599.6   278.6  5694.2  293.62  5723.2  296.55
#Mann= 4 ,-1 , 0
  3556.4     .16       0    3656     .05       0  4962.9     .05       0
  5018.7     .05       0
Bank Sta=4962.9,5018.7
XS Rating Curve= 0 ,0
Exp/Cntr=0.3,0.1

Type RM Length L Ch R = 1 ,73066   ,610,610,610
BEGIN DESCRIPTION:
ALLIGATOR BRANCH 48.0
END DESCRIPTION:
XS GIS Cut Line= 3
      3669999.63     10536260.19      3669199.61     10536110.19
      3668399.58     10535510.16
#Sta/Elev= 30
  4157.6  290.26    4178  288.59  4183.9  286.91  4346.7  273.74  4523.9  262.15
  4686.7  253.38  4899.4  249.68  4993.4  249.34  4996.7  246.08  4999.4  245.58
    5008  246.32  5014.3  249.24  5021.6  249.91  5049.7  248.71  5114.3  249.42
  5164.3  248.57  5287.3  250.69  5314.3  250.85  5321.6  251.97  5371.6  253.51
  5564.3  264.49  5585.1  267.25  5621.6   269.1    5758  281.56  5785.1  282.62
  5849.7  289.24    5858  291.44  5871.6  291.13  5943.4  299.33  5971.6   301.2
#Mann= 5 ,-1 , 0
  4157.6     .05       0  4899.4     .16       0  4993.4     .07       0
  5021.6     .16       0  5287.3     .05       0
Bank Sta=4993.4,5021.6
XS Rating Curve= 0 ,0
Exp/Cntr=0.3,0.1

Type RM Length L Ch R = 1 ,72456   ,565,565,565
BEGIN DESCRIPTION:
ALLIGATOR BRANCH 47.0
END DESCRIPTION:
XS GIS Cut Line= 3
      3670299.57     10536360.16      3669499.61     10535810.19
      3668699.61     10535260.19
#Sta/Elev= 30
  3996.8  322.93  4037.2  316.99  4147.6   304.5  4198.4  301.01  4255.2  294.08
    4291  290.63  4299.9  290.93  4312.3  288.62    4494  270.63  4788.4  250.64
  4873.5  247.72  4939.2  247.67    4975  245.79    4996  246.61  5003.7  244.95
  5010.9  245.66  5016.9  247.92  5046.7   247.1  5067.7  248.98    5205  249.29
  5370.8  252.17  5396.7   253.4  5665.1   265.9  5700.9  269.47  5730.7  271.48
  5736.8  270.85  5751.7  273.19    5817  277.13  5895.1  286.69  5938.4  289.76
#Mann= 7 ,-1 , 0
  3996.8     .16       0  4037.2     .05       0  4788.4     .16       0
    4996     .07       0  5016.9     .05       0  5370.8     .16       0
  5396.7     .05       0
Bank Sta=4939.2,5016.9
XS Rating Curve= 0 ,0
Exp/Cntr=0.3,0.1

Type RM Length L Ch R = 1 ,71891   ,271,271,271
BEGIN DESCRIPTION:
ALLIGATOR BRANCH 46.0
END DESCRIPTION:
XS GIS Cut Line= 3
      3670399.62      10536310.2      3669849.61     10535510.19
      3668399.61     10535110.19
#Sta/Elev= 30
  4008.3  326.45  4136.5  311.68  4383.1  286.21  4490.7  278.42  4613.1  273.43
  4777.5   255.4  4821.4  252.94  4858.9   248.7  4971.7  247.91  4989.5  247.53
  4996.3  247.63  5001.3  244.94  5020.6  247.99  5088.1  248.32  5155.5  249.34
  5176.2  251.74  5223.2  250.12  5228.4  251.65  5262.8  252.29  5302.3  250.27
  5539.3  252.84    5809  260.75  5864.5  264.73  5881.6  267.94  5938.4  270.48
  5977.9  274.08  5985.4  276.49  6017.5  277.87  6172.1   292.2  6483.3  305.58
#Mann= 6 ,-1 , 0
  4008.3     .16       0  4136.5     .05       0  4858.9     .16       0
  4989.5     .07       0  5020.6     .16       0  5088.1     .05       0
Bank Sta=4971.7,5020.6
XS Rating Curve= 0 ,0
Exp/Cntr=0.3,0.1

Type RM Length L Ch R = 1 ,71620   ,921,921,921
BEGIN DESCRIPTION:
ALLIGATOR BRANCH 45.0
END DESCRIPTION:
XS GIS Cut Line= 3
      3671544.24     10535401.89       3670077.2      10535306.4
       3668454.3     10534933.22
#Sta/Elev= 30
  3423.1  325.48  3488.5  318.29  3758.4  295.32  3838.9  292.01  3908.8     287
  3978.9  286.88  4049.1  289.33  4199.4  286.61  4319.6  280.22  4590.2  257.37
  4640.3  256.43  4756.7  250.39  4988.1  246.34  4993.4  245.15  5003.4  244.48
  5024.2  247.53    5096  247.05  5297.3  250.12  5656.2  254.59  5757.9  257.16
  5800.1  257.96  5906.6  261.33  6057.1  275.73  6132.4  280.07  6238.7  289.12
  6245.2  288.15  6286.7  290.02  6399.1  298.38    6512  302.87  6558.5  299.81
#Mann= 7 ,-1 , 0
  3423.1     .05       0  3488.5     .16       0  4993.4     .07       0
  5024.2     .16       0  5297.3     .05       0  5757.9     .08       0
  5800.1     .05       0
Bank Sta=4988.1,5024.2
XS Rating Curve= 0 ,0
Exp/Cntr=0.3,0.1

Type RM Length L Ch R = 1 ,70699   ,570,570,570
BEGIN DESCRIPTION:
ALLIGATOR BRANCH 44.0
END DESCRIPTION:
XS GIS Cut Line= 3
      3670199.63      10534710.2      3669849.61     10534510.19
      3669049.58     10533960.17
#Sta/Elev= 30
    4606  286.31  4629.1  285.01  4686.6   278.2  4775.2  264.68  4824.9   259.8
  4847.9  256.03  4861.6  256.03  4914.8  250.93  4928.5  250.87    4958  246.52
  4986.1  246.96  4995.2  243.06  5001.2  244.01  5006.3  247.26  5031.5   248.6
  5045.5  245.96  5058.5   247.6  5081.9  247.92  5174.9  247.22  5295.4  253.01
  5305.6  253.53  5476.6  263.77  5727.6  275.08  5829.1  283.12  5850.1  283.66
  5895.1  288.64  5943.6  292.46  5951.6  294.24  5972.5  294.82    5980  296.54
#Mann= 6 ,-1 , 0
    4606     .16       0  4986.1     .07       0  5006.3     .16       0
  5295.4     .12       0  5305.6     .16       0  5895.1     .05       0
Bank Sta=4986.1,5006.3
XS Rating Curve= 0 ,0
Exp/Cntr=0.3,0.1

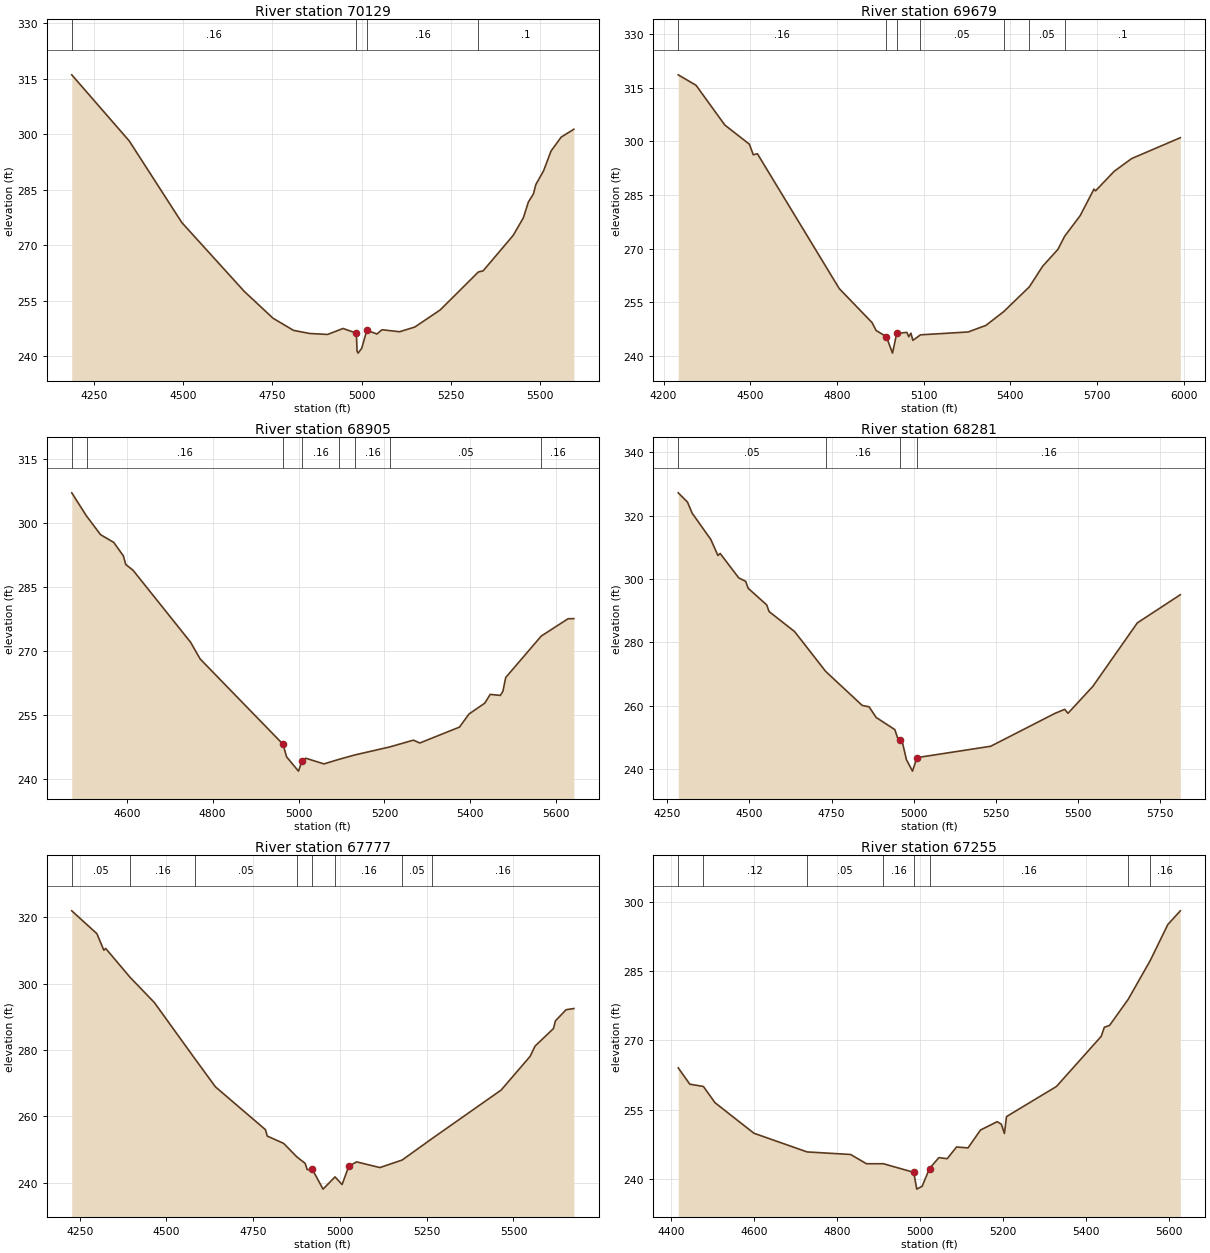
Type RM Length L Ch R = 1 ,70129   ,450,450,450
BEGIN DESCRIPTION:
ALLIGATOR BRANCH 43.0
END DESCRIPTION:
XS GIS Cut Line= 3
      3670699.61     10534410.19      3669999.61     10534010.19
      3669599.61     10533560.19
#Sta/Elev= 30
    4187  316.03  4348.2  298.17  4495.8   276.1  4670.7  257.53  4751.4  250.27
  4808.9  246.98    4855  246.13  4904.7  245.88  4947.9  247.49  4985.3  246.23
  4987.3  241.33  4990.1  240.83  5000.3  242.14  5014.6  246.99    5043  246.01
  5057.2  247.15  5106.5  246.61  5149.2  247.88  5220.3  252.49  5327.6  262.77
  5340.7  263.05  5425.1  272.64  5453.6  277.38  5467.8  281.67    5482  283.87
  5488.7  286.38  5510.4   290.1  5531.3  295.44  5559.8   299.2  5595.3  301.33
#Mann= 4 ,-1 , 0
    4187     .16       0  4985.3     .07       0  5014.6     .16       0
  5327.6      .1       0
Bank Sta=4985.3,5014.6
XS Rating Curve= 0 ,0
Exp/Cntr=0.3,0.1

Type RM Length L Ch R = 1 ,69679   ,774,774,774
BEGIN DESCRIPTION:
ALLIGATOR BRANCH 42.0
END DESCRIPTION:
XS GIS Cut Line= 3
       3670823.7     10534403.59      3670146.64     10533648.41
      3669478.22     10533370.63
#Sta/Elev= 30
  4250.7  318.58  4312.5  315.65  4411.9  304.56    4497   299.2  4510.6  296.25
  4524.8  296.53  4808.1  258.86  4921.8  249.35    4936  247.13  4971.1  245.45
  4992.5  240.83    5007  246.33  5042.1  246.63  5048.8  245.42  5056.3   246.4
    5063   244.4  5089.3  245.94  5254.4  246.74  5315.9  248.58  5377.6  252.44
  5466.2  259.35    5512  265.08  5565.2  269.83  5588.3  273.47  5642.2  279.25
  5689.9  286.66  5695.3  286.16  5759.9  291.63    5820  295.17  5988.8  301.01
#Mann= 7 ,-1 , 0
  4250.7     .16       0  4971.1     .07       0    5007     .16       0
  5089.3     .05       0  5377.6     .16       0  5466.2     .05       0
  5588.3      .1       0
Bank Sta=4971.1,5007
XS Rating Curve= 0 ,0
Exp/Cntr=0.3,0.1

Type RM Length L Ch R = 1 ,68905   ,624,624,624
BEGIN DESCRIPTION:
ALLIGATOR BRANCH 41.0
END DESCRIPTION:
XS GIS Cut Line= 3
       3671199.6     10533610.18      3670699.61     10533360.19
      3670199.63     10533010.21
#Sta/Elev= 30
  4471.9  307.06  4506.3  301.63    4539  297.27  4569.7  295.46  4592.1   292.3
  4597.7  290.29  4614.4  288.97  4748.6  272.11    4771  268.18  4963.8  248.25
  4972.2  245.29  4999.9  241.95  5008.5  244.39  5016.9  244.97  5059.2  243.64
  5095.3  244.74  5131.7  245.75  5212.8  247.62  5267.6   249.2  5282.4  248.53
  5374.9  252.25  5397.1  255.32  5433.7  257.85  5446.4   259.9  5469.9  259.66
    5476  260.62  5482.5  263.85  5565.3  273.55  5627.7   277.6  5641.2  277.63
#Mann= 8 ,-1 , 0
  4471.9     .05       0  4506.3     .16       0  4963.8     .07       0
  5008.5     .16       0  5095.3     .05       0  5131.7     .16       0
  5212.8     .05       0  5565.3     .16       0
Bank Sta=4963.8,5008.5
XS Rating Curve= 0 ,0
Exp/Cntr=0.3,0.1

Type RM Length L Ch R = 1 ,68281   ,504,504,504
BEGIN DESCRIPTION:
ALLIGATOR BRANCH 40.0
END DESCRIPTION:
XS GIS Cut Line= 3
      3671499.64     10533460.22      3670999.61     10533010.19
      3670699.62     10532210.21
#Sta/Elev= 30
  4283.6   327.2  4311.7  324.29  4325.9  320.79  4382.7  312.48  4404.4  307.42
  4411.1  308.07  4467.9  300.33  4488.8  299.27  4496.3  297.08  4552.7  291.83
  4559.8  289.74  4637.5  283.42    4732  270.85  4843.1  260.11    4864  259.67
  4885.7   256.3  4942.5  252.47    4953  249.16    4959  249.16  4966.1  248.16
  4977.7  242.99  4996.1  239.37  5009.7  243.63    5234  247.22  5428.9  257.57
  5459.2  258.87    5469  257.62  5544.6  266.11  5679.9  286.15  5810.7  295.04
#Mann= 4 ,-1 , 0
  4283.6     .05       0    4732     .16       0    4959     .07       0
  5009.7     .16       0
Bank Sta=4959,5009.7
XS Rating Curve= 0 ,0
Exp/Cntr=0.3,0.1

Type RM Length L Ch R = 1 ,67777   ,522,522,522
BEGIN DESCRIPTION:
ALLIGATOR BRANCH 39.0
END DESCRIPTION:
XS GIS Cut Line= 3
       3671499.6     10533410.17      3671299.61     10532660.19
      3670999.61      10532060.2
#Sta/Elev= 30
    4227  321.96  4299.4  315.08  4319.5  310.07  4324.7  310.63  4394.9  301.93
    4465  294.31  4582.1  277.33    4641  268.89  4785.2  255.97  4790.4  254.04
  4837.6  251.84    4876  247.73  4899.7  245.81  4905.5  243.92  4920.4  243.99
  4951.2  238.04  4985.7  241.74    5006  239.42  5025.5  244.96  5047.9  246.26
    5115  244.54  5179.1  246.81  5263.8  253.17  5464.4  267.91  5548.2   278.1
  5562.2  281.18  5615.3  286.46  5620.9  288.78  5651.6  292.14    5674   292.5
#Mann= 8 ,-1 , 0
    4227     .05       0  4394.9     .16       0  4582.1     .05       0
    4876     .16       0  4920.4     .07       0  4985.7     .16       0
  5179.1     .05       0  5263.8     .16       0
Bank Sta=4920.4,5025.5
XS Rating Curve= 0 ,0
Exp/Cntr=0.3,0.1

Type RM Length L Ch R = 1 ,67255   ,402,402,402
BEGIN DESCRIPTION:
ALLIGATOR BRANCH 38.0
END DESCRIPTION:
XS GIS Cut Line= 3
      3671549.61     10532960.21      3671649.61     10532360.19
      3671699.61     10531760.17
#Sta/Elev= 30
  4417.3  264.04  4445.2   260.5    4478     260    4506  256.48  4599.8  249.86
  4727.9  245.81    4833  245.25    4871  243.25  4911.9  243.25    4985  241.38
  4992.4  237.74  5005.3  238.36  5023.1  242.21  5045.7  244.57  5065.7  244.34
  5088.3  246.88  5115.9  246.68    5146  250.56  5186.2  252.37  5196.2  251.83
  5203.7   249.8  5208.7  253.47  5329.1     260    5437  270.87  5444.5  272.84
  5457.1  273.24    5502  278.89  5555.2  287.31  5597.6  295.12  5627.7  298.09
#Mann= 8 ,-1 , 0
  4417.3     .05       0    4478     .12       0  4727.9     .05       0
  4911.9     .16       0    4985     .07       0  5023.1     .16       0
    5502     .12       0  5555.2     .16       0
Bank Sta=4985,5023.1
XS Rating Curve= 0 ,0
Exp/Cntr=0.3,0.1

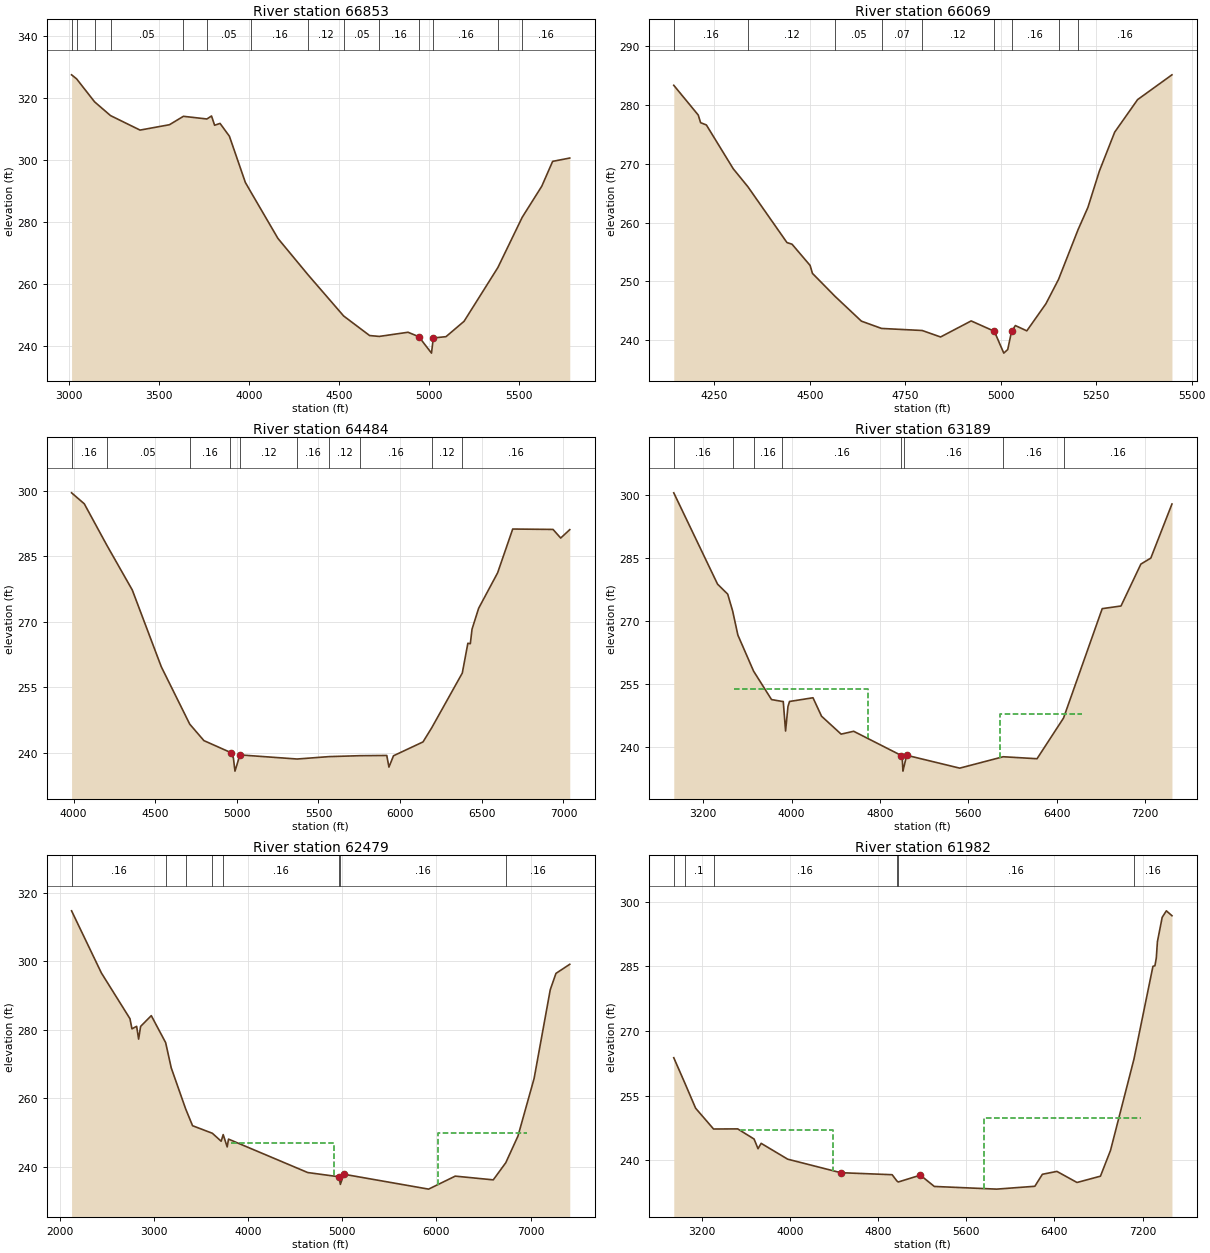
Type RM Length L Ch R = 1 ,66853   ,784,784,784
BEGIN DESCRIPTION:
ALLIGATOR BRANCH 37.0
END DESCRIPTION:
XS GIS Cut Line= 2
      3672123.65     10534271.58      3671841.52     10531515.48
#Sta/Elev= 30
  3013.3  327.43  3041.3  326.13  3141.4  318.72  3229.9   314.3  3394.2  309.63
  3557.5  311.36  3635.3  314.07  3765.8  313.21  3791.6  314.17  3808.8  311.19
    3839  311.78    3891  307.66  3979.7  292.78    4010  289.72  4160.7  274.76
  4328.4  263.02  4526.4  249.76  4670.8  243.46  4724.5  243.18  4884.4  244.52
  4944.7  243.09  5014.8   237.8  5025.1  242.69  5095.5   243.1    5196  248.05
    5384  265.36  5519.5  281.56  5628.3  291.57  5688.6  299.56  5783.8  300.63
#Mann= 14 ,-1 , 0
  3013.3     .05       0  3041.3      .1       0  3141.4     .16       0
  3229.9     .05       0  3635.3     .16       0  3765.8     .05       0
    4010     .16       0  4328.4     .12       0  4526.4     .05       0
  4724.5     .16       0  4944.7     .07       0  5025.1     .16       0
    5384     .12       0  5519.5     .16       0
Bank Sta=4944.7,5025.1
XS Rating Curve= 0 ,0
Exp/Cntr=0.3,0.1

Type RM Length L Ch R = 1 ,66069   ,1585,1585,1585
BEGIN DESCRIPTION:
ALLIGATOR BRANCH 36.0
END DESCRIPTION:
XS GIS Cut Line= 3
       3672949.6     10533110.17      3672649.61     10532310.19
      3672649.61     10531860.17
#Sta/Elev= 30
    4144  283.36  4208.1   278.3  4214.3     277  4229.4  276.61  4299.7  269.16
  4338.2  266.09  4440.4   256.6  4453.7  256.32  4500.9  252.72  4507.1  251.36
  4566.6  247.43  4635.3  243.23  4688.1  241.99  4794.4  241.64  4842.6  240.54
  4922.7  243.27  4983.3  241.51  5008.1  237.79  5018.4   238.4  5028.4  241.47
  5038.4  242.48  5068.4  241.58  5118.4  246.19  5151.4  250.33  5202.6   258.8
  5228.4  262.59  5258.4  268.77  5298.4  275.38  5358.4  280.92  5448.4  285.14
#Mann= 9 ,-1 , 0
    4144     .16       0  4338.2     .12       0  4566.6     .05       0
  4688.1     .07       0  4794.4     .12       0  4983.3     .07       0
  5028.4     .16       0  5151.4     .12       0  5202.6     .16       0
Bank Sta=4983.3,5028.4
XS Rating Curve= 0 ,0
Exp/Cntr=0.3,0.1

Type RM Length L Ch R = 1 ,64484   ,1295,1295,1295
BEGIN DESCRIPTION:
ALLIGATOR BRANCH 35.0
END DESCRIPTION:
XS GIS Cut Line= 3
      3674055.07     10533457.78      3673946.56      10532144.8
      3672286.42     10531645.67
#Sta/Elev= 30
  3987.9  299.47  4065.8  296.96  4203.8  287.49  4359.7  277.25  4537.4  259.69
  4711.5  246.58  4798.2  242.81  4958.8  240.14  4964.3  239.93  4978.9  238.85
  4988.6  235.83    5019  239.54  5369.6   238.6  5565.3  239.15  5754.9  239.36
  5918.3  239.41  5931.5  236.75  5959.4  239.34  6140.2  242.51  6193.7  245.75
  6380.8  258.26  6414.8  265.06  6429.9  264.97  6440.4  268.29  6480.9  273.07
    6597  281.17  6689.5  291.19  6936.4   291.1  6983.4  289.13  7038.9  291.05
#Mann= 10 ,-1 , 0
  3987.9     .16       0  4203.8     .05       0  4711.5     .16       0
  4958.8     .07       0    5019     .12       0  5369.6     .16       0
  5565.3     .12       0  5754.9     .16       0  6193.7     .12       0
  6380.8     .16       0
Bank Sta=4964.3,5019
XS Rating Curve= 0 ,0
Exp/Cntr=0.3,0.1

Type RM Length L Ch R = 1 ,63189   ,710,710,710
BEGIN DESCRIPTION:
ALLIGATOR BRANCH 34.0
END DESCRIPTION:
XS GIS Cut Line= 3
      3675899.59     10532910.17      3674349.61     10531510.19
       3671928.3     10531493.76
#Sta/Elev= 30
  2932.9  300.48  3329.3  278.76  3421.2  276.38  3466.2  272.35  3513.2  266.65
  3655.4  258.07    3818   251.3    3910  250.88  3924.2  250.84  3945.1  243.82
  3966.7  249.64  3980.9  250.85  4193.2  251.73  4270.9  247.34    4448  243.08
  4561.6  243.76  4993.5  237.99  5000.2  237.87  5007.5  234.28  5014.4  235.06
  5041.5  238.05  5521.6  234.99  5915.2   237.7  6221.6  237.23  6461.6  246.92
  6811.6  272.93  6981.6  273.56  7161.6  283.53  7251.6  284.96  7442.9  297.82
#Mann= 8 ,-1 , 0
  2932.9     .16       0  3466.2     .05       0  3655.4     .16       0
    3910     .16       0  4993.5     .07       0  5014.4     .16       0
  5915.2     .16       0  6461.6     .16       0
#XS Ineff= 2 ,-1
 3476.14 4689.77  253.93 5886.36 6632.95  247.82
Permanent Ineff=
       F       F
Bank Sta=4993.5,5041.5
XS Rating Curve= 0 ,0
Exp/Cntr=0.3,0.1

Type RM Length L Ch R = 1 ,62479   ,497,497,497
BEGIN DESCRIPTION:
ALLIGATOR BRANCH 33.0
END DESCRIPTION:
XS GIS Cut Line= 3
      3676420.53     10533056.27      3674228.68     10530940.37
      3672004.44     10531244.17
#Sta/Elev= 30
  2124.9   314.8  2441.1  296.65  2745.1  283.25  2766.2  280.28  2815.9  281.02
    2837  277.27  2858.3  280.99  2971.5  284.14  3124.1  276.25  3183.5  268.86
  3335.9  256.91  3409.9  251.94    3620  249.73  3713.9   247.4  3735.3  249.34
  3777.7  245.74  3791.9  248.02  4633.4  238.24  4965.7     237  4979.9  234.77
  5015.4  237.75  5917.1  233.39  6199.9  237.19  6603.7   236.1  6736.6  241.11
  6866.1  248.91  7037.6  265.76  7209.2  291.73  7269.8   296.5  7416.3  299.16
#Mann= 8 ,-1 , 0
  2124.9     .16       0  3124.1     .05       0  3335.9      .1       0
    3620     .05       0  3735.3     .16       0  4965.7     .07       0
  4979.9     .16       0  6736.6     .16       0
#XS Ineff= 2 ,-1
 3817.05 4907.95  246.78 6015.91 6967.05  249.79
Permanent Ineff=
       F       F
Bank Sta=4965.7,5015.4
XS Rating Curve= 0 ,0
Exp/Cntr=0.3,0.1

Type RM Length L Ch R = 1 ,61982   ,1038,1038,1038
BEGIN DESCRIPTION:
ALLIGATOR BRANCH 32.0
END DESCRIPTION:
XS GIS Cut Line= 3
      3675799.61     10532210.19      3674399.61     10530660.19
      3671999.58     10531060.19
#Sta/Elev= 30
  2944.3   263.8  3043.8  257.99  3142.7   252.1  3305.6  247.28  3524.6  247.31
  3673.3  244.96  3709.1  242.71  3737.5  243.96  3978.2  240.29  4459.4  237.16
  4926.5  236.69  4969.1  235.26  4981.7     235  5182.5  236.59  5309.2  233.97
  5874.2  233.35  6221.6  234.01  6290.1  236.79  6421.9  237.46  6604.3  234.89
  6817.2  236.35  6908.5  242.33  7121.4  263.49  7293.7  284.99  7311.5  285.11
  7324.1  286.91  7334.3  290.71  7377.4  296.33  7415.4  297.84  7466.1  296.71
#Mann= 6 ,-1 , 0
  2944.3     .05       0  3043.8      .1       0  3305.6     .16       0
  4969.1     .07       0  4981.7     .16       0  7121.4     .16       0
#XS Ineff= 2 ,-1
 3550.49 4392.45246.9876 5756.82 7185.23  249.89
Permanent Ineff=
       F       F
Bank Sta=4459.4,5182.5
XS Rating Curve= 0 ,0
Exp/Cntr=0.3,0.1