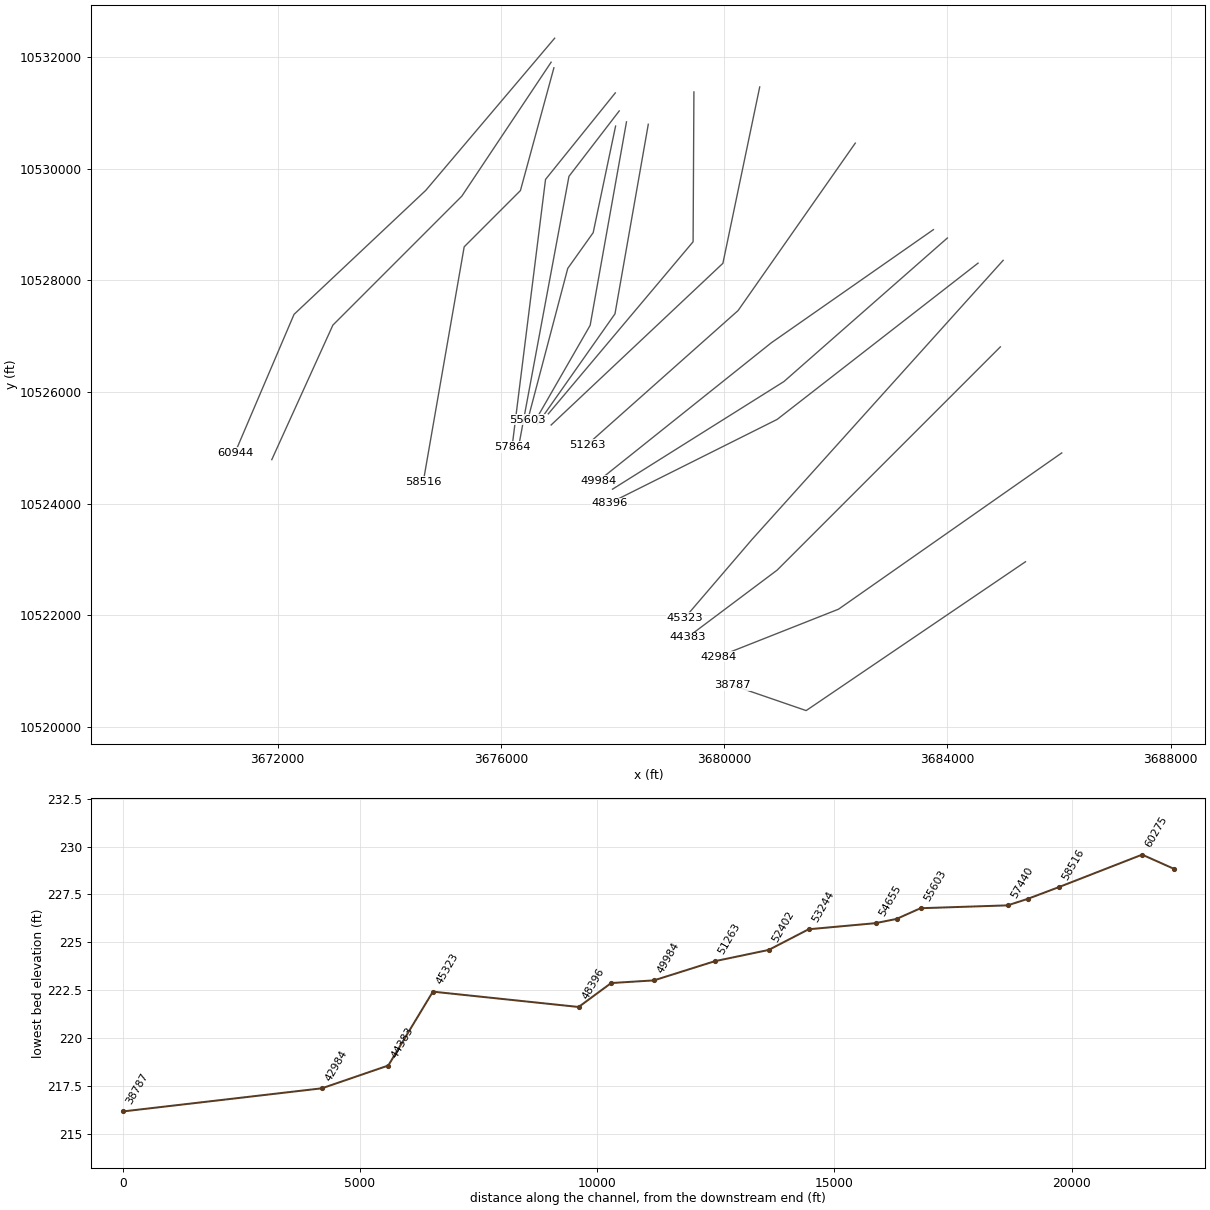
HEC-RAS study ALLIGATOR BRANCH.prj: ALLIGATOR BRANCH Base Level Engineering

--- ALLIGATOR BRANCH.g01 (geometry) --- (continued)

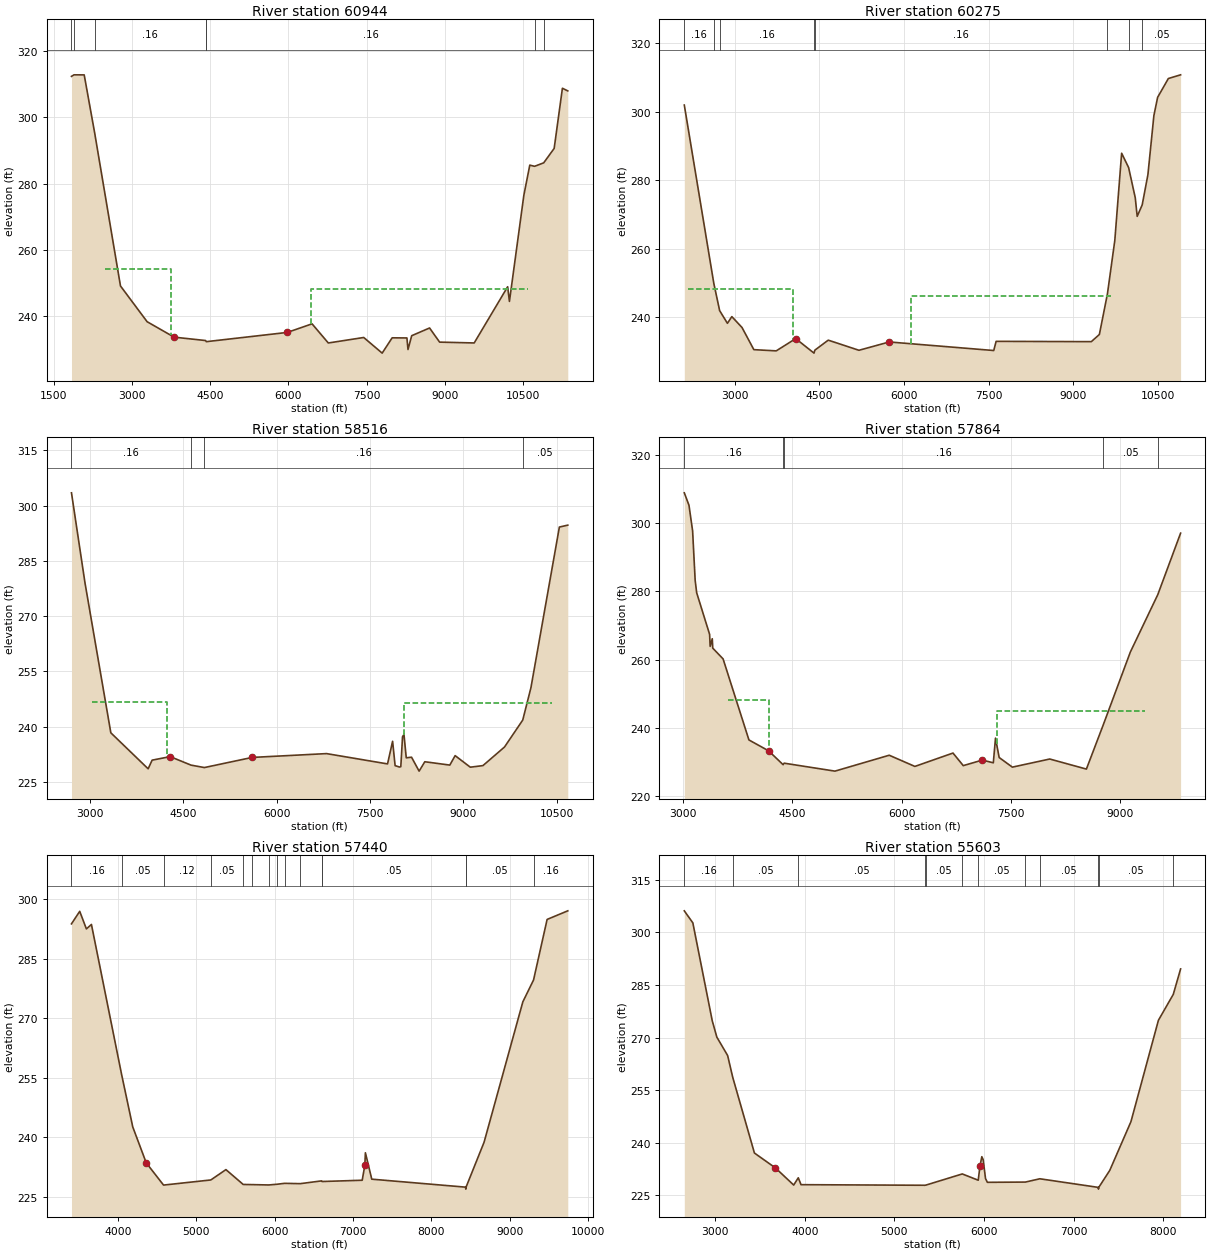
Type RM Length L Ch R = 1 ,60944   ,669,669,669
BEGIN DESCRIPTION:
ALLIGATOR BRANCH 31.0
END DESCRIPTION:
XS GIS Cut Line= 4
      3676963.08     10532340.14      3674654.02     10529614.42
      3672292.91     10527392.19      3671234.27     10524910.45
#Sta/Elev= 30
  1843.6  312.37  1892.7  312.83  2087.4  312.81  2286.2  295.47  2782.8  249.11
  3293.6  238.32    3811  233.66  4414.1  232.64  4428.4   232.3    5981  235.09
  6454.7  237.68  6766.3   231.9  7445.2  233.56  7798.6  228.84  7989.9  233.46
    8273  233.42    8294  229.94  8364.8   234.1  8707.2  236.43  8899.7  232.16
  9562.8  231.91 10203.7  248.87 10238.2  244.45 10514.3  276.48 10628.3  285.58
 10719.5  285.22 10895.1  286.27 11095.5  290.62 11253.5  308.78 11356.4  307.98
#Mann= 7 ,-1 , 0
  1843.6     .05       0  1892.7     .16       0  2286.2     .16       0
  4414.1     .07       0  4428.4     .16       0 10719.5     .16       0
 10895.1     .05       0
#XS Ineff= 2 ,-1
 2495.45 3743.18  254.17 6436.3610588.64248.1564
Permanent Ineff=
       F       F
Bank Sta=3811,5981
XS Rating Curve= 0 ,0
Exp/Cntr=0.3,0.1

Type RM Length L Ch R = 1 ,60275   ,1759,1759,1759
BEGIN DESCRIPTION:
ALLIGATOR BRANCH 30.0
END DESCRIPTION:
XS GIS Cut Line= 4
       3676899.6     10531910.18      3675299.61     10529510.19
        3672989.     10527199.58       3671894.1     10524789.12
#Sta/Elev= 30
  2103.7  302.01  2626.8  249.97  2730.2     242  2868.4  238.28  2946.5  240.24
  3126.8  237.07  3337.1  230.59  3733.7  230.24  4079.2  233.82  4403.5  229.58
  4418.8  230.45  4656.1  233.37  5200.3  230.41  5737.7  232.84  7590.3  230.34
  7632.7  233.02  9320.5  232.93  9463.3  235.03  9606.1  246.89  9736.9   262.5
  9857.8  287.95  9981.7  283.76 10099.5  274.94 10133.6  269.52 10222.4  272.86
 10323.6  281.67 10429.8  298.96 10496.1  304.27 10686.2  309.76 10903.3  310.84
#Mann= 8 ,-1 , 0
  2103.7     .16       0  2626.8     .05       0  2730.2     .16       0
  4403.5     .07       0  4418.8     .16       0  9606.1     .05       0
  9981.7     .16       0 10222.4     .05       0
#XS Ineff= 2 ,-1
 2170.45 4034.09  248.29 6119.32 9670.45246.2866
Permanent Ineff=
       F       F
Bank Sta=4079.2,5737.7
XS Rating Curve= 0 ,0
Exp/Cntr=0.3,0.1

Type RM Length L Ch R = 1 ,58516   ,652,652,652
BEGIN DESCRIPTION:
ALLIGATOR BRANCH 29.0
END DESCRIPTION:
XS GIS Cut Line= 4
      3676949.62     10531810.23      3676349.61     10529610.19
      3675341.85     10528602.43      3674609.54      10524397.2
#Sta/Elev= 30
  2705.2  303.49  2922.9  278.96  3337.5  238.29    3937  228.51  4000.9  230.86
  4291.1  231.82  4626.3  229.51  4840.5  228.85  5607.8   231.6  6803.3  232.64
  7783.4  229.84  7864.6  235.99  7905.1  229.37  7976.2  228.99  7996.5  229.08
  8024.3  237.23  8047.3  237.83  8083.9   231.5  8169.1  231.66  8290.6  227.88
  8382.3  230.43  8783.8  229.52  8869.5  232.09  9113.1  228.95  9316.1  229.38
  9662.6  234.43  9955.6  241.75 10087.5  250.56 10544.3  294.19 10679.3  294.71
#Mann= 4 ,-1 , 0
  2705.2     .16       0  4626.3     .05       0  4840.5     .16       0
  9955.6     .05       0
#XS Ineff= 2 ,-1
 3039.77 4232.95  246.66 8039.7710426.14  246.41
Permanent Ineff=
       F       F
Bank Sta=4291.1,5607.8
XS Rating Curve= 0 ,0
Exp/Cntr=0.3,0.1

Type RM Length L Ch R = 1 ,57864   ,424,424,424
BEGIN DESCRIPTION:
ALLIGATOR BRANCH 28.0
END DESCRIPTION:
XS GIS Cut Line= 3
       3678049.6     10531360.17      3676799.61     10529810.19
      3676199.41     10525015.02
#Sta/Elev= 30
  3012.4  308.89  3076.6  305.26  3126.7  297.74  3161.9   283.2  3182.7  279.58
  3360.3  267.39  3368.2  263.86    3397   266.1  3403.4  263.35  3545.8  260.18
  3900.9  236.42  4171.1  233.23    4371  229.16  4385.4   229.6    5084  227.27
    5830  231.93  6182.7  228.65  6706.8  232.57  6847.9  228.88  7109.9  230.51
  7261.1  229.71  7291.3  236.95  7341.7  231.26  7523.1  228.44  8037.1  230.82
    8541  227.87  8772.8  240.84  9145.4   262.2  9522.4  279.02  9836.2  297.06
#Mann= 5 ,-1 , 0
  3012.4     .16       0    4371     .05       0  4385.4     .16       0
  8772.8     .05       0  9522.4     .16       0
#XS Ineff= 2 ,-1
 3608.52  4173.3  248.16 7307.39 9343.75  244.91
Permanent Ineff=
       F       F
Bank Sta=4171.1,7109.9
XS Rating Curve= 0 ,0
Exp/Cntr=0.3,0.1

Type RM Length L Ch R = 1 ,57440   ,1837,1837,1837
BEGIN DESCRIPTION:
ALLIGATOR BRANCH 27.0
END DESCRIPTION:
XS GIS Cut Line= 3
      3678119.93     10531036.95      3677219.35     10529865.11
       3676329.6     10525090.83
#Sta/Elev= 30
  3406.2  293.85  3511.4     297  3596.5  292.57  3660.9  293.69  4046.4  255.81
  4188.3  242.62  4360.5  233.55  4581.2  227.95  5184.6  229.24  5377.4  231.85
  5597.9  228.11  5704.4  228.07  5924.5  227.98    6025  228.15  6125.5  228.39
  6326.6  228.31  6597.9  229.01    6604  228.85  7116.8  229.17  7150.2  232.91
  7157.5   236.1  7238.9  229.44  8436.2  227.43    8439  226.93  8442.2  227.43
  8672.1  238.75    9167  274.17  9303.7  279.69  9476.8  294.96  9740.6  297.13
#Mann= 15 ,-1 , 0
  3406.2     .16       0  4046.4     .05       0  4581.2     .12       0
  5184.6     .05       0  5597.9     .12       0  5704.4     .05       0
  5924.5     .12       0    6025     .05       0  6125.5     .07       0
  6326.6     .05       0  6597.9     .07       0    6604     .05       0
  8436.2     .07       0  8442.2     .05       0  9303.7     .16       0
Bank Sta=4360.5,7150.2
XS Rating Curve= 0 ,0
Exp/Cntr=0.3,0.1

Type RM Length L Ch R = 1 ,55603   ,506,506,506
BEGIN DESCRIPTION:
ALLIGATOR BRANCH 26.0
END DESCRIPTION:
XS GIS Cut Line= 4
      3678054.85      10530765.7      3677653.38       10528856.
      3677197.65      10528215.8      3676481.78     10525504.19
#Sta/Elev= 30
  2653.9  306.11  2749.3  302.68  2966.1  274.77  3017.2  270.12  3137.9  264.86
  3194.7  258.66    3437  237.07  3670.9  232.84  3875.5  227.94  3926.6  230.01
  3957.3  228.05  5338.6  227.88  5351.9  227.93  5758.1  231.11  5935.9  229.32
  5956.1  233.44  5976.2  236.02  5991.2  235.17  6017.5  229.77  6038.2  228.72
  6462.8  228.79  6624.1  229.73  7275.9  227.28  7278.6  226.78  7281.9  227.28
  7404.9  232.13  7641.3  246.01    7948  274.91  8113.9  282.29  8195.7  289.54
#Mann= 12 ,-1 , 0
  2653.9     .16       0  3194.7     .05       0  3926.6     .05       0
  5338.6     .07       0  5351.9     .05       0  5758.1     .16       0
  5935.9     .05       0  6462.8     .12       0  6624.1     .05       0
  7275.9     .07       0  7281.9     .05       0  8113.9     .16       0
Bank Sta=3670.9,5956.1
XS Rating Curve= 0 ,0
Exp/Cntr=0.3,0.1

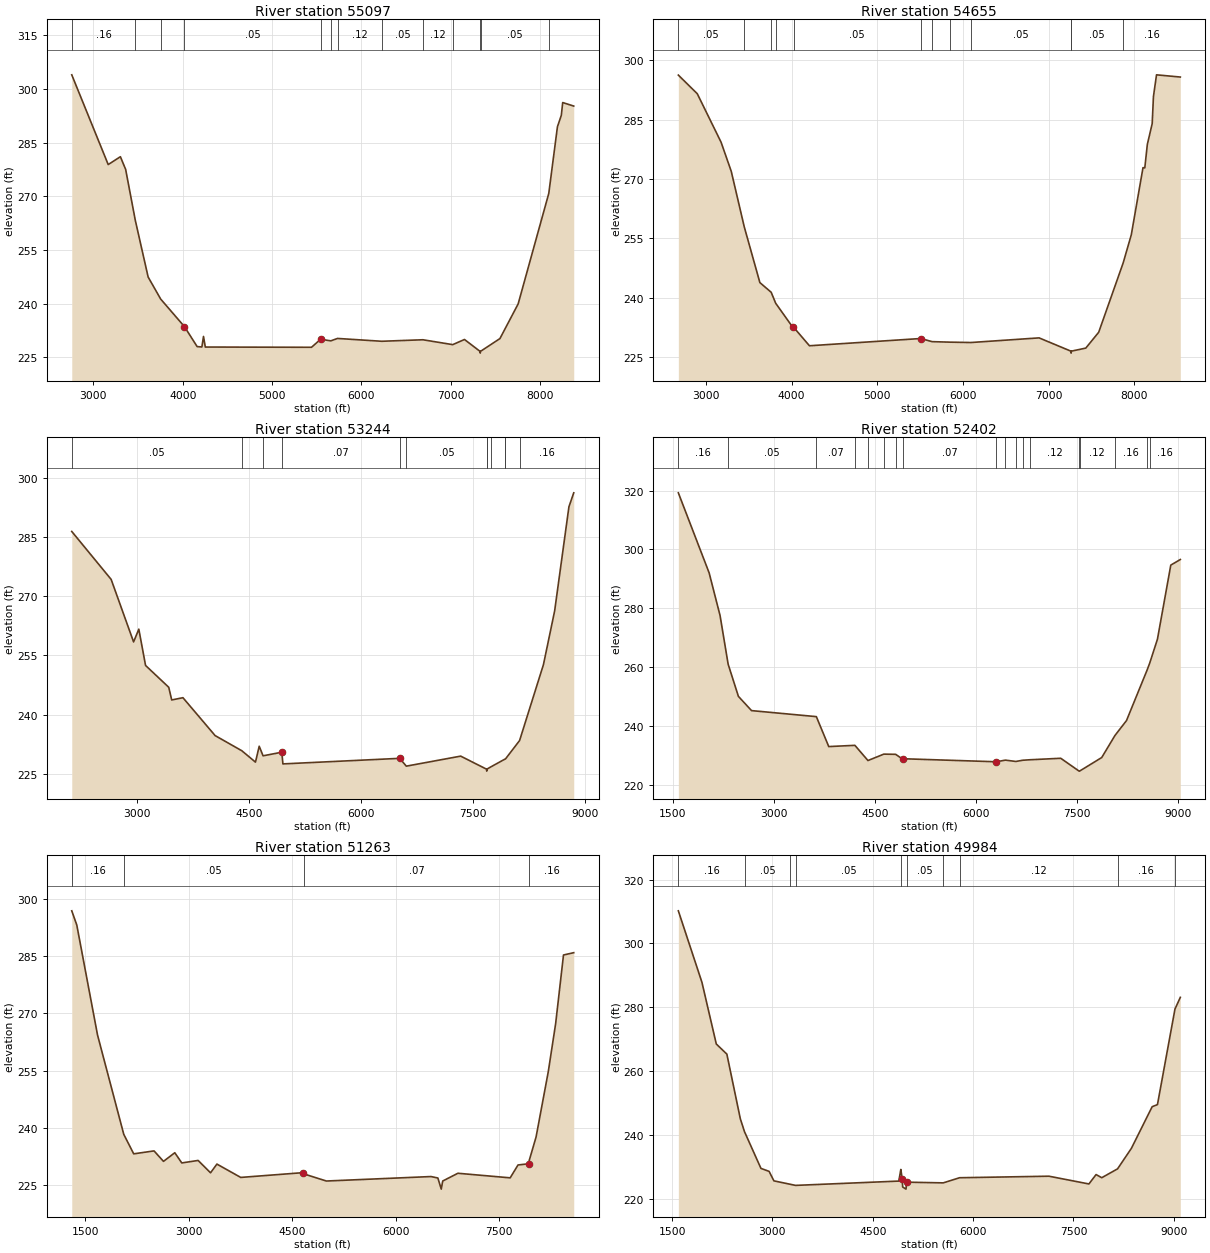
Type RM Length L Ch R = 1 ,55097   ,442,442,442
BEGIN DESCRIPTION:
ALLIGATOR BRANCH 25.0
END DESCRIPTION:
XS GIS Cut Line= 3
      3678250.17     10530841.71      3677599.13     10527195.84
      3676644.42     10525535.96
#Sta/Elev= 30
  2757.7  303.91  3165.6  278.86    3302  281.05  3360.9  277.51  3469.1  263.27
  3612.5  247.47    3753  241.31  4018.9  233.62  4161.1  228.04  4214.2  227.94
  4232.2  230.87  4252.5  227.92    5441  227.85  5542.6  230.08  5657.5  229.65
  5732.3  230.32  6226.5  229.53  6688.3  229.95  7021.7  228.59  7153.2  230.03
    7327  226.72  7329.7  226.22    7333  226.72  7549.9  230.28    7754  239.96
  8096.8  270.81  8193.8  289.43  8236.9  292.59  8252.7  296.17  8376.1  295.19
#Mann= 13 ,-1 , 0
  2757.7     .16       0  3469.1     .05       0    3753     .12       0
  4018.9     .05       0  5542.6     .12       0  5657.5     .05       0
  5732.3     .12       0  6226.5     .05       0  6688.3     .12       0
  7021.7     .05       0    7327     .07       0    7333     .05       0
  8096.8     .16       0
Bank Sta=4018.9,5542.6
XS Rating Curve= 0 ,0
Exp/Cntr=0.3,0.1

Type RM Length L Ch R = 1 ,54655   ,1411,1411,1411
BEGIN DESCRIPTION:
ALLIGATOR BRANCH 24.0
END DESCRIPTION:
XS GIS Cut Line= 3
      3678640.79     10530798.24        3678044.       10527402.
      3676655.11     10525427.17
#Sta/Elev= 30
  2676.7  296.23  2898.1  291.52    3176  279.27  3294.7  271.92  3446.4  257.91
  3629.1  243.81  3761.1  241.37  3813.6   238.6  4014.9  232.48  4025.1  232.48
  4207.9  227.86  5507.5  229.69  5639.5   228.9  5852.1  228.77  6094.2  228.68
    6890  229.85  7261.2   226.5  7263.9     226  7267.2   226.5  7435.3  227.27
  7586.1  231.27  7872.1   248.8  7966.8  255.89  8103.6  272.85  8124.5  272.79
  8154.1  278.72  8210.8  283.97  8225.6  290.83  8261.3   296.3  8539.3  295.74
#Mann= 12 ,-1 , 0
  2676.7     .05       0  3446.4     .12       0  3761.1     .07       0
  3813.6     .12       0  4025.1     .05       0  5507.5     .05       0
  5639.5     .12       0  5852.1     .16       0  6094.2     .05       0
  7261.2     .03       0  7267.2     .05       0  7872.1     .16       0
Bank Sta=4014.9,5507.5
XS Rating Curve= 0 ,0
Exp/Cntr=0.3,0.1

Type RM Length L Ch R = 1 ,53244   ,842,842,842
BEGIN DESCRIPTION:
ALLIGATOR BRANCH 23.0
END DESCRIPTION:
XS GIS Cut Line= 3
      3679458.21     10531376.99      3679443.74     10528693.24
      3676849.63     10525610.21
#Sta/Elev= 30
  2131.9  286.41  2658.7  274.26  2958.7  258.42  3028.7  261.65  3118.7  252.46
  3428.7  246.93  3468.7  243.71  3618.7  244.29  4048.7  234.69  4406.5  230.84
  4588.7  227.96  4638.7  231.99  4690.1  229.56  4941.2  230.47  4955.5  227.51
  6517.5  228.92  6605.8  226.94    7333  229.48  7678.5  226.18  7681.3  225.68
  7684.5  226.18  7684.6  226.19  7733.1  226.72  7923.6  228.71  7931.1  228.74
  8120.7  233.43  8439.8  252.67  8589.4  266.26  8780.6  292.66  8844.9   296.2
#Mann= 13 ,-1 , 0
  2131.9     .05       0  4406.5     .12       0  4690.1     .05       0
  4941.2     .07       0  6517.5     .16       0  6605.8     .05       0
  7678.5     .03       0  7684.5     .05       0  7684.6     .16       0
  7733.1     .05       0  7923.6     .16       0  7931.1     .05       0
  8120.7     .16       0
Bank Sta=4941.2,6517.5
XS Rating Curve= 0 ,0
Exp/Cntr=0.3,0.1

Type RM Length L Ch R = 1 ,52402   ,1139,1139,1139
BEGIN DESCRIPTION:
ALLIGATOR BRANCH 22.0
END DESCRIPTION:
XS GIS Cut Line= 3
      3680637.32     10531466.66       3679977.6     10528306.95
      3676899.59     10525410.17
#Sta/Elev= 30
  1583.5  319.24  2040.9  292.02  2203.1  277.51  2323.1  260.97  2475.6  250.02
  2670.5  245.18  3633.2  243.13  3817.1  232.95  4205.3  233.37  4399.4   228.2
  4634.9  230.38  4811.3  230.31  4913.8  228.68  4920.7  228.81  6307.2  227.78
  6439.6  228.34  6595.7  227.89  6697.2   228.3  6808.4  228.47  7262.5  228.97
  7535.4   224.6  7541.4   224.6  7870.8  229.22  8067.5  236.72  8238.8  241.79
  8544.8  258.96  8583.4  261.31  8698.4  269.46  8896.7  294.66  9038.1  296.56
#Mann= 18 ,-1 , 0
  1583.5     .16       0  2323.1     .05       0  3633.2     .07       0
  4205.3     .12       0  4399.4     .05       0  4634.9     .12       0
  4811.3     .07       0  4913.8     .07       0  6307.2     .12       0
  6439.6     .16       0  6595.7     .12       0  6697.2     .16       0
  6808.4     .12       0  7535.4     .03       0  7541.4     .12       0
  8067.5     .16       0  8544.8     .12       0  8583.4     .16       0
Bank Sta=4920.7,6307.2
XS Rating Curve= 0 ,0
Exp/Cntr=0.3,0.1

Type RM Length L Ch R = 1 ,51263   ,1279,1279,1279
BEGIN DESCRIPTION:
ALLIGATOR BRANCH 21.0
END DESCRIPTION:
XS GIS Cut Line= 3
      3682349.63     10530460.22      3680249.61     10527460.19
       3677549.6     10525060.18
#Sta/Elev= 30
  1305.2   296.8    1378  293.09  1678.8  264.31  2058.8  238.34  2202.9  233.24
  2497.6  234.01  2634.4  231.27  2798.4  233.53  2899.5  230.86  3136.2  231.51
  3316.3  228.28  3408.7  230.56    3754  227.07    4659  228.32  4665.1  228.01
  4995.2  226.13  6511.3   227.3  6610.8  226.92  6659.9  224.01    6681  226.13
    6901  228.16  7658.6  226.96  7772.3  230.33  7927.8  230.64  7935.4  231.56
  8034.1  237.66  8211.3  254.78  8317.5  267.29  8431.3  285.25  8579.7  285.85
#Mann= 4 ,-1 , 0
  1305.2     .16       0  2058.8     .05       0  4665.1     .07       0
  7935.4     .16       0
Bank Sta=4659,7927.8
XS Rating Curve= 0 ,0
Exp/Cntr=0.3,0.1

Type RM Length L Ch R = 1 ,49984   ,903,903,903
BEGIN DESCRIPTION:
ALLIGATOR BRANCH 20.0
END DESCRIPTION:
XS GIS Cut Line= 3
      3683749.61     10528910.19      3680845.65     10526883.34
      3677749.62      10524410.2
#Sta/Elev= 30
  1593.7  310.22  1946.6  287.81  2161.2  268.48    2319  265.32  2520.5  245.04
  2583.2  240.99  2828.5  229.51  2950.6  228.57  3022.1   225.6  3266.7  224.53
    3346  224.18  4889.8  225.53  4919.5  229.18  4925.6  228.35  4940.4  226.12
  4947.3  223.68  4996.9  223.01  5005.8  225.19  5553.7  224.97  5798.1  226.58
  7133.9  227.06  7731.1  224.63  7838.4  227.57  7923.2  226.59  8159.4  229.36
  8365.1  235.75  8677.3  248.85  8755.8  249.49  9017.9  279.46  9097.6   283.1
#Mann= 10 ,-1 , 0
  1593.7     .16       0  2583.2     .05       0  3266.7     .07       0
    3346     .05       0  4925.6     .07       0  5005.8     .05       0
  5553.7     .05       0  5798.1     .12       0  8159.4     .16       0
  9017.9     .12       0
Bank Sta=4940.4,5005.8
XS Rating Curve= 0 ,0
Exp/Cntr=0.3,0.1

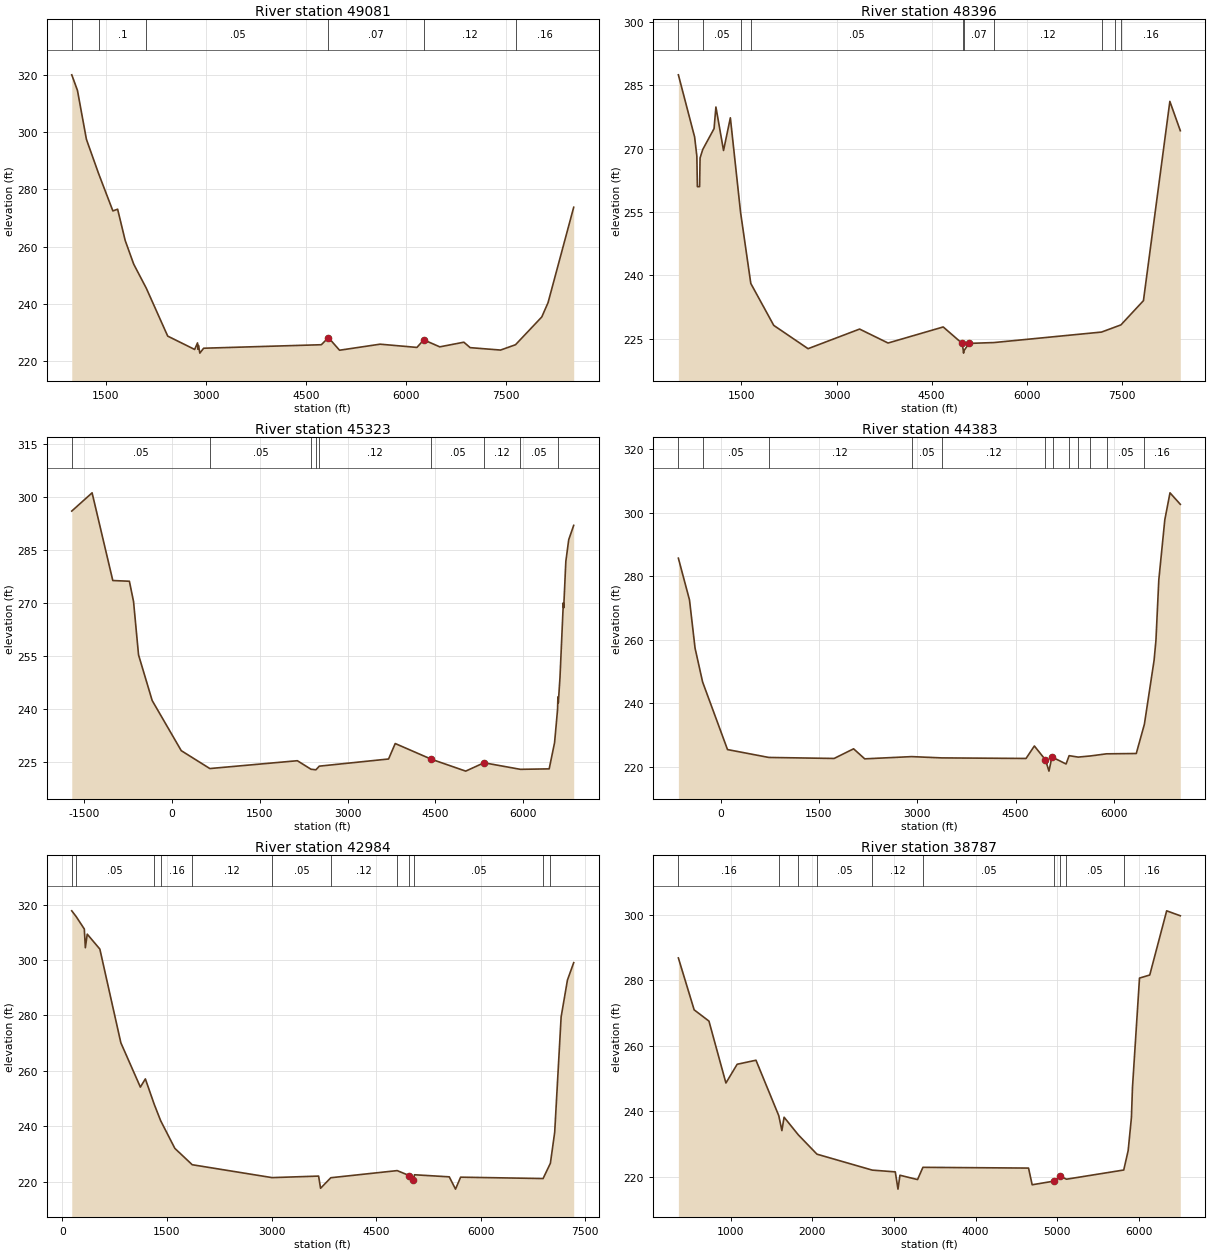
Type RM Length L Ch R = 1 ,49081   ,685,685,685
BEGIN DESCRIPTION:
ALLIGATOR BRANCH 19.0
END DESCRIPTION:
XS GIS Cut Line= 3
      3683999.64     10528760.22      3681071.35      10526188.9
      3677999.65     10524260.21
#Sta/Elev= 30
   989.5  319.94  1074.5  314.54  1209.2  297.44  1391.8  285.49  1605.9  272.47
    1677  273.07  1789.9   262.2    1918  253.91  2107.4  245.48  2427.6  228.81
  2831.8  224.15  2874.5  226.44  2881.2  224.22  2888.8  225.55  2909.4  222.87
  2966.6  224.58  4730.6   225.8  4836.9  228.29  5003.5  223.88  5611.4  225.99
  6163.8  224.86  6265.2  227.51  6505.5  225.06  6867.2  226.68  6961.5  224.78
  7417.4  223.94  7641.3   225.8  8034.7  235.48  8128.9  240.47  8513.5  273.75
#Mann= 6 ,-1 , 0
   989.5     .16       0  1391.8      .1       0  2107.4     .05       0
  4836.9     .07       0  6265.2     .12       0  7641.3     .16       0
Bank Sta=4836.9,6265.2
XS Rating Curve= 0 ,0
Exp/Cntr=0.3,0.1

Type RM Length L Ch R = 1 ,48396   ,3073,3073,3073
BEGIN DESCRIPTION:
ALLIGATOR BRANCH 18.0
END DESCRIPTION:
XS GIS Cut Line= 3
      3684549.59     10528310.17      3680949.61     10525510.19
      3677949.59     10524010.18
#Sta/Elev= 30
   506.5  287.44   762.6  272.75   797.9   268.2     806  260.99   841.3  260.99
   848.5  267.77     891  269.79  1069.3  274.72  1098.3  279.83  1218.6  269.55
  1326.3  277.28  1487.2  254.91  1648.5   238.1  2010.4  228.18  2551.6  222.67
  3364.2  227.31    3813  224.01  4682.6  227.81  4981.2  223.92  5000.8  222.12
  5003.6  221.62  5006.8  222.12  5089.5  223.92  5483.2  224.12    7179   226.6
  7388.2  227.76    7485   228.3  7839.9  234.03  8256.4  281.16  8421.3  274.22
#Mann= 10 ,-1 , 0
   506.5     .16       0     891     .05       0  1487.2      .1       0
  1648.5     .05       0  5000.8     .03       0  5006.8     .07       0
  5483.2     .12       0    7179     .05       0  7388.2     .12       0
    7485     .16       0
Bank Sta=4981.2,5089.5
XS Rating Curve= 0 ,0
Exp/Cntr=0.3,0.1

Type RM Length L Ch R = 1 ,45323   ,940,940,940
BEGIN DESCRIPTION:
ALLIGATOR BRANCH 17.0
END DESCRIPTION:
XS GIS Cut Line= 3
      3684999.61     10528360.19      3680499.61     10523360.19
      3679299.63     10521960.21
#Sta/Elev= 30
 -1709.3  296.13 -1362.1   301.3 -1008.6  276.44  -725.3  276.24  -654.3  270.48
  -569.1  255.37  -335.9  242.42   160.4  228.22   648.5  223.15  2142.6  225.37
  2375.2  222.96  2460.2   222.8  2517.4  223.83  3700.2  225.86  3813.8  230.24
  4429.7   225.8  5017.5  222.42  5329.8  224.79  5951.4  222.93  6442.7  223.06
  6534.9  230.51  6585.6  239.88    6592  243.45  6598.6  241.79  6627.1  248.92
  6684.2  270.12  6690.8  268.71    6727  281.84  6776.4  288.02  6861.4  292.08
#Mann= 9 ,-1 , 0
 -1709.3     .05       0   648.5     .05       0  2375.2     .12       0
  2460.2     .07       0  2517.4     .12       0  4429.7     .05       0
  5329.8     .12       0  5951.4     .05       0  6585.6     .16       0
Bank Sta=4429.7,5329.8
XS Rating Curve= 0 ,0
Exp/Cntr=0.3,0.1

Type RM Length L Ch R = 1 ,44383   ,1399,1399,1399
BEGIN DESCRIPTION:
ALLIGATOR BRANCH 16.0
END DESCRIPTION:
XS GIS Cut Line= 3
      3684949.58     10526810.16      3680949.61     10522810.19
      3679349.62      10521610.2
#Sta/Elev= 30
  -644.7  285.64    -475  272.49  -390.2  257.31  -275.3  246.66   104.8  225.35
   734.7  222.87  1731.1  222.55  2028.1  225.59  2197.8  222.43  2914.3  223.13
  3371.3  222.73  4658.6  222.55  4785.8  226.48  4955.5   222.1  5008.3  218.56
  5054.8  223.15  5069.4  222.85  5269.4  220.81  5315.9  223.43  5453.6  222.98
  5640.6  223.34  5886.4  224.01  6340.2  224.11    6464  233.32  6612.1  253.48
  6640.2  259.75    6684  278.79  6775.7  297.76  6854.8  306.23  7012.1  302.61
#Mann= 12 ,-1 , 0
  -644.7     .16       0  -275.3     .05       0   734.7     .12       0
  2914.3     .05       0  3371.3     .12       0  4955.5     .07       0
  5069.4     .12       0  5315.9     .05       0  5453.6     .07       0
  5640.6     .12       0  5886.4     .05       0    6464     .16       0
Bank Sta=4955.5,5054.8
XS Rating Curve= 0 ,0
Exp/Cntr=0.3,0.1

Type RM Length L Ch R = 1 ,42984   ,4197,4197,4197
BEGIN DESCRIPTION:
ALLIGATOR BRANCH 15.0
END DESCRIPTION:
XS GIS Cut Line= 3
       3686049.6     10524910.18      3682049.61     10522110.19
      3679896.04     10521259.23
#Sta/Elev= 30
   135.4  317.75   198.9  315.66   315.4  311.19   330.3  304.43   357.3  309.34
   538.2  303.95   839.4  270.15  1119.3  254.17  1190.8  257.13  1318.4  247.94
  1410.3  242.05  1613.7  232.07    1863  226.17  3007.7  221.52  3675.3  222.07
  3703.6  217.68  3850.5  221.48  4802.2  224.05  4974.8  222.26  5032.9   220.6
  5050.3  222.55  5549.4   221.8  5638.6  217.37  5711.7  221.68  6894.5  221.19
  6999.2  226.69    7061  237.87  7153.2  279.47  7243.7  292.76  7333.6  299.06
#Mann= 12 ,-1 , 0
   135.4     .16       0   198.9     .05       0  1318.4     .12       0
  1410.3     .16       0    1863     .12       0  3007.7     .05       0
  3850.5     .12       0  4802.2     .05       0  4974.8     .07       0
  5050.3     .05       0  6894.5     .07       0  6999.2     .16       0
Bank Sta=4974.8,5032.9
XS Rating Curve= 0 ,0
Exp/Cntr=0.3,0.1

Type RM Length L Ch R = 1 ,38787   ,4753,4753,4753
BEGIN DESCRIPTION:
ALLIGATOR BRANCH 14.0
END DESCRIPTION:
XS GIS Cut Line= 3
      3685399.61     10522960.19      3681469.35      10520293.5
      3680145.55     10520749.23
#Sta/Elev= 30
     359  286.79   552.4  270.94   733.6   267.5   941.5  248.58  1079.2  254.31
  1309.8  255.54  1589.1   238.6  1627.1  234.04  1654.2  238.13  1828.3  232.75
  2056.8  226.84  2734.4  221.97  3016.6  221.43  3049.6  216.16  3073.6   220.4
  3289.2  219.08    3355  222.82    4649  222.59  4693.6  217.49  4966.2  218.63
    5038  220.16  5113.7  219.19  5815.4     222  5869.7  227.95  5909.6  238.02
  5922.6  247.27  6008.6  280.64  6134.1  281.58  6341.5  301.19  6508.6  299.68
#Mann= 10 ,-1 , 0
     359     .16       0  1589.1     .05       0  1828.3     .16       0
  2056.8     .05       0  2734.4     .12       0    3355     .05       0
  4966.2     .07       0    5038     .12       0  5113.7     .05       0
  5815.4     .16       0
Bank Sta=4966.2,5038
XS Rating Curve= 0 ,0
Exp/Cntr=0.3,0.1