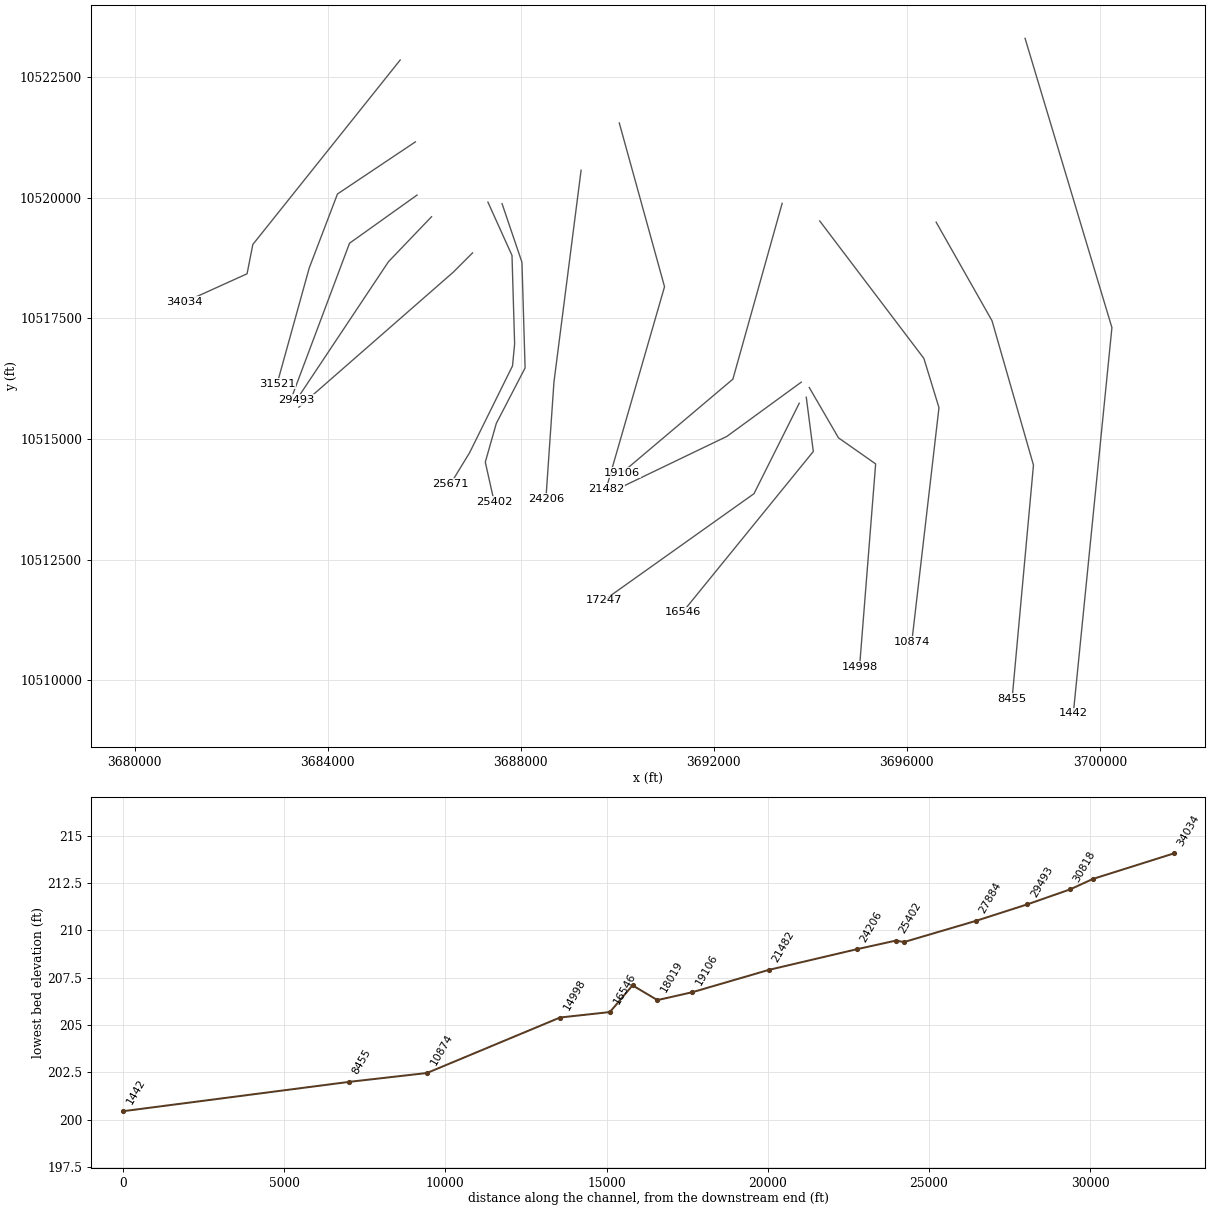
HEC-RAS study ALLIGATOR BRANCH.prj: ALLIGATOR BRANCH Base Level Engineering

--- ALLIGATOR BRANCH.g01 (geometry) --- (continued)

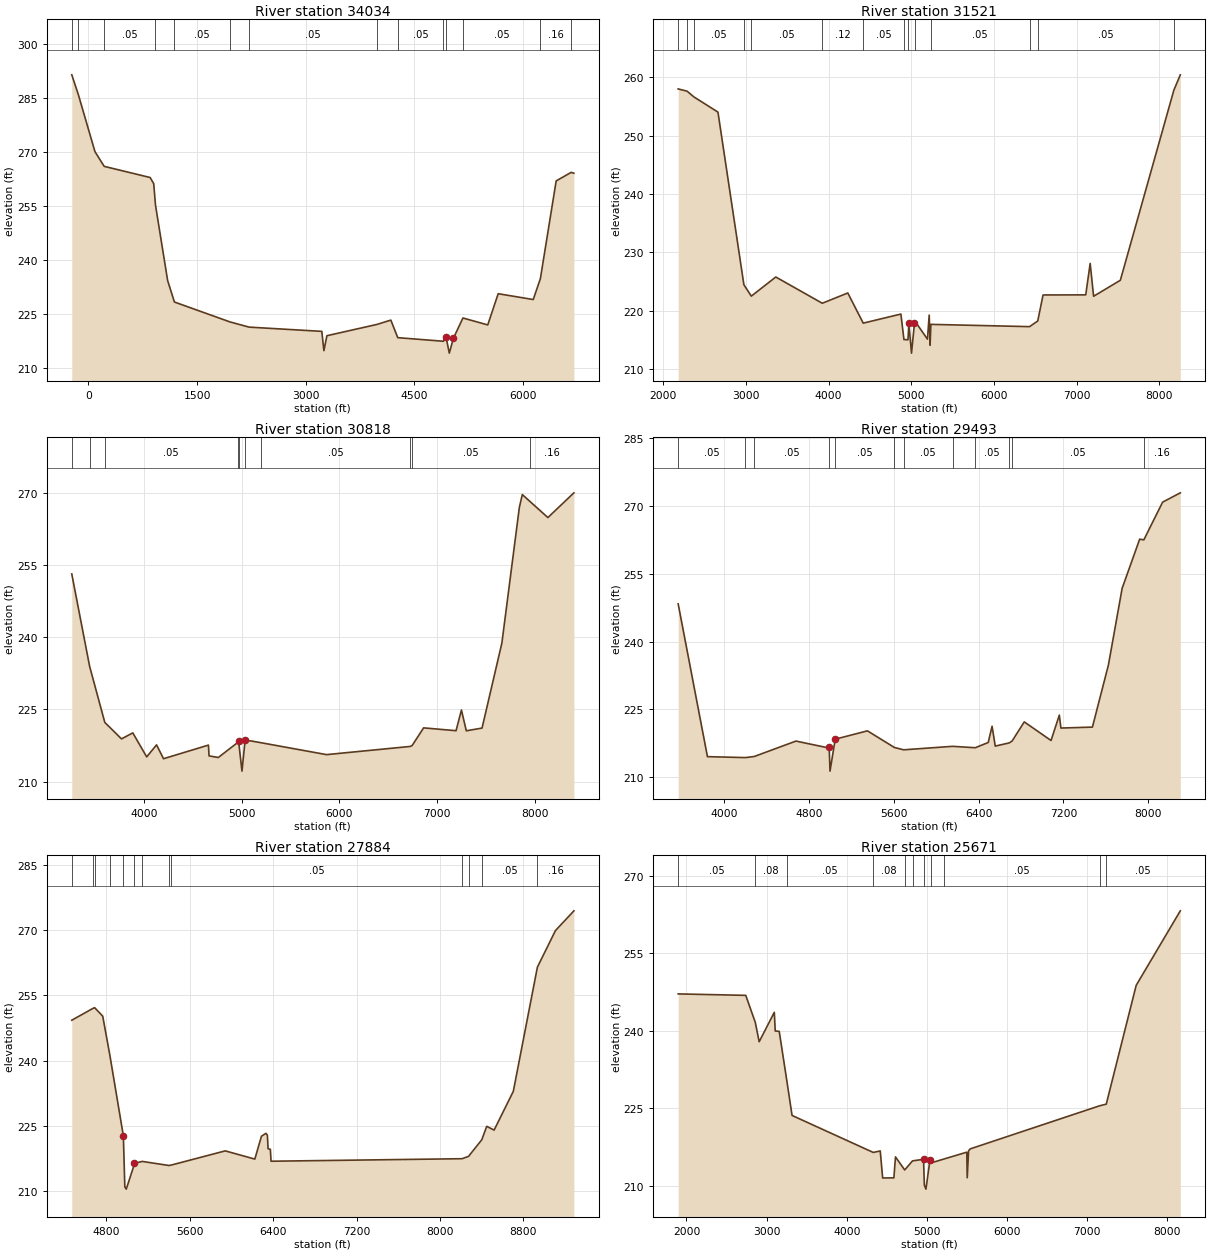
Type RM Length L Ch R = 1 ,34034   ,2513,2513,2513
BEGIN DESCRIPTION:
ALLIGATOR BRANCH 13.0
END DESCRIPTION:
XS GIS Cut Line= 4
      3685499.64     10522860.22      3682445.91     10519034.82
      3682326.56     10518427.18      3681035.93     10517842.32
#Sta/Elev= 30
  -229.6  291.44  -139.6  285.99    90.3  270.09   217.7  265.99     852  262.89
   901.7  261.17   925.8  255.25  1093.8  234.23  1187.4  228.27  1952.3  222.75
    2218  221.29  3221.7  220.11  3250.6  214.75  3292.2   218.9    3987  222.06
  4174.4  223.24  4270.1  218.36    4900  217.36  4930.6  218.28  4935.7  218.57
  4981.7  214.06  5038.5   218.2  5169.7  223.83  5512.2   221.9  5656.3  230.58
  6140.1  228.96  6238.8  234.78  6456.7  261.94  6663.5  264.32  6701.4  264.08
#Mann= 14 ,-1 , 0
  -229.6     .05       0  -139.6     .16       0   217.7     .05       0
   925.8     .12       0  1187.4     .05       0  1952.3     .12       0
    2218     .05       0    3987     .16       0  4270.1     .05       0
    4900     .12       0  4930.6     .07       0  5169.7     .05       0
  6238.8     .16       0  6663.5     .05       0
Bank Sta=4935.7,5038.5
XS Rating Curve= 0 ,0
Exp/Cntr=0.3,0.1

Type RM Length L Ch R = 1 ,31521   ,703,703,703
BEGIN DESCRIPTION:
Mapping XS 27f04f9c
END DESCRIPTION:
XS GIS Cut Line= 4
      3685814.62     10521162.65      3684200.03     10520081.92
      3683614.09     10518545.46      3682950.02     10516149.58
#Sta/Elev= 30
  2180.1     258  2287.5  257.62  2370.8  256.63  2661.2  254.03  2975.1  224.43
  3064.8  222.48  3360.7  225.76  3923.2  221.26  4231.9  223.02  4418.4  217.85
    4874  219.41    4911  215.04  4959.6     215  4970.3  217.79  5002.2  212.71
  5038.1  217.82  5045.3  218.16  5195.1  215.11  5216.5  219.23  5227.2  214.07
  5236.7  217.64  6430.3  217.25  6529.2  218.22  6593.5  222.68  7109.8   222.7
  7163.4  228.09  7204.9  222.46  7528.4   225.2  8175.5  257.78  8253.6  260.42
#Mann= 14 ,-1 , 0
  2180.1     .05       0  2287.5     .16       0  2370.8     .05       0
  2975.1     .12       0  3064.8     .05       0  3923.2     .12       0
  4418.4     .05       0    4911     .12       0  4959.6     .07       0
  5045.3     .12       0  5236.7     .05       0  6430.3     .07       0
  6529.2     .05       0  8175.5     .16       0
Bank Sta=4970.3,5038.1
XS Rating Curve= 0 ,0
Exp/Cntr=0.3,0.1

Type RM Length L Ch R = 1 ,30818   ,1325,1325,1325
BEGIN DESCRIPTION:
ALLIGATOR BRANCH 12.0
END DESCRIPTION:
XS GIS Cut Line= 3
      3685849.62      10520060.2      3684449.61     10519060.19
       3683249.6     10515860.17
#Sta/Elev= 30
  3261.2  253.14    3444  233.93  3599.1  222.29    3770  218.86  3885.5  220.11
    4028  215.12  4128.8  217.62  4200.1  214.74  4659.7  217.57  4665.9  215.33
  4760.5  214.99  4957.2  218.08  4968.2  218.41  5002.8  212.16  5035.1  218.64
  5201.8  218.05  5868.1  215.59  6724.1  217.29    6744  217.48  6861.4  221.15
  7193.3  220.56  7248.5  224.86  7298.3  220.54  7459.4  221.11  7662.4  238.79
  7841.3  266.99  7871.5  269.64  7952.2  268.16  8133.2  264.86  8399.3     270
#Mann= 10 ,-1 , 0
  3261.2     .05       0    3444     .16       0  3599.1     .05       0
  4957.2     .12       0  4968.2     .07       0  5035.1     .12       0
  5201.8     .05       0  6724.1     .07       0    6744     .05       0
  7952.2     .16       0
Bank Sta=4968.2,5035.1
XS Rating Curve= 0 ,0
Exp/Cntr=0.3,0.1

Type RM Length L Ch R = 1 ,29493   ,1609,1609,1609
BEGIN DESCRIPTION:
ALLIGATOR BRANCH 11.0
END DESCRIPTION:
XS GIS Cut Line= 3
      3686149.63     10519610.21      3685256.24     10518676.74
      3683349.62     10515810.21
#Sta/Elev= 30
  3567.7  248.33  3843.7  214.57  4201.6  214.36  4284.6   214.6  4678.1  218.01
  4985.4   216.5  4991.5  216.76  4999.5  211.37  5048.6  218.43  5352.2  220.27
  5606.4   216.6  5694.5  216.08    6155  216.85  6369.2  216.54  6491.4   217.7
  6527.5  221.29  6557.6   216.9  6689.7  217.61  6716.5  218.02  6831.1  222.25
  7083.6  218.14  7161.8  223.75  7176.8  220.89  7473.8   221.1  7624.7  234.83
  7753.9  251.75  7919.3  262.63  7958.7  262.48  8135.7  270.81  8302.5  272.87
#Mann= 12 ,-1 , 0
  3567.7     .05       0  4201.6     .07       0  4284.6     .05       0
  4985.4     .07       0  5048.6     .05       0  5606.4     .07       0
  5694.5     .05       0    6155     .07       0  6369.2     .05       0
  6689.7      .1       0  6716.5     .05       0  7958.7     .16       0
Bank Sta=4991.5,5048.6
XS Rating Curve= 0 ,0
Exp/Cntr=0.3,0.1

Type RM Length L Ch R = 1 ,27884   ,2213,2213,2213
BEGIN DESCRIPTION:
ALLIGATOR BRANCH 10.0
END DESCRIPTION:
XS GIS Cut Line= 3
      3686999.58     10518860.16      3686599.61     10518460.19
      3683399.61     10515660.19
#Sta/Elev= 30
    4467   249.3  4668.4     252  4686.6  252.18  4763.9  250.24  4831.9  241.34
  4961.9  222.75  4976.1  211.01    4990  210.49  5060.6  215.71  5068.2  216.42
  5143.2  216.86    5399  215.92  5423.2  216.03  5939.5  219.28  6223.3  217.39
  6286.9  222.64  6329.6  223.31  6343.9  222.86  6350.5  219.77  6372.3  219.64
    6379   216.9  8211.7  217.48  8273.9  218.02    8401  221.84  8448.1  224.92
  8519.2  224.06  8703.4  232.96  8934.4  261.49  9107.7   269.9  9284.7  274.44
#Mann= 13 ,-1 , 0
    4467     .16       0  4668.4     .12       0  4686.6     .16       0
  4831.9     .12       0  4961.9     .07       0  5060.6     .12       0
  5143.2     .05       0    5399     .07       0  5423.2     .05       0
  8211.7     .07       0  8273.9     .12       0    8401     .05       0
  8934.4     .16       0
Bank Sta=4961.9,5068.2
XS Rating Curve= 0 ,0
Exp/Cntr=0.3,0.1

Type RM Length L Ch R = 1 ,25671   ,269,269,269
BEGIN DESCRIPTION:
ALLIGATOR BRANCH 9.0
END DESCRIPTION:
XS GIS Cut Line= 6
      3687317.88     10519913.71      3687817.01     10518806.95
      3687871.26     10516973.18      3687827.86     10516517.45
       3686938.1     10514716.24      3686547.48     10514076.05
#Sta/Elev= 30
  1896.8  247.16    2740  246.88  2858.9  241.66  2907.4   237.9  3096.4   243.6
    3108  239.98  3157.7  239.91  3252.5  230.37  3317.8  223.64  4330.9  216.48
  4418.2  216.77  4448.2  211.54  4588.3  211.56  4608.3  215.62  4723.1  213.09
  4821.1  214.85  4958.5  215.15  4968.6  210.14  4988.4  209.38  5038.9  215.07
  5048.9  214.44  5215.7  215.22    5498  216.53  5503.5  211.58  5520.4  216.81
  5542.9  217.18  7153.9   225.5  7238.3  225.83  7611.8  248.82  8162.2  263.24
#Mann= 11 ,-1 , 0
  1896.8     .05       0  2858.9     .08       0  3252.5     .05       0
  4330.9     .08       0  4723.1      .1       0  4821.1     .08       0
  4958.5     .07       0  5048.9     .08       0  5215.7     .05       0
  7153.9     .08       0  7238.3     .05       0
Bank Sta=4958.5,5038.9
XS Rating Curve= 0 ,0
Exp/Cntr=0.3,0.1

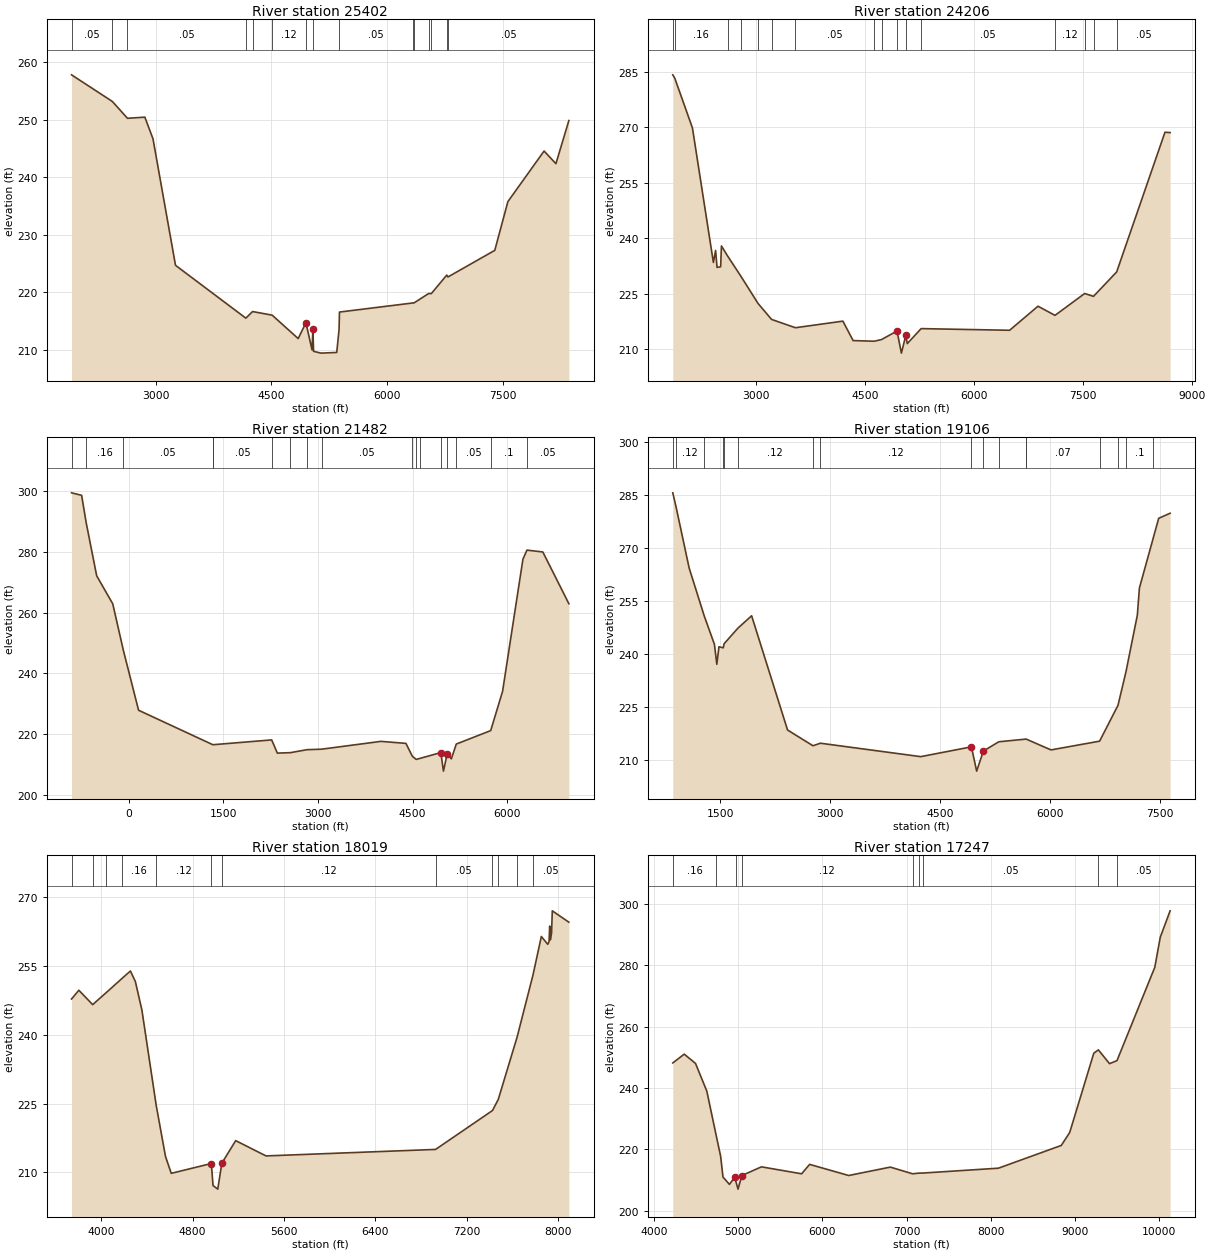
Type RM Length L Ch R = 1 ,25402   ,1196,1196,1196
BEGIN DESCRIPTION:
ALLIGATOR BRANCH 8.0
END DESCRIPTION:
XS GIS Cut Line= 6
      3687610.85     10519881.14      3688023.17     10518665.89
      3688088.27     10516474.05      3687491.49     10515323.88
      3687263.62     10514520.93      3687448.07     10513696.32
#Sta/Elev= 30
  1908.5  257.84  2438.1  253.21  2634.5  250.28  2859.9  250.48  2965.5  246.71
  3257.6  224.72    4170  215.53  4257.3  216.68  4511.6  216.05  4849.2  211.98
  4949.2  214.73  4949.6  214.71  5029.2     210  5039.2  213.57  5049.2  209.76
  5145.9  209.45  5349.2  209.57  5379.2  213.52  5384.8  216.59  6341.5  218.18
  6350.8  218.17  6541.3  219.81  6576.4   219.8  6776.6  223.02  6791.7  222.69
  7399.7  227.32  7569.5  235.79  8039.2  244.59  8192.9  242.39  8360.8  249.89
#Mann= 15 ,-1 , 0
  1908.5     .05       0  2438.1     .08       0  2634.5     .05       0
    4170     .08       0  4257.3     .05       0  4511.6     .12       0
  4949.2     .07       0  5039.2     .05       0  5379.2     .05       0
  6341.5     .08       0  6350.8     .05       0  6541.3     .08       0
  6576.4     .05       0  6776.6     .08       0  6791.7     .05       0
Bank Sta=4949.6,5039.2
XS Rating Curve= 0 ,0
Exp/Cntr=0.3,0.1

Type RM Length L Ch R = 1 ,24206   ,2724,2724,2724
BEGIN DESCRIPTION:
Mapping XS 475246da
END DESCRIPTION:
XS GIS Cut Line= 3
      3689248.87     10520575.22      3688686.37     10516179.35
      3688519.78      10513763.9
#Sta/Elev= 30
  1849.3  284.15  1877.9  283.19  2120.4   269.8  2408.9  233.49  2439.3  236.72
  2459.3  232.15  2508.9  232.33  2519.8  237.94  2604.5  235.24    2788  229.76
  3024.1  222.42  3210.7   218.1  3539.3  215.86  4193.3  217.64  4334.4  212.39
  4622.8  212.21  4725.3  212.66  4939.3  214.97  4999.6     209  5060.3   213.8
  5080.5  211.57  5271.4  215.62  6490.7  215.17  6881.6  221.67  7116.1   219.2
  7525.2   225.1  7646.6  224.33  7965.7  230.92  8631.4  268.65  8702.2  268.55
#Mann= 16 ,-1 , 0
  1849.3     .05       0  1877.9     .16       0  2604.5     .05       0
    2788     .16       0  3024.1     .05       0  3210.7     .12       0
  3539.3     .05       0  4622.8     .07       0  4725.3     .05       0
  4939.3     .05       0  5060.3     .12       0  5271.4     .05       0
  7116.1     .12       0  7525.2     .05       0  7646.6     .16       0
  7965.7     .05       0
Bank Sta=4939.3,5060.3
XS Rating Curve= 0 ,0
Exp/Cntr=0.3,0.1

Type RM Length L Ch R = 1 ,21482   ,2376,2376,2376
BEGIN DESCRIPTION:
ALLIGATOR BRANCH 7.0
END DESCRIPTION:
XS GIS Cut Line= 3
      3690040.52     10521554.39      3690978.03     10518158.51
      3689769.69     10513970.98
#Sta/Elev= 30
  -904.8  299.37  -744.8  298.55  -672.4  289.54  -506.2  272.11  -251.3  262.88
   -84.9  247.74   157.6  227.92  1334.4  216.59  1337.2  216.59  2266.9  218.17
    2357  213.83  2564.5  213.98  2826.9  214.96  3058.1  215.12  3998.3  217.69
  4394.4  217.03  4497.1  212.76  4557.3  211.76  4613.6  212.08  4947.8  214.01
  4989.1  207.91  5046.9   213.5  5114.2  211.95  5192.2   216.8  5737.9  221.23
  5926.1  234.14  6248.8  277.57    6312  280.54  6564.1  279.93  6976.5  262.93
#Mann= 17 ,-1 , 0
  -904.8     .05       0  -672.4     .16       0   -84.9     .05       0
  1334.4     .12       0  1337.2     .05       0  2266.9     .12       0
  2564.5     .05       0  2826.9     .12       0  3058.1     .05       0
  4497.1     .12       0  4557.3     .07       0  4613.6     .12       0
  4947.8     .07       0  5046.9     .12       0  5192.2     .05       0
  5737.9      .1       0    6312     .05       0
Bank Sta=4947.8,5046.9
XS Rating Curve= 0 ,0
Exp/Cntr=0.3,0.1

Type RM Length L Ch R = 1 ,19106   ,1087,1087,1087
BEGIN DESCRIPTION:
Mapping XS e3be1ebc
END DESCRIPTION:
XS GIS Cut Line= 3
      3693415.53     10519887.66       3692394.7     10516241.85
      3690104.31     10514305.43
#Sta/Elev= 30
   855.1  285.69   900.8  281.61  1078.4  264.36  1284.6  250.74  1423.6  242.69
  1455.9  237.04  1484.9  242.01  1544.1  241.72  1554.6  242.85  1741.2  247.24
  1930.7  250.81    2421   218.4  2767.7  213.93  2869.2  214.65  4238.3  210.84
  4929.8  213.62    5001  206.73    5093  212.43  5303.5  215.06  5675.1  215.82
  5676.3  215.82  6015.3  212.75  6678.6  215.23  6929.3   225.4  7038.2  234.92
  7193.2  250.99  7221.8   258.7  7413.6  273.12  7484.4  278.46  7640.4   279.9
#Mann= 17 ,-1 , 0
   855.1     .16       0   900.8     .12       0  1284.6     .16       0
  1544.1     .12       0  1554.6     .16       0  1741.2     .12       0
  2767.7     .16       0  2869.2     .12       0  4929.8     .07       0
    5093     .12       0  5303.5     .05       0  5675.1     .12       0
  5676.3     .07       0  6678.6     .05       0  6929.3     .07       0
  7038.2      .1       0  7413.6     .05       0
Bank Sta=4929.8,5093
XS Rating Curve= 0 ,0
Exp/Cntr=0.3,0.1

Type RM Length L Ch R = 1 ,18019   ,772,772,772
BEGIN DESCRIPTION:
ALLIGATOR BRANCH 6.0
END DESCRIPTION:
XS GIS Cut Line= 3
      3693811.36     10516179.34       3692269.7     10515054.35
      3690063.01     10513992.64
#Sta/Elev= 30
  3739.4  247.82  3803.5  249.73  3924.7  246.59  4043.7  249.22  4184.8  252.38
  4255.3  253.93  4298.6  251.64  4355.8  245.44  4481.7  224.54  4562.8  213.43
    4613  209.76  4964.4   211.9  4979.1  207.09  5020.6  206.31  5056.3  211.96
  5177.6   216.9  5443.3  213.56  6929.2  214.98  7427.5  223.47  7478.1  225.89
    7643  239.48  7782.9  253.11  7855.5  261.47  7911.8  259.76  7922.9  260.32
  7928.9  263.75  7934.5  260.72  7945.1  262.22  7951.5  267.07  8096.7  264.59
#Mann= 12 ,-1 , 0
  3739.4      .1       0  3924.7     .16       0  4043.7     .12       0
  4184.8     .16       0  4481.7     .12       0  4964.4     .07       0
  5056.3     .12       0  6929.2     .05       0  7427.5      .1       0
  7478.1     .05       0    7643      .1       0  7782.9     .05       0
Bank Sta=4964.4,5056.3
XS Rating Curve= 0 ,0
Exp/Cntr=0.3,0.1

Type RM Length L Ch R = 1 ,17247   ,701,701,701
BEGIN DESCRIPTION:
ALLIGATOR BRANCH 5.0
END DESCRIPTION:
XS GIS Cut Line= 3
      3693769.72     10515741.88       3692832.2     10513866.85
      3689728.02     10511658.51
#Sta/Elev= 30
  4223.5  248.19  4359.6  251.06  4493.7  248.03  4627.9     239  4742.6  224.12
    4792  217.78  4819.9  211.02  4896.2  208.64  4963.3  211.11  4970.9  209.79
  4998.6  207.09  5043.5  211.51  5276.3  214.35  5753.5  212.08  5848.5  215.15
  6312.5  211.53  6806.8  214.26  7072.2  212.08  7143.5   212.3  7195.7  212.33
  8090.2  213.91    8837  221.32    8937  225.53  9223.1  251.37  9277.2  252.45
  9410.1  247.96  9498.6  248.95  9947.4  279.34 10012.6  289.15 10129.4  297.74
#Mann= 9 ,-1 , 0
  4223.5     .16       0  4742.6     .12       0  4970.9     .07       0
  5043.5     .12       0  7072.2     .05       0  7143.5     .07       0
  7195.7     .05       0  9277.2     .16       0  9498.6     .05       0
Bank Sta=4963.3,5043.5
XS Rating Curve= 0 ,0
Exp/Cntr=0.3,0.1

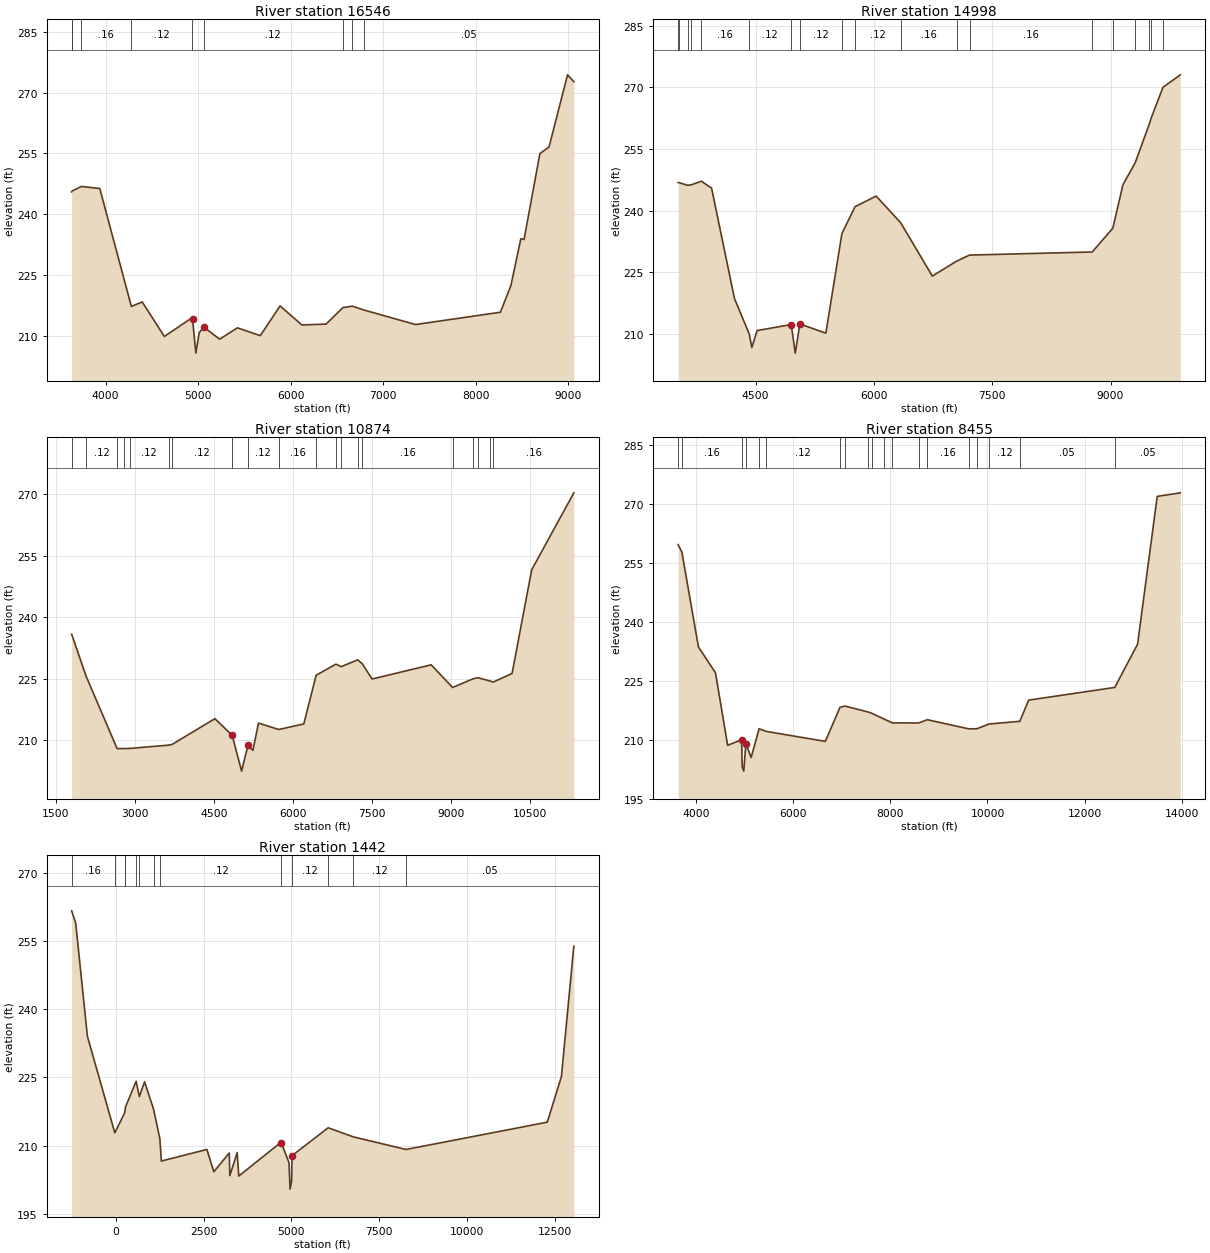
Type RM Length L Ch R = 1 ,16546   ,1548,1548,1548
BEGIN DESCRIPTION:
Mapping XS 804a69c2
END DESCRIPTION:
XS GIS Cut Line= 3
      3693915.53     10515866.83      3694061.37     10514741.85
      3691353.85     10511409.52
#Sta/Elev= 30
    3634  245.51  3640.6  245.75    3739  246.85  3938.1  246.33  4279.5  217.21
    4397  218.32    4636  209.79  4934.6  214.41  4941.1  214.03  4976.4  205.68
  5012.9  210.73  5062.5  212.12  5233.5  209.12  5425.2  211.92    5673     210
  5887.1  217.34    6122  212.64  6384.2  212.85  6566.2  216.93  6666.7  217.28
    6792  216.34    7351  212.74  8268.3  215.78  8381.8  222.35  8488.8  233.92
    8524  233.76    8695  254.95  8794.1  256.62  8993.8  274.42    9062  272.72
#Mann= 9 ,-1 , 0
    3634      .1       0  3640.6     .05       0    3739     .16       0
  4279.5     .12       0  4934.6     .07       0  5062.5     .12       0
  6566.2     .16       0  6666.7     .12       0    6792     .05       0
Bank Sta=4941.1,5062.5
XS Rating Curve= 0 ,0
Exp/Cntr=0.3,0.1

Type RM Length L Ch R = 1 ,14998   ,4124,4124,4124
BEGIN DESCRIPTION:
ALLIGATOR BRANCH 4.0
END DESCRIPTION:
XS GIS Cut Line= 4
      3693978.01     10516067.23      3694582.19     10515025.54
      3695353.03     10514483.87      3695019.69     10510275.49
#Sta/Elev= 30
  3517.2  246.86  3526.6  246.85  3637.5  246.19  3686.5  246.32  3812.1  247.18
  3941.5   245.5  4232.1  218.64  4419.9     210  4451.6  206.77  4519.5  210.88
  4946.3  212.32  4952.4  212.19  5002.7  205.39  5060.5  212.49  5390.5  210.24
  5594.5  234.47  5760.8  240.99  6028.4  243.57  6340.6  237.05  6740.6  224.12
  7050.2  227.76  7212.7  229.22  8768.3  229.98  9029.5  235.76  9158.1  246.34
  9314.1   251.7  9490.9  261.02  9518.9  262.68  9665.2     270  9885.1  273.04
#Mann= 19 ,-1 , 0
  3517.2     .16       0  3526.6     .05       0  3637.5     .16       0
  3686.5     .05       0  3812.1     .16       0  4419.9     .12       0
  4946.3     .07       0  5060.5     .12       0  5594.5     .16       0
  5760.8     .12       0  6340.6     .16       0  7050.2     .12       0
  7212.7     .16       0  8768.3     .05       0  9029.5     .16       0
  9314.1     .12       0  9490.9     .16       0  9518.9     .12       0
  9665.2     .16       0
Bank Sta=4952.4,5060.5
XS Rating Curve= 0 ,0
Exp/Cntr=0.3,0.1

Type RM Length L Ch R = 1 ,10874   ,2419,2419,2419
BEGIN DESCRIPTION:
ALLIGATOR BRANCH 3.0
END DESCRIPTION:
XS GIS Cut Line= 4
      3694194.07     10519522.69      3696353.03     10516671.37
      3696665.53     10515650.54      3696103.03     10510796.38
#Sta/Elev= 30
  1797.9  235.84  2073.4  225.57    2661  207.94  2792.6  207.97  2900.1  207.99
  3637.7   208.8  3706.1  208.98  4516.1  215.25  4844.8  211.19  5023.5  202.46
  5144.4  208.77  5237.9  207.53  5344.2  214.17    5727  212.61  6203.4  213.96
  6438.5  225.84  6812.4  228.54  6915.8  227.94  7225.9  229.59  7312.7  228.65
  7499.3  224.92  8621.8  228.38  9027.8  222.85    9413  224.95  9505.6  225.23
  9731.8  224.45  9801.9  224.19   10157  226.28 10528.7  251.54 11328.6  270.31
#Mann= 20 ,-1 , 0
  1797.9     .16       0  2073.4     .12       0    2661     .07       0
  2792.6     .12       0  2900.1     .12       0  3637.7     .16       0
  3706.1     .12       0  4844.8     .07       0  5144.4     .12       0
    5727     .16       0  6438.5     .05       0  6812.4     .16       0
  6915.8     .05       0  7225.9     .15       0  7312.7     .16       0
  9027.8     .16       0    9413     .12       0  9505.6     .16       0
  9731.8     .12       0  9801.9     .16       0
Bank Sta=4844.8,5144.4
XS Rating Curve= 0 ,0
Exp/Cntr=0.3,0.1

Type RM Length L Ch R = 1 ,8455    ,7013,7013,7013
BEGIN DESCRIPTION:
ALLIGATOR BRANCH 2.0
END DESCRIPTION:
XS GIS Cut Line= 4
       3696607.3     10519496.59      3697764.49     10517453.65
      3698623.87     10514458.86      3698181.16     10509615.12
#Sta/Elev= 30
  3638.5  259.72    3716  257.81  4056.5  233.64  4407.1  227.05  4657.2  208.57
  4944.5     210  4956.8  203.06  4988.4  201.99  5031.9  208.96  5140.1  205.46
  5304.4  212.79  5451.7  212.11  6666.2  209.57  6967.7  218.24  7068.6  218.58
  7552.2  217.03  7619.5  216.74  7876.2  215.25  8041.9  214.29  8582.9  214.26
    8766  215.09    9612  212.77    9780  212.78 10033.4     214 10665.7  214.68
 10847.4  220.08 12618.2  223.32 13087.3  234.33 13491.3     272   13966  272.91
#Mann= 19 ,-1 , 0
  3638.5     .12       0    3716     .16       0  4944.5     .07       0
  5031.9     .12       0  5304.4     .16       0  5451.7     .12       0
  6967.7     .16       0  7068.6     .12       0  7552.2     .16       0
  7619.5     .12       0  7876.2     .16       0  8041.9     .16       0
  8582.9     .16       0    8766     .16       0    9612     .12       0
    9780     .16       0 10033.4     .12       0 10665.7     .05       0
 12618.2     .05       0
Bank Sta=4944.5,5031.9
XS Rating Curve= 0 ,0
Exp/Cntr=0.3,0.1

Type RM Length L Ch R = 1 ,1442    ,0,0,0
BEGIN DESCRIPTION:
ALLIGATOR BRANCH 1.0
END DESCRIPTION:
XS GIS Cut Line= 3
      3698449.62     10523310.14      3700249.61     10517310.19
      3699449.61     10509310.22
#Sta/Elev= 30
 -1256.9  261.63 -1142.1  258.98    -808  234.04   -27.4  212.82     254  217.22
   276.3  218.48   580.1  224.16   670.5   220.8   820.7  224.04  1077.3  217.99
  1255.6  211.54  1298.3  206.61  2595.5  209.16    2793  204.25  3232.4  208.38
  3248.9  203.41  3457.7  208.48  3503.8  203.32  4704.5  210.73  4715.8  210.62
  4934.2  206.25  4965.2  200.44  5009.7  202.31  5017.3  207.78  6050.4  213.93
  6761.3  211.94  8267.9  209.16 12290.9  215.16 12692.9  225.18 13047.1  253.87
#Mann= 13 ,-1 , 0
 -1256.9     .16       0   -27.4     .12       0     254     .16       0
   276.3     .12       0   580.1     .16       0   670.5     .12       0
  1077.3     .16       0  1255.6     .12       0  4704.5     .07       0
  5017.3     .12       0  6050.4     .16       0  6761.3     .12       0
  8267.9     .05       0
Bank Sta=4715.8,5017.3
XS Rating Curve= 0 ,0
Exp/Cntr=0.3,0.1

Chan Stop Cuts=-1
Use User Specified Reach Order=0
Composite Channel Slope=5