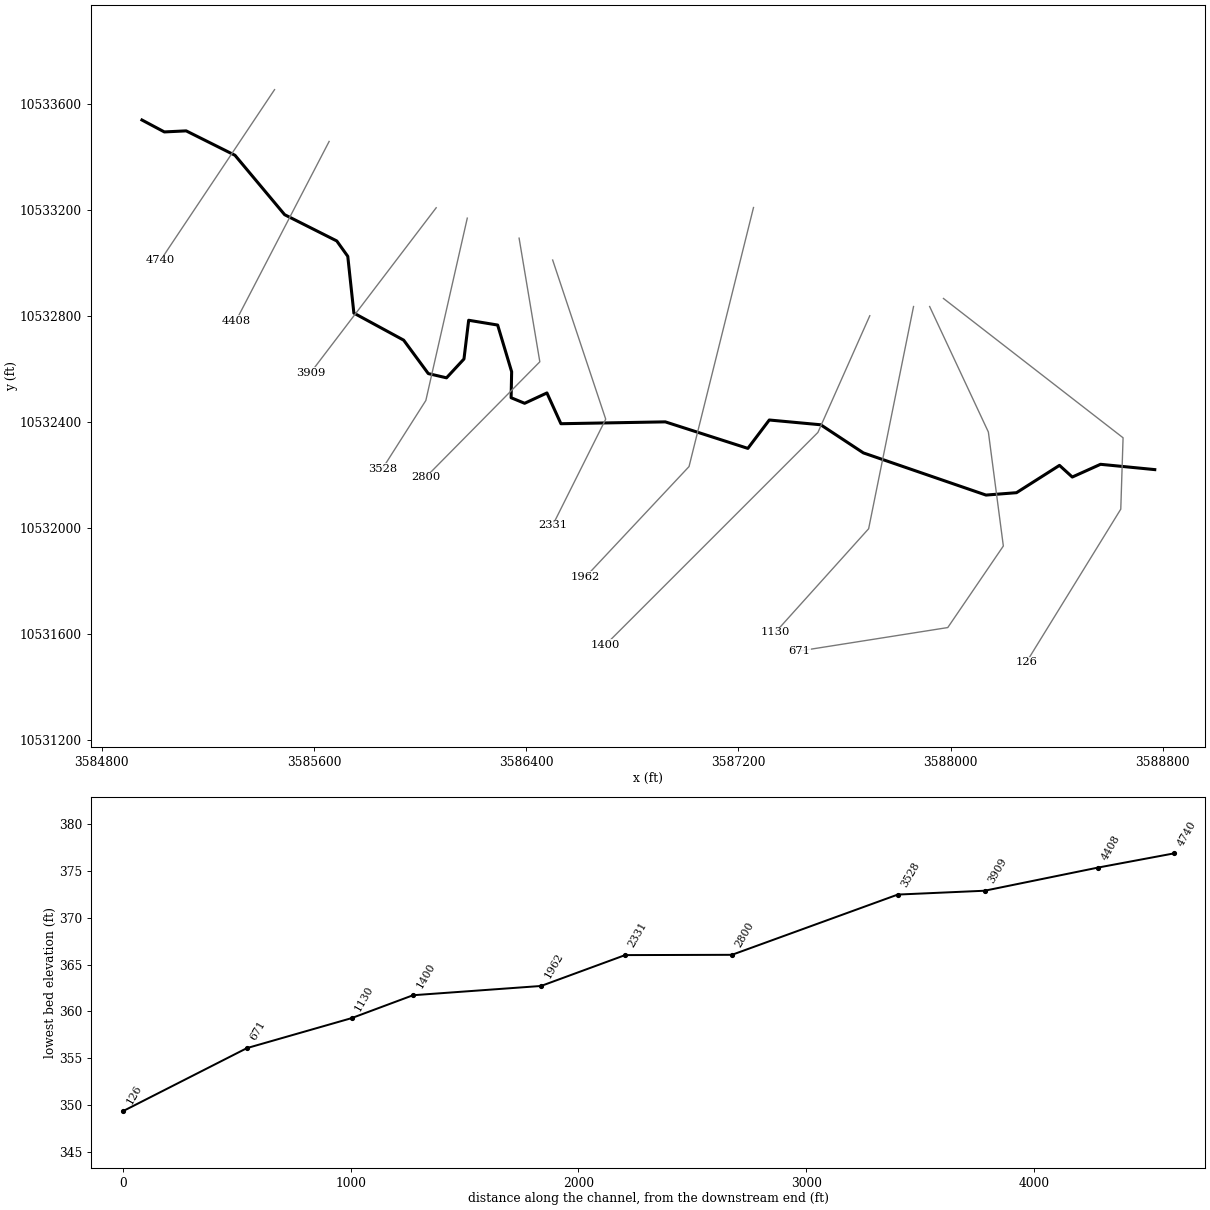
--- BELL BRANCH.prj (project) ---

Proj Title=BELL BRANCH Base Level Engineering
Current Plan=p01
Default Exp/Contr=0.3,0.1
English Units
Geom File=g01
Flow File=f01
Plan File=p01
BEGIN DESCRIPTION:
BELL BRANCH
END DESCRIPTION:

--- BELL BRANCH.p01 (plan) ---

Plan Title=Multiple Run
Short Identifier=Multiple
Geom File=g01
Flow File=f01
Subcritical Flow
K Sum by GR= 0
Std Step Tol= 0.01
Critical Tol= 0.01
Num of Std Step Trials= 20
Max Error Tol= 0.3
Flow Tol Ratio= 0.001
Split Flow NTrial= 30
Split Flow Tol= 0.02
Split Flow Ratio= 0.02
Log Output Level= 0
Friction Slope Method= 1
Unsteady Friction Slope Method= 2
Unsteady Bridges Friction Slope Method= 1
Parabolic Critical Depth
Global Vel Dist=  1 , 1 , 1
Global Log Level= 0
CheckData=True
Encroach Param= -1, 0, 0, 0
BEGIN DESCRIPTION:
Multiple Run
END DESCRIPTION:

--- BELL BRANCH.f01 (steady flow) ---

Flow Title=Multiple
Number of Profiles=7
Profile Names=10-year,25-year,50-year,1pct_min,100-year,1pct_plu,500-year
River Rch & RM= BELL BRANCH,Reach-1,4740
    1155    1605    1980    1783    2412    3262    3566
Boundary for River Rch & Prof#=BELL BRANCH,Reach-1,1
Up Type=0
Dn Type=3
Dn Slope=0.005
Boundary for River Rch & Prof#=BELL BRANCH,Reach-1,2
Up Type=0
Dn Type=3
Dn Slope=0.005
Boundary for River Rch & Prof#=BELL BRANCH,Reach-1,3
Up Type=0
Dn Type=3
Dn Slope=0.005
Boundary for River Rch & Prof#=BELL BRANCH,Reach-1,4
Up Type=0
Dn Type=3
Dn Slope=0.005
Boundary for River Rch & Prof#=BELL BRANCH,Reach-1,5
Up Type=0
Dn Type=3
Dn Slope=0.005
Boundary for River Rch & Prof#=BELL BRANCH,Reach-1,6
Up Type=0
Dn Type=3
Dn Slope=0.005
Boundary for River Rch & Prof#=BELL BRANCH,Reach-1,7
Up Type=0
Dn Type=3
Dn Slope=0.005

--- BELL BRANCH.g01 (geometry) ---

Geom Title=Existing Conditions

River Reach=BELL BRANCH,Reach-1
Reach XY= 30
      3584951.25     10533538.00      3585035.75     10533493.00
      3585118.00     10533497.00      3585302.00     10533405.00
      3585489.25     10533181.00      3585685.75     10533082.00
      3585727.25     10533024.00      3585750.25     10532810.00
      3585938.00     10532708.00      3586030.75     10532582.00
      3586099.50     10532566.00      3586165.25     10532637.00
      3586183.00     10532783.00      3586292.25     10532765.00
      3586345.00     10532589.00      3586343.00     10532491.00
      3586394.00     10532470.00      3586478.00     10532509.00
      3586530.75     10532393.00      3586924.25     10532400.00
      3587235.50     10532300.00      3587316.25     10532407.00
      3587510.25     10532389.00      3587671.00     10532283.00
      3588133.25     10532124.00      3588248.25     10532133.00
      3588410.25     10532236.00      3588458.50     10532192.00
      3588565.00     10532240.00      3588769.50     10532220.00

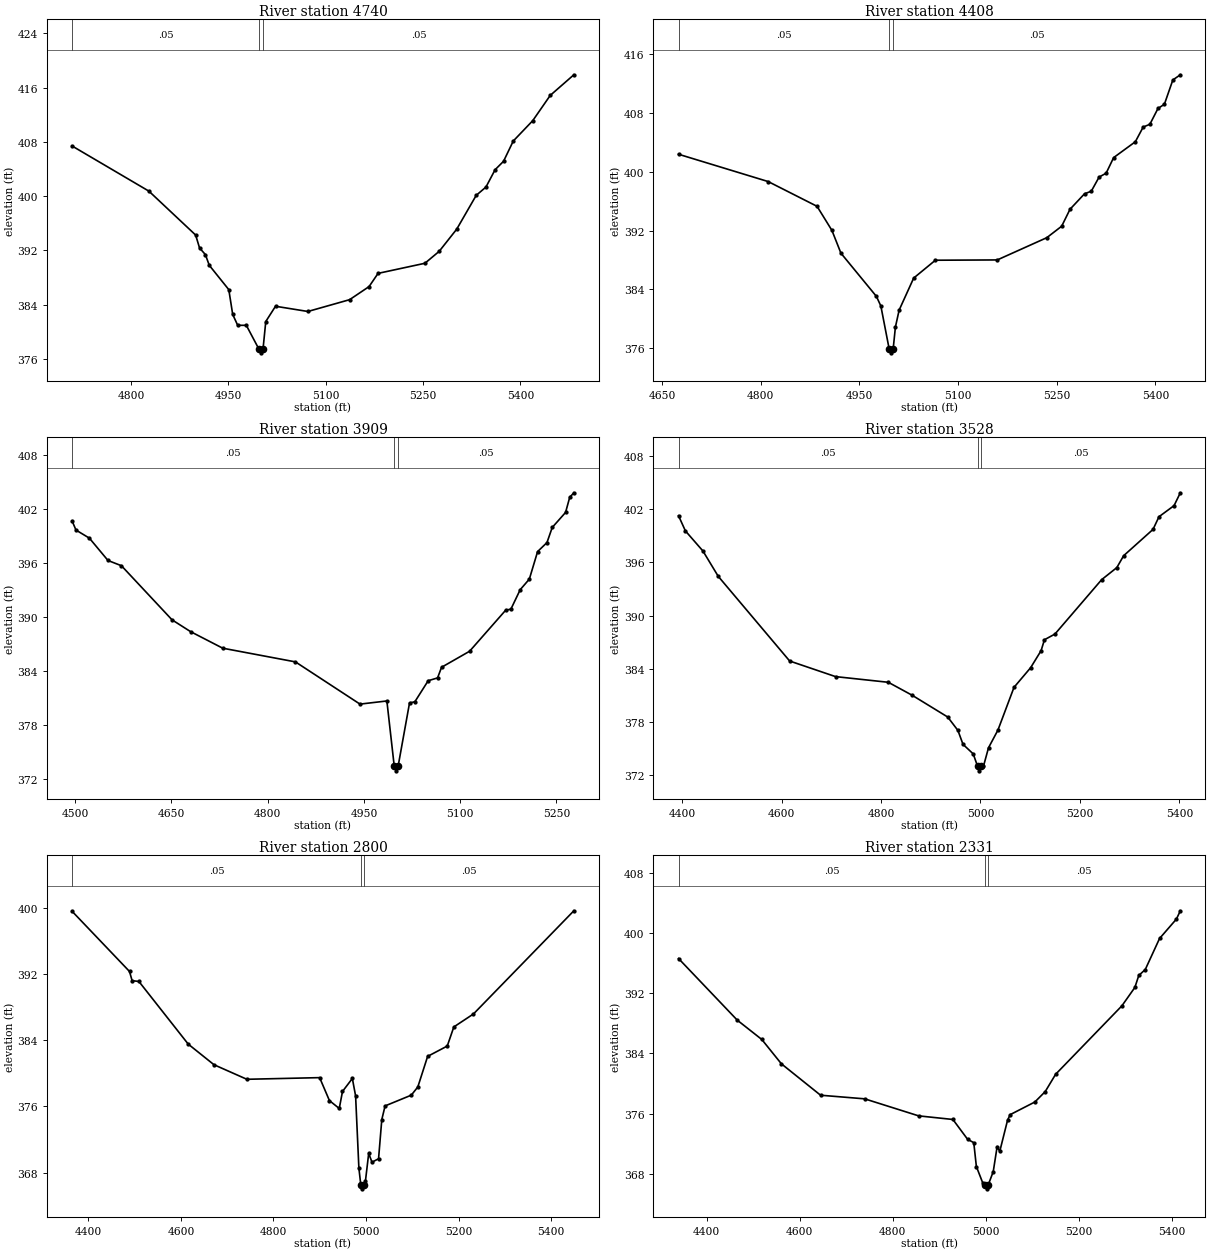
Type RM Length L Ch R = 1,4740,332,332,332
BEGIN DESCRIPTION:
BELL BRANCH 9.0
END DESCRIPTION:
XS GIS Cut Line= 2
      3585451.20     10533652.44      3585021.54     10533009.25
#Sta/Elev= 30
  4708.9  407.39  4827.3  400.73  4899.4  394.25  4905.4  392.35  4914.4  391.37
  4920.4  389.79  4950.5  386.20  4956.5  382.55  4964.2  380.94  4977.5  380.94
  4997.2  377.38  5000.0  376.88  5003.2  377.38  5007.5  381.50  5022.5  383.75
  5072.4  382.98  5136.7  384.72  5166.7  386.65  5180.6  388.60  5252.8  390.09
  5274.8  391.85  5301.9  395.13  5331.9  400.11  5346.9  401.33  5361.0  403.89
  5374.0  405.13  5389.0  408.12  5419.0  411.12  5446.0  414.85  5482.4  417.89
#Mann=3,-1,0
  4708.9    0.05       0  4997.2    0.03       0  5003.2    0.05       0
Bank Sta=4997.2,5003.2
Exp/Cntr=0.3,0.1

Type RM Length L Ch R = 1,4408,499,499,499
BEGIN DESCRIPTION:
BELL BRANCH 8.0
END DESCRIPTION:
XS GIS Cut Line= 2
      3585656.93     10533457.12      3585305.37     10532780.05
#Sta/Elev= 30
  4675.1  402.41  4811.4  398.69  4885.7  395.32  4908.3  392.04  4922.0  388.94
  4975.9  383.06  4982.7  381.75  4995.4  375.87  4998.2  375.37  5001.4  375.87
  5004.8  378.87  5010.5  381.19  5032.6  385.55  5065.6  387.98  5159.7  388.02
  5235.0  391.05  5257.6  392.61  5270.3  394.92  5292.4  397.03  5302.6  397.37
  5314.5  399.30  5325.2  399.83  5336.6  401.95  5369.6  404.11  5381.5  406.11
  5391.7  406.49  5404.0  408.64  5413.8  409.22  5426.6  412.52  5438.0  413.23
#Mann=3,-1,0
  4675.1    0.05       0  4995.4    0.03       0  5001.4    0.05       0
Bank Sta=4995.4,5001.4
Exp/Cntr=0.3,0.1

Type RM Length L Ch R = 1,3909,381,381,381
BEGIN DESCRIPTION:
BELL BRANCH 7.0
END DESCRIPTION:
XS GIS Cut Line= 2
      3586060.58     10533207.13      3585586.81     10532584.99
#Sta/Elev= 30
  4495.1  400.65  4501.2  399.63  4522.1  398.73  4551.1  396.25  4572.0  395.67
  4650.9  389.66  4679.8  388.35  4729.9  386.51  4843.2  384.99  4943.8  380.30
  4985.7  380.65  4997.2  373.39  5000.0  372.89  5003.2  373.39  5021.0  380.43
  5029.3  380.56  5050.1  382.90  5064.7  383.21  5070.9  384.39  5114.6  386.17
  5170.7  390.72  5179.0  390.85  5193.5  393.01  5207.7  394.18  5220.6  397.24
  5235.2  398.24  5243.4  399.92  5264.2  401.59  5270.6  403.26  5277.1  403.77
#Mann=3,-1,0
  4495.1    0.05       0  4997.2    0.03       0  5003.2    0.05       0
Bank Sta=4997.2,5003.2
Exp/Cntr=0.3,0.1

Type RM Length L Ch R = 1,3528,728,728,728
BEGIN DESCRIPTION:
BELL BRANCH 6.0
END DESCRIPTION:
XS GIS Cut Line= 3
      3586177.78     10533168.10      3586021.53     10532480.60
      3585858.23     10532223.99
#Sta/Elev= 30
  4392.7  401.26  4406.5  399.55  4441.8  397.28  4472.6  394.42  4616.2  384.87
  4708.5  383.11  4814.6  382.47  4862.8  381.00  4934.1  378.55  4954.6  377.04
  4964.8  375.47  4985.4  374.39  4994.2  372.98  4996.9  372.48  5000.2  372.98
  5005.9  372.98  5016.1  375.08  5035.1  377.08  5067.4  381.90  5100.9  384.12
  5121.9  386.04  5128.6  387.27  5149.7  387.91  5243.7  394.05  5274.2  395.41
  5287.9  396.75  5347.0  399.72  5359.0  401.15  5389.3  402.40  5401.9  403.85
#Mann=3,-1,0
  4392.7    0.05       0  4994.2    0.03       0  5000.2    0.05       0
Bank Sta=4994.2,5000.2
Exp/Cntr=0.3,0.1

Type RM Length L Ch R = 1,2800,469,469,469
BEGIN DESCRIPTION:
BELL BRANCH 5.0
END DESCRIPTION:
XS GIS Cut Line= 3
      3586373.10     10533092.57      3586451.22     10532626.43
      3586021.53     10532191.54
#Sta/Elev= 30
  4364.9  399.61  4489.0  392.33  4494.6  391.22  4509.3  391.12  4615.9  383.54
  4671.5  381.05  4742.5  379.29  4899.7  379.49  4920.9  376.71  4942.1  375.76
  4949.1  377.82  4970.4  379.39  4977.4  377.28  4984.5  368.55  4988.6  366.54
  4991.3  366.04  4994.6  366.54  4998.7  367.00  5005.7  370.33  5012.8  369.26
  5027.0  369.68  5034.0  374.42  5041.1  376.07  5097.7  377.37  5111.8  378.36
  5133.0  382.06  5175.4  383.31  5189.6  385.62  5232.0  387.19  5448.9  399.67
#Mann=3,-1,0
  4364.9    0.05       0  4988.6    0.03       0  4994.6    0.05       0
Bank Sta=4988.6,4994.6
Exp/Cntr=0.3,0.1

Type RM Length L Ch R = 1,2331,369,369,369
BEGIN DESCRIPTION:
BELL BRANCH 4.0
END DESCRIPTION:
XS GIS Cut Line= 3
      3586499.62     10533010.15      3586699.61     10532410.19
      3586499.62     10532010.22
#Sta/Elev= 30
  4339.3  396.59  4465.8  388.40  4518.5  385.84  4560.6  382.61  4644.9  378.44
  4739.8  377.96  4855.8  375.70  4929.6  375.22  4961.2  372.59  4974.5  372.14
  4980.1  368.97  4994.1  366.75  4999.5  366.51  5002.2  366.01  5005.5  366.51
  5016.4  368.30  5024.8  371.63  5030.4  370.98  5047.2  375.13  5052.8  375.86
  5105.9  377.54  5128.2  378.92  5150.6  381.22  5293.2  390.31  5321.1  392.75
  5329.5  394.34  5343.5  395.13  5374.2  399.25  5410.5  401.83  5418.9  402.93
#Mann=3,-1,0
  4339.3    0.05       0  4999.5    0.03       0  5005.5    0.05       0
Bank Sta=4999.5,5005.5
Exp/Cntr=0.3,0.1

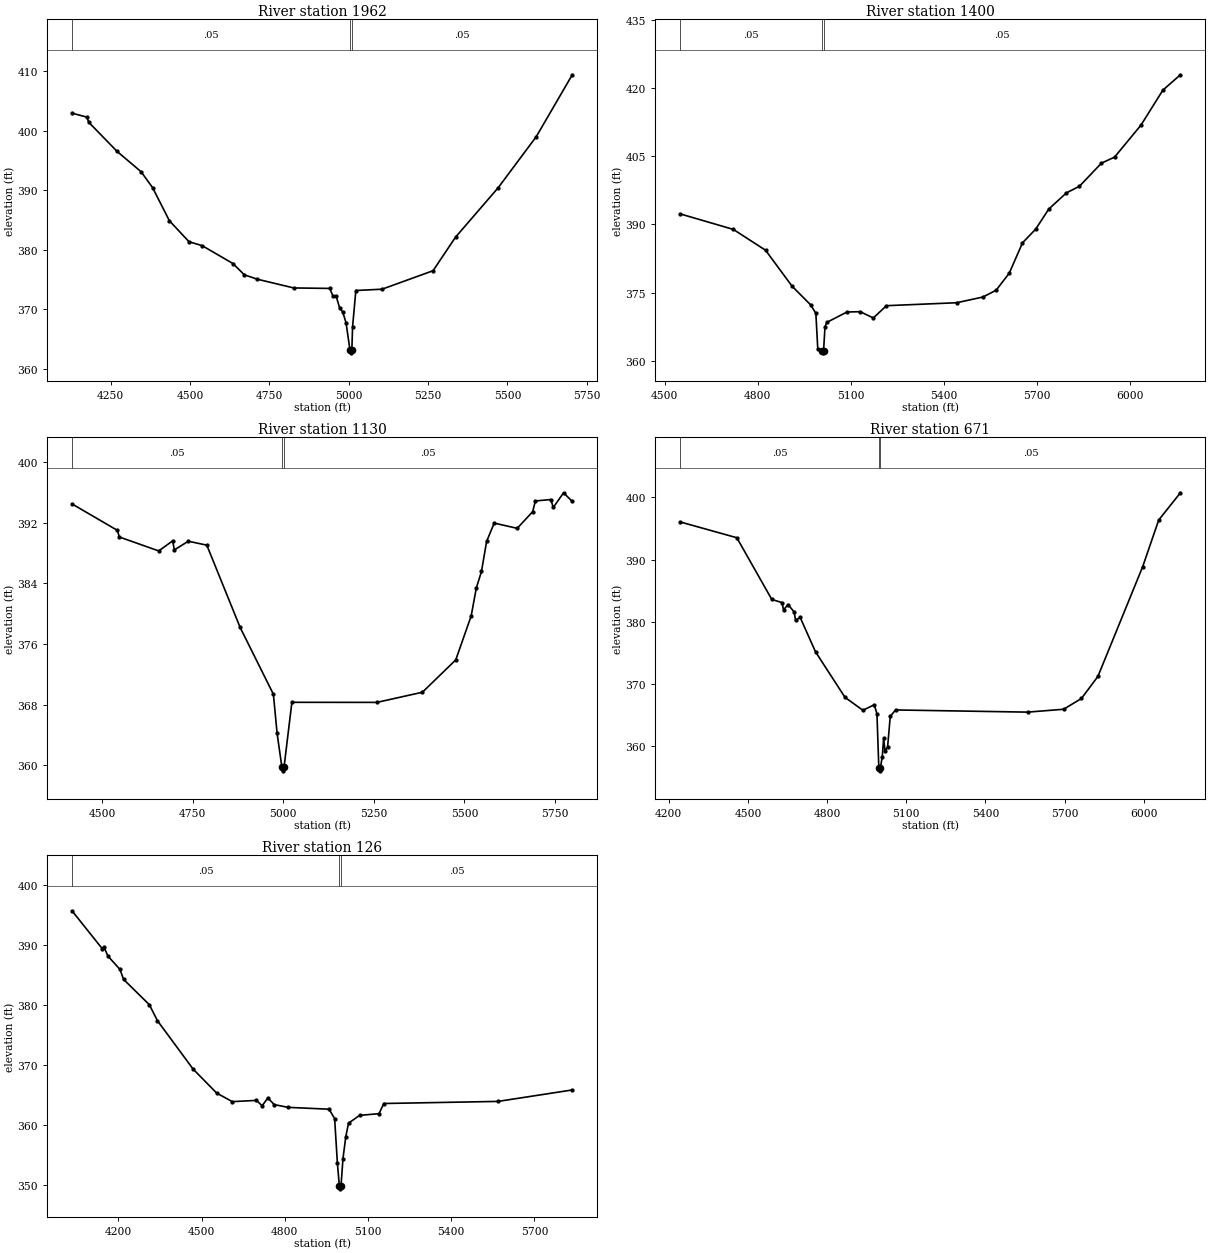
Type RM Length L Ch R = 1,1962,562,562,562
BEGIN DESCRIPTION:
BELL BRANCH 3.0
END DESCRIPTION:
XS GIS Cut Line= 3
      3587256.78     10533208.04      3587013.72     10532231.47
      3586624.05     10531815.82
#Sta/Elev= 30
  4128.0  402.93  4175.3  402.26  4180.4  401.42  4270.1  396.51  4345.7  393.10
  4381.8  390.44  4434.9  384.87  4496.8  381.35  4538.0  380.70  4634.9  377.70
  4671.0  375.80  4712.3  375.06  4826.5  373.60  4939.9  373.52  4950.2  372.25
  4960.2  372.22  4970.8  370.31  4981.1  369.53  4991.4  367.75  5003.7  363.21
  5006.4  362.71  5009.7  363.21  5012.0  367.12  5022.3  373.17  5104.8  373.39
  5265.5  376.49  5336.3  382.12  5470.6  390.41  5590.8  399.00  5704.1  409.37
#Mann=3,-1,0
  4128.0    0.05       0  5003.7    0.03       0  5009.7    0.05       0
Bank Sta=5003.7,5009.7
Exp/Cntr=0.3,0.1

Type RM Length L Ch R = 1,1400,270,270,270
BEGIN DESCRIPTION:
BELL BRANCH 2.0
END DESCRIPTION:
XS GIS Cut Line= 3
      3587695.16     10532800.08      3587499.61     10532360.19
      3586699.59     10531560.17
#Sta/Elev= 30
  4549.6  392.31  4721.2  388.89  4825.1  384.30  4910.6  376.38  4970.1  372.30
  4987.2  370.42  4993.4  362.54  5006.1  362.22  5008.9  361.72  5012.1  362.22
  5016.6  367.42  5022.1  368.41  5087.6  370.71  5130.0  370.78  5172.4  369.40
  5214.8  372.10  5441.1  372.75  5526.0  374.01  5568.4  375.51  5610.8  379.27
  5653.3  385.93  5695.7  388.94  5738.1  393.37  5794.7  396.92  5837.1  398.40
  5907.8  403.47  5950.2  404.81  6035.1  411.83  6105.8  419.54  6162.4  422.93
#Mann=3,-1,0
  4549.6    0.05       0  5006.1    0.03       0  5012.1    0.05       0
Bank Sta=5006.1,5012.1
Exp/Cntr=0.3,0.1

Type RM Length L Ch R = 1,1130,459,459,459
BEGIN DESCRIPTION:
Mapping XS 605eb976
END DESCRIPTION:
XS GIS Cut Line= 3
      3587860.07     10532834.77      3587690.80     10531997.09
      3587339.27     10531606.50
#Sta/Elev= 30
  4417.4  394.48  4542.7  390.99  4547.8  390.12  4656.7  388.28  4694.9  389.60
  4700.0  388.42  4738.3  389.56  4789.3  389.04  4881.2  378.19  4973.0  369.37
  4983.2  364.22  4996.4  359.77  4999.2  359.27  5002.4  359.77  5024.0  368.31
  5258.6  368.30  5384.1  369.64  5476.0  373.90  5518.6  379.70  5532.8  383.39
  5547.0  385.57  5561.2  389.53  5582.1  391.95  5645.6  391.26  5688.3  393.46
  5695.7  394.87  5738.3  395.06  5745.1  394.01  5773.5  395.95  5797.5  394.80
#Mann=3,-1,0
  4417.4    0.05       0  4996.4    0.03       0  5002.4    0.05       0
Bank Sta=4996.4,5002.4
Exp/Cntr=0.3,0.1

Type RM Length L Ch R = 1,671,545,545,545
BEGIN DESCRIPTION:
Mapping XS f26b16f2
END DESCRIPTION:
XS GIS Cut Line= 5
      3587920.83     10532834.78      3588142.19     10532361.67
      3588198.62     10531931.99      3587989.13     10531624.58
      3587428.38     10531536.04
#Sta/Elev= 30
  4243.3  396.05  4458.1  393.51  4590.6  383.60  4629.5  383.09  4635.0  381.93
  4652.3  382.78  4675.2  381.59  4680.7  380.26  4698.0  380.72  4756.2  375.19
  4868.0  367.87  4935.7  365.80  4978.9  366.68  4989.0  365.24  4996.1  356.57
  4998.8  356.07  5002.1  356.57  5009.2  358.35  5014.4  361.33  5019.5  359.23
  5029.4  359.89  5039.4  364.82  5059.6  365.85  5559.7  365.50  5696.2  365.96
  5763.7  367.69  5826.1  371.23  5995.7  388.85  6056.5  396.35  6138.7  400.73
#Mann=3,-1,0
  4243.3    0.05       0  4996.1    0.03       0  5002.1    0.05       0
Bank Sta=4996.1,5002.1
Exp/Cntr=0.3,0.1

Type RM Length L Ch R = 1,126,0,0,0
BEGIN DESCRIPTION:
BELL BRANCH 1.0
END DESCRIPTION:
XS GIS Cut Line= 4
      3587972.93     10532865.14      3588650.00     10532339.97
      3588641.32     10532070.88      3588285.92     10531494.44
#Sta/Elev= 30
  4033.0  395.69  4141.7  389.39  4148.1  389.66  4162.6  388.13  4206.0  385.91
  4218.7  384.26  4311.9  380.02  4340.9  377.37  4469.4  369.30  4554.5  365.29
  4610.9  363.86  4697.5  364.07  4718.4  363.18  4739.2  364.48  4761.8  363.37
  4811.6  362.91  4959.7  362.60  4979.7  361.04  4989.7  353.57  4996.7  349.82
  4999.5  349.32  5002.7  349.82  5009.7  354.31  5019.7  357.95  5029.7  360.27
  5069.7  361.57  5139.8  361.86  5156.9  363.55  5568.6  363.90  5836.3  365.81
#Mann=3,-1,0
  4033.0    0.05       0  4996.7    0.03       0  5002.7    0.05       0
Bank Sta=4996.7,5002.7
Exp/Cntr=0.3,0.1

Chan Stop Cuts=-1