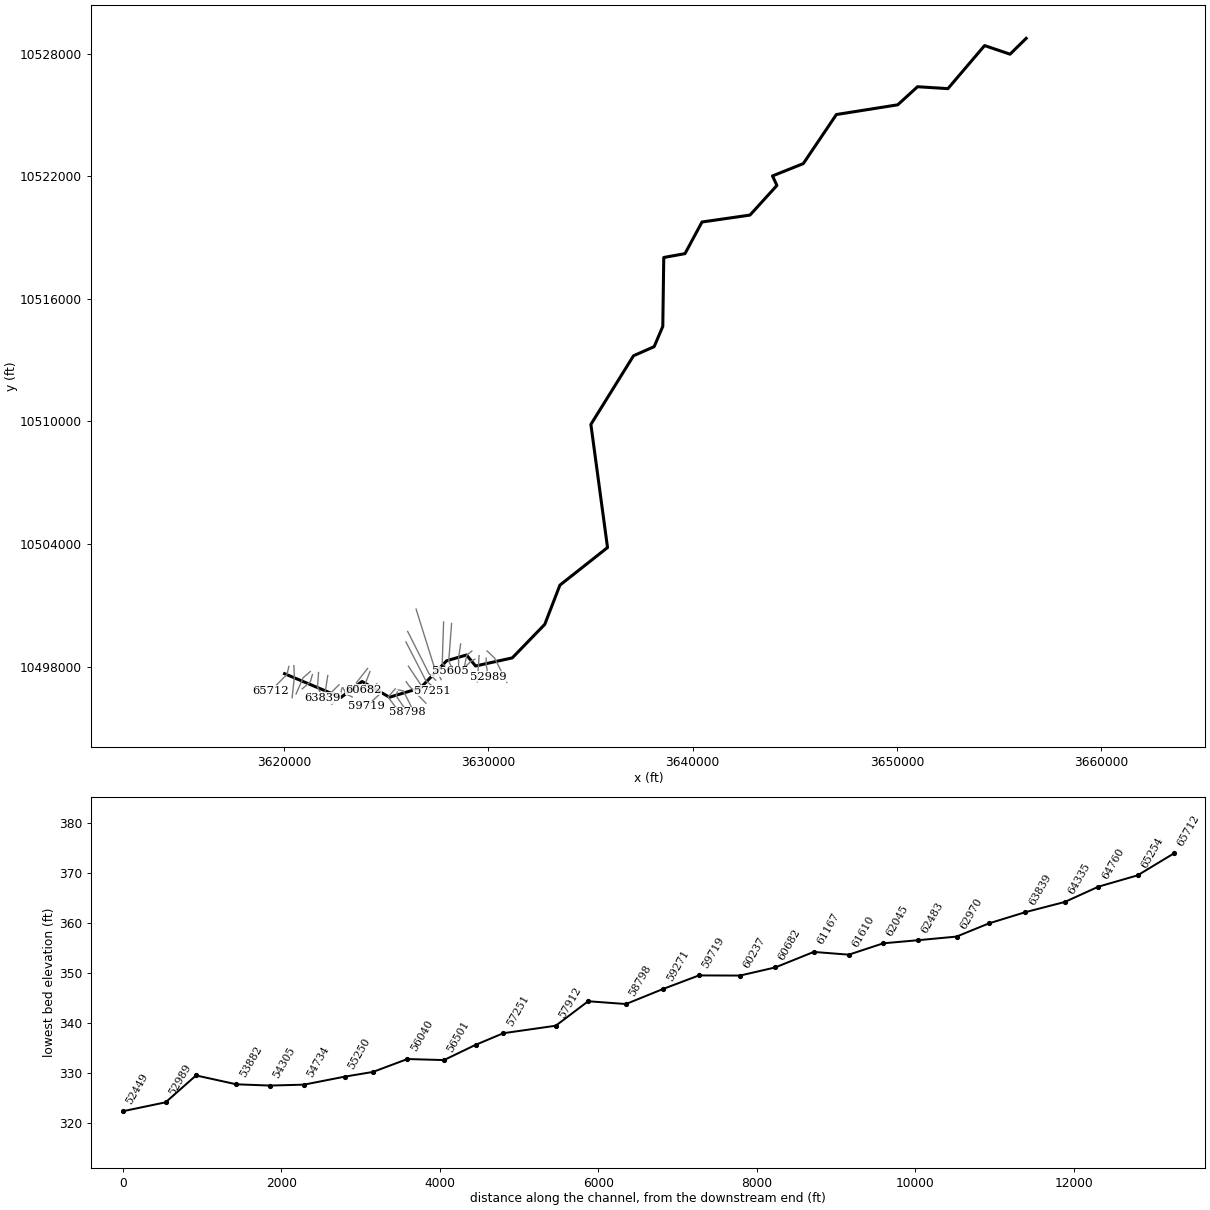
--- BLISS CREEK.prj (project) ---

Proj Title=BLISS CREEK Base Level Engineering
Current Plan=p01
Default Exp/Contr=0.3,0.1
English Units
Geom File=g01
Flow File=f01
Plan File=p01
Y Axis Title=Elevation
X Axis Title(PF)=Main Channel Distance
X Axis Title(XS)=Station
BEGIN DESCRIPTION:
BLISS CREEK
END DESCRIPTION:
DSS Export Rating Curves= 0
DSS Export Rating Curve Sorted= 0
DSS Export Volume Flow Curves= 0
DXF OffsetX= 0
DXF OffsetY= 0
DXF ScaleX= 1
DXF ScaleY= 10

--- BLISS CREEK.p01 (plan) ---

Plan Title=Multiple Run
Short Identifier=Multiple
Geom File=g01
Flow File=f01
Subcritical Flow
K Sum by GR= 0
Std Step Tol= 0.01
Critical Tol= 0.01
Num of Std Step Trials= 20
Max Error Tol= 0.3
Flow Tol Ratio= 0.001
Split Flow NTrial= 30
Split Flow Tol= 0.02
Split Flow Ratio= 0.02
Log Output Level= 0
Friction Slope Method= 1
Unsteady Friction Slope Method= 2
Unsteady Bridges Friction Slope Method= 1
Parabolic Critical Depth
Global Vel Dist=  1 , 1 , 1
Global Log Level= 0
CheckData=True
Encroach Param= -1, 0, 0, 0
BEGIN DESCRIPTION:
Multiple Run
END DESCRIPTION:

--- BLISS CREEK.f01 (steady flow) ---

Flow Title=Multiple
Program Version=4.10
Number of Profiles= 7
Profile Names=10-year,25-year,50-year,1pct_min,100-year,1pct_plu,500-year
River Rch & RM=BLISS CREEK,Reach-1         ,65712
    1123    1552    1907    1710    2313    3128    3390
River Rch & RM=BLISS CREEK,Reach-1         ,65254
    1700    2395    2982    2704    3657    4946    5487
River Rch & RM=BLISS CREEK,Reach-1         ,60237
    2268    3241    4072    3724    5036    6811    7686
River Rch & RM=BLISS CREEK,Reach-1         ,58321
    2770    3995    5054    4649    6287    8502    9709
River Rch & RM=BLISS CREEK,Reach-1         ,56040
    3058    4416    5589    5141    6953    9403   10739
River Rch & RM=BLISS CREEK,Reach-1         ,53373
    3210    4645    5887    5422    7333    9917   11355
River Rch & RM=BLISS CREEK,Reach-1         ,51132
    3462    5011    6351    5847    7908   10695   12237
River Rch & RM=BLISS CREEK,Reach-1         ,45829
    3922    5704    7253    6697    9057   12249   14095
River Rch & RM=BLISS CREEK,Reach-1         ,44561
    3972    5770    7333    6765    9149   12373   14215
River Rch & RM=BLISS CREEK,Reach-1         ,43025
    5889    8670   11118   10341   13985   18913   22080
River Rch & RM=BLISS CREEK,Reach-1         ,41377
    5889    8670   11118   10341   13985   18913   22080
River Rch & RM=BLISS CREEK,Reach-1         ,36046
    7331   10859   13982   13052   17651   23871   28063
River Rch & RM=BLISS CREEK,Reach-1         ,35510
    7331   10859   13982   13052   17651   23871   28063
River Rch & RM=BLISS CREEK,Reach-1         ,31263
    7304   10795   13879   12934   17492   23656   27718
River Rch & RM=BLISS CREEK,Reach-1         ,27360
    7825   11577   14895   13889   18783   25402   29794
River Rch & RM=BLISS CREEK,Reach-1         ,26883
    7825   11577   14895   13889   18783   25402   29794
River Rch & RM=BLISS CREEK,Reach-1         ,26328
    8502   12614   16262   15193   20547   27788   32724
River Rch & RM=BLISS CREEK,Reach-1         ,24063
    8502   12614   16262   15193   20547   27788   32724
River Rch & RM=BLISS CREEK,Reach-1         ,23660
    8811   13063   16833   15717   21255   28745   33805
River Rch & RM=BLISS CREEK,Reach-1         ,22934
    8811   13063   16833   15717   21255   28745   33805
River Rch & RM=BLISS CREEK,Reach-1         ,20252
    8902   13188   16987   15852   21438   28992   34058
River Rch & RM=BLISS CREEK,Reach-1         ,16382
    8915   13200   16995   15854   21441   28997   34042
River Rch & RM=BLISS CREEK,Reach-1         ,15274
    8892   13148   16911   15760   21313   28824   33772
River Rch & RM=BLISS CREEK,Reach-1         ,9221
    8860   13096   16841   15694   21225   28704   33636
River Rch & RM=BLISS CREEK,Reach-1         ,7395
    8564   12614   16183   15046   20347   27518   32101
River Rch & RM=BLISS CREEK,Reach-1         ,4875
    8510   12519   16054   14928   20189   27303   31890
River Rch & RM=BLISS CREEK,Reach-1         ,909
    8510   12519   16054   14928   20189   27303   31890
Boundary for River Rch & Prof#=BLISS CREEK,Reach-1         , 1
Up Type= 0
Dn Type= 3
Dn Slope=0.002
Boundary for River Rch & Prof#=BLISS CREEK,Reach-1         , 2
Up Type= 0
Dn Type= 3
Dn Slope=0.002
Boundary for River Rch & Prof#=BLISS CREEK,Reach-1         , 3
Up Type= 0
Dn Type= 3
Dn Slope=0.002
Boundary for River Rch & Prof#=BLISS CREEK,Reach-1         , 4
Up Type= 0
Dn Type= 3
Dn Slope=0.002
Boundary for River Rch & Prof#=BLISS CREEK,Reach-1         , 5
Up Type= 0
Dn Type= 3
Dn Slope=0.002
Boundary for River Rch & Prof#=BLISS CREEK,Reach-1         , 6
Up Type= 0
Dn Type= 3
Dn Slope=0.002
Boundary for River Rch & Prof#=BLISS CREEK,Reach-1         , 7
Up Type= 0
Dn Type= 3
Dn Slope=0.002
DSS Import GetInterval= 0
DSS Import GetPeak= 0
DSS Import FillOption= 0

--- BLISS CREEK.g01 (geometry) ---

Geom Title=Existing Conditions
Program Version=4.10

River Reach=BLISS CREEK     ,Reach-1
Reach XY= 30
      3620037.25       10497652.      3622796.75       10496491.
        3623825.       10497270.       3625169.5       10496500.
       3626682.5       10496955.      3627966.75       10498286.
      3628939.25       10498570.       3629380.5       10498030.
       3631176.5       10498426.      3632765.75       10500067.
       3633506.5       10501987.      3635835.75       10503828.
        3635022.       10509855.       3637107.5       10513217.
      3638116.75       10513662.       3638539.5       10514654.
      3638587.25       10518028.       3639626.5       10518216.
      3640458.25       10519765.      3642806.25       10520104.
      3644122.25       10521554.        3643906.       10522020.
        3645413.       10522623.        3647032.       10525026.
        3650034.       10525502.      3651001.25       10526387.
        3652488.       10526294.      3654282.25       10528401.
       3655527.5       10527980.      3656317.25       10528756.

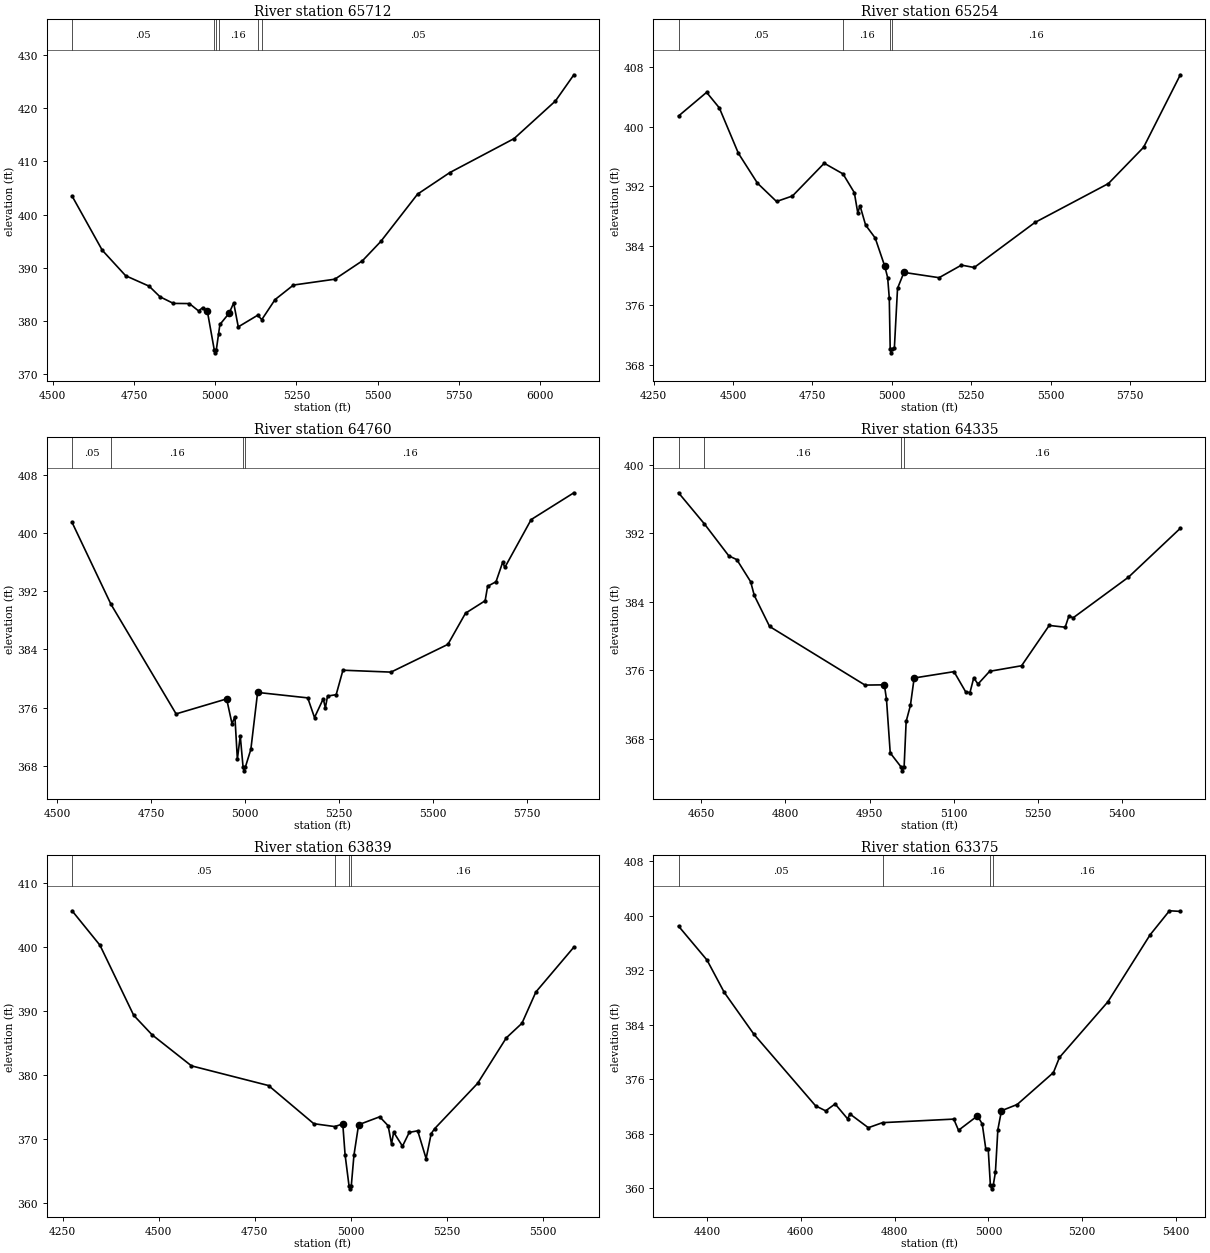
Type RM Length L Ch R = 1 ,65712   ,458,458,458
BEGIN DESCRIPTION:
BLISS CREEK 122.0
END DESCRIPTION:
XS GIS Cut Line= 3
      3620249.62     10498010.21      3620149.61     10497610.19
      3619349.61     10496810.19
#Sta/Elev= 30
  4559.7  403.47  4652.5  393.29  4724.6  388.49  4796.8  386.53  4830.3  384.53
  4871.5  383.29  4920.5  383.26  4948.8  381.88  4961.7   382.5  4975.6  381.93
  4997.3   374.5  5000.1     374  5003.3   374.5  5010.4  377.56  5014.5  379.33
  5042.7  381.43  5056.9  383.37    5071  378.88  5130.5  381.06  5143.4  380.25
  5184.2  384.01  5240.7  386.74    5368  387.84  5452.9   391.3  5509.4  394.93
  5622.6  403.83  5721.6  407.87  5919.6  414.27  6046.8  421.34  6103.4  426.26
#Mann= 6 ,-1 , 0
  4559.7     .05       0  4997.3     .03       0  5003.3     .05       0
  5010.4     .16       0  5130.5     .12       0  5143.4     .05       0
Bank Sta=4975.6,5042.7
XS Rating Curve= 0 ,0
Exp/Cntr=0.3,0.1

Type RM Length L Ch R = 1 ,65254   ,494,494,494
BEGIN DESCRIPTION:
BLISS CREEK 121.0
END DESCRIPTION:
XS GIS Cut Line= 3
      3620493.36     10498048.49      3620515.06     10497484.24
      3620406.55     10496475.13
#Sta/Elev= 30
  4328.5  401.43  4416.9  404.61  4456.9  402.52  4516.9  396.42    4577   392.4
    4637  389.94  4687.1  390.68  4787.1  395.08  4846.2  393.65  4881.9  391.13
  4892.7  388.41  4899.8  389.37  4917.4  386.77  4947.5  385.04  4977.7  381.24
  4986.8  379.71  4991.9  376.97  4994.8   370.1  4997.6   369.6  5000.8   370.1
  5007.9  370.22  5017.9  378.27  5038.1  380.41  5148.7   379.7  5219.1  381.39
  5259.3  381.07  5450.4  387.12  5681.7  392.35  5792.4  397.22  5908.1  406.97
#Mann= 4 ,-1 , 0
  4328.5     .05       0  4846.2     .16       0  4994.8     .07       0
  5000.8     .16       0
Bank Sta=4977.7,5038.1
XS Rating Curve= 0 ,0
Exp/Cntr=0.3,0.1

Type RM Length L Ch R = 1 ,64760   ,425,425,425
BEGIN DESCRIPTION:
BLISS CREEK 120.0
END DESCRIPTION:
XS GIS Cut Line= 3
      3621299.59     10497760.17      3620949.61     10497460.19
      3620599.59     10496660.15
#Sta/Elev= 30
  4540.3  401.45  4643.7  390.21  4816.9  375.15  4951.3  377.21  4965.6  373.79
  4973.3  374.76  4979.8  368.93  4987.5  372.13    4995  367.83  4997.7  367.33
    5001  367.83  5015.7  370.29  5033.6   378.1  5166.9  377.35  5184.9  374.65
  5208.2  377.23  5213.7  375.97  5219.6   377.6  5242.5  377.79  5260.5  381.15
  5388.3  380.89  5539.6   384.7  5586.4  388.98  5638.6  390.69  5645.2  392.68
  5667.5   393.3  5685.4     396  5690.9  395.26    5761  401.84  5874.5  405.52
#Mann= 4 ,-1 , 0
  4540.3     .05       0  4643.7     .16       0    4995     .07       0
    5001     .16       0
Bank Sta=4951.3,5033.6
XS Rating Curve= 0 ,0
Exp/Cntr=0.3,0.1

Type RM Length L Ch R = 1 ,64335   ,496,496,496
BEGIN DESCRIPTION:
BLISS CREEK 119.0
END DESCRIPTION:
XS GIS Cut Line= 3
       3621399.6     10497610.17      3621299.61     10497260.19
      3620899.61     10496910.19
#Sta/Elev= 30
  4609.2  396.75  4655.4  393.11  4698.9  389.38  4713.2  388.94  4737.9  386.36
  4744.4  384.75  4771.7  381.13    4942  374.28  4976.5  374.31  4980.3  372.63
    4987  366.35  5005.8  364.76  5008.5  364.26  5011.8  364.76  5015.4  370.03
    5023   371.9  5029.7  375.11  5100.8  375.85  5121.7  373.48  5129.3  373.41
    5136  375.12  5143.6   374.4  5164.4  375.89  5221.4  376.54  5270.7  381.25
  5299.2  381.04  5305.9  382.37  5313.4  382.14  5412.2  386.89  5504.7   392.6
#Mann= 4 ,-1 , 0
  4609.2     .05       0  4655.4     .16       0  5005.8     .07       0
  5011.8     .16       0
Bank Sta=4976.5,5029.7
XS Rating Curve= 0 ,0
Exp/Cntr=0.3,0.1

Type RM Length L Ch R = 1 ,63839   ,464,464,464
BEGIN DESCRIPTION:
BLISS CREEK 118.0
END DESCRIPTION:
XS GIS Cut Line= 3
      3621699.61     10497710.15      3621649.61     10497010.19
      3621899.61     10496460.18
#Sta/Elev= 30
  4274.8  405.72  4347.4  400.33  4435.2  389.37  4482.8  386.33  4585.5  381.46
  4786.1  378.38  4903.9  372.41  4958.5  371.96  4979.3  372.38  4985.3  367.56
  4995.5  362.72  4998.3  362.22  5001.5  362.72  5008.4  367.49  5020.5  372.25
  5075.4  373.49  5097.4  372.09  5106.2  369.24  5111.7  371.08  5134.7  368.89
  5152.3  371.05  5174.3   371.3  5196.2  366.95  5209.4  370.86  5218.2  371.62
  5330.2  378.72  5404.9  385.84  5445.6  388.12  5481.8  393.01  5580.7  400.03
#Mann= 4 ,-1 , 0
  4274.8     .05       0  4958.5     .16       0  4995.5     .07       0
  5001.5     .16       0
Bank Sta=4979.3,5020.5
XS Rating Curve= 0 ,0
Exp/Cntr=0.3,0.1

Type RM Length L Ch R = 1 ,63375   ,405,405,405
BEGIN DESCRIPTION:
BLISS CREEK 117.0
END DESCRIPTION:
XS GIS Cut Line= 3
      3622149.61     10497560.22      3622049.61     10496910.19
      3621949.61     10496510.17
#Sta/Elev= 30
  4339.3  398.45    4400  393.48  4436.7  388.75  4499.9  382.62  4631.5  372.12
    4653  371.38  4673.2  372.39  4699.8  370.21  4704.8  370.92    4744  368.91
  4774.3  369.65  4926.2  370.17  4936.3  368.53  4976.7  370.64  4986.9  369.46
  4994.4  365.84  4999.6  365.84  5004.3  360.45    5007  359.95  5010.3  360.45
    5015  362.37  5020.2  368.62  5027.9   371.4  5061.4  372.31  5138.7  376.99
  5151.6  379.21  5254.7  387.35  5344.9  397.18  5386.1   400.7  5409.3  400.61
#Mann= 4 ,-1 , 0
  4339.3     .05       0  4774.3     .16       0  5004.3     .07       0
  5010.3     .16       0
Bank Sta=4976.7,5027.9
XS Rating Curve= 0 ,0
Exp/Cntr=0.3,0.1

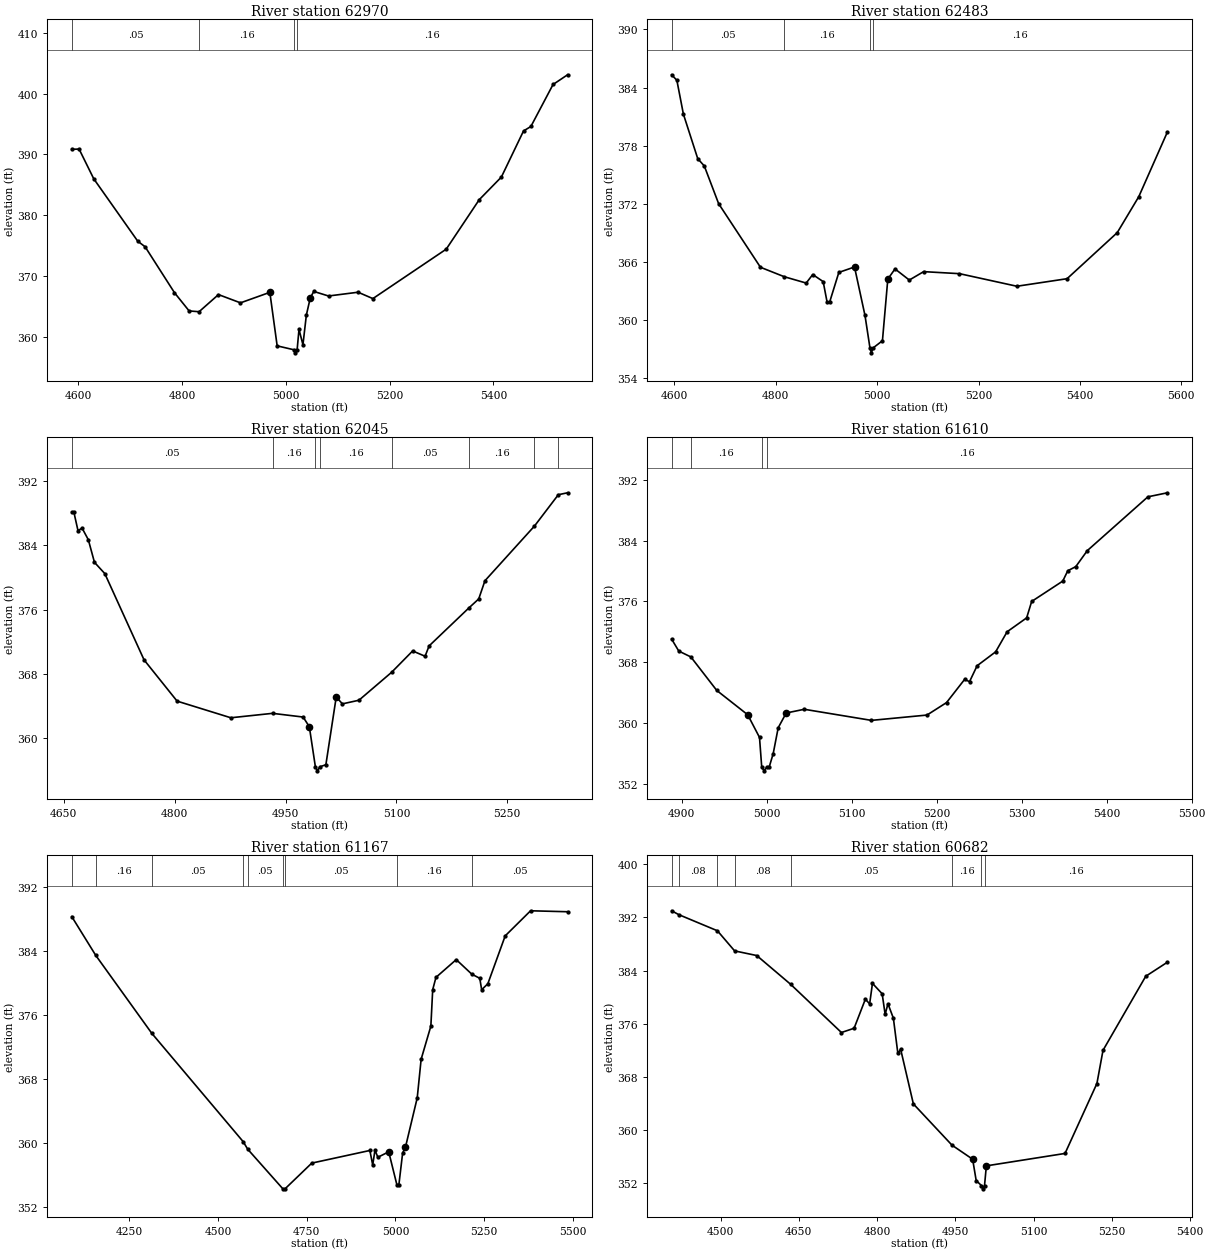
Type RM Length L Ch R = 1 ,62970   ,487,487,487
BEGIN DESCRIPTION:
BLISS CREEK 116.0
END DESCRIPTION:
XS GIS Cut Line= 3
      3622699.59     10497110.17      3622399.61     10496810.19
      3621999.64     10496460.21
#Sta/Elev= 30
  4587.2  390.83  4601.3  390.87  4629.6  385.97  4714.4   375.7  4728.6  374.78
  4785.2  367.22  4813.4  364.22  4832.6  364.09    4870  366.91  4912.4  365.55
    4969  367.28  4983.1  358.47  5015.6  357.82  5018.3  357.32  5021.6  357.82
  5025.2  361.18  5032.8  358.65  5039.4  363.54    5047  366.39  5053.7  367.43
  5082.1  366.68  5139.1   367.3  5167.6  366.25    5309  374.39  5372.6  382.53
  5415.3  386.26    5458  393.85  5472.2  394.59  5514.9   401.5  5542.9   403.1
#Mann= 4 ,-1 , 0
  4587.2     .05       0  4832.6     .16       0  5015.6     .07       0
  5021.6     .16       0
Bank Sta=4969,5047
XS Rating Curve= 0 ,0
Exp/Cntr=0.3,0.1

Type RM Length L Ch R = 1 ,62483   ,438,438,438
BEGIN DESCRIPTION:
BLISS CREEK 115.0
END DESCRIPTION:
XS GIS Cut Line= 3
       3622849.6     10496960.16      3622749.61     10496560.19
      3622349.58     10496160.16
#Sta/Elev= 30
  4594.7  385.32    4605  384.75  4617.9  381.25  4646.2  376.65  4659.1   375.9
  4687.4     372  4769.9  365.43  4817.1  364.45  4860.1   363.8    4873  364.68
  4893.6  363.95  4901.3  361.84  4906.5  361.86  4924.5   364.9  4955.4  365.46
  4976.1  360.45  4985.9  357.09  4988.7  356.59  4991.9  357.09  5010.5  357.84
  5021.1  364.21  5035.3  365.26  5063.5  364.11  5091.8  364.98  5162.5  364.77
  5275.7  363.47  5374.7  364.25  5473.7  369.01  5516.1  372.72  5572.7  379.42
#Mann= 4 ,-1 , 0
  4594.7     .05       0  4817.1     .16       0  4985.9     .07       0
  4991.9     .16       0
Bank Sta=4955.4,5021.1
XS Rating Curve= 0 ,0
Exp/Cntr=0.3,0.1

Type RM Length L Ch R = 1 ,62045   ,435,435,435
BEGIN DESCRIPTION:
BLISS CREEK 114.0
END DESCRIPTION:
XS GIS Cut Line= 3
      3622899.61     10496960.18      3623049.61     10496660.19
       3623349.6     10496510.19
#Sta/Elev= 30
  4660.8  388.16  4663.6  388.16  4669.2  385.85  4674.8  386.15  4683.2  384.71
  4691.5   381.9  4705.5   380.5  4758.6  369.77  4803.3  364.64    4876  362.57
  4932.4  363.12  4973.8  362.66  4982.2  361.46  4990.4  356.47  4993.2  355.97
  4996.4  356.47  5004.6  356.73  5018.6  365.15    5027   364.3  5049.3  364.75
  5093.6  368.23    5122  370.88  5138.8  370.22  5144.3  371.51  5198.2  376.24
  5211.4  377.35  5219.8  379.61  5286.8  386.41  5319.1  390.31  5331.6  390.55
#Mann= 8 ,-1 , 0
  4660.8     .05       0  4932.4     .16       0  4990.4     .07       0
  4996.4     .16       0  5093.6     .05       0  5198.2     .16       0
  5286.8     .08       0  5319.1     .16       0
Bank Sta=4982.2,5018.6
XS Rating Curve= 0 ,0
Exp/Cntr=0.3,0.1

Type RM Length L Ch R = 1 ,61610   ,443,443,443
BEGIN DESCRIPTION:
BLISS CREEK 113.0
END DESCRIPTION:
XS GIS Cut Line= 3
      3623099.59      10497110.2      3623199.61     10497060.19
      3623599.59      10496810.2
#Sta/Elev= 30
    4888  371.02  4896.4  369.45  4910.6  368.68  4941.1  364.27  4977.5  361.07
  4991.4  358.09    4994  354.19  4996.8  353.69    5000  354.19  5002.8  354.19
  5007.5  355.95  5013.4  359.36  5022.8   361.3  5044.1  361.79  5123.1  360.33
  5188.5  361.03  5211.5  362.67  5232.7  365.71  5238.6  365.43  5247.5  367.52
  5269.3  369.35  5282.8  371.99  5305.8  373.82  5311.7  375.98  5348.3  378.66
  5354.2  380.02  5363.6  380.56  5377.2  382.67  5448.5  389.75  5471.5  390.28
#Mann= 4 ,-1 , 0
    4888     .05       0  4910.6     .16       0    4994     .07       0
    5000     .16       0
Bank Sta=4977.5,5022.8
XS Rating Curve= 0 ,0
Exp/Cntr=0.3,0.1

Type RM Length L Ch R = 1 ,61167   ,485,485,485
BEGIN DESCRIPTION:
BLISS CREEK 112.0
END DESCRIPTION:
XS GIS Cut Line= 3
      3624099.62      10497910.2      3623549.61     10497210.19
      3623694.24     10496724.92
#Sta/Elev= 30
  4088.2   388.3  4155.9  383.44  4313.4  373.71  4570.9  360.15  4583.8   359.2
  4682.9  354.24  4688.9  354.24  4764.3  357.46  4927.9  359.04  4935.9  357.22
  4942.3  359.09  4950.4  358.19    4981  358.87  5004.2  354.71  5009.7  354.78
  5020.2  358.72  5028.2  359.46  5061.3  365.62  5072.3  370.45  5099.7   374.6
  5104.9  379.16  5114.1   380.7  5171.2  382.92    5215   381.1  5237.5  380.58
  5242.8  379.15  5260.2   379.9  5309.1  385.89  5380.6  389.03  5484.8  388.91
#Mann= 9 ,-1 , 0
  4088.2     .05       0  4155.9     .16       0  4313.4     .05       0
  4570.9     .16       0  4583.8     .05       0  4682.9     .03       0
  4688.9     .05       0  5004.2     .16       0    5215     .05       0
Bank Sta=4981,5028.2
XS Rating Curve= 0 ,0
Exp/Cntr=0.3,0.1

Type RM Length L Ch R = 1 ,60682   ,445,445,445
BEGIN DESCRIPTION:
BLISS CREEK 111.0
END DESCRIPTION:
XS GIS Cut Line= 3
      3624215.14     10497755.48      3623999.61     10497210.19
      3623899.62     10496860.23
#Sta/Elev= 30
  4406.2     393  4419.8  392.42  4493.9  389.99  4526.9  386.96  4569.3  386.26
  4634.1  381.94  4731.6  374.67  4755.9  375.31  4777.5  379.69  4785.7  378.98
  4791.1  382.07  4809.7   380.5  4815.4   377.4  4820.8     379  4831.2  376.82
  4839.8  371.51  4845.1  372.16  4869.5  363.92  4943.5  357.71  4983.1  355.59
  4989.9  352.38  4999.9  351.63  5002.7  351.13  5005.9  351.63  5009.4  354.59
  5160.2  356.46  5221.3  366.99    5233  371.99  5314.9  383.14  5356.5  385.26
#Mann= 8 ,-1 , 0
  4406.2     .05       0  4419.8     .08       0  4493.9     .16       0
  4526.9     .08       0  4634.1     .05       0  4943.5     .16       0
  4999.9     .07       0  5005.9     .16       0
Bank Sta=4983.1,5009.4
XS Rating Curve= 0 ,0
Exp/Cntr=0.3,0.1

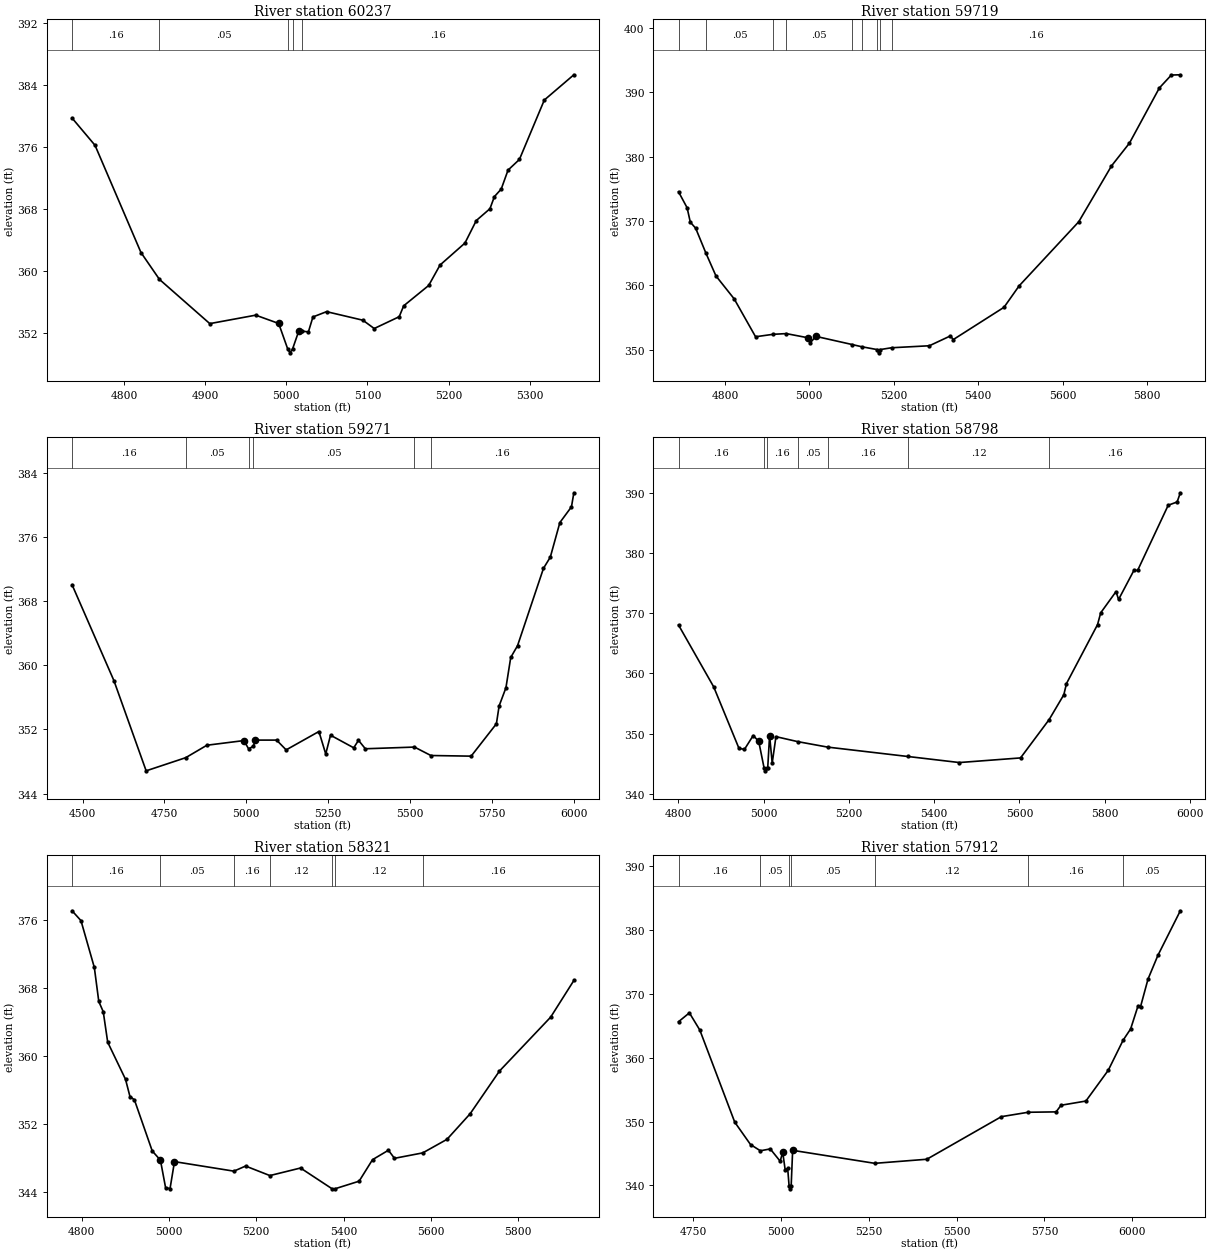
Type RM Length L Ch R = 1 ,60237   ,518,518,518
BEGIN DESCRIPTION:
BLISS CREEK 110.0
END DESCRIPTION:
XS GIS Cut Line= 3
      3624549.62      10497160.2      3624349.61     10496960.19
      3624049.58     10496810.18
#Sta/Elev= 30
    4736  379.72  4764.3  376.21  4820.9  362.41  4843.7  358.95  4905.7  353.26
  4962.3  354.35  4990.6  353.28  5001.7     350  5004.5   349.5  5007.7     350
  5015.3  352.29  5019.3  352.29  5027.2   352.2  5032.8  354.12  5049.6   354.8
  5094.3   353.7  5108.3  352.63  5139.1  354.15  5144.6  355.55  5175.4  358.17
  5189.4   360.8  5220.1  363.63  5234.1  366.53  5250.9  368.05  5256.4  369.61
  5264.8  370.58  5273.2  373.02  5287.2  374.39  5317.9  382.04  5354.3  385.29
#Mann= 5 ,-1 , 0
    4736     .16       0  4843.7     .05       0  5001.7     .03       0
  5007.7     .05       0  5019.3     .16       0
Bank Sta=4990.6,5015.3
XS Rating Curve= 0 ,0
Exp/Cntr=0.3,0.1

Type RM Length L Ch R = 1 ,59719   ,448,448,448
BEGIN DESCRIPTION:
BLISS CREEK 109.0
END DESCRIPTION:
XS GIS Cut Line= 3
      3624749.61     10496960.22      3624699.61     10496660.19
      3624049.58     10496060.16
#Sta/Elev= 30
  4690.2  374.56  4710.5  372.08  4718.1  369.84  4730.8   368.9  4755.1  365.02
  4778.9  361.48    4822  357.92  4872.7  352.03  4914.2  352.41  4945.4  352.52
  4997.8  351.86  5001.5  351.03  5015.6  352.09  5101.6  350.82    5124  350.48
  5161.2  350.03    5164  349.53  5167.2  350.03  5194.8  350.32  5284.4  350.63
  5334.3  352.16  5341.1  351.59  5461.3  356.61  5497.1  359.94  5638.3   369.9
  5715.9  378.58  5758.5  382.13  5829.3   390.7  5857.7  392.71    5879  392.75
#Mann= 9 ,-1 , 0
  4690.2     .16       0  4755.1     .05       0  4914.2     .16       0
  4945.4     .05       0  5101.6     .16       0    5124     .12       0
  5161.2     .03       0  5167.2     .12       0  5194.8     .16       0
Bank Sta=4997.8,5015.6
XS Rating Curve= 0 ,0
Exp/Cntr=0.3,0.1

Type RM Length L Ch R = 1 ,59271   ,473,473,473
BEGIN DESCRIPTION:
BLISS CREEK 108.0
END DESCRIPTION:
XS GIS Cut Line= 3
      3625449.62      10496910.2      3625099.61     10496510.19
       3625699.6      10495710.2
#Sta/Elev= 30
  4468.1  370.02  4595.8  358.08  4694.2  346.84    4815  348.48  4879.6  350.03
  4992.5  350.61  5006.9  349.58  5021.5  349.91  5027.7  350.67  5092.3  350.67
  5121.5  349.45  5221.5  351.74  5242.3  348.94  5256.9  351.28  5327.7  349.71
  5342.3  350.64  5363.2  349.59  5513.2   349.8  5563.2  348.75  5686.1  348.67
  5763.2   352.7  5771.5  354.93  5792.3  357.19  5806.9  360.96  5827.7  362.43
  5906.9  372.07  5927.7  373.46  5956.9  377.77  5992.3  379.73  5999.6  381.48
#Mann= 6 ,-1 , 0
  4468.1     .16       0    4815     .05       0  5006.9     .07       0
  5021.5     .05       0  5513.2     .12       0  5563.2     .16       0
Bank Sta=4992.5,5027.7
XS Rating Curve= 0 ,0
Exp/Cntr=0.3,0.1

Type RM Length L Ch R = 1 ,58798   ,477,477,477
BEGIN DESCRIPTION:
BLISS CREEK 107.0
END DESCRIPTION:
XS GIS Cut Line= 3
      3625549.61     10496760.18      3625499.61     10496560.19
      3626049.62     10495760.17
#Sta/Elev= 30
  4800.3  368.05  4882.8  357.76    4942  347.54  4954.9  347.36  4975.5  349.67
  4988.4  348.69  5000.9  344.29  5003.6  343.79  5006.9  344.29  5009.5  344.29
  5013.9  349.67    5020  345.08  5028.8  349.48  5079.9  348.65  5149.9  347.74
  5337.9  346.18    5459  345.17  5602.5  345.94  5669.7  352.33    5704  356.45
  5710.3  358.32  5783.1  368.12  5790.6  370.09  5826.4  373.61  5832.5  372.31
  5868.3  377.13  5877.2  377.15  5948.9  387.99  5969.8  388.53  5977.3  390.06
#Mann= 7 ,-1 , 0
  4800.3     .16       0  5000.9     .07       0  5006.9     .16       0
  5079.9     .05       0  5149.9     .16       0  5337.9     .12       0
  5669.7     .16       0
Bank Sta=4988.4,5013.9
XS Rating Curve= 0 ,0
Exp/Cntr=0.3,0.1

Type RM Length L Ch R = 1 ,58321   ,409,409,409
BEGIN DESCRIPTION:
BLISS CREEK 106.0
END DESCRIPTION:
XS GIS Cut Line= 3
      3625599.57      10496860.2      3625849.61     10496810.19
       3626249.6     10496010.21
#Sta/Elev= 30
  4778.2  377.06  4798.6   375.9  4829.2  370.39  4839.4  366.39  4849.6  365.19
  4859.8   361.6  4900.6  357.24  4910.8  355.21    4921  354.82  4961.8  348.81
  4980.6  347.72  4992.4  344.49  5002.6  344.37  5012.8  347.55  5148.9  346.43
  5175.7  347.03  5231.3  345.91  5301.5   346.8    5374  344.35    5380  344.35
  5435.7  345.25  5466.4  347.78  5502.8  348.89  5516.7  347.94  5581.5  348.58
  5636.9  350.17    5690  353.18  5757.1   358.2  5874.5  364.55  5927.6  368.86
#Mann= 7 ,-1 , 0
  4778.2     .16       0  4980.6     .05       0  5148.9     .16       0
  5231.3     .12       0    5374     .03       0    5380     .12       0
  5581.5     .16       0
Bank Sta=4980.6,5012.8
XS Rating Curve= 0 ,0
Exp/Cntr=0.3,0.1

Type RM Length L Ch R = 1 ,57912   ,661,661,661
BEGIN DESCRIPTION:
BLISS CREEK 105.0
END DESCRIPTION:
XS GIS Cut Line= 3
      3625987.11     10497260.47      3626121.67      10497060.8
      3626949.61     10496210.19
#Sta/Elev= 30
  4708.9  365.65  4739.8  367.04  4769.5  364.34  4868.8   349.9  4913.7  346.39
  4941.7  345.41  4969.9   345.7  4998.1  343.77  5005.3  345.19  5012.3  342.43
  5019.5  342.64  5023.4  339.94  5026.2  339.44  5029.4  339.94  5033.6  345.48
  5267.3  343.44  5415.4  344.08  5627.5  350.76  5703.8  351.45  5783.2  351.51
  5797.3  352.55    5868  353.21  5931.6  358.03  5973.9  362.75  5995.3  364.52
  6016.5  368.16  6023.6  368.03  6044.8  372.34    6073  376.07  6136.7  383.05
#Mann= 7 ,-1 , 0
  4708.9     .16       0  4941.7     .05       0  5023.4     .03       0
  5029.4     .05       0  5267.3     .12       0  5703.8     .16       0
  5973.9     .05       0
Bank Sta=5005.3,5033.6
XS Rating Curve= 0 ,0
Exp/Cntr=0.3,0.1

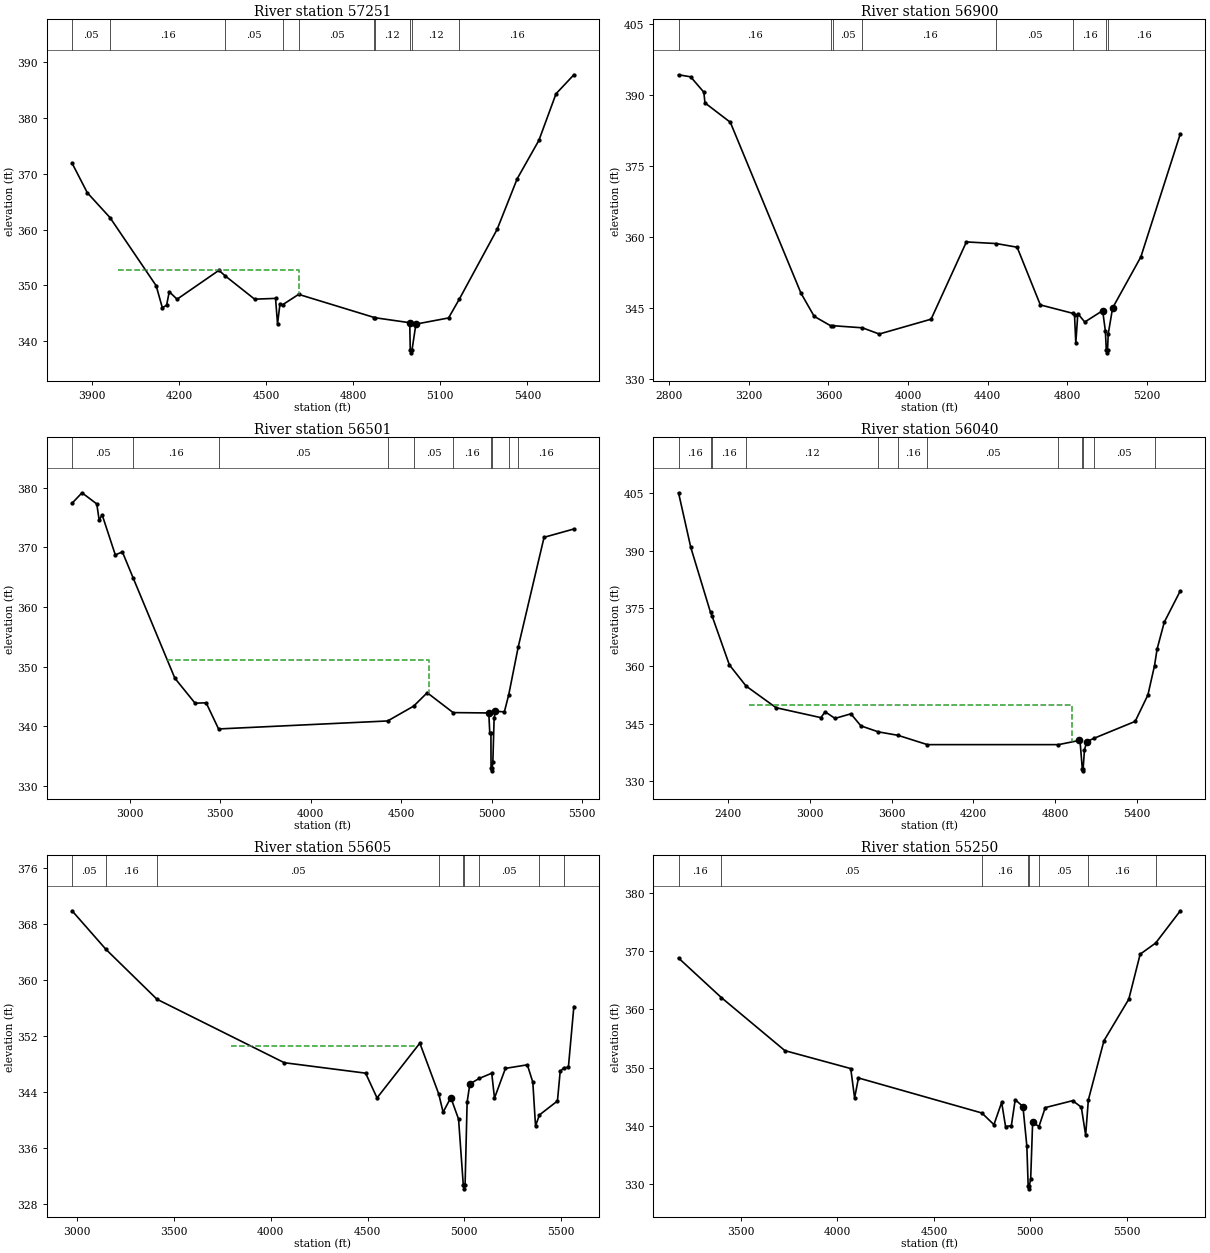
Type RM Length L Ch R = 1 ,57251   ,351,351,351
BEGIN DESCRIPTION:
BLISS CREEK 104.0
END DESCRIPTION:
XS GIS Cut Line= 3
      3626095.29     10498018.82        3626745.       10497047.
      3627255.67     10496816.21
#Sta/Elev= 30
    3831  371.87  3883.6  366.57  3961.6  362.14  4120.9  349.94  4142.1     346
  4156.9  346.47  4165.9  348.87  4192.9  347.53  4337.1   352.7  4359.2  351.69
  4460.2  347.54  4532.3  347.68  4539.1  343.12  4547.3  346.59  4556.8  346.55
  4611.9   348.4  4873.3  344.25  4873.6  344.23  4994.7  343.33  4996.6  338.44
  4999.4  337.94  5002.6  338.44    5016  343.08  5128.5  344.18    5166  347.58
  5295.8  360.01  5365.2  369.09    5440  375.96  5498.9  384.28  5560.4  387.68
#Mann= 10 ,-1 , 0
    3831     .05       0  3961.6     .16       0  4359.2     .05       0
  4556.8     .16       0  4611.9     .05       0  4873.3     .16       0
  4873.6     .12       0  4996.6     .07       0  5002.6     .12       0
    5166     .16       0
#XS Ineff= 1 ,-1
 3990.23 4614.09  352.68
Permanent Ineff=
       F
Bank Sta=4994.7,5016
XS Rating Curve= 0 ,0
Exp/Cntr=0.3,0.1

Type RM Length L Ch R = 1 ,56900   ,399,399,399
BEGIN DESCRIPTION:
BLISS CREEK 103.0
END DESCRIPTION:
XS GIS Cut Line= 3
      3625975.46     10499206.39      3626949.61     10497310.19
       3627249.6     10497060.19
#Sta/Elev= 30
  2846.6  394.26  2907.3  393.83  2973.8  390.59  2979.4  388.33  3106.9  384.24
  3461.9   348.2  3528.4   343.3  3610.5  341.33  3624.1  341.32  3770.9  340.88
  3855.6  339.57  4116.2   342.7  4293.6     359  4444.7  358.65  4548.6  357.88
  4665.2  345.71  4829.2  343.93    4837  343.64  4843.5  337.63  4853.6  343.87
  4888.5   342.1  4978.4   344.5  4992.1  340.23  4996.9   336.1  4999.6   335.6
  5002.9   336.1  5006.4  339.55  5028.5  345.07  5170.4  355.83  5368.9  381.82
#Mann= 8 ,-1 , 0
  2846.6     .16       0  3610.5     .07       0  3624.1     .05       0
  3770.9     .16       0  4444.7     .05       0  4829.2     .16       0
  4996.9     .07       0  5002.9     .16       0
#XS Ineff= 1 ,-1
 3313.07 4381.82 351.905
Permanent Ineff=
       F
Bank Sta=4978.4,5028.5
XS Rating Curve= 0 ,0
Exp/Cntr=0.3,0.1

Type RM Length L Ch R = 1 ,56501   ,461,461,461
BEGIN DESCRIPTION:
BLISS CREEK 102.0
END DESCRIPTION:
XS GIS Cut Line= 3
       3626058.8       10499722.      3627099.61     10497660.19
       3627428.6     10497336.57
#Sta/Elev= 30
  2682.5   377.4  2737.4  379.15    2819  377.28  2832.1  374.59  2848.8  375.44
  2921.3  368.74  2960.3  369.24  3019.4  364.91  3250.2  348.07  3361.7  343.89
    3423  343.95  3491.6  339.57  4425.4  340.91  4569.1   343.4  4643.7  345.64
  4786.9  342.31  4983.8  342.25  4989.3  338.84  4995.6  338.84  4996.2  333.05
  4998.9  332.55  5002.2  333.05  5006.2     334  5013.3  341.41  5020.3  342.52
  5069.9  342.44  5093.9   345.3  5146.5  353.33  5289.1  371.69  5453.6  373.08
#Mann= 10 ,-1 , 0
  2682.5     .05       0  3019.4     .16       0  3491.6     .05       0
  4425.4     .16       0  4569.1     .05       0  4786.9     .16       0
  4996.2     .07       0  5002.2     .16       0  5093.9     .05       0
  5146.5     .16       0
#XS Ineff= 1 ,-1
 3207.39 4651.14351.1496
Permanent Ineff=
       F
Bank Sta=4983.8,5020.3
XS Rating Curve= 0 ,0
Exp/Cntr=0.3,0.1

Type RM Length L Ch R = 1 ,56040   ,435,435,435
BEGIN DESCRIPTION:
BLISS CREEK 101.0
END DESCRIPTION:
XS GIS Cut Line= 3
      3626470.27     10500815.72      3627349.61     10498010.19
      3627699.63     10497360.15
#Sta/Elev= 30
  2038.4  405.03    2128  390.86  2272.9  373.92  2283.9  373.05    2411   360.3
  2533.2  354.81  2753.3  349.17  3081.7  346.59  3113.1   348.1  3185.5  346.39
  3301.8  347.58  3375.1  344.45  3502.9  342.89  3647.2  341.99  3862.8  339.57
  4823.5  339.57  4975.9  340.66  4981.3  340.66  4998.2  333.26    5001  332.76
  5004.2  333.26  5014.2   338.2  5030.4  340.32  5082.6   341.2  5385.8  345.61
  5479.1  352.48  5527.7  360.11  5546.4  364.39  5599.1   371.4  5716.8  379.55
#Mann= 12 ,-1 , 0
  2038.4     .16       0  2272.9     .05       0  2283.9     .16       0
  2533.2     .12       0  3502.9     .05       0  3647.2     .16       0
  3862.8     .05       0  4823.5     .16       0  4998.2     .07       0
  5004.2     .16       0  5082.6     .05       0  5527.7     .16       0
#XS Ineff= 1 ,-1
 2554.55    4925349.9289
Permanent Ineff=
       F
Bank Sta=4975.9,5030.4
XS Rating Curve= 0 ,0
Exp/Cntr=0.3,0.1

Type RM Length L Ch R = 1 ,55605   ,355,355,355
BEGIN DESCRIPTION:
BLISS CREEK 100.0
END DESCRIPTION:
XS GIS Cut Line= 3
      3627817.58     10500186.07      3627749.61     10498160.19
      3628149.61     10497760.19
#Sta/Elev= 30
  2973.2  369.83  3147.8  364.34    3412  357.21  4069.7  348.16  4489.9  346.67
  4548.9  343.14  4770.1  350.95    4868  343.68  4890.2   341.1  4930.2  343.18
  4970.2  340.11  4994.7  330.67  4997.5  330.17  5000.7  330.67  5003.8  330.67
  5014.4  342.53  5028.5  345.13  5076.4  345.91  5141.6  346.66  5155.8  343.11
  5212.3  347.35  5325.5  347.86  5353.8  345.39  5367.9  339.14    5388  340.71
  5481.1   342.7  5495.2  346.92  5513.5  347.43  5537.6  347.51  5565.9  356.17
#Mann= 9 ,-1 , 0
  2973.2     .05       0  3147.8     .16       0    3412     .05       0
    4868     .16       0  4994.7     .07       0  5000.7     .16       0
  5076.4     .05       0    5388     .16       0  5513.5     .05       0
#XS Ineff= 1 ,-1
 3796.59  4757.1  350.53
Permanent Ineff=
       F
Bank Sta=4930.2,5028.5
XS Rating Curve= 0 ,0
Exp/Cntr=0.3,0.1

Type RM Length L Ch R = 1 ,55250   ,516,516,516
BEGIN DESCRIPTION:
BLISS CREEK 99.0
END DESCRIPTION:
XS GIS Cut Line= 3
       3628208.2     10500110.12      3628067.14     10498265.49
       3628402.9     10497593.96
#Sta/Elev= 30
  3176.5  368.78  3398.3  362.01    3728  352.91    4069  349.84  4089.1  344.81
  4109.1  348.23  4748.5  342.23  4811.2  340.23  4851.3  344.05  4871.4  339.91
  4901.5  340.05  4921.5  344.51  4961.6  343.33  4981.7   336.6  4988.7  329.73
  4991.5  329.23  4994.7  329.73  5001.7  330.95  5011.8  340.64  5044.6  339.91
  5077.2  343.15  5219.5  344.34  5264.2  343.22  5286.6  338.42  5300.6  344.47
  5381.6  354.62  5510.2  361.73  5569.1  369.44  5649.5  371.35  5777.3  376.88
#Mann= 8 ,-1 , 0
  3176.5     .16       0  3398.3     .05       0  4748.5     .16       0
  4988.7     .07       0  4994.7     .16       0  5044.6     .05       0
  5300.6     .16       0  5649.5     .05       0
Bank Sta=4961.6,5011.8
XS Rating Curve= 0 ,0
Exp/Cntr=0.3,0.1

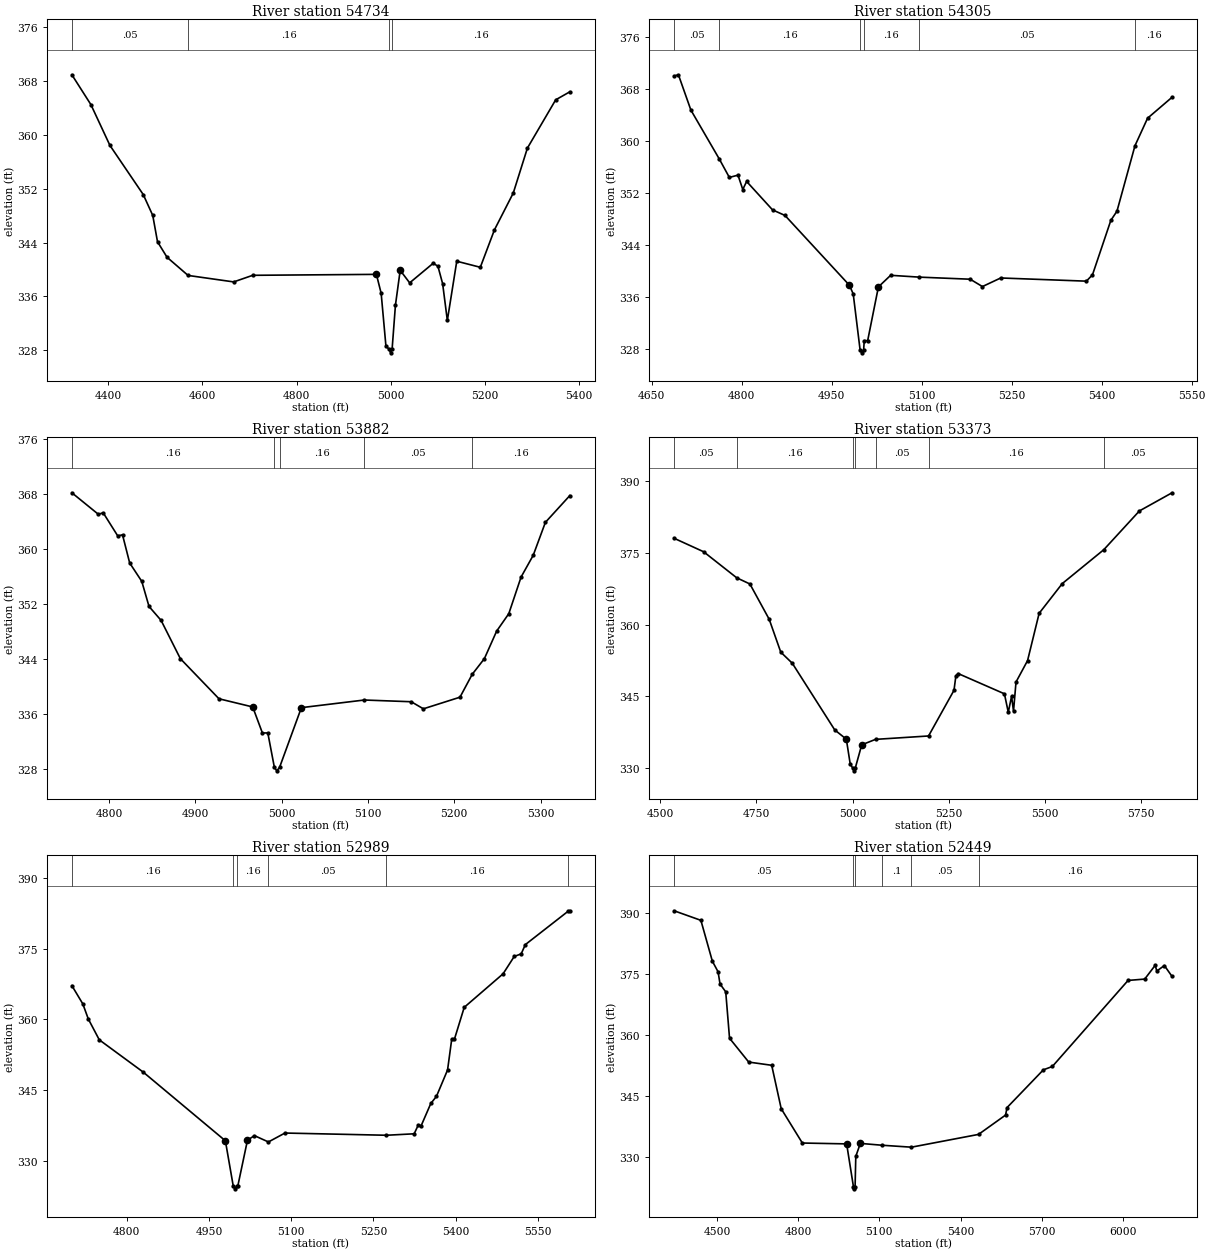
Type RM Length L Ch R = 1 ,54734   ,429,429,429
BEGIN DESCRIPTION:
BLISS CREEK 98.0
END DESCRIPTION:
XS GIS Cut Line= 3
      3628649.61     10499110.19      3628549.61     10498410.19
      3628549.61      10498060.2
#Sta/Elev= 30
  4322.8   368.9  4363.2  364.47  4403.6  358.41  4474.3  351.12  4494.5  348.02
  4504.6  344.11  4524.8  341.81  4569.5  339.11  4666.3  338.15  4706.7  339.13
  4969.3  339.27  4979.4  336.46  4989.5  328.64  4996.6  328.12  4999.4  327.62
  5002.6  328.12  5009.7  334.69  5019.8  339.87  5039.9  338.01  5089.9  340.92
  5099.9  340.48  5109.9  337.89  5119.9  332.43  5139.9  341.22  5189.9  340.32
  5219.9  345.88  5259.9  351.35  5289.9  358.02  5349.9  365.18  5379.9  366.37
#Mann= 4 ,-1 , 0
  4322.8     .05       0  4569.5     .16       0  4996.6     .07       0
  5002.6     .16       0
Bank Sta=4969.3,5019.8
XS Rating Curve= 0 ,0
Exp/Cntr=0.3,0.1

Type RM Length L Ch R = 1 ,54305   ,423,423,423
BEGIN DESCRIPTION:
BLISS CREEK 97.0
END DESCRIPTION:
XS GIS Cut Line= 3
      3629199.63     10498760.21      3628949.61     10498560.19
      3628849.61     10498060.18
#Sta/Elev= 30
  4687.2     370  4694.4  370.19  4715.2  364.76  4762.8   357.2  4779.3  354.41
  4793.7  354.76  4801.7  352.55  4808.1  353.79  4851.3  349.42  4872.1  348.56
  4979.4  337.84  4985.8   336.5  4997.2  327.94  4999.9  327.44  5003.2  327.94
  5004.2  329.32  5009.9  329.32  5027.8  337.58  5048.2  339.36  5095.8  339.08
  5180.8  338.76  5201.2  337.63  5231.7  338.95  5374.5  338.46  5384.7  339.44
  5415.3  347.81  5425.5  349.22  5455.5  359.28  5476.5  363.51  5517.3  366.73
#Mann= 6 ,-1 , 0
  4687.2     .05       0  4762.8     .16       0  4997.2     .07       0
  5003.2     .16       0  5095.8     .05       0  5455.5     .16       0
Bank Sta=4979.4,5027.8
XS Rating Curve= 0 ,0
Exp/Cntr=0.3,0.1

Type RM Length L Ch R = 1 ,53882   ,509,509,509
BEGIN DESCRIPTION:
BLISS CREEK 96.0
END DESCRIPTION:
XS GIS Cut Line= 3
      3629349.58     10498360.17      3629149.61     10498260.19
      3628899.63     10498010.21
#Sta/Elev= 30
  4756.8  368.13  4787.5     365  4793.1  365.22  4809.9  361.87  4815.5  362.01
  4823.8  357.92  4837.8  355.25  4846.2   351.6  4860.2  349.57  4882.5  344.01
  4927.3  338.17  4966.4  336.98  4977.6   333.2  4983.9   333.2  4991.5  328.19
  4994.3  327.69  4997.5  328.19  5022.8  336.88  5095.7  337.99  5150.1  337.74
  5164.2  336.71  5206.6   338.4  5220.8  341.73  5234.9  344.01  5249.1  348.01
  5263.2  350.55  5277.4  355.87  5291.5  359.04  5305.6  363.83  5333.9  367.72
#Mann= 5 ,-1 , 0
  4756.8     .16       0  4991.5     .07       0  4997.5     .16       0
  5095.7     .05       0  5220.8     .16       0
Bank Sta=4966.4,5022.8
XS Rating Curve= 0 ,0
Exp/Cntr=0.3,0.1

Type RM Length L Ch R = 1 ,53373   ,384,384,384
BEGIN DESCRIPTION:
BLISS CREEK 95.0
END DESCRIPTION:
XS GIS Cut Line= 2
      3629553.69     10498536.74      3629466.88     10497245.55
#Sta/Elev= 30
  4536.3  378.02    4613  375.21    4699  369.77  4733.3  368.48  4783.4  361.12
  4813.5  354.25  4843.5  351.93  4953.8  338.01  4983.9  336.08  4993.9  330.96
  5000.9  329.97  5003.7  329.47  5006.9  329.97  5023.9   334.9  5059.8  336.04
  5197.6  336.75  5263.7  346.28  5268.7  349.33  5274.5  349.78  5394.8  345.55
  5404.8   341.7  5413.4  345.03  5418.4  341.93  5424.9  348.01  5454.9  352.48
    5485  362.36  5545.1  368.56  5653.1  375.64  5745.6  383.73  5830.4  387.52
#Mann= 7 ,-1 , 0
  4536.3     .05       0    4699     .16       0  5000.9     .07       0
  5006.9     .16       0  5059.8     .05       0  5197.6     .16       0
  5653.1     .05       0
Bank Sta=4983.9,5023.9
XS Rating Curve= 0 ,0
Exp/Cntr=0.3,0.1

Type RM Length L Ch R = 1 ,52989   ,540,540,540
BEGIN DESCRIPTION:
BLISS CREEK 94.0
END DESCRIPTION:
XS GIS Cut Line= 3
      3629899.61      10498410.2      3629899.61     10498110.19
      3629999.61     10497510.17
#Sta/Elev= 30
  4699.8  367.16  4719.8  363.28  4729.8  360.08  4749.8  355.67  4829.8  348.84
  4979.8  334.27  4994.3  324.58  4997.1  324.08  5000.3  324.58  5002.3  324.58
  5020.1  334.39  5032.8  335.36  5058.3  334.02  5088.5  335.91  5273.7  335.44
  5324.2  335.75  5331.8  337.64  5336.9  337.45  5354.6  342.19  5364.8  343.67
  5385.1  349.28  5392.7  355.81  5397.7  355.83  5415.5  362.56  5486.4  369.67
  5506.7  373.34  5519.4   373.9    5527  375.86    5605  382.93  5608.1  383.03
#Mann= 6 ,-1 , 0
  4699.8     .16       0  4994.3     .07       0  5000.3     .16       0
  5058.3     .05       0  5273.7     .16       0    5605     .05       0
Bank Sta=4979.8,5020.1
XS Rating Curve= 0 ,0
Exp/Cntr=0.3,0.1

Type RM Length L Ch R = 1 ,52449   ,356,356,356
BEGIN DESCRIPTION:
BLISS CREEK 93.0
END DESCRIPTION:
XS GIS Cut Line= 3
      3629944.29     10498764.64      3630313.23      10498417.4
      3630909.66     10497224.55
#Sta/Elev= 30
  4341.5  390.64  4440.5  388.29  4482.9  378.25    4504  375.64  4511.3  372.63
  4532.3  370.72  4546.4  359.31  4617.3  353.45  4702.2  352.66  4737.4  341.98
  4815.5  333.55  4979.2  333.34  5004.4  322.79  5007.2  322.29  5010.4  322.79
    5013  330.27  5029.8  333.46  5111.1     333  5218.7  332.53  5466.6  335.67
  5566.5  340.42  5572.1  342.27  5706.2  351.54  5739.5  352.37  6019.3  373.52
  6080.8  373.85  6119.6  377.24  6125.5  375.82  6153.4  377.18  6181.8  374.51
#Mann= 6 ,-1 , 0
  4341.5     .05       0  5004.4     .03       0  5010.4     .05       0
  5111.1      .1       0  5218.7     .05       0  5466.6     .16       0
Bank Sta=4979.2,5029.8
XS Rating Curve= 0 ,0
Exp/Cntr=0.3,0.1