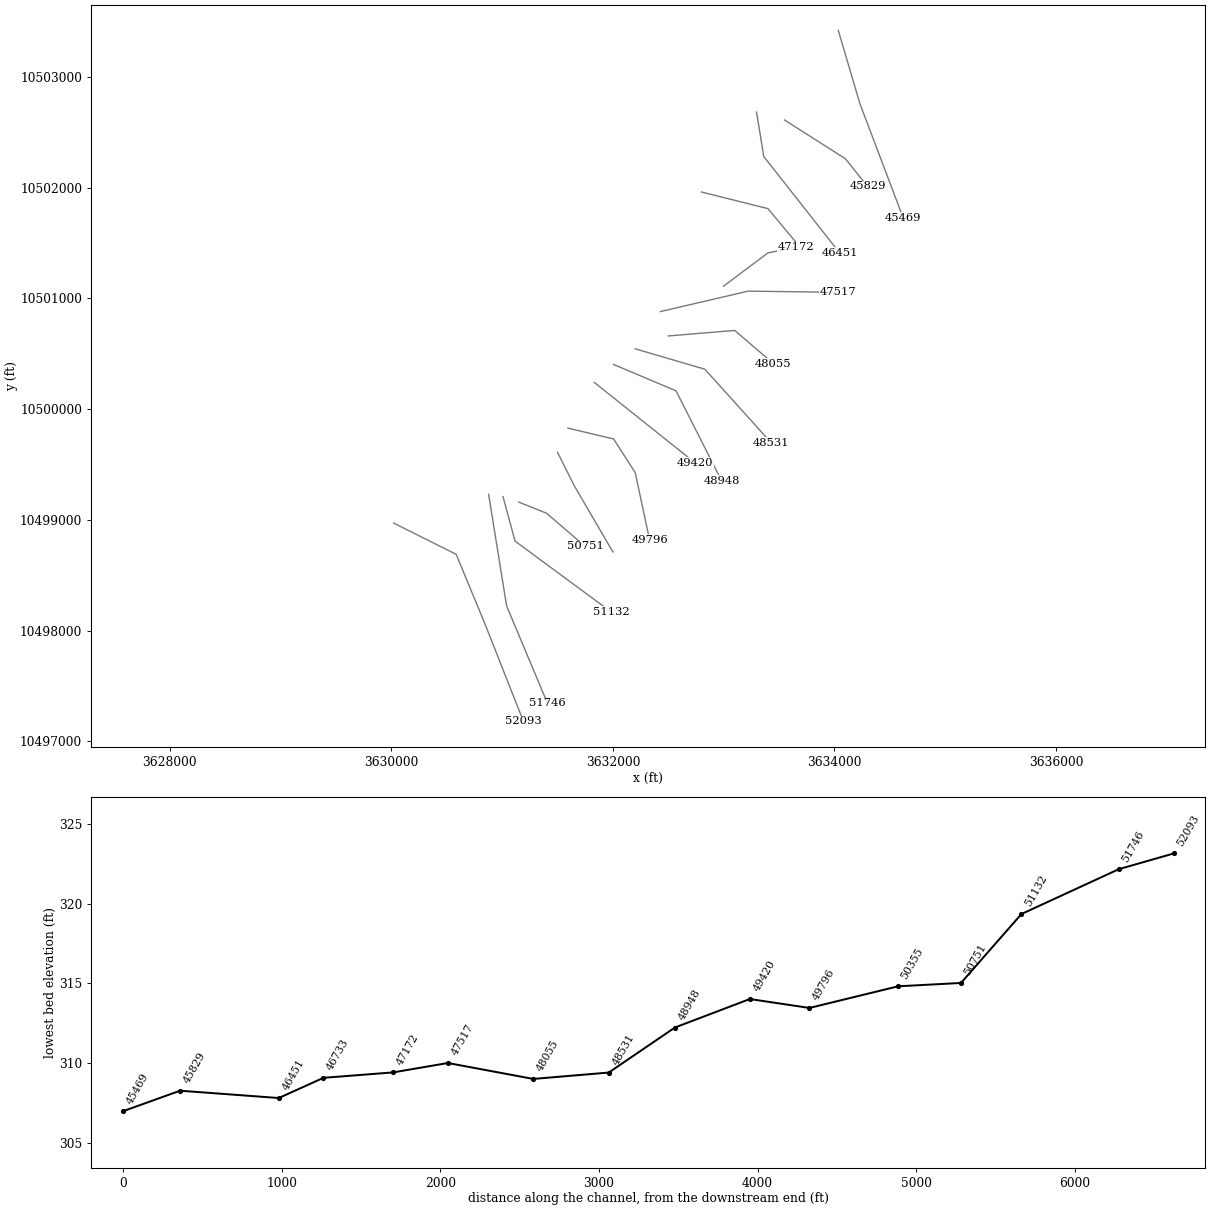
HEC-RAS study BLISS CREEK.prj: BLISS CREEK Base Level Engineering

--- BLISS CREEK.g01 (geometry) --- (continued)

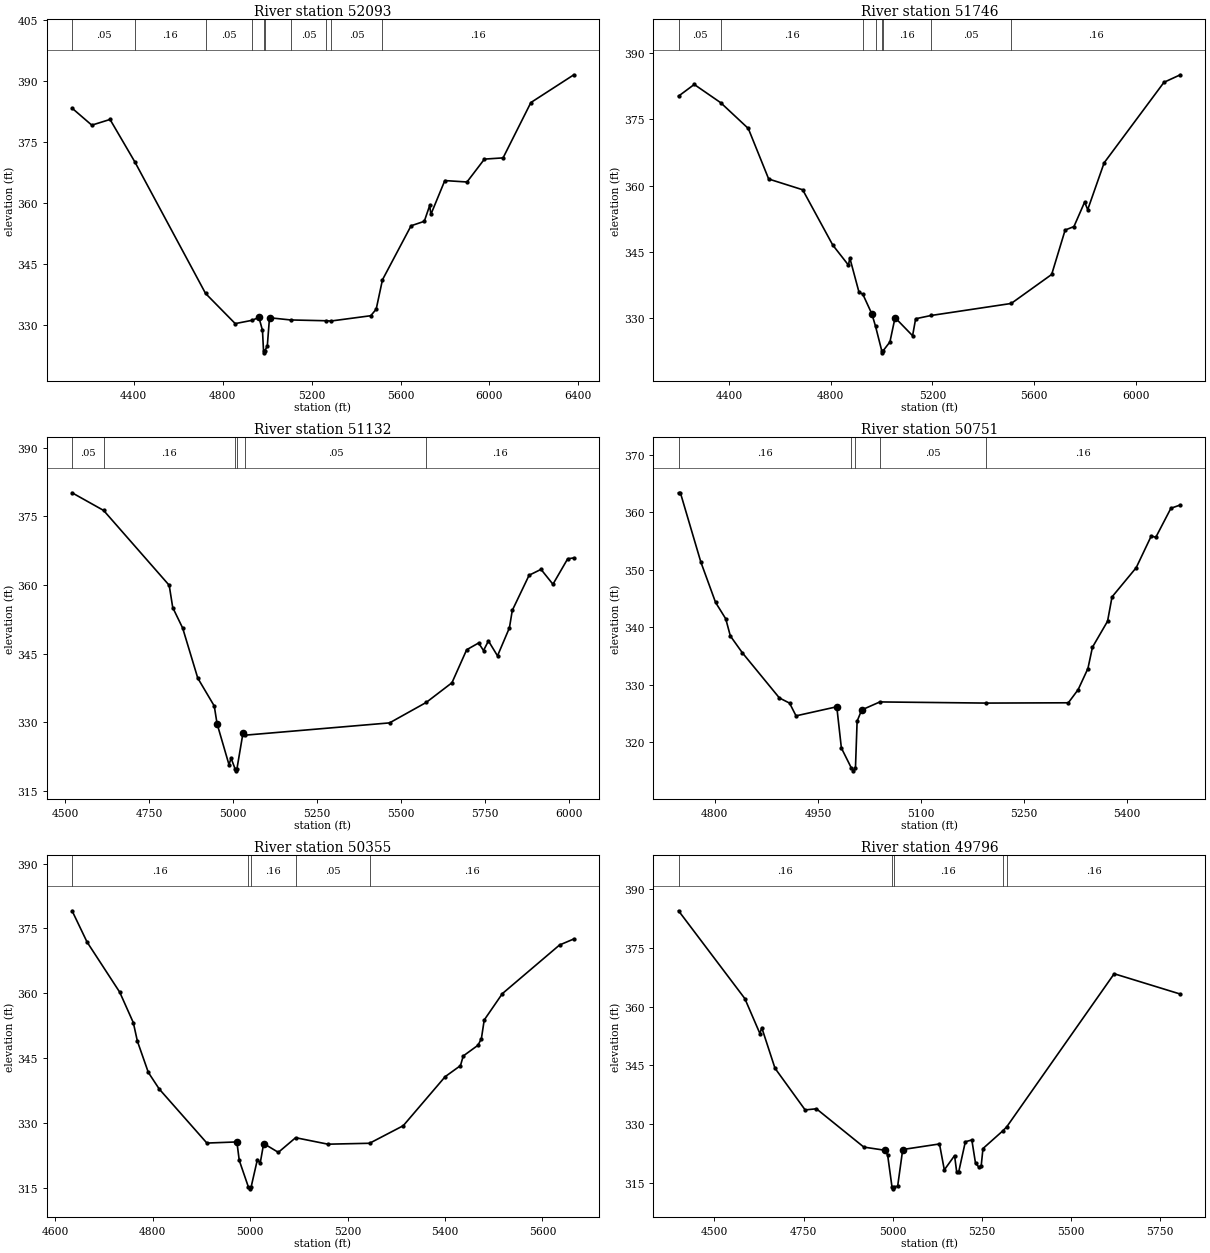
Type RM Length L Ch R = 1 ,52093   ,347,347,347
BEGIN DESCRIPTION:
BLISS CREEK 92.0
END DESCRIPTION:
XS GIS Cut Line= 4
       3630020.3     10498970.76       3630584.5     10498688.66
      3630844.92     10498059.32      3631192.14     10497180.41
#Sta/Elev= 30
  4122.8  383.35  4211.5  379.17  4293.6  380.57  4405.7  370.08  4723.3  337.77
  4856.6  330.36  4933.5  331.18    4963  331.92  4979.2  328.69  4983.9  323.67
  4986.7  323.17  4989.9  323.67  5000.9  324.86  5010.8   331.8  5105.5  331.26
  5266.9  331.06  5286.3  330.99  5466.2   332.3  5490.6   333.9  5518.9  341.14
  5647.5  354.42    5707  355.52  5731.3  359.41  5736.7  357.23  5799.3  365.54
    5899  365.19  5977.5  370.82  6061.3  371.12  6186.4  384.73  6379.7  391.56
#Mann= 10 ,-1 , 0
  4122.8     .05       0  4405.7     .16       0  4723.3     .05       0
  4933.5     .16       0  4983.9     .07       0  4989.9     .16       0
  5105.5     .05       0  5266.9     .16       0  5286.3     .05       0
  5518.9     .16       0
Bank Sta=4963,5010.8
XS Rating Curve= 0 ,0
Exp/Cntr=0.3,0.1

Type RM Length L Ch R = 1 ,51746   ,614,614,614
BEGIN DESCRIPTION:
BLISS CREEK 91.0
END DESCRIPTION:
XS GIS Cut Line= 3
      3630877.47     10499231.23      3631040.23     10498222.08
      3631408.74     10497344.18
#Sta/Elev= 30
  4200.9  380.25  4262.7  382.89  4366.9  378.76  4475.4  372.93  4555.6   361.5
  4689.3  359.07  4807.8  346.55  4869.6  342.01  4874.7  343.66    4911  335.88
  4925.9  335.45  4961.6  330.98    4976  328.18  5000.3  322.68  5003.1  322.18
  5006.3  322.68  5032.6  324.65  5052.8  330.14  5121.8  326.05  5133.8  329.89
  5194.5  330.63  5509.8  333.35    5669  339.91    5722  349.96  5756.6  350.74
  5798.7  356.28  5810.8  354.57  5875.4  365.16  6110.9  383.38  6175.2  385.08
#Mann= 8 ,-1 , 0
  4200.9     .05       0  4366.9     .16       0  4925.9     .05       0
    4976     .16       0  5000.3     .07       0  5006.3     .16       0
  5194.5     .05       0  5509.8     .16       0
Bank Sta=4961.6,5052.8
XS Rating Curve= 0 ,0
Exp/Cntr=0.3,0.1

Type RM Length L Ch R = 1 ,51132   ,381,381,381
BEGIN DESCRIPTION:
BLISS CREEK 90.0
END DESCRIPTION:
XS GIS Cut Line= 3
      3631007.68     10499209.48      3631116.19     10498808.02
      3631984.28      10498167.8
#Sta/Elev= 30
  4521.1  380.13  4615.1  376.27  4810.4  359.91  4820.9  355.05  4850.5  350.56
  4895.5  339.62  4944.6  333.53    4953  329.64  4988.5   320.7  4994.7  322.12
  5006.3  319.86  5009.1  319.36  5012.3  319.86  5030.2  327.64  5037.4  327.16
  5466.7  329.84  5575.9  334.31  5652.5  338.61  5696.4  345.83  5731.9   347.3
  5746.5  345.65  5761.2  347.75  5788.2  344.49  5823.7  350.62  5832.2  354.42
  5882.3  362.11  5917.8  363.39  5953.3  360.14  5997.2   365.7  6015.6   365.9
#Mann= 6 ,-1 , 0
  4521.1     .05       0  4615.1     .16       0  5006.3     .07       0
  5012.3     .16       0  5037.4     .05       0  5575.9     .16       0
Bank Sta=4953,5030.2
XS Rating Curve= 0 ,0
Exp/Cntr=0.3,0.1

Type RM Length L Ch R = 1 ,50751   ,396,396,396
BEGIN DESCRIPTION:
BLISS CREEK 89.0
END DESCRIPTION:
XS GIS Cut Line= 3
      3631149.57      10499160.2      3631399.61     10499060.19
      3631749.63     10498760.17
#Sta/Elev= 30
  4747.2  363.37  4749.9  363.37  4779.6  351.35  4801.1  344.31  4815.9  341.46
  4822.6  338.48  4840.1  335.55    4894   327.7  4908.8   326.8  4918.2  324.59
  4977.5  326.17  4984.2     319  4998.7  315.53  5001.4  315.03  5004.7  315.53
  5007.1  323.66  5013.8  325.62  5040.2  327.01  5194.3  326.81  5314.5  326.86
  5328.8  329.15    5343  332.81  5349.6  336.52  5371.6  341.04  5378.1  345.27
  5413.3  350.35  5435.2  355.86  5441.8  355.63  5463.8  360.68  5477.5  361.25
#Mann= 5 ,-1 , 0
  4747.2     .16       0  4998.7     .07       0  5004.7     .16       0
  5040.2     .05       0  5194.3     .16       0
Bank Sta=4977.5,5013.8
XS Rating Curve= 0 ,0
Exp/Cntr=0.3,0.1

Type RM Length L Ch R = 1 ,50355   ,559,559,559
BEGIN DESCRIPTION:
BLISS CREEK 88.0
END DESCRIPTION:
XS GIS Cut Line= 3
      3631499.62     10499610.16      3631649.61     10499310.19
      3631999.61     10498710.19
#Sta/Elev= 30
  4634.5  379.08  4665.2  371.87  4732.3  360.27  4760.2  353.23  4768.6  348.94
    4791  341.73  4813.4  337.89  4911.2   325.4  4972.8  325.66  4977.7  321.39
  4996.2  315.32    4999  314.82  5002.2  315.32  5014.9  321.59  5020.7  320.77
  5027.8  325.29  5057.9  323.25  5093.4  326.64  5159.7  325.14  5245.1  325.35
  5314.3  329.41  5400.3  340.74  5431.7  343.29  5437.5  345.53  5467.7     348
  5474.7  349.54  5480.5  353.84  5517.7  359.93  5635.1  371.17  5664.5  372.57
#Mann= 5 ,-1 , 0
  4634.5     .16       0  4996.2     .07       0  5002.2     .16       0
  5093.4     .05       0  5245.1     .16       0
Bank Sta=4972.8,5027.8
XS Rating Curve= 0 ,0
Exp/Cntr=0.3,0.1

Type RM Length L Ch R = 1 ,49796   ,376,376,376
BEGIN DESCRIPTION:
BLISS CREEK 87.0
END DESCRIPTION:
XS GIS Cut Line= 4
      3631593.64     10499827.98      3632005.94     10499730.33
      3632201.26     10499426.51      3632331.46      10498818.9
#Sta/Elev= 30
  4399.7  384.46  4585.5  362.04  4627.8   353.1  4632.9  354.62    4670  344.26
  4754.5  333.61  4786.1   333.9    4919  324.12  4978.1  323.31  4985.7   322.1
  4997.9  313.96  5000.7  313.46  5003.9  313.96  5013.8  314.13    5028   323.5
    5131  324.92  5144.6   318.3  5173.3  321.95  5179.4  317.67  5184.6  317.67
  5203.5  325.48  5221.7  325.94    5232  319.99  5242.2  318.95  5247.8  319.22
  5252.9  323.75  5307.8  328.21  5319.5  329.29  5620.6  368.38    5806  363.19
#Mann= 5 ,-1 , 0
  4399.7     .16       0  4997.9     .07       0  5003.9     .16       0
  5307.8     .05       0  5319.5     .16       0
Bank Sta=4978.1,5028
XS Rating Curve= 0 ,0
Exp/Cntr=0.3,0.1

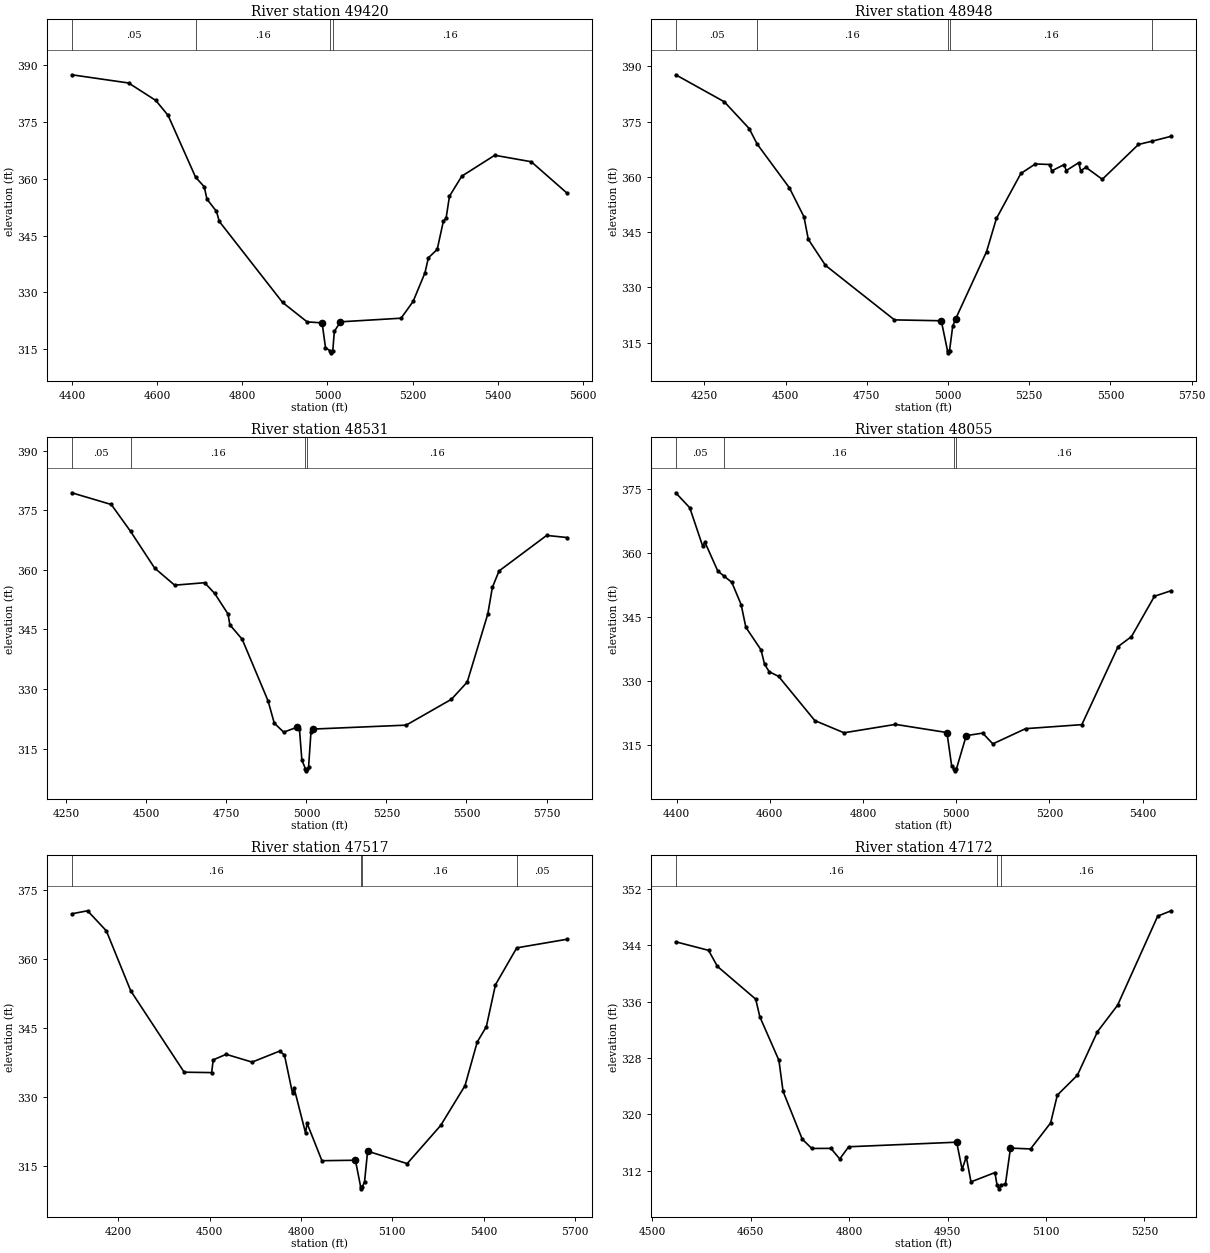
Type RM Length L Ch R = 1 ,49420   ,472,472,472
BEGIN DESCRIPTION:
BLISS CREEK 86.0
END DESCRIPTION:
XS GIS Cut Line= 2
      3631832.37     10500240.29      3632742.59     10499514.28
#Sta/Elev= 30
  4399.1  387.54  4532.7  385.37  4596.8  380.74  4625.6  376.79  4690.2  360.45
  4710.5  357.94  4716.9  354.65  4739.3  351.43  4745.7   348.8  4894.6  327.35
  4952.3  322.21  4987.5  321.94  4995.5  315.41  5006.6  314.52  5009.3  314.02
  5012.6  314.52  5016.3   319.7  5030.7  322.22  5173.2  323.18  5201.4  327.61
  5229.3  335.18  5237.3  339.14  5258.1  341.37  5272.5  348.81  5278.9  349.59
  5286.9  355.43  5315.8  360.73  5393.3  366.26  5479.1  364.55  5563.4  356.23
#Mann= 4 ,-1 , 0
  4399.1     .05       0  4690.2     .16       0  5006.6     .07       0
  5012.6     .16       0
Bank Sta=4987.5,5030.7
XS Rating Curve= 0 ,0
Exp/Cntr=0.3,0.1

Type RM Length L Ch R = 1 ,48948   ,417,417,417
BEGIN DESCRIPTION:
BLISS CREEK 85.0
END DESCRIPTION:
XS GIS Cut Line= 3
      3632005.98     10500403.06      3632570.18     10500164.36
       3632982.5     10499350.57
#Sta/Elev= 30
  4161.8  387.74  4311.3  380.41  4387.8  373.15  4412.3  368.95  4511.7  357.04
  4556.6  349.16  4569.9  343.05  4622.8  335.98  4835.1  321.18  4979.3  320.94
  4998.6  312.73  5001.3  312.23  5004.6  312.73  5014.5   319.5  5023.9  321.53
  5118.6   339.7    5149  348.72  5224.3  360.94  5268.9  363.53  5313.4  363.37
    5319  361.63    5358  363.37  5363.6   361.7  5402.5  363.88  5408.1  361.72
  5424.8  362.59  5474.9  359.35  5586.3  368.82  5626.8  369.68  5686.7  371.03
#Mann= 5 ,-1 , 0
  4161.8     .05       0  4412.3     .16       0  4998.6     .07       0
  5004.6     .16       0  5626.8     .05       0
Bank Sta=4979.3,5023.9
XS Rating Curve= 0 ,0
Exp/Cntr=0.3,0.1

Type RM Length L Ch R = 1 ,48531   ,476,476,476
BEGIN DESCRIPTION:
BLISS CREEK 84.0
END DESCRIPTION:
XS GIS Cut Line= 3
      3632201.22     10500544.14       3632830.6     10500359.67
      3633427.41     10499697.75
#Sta/Elev= 30
  4267.2  379.43  4390.6  376.48  4450.8  369.72    4526  360.47  4588.6  356.16
  4682.3  356.78  4713.6  354.08  4755.3  348.89  4760.9  346.19  4799.5  342.54
  4880.3  327.03  4899.7  321.41  4929.1  319.14  4971.7  320.41  4978.4  319.86
  4985.9  312.13  4997.1   309.9  4999.8   309.4  5003.1   309.9  5006.8  310.29
  5014.3  319.16    5021  319.92  5311.7  320.91    5453  327.42  5502.3  331.75
  5566.6  348.91  5580.8  355.58  5601.7  359.74  5750.4  368.69  5814.3  368.16
#Mann= 4 ,-1 , 0
  4267.2     .05       0  4450.8     .16       0  4997.1     .07       0
  5003.1     .16       0
Bank Sta=4971.7,5021
XS Rating Curve= 0 ,0
Exp/Cntr=0.3,0.1

Type RM Length L Ch R = 1 ,48055   ,538,538,538
BEGIN DESCRIPTION:
BLISS CREEK 83.0
END DESCRIPTION:
XS GIS Cut Line= 3
      3632499.65     10500660.19      3633099.61     10500710.19
       3633449.6      10500410.2
#Sta/Elev= 30
  4398.1  374.19  4428.2  370.68  4455.8  361.74  4460.8  362.59  4488.4  355.84
  4500.9  354.73  4518.5  353.19  4538.5  347.96  4548.6  342.65  4581.2  337.35
  4588.7     334  4598.8  332.23  4618.8  331.15  4696.6  320.78  4759.3  317.92
  4869.7  319.89  4980.1  317.98  4990.1  310.25  4994.6   309.5  4997.4     309
  5000.6   309.5  5021.5  317.25  5056.7  317.85  5078.6  315.32  5148.9  318.89
  5269.6  319.83  5347.5  338.15  5376.1  340.47  5425.4  349.93  5461.1  351.23
#Mann= 4 ,-1 , 0
  4398.1     .05       0  4500.9     .16       0  4994.6     .07       0
  5000.6     .16       0
Bank Sta=4980.1,5021.5
XS Rating Curve= 0 ,0
Exp/Cntr=0.3,0.1

Type RM Length L Ch R = 1 ,47517   ,345,345,345
BEGIN DESCRIPTION:
BLISS CREEK 82.0
END DESCRIPTION:
XS GIS Cut Line= 3
      3632429.11      10500880.5      3633221.22     10501064.97
      3634034.84     10501054.12
#Sta/Elev= 30
  4047.4  369.72  4099.3  370.38  4161.1  366.02  4241.1     353  4416.6  335.33
  4506.9  335.24    4512  338.01  4554.6  339.21  4639.8  337.52  4730.1  339.91
  4746.1  339.04  4772.6  330.71  4777.8  331.86  4815.2  322.15  4820.4  324.22
  4869.1  316.11  4979.1  316.21  4996.1   310.5  4998.9     310  5002.1   310.5
  5009.1  311.54  5019.1  318.18  5149.1  315.48  5259.1  323.76  5339.1  332.41
  5379.1  341.87  5409.1  345.21  5439.1  354.32    5509  362.33  5674.4   364.2
#Mann= 4 ,-1 , 0
  4047.4     .16       0  4996.1     .07       0  5002.1     .16       0
    5509     .05       0
Bank Sta=4979.1,5019.1
XS Rating Curve= 0 ,0
Exp/Cntr=0.3,0.1

Type RM Length L Ch R = 1 ,47172   ,439,439,439
BEGIN DESCRIPTION:
BLISS CREEK 81.0
END DESCRIPTION:
XS GIS Cut Line= 3
      3632999.57     10501110.16      3633399.61     10501410.19
      3633649.61     10501460.19
#Sta/Elev= 30
  4535.7  344.52  4585.7  343.31  4599.3  341.02  4657.6  336.37  4663.9  333.86
    4693  327.67  4699.3  323.27  4728.5  316.48    4743  315.15  4772.2  315.16
  4785.7  313.66  4799.3  315.39  4963.9  316.04  4972.2  312.17  4978.5  313.96
  4985.7   310.4  5022.2  311.72  5025.5  309.91  5028.2  309.41  5031.5  309.91
  5038.3  310.13  5045.9   315.2  5076.5  315.08  5107.1  318.78  5117.3  322.73
  5147.9  325.56  5178.5  331.75  5209.1   335.5  5270.3  348.17  5290.7  348.93
#Mann= 3 ,-1 , 0
  4535.7     .16       0  5025.5     .07       0  5031.5     .16       0
Bank Sta=4963.9,5045.9
XS Rating Curve= 0 ,0
Exp/Cntr=0.3,0.1

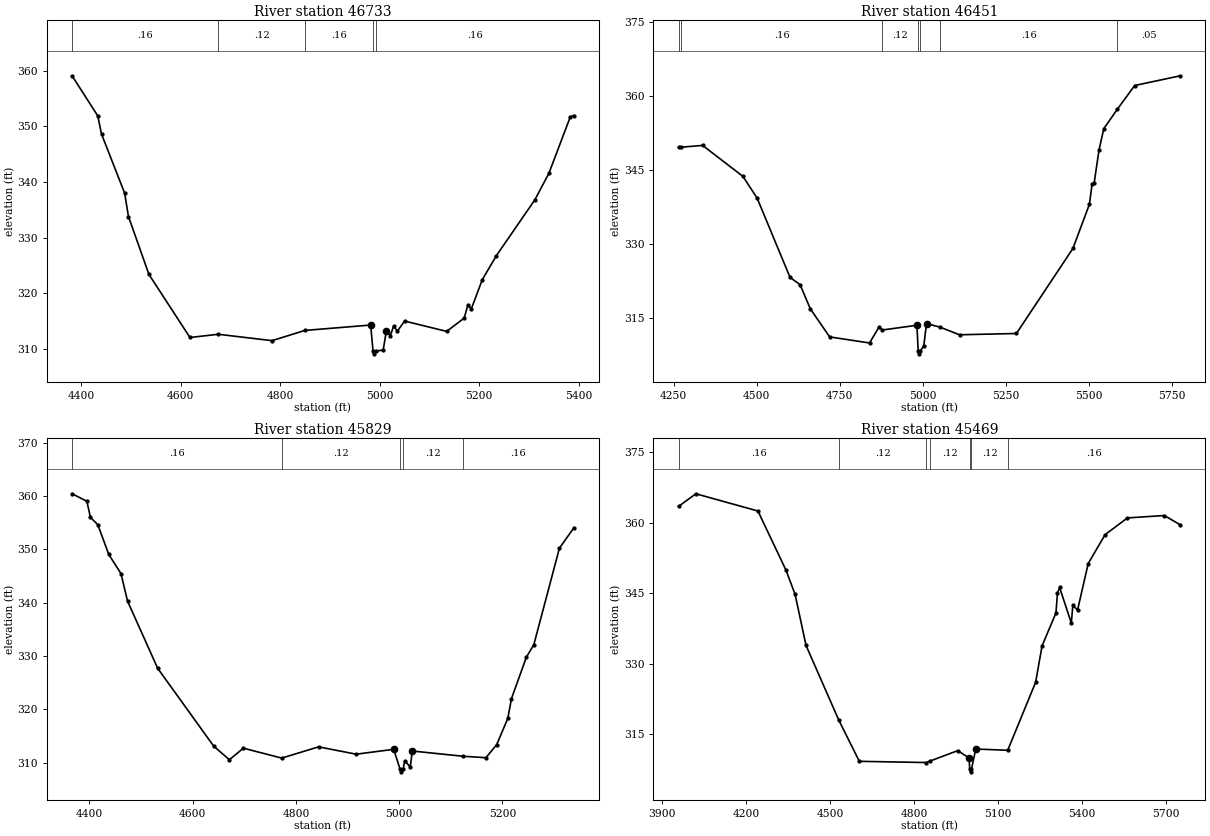
Type RM Length L Ch R = 1 ,46733   ,282,282,282
BEGIN DESCRIPTION:
BLISS CREEK 80.0
END DESCRIPTION:
XS GIS Cut Line= 3
       3632799.6     10501960.19      3633399.61     10501810.19
      3633649.61     10501510.18
#Sta/Elev= 30
  4381.3   359.1  4432.9  351.89  4440.6  348.59    4487  337.98  4494.7  333.78
  4535.9  323.35  4618.4  312.01  4675.3  312.59  4783.3  311.44  4849.4  313.28
  4981.7  314.25  4986.5  309.57  4989.2  309.07  4992.5  309.57  5006.9  309.75
  5013.4  313.26  5021.3  312.35  5027.8  314.03  5035.6  313.17  5049.9  314.97
  5134.5  313.11  5169.7  315.49  5177.5  317.92    5184  317.13  5206.1   322.4
  5234.1  326.68  5312.2  336.83  5340.2  341.57  5383.1   351.7  5390.3  351.95
#Mann= 5 ,-1 , 0
  4381.3     .16       0  4675.3     .12       0  4849.4     .16       0
  4986.5     .07       0  4992.5     .16       0
Bank Sta=4981.7,5013.4
XS Rating Curve= 0 ,0
Exp/Cntr=0.3,0.1

Type RM Length L Ch R = 1 ,46451   ,622,622,622
BEGIN DESCRIPTION:
BLISS CREEK 79.0
END DESCRIPTION:
XS GIS Cut Line= 3
      3633297.17     10502681.74      3633362.28     10502280.24
      3634045.84     10501412.23
#Sta/Elev= 30
  4264.3  349.59  4272.6  349.65  4336.8  350.01  4458.4  343.73  4501.1  339.33
  4600.2  323.28  4630.6   321.8    4661  316.95  4719.5  311.23  4839.7     310
  4868.6  313.27  4878.7  312.63  4982.4  313.59  4986.3   308.3  4989.1   307.8
  4992.3   308.3  5003.2  309.48  5011.3  313.93  5052.3   313.2  5110.7  311.66
  5282.1  311.92  5452.3  329.14    5502  338.08  5510.1  342.14  5516.4  342.41
  5530.9  349.05  5545.3   353.4  5586.3  357.35  5638.4  362.14  5775.9  364.11
#Mann= 7 ,-1 , 0
  4264.3     .05       0  4272.6     .16       0  4878.7     .12       0
  4986.3     .07       0  4992.3     .12       0  5052.3     .16       0
  5586.3     .05       0
Bank Sta=4982.4,5011.3
XS Rating Curve= 0 ,0
Exp/Cntr=0.3,0.1

Type RM Length L Ch R = 1 ,45829   ,360,360,360
BEGIN DESCRIPTION:
BLISS CREEK 78.0
END DESCRIPTION:
XS GIS Cut Line= 3
      3633549.65     10502610.16      3634099.61     10502260.19
      3634299.59     10502010.21
#Sta/Elev= 30
  4366.4  360.45  4395.1  359.05  4401.9  356.04  4416.3  354.64  4437.5  349.06
  4461.2  345.46  4473.9  340.29  4532.3  327.68  4640.7  313.09  4671.1  310.53
  4698.2   312.7  4772.6  310.84  4843.9  312.95  4916.7  311.57  4989.5  312.49
  5001.7  308.76  5004.5  308.26  5007.7  308.76  5010.7  310.34  5021.5  309.17
  5025.5  312.17  5123.1  311.19  5167.9  310.91  5188.8  313.34  5210.4  318.28
  5217.6  322.01  5246.4  329.78  5260.8  332.11  5310.4  350.23  5338.4  354.06
#Mann= 5 ,-1 , 0
  4366.4     .16       0  4772.6     .12       0  5001.7     .07       0
  5007.7     .12       0  5123.1     .16       0
Bank Sta=4989.5,5025.5
XS Rating Curve= 0 ,0
Exp/Cntr=0.3,0.1

Type RM Length L Ch R = 1 ,45469   ,446,446,446
BEGIN DESCRIPTION:
BLISS CREEK 77.0
END DESCRIPTION:
XS GIS Cut Line= 3
      3634035.03     10503419.55      3634230.34     10502757.67
      3634620.95     10501726.89
#Sta/Elev= 30
  3959.2  363.49  4021.1  366.18  4242.8  362.51  4342.7  349.95  4375.6  344.75
  4414.6  333.88  4531.3  318.03    4605  309.21  4844.3  308.95  4856.8  309.25
  4956.7  311.49  4997.1  309.92  4999.4  307.47  5002.2  306.97  5005.4  307.47
  5020.9  311.83    5135  311.56  5234.8  326.05  5257.7  333.79  5307.3   340.8
  5312.7  344.97  5320.3  346.25  5362.3  338.63  5367.6  342.41  5384.5  341.43
  5422.6  351.33  5482.9  357.48  5562.7  361.04  5694.6  361.55  5751.6  359.56
#Mann= 7 ,-1 , 0
  3959.2     .16       0  4531.3     .12       0  4844.3     .16       0
  4856.8     .12       0  4999.4     .07       0  5005.4     .12       0
    5135     .16       0
Bank Sta=4997.1,5020.9
XS Rating Curve= 0 ,0
Exp/Cntr=0.3,0.1