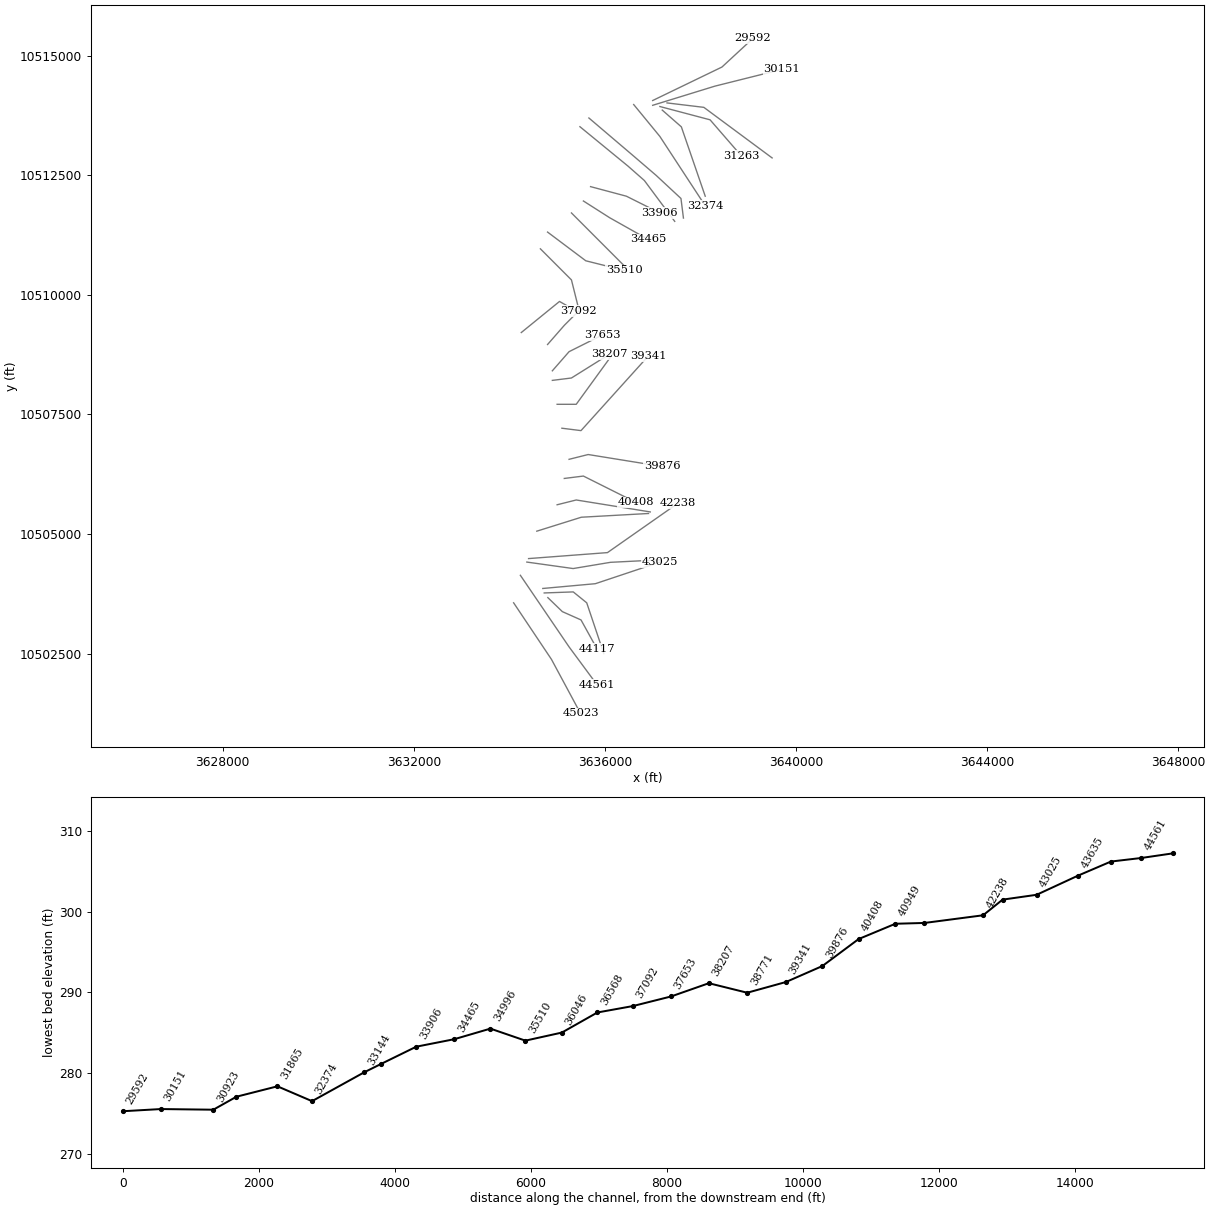
HEC-RAS study BLISS CREEK.prj: BLISS CREEK Base Level Engineering

--- BLISS CREEK.g01 (geometry) --- (continued)

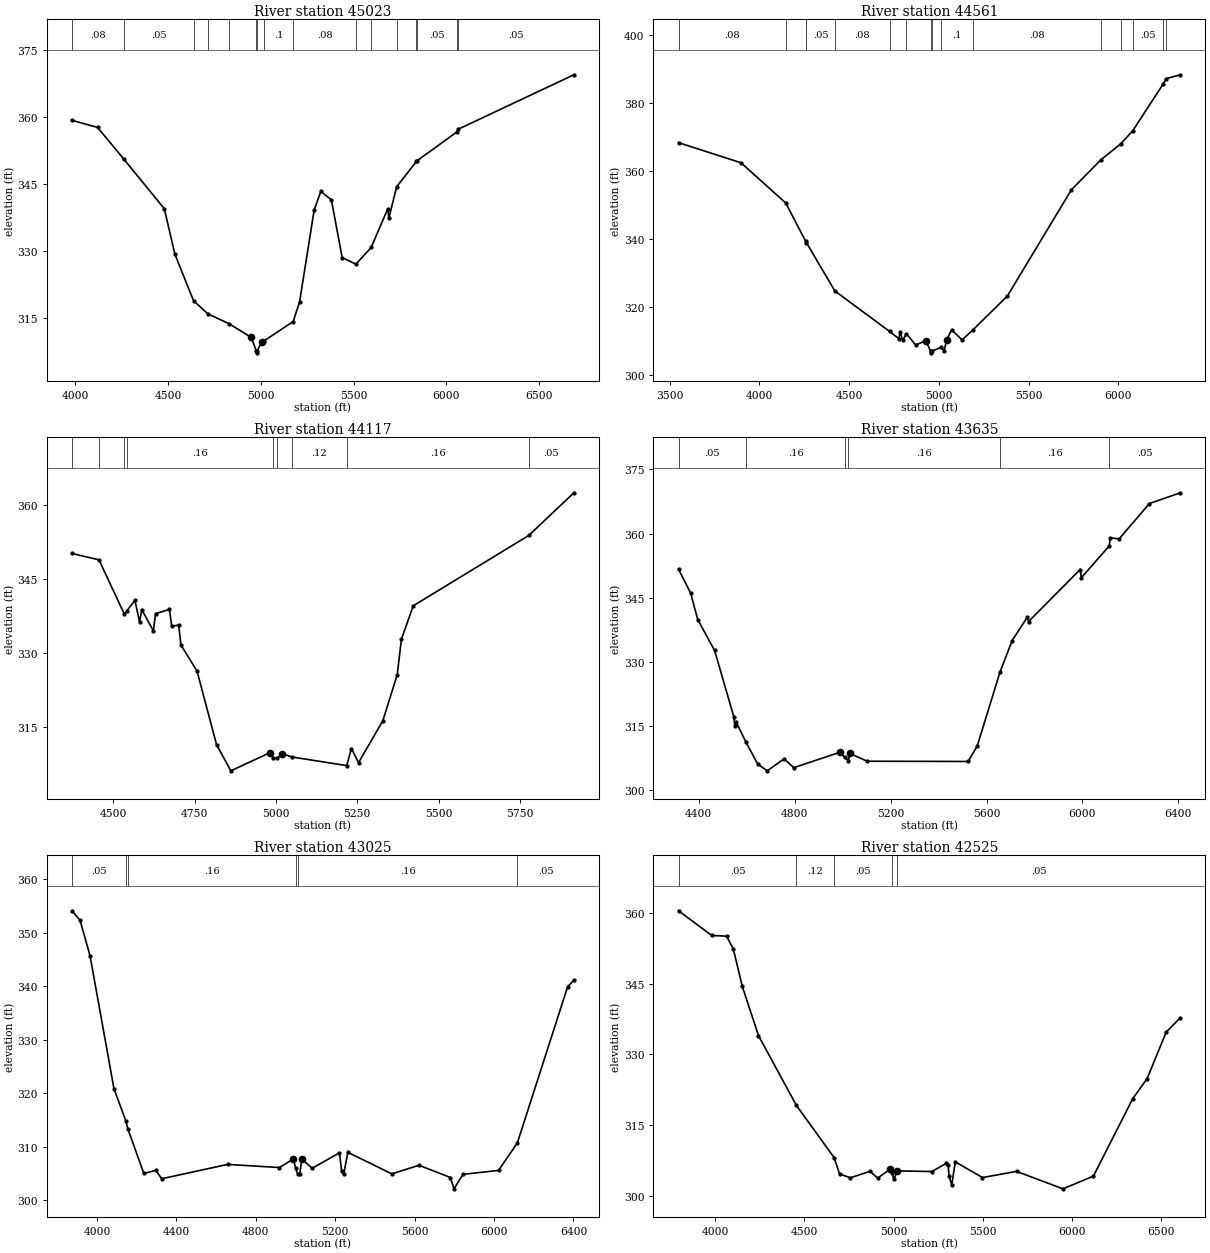
Type RM Length L Ch R = 1 ,45023   ,462,462,462
BEGIN DESCRIPTION:
BLISS CREEK 76.0
END DESCRIPTION:
XS GIS Cut Line= 3
      3634089.26     10503560.66      3634881.38      10502377.9
      3635489.03     10501249.41
#Sta/Elev= 30
  3982.6  359.25  4119.8  357.68  4260.2  350.65    4480  339.47  4537.1  329.27
  4637.5   318.9  4714.5  315.95  4829.6  313.74  4948.3  310.68  4975.4  307.73
  4978.1  307.23  4981.4  307.73  5006.2  309.75  5014.9  309.83  5174.8  314.24
  5209.5  318.69  5287.6  339.15  5323.6  343.37  5380.6  341.46  5438.6  328.55
  5512.7  327.07  5595.3  330.82  5684.4  339.46  5690.1  337.32  5732.5  344.39
  5839.2  350.07  5841.6  350.18  6059.9  356.74    6064  357.26  6687.8  369.45
#Mann= 16 ,-1 , 0
  3982.6     .08       0  4260.2     .05       0  4637.5     .08       0
  4714.5     .05       0  4829.6     .08       0  4975.4     .07       0
  4981.4     .08       0  5014.9      .1       0  5174.8     .08       0
  5512.7     .05       0  5595.3     .08       0  5732.5     .05       0
  5839.2     .08       0  5841.6     .05       0  6059.9     .16       0
    6064     .05       0
Bank Sta=4948.3,5006.2
XS Rating Curve= 0 ,0
Exp/Cntr=0.3,0.1

Type RM Length L Ch R = 1 ,44561   ,444,444,444
BEGIN DESCRIPTION:
BLISS CREEK 75.0
END DESCRIPTION:
XS GIS Cut Line= 3
      3634230.35     10504135.69       3635250.3     10502638.32
       3635835.4     10501847.35
#Sta/Elev= 30
  3550.2  368.46  3898.5  362.54  4147.6  350.71  4258.3  339.48  4263.1  339.02
    4421  324.86  4725.6  312.97  4778.1   310.8  4784.2  312.91  4799.1  310.37
  4820.2  312.28  4870.9  308.98  4927.8   310.2  4954.7  307.16  4957.4  306.66
  4960.7  307.16  5012.5  308.23  5029.5  307.28  5044.5  310.52  5071.5  313.45
  5129.8  310.47  5188.2  313.31  5382.1  323.35  5739.1  354.62  5904.6  363.48
  6014.1  368.13  6080.1  371.92  6251.3  385.79  6267.7   387.3  6345.8  388.42
#Mann= 16 ,-1 , 0
  3550.2     .08       0  4147.6     .05       0  4258.3     .08       0
  4263.1     .05       0    4421     .08       0  4725.6     .05       0
  4820.2     .08       0  4954.7     .07       0  4960.7     .08       0
  5012.5      .1       0  5188.2     .08       0  5904.6     .05       0
  6014.1     .08       0  6080.1     .05       0  6251.3     .08       0
  6267.7     .05       0
Bank Sta=4927.8,5044.5
XS Rating Curve= 0 ,0
Exp/Cntr=0.3,0.1

Type RM Length L Ch R = 1 ,44117   ,482,482,482
BEGIN DESCRIPTION:
BLISS CREEK 74.0
END DESCRIPTION:
XS GIS Cut Line= 4
      3634805.39     10503669.16      3635109.24     10503376.16
      3635499.87     10503202.55      3635835.36     10502596.49
#Sta/Elev= 30
  4373.6  350.21  4456.3  348.93    4534  337.96  4542.7  338.65  4566.8  340.73
    4581  336.38  4587.9  338.85  4623.4  334.54  4630.3  338.04  4672.8  338.89
    4680   335.5  4701.1  335.71  4708.3  331.69  4757.7   326.4  4817.6  311.54
  4861.5  306.22  4982.1  309.91  4991.4  308.86    5004  308.77  5020.1  309.67
  5048.8  309.03  5217.7  307.28  5232.3  310.73    5254  307.87  5328.7  316.35
  5373.1   325.7  5385.9  332.87  5422.3  339.63  5777.5  353.87  5915.9   362.5
#Mann= 9 ,-1 , 0
  4373.6     .05       0  4456.3     .16       0    4534     .05       0
  4542.7     .16       0  4991.4     .07       0    5004     .16       0
  5048.8     .12       0  5217.7     .16       0  5777.5     .05       0
Bank Sta=4982.1,5020.1
XS Rating Curve= 0 ,0
Exp/Cntr=0.3,0.1

Type RM Length L Ch R = 1 ,43635   ,610,610,610
BEGIN DESCRIPTION:
BLISS CREEK 73.0
END DESCRIPTION:
XS GIS Cut Line= 4
      3634729.45     10503766.79      3635337.11     10503788.49
      3635619.22     10503560.63      3635977.29     10502497.28
#Sta/Elev= 30
  4315.6  351.65  4365.8   346.1  4395.8  339.85  4465.9  332.65  4545.9  317.18
  4550.9  314.88  4555.9  315.89    4597  311.17    4646  306.06  4685.7  304.48
    4756   307.3  4796.1  305.22  4988.6  308.82  5009.4  307.61  5023.8  306.86
  5030.3  308.55  5102.2  306.73  5523.3  306.67  5561.1  310.26  5656.1  327.56
    5707  334.97    5770  340.42  5775.3   339.4  5990.5  351.58  5995.8  349.68
  6111.5  357.07  6116.5  358.98  6153.2  358.75  6279.2  367.01  6408.3  369.53
#Mann= 6 ,-1 , 0
  4315.6     .05       0    4597     .16       0  5009.4     .07       0
  5023.8     .16       0  5656.1     .16       0  6111.5     .05       0
Bank Sta=4988.6,5030.3
XS Rating Curve= 0 ,0
Exp/Cntr=0.3,0.1

Type RM Length L Ch R = 1 ,43025   ,500,500,500
BEGIN DESCRIPTION:
BLISS CREEK 72.0
END DESCRIPTION:
XS GIS Cut Line= 3
      3634699.62     10503860.19      3635799.61     10503960.19
      3637149.56     10504410.17
#Sta/Elev= 30
  3874.5  354.13  3914.7  352.34  3964.9  345.73  4085.4  320.86  4145.6  314.79
  4155.3  313.33    4236  304.98  4296.2  305.55  4326.3  303.99  4657.7  306.67
  4918.8  306.09  4989.6   307.7  5000.1  305.99  5010.6  304.93  5021.2  304.86
  5031.7  307.66  5084.4  305.96  5221.5  308.84    5232  305.48  5242.5  304.85
  5263.6  308.93    5485   304.9    5622  306.51  5780.1  304.22  5798.2   302.1
  5843.4  304.81  6022.6  305.54  6117.4   310.7  6370.4  339.88    6402  341.15
#Mann= 6 ,-1 , 0
  3874.5     .05       0  4145.6     .16       0  4155.3     .16       0
  5000.1     .05       0  5010.6     .16       0  6117.4     .05       0
Bank Sta=4989.6,5031.7
XS Rating Curve= 0 ,0
Exp/Cntr=0.3,0.1

Type RM Length L Ch R = 1 ,42525   ,287,287,287
BEGIN DESCRIPTION:
BLISS CREEK 71.0
END DESCRIPTION:
XS GIS Cut Line= 4
      3634365.92     10504412.19      3635334.65     10504276.77
       3636115.9     10504406.98      3637156.12     10504458.99
#Sta/Elev= 30
  3794.6  360.44  3980.1  355.22  4063.9  355.05  4101.2   352.4  4151.7  344.43
  4242.6  333.98  4454.6  319.21  4666.7   308.1    4697  304.66  4757.6  303.84
    4869  305.23  4909.6  303.76  4980.5  305.66  4990.7  304.91  5000.8  303.53
  5021.1  305.31  5213.7  305.17  5294.8  306.89    5305  306.59  5310.3  304.28
  5325.2  302.28  5345.5  307.22  5497.8  303.89  5688.6   305.2  5948.7   301.5
  6119.2  304.19  6339.5   320.6  6419.6  324.83  6527.4  334.74  6606.3  337.77
#Mann= 5 ,-1 , 0
  3794.6     .05       0  4454.6     .12       0  4666.7     .05       0
  4990.7     .07       0  5021.1     .05       0
Bank Sta=4980.5,5021.1
XS Rating Curve= 0 ,0
Exp/Cntr=0.3,0.1

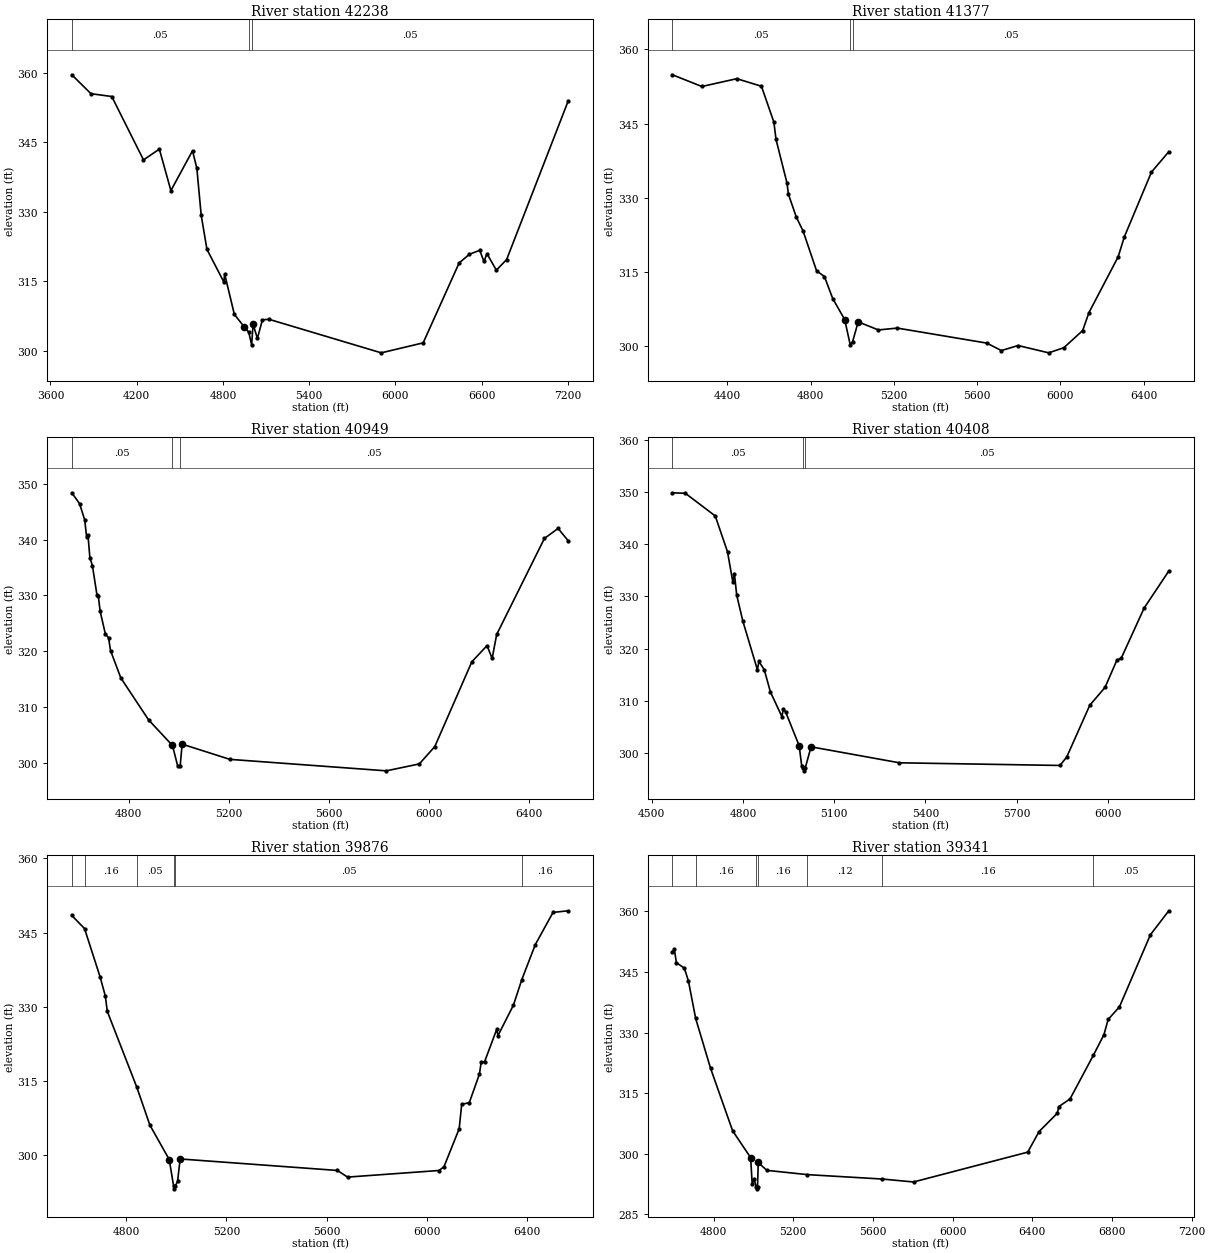
Type RM Length L Ch R = 1 ,42238   ,861,861,861
BEGIN DESCRIPTION:
BLISS CREEK 70.0
END DESCRIPTION:
XS GIS Cut Line= 3
      3634402.33      10504485.1       3636053.4      10504610.1
      3637525.97     10505640.38
#Sta/Elev= 30
  3748.9  359.56    3882  355.48    4027  354.87  4247.6  341.19  4357.9  343.52
  4438.2  334.57  4588.6  343.16  4618.7  339.38  4648.8  329.28  4688.9  321.89
    4807  314.81    4812   316.6  4879.4  307.87  4949.6  305.12  4979.7  304.01
  4999.8  301.29  5009.8  305.72  5039.9  302.67  5074.8  306.68  5120.1   306.8
  5901.3  299.56  6192.9  301.71  6443.2  318.96  6514.7  320.83  6586.2  321.68
  6615.8  319.28  6636.7  320.94  6702.1  317.39  6773.6   319.7  7201.9  353.93
#Mann= 3 ,-1 , 0
  3748.9     .05       0  4979.7     .03       0  4999.8     .05       0
Bank Sta=4949.6,5009.8
XS Rating Curve= 0 ,0
Exp/Cntr=0.3,0.1

Type RM Length L Ch R = 1 ,41377   ,428,428,428
BEGIN DESCRIPTION:
BLISS CREEK 69.0
END DESCRIPTION:
XS GIS Cut Line= 3
      3634574.25     10505058.03      3635506.52     10505349.69
      3636912.72     10505427.81
#Sta/Elev= 30
  4135.4  354.86  4277.2  352.49  4444.9  354.07  4563.3  352.54    4623   345.3
  4633.5  341.77  4685.9     333  4693.2  330.67  4730.9  326.07  4763.3  323.27
  4828.3   315.2    4866  314.05  4905.9  309.59  4963.4  305.34  4989.7  300.28
  5001.1  300.84  5028.3  304.88  5125.3  303.24  5215.9  303.62  5646.1  300.58
  5716.2  299.07  5796.4  300.09  5943.6  298.61  6016.7  299.66  6106.8  303.12
  6136.9  306.74  6277.1  318.02  6307.2  322.09  6437.4  335.18  6520.6   339.3
#Mann= 3 ,-1 , 0
  4135.4     .05       0  4989.7     .03       0  5001.1     .05       0
Bank Sta=4963.4,5028.3
XS Rating Curve= 0 ,0
Exp/Cntr=0.3,0.1

Type RM Length L Ch R = 1 ,40949   ,541,541,541
BEGIN DESCRIPTION:
BLISS CREEK 68.0
END DESCRIPTION:
XS GIS Cut Line= 3
      3634999.58     10505610.18      3635399.61     10505710.19
      3636949.64     10505460.18
#Sta/Elev= 30
  4573.3  348.41  4604.2  346.46  4624.9  343.54  4632.6  340.39  4637.7  340.89
  4645.5  336.79  4655.8  335.28  4673.8  330.06    4679  329.89  4686.7  327.12
  4707.3  323.07  4720.2  322.38  4727.9   320.1  4769.2  315.17    4880  307.65
  4975.3  303.06  4995.8  299.44  5005.9  299.31    5014   303.3  5204.4  300.57
  5829.4  298.51  5961.1  299.75  6022.9  302.87  6170.8  318.08  6231.5  320.99
  6251.8  318.68    6270  322.98  6460.5  340.21  6515.2  342.01  6555.7  339.79
#Mann= 3 ,-1 , 0
  4573.3     .05       0  4975.3     .03       0  5005.9     .05       0
Bank Sta=4975.3,5014
XS Rating Curve= 0 ,0
Exp/Cntr=0.3,0.1

Type RM Length L Ch R = 1 ,40408   ,532,532,532
BEGIN DESCRIPTION:
BLISS CREEK 67.0
END DESCRIPTION:
XS GIS Cut Line= 3
       3635149.6     10506160.19      3635549.61     10506210.19
      3636649.65     10505660.17
#Sta/Elev= 30
  4567.6  349.86  4610.4  349.76  4708.7  345.42    4749  338.55  4766.6  332.75
  4771.7  334.39  4779.2  330.26  4799.4  325.29  4847.3  315.97  4852.3  317.56
  4869.9  315.97  4890.1  311.72  4927.9     307  4932.9   308.5  4940.5  307.84
  4984.7  301.42  4993.1  297.55  4998.5  297.11  5001.2  296.61  5004.5  297.11
  5023.8  301.21  5314.5  298.15  5842.8  297.64  5865.1  299.29  5940.6  309.16
  5990.9   312.6  6030.1  317.84    6044  318.16  6119.5  327.79  6200.6  334.87
#Mann= 3 ,-1 , 0
  4567.6     .05       0  4998.5     .03       0  5004.5     .05       0
Bank Sta=4984.7,5023.8
XS Rating Curve= 0 ,0
Exp/Cntr=0.3,0.1

Type RM Length L Ch R = 1 ,39876   ,535,535,535
BEGIN DESCRIPTION:
BLISS CREEK 66.0
END DESCRIPTION:
XS GIS Cut Line= 3
       3635249.6     10506560.19      3635649.61     10506660.19
      3637199.56      10506410.2
#Sta/Elev= 30
  4582.4  348.44  4633.3  345.79  4695.8  335.98  4716.4  332.16  4724.1  329.09
  4841.9  313.79  4894.2  306.13  4971.5  299.18  4989.1  293.77  4991.9  293.27
  4995.1  293.77  5004.8  294.78    5015   299.3    5643  296.98  5683.5  295.64
  6048.2  296.97  6068.4  297.71  6129.2  305.39  6139.3  310.31  6169.7  310.67
  6210.2  316.44  6217.3   318.9  6230.5   318.9  6279.1  325.45  6284.2   324.2
    6346  330.36  6379.3  335.49  6433.1  342.55    6504  349.06  6564.7  349.39
#Mann= 6 ,-1 , 0
  4582.4     .05       0  4633.3     .16       0  4841.9     .05       0
  4989.1     .03       0  4995.1     .05       0  6379.3     .16       0
Bank Sta=4971.5,5015
XS Rating Curve= 0 ,0
Exp/Cntr=0.3,0.1

Type RM Length L Ch R = 1 ,39341   ,570,570,570
BEGIN DESCRIPTION:
BLISS CREEK 65.0
END DESCRIPTION:
XS GIS Cut Line= 3
      3635099.65     10507210.18      3635499.61     10507160.19
      3636899.59     10508710.17
#Sta/Elev= 30
  4593.2     350  4603.2  350.61  4613.3  347.32  4653.6  345.93  4673.8  342.77
  4710.1   333.5  4784.6  321.19  4895.5  305.68  4986.2  299.01  4993.8  292.48
  5003.4  293.63  5014.6  291.79  5017.3  291.29  5020.6  291.79  5024.3  297.82
  5066.9  295.87  5270.8  294.81    5646  293.72  5803.7  292.99  6376.9  300.38
  6433.7  305.47  6525.6  310.03  6532.4  311.65  6589.1  313.55  6706.1  324.35
  6759.5  329.49  6780.4  333.24  6837.2  336.36  6992.6  354.22  7084.9  360.16
#Mann= 7 ,-1 , 0
  4593.2     .05       0  4710.1     .16       0  5014.6     .07       0
  5020.6     .16       0  5270.8     .12       0    5646     .16       0
  6706.1     .05       0
Bank Sta=4986.2,5024.3
XS Rating Curve= 0 ,0
Exp/Cntr=0.3,0.1

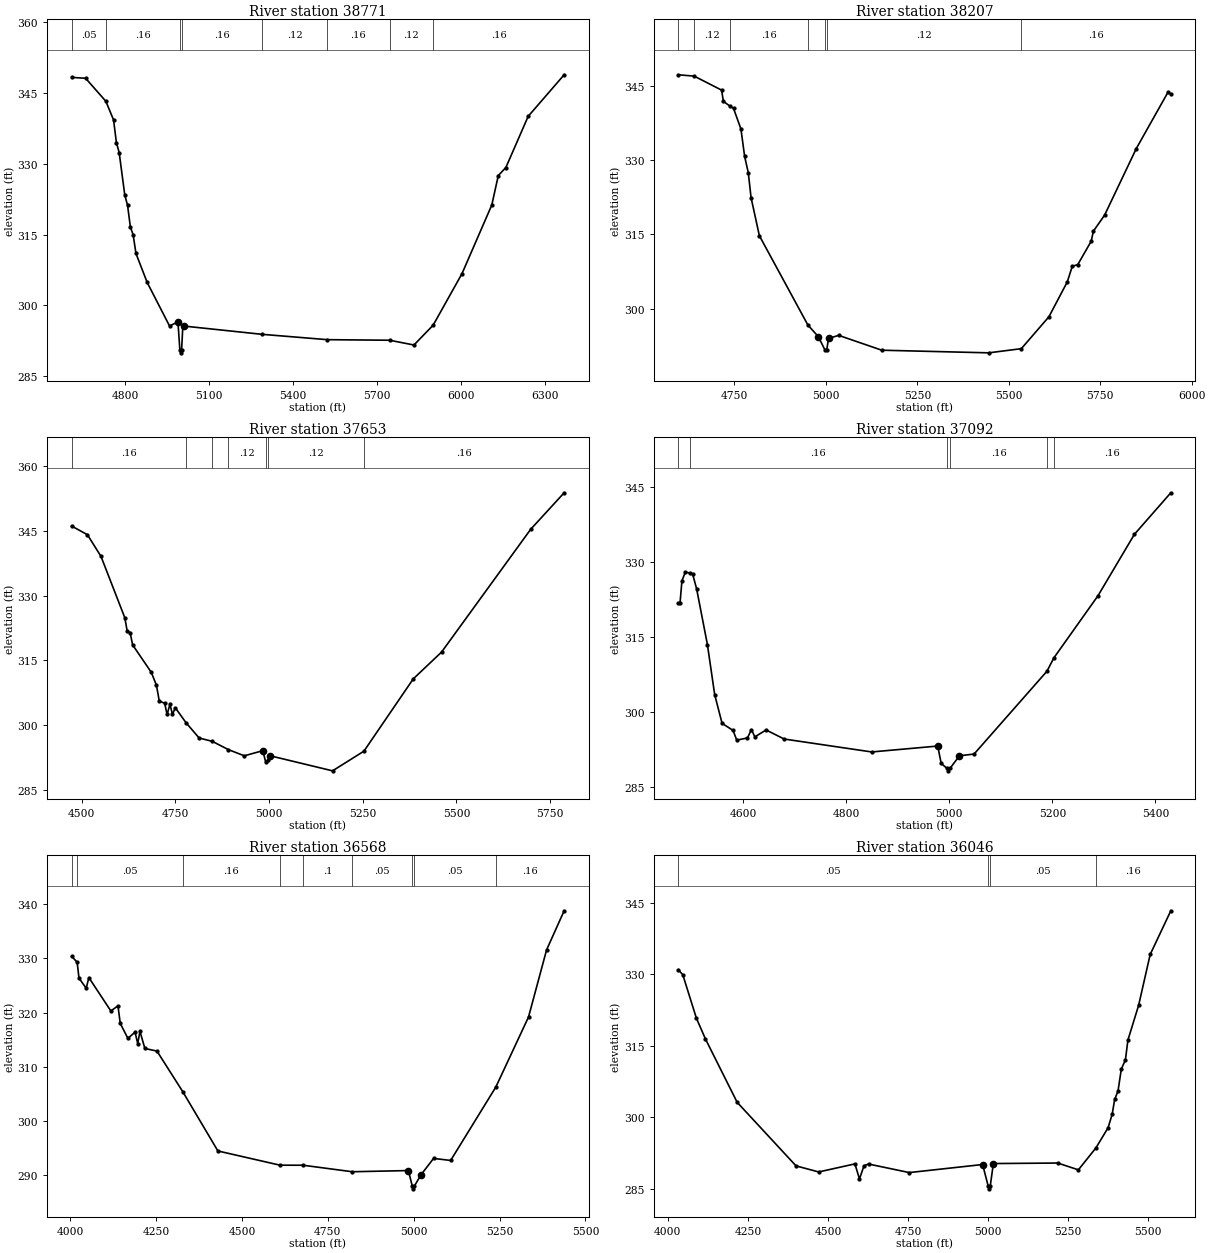
Type RM Length L Ch R = 1 ,38771   ,564,564,564
BEGIN DESCRIPTION:
BLISS CREEK 64.0
END DESCRIPTION:
XS GIS Cut Line= 3
      3634999.61     10507710.19      3635399.61     10507710.19
      3636199.58     10508810.15
#Sta/Elev= 30
  4608.7  348.32  4658.7  348.13  4731.2  343.25  4758.7  339.29  4768.7  334.52
  4778.7  332.39  4798.7  323.39  4808.7  321.19  4818.7  316.63  4828.7  314.94
  4838.7  311.01  4878.7  304.88  4958.7  295.65  4988.7  296.51  4995.7  290.46
  4998.4  289.96  5001.7  290.46  5006.2  295.64  5008.7  295.64  5287.9  293.89
  5522.6  292.75  5744.8  292.63  5832.1  291.62  5900.7  295.82  6003.7  306.73
  6110.3  321.28  6133.5  327.52  6160.6  329.22  6240.2  340.06  6368.8  348.87
#Mann= 8 ,-1 , 0
  4608.7     .05       0  4731.2     .16       0  4995.7     .07       0
  5001.7     .16       0  5287.9     .12       0  5522.6     .16       0
  5744.8     .12       0  5900.7     .16       0
Bank Sta=4988.7,5008.7
XS Rating Curve= 0 ,0
Exp/Cntr=0.3,0.1

Type RM Length L Ch R = 1 ,38207   ,554,554,554
BEGIN DESCRIPTION:
BLISS CREEK 63.0
END DESCRIPTION:
XS GIS Cut Line= 3
      3634899.65     10508210.19      3635299.61     10508260.19
      3636099.63      10508760.2
#Sta/Elev= 30
  4596.5  347.17    4640   346.9  4714.9  344.08  4719.9   341.8  4739.1  340.79
  4747.6  340.38  4767.8  336.25  4777.9  330.72  4787.9  327.44  4795.5  322.41
  4818.2  314.74  4950.8  296.75  4979.4   294.4  4997.1  291.77  5002.5  291.77
  5007.2  294.04    5035  294.66  5152.9  291.67  5445.3  291.14  5534.3  291.98
  5609.8  298.41    5660  305.44  5673.5  308.55  5688.8  308.94  5725.4  313.64
  5731.3  315.65    5762  318.89  5848.6   332.3  5935.3  343.66    5943  343.29
#Mann= 7 ,-1 , 0
  4596.5     .05       0    4640     .12       0  4739.1     .16       0
  4950.8     .12       0  4997.1     .07       0  5002.5     .12       0
  5534.3     .16       0
Bank Sta=4979.4,5007.2
XS Rating Curve= 0 ,0
Exp/Cntr=0.3,0.1

Type RM Length L Ch R = 1 ,37653   ,561,561,561
BEGIN DESCRIPTION:
BLISS CREEK 62.0
END DESCRIPTION:
XS GIS Cut Line= 3
      3634899.62      10508410.2      3635249.61     10508810.19
      3635949.59     10509160.18
#Sta/Elev= 30
  4473.3  346.06  4515.5  344.05  4551.6  339.06  4615.2  324.88  4621.8  321.72
  4629.4  321.46  4636.1   318.6  4685.9  312.26  4699.7  309.26  4707.2  305.62
  4721.5  305.12  4728.1  302.52  4735.7  304.88  4742.4  302.55    4750  304.07
  4778.4  300.64  4813.5  297.09  4848.7  296.31  4891.4  294.41  4934.1  292.97
  4983.4  294.16    4991  291.58  4997.7  291.89  5001.5  293.01  5169.5   289.5
  5253.2  294.04  5384.9  310.75  5460.4  316.94    5698  345.29  5787.4  353.74
#Mann= 7 ,-1 , 0
  4473.3     .16       0  4778.4     .12       0  4848.7     .16       0
  4891.4     .12       0    4991     .07       0  4997.7     .12       0
  5253.2     .16       0
Bank Sta=4983.4,5001.5
XS Rating Curve= 0 ,0
Exp/Cntr=0.3,0.1

Type RM Length L Ch R = 1 ,37092   ,524,524,524
BEGIN DESCRIPTION:
BLISS CREEK 61.0
END DESCRIPTION:
XS GIS Cut Line= 3
      3634799.59     10508960.17      3635149.61     10509360.19
      3635449.61     10509660.19
#Sta/Elev= 30
  4474.1  321.82  4477.5  321.82  4481.2  326.25  4487.9  328.01  4496.3  327.79
  4502.1  327.54  4509.7  324.64  4530.6  313.53  4544.8   303.5  4559.1  297.79
  4580.4  296.38  4587.5  294.45  4608.4  294.87    4616  296.55  4622.7  295.09
  4644.5  296.47  4679.6  294.66  4849.5  292.08  4977.6  293.26  4984.3  289.79
  4995.5  288.81  4998.3  288.31  5001.5  288.81  5019.8  291.32  5048.1  291.66
  5189.5  308.19  5203.1  310.88  5288.5  323.25  5359.2  335.52  5429.9  343.82
#Mann= 6 ,-1 , 0
  4474.1     .08       0  4496.3     .16       0  4995.5     .07       0
  5001.5     .16       0  5189.5     .05       0  5203.1     .16       0
Bank Sta=4977.6,5019.8
XS Rating Curve= 0 ,0
Exp/Cntr=0.3,0.1

Type RM Length L Ch R = 1 ,36568   ,522,522,522
BEGIN DESCRIPTION:
BLISS CREEK 60.0
END DESCRIPTION:
XS GIS Cut Line= 3
      3634249.62      10509210.2      3635049.61     10509860.19
      3635399.63     10509660.18
#Sta/Elev= 30
  4004.2  330.37  4020.3  329.29  4025.7  326.34  4046.6  324.49  4054.5  326.44
  4118.4   320.3  4139.2  321.23  4145.9  317.99    4168  315.25  4188.8  316.38
  4196.7  314.29  4203.2  316.54  4217.5  313.38  4252.7   312.9  4327.5  305.45
  4430.1  294.49  4610.9  291.87  4678.3  291.86  4821.4  290.66  4984.7  290.88
    4996  288.01  4998.8  287.51    5002  288.01  5021.3  290.09    5058  293.12
  5107.7  292.74  5239.3  306.28  5334.4  319.18    5387  331.55  5438.1  338.76
#Mann= 9 ,-1 , 0
  4004.2     .16       0  4020.3     .05       0  4327.5     .16       0
  4610.9     .05       0  4678.3      .1       0  4821.4     .05       0
    4996     .03       0    5002     .05       0  5239.3     .16       0
Bank Sta=4984.7,5021.3
XS Rating Curve= 0 ,0
Exp/Cntr=0.3,0.1

Type RM Length L Ch R = 1 ,36046   ,536,536,536
BEGIN DESCRIPTION:
BLISS CREEK 59.0
END DESCRIPTION:
XS GIS Cut Line= 3
      3634649.61     10510960.18      3635299.61     10510310.19
      3635449.61     10509710.19
#Sta/Elev= 30
  4032.5  330.95  4046.6   329.9  4089.1  320.78  4117.3  316.44  4216.3  303.16
  4400.2  289.83  4470.9  288.56    4584  290.25  4598.2  287.08  4612.3  289.86
  4626.5  290.22  4753.7  288.43  4982.7  290.12  5000.3  285.52    5003  285.02
  5006.3  285.52  5016.2  290.32  5217.2  290.43  5281.6     289  5336.3  293.59
  5374.4  297.83  5387.2  300.67    5395   303.8  5405.3  305.49  5415.6   310.1
  5428.5  312.06  5436.2  316.18  5469.7  323.49  5505.8  334.15  5570.2  343.31
#Mann= 4 ,-1 , 0
  4032.5     .05       0  5000.3     .03       0  5006.3     .05       0
  5336.3     .16       0
Bank Sta=4982.7,5016.2
XS Rating Curve= 0 ,0
Exp/Cntr=0.3,0.1

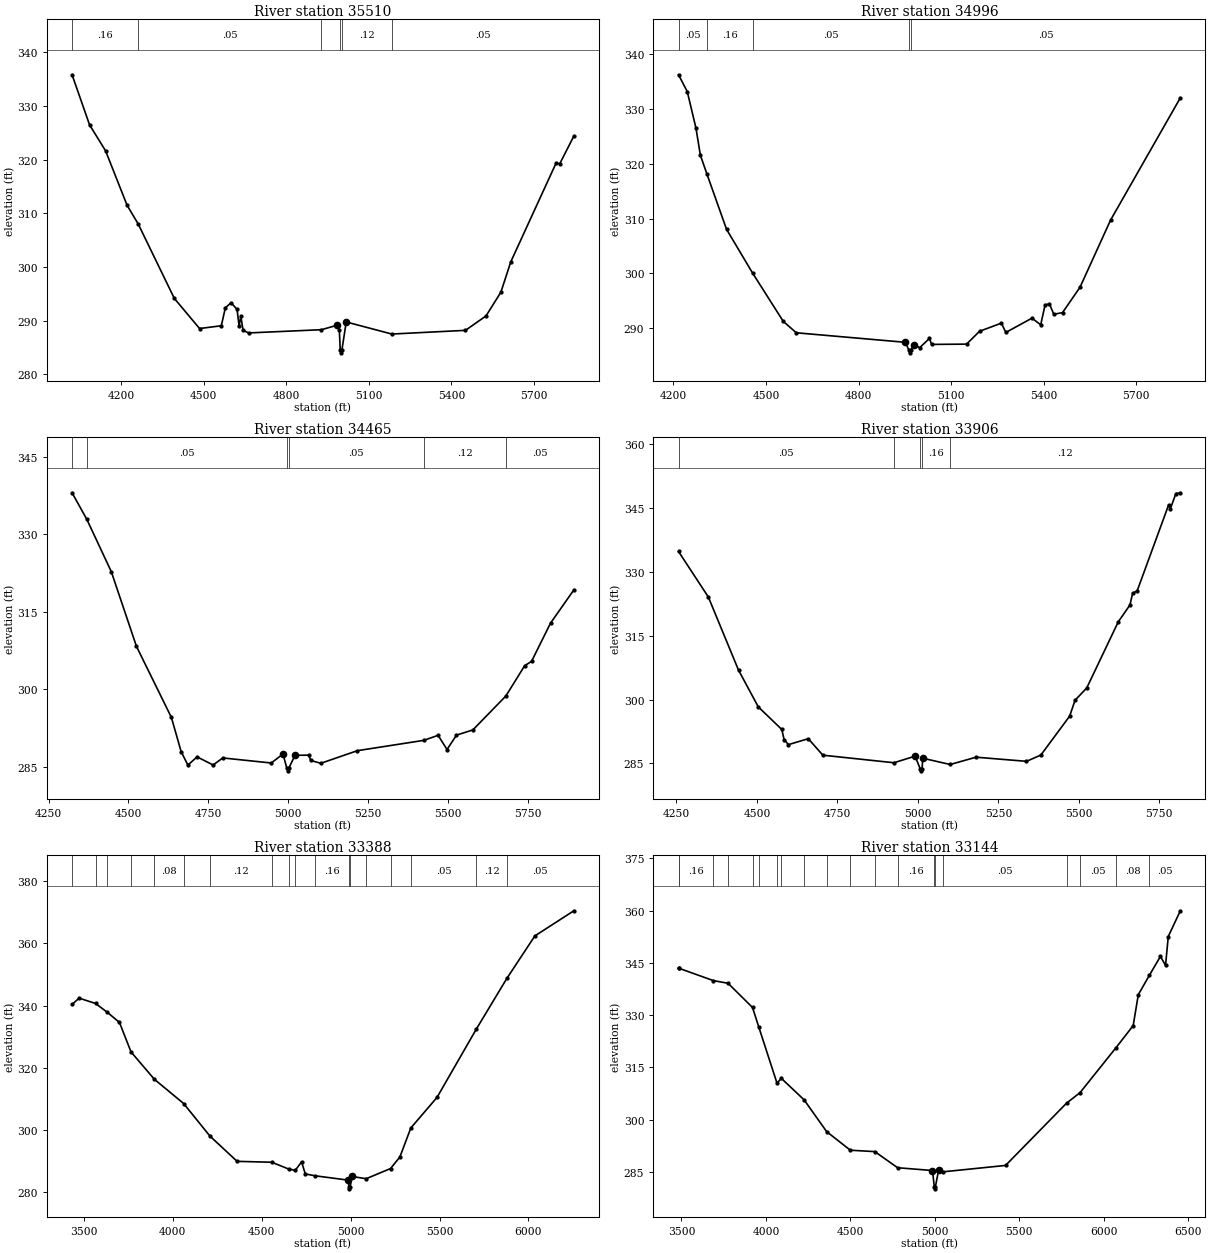
Type RM Length L Ch R = 1 ,35510   ,514,514,514
BEGIN DESCRIPTION:
BLISS CREEK 58.0
END DESCRIPTION:
XS GIS Cut Line= 3
       3634799.6      10511310.2      3635599.61     10510710.19
      3636399.57      10510510.2
#Sta/Elev= 30
    4021  335.81  4084.6  326.48  4142.9  321.64    4221  311.51  4261.6  308.01
  4392.9  294.15  4484.6  288.55  4563.7  289.06  4578.3   292.4  4599.1  293.35
    4621  292.11  4628.3  288.99  4634.6  290.87  4642.9  288.19  4663.7  287.73
  4927.9  288.33  4984.6  289.16  4992.9  288.19  4996.1  284.52  4998.9  284.02
  5002.1  284.52  5017.9  289.77  5183.7  287.52  5451.4  288.21  5526.1  290.89
  5580.2  295.31  5616.3  300.98  5781.2  319.39  5794.1  319.21  5845.6   324.4
#Mann= 6 ,-1 , 0
    4021     .16       0  4261.6     .05       0  4927.9     .12       0
  4996.1     .07       0  5002.1     .12       0  5183.7     .05       0
Bank Sta=4984.6,5017.9
XS Rating Curve= 0 ,0
Exp/Cntr=0.3,0.1

Type RM Length L Ch R = 1 ,34996   ,531,531,531
BEGIN DESCRIPTION:
BLISS CREEK 57.0
END DESCRIPTION:
XS GIS Cut Line= 3
      3635299.61     10511710.19      3635849.61     10511160.19
      3636449.57     10510560.22
#Sta/Elev= 30
  4216.4  336.25  4244.7  333.18    4273  326.49  4287.1  321.59  4308.3  318.16
    4372  308.05  4456.5  300.06  4555.8  291.25  4598.2  289.17  4951.8  287.43
  4962.9  286.01  4965.7  285.51  4968.9  286.01  4980.1  287.03  4997.8  286.44
  5029.6  288.14  5036.6  287.05  5149.8   287.1  5192.2  289.45  5262.9  290.93
  5277.1  289.23  5361.9  291.84  5390.2  290.62  5404.3  294.25  5418.5  294.45
  5432.6  292.55  5460.9  292.85  5517.5  297.47  5616.5  309.72  5842.7  332.04
#Mann= 5 ,-1 , 0
  4216.4     .05       0  4308.3     .16       0  4456.5     .05       0
  4962.9     .03       0  4968.9     .05       0
Bank Sta=4951.8,4980.1
XS Rating Curve= 0 ,0
Exp/Cntr=0.3,0.1

Type RM Length L Ch R = 1 ,34465   ,559,559,559
BEGIN DESCRIPTION:
BLISS CREEK 56.0
END DESCRIPTION:
XS GIS Cut Line= 3
      3635549.64     10511960.17      3636099.61     10511610.19
      3636899.64     10511160.17
#Sta/Elev= 30
  4323.5  338.08  4369.6  332.94  4446.2   322.8    4525  308.31  4634.2  294.55
  4664.7  287.93  4685.8  285.31  4714.6  286.91  4764.6  285.33  4795.1   286.7
  4946.6  285.72  4983.4  287.46  4995.3   284.7  4998.1   284.2  5001.3   284.7
    5021  287.21  5064.3  287.24    5070  286.22  5101.6  285.66  5216.3  288.11
  5423.2   290.1  5468.7  291.08  5496.5  288.33  5526.1  291.12  5577.4  292.13
  5680.7  298.71  5739.3  304.56    5761  305.42  5820.3  312.82  5893.3  319.26
#Mann= 6 ,-1 , 0
  4323.5     .16       0  4369.6     .05       0  4995.3     .03       0
  5001.3     .05       0  5423.2     .12       0  5680.7     .05       0
Bank Sta=4983.4,5021
XS Rating Curve= 0 ,0
Exp/Cntr=0.3,0.1

Type RM Length L Ch R = 1 ,33906   ,518,518,518
BEGIN DESCRIPTION:
BLISS CREEK 55.0
END DESCRIPTION:
XS GIS Cut Line= 3
      3635699.61     10512260.19      3636449.61     10512060.19
      3637149.58      10511710.2
#Sta/Elev= 30
  4256.6  334.72  4349.1  324.05  4442.9   306.9  4504.3  298.28  4577.4  292.97
  4584.5  290.62  4598.1  289.42  4659.6  290.81  4704.9  286.94  4925.7  285.17
  4991.4  286.71  5007.2  283.77  5009.9  283.27  5013.2  283.77  5015.3  286.23
  5100.4  284.76  5180.9  286.47  5337.5   285.5  5382.2  286.98  5471.6   296.1
  5488.4  299.83  5524.7  302.71  5622.6  318.22  5658.9  322.17  5667.3  324.93
  5681.3  325.48  5779.1  345.65  5784.7  344.79  5801.5  348.29  5815.4  348.49
#Mann= 5 ,-1 , 0
  4256.6     .05       0  4925.7     .16       0  5007.2     .07       0
  5013.2     .16       0  5100.4     .12       0
Bank Sta=4991.4,5015.3
XS Rating Curve= 0 ,0
Exp/Cntr=0.3,0.1

Type RM Length L Ch R = 1 ,33388   ,244,244,244
BEGIN DESCRIPTION:
BLISS CREEK 54.0
END DESCRIPTION:
XS GIS Cut Line= 4
      3635477.02     10513512.87      3636482.22     10512689.97
      3636825.97     10512387.88      3637460.85     10511534.43
#Sta/Elev= 30
  3434.7  340.36  3474.4  342.38  3566.6  340.67  3633.3  337.81  3701.2  334.57
    3766  325.11  3897.3  316.32  4061.7  308.54  4209.5  298.08  4362.3  289.96
  4557.3  289.67  4653.1  287.47  4689.3  287.09  4724.7  289.78  4745.6  285.92
  4798.4  285.34  4986.6  283.93  4991.2  281.63    4994  281.13  4997.2  281.63
  5008.5   285.1  5087.7  284.38    5225  287.66  5277.4  291.38  5338.6  300.67
  5486.1  310.51  5707.8  332.53  5878.5  348.72    6036  362.37  6255.1  370.44
#Mann= 18 ,-1 , 0
  3434.7     .08       0  3566.6     .05       0  3633.3     .08       0
    3766     .05       0  3897.3     .08       0  4061.7     .05       0
  4209.5     .12       0  4557.3     .16       0  4653.1     .08       0
  4689.3     .05       0  4798.4     .16       0  4991.2     .07       0
  4997.2     .16       0  5087.7     .12       0    5225     .16       0
  5338.6     .05       0  5707.8     .12       0  5878.5     .05       0
Bank Sta=4986.6,5008.5
XS Rating Curve= 0 ,0
Exp/Cntr=0.3,0.1

Type RM Length L Ch R = 1 ,33144   ,770,770,770
BEGIN DESCRIPTION:
BLISS CREEK 53.0
END DESCRIPTION:
XS GIS Cut Line= 5
       3635664.5     10513695.18      3636602.01      10512898.3
      3637075.97     10512492.05      3637591.59     10512012.88
      3637643.44     10511603.31
#Sta/Elev= 30
  3482.6  343.48  3486.2  343.43  3688.8  339.91  3775.9  339.14  3920.7  332.19
  3957.2  326.67  4065.5  310.48  4091.5  311.83  4225.7  305.69  4359.9  296.53
  4500.1   291.2  4644.9   290.8    4780  286.17  4986.4  285.37  4997.3  280.61
    5000  280.11  5003.3  280.61  5022.2  285.39  5051.3  285.01  5419.1  286.83
    5780   304.7  5860.4  307.75  6073.1  320.64  6174.9  326.99  6205.1  335.86
  6271.2  341.47  6336.2  346.86  6366.4  344.26  6382.6  352.57    6454  359.96
#Mann= 20 ,-1 , 0
  3482.6     .05       0  3486.2     .16       0  3688.8     .05       0
  3775.9     .16       0  3920.7     .05       0  3957.2     .16       0
  4065.5     .05       0  4091.5     .16       0  4225.7     .16       0
  4359.9     .16       0  4500.1     .05       0  4644.9     .05       0
    4780     .16       0  4997.3     .07       0  5003.3     .16       0
  5051.3     .05       0    5780     .08       0  5860.4     .05       0
  6073.1     .08       0  6271.2     .05       0
Bank Sta=4986.4,5022.2
XS Rating Curve= 0 ,0
Exp/Cntr=0.3,0.1

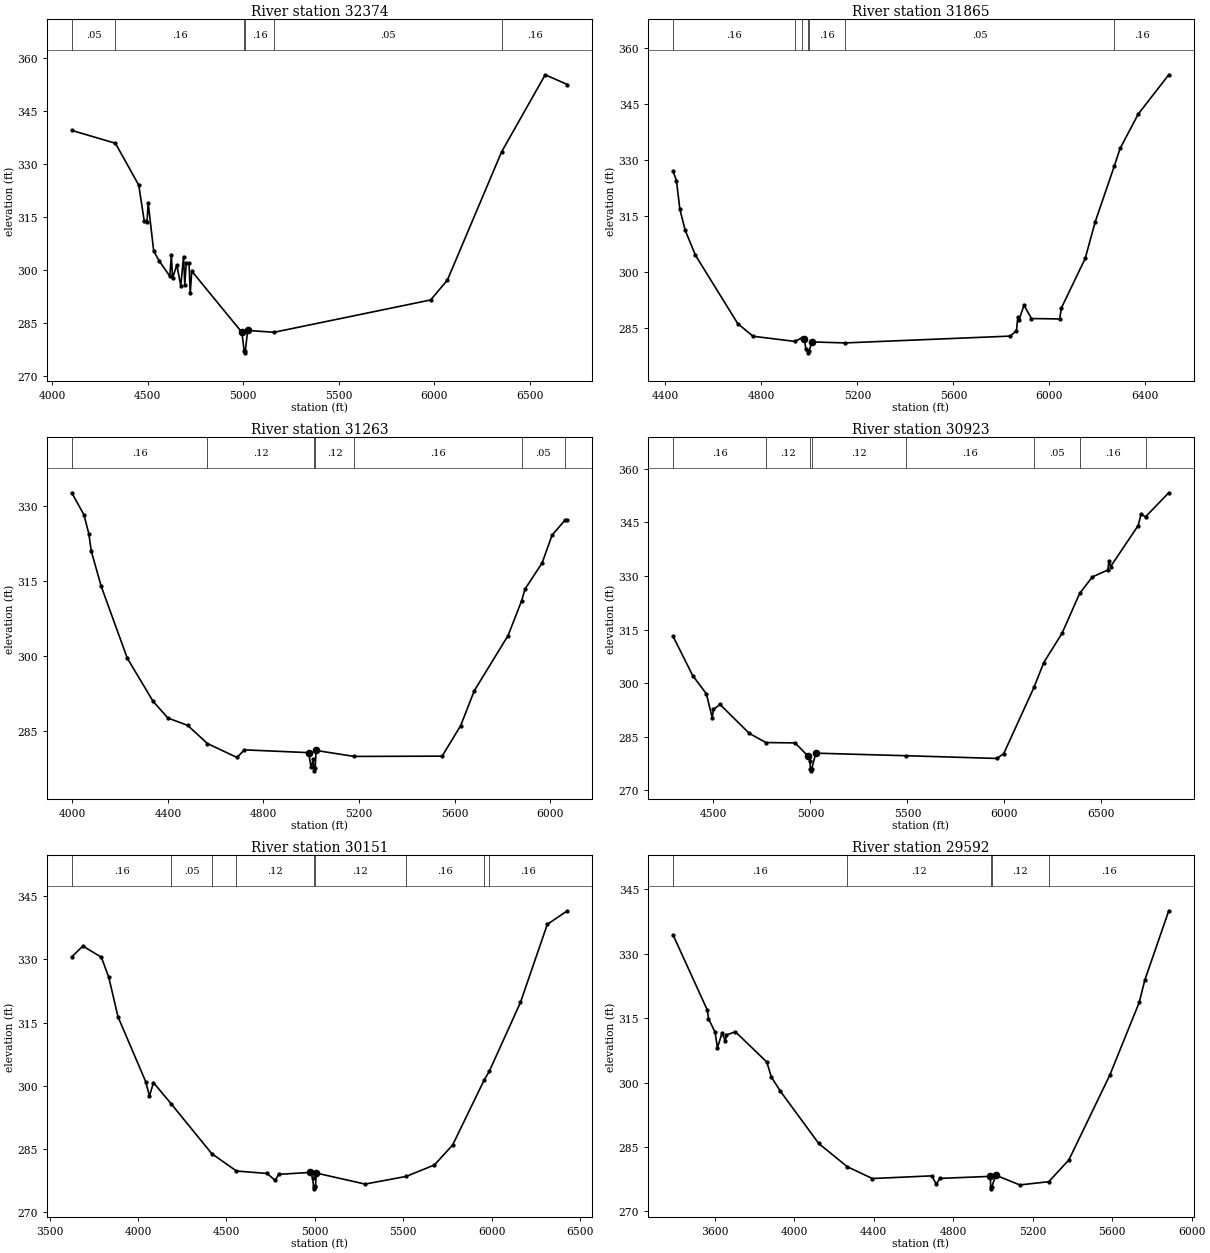
Type RM Length L Ch R = 1 ,32374   ,509,509,509
BEGIN DESCRIPTION:
BLISS CREEK 52.0
END DESCRIPTION:
XS GIS Cut Line= 3
        3636602.     10513976.44      3637149.61     10513310.19
       3638099.6      10511860.2
#Sta/Elev= 30
  4101.7  339.55  4330.2  335.92  4452.5  324.06  4481.2  313.91  4495.6  313.56
  4502.1  318.92  4530.8  305.37  4559.4  302.59  4615.4  298.24  4623.3  304.18
  4629.8  297.68    4652  301.45  4672.8  295.54  4687.2  303.82  4693.6  295.85
  4701.5  302.01  4715.9  301.84  4722.3  293.37  4730.2  299.68  4992.7  282.34
  5004.8  277.02  5007.6  276.52  5010.8  277.02  5022.9  282.87  5161.5  282.35
  5981.6  291.51    6069  297.13    6353  333.47  6581.5  355.32  6697.6  352.56
#Mann= 6 ,-1 , 0
  4101.7     .05       0  4330.2     .16       0  5004.8     .07       0
  5010.8     .16       0  5161.5     .05       0    6353     .16       0
Bank Sta=4992.7,5022.9
XS Rating Curve= 0 ,0
Exp/Cntr=0.3,0.1

Type RM Length L Ch R = 1 ,31865   ,602,602,602
BEGIN DESCRIPTION:
BLISS CREEK 51.0
END DESCRIPTION:
XS GIS Cut Line= 3
      3637199.58     10513860.22      3637599.61     10513510.19
       3638099.6     10512060.22
#Sta/Elev= 30
  4431.9  327.03  4445.7  324.54  4459.9  316.89  4481.8   311.3  4524.5  304.58
    4701  286.22  4764.6  282.81  4938.3  281.43  4968.7  282.37  4979.1  282.19
  4984.6  279.46  4992.2  278.86  4994.9  278.36  4998.2  278.86  5010.3  281.29
  5147.2  281.02  5836.9  282.85  5862.6   284.3  5868.1  287.92  5873.4  287.23
    5894  291.12  5925.2  287.56  6042.4  287.45  6050.1  290.43    6149  303.67
  6190.5  313.47  6269.9  328.36  6294.4  333.18  6370.3  342.43  6497.2  352.94
#Mann= 7 ,-1 , 0
  4431.9     .16       0  4938.3     .12       0  4968.7     .16       0
  4992.2     .07       0  4998.2     .16       0  5147.2     .05       0
  6269.9     .16       0
Bank Sta=4979.1,5010.3
XS Rating Curve= 0 ,0
Exp/Cntr=0.3,0.1

Type RM Length L Ch R = 1 ,31263   ,340,340,340
BEGIN DESCRIPTION:
BLISS CREEK 50.0
END DESCRIPTION:
XS GIS Cut Line= 3
      3637150.62     10513934.76      3638200.97     10513656.98
       3638849.6      10512910.2
#Sta/Elev= 30
  3997.1  332.69  4047.8  328.31  4068.5  324.54  4078.8  321.02  4120.2  314.02
  4229.4  299.62  4337.4     291  4399.5  287.64  4482.2  286.17  4565.5  282.53
  4689.1  279.74  4720.1  281.27  4989.1  280.71  4999.4  277.74  5008.5  279.41
  5010.6  277.57  5013.4  277.07  5016.6  277.57  5020.1  281.15  5180.1  279.95
  5548.1  280.01  5625.9  286.12  5682.9   293.1  5824.4  304.14    5881  311.08
  5895.6  313.46  5966.8  318.64  6008.6  324.22  6062.2  327.17  6072.7  327.21
#Mann= 7 ,-1 , 0
  3997.1     .16       0  4565.5     .12       0  5010.6     .07       0
  5016.6     .12       0  5180.1     .16       0    5881     .05       0
  6062.2     .16       0
Bank Sta=4989.1,5020.1
XS Rating Curve= 0 ,0
Exp/Cntr=0.3,0.1

Type RM Length L Ch R = 1 ,30923   ,772,772,772
BEGIN DESCRIPTION:
BLISS CREEK 49.0
END DESCRIPTION:
XS GIS Cut Line= 3
       3637299.6     10514010.19      3638070.76      10513917.4
      3639499.64     10512860.16
#Sta/Elev= 30
  4292.7  313.08  4393.4  302.15  4463.9  297.04  4494.1  290.33  4500.6  292.67
  4534.4  294.05  4685.5  285.93  4771.1  283.38  4921.4  283.28  4987.7   279.6
  4997.8   278.3  5000.5  275.96  5003.2  275.46  5006.5  275.96    5028  280.41
  5494.6  279.69  5960.8  278.93  5996.3  280.27  6152.7  298.87  6202.9  305.79
  6296.9  313.97  6387.9  325.16  6453.4  329.76  6532.7  331.69    6539  334.22
  6547.4  332.65  6689.3  344.14  6703.9  347.26  6727.4   346.6  6846.9  353.31
#Mann= 8 ,-1 , 0
  4292.7     .16       0  4771.1     .12       0  5000.5     .07       0
  5006.5     .12       0  5494.6     .16       0  6152.7     .05       0
  6387.9     .16       0  6727.4     .05       0
Bank Sta=4987.7,5028
XS Rating Curve= 0 ,0
Exp/Cntr=0.3,0.1

Type RM Length L Ch R = 1 ,30151   ,559,559,559
BEGIN DESCRIPTION:
BLISS CREEK 48.0
END DESCRIPTION:
XS GIS Cut Line= 3
      3636999.59     10513960.18      3638299.61     10514360.19
      3639699.65      10514710.2
#Sta/Elev= 30
  3624.9  330.62  3687.7  333.18  3792.3  330.54  3834.2  325.77  3886.5  316.38
  4043.4  300.96  4064.4  297.58  4087.2  300.75  4188.2  295.68  4416.5   283.9
  4556.5  279.77  4729.4  279.19  4775.8  277.53  4794.8  278.98  4974.6  279.44
  4987.6  278.14  4992.4  276.04  4995.1  275.54  4998.4  276.04  5003.1   276.1
  5008.3  279.28    5284  276.67  5516.4  278.49  5675.7   281.2  5778.8  285.92
    5959   301.5  5986.2  303.42  6162.7  319.79  6314.8  338.35  6428.2  341.56
#Mann= 9 ,-1 , 0
  3624.9     .16       0  4188.2     .05       0  4416.5     .16       0
  4556.5     .12       0  4992.4     .07       0  4998.4     .12       0
  5516.4     .16       0    5959     .12       0  5986.2     .16       0
Bank Sta=4974.6,5008.3
XS Rating Curve= 0 ,0
Exp/Cntr=0.3,0.1

Type RM Length L Ch R = 1 ,29592   ,565,565,565
BEGIN DESCRIPTION:
BLISS CREEK 47.0
END DESCRIPTION:
XS GIS Cut Line= 3
       3636999.6     10514060.18      3638449.61     10514760.19
      3639099.59     10515360.17
#Sta/Elev= 30
    3390  334.28  3562.3  316.83  3567.9  314.86    3601   311.7  3613.1  308.06
  3635.7  311.46  3652.7  309.67  3658.3  311.07  3703.5   311.8  3861.7  304.75
  3884.4  301.27  3929.6  297.99  4122.9  285.82  4266.5  280.42  4392.8  277.67
  4692.2  278.29  4714.8   276.3  4731.8   277.7  4986.1  278.17  4988.6  275.77
  4991.4  275.27  4994.6  275.77    5014  278.44  5134.8  276.18  5280.8  276.93
    5382     282  5587.3  301.65  5735.9  318.61  5764.2  323.82  5884.7  339.94
#Mann= 5 ,-1 , 0
    3390     .16       0  4266.5     .12       0  4988.6     .07       0
  4994.6     .12       0  5280.8     .16       0
Bank Sta=4986.1,5014
XS Rating Curve= 0 ,0
Exp/Cntr=0.3,0.1