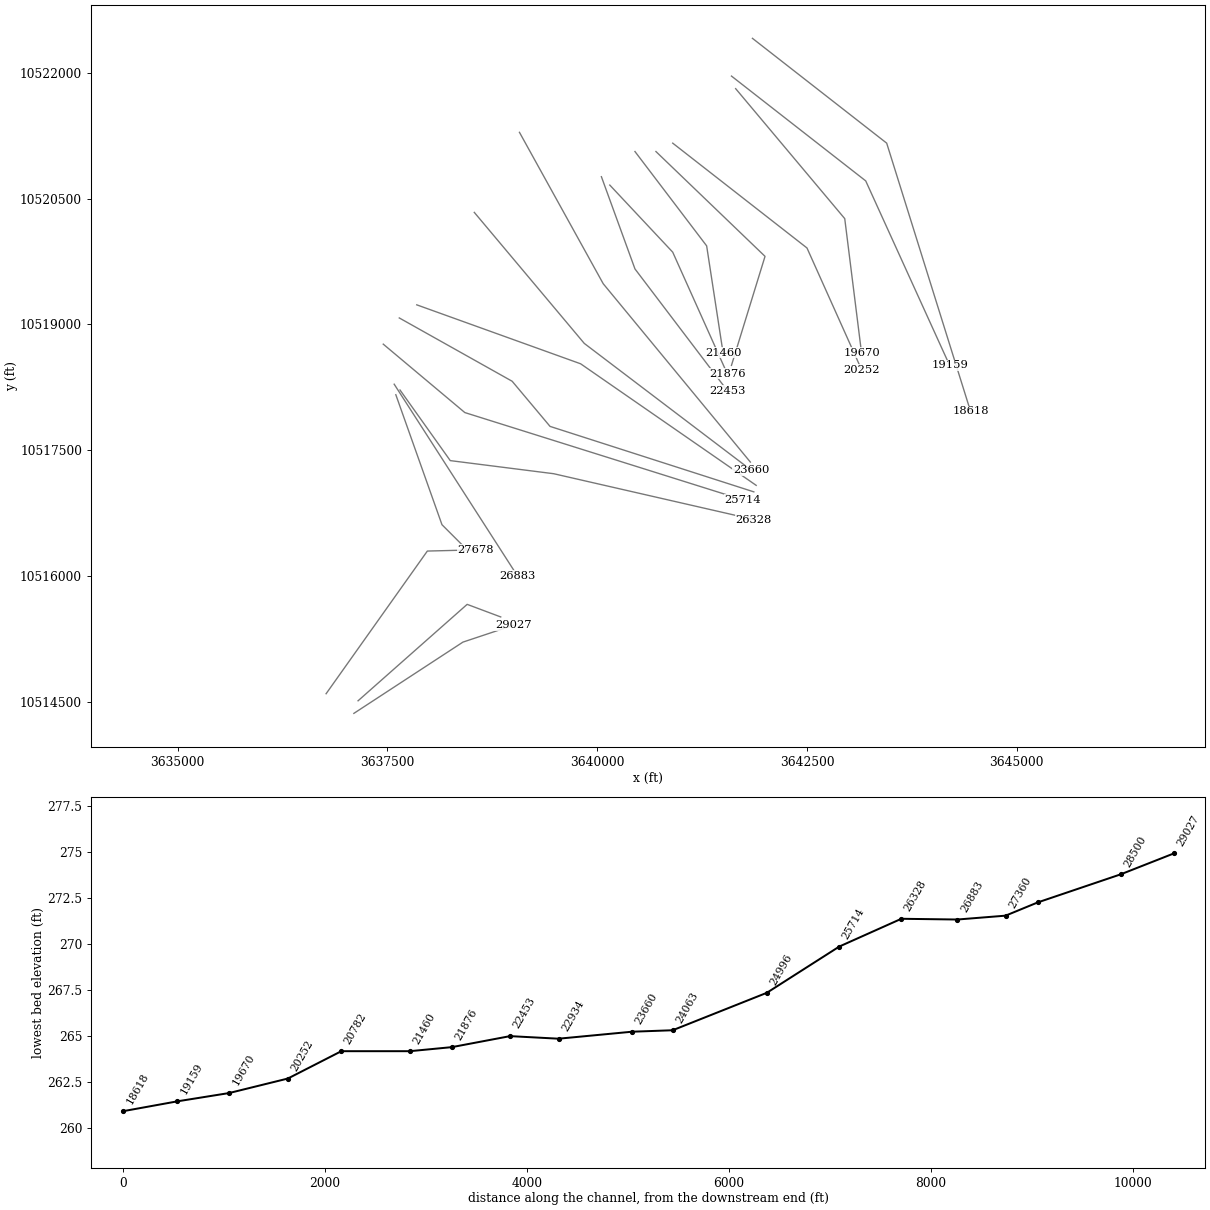
HEC-RAS study BLISS CREEK.prj: BLISS CREEK Base Level Engineering

--- BLISS CREEK.g01 (geometry) --- (continued)

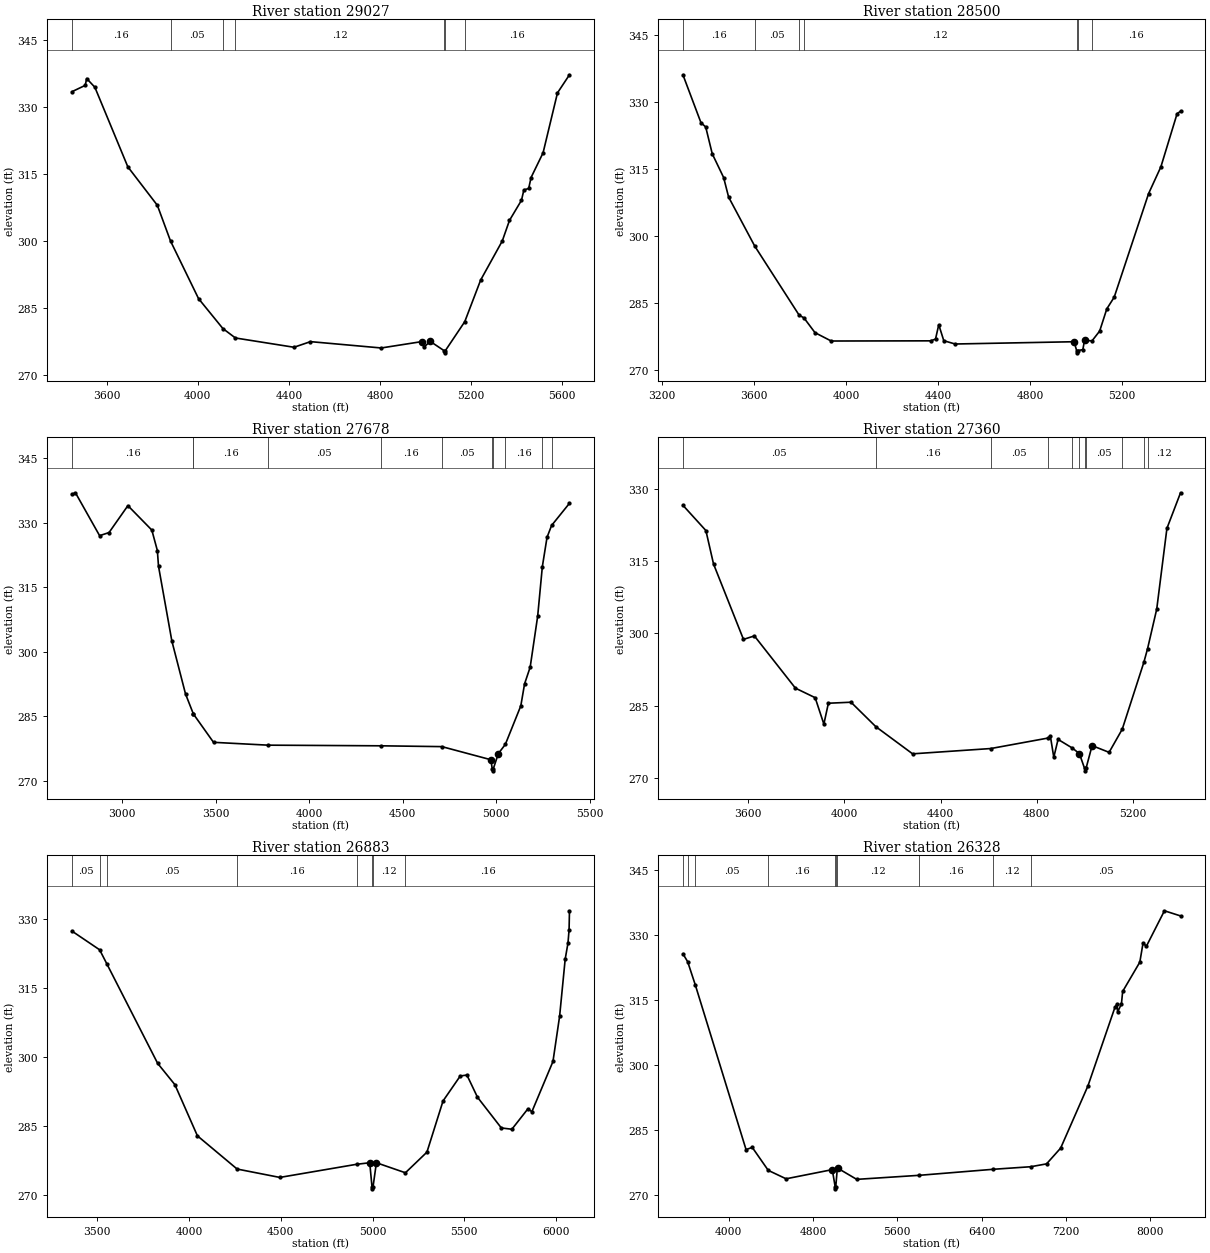
Type RM Length L Ch R = 1 ,29027   ,527,527,527
BEGIN DESCRIPTION:
BLISS CREEK 46.0
END DESCRIPTION:
XS GIS Cut Line= 3
      3637099.59     10514360.18      3638399.61     10515210.19
      3638999.61     10515410.19
#Sta/Elev= 30
  3446.5  333.47  3505.4   334.9  3511.4  336.43  3547.5  334.48  3692.3  316.64
    3822  308.01  3879.8  300.01    4003  287.09  4109.9  280.38    4165  278.27
  4422.2  276.19  4494.6  277.45  4805.2  276.03  4986.2  277.48  4992.2  276.18
  5020.8   277.5  5081.1  275.44  5083.8  274.94  5087.1  275.44  5172.2  281.92
  5242.2  291.27  5337.1  300.02  5368.7  304.63  5421.4  309.14  5431.9  311.46
    5453  311.78  5463.5  314.24  5516.2  319.77  5579.5  333.21  5632.2  337.27
#Mann= 7 ,-1 , 0
  3446.5     .16       0  3879.8     .05       0  4109.9     .16       0
    4165     .12       0  5081.1     .07       0  5087.1     .12       0
  5172.2     .16       0
Bank Sta=4986.2,5020.8
XS Rating Curve= 0 ,0
Exp/Cntr=0.3,0.1

Type RM Length L Ch R = 1 ,28500   ,822,822,822
BEGIN DESCRIPTION:
BLISS CREEK 45.0
END DESCRIPTION:
XS GIS Cut Line= 3
      3637149.63     10514510.21      3638449.61     10515660.19
      3638849.59      10515510.2
#Sta/Elev= 30
  3290.6  336.11  3368.8   325.4  3389.7   324.4  3418.1   318.4  3467.5  313.09
  3489.2   308.7  3602.6  297.73  3795.5  282.26  3816.8  281.62  3864.7  278.32
  3935.1  276.45  4367.5  276.49  4388.4  276.88  4402.6   280.1  4424.4  276.52
  4473.7  275.78  4990.7  276.29  5001.9   274.3  5004.6   273.8  5007.9   274.3
  5028.9  274.53    5036  276.59  5068.8  276.49  5101.9  278.68    5133  283.66
  5165.1  286.27  5314.6  309.49    5368  315.48  5438.3  327.37  5453.4  327.95
#Mann= 7 ,-1 , 0
  3290.6     .16       0  3602.6     .05       0  3795.5     .16       0
  3816.8     .12       0  5001.9     .07       0  5007.9     .12       0
  5068.8     .16       0
Bank Sta=4990.7,5036
XS Rating Curve= 0 ,0
Exp/Cntr=0.3,0.1

Type RM Length L Ch R = 1 ,27678   ,318,318,318
BEGIN DESCRIPTION:
BLISS CREEK 44.0
END DESCRIPTION:
XS GIS Cut Line= 3
      3636768.68     10514594.49      3637975.27     10516295.87
       3638549.6     10516310.19
#Sta/Elev= 30
  2731.1  336.55  2750.3  336.92  2879.4  326.95  2929.8  327.67  3030.7  333.93
  3158.6  328.25  3188.2  323.49  3194.3  319.85  3265.7  302.46  3338.8  290.14
  3380.6  285.51  3381.1  285.47  3488.4   278.9  3779.8  278.24  4382.2  278.09
  4709.3   277.9  4971.3  274.85  4978.3  272.77    4981  272.27  4984.3  272.77
  5011.3   276.3  5048.4  278.41  5131.3  287.39  5151.3  292.49  5181.3  296.38
  5221.4  308.24  5246.4  319.76  5271.4  326.56  5295.8  329.32  5391.4  334.48
#Mann= 11 ,-1 , 0
  2731.1     .16       0  3380.6     .05       0  3381.1     .16       0
  3779.8     .05       0  4382.2     .16       0  4709.3     .05       0
  4978.3    .035       0  4984.3     .05       0  5048.4     .16       0
  5246.4     .12       0  5295.8     .16       0
Bank Sta=4971.3,5011.3
XS Rating Curve= 0 ,0
Exp/Cntr=0.3,0.1

Type RM Length L Ch R = 1 ,27360   ,477,477,477
BEGIN DESCRIPTION:
BLISS CREEK 43.0
END DESCRIPTION:
XS GIS Cut Line= 3
      3637599.61     10518160.19      3638149.61     10516610.19
      3638449.64     10516310.16
#Sta/Elev= 30
  3328.6  326.54  3424.1  321.31  3455.9  314.38  3580.4  298.77  3625.7  299.49
  3796.4  288.67  3878.4   286.7  3914.6  281.23  3933.4  285.55  4027.5  285.76
  4130.6   280.7  4283.6  275.07  4608.9  276.17  4844.6  278.32  4856.6  278.67
  4870.6  274.36  4888.4  278.06  4947.3  276.28    4977  275.13  4998.6  272.05
  5001.3  271.55  5004.6  272.05  5029.9  276.77  5100.6  275.38  5155.3  280.18
  5244.9  293.99  5260.3   296.8  5298.6  305.04    5341  321.76  5397.6  329.13
#Mann= 11 ,-1 , 0
  3328.6     .05       0  4130.6     .16       0  4608.9     .05       0
  4844.6     .16       0  4947.3      .1       0    4977     .05       0
  4998.6    .035       0  5004.6     .05       0  5155.3     .12       0
  5244.9     .16       0  5260.3     .12       0
Bank Sta=4977,5029.9
XS Rating Curve= 0 ,0
Exp/Cntr=0.3,0.1

Type RM Length L Ch R = 1 ,26883   ,555,555,555
BEGIN DESCRIPTION:
Mapping XS a0660db8
END DESCRIPTION:
XS GIS Cut Line= 2
        3637580.     10518285.86      3639046.26     10516004.05
#Sta/Elev= 30
    3361  327.36  3512.4  323.28  3552.1  320.19  3828.7   298.6  3922.5  293.98
  4045.3  282.86  4261.8  275.64  4494.5  273.82  4912.5  276.67  4984.6  277.01
  4996.8  271.84  4999.5  271.34  5002.8  271.84  5020.9  277.01  5179.1  274.83
  5296.3  279.31  5384.2  290.44    5478  295.86  5514.3  296.07  5571.8  291.25
  5701.9  284.57  5759.3  284.29  5847.2  288.75  5868.3  288.09  5983.3  299.01
  6019.6  308.87    6050  321.27  6065.2  324.76  6071.1  327.61  6073.3  331.76
#Mann= 8 ,-1 , 0
    3361     .05       0  3512.4     .16       0  3552.1     .05       0
  4261.8     .16       0  4912.5     .12       0  4996.8     .07       0
  5002.8     .12       0  5179.1     .16       0
Bank Sta=4984.6,5020.9
XS Rating Curve= 0 ,0
Exp/Cntr=0.3,0.1

Type RM Length L Ch R = 1 ,26328   ,614,614,614
BEGIN DESCRIPTION:
BLISS CREEK 42.0
END DESCRIPTION:
XS GIS Cut Line= 4
      3637649.41     10518216.47      3638248.38     10517374.44
      3639481.02     10517218.19      3641866.39     10516671.72
#Sta/Elev= 30
  3564.9  325.71  3609.9  323.88  3681.8  318.56  4164.1  280.45    4223  280.96
  4374.8  275.65  4544.1   273.7  4982.5  275.82  5009.8  271.88  5012.5  271.38
  5015.8  271.88  5029.4  275.88  5032.9  276.17  5214.4  273.57  5810.2  274.51
  6510.6   275.9    6866  276.49  7016.2  277.15  7150.1   280.8  7408.9  295.16
  7665.4  313.34  7685.5  314.11  7690.6  312.24    7727  314.13  7738.7  317.01
  7901.4  323.77  7932.1   328.2  7963.5  327.44  8135.1  335.65  8287.9  334.46
#Mann= 10 ,-1 , 0
  3564.9     .05       0  3609.9     .16       0  3681.8     .05       0
  4374.8     .16       0  5009.8     .07       0  5015.8     .16       0
  5029.4     .12       0  5810.2     .16       0  6510.6     .12       0
    6866     .05       0
Bank Sta=4982.5,5032.9
XS Rating Curve= 0 ,0
Exp/Cntr=0.3,0.1

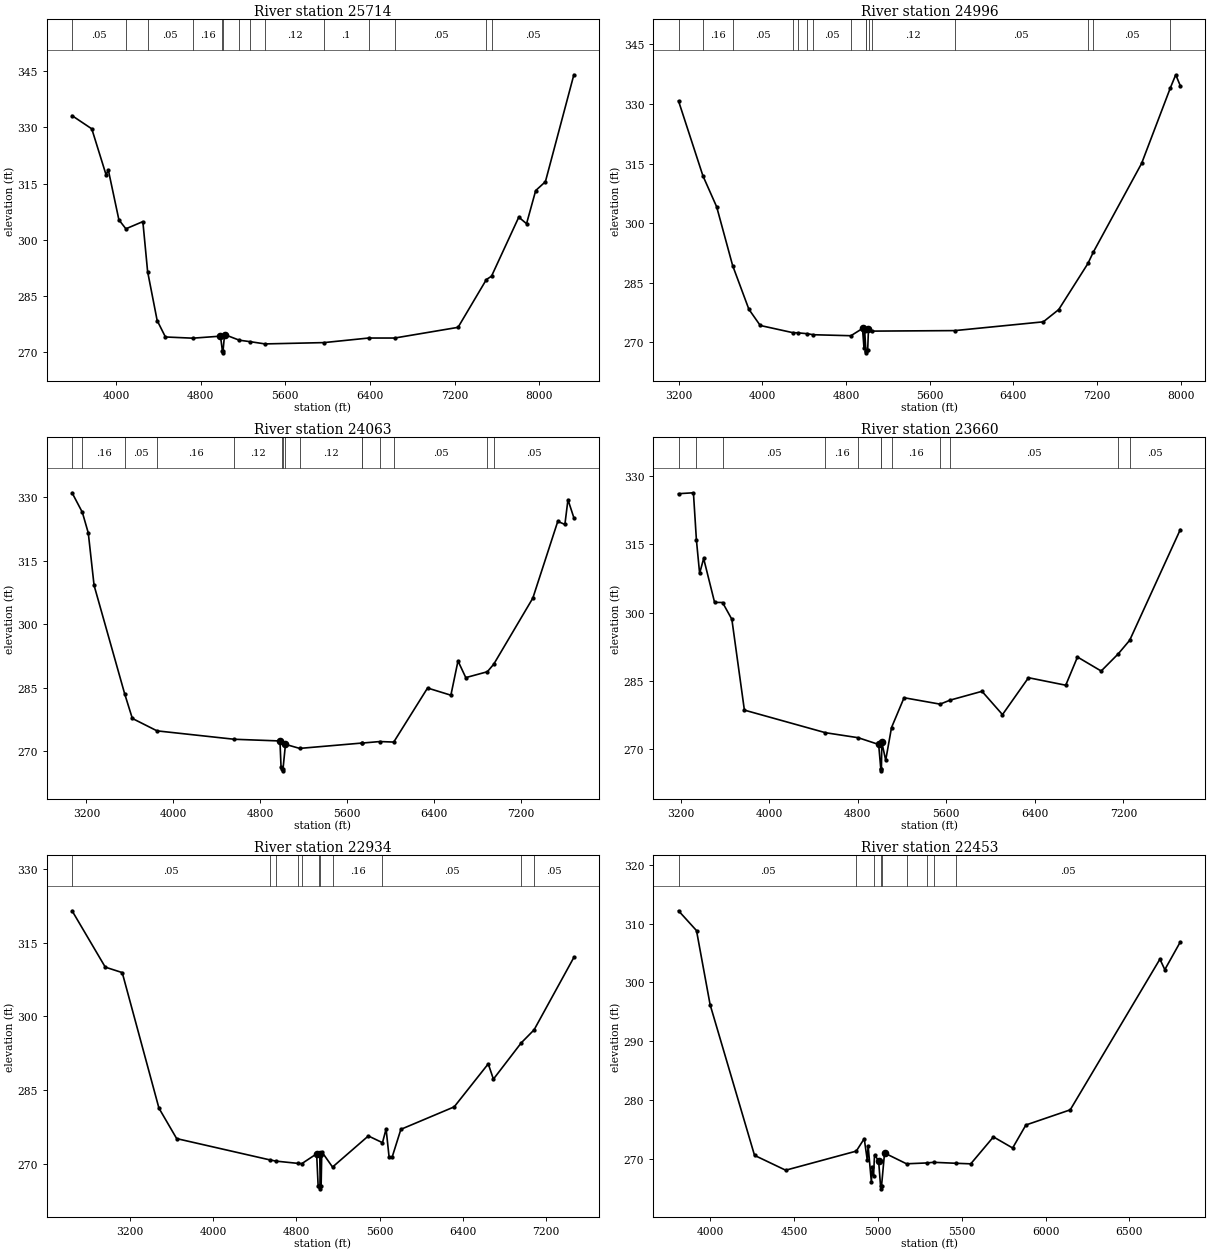
Type RM Length L Ch R = 1 ,25714   ,718,718,718
BEGIN DESCRIPTION:
BLISS CREEK 41.0
END DESCRIPTION:
XS GIS Cut Line= 3
      3637449.77     10518763.33      3638421.99     10517947.36
      3641736.25     10516906.23
#Sta/Elev= 30
  3584.1  333.13  3770.5  329.61  3905.8  317.32  3926.6  318.66  4026.8  305.34
  4092.9  302.95  4253.2  304.87  4298.2  291.54  4388.4  278.49  4466.5   274.1
  4725.5  273.78  4987.1  274.32  5005.1  270.37  5007.8  269.87  5011.1  270.37
  5025.6  274.75  5164.8  273.24  5269.7  272.84  5407.8  272.25  5965.2   272.6
  6387.3  273.82  6633.7  273.82  7232.6  276.67  7500.4  289.42  7548.9  290.31
  7806.7  306.06  7880.1  304.31  7966.5  313.15  8058.3  315.51  8327.3  344.03
#Mann= 14 ,-1 , 0
  3584.1     .05       0  4092.9     .16       0  4298.2     .05       0
  4725.5     .16       0  5005.1     .07       0  5011.1     .16       0
  5164.8     .12       0  5269.7     .07       0  5407.8     .12       0
  5965.2      .1       0  6387.3     .16       0  6633.7     .05       0
  7500.4     .08       0  7548.9     .05       0
Bank Sta=4987.1,5025.6
XS Rating Curve= 0 ,0
Exp/Cntr=0.3,0.1

Type RM Length L Ch R = 1 ,24996   ,933,933,933
BEGIN DESCRIPTION:
BLISS CREEK 40.0
END DESCRIPTION:
XS GIS Cut Line= 4
      3637640.77     10519075.81      3638986.22     10518320.62
      3639437.61     10517782.43       3641866.4     10517001.75
#Sta/Elev= 30
  3199.6  330.77  3432.9  311.91  3564.1  304.12  3716.6  289.34  3872.1  278.32
  3980.5  274.24  4292.1  272.43  4339.1  272.39  4429.9  272.17    4488  271.91
  4847.6  271.66  4958.1  273.49  4972.4  268.57    4979  272.92  4990.3  267.85
    4993  267.35  4996.3  267.85  5007.6  268.11  5015.4  273.42  5016.5  273.43
  5046.9  272.82  5840.5  272.95  6686.5  275.16  6833.5  278.24  7112.9  289.85
    7165  292.74    7626  315.05  7902.1  334.16  7952.2  337.37  7996.1  334.59
#Mann= 16 ,-1 , 0
  3199.6     .05       0  3432.9     .16       0  3716.6     .05       0
  4292.1     .07       0  4339.1     .05       0  4429.9     .07       0
    4488     .05       0  4847.6     .12       0  4990.3     .07       0
  4996.3     .12       0  5016.5     .07       0  5046.9     .12       0
  5840.5     .05       0  7112.9     .08       0    7165     .05       0
  7902.1     .16       0
Bank Sta=4958.1,5015.4
XS Rating Curve= 0 ,0
Exp/Cntr=0.3,0.1

Type RM Length L Ch R = 1 ,24063   ,403,403,403
BEGIN DESCRIPTION:
BLISS CREEK 39.0
END DESCRIPTION:
XS GIS Cut Line= 3
       3637849.1     10519232.07       3639802.2     10518528.96
      3641894.21      10517079.3
#Sta/Elev= 30
  3067.5  331.11  3162.2  326.48  3216.8   321.6  3270.1  309.21  3552.1  283.52
  3622.6  277.71    3850  274.77  4561.8  272.78  4981.9  272.38  4991.8  266.32
  5004.3  265.81    5007  265.31  5010.3  265.81  5032.6  271.58  5163.4  270.62
  5734.2  271.88    5738  271.88  5901.1  272.24  6029.8  272.12  6341.2  284.91
    6556  283.21  6621.5  291.31  6693.2  287.37  6891.8  288.76    6951  290.56
  7310.6  306.18  7540.3  324.34  7605.9  323.62  7634.2  329.48  7688.5   325.2
#Mann= 15 ,-1 , 0
  3067.5     .05       0  3162.2     .16       0  3552.1     .05       0
    3850     .16       0  4561.8     .12       0  5004.3     .07       0
  5010.3     .12       0  5032.6     .16       0  5163.4     .12       0
  5734.2      .1       0    5738     .16       0  5901.1      .1       0
  6029.8     .05       0  6891.8     .08       0    6951     .05       0
Bank Sta=4981.9,5032.6
XS Rating Curve= 0 ,0
Exp/Cntr=0.3,0.1

Type RM Length L Ch R = 1 ,23660   ,726,726,726
BEGIN DESCRIPTION:
BLISS CREEK 38.0
END DESCRIPTION:
XS GIS Cut Line= 3
      3638534.86     10520334.48       3639845.6     10518772.01
      3641833.43     10517261.61
#Sta/Elev= 30
  3179.1  326.15  3313.7  326.35  3340.6  316.01  3369.7  308.63  3406.1  311.91
    3505  302.26    3577  302.23  3661.1  298.54  3774.3  278.58  4507.5  273.61
  4803.6  272.51  4988.1  271.03  5007.1  265.73  5009.9  265.23  5013.1  265.73
  5016.7   271.5  5051.8  267.56  5104.3  274.74  5217.8   281.3  5543.5  279.89
  5633.7  280.77  5922.3  282.71  6107.4  277.59  6342.5   285.7  6679.3  284.05
  6785.4  290.25  6999.6  287.17  7153.3  290.93  7257.4  293.93  7715.1  318.27
#Mann= 12 ,-1 , 0
  3179.1     .05       0  3340.6     .16       0    3577     .05       0
  4507.5     .16       0  4803.6     .12       0  5007.1     .07       0
  5013.1     .12       0  5104.3     .16       0  5543.5     .12       0
  5633.7     .05       0  7153.3     .08       0  7257.4     .05       0
Bank Sta=4988.1,5016.7
XS Rating Curve= 0 ,0
Exp/Cntr=0.3,0.1

Type RM Length L Ch R = 1 ,22934   ,481,481,481
BEGIN DESCRIPTION:
BLISS CREEK 37.0
END DESCRIPTION:
XS GIS Cut Line= 3
      3639073.02     10521289.38      3640071.29     10519483.82
      3641824.67     10517357.19
#Sta/Elev= 30
  2645.9  321.53  2964.9  310.04  3127.6  308.93  3480.4  281.29  3650.5  275.09
  4543.5  270.76  4604.5   270.5  4820.1  270.03  4853.2     270  4994.8  271.99
  5009.2  265.47  5020.5  265.35  5023.2  264.85  5026.5  265.35    5030  271.93
  5037.8  265.35  5044.3   272.4  5147.6  269.29  5491.4  275.63  5627.2  274.26
  5661.9  277.06  5690.6  271.35  5719.3  271.27  5803.9  276.98    6316  281.56
  6643.1  290.33  6692.6  287.21  6960.1  294.61  7083.3  297.26  7465.3  312.02
#Mann= 11 ,-1 , 0
  2645.9     .05       0  4543.5      .1       0  4604.5     .12       0
  4820.1     .07       0  4853.2     .12       0  5020.5     .07       0
  5026.5     .12       0  5147.6     .16       0  5627.2     .05       0
  6960.1     .08       0  7083.3     .05       0
Bank Sta=4994.8,5030
XS Rating Curve= 0 ,0
Exp/Cntr=0.3,0.1

Type RM Length L Ch R = 1 ,22453   ,577,577,577
BEGIN DESCRIPTION:
BLISS CREEK 36.0
END DESCRIPTION:
XS GIS Cut Line= 3
      3640049.59     10520760.23      3640449.61     10519660.19
      3641549.59     10518210.22
#Sta/Elev= 30
  3812.6  312.16  3919.7   308.8  4000.8  296.23  4265.5  270.67  4451.1  268.15
  4871.9  271.39  4919.3   273.5  4937.2  269.91  4942.5  272.25  4961.8  266.17
  4967.8  268.73  4974.8  267.16  4980.5  270.71  5004.9  269.79  5016.5  265.49
  5019.2  264.99  5022.5  265.49  5040.3  271.07  5171.2  269.24    5291  269.38
  5332.3  269.49  5463.4  269.33  5554.1  269.23  5689.3   273.8  5803.7  271.92
  5882.7  275.82  6146.9  278.39  6681.5  303.96  6710.6  302.17  6803.1  306.88
#Mann= 9 ,-1 , 0
  3812.6     .05       0  4871.9     .08       0  4974.8     .05       0
  5016.5     .04       0  5022.5     .05       0  5171.2     .12       0
    5291     .08       0  5332.3     .12       0  5463.4     .05       0
Bank Sta=5004.9,5040.3
XS Rating Curve= 0 ,0
Exp/Cntr=0.3,0.1

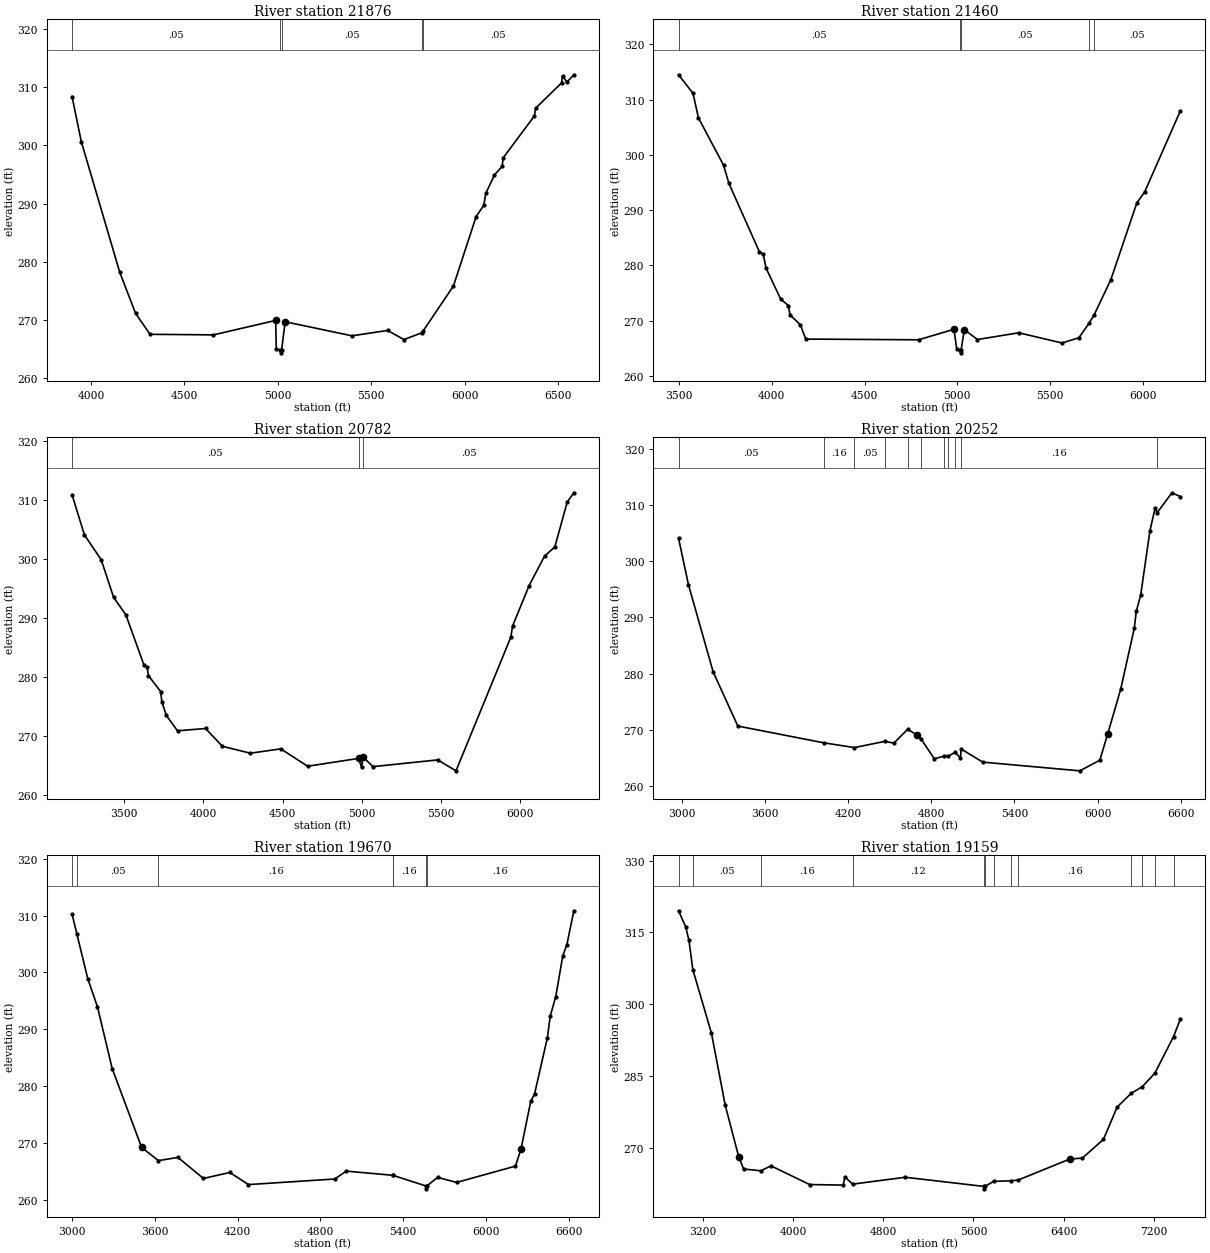
Type RM Length L Ch R = 1 ,21876   ,416,416,416
BEGIN DESCRIPTION:
BLISS CREEK 35.0
END DESCRIPTION:
XS GIS Cut Line= 3
      3640149.59     10520660.21      3640899.61     10519860.19
      3641549.59     10518410.22
#Sta/Elev= 30
  3898.8  308.34  3948.4   300.6  4153.6  278.25  4238.5  271.17  4316.2  267.57
  4655.7  267.47  4988.3  269.95    4992  265.03  5014.3  264.89  5017.1  264.39
  5020.3  264.89  5039.2  269.72  5397.1  267.31  5587.2  268.23  5674.9  266.67
  5770.8  267.83  5776.4  268.08    5940  275.87  6061.4  287.77  6102.2  289.69
  6113.2  291.75  6159.6  294.92  6200.5  296.36  6205.9  297.83  6373.7  305.05
  6379.2  306.34  6518.3  310.69  6523.7  311.92  6546.9  310.82  6584.4  312.09
#Mann= 5 ,-1 , 0
  3898.8     .05       0  5014.3     .03       0  5020.3     .05       0
  5770.8     .08       0  5776.4     .05       0
Bank Sta=4988.3,5039.2
XS Rating Curve= 0 ,0
Exp/Cntr=0.3,0.1

Type RM Length L Ch R = 1 ,21460   ,678,678,678
BEGIN DESCRIPTION:
BLISS CREEK 34.0
END DESCRIPTION:
XS GIS Cut Line= 3
      3640449.62     10521060.17      3641303.93     10519935.21
       3641499.6     10518660.22
#Sta/Elev= 30
  3498.4  314.49  3576.4  311.13  3605.5  306.69  3740.7  298.14  3769.8  294.82
  3934.1  282.44  3954.9  282.01  3969.4  279.53  4048.4  273.91  4090.1  272.73
  4098.4  271.06  4154.6  269.24  4183.6  266.66  4790.9  266.53  4981.6  268.43
    4997   264.8  5014.2  264.67    5017  264.17  5020.2  264.67  5037.5  268.37
  5108.2  266.58  5330.9   267.8  5563.6  265.95  5654.6   266.9  5710.1  269.56
  5736.5  271.03  5826.6   277.4  5966.7  291.31  6008.7  293.28  6200.9  307.94
#Mann= 5 ,-1 , 0
  3498.4     .05       0  5014.2     .03       0  5020.2     .05       0
  5710.1     .08       0  5736.5     .05       0
Bank Sta=4981.6,5037.5
XS Rating Curve= 0 ,0
Exp/Cntr=0.3,0.1

Type RM Length L Ch R = 1 ,20782   ,530,530,530
BEGIN DESCRIPTION:
BLISS CREEK 33.0
END DESCRIPTION:
XS GIS Cut Line= 3
      3640699.63     10521060.17      3641999.61     10519810.19
      3641599.61     10518510.18
#Sta/Elev= 30
    3173  310.86  3250.8  304.07  3356.8  299.86  3434.8  293.51  3512.4  290.54
  3625.6  282.11  3646.7  281.72  3653.9  280.28  3731.6  277.58  3738.8  275.88
  3767.2  273.54  3837.9  270.94  4014.6  271.33  4120.6  268.32  4297.4  267.15
  4488.5  267.89  4658.1  264.95  4979.1  266.27    4998   264.8  5007.8  266.49
  5070.6  264.88  5478.7  266.02  5593.5  264.17    5939  286.76  5950.1  288.65
  6054.1  295.47  6151.5  300.47  6216.9  302.05  6294.7  309.63  6336.6  311.19
#Mann= 3 , 0 , 0
    3173     .05       0  4979.1     .03       0  5007.8     .05       0
Bank Sta=4979.1,5007.8
XS Rating Curve= 0 ,0
Exp/Cntr=0.3,0.1

Type RM Length L Ch R = 1 ,20252   ,582,582,582
BEGIN DESCRIPTION:
BLISS CREEK 32.0
END DESCRIPTION:
XS GIS Cut Line= 3
      3640899.61     10521160.19      3642499.61     10519910.19
       3643149.6     10518460.21
#Sta/Elev= 30
  2976.8  304.08  3048.2  295.83  3226.4   280.3  3404.6  270.65  4024.1  267.67
  4245.7  266.82  4465.5  267.93  4529.7  267.61  4629.2  270.07  4693.4  269.11
  4728.7  268.26  4821.8  264.83    4893   265.3  4921.3  265.28    4971  265.97
  5009.9  264.98    5016  266.55  5171.6  264.23    5871  262.68  6015.4  264.57
  6073.1   269.3  6165.9  277.19  6264.1  288.06  6278.4  291.05  6310.4  293.99
    6377  305.42  6414.1  309.43  6429.3  308.62  6535.5  312.17  6596.2  311.49
#Mann= 11 ,-1 , 0
  2976.8     .05       0  4024.1     .16       0  4245.7     .05       0
  4465.5     .16       0  4629.2     .05       0  4728.7     .07       0
    4893     .05       0  4921.3     .16       0    4971     .03       0
    5016     .16       0  6429.3     .05       0
Bank Sta=4693.4,6073.1
XS Rating Curve= 0 ,0
Exp/Cntr=0.3,0.1

Type RM Length L Ch R = 1 ,19670   ,511,511,511
BEGIN DESCRIPTION:
BLISS CREEK 31.0
END DESCRIPTION:
XS GIS Cut Line= 3
      3641649.59     10521810.21      3642949.61     10520260.19
      3643149.61     10518660.17
#Sta/Elev= 30
  3000.4  310.26  3035.3  306.75  3114.3  298.88  3184.5  293.92  3291.2  283.05
  3504.5  269.17  3625.9  266.86  3767.3  267.42  3952.1  263.72  4143.3  264.77
  4278.6  262.64  4903.1  263.62  4987.7  265.01  5322.7  264.28  5323.5  264.28
  5564.6  262.39  5567.4  261.89  5570.6  262.39  5648.3  263.91  5786.8  263.02
  6212.6  265.89  6252.9  268.89  6323.5   277.3  6351.2   278.6  6444.4  288.53
  6464.6  292.31  6504.9  295.73  6555.3  302.88  6585.5   304.9  6635.9  310.84
#Mann= 7 ,-1 , 0
  3000.4     .16       0  3035.3     .05       0  3625.9     .16       0
  5322.7     .12       0  5323.5     .16       0  5564.6     .07       0
  5570.6     .16       0
Bank Sta=3504.5,6252.9
XS Rating Curve= 0 ,0
Exp/Cntr=0.3,0.1

Type RM Length L Ch R = 1 ,19159   ,541,541,541
BEGIN DESCRIPTION:
BLISS CREEK 30.0
END DESCRIPTION:
XS GIS Cut Line= 3
      3641599.59      10521960.2      3643199.61     10520710.19
       3644199.6     10518510.21
#Sta/Elev= 30
  2986.3  319.51  3049.8  316.17  3078.6  313.33  3113.2  307.21  3278.2  293.92
  3399.6  278.95  3519.9   268.1  3563.3  265.58  3715.1  265.21  3805.7  266.24
  4147.6  262.34    4446  262.22  4460.5  263.94  4529.3  262.42    4995  263.86
  5694.8  261.94  5697.5  261.44  5700.8  261.94    5779     263  5929.3  263.11
  5995.6  263.27  6452.4  267.65  6565.5  267.87  6752.3  271.77  6873.1  278.51
    6998  281.39  7096.2  282.77  7208.3  285.62  7373.4  293.25  7433.3  296.85
#Mann= 13 ,-1 , 0
  2986.3     .16       0  3113.2     .05       0  3715.1     .16       0
  4529.3     .12       0  5694.8     .07       0  5700.8     .12       0
    5779     .16       0  5929.3     .12       0  5995.6     .16       0
    6998     .12       0  7096.2     .16       0  7208.3     .12       0
  7373.4     .16       0
Bank Sta=3519.9,6452.4
XS Rating Curve= 0 ,0
Exp/Cntr=0.3,0.1

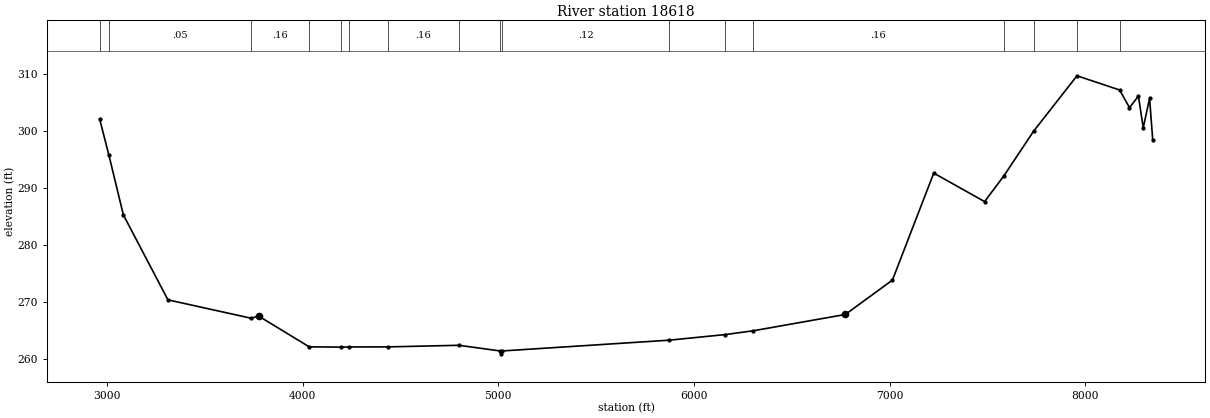
Type RM Length L Ch R = 1 ,18618   ,474,474,474
BEGIN DESCRIPTION:
BLISS CREEK 29.0
END DESCRIPTION:
XS GIS Cut Line= 3
      3641849.61     10522410.19      3643449.61     10521160.19
      3644449.61     10517960.19
#Sta/Elev= 30
  2962.6  302.13  3010.2  295.75  3083.8   285.3  3311.7  270.38    3737  267.15
  3774.8  267.54  4033.9  262.13  4197.3  262.08  4236.5  262.11  4435.8  262.12
  4798.4   262.4  5011.5   261.4  5014.2   260.9  5017.5   261.4  5874.7   263.3
  6159.6  264.28  6302.1  264.94  6774.1  267.81    7015  273.85  7226.1  292.63
    7486  287.63    7584  292.12  7736.5  299.99  7958.4  309.72  8176.5  307.22
  8226.7  304.12  8272.3  306.16  8296.9  300.59  8329.4  305.76  8345.6  298.38
#Mann= 17 ,-1 , 0
  2962.6     .16       0  3010.2     .05       0    3737     .16       0
  4033.9     .12       0  4197.3     .16       0  4236.5     .12       0
  4435.8     .16       0  4798.4     .12       0  5011.5     .07       0
  5017.5     .12       0  5874.7     .16       0  6159.6     .05       0
  6302.1     .16       0    7584     .12       0  7736.5     .05       0
  7958.4     .16       0  8176.5     .05       0
Bank Sta=3774.8,6774.1
XS Rating Curve= 0 ,0
Exp/Cntr=0.3,0.1