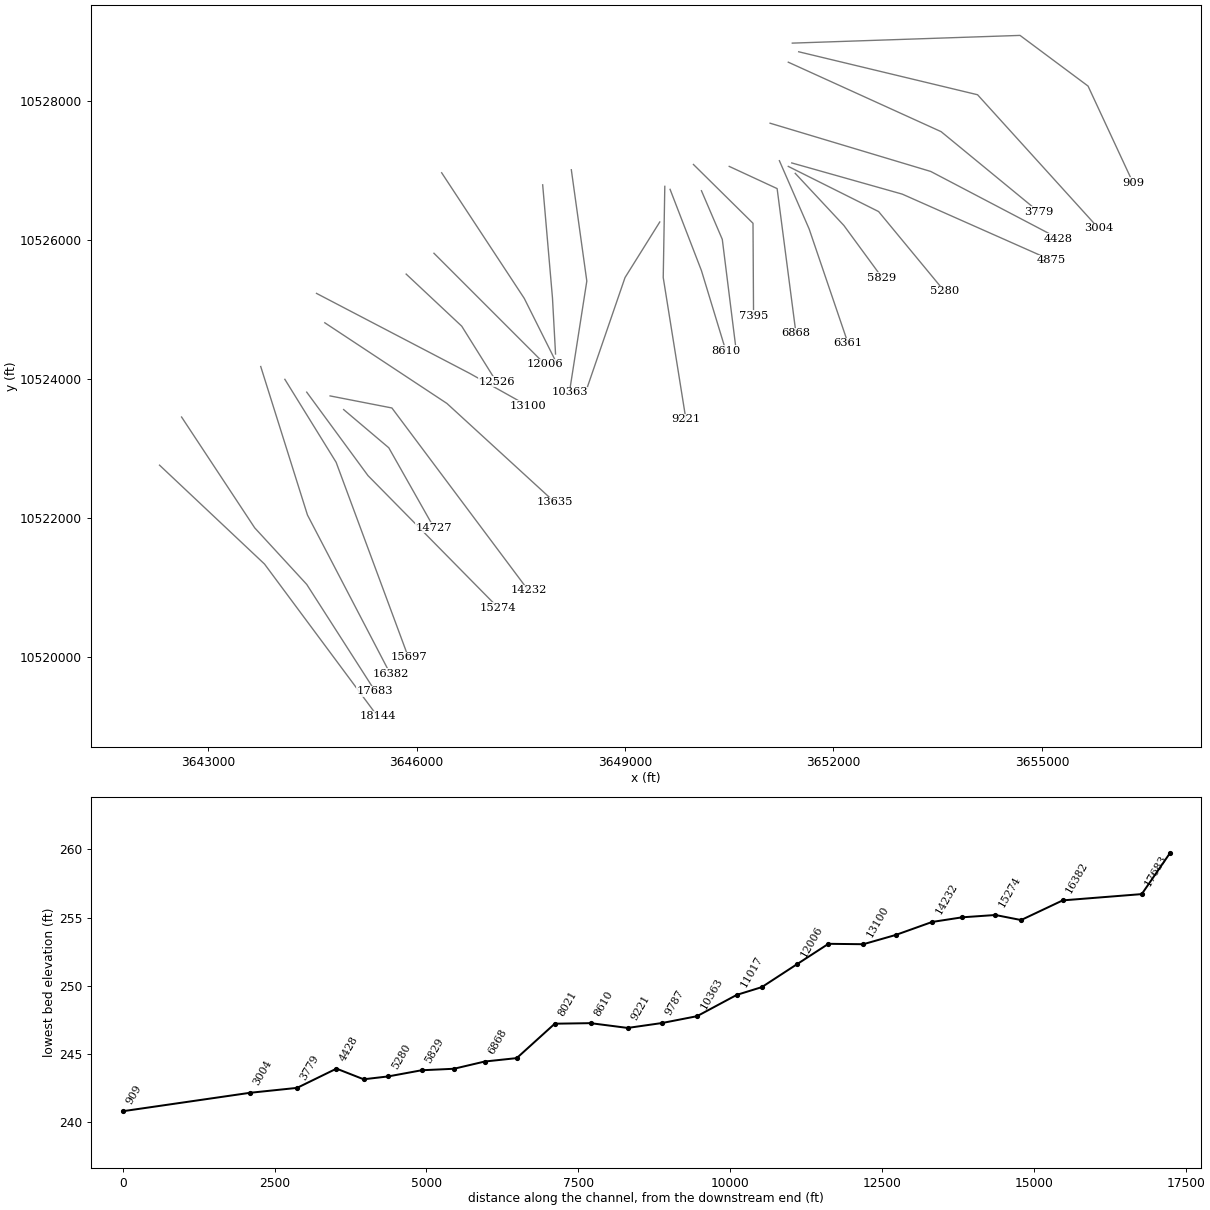
HEC-RAS study BLISS CREEK.prj: BLISS CREEK Base Level Engineering

--- BLISS CREEK.g01 (geometry) --- (continued)

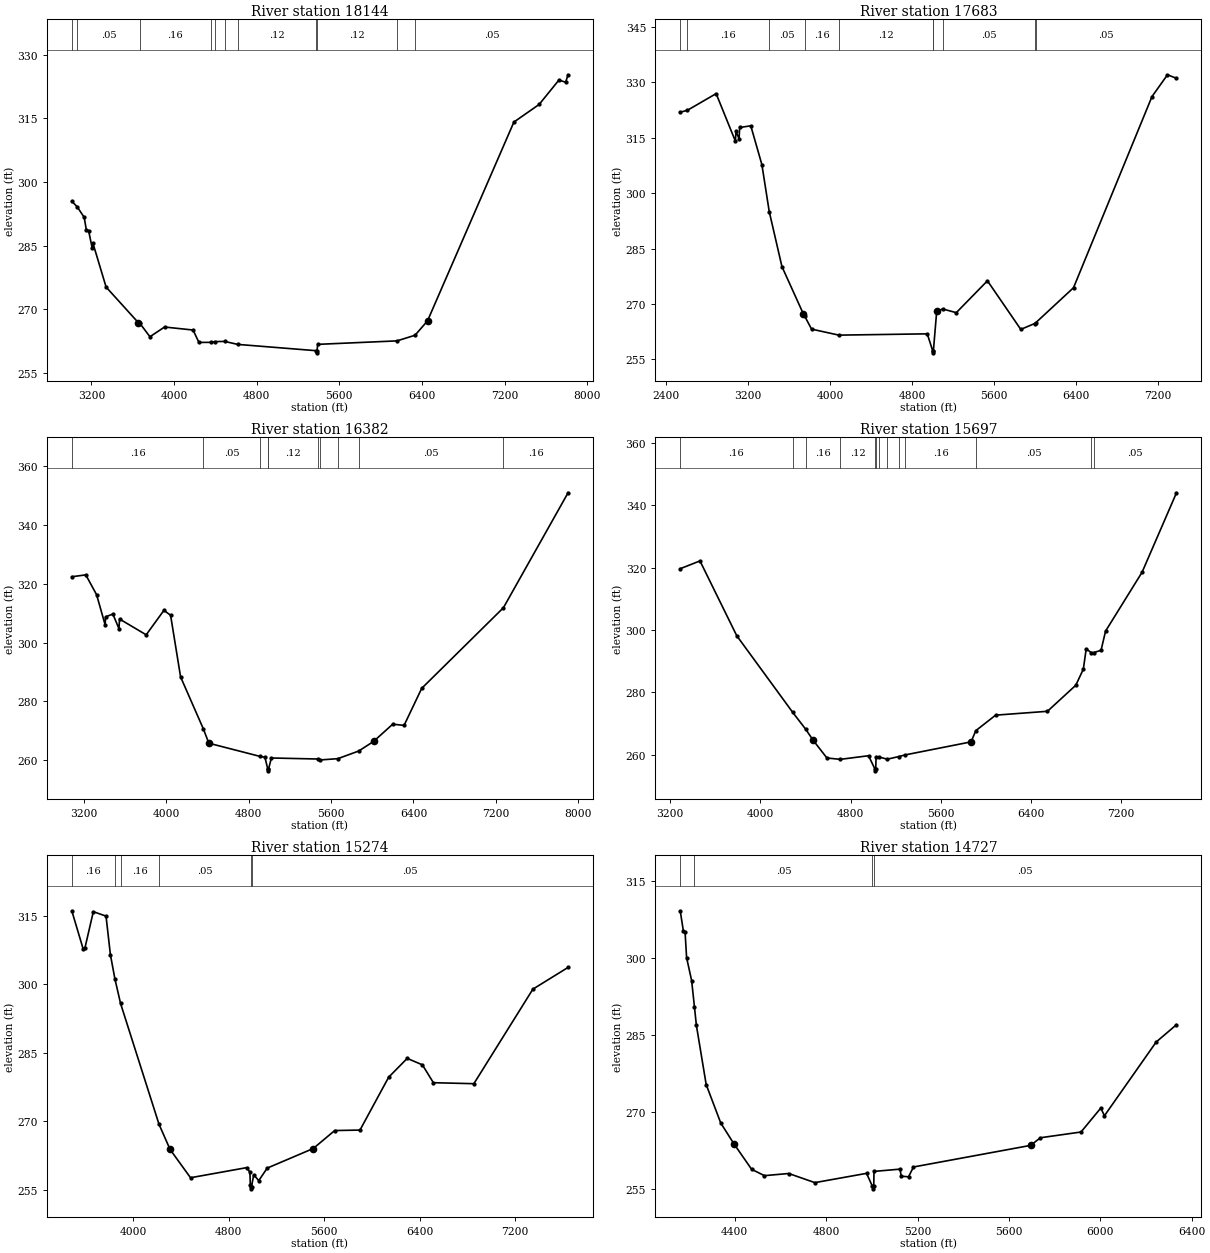
Type RM Length L Ch R = 1 ,18144   ,461,461,461
BEGIN DESCRIPTION:
BLISS CREEK 28.0
END DESCRIPTION:
XS GIS Cut Line= 3
      3642299.64     10522760.16      3643810.44     10521337.12
      3645438.03      10519145.3
#Sta/Elev= 30
  3009.9  295.46  3062.1  294.14  3130.2  291.65  3151.3   288.6  3172.7  288.52
  3207.9  284.36  3215.2  285.51  3342.2  275.21  3653.8  266.83  3668.5  266.67
  3766.6   263.5  3908.2  265.79  4184.2  265.08  4240.8  262.16  4353.8  262.17
    4399  262.35  4491.2  262.39  4616.3  261.69  5379.1   260.2  5381.9   259.7
  5385.1   260.2  5390.5   261.7  6158.7  262.52  6333.8  263.85  6454.4  267.24
    7291  314.13  7535.2  318.28  7727.1  324.04  7791.8  323.52  7815.4  325.28
#Mann= 11 ,-1 , 0
  3009.9     .16       0  3062.1     .05       0  3668.5     .16       0
  4353.8     .07       0    4399     .05       0  4491.2     .16       0
  4616.3     .12       0  5379.1     .07       0  5385.1     .12       0
  6158.7     .16       0  6333.8     .05       0
Bank Sta=3653.8,6454.4
XS Rating Curve= 0 ,0
Exp/Cntr=0.3,0.1

Type RM Length L Ch R = 1 ,17683   ,1301,1301,1301
BEGIN DESCRIPTION:
BLISS CREEK 27.0
END DESCRIPTION:
XS GIS Cut Line= 4
      3642616.89     10523452.96      3643669.38     10521857.95
      3644418.08     10521044.15      3645404.46     10519504.97
#Sta/Elev= 30
  2536.3  321.94  2606.7  322.47  2887.1  326.98  3074.8  314.11  3080.8  316.72
  3110.9  314.77  3116.9   317.8  3225.3  318.26  3333.7  307.74  3405.4  295.01
  3529.4   280.1  3737.7  267.32  3751.9  266.65  3818.4  263.15    4085  261.52
  4948.1  261.87  5001.8  257.22  5004.6  256.72  5007.8  257.22  5040.5  268.04
    5100   268.6  5231.7  267.61  5535.6  276.25  5861.2  263.07  5997.2  264.67
  6004.9  264.82    6376  274.37    7142  326.18  7293.3  332.09  7381.2  331.13
#Mann= 10 ,-1 , 0
  2536.3     .05       0  2606.7     .16       0  3405.4     .05       0
  3751.9     .16       0    4085     .12       0  5001.8     .07       0
  5007.8     .12       0    5100     .05       0  5997.2     .16       0
  6004.9     .05       0
Bank Sta=3737.7,5040.5
XS Rating Curve= 0 ,0
Exp/Cntr=0.3,0.1

Type RM Length L Ch R = 1 ,16382   ,685,685,685
BEGIN DESCRIPTION:
BLISS CREEK 26.0
END DESCRIPTION:
XS GIS Cut Line= 3
       3643756.2     10524179.98      3644428.93     10522042.41
      3645621.92     10519754.04
#Sta/Elev= 30
  3080.2  322.41  3216.3  323.05  3321.1  316.29  3403.9  306.05  3409.1  308.76
  3479.1  309.69  3538.6  304.73  3543.9  308.01  3802.9  302.62  3975.3  310.96
  4040.1  309.28  4137.2  288.28    4357  270.67    4412  265.67  4910.3  261.17
  4956.5  260.89    4985  256.76  4987.7  256.26    4991  256.76  5019.4  260.64
  5473.6  260.29  5492.3  259.97  5665.2  260.41  5868.4  263.02  6011.6  266.27
  6198.2  272.16  6308.6  271.75  6479.7  284.37  7273.7  311.85  7901.8  351.03
#Mann= 10 ,-1 , 0
  3080.2     .16       0    4357     .05       0  4910.3     .12       0
    4985     .07       0    4991     .12       0  5473.6     .07       0
  5492.3     .12       0  5665.2     .16       0  5868.4     .05       0
  7273.7     .16       0
Bank Sta=4412,6011.6
XS Rating Curve= 0 ,0
Exp/Cntr=0.3,0.1

Type RM Length L Ch R = 1 ,15697   ,423,423,423
BEGIN DESCRIPTION:
BLISS CREEK 25.0
END DESCRIPTION:
XS GIS Cut Line= 3
      3644103.41     10523995.53      3644841.26     10522801.96
      3645882.27      10519993.4
#Sta/Elev= 30
  3290.5  319.69  3465.6  322.19  3791.8  298.17  4286.7  273.63  4401.7  268.22
  4469.2  264.61  4590.9  258.94    4710  258.51  4959.6  259.67  5017.4  255.32
  5020.1  254.82  5023.4  255.32  5026.2   259.2  5052.7  259.25  5126.6  258.56
  5229.7  259.42  5285.2  259.94  5868.7  264.12  5909.9   267.7  6085.9  272.69
  6545.4  273.93  6796.6  282.29  6863.6  287.47  6888.7  293.96  6933.8  292.75
  6953.6  292.75  7020.5   293.5  7060.3  299.66  7383.9  318.55    7689  344.06
#Mann= 13 ,-1 , 0
  3290.5     .16       0  4286.7     .05       0  4401.7     .16       0
    4710     .12       0  5017.4     .07       0  5023.4     .16       0
  5052.7     .12       0  5126.6     .16       0  5229.7     .12       0
  5285.2     .16       0  5909.9     .05       0  6933.8     .08       0
  6953.6     .05       0
Bank Sta=4469.2,5868.7
XS Rating Curve= 0 ,0
Exp/Cntr=0.3,0.1

Type RM Length L Ch R = 1 ,15274   ,547,547,547
BEGIN DESCRIPTION:
BLISS CREEK 24.0
END DESCRIPTION:
XS GIS Cut Line= 3
      3644418.09     10523811.06      3645299.61     10522610.19
      3647174.17     10520707.76
#Sta/Elev= 30
  3484.2  316.07    3579  307.76  3593.7  307.85  3664.7  315.88  3771.2   314.9
  3807.8  306.47  3845.4  301.19  3893.1  295.77  4215.3  269.33  4308.3  263.81
  4479.6  257.62  4951.9  259.84  4977.4   258.8    4981  255.99    4985  255.69
  4987.7  255.19    4991  255.69  5009.3  258.26  5051.7  256.99  5122.4  259.73
 5508.52  264.02  5688.1  267.95  5900.3  268.06  6140.6  279.63  6296.2  283.75
  6423.5  282.34  6515.5  278.43  6854.9  278.21  7349.8  298.91  7644.7  303.67
#Mann= 6 ,-1 , 0
  3484.2     .16       0  3845.4     .05       0  3893.1     .16       0
  4215.3     .05       0    4985     .03       0    4991     .05       0
Bank Sta=4308.3,5508.52
XS Rating Curve= 0 ,0
Exp/Cntr=0.3,0.1

Type RM Length L Ch R = 1 ,14727   ,495,495,495
BEGIN DESCRIPTION:
BLISS CREEK 23.0
END DESCRIPTION:
XS GIS Cut Line= 3
      3644949.62     10523560.18      3645599.61     10523010.19
      3646249.59     10521860.23
#Sta/Elev= 30
    4161  309.23  4174.7  305.33  4182.4  305.01    4189  300.08    4211  295.63
  4223.3   290.5  4231.8   286.9  4274.7  275.35  4338.4  267.86  4395.6  263.83
  4473.6  258.83  4529.6  257.59  4636.1  258.01  4750.5  256.23  4976.7  258.04
  5002.3  255.52  5005.1  255.02  5008.3  255.52  5009.2  258.42  5122.9  258.86
  5128.7  257.48  5160.5  257.37  5182.1  259.28  5694.6  263.49  5737.9  264.98
  5915.5   266.1  6002.1  270.77    6018  269.27  6244.6  283.65  6333.4  287.02
#Mann= 4 ,-1 , 0
    4161     .16       0  4223.3     .05       0  5002.3     .03       0
  5008.3     .05       0
Bank Sta=4395.6,5694.6
XS Rating Curve= 0 ,0
Exp/Cntr=0.3,0.1

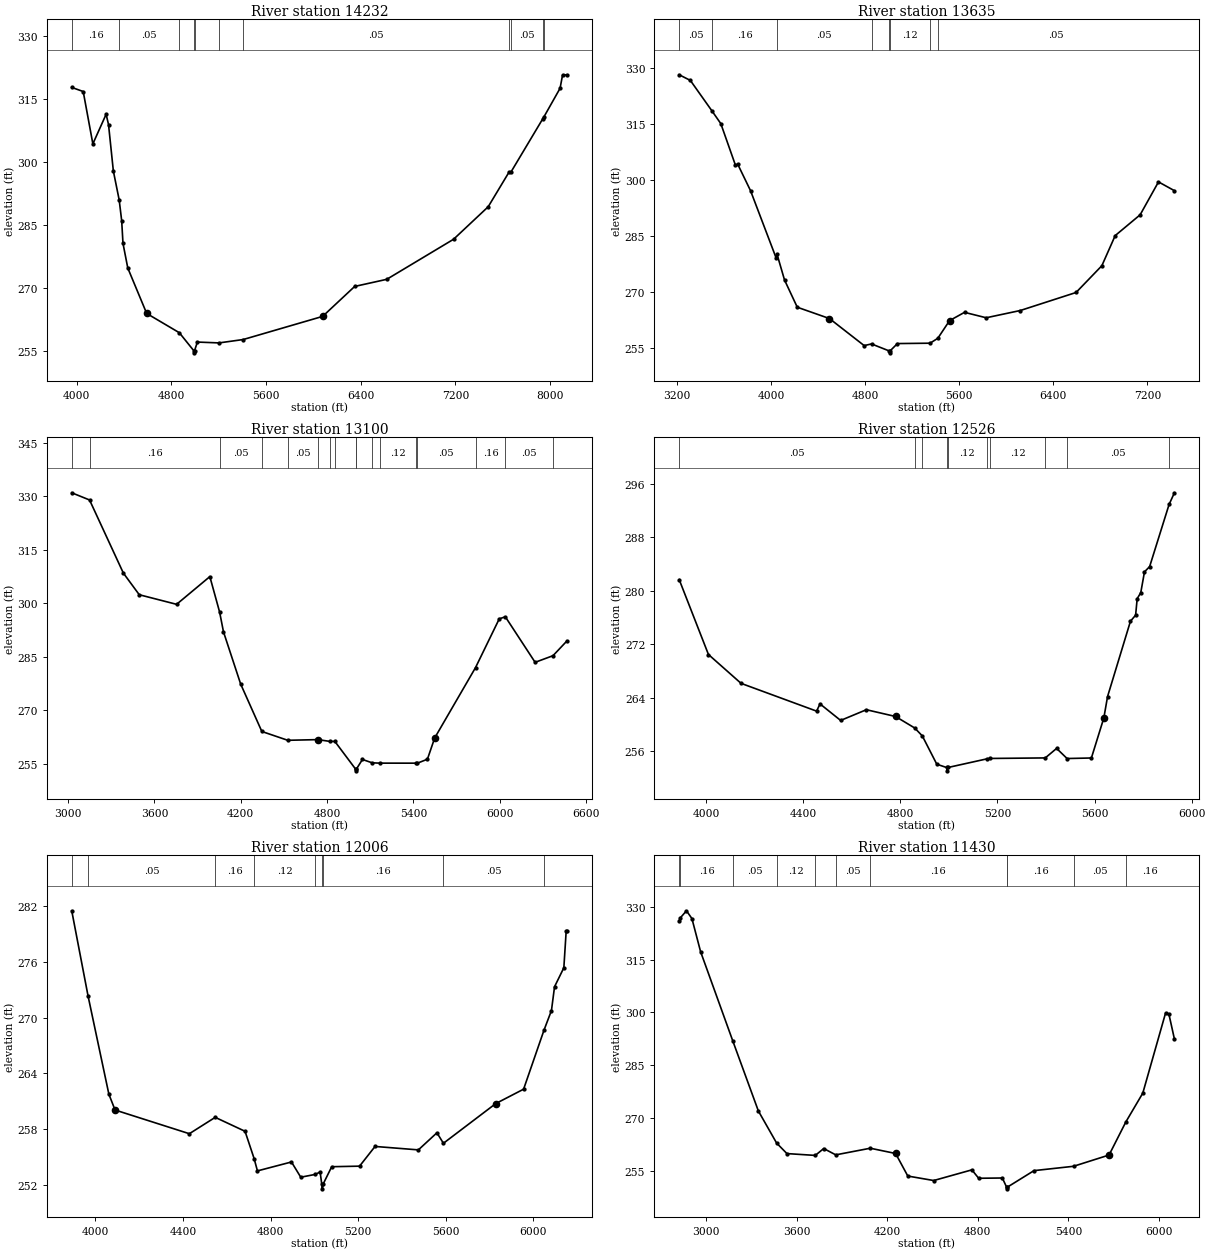
Type RM Length L Ch R = 1 ,14232   ,597,597,597
BEGIN DESCRIPTION:
BLISS CREEK 22.0
END DESCRIPTION:
XS GIS Cut Line= 3
      3644754.42     10523756.83      3645644.21     10523583.21
      3647608.22      10520957.3
#Sta/Elev= 30
  3957.3  317.76  4054.3  316.78  4135.8  304.34  4247.9  311.37  4268.2  308.94
    4309   297.9  4358.2  291.04  4379.4   286.1  4390.5  280.69    4431  274.84
  4590.8  264.04  4866.7  259.46  4989.2  255.18  4991.9  254.68  4995.2  255.18
  5019.3  257.24    5202  257.04  5406.3  257.84    6078  263.34    6349  270.46
  6619.9  272.15  7184.7  281.67  7477.6   289.4  7655.2   297.7  7671.5  297.72
  7940.1  310.36  7946.5  310.65    8085  317.55  8105.9  320.67    8143  320.76
#Mann= 11 ,-1 , 0
  3957.3     .16       0  4358.2     .05       0  4866.7     .12       0
  4989.2     .07       0  4995.2     .12       0    5202     .16       0
  5406.3     .05       0  7655.2     .16       0  7671.5     .05       0
  7940.1     .16       0  7946.5     .05       0
Bank Sta=4590.8,6078
XS Rating Curve= 0 ,0
Exp/Cntr=0.3,0.1

Type RM Length L Ch R = 1 ,13635   ,535,535,535
BEGIN DESCRIPTION:
BLISS CREEK 21.0
END DESCRIPTION:
XS GIS Cut Line= 3
      3644678.49     10524809.34      3646436.31     10523648.31
      3647987.93      10522226.9
#Sta/Elev= 30
  3218.4   328.1  3313.1  326.59  3496.7  318.44    3572  315.04  3695.4  304.01
  3716.5  304.14  3824.8   297.1  4041.6  279.18  4050.7  280.04  4113.8  273.22
  4222.2  265.93  4496.1   262.9    4791  255.67  4853.6  256.11  5004.8  254.23
  5007.5  253.73  5010.8  254.23    5074  256.21  5351.5  256.31  5417.3  257.62
  5517.4  262.35  5644.4  264.56  5828.8  263.11  6118.6  265.05  6592.8  269.87
  6812.3  277.03  6925.8  285.09  7137.9  290.65  7293.9  299.45  7429.3   297.1
#Mann= 8 ,-1 , 0
  3218.4     .05       0  3496.7     .16       0  4050.7     .05       0
  4853.6     .12       0  5004.8     .07       0  5010.8     .12       0
  5351.5     .16       0  5417.3     .05       0
Bank Sta=4496.1,5517.4
XS Rating Curve= 0 ,0
Exp/Cntr=0.3,0.1

Type RM Length L Ch R = 1 ,13100   ,574,574,574
BEGIN DESCRIPTION:
BLISS CREEK 20.0
END DESCRIPTION:
XS GIS Cut Line= 3
      3644559.12     10525232.53      3646761.83     10524082.34
      3647595.95     10523616.53
#Sta/Elev= 30
  3025.8  330.97  3149.6  328.95  3384.5  308.46  3494.9   302.4  3754.3  299.71
  3985.3  307.48  4053.3  297.52  4079.9  292.02  4199.6  277.35  4346.5  264.08
  4526.6  261.61  4736.5   261.8  4817.3  261.31  4853.7   261.3  4997.6  253.55
  5000.3  253.05  5003.6  253.55  5045.5  256.24  5112.6   255.3  5164.6  255.21
  5414.8   255.2    5424  255.14  5496.9  256.31  5547.1  262.24  5831.2  281.99
    5996  295.65  6038.2  296.22  6245.1  283.46  6369.4  285.32  6466.1  289.45
#Mann= 17 ,-1 , 0
  3025.8     .05       0  3149.6     .16       0  4053.3     .05       0
  4346.5      .1       0  4526.6     .05       0  4736.5     .16       0
  4817.3     .05       0  4853.7     .12       0  4997.6     .07       0
  5003.6     .12       0  5112.6     .16       0  5164.6     .12       0
  5414.8     .16       0    5424     .05       0  5831.2     .16       0
  6038.2     .05       0  6369.4     .12       0
Bank Sta=4736.5,5547.1
XS Rating Curve= 0 ,0
Exp/Cntr=0.3,0.1

Type RM Length L Ch R = 1 ,12526   ,520,520,520
BEGIN DESCRIPTION:
BLISS CREEK 19.0
END DESCRIPTION:
XS GIS Cut Line= 3
      3645849.63     10525510.17      3646649.61     10524760.19
      3647149.63     10523960.15
#Sta/Elev= 30
    3889  281.64  4009.4  270.46  4143.7  266.15  4454.9     262    4469  263.08
    4554  260.61    4660  262.21  4780.2   261.2  4859.1  259.48  4890.4   258.3
  4950.1  254.07  4990.2  253.58    4993  253.08  4996.2  253.58  5155.3  254.86
  5167.8  254.93    5397  255.01  5443.7  256.43  5486.8  254.92    5587     255
  5638.3  260.99  5653.6  264.18  5747.9  275.43  5769.2  276.34  5775.6   278.8
  5790.4   279.7  5805.7  282.81  5826.9  283.59    5907  292.87    5929  294.62
#Mann= 10 ,-1 , 0
    3889     .05       0  4859.1     .16       0  4890.4     .12       0
  4990.2     .07       0  4996.2     .12       0  5155.3     .16       0
  5167.8     .12       0    5397     .16       0  5486.8     .05       0
    5907     .16       0
Bank Sta=4780.2,5638.3
XS Rating Curve= 0 ,0
Exp/Cntr=0.3,0.1

Type RM Length L Ch R = 1 ,12006   ,576,576,576
BEGIN DESCRIPTION:
BLISS CREEK 18.0
END DESCRIPTION:
XS GIS Cut Line= 3
      3646249.64     10525810.16      3647049.61     10525010.19
      3647849.61     10524210.19
#Sta/Elev= 30
  3891.6  281.49  3966.2  272.32  4061.3  261.76  4089.5  260.06    4429  257.51
  4547.2  259.27  4683.5  257.77    4725  254.83  4740.1  253.51  4895.6  254.47
  4938.1  252.83  5003.7  253.13  5026.5  253.39  5034.1  252.08  5036.8  251.58
  5040.1  252.08  5079.5  253.96  5206.8  254.02  5277.5  256.14  5475.5  255.77
  5560.3  257.61  5589.9  256.48    5829  260.75  5956.3   262.3  6049.7  268.66
  6083.6  270.76  6097.7  273.32  6140.2  275.36  6150.8  279.28  6154.3  279.28
#Mann= 9 ,-1 , 0
  3891.6     .16       0  3966.2     .05       0  4547.2     .16       0
    4725     .12       0  5003.7     .16       0  5034.1     .07       0
  5040.1     .16       0  5589.9     .05       0  6049.7     .16       0
Bank Sta=4089.5,5829
XS Rating Curve= 0 ,0
Exp/Cntr=0.3,0.1

Type RM Length L Ch R = 1 ,11430   ,413,413,413
BEGIN DESCRIPTION:
BLISS CREEK 17.0
END DESCRIPTION:
XS GIS Cut Line= 3
      3646360.38      10526968.6      3647549.61     10525160.19
      3648049.59     10524160.22
#Sta/Elev= 30
  2820.8  325.92    2828  326.84  2868.8  328.86    2905  326.65  2962.5  317.24
  3175.1     292  3345.5  272.01  3466.5   262.9  3534.7  259.92  3722.5   259.4
  3778.6  261.35  3858.4  259.56  4087.3  261.44  4255.1  259.95    4336  253.54
  4507.7  252.27  4760.7   255.3  4805.7  252.91  4962.6  252.99  4990.6  250.41
  4993.3  249.91  4996.6  250.41  5172.5  255.08  5434.4  256.31    5670  259.51
  5781.6  268.93  5893.6  277.08  6044.5  299.82  6066.9  299.48  6103.2  292.45
#Mann= 11 ,-1 , 0
  2820.8     .08       0    2828     .16       0  3175.1     .05       0
  3466.5     .12       0  3722.5     .16       0  3858.4     .05       0
  4087.3     .16       0  4990.6     .07       0  4996.6     .16       0
  5434.4     .05       0  5781.6     .16       0
Bank Sta=4255.1,5670
XS Rating Curve= 0 ,0
Exp/Cntr=0.3,0.1

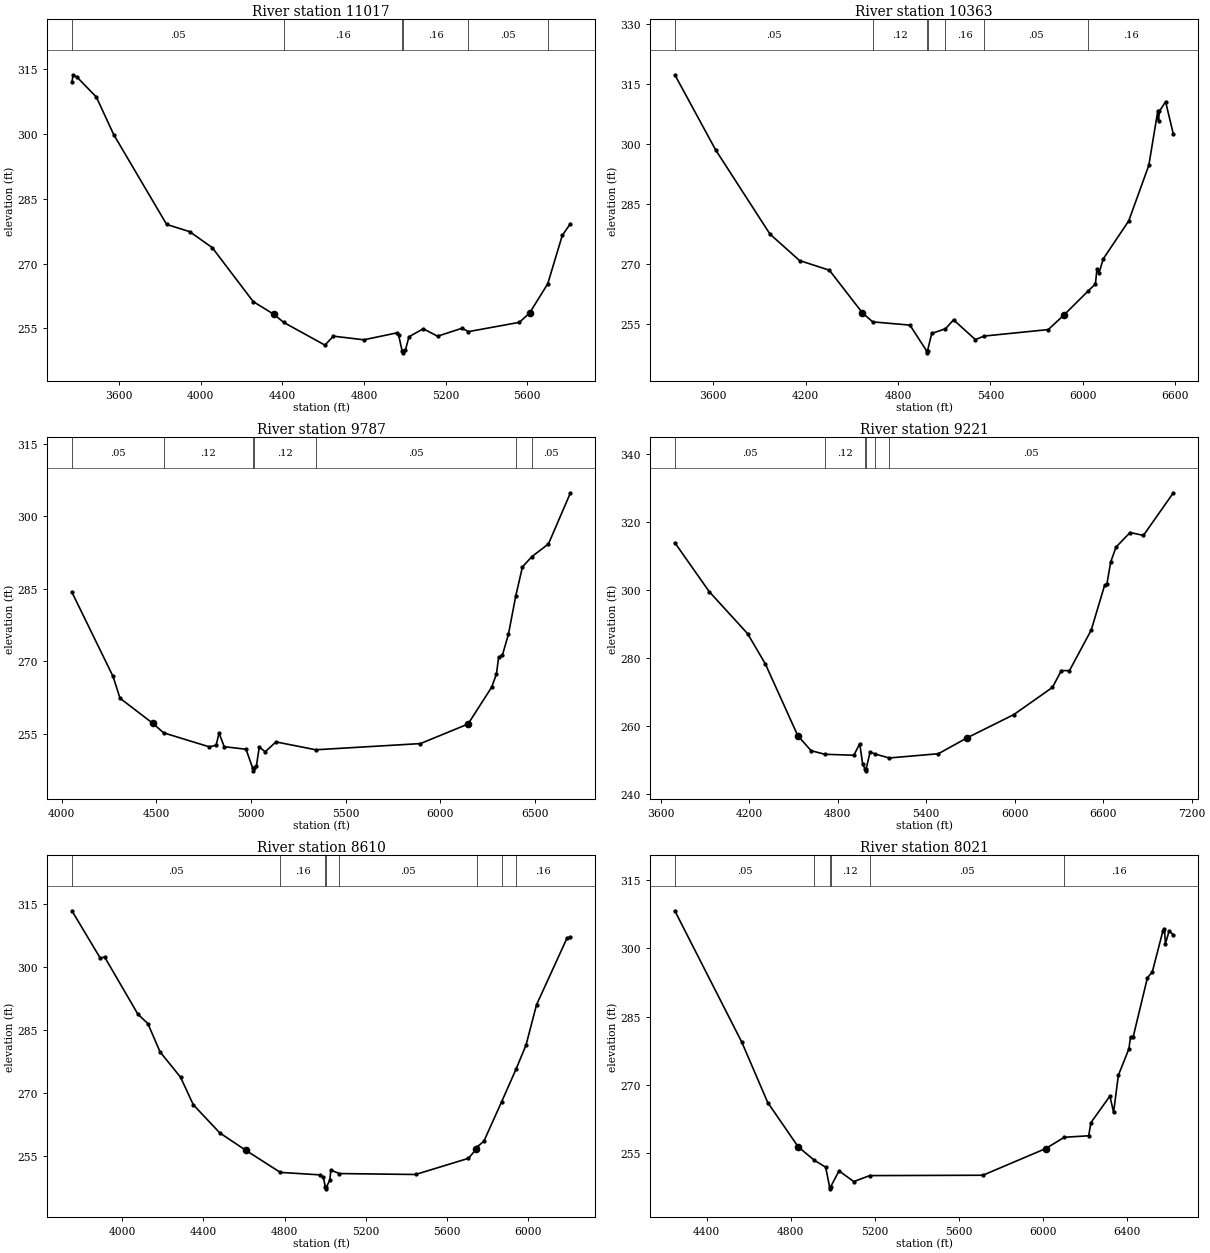
Type RM Length L Ch R = 1 ,11017   ,654,654,654
BEGIN DESCRIPTION:
BLISS CREEK 16.0
END DESCRIPTION:
XS GIS Cut Line= 3
      3647814.35     10526795.05      3647955.41     10525167.41
      3647999.61     10524360.16
#Sta/Elev= 30
  3368.9   312.1  3375.4  313.71  3393.9  313.17  3488.5  308.57  3574.5  299.79
  3832.9  279.07  3945.9  277.39  4056.3   273.7  4257.1   261.2  4357.5  258.28
  4406.5  256.38  4608.4  251.13  4649.8   253.2  4799.1  252.36  4959.7  253.95
  4969.7  253.37  4986.1  249.84  4988.8  249.34  4992.1  249.84  5002.6  249.97
  5019.9  253.06    5090  254.91  5160.1  253.19  5280.3  255.04  5311.4  254.25
  5560.7   256.4  5610.8  258.55  5699.6  265.31    5771  276.52  5811.1  279.27
#Mann= 6 ,-1 , 0
  3368.9     .05       0  4406.5     .16       0  4986.1     .07       0
  4992.1     .16       0  5311.4     .05       0  5699.6     .16       0
Bank Sta=4357.5,5610.8
XS Rating Curve= 0 ,0
Exp/Cntr=0.3,0.1

Type RM Length L Ch R = 1 ,10363   ,576,576,576
BEGIN DESCRIPTION:
BLISS CREEK 15.0
END DESCRIPTION:
XS GIS Cut Line= 3
      3648226.67     10527012.05      3648449.61     10525410.19
      3648199.61      10523810.2
#Sta/Elev= 30
    3351  317.36  3615.4   298.6  3968.8  277.49  4160.6  270.88  4354.6  268.45
  4569.4  257.76  4635.6  255.53  4877.4  254.72  4985.5  248.28  4988.3  247.78
  4991.5  248.28  5018.9  252.64    5108   253.8  5160.6  256.03  5302.3  251.09
  5359.4  251.98  5775.5   253.6  5879.2  257.32  6035.7  263.31  6081.6  265.02
  6091.8   268.8  6104.4  267.68  6132.3  271.29  6297.7  280.79  6428.3  294.71
    6486  308.18  6491.1  305.84  6496.6   308.2  6537.1  310.63  6587.7  302.46
#Mann= 7 ,-1 , 0
    3351     .05       0  4635.6     .12       0  4985.5     .07       0
  4991.5     .12       0    5108     .16       0  5359.4     .05       0
  6035.7     .16       0
Bank Sta=4569.4,5879.2
XS Rating Curve= 0 ,0
Exp/Cntr=0.3,0.1

Type RM Length L Ch R = 1 ,9787    ,566,566,566
BEGIN DESCRIPTION:
BLISS CREEK 14.0
END DESCRIPTION:
XS GIS Cut Line= 3
      3649499.62     10526260.21      3648999.61     10525460.19
      3648449.61      10523860.2
#Sta/Elev= 30
  4053.2  284.26  4270.8  266.81  4307.4  262.31  4480.7  257.12  4537.7  255.15
  4779.1  252.25  4815.6  252.58  4830.9  255.11  4858.1  252.28  4973.6  251.75
  5009.2  247.78    5012  247.28  5015.2  247.78  5028.3  248.24  5043.5  252.22
  5074.7  251.22  5131.9  253.27  5342.2  251.64  5895.4  252.92  6147.1  256.97
    6272   264.6  6297.3  267.34  6308.6  270.75    6329  271.26  6360.5  275.54
  6399.7  283.55  6434.7   289.5  6484.4  291.62  6572.2  294.25  6688.5  304.84
#Mann= 7 ,-1 , 0
  4053.2     .05       0  4537.7     .12       0  5009.2     .07       0
  5015.2     .12       0  5342.2     .05       0  6399.7     .16       0
  6484.4     .05       0
Bank Sta=4480.7,6147.1
XS Rating Curve= 0 ,0
Exp/Cntr=0.3,0.1

Type RM Length L Ch R = 1 ,9221    ,611,611,611
BEGIN DESCRIPTION:
BLISS CREEK 13.0
END DESCRIPTION:
XS GIS Cut Line= 3
      3649572.16     10526773.33      3649549.61     10525460.19
      3649875.98     10523420.47
#Sta/Elev= 30
  3696.7  313.89  3929.9  299.52  4189.9  287.19  4309.9  278.34    4530  257.25
    4620  252.84  4713.3  251.78    4910   251.5    4950  254.88    4970  248.83
    4987  247.42  4989.8  246.92    4993  247.42  5020.2  252.49  5051.6  251.88
  5150.3   250.7  5482.8  251.94  5679.1  256.64  5994.3  263.43  6255.7   271.4
  6316.4  276.34  6371.5  276.34    6519  288.25  6610.1  301.46  6624.7  301.65
  6650.6  308.16  6686.7  312.59  6782.3  316.87  6872.8  316.03  7075.7  328.54
#Mann= 6 ,-1 , 0
  3696.7     .05       0  4713.3     .12       0    4987     .07       0
    4993     .12       0  5051.6     .16       0  5150.3     .05       0
Bank Sta=4530,5679.1
XS Rating Curve= 0 ,0
Exp/Cntr=0.3,0.1

Type RM Length L Ch R = 1 ,8610    ,589,589,589
BEGIN DESCRIPTION:
BLISS CREEK 12.0
END DESCRIPTION:
XS GIS Cut Line= 3
      3649648.12      10526729.9      3650099.61     10525560.19
      3650449.61     10524410.19
#Sta/Elev= 30
  3752.3  313.34  3891.3  302.14  3913.7  302.33  4077.4  288.77  4126.6  286.53
  4186.5  279.81  4287.9  273.76  4350.2  267.25  4480.9  260.55  4609.5  256.41
  4778.9  251.18    4974  250.59  4991.1  249.98  5000.4  247.77  5003.2  247.27
  5006.4  247.77  5022.5  249.27  5027.8  251.71    5070   250.9  5445.1  250.68
  5705.7  254.52  5743.8  256.68  5747.5  257.18  5781.9  258.61  5868.8  267.93
  5940.8  275.78  5989.4  281.45    6041     291  6191.8  306.92  6208.2  307.03
#Mann= 8 ,-1 , 0
  3752.3     .05       0  4778.9     .16       0  5000.4     .07       0
  5006.4     .16       0    5070     .05       0  5747.5     .16       0
  5868.8     .12       0  5940.8     .16       0
Bank Sta=4609.5,5743.8
XS Rating Curve= 0 ,0
Exp/Cntr=0.3,0.1

Type RM Length L Ch R = 1 ,8021    ,626,626,626
BEGIN DESCRIPTION:
BLISS CREEK 11.0
END DESCRIPTION:
XS GIS Cut Line= 3
      3650099.61     10526710.19      3650399.61     10526010.19
      3650599.61     10524410.22
#Sta/Elev= 30
  4247.9  308.17    4567  279.36  4690.3  266.15  4835.4  256.43  4912.5  253.48
    4966  251.98  4984.7  247.73  4987.5  247.23  4990.7  247.73  5029.6  251.17
  5100.2  248.82  5175.7  250.13  5714.9  250.21  6014.7  256.07  6102.3  258.53
  6218.8  258.86  6228.9  261.71  6319.6  267.56  6337.2  264.01  6359.9  272.11
  6410.3  277.94  6417.9  280.58  6430.5  280.53  6498.5  293.54  6521.2   294.7
  6571.5  303.67  6579.1  304.26  6584.1  300.96  6601.8  303.77  6621.9  302.89
#Mann= 6 ,-1 , 0
  4247.9     .05       0  4912.5     .12       0  4984.7     .07       0
  4990.7     .12       0  5175.7     .05       0  6102.3     .16       0
Bank Sta=4835.4,6014.7
XS Rating Curve= 0 ,0
Exp/Cntr=0.3,0.1

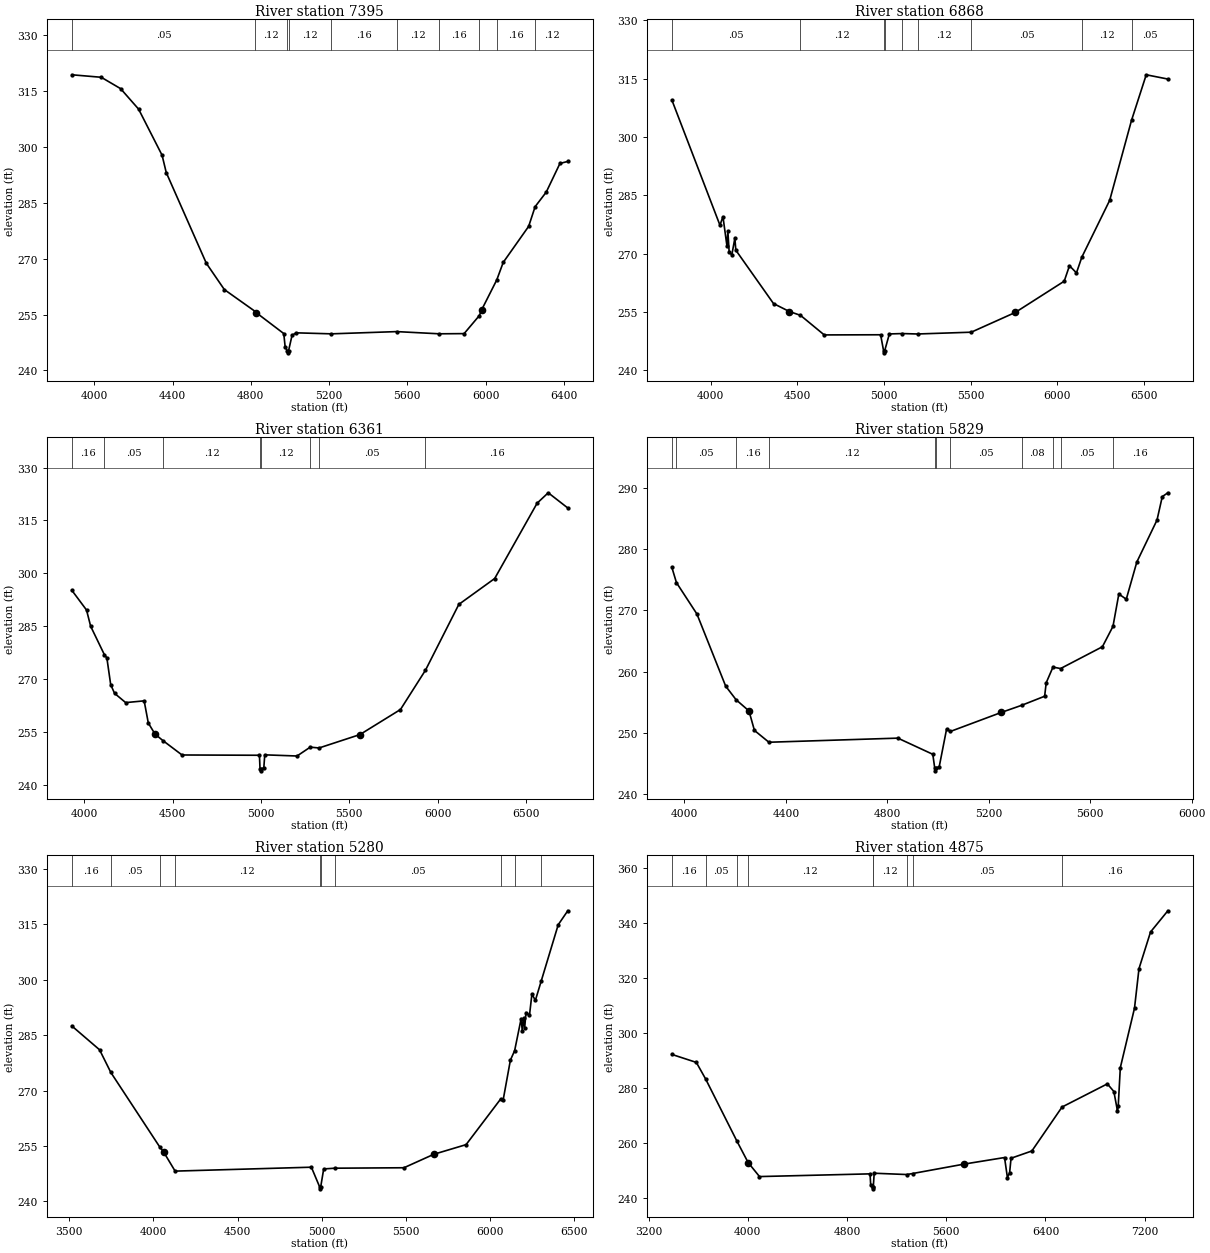
Type RM Length L Ch R = 1 ,7395    ,527,527,527
BEGIN DESCRIPTION:
BLISS CREEK 10.0
END DESCRIPTION:
XS GIS Cut Line= 3
      3649984.47     10527088.01      3650841.69     10526241.63
      3650849.61     10524910.21
#Sta/Elev= 30
  3884.4  319.35    4035  318.68    4134  315.63  4225.9  310.14  4346.1  297.76
  4367.4  293.11  4572.4  268.75  4664.4   261.7  4822.7   255.8    4827  255.52
  4968.4  249.88  4975.4  246.32  4986.6  245.21  4989.3  244.71  4992.6  245.21
  5010.8  249.43    5032  250.08  5211.8  249.81  5546.2  250.41  5763.2  249.82
  5890.5  249.87  5968.5  254.72  5980.5  256.29  6057.5  264.29  6090.5  268.99
  6220.5  278.66  6253.6  283.95  6310.5  287.86  6380.5  295.55  6420.5  296.09
#Mann= 10 ,-1 , 0
  3884.4     .05       0  4822.7     .12       0  4986.6     .07       0
  4992.6     .12       0  5211.8     .16       0  5546.2     .12       0
  5763.2     .16       0  5968.5     .05       0  6057.5     .16       0
  6253.6     .12       0
Bank Sta=4827,5980.5
XS Rating Curve= 0 ,0
Exp/Cntr=0.3,0.1

Type RM Length L Ch R = 1 ,6868    ,507,507,507
BEGIN DESCRIPTION:
BLISS CREEK 9.0
END DESCRIPTION:
XS GIS Cut Line= 3
      3650499.61     10527060.19      3651188.91     10526740.76
      3651460.18     10524657.47
#Sta/Elev= 30
  3776.8  309.51  4054.1   277.3  4071.5  279.49  4094.4     272  4099.9  275.69
  4107.4   270.3  4122.8  269.69  4140.2  273.97  4145.7  270.87    4363  257.14
  4454.6  255.09  4518.6  254.11  4655.6  249.07  4980.8  249.11    4998  244.96
  5000.7  244.46    5004  244.96  5031.2  249.32  5106.5  249.42  5193.5  249.31
  5503.4  249.77  5757.3  254.85  6039.7  262.89  6069.9  266.87  6110.3  265.03
  6141.3  269.08  6301.9  283.69  6427.8  304.27  6512.7     316  6637.4   314.9
#Mann= 9 ,-1 , 0
  3776.8     .05       0  4518.6     .12       0    4998     .07       0
    5004     .12       0  5106.5     .16       0  5193.5     .12       0
  5503.4     .05       0  6141.3     .12       0  6427.8     .05       0
Bank Sta=4454.6,5757.3
XS Rating Curve= 0 ,0
Exp/Cntr=0.3,0.1

Type RM Length L Ch R = 1 ,6361    ,532,532,532
BEGIN DESCRIPTION:
BLISS CREEK 8.0
END DESCRIPTION:
XS GIS Cut Line= 3
      3651221.48     10527142.21      3651649.61     10526160.19
      3652208.87     10524516.41
#Sta/Elev= 30
  3929.6  295.18  4013.1  289.56  4036.5  284.95  4114.3  276.87  4128.2  275.98
    4150  268.36  4171.8  265.92  4234.7  263.29  4339.3  263.79  4362.8   257.5
  4400.9  254.35  4445.4  252.52  4553.6  248.43  4991.9  248.35  4995.2  244.43
  4997.9  243.93  5001.2  244.43  5016.6  244.78    5022  248.47  5204.8  248.14
  5279.3  250.65  5329.4  250.42  5560.7  254.22  5790.2  261.33  5931.8  272.49
  6120.6  291.16  6323.5   298.5  6563.8  319.88  6626.6  322.83  6737.2  318.52
#Mann= 8 ,-1 , 0
  3929.6     .16       0  4114.3     .05       0  4445.4     .12       0
  4995.2     .07       0  5001.2     .12       0  5279.3     .07       0
  5329.4     .05       0  5931.8     .16       0
Bank Sta=4400.9,5560.7
XS Rating Curve= 0 ,0
Exp/Cntr=0.3,0.1

Type RM Length L Ch R = 1 ,5829    ,549,549,549
BEGIN DESCRIPTION:
BLISS CREEK 7.0
END DESCRIPTION:
XS GIS Cut Line= 3
      3651449.64     10526960.16      3652149.61     10526210.19
       3652699.6     10525460.21
#Sta/Elev= 30
  3950.2  277.04  3968.3  274.55  4049.1  269.42  4162.4  257.65  4203.4  255.43
  4254.3   253.6  4275.8  250.42  4332.9  248.49  4841.5  249.16  4979.2  246.52
  4986.6  244.32  4989.3  243.82  4992.6  244.32  5004.3  244.45  5033.6  250.65
  5048.4  250.25  5248.9  253.35  5329.6  254.52  5420.2     256  5426.4   258.2
  5453.1  260.76    5483  260.52    5648  264.08  5689.7  267.41  5712.8  272.69
  5742.1  271.84  5783.8  277.92  5863.3  284.76  5884.1  288.59  5906.1  289.22
#Mann= 11 ,-1 , 0
  3950.2     .16       0  3968.3     .05       0  4203.4     .16       0
  4332.9     .12       0  4986.6     .07       0  4992.6     .12       0
  5048.4     .05       0  5329.6     .08       0  5453.1     .16       0
    5483     .05       0  5689.7     .16       0
Bank Sta=4254.3,5248.9
XS Rating Curve= 0 ,0
Exp/Cntr=0.3,0.1

Type RM Length L Ch R = 1 ,5280    ,405,405,405
BEGIN DESCRIPTION:
BLISS CREEK 6.0
END DESCRIPTION:
XS GIS Cut Line= 3
      3651349.59      10527060.2      3652649.61     10526410.19
      3653599.61     10525260.19
#Sta/Elev= 30
  3515.8  287.49  3680.7  281.03  3747.8  274.88  4037.5  254.75  4060.9  253.37
  4129.4  248.17  4938.5  249.23  4987.8  243.87  4990.5  243.37  4993.8  243.87
  5011.6  248.76  5078.3  248.96  5488.1  249.08  5665.6  252.73  5857.1  255.34
  6063.2  267.74  6077.2  267.43  6120.2  278.22  6145.4  280.79  6184.1  289.47
  6190.6  286.23  6198.4  289.63  6204.9  286.95  6212.8  291.12  6233.6  290.38
  6247.9  296.07  6268.7  294.42  6302.5  299.53  6404.2  314.89  6460.9  318.67
#Mann= 10 ,-1 , 0
  3515.8     .16       0  3747.8     .05       0  4037.5     .16       0
  4129.4     .12       0  4987.8     .07       0  4993.8     .12       0
  5078.3     .05       0  6063.2     .16       0  6145.4     .05       0
  6302.5     .16       0
Bank Sta=4060.9,5665.6
XS Rating Curve= 0 ,0
Exp/Cntr=0.3,0.1

Type RM Length L Ch R = 1 ,4875    ,447,447,447
BEGIN DESCRIPTION:
BLISS CREEK 5.0
END DESCRIPTION:
XS GIS Cut Line= 3
      3651399.62     10527110.19      3652990.48     10526661.07
      3655135.47     10525710.06
#Sta/Elev= 30
  3387.6  292.15  3584.9  289.24    3659  283.27  3913.2  260.46  4002.7  252.74
  4094.2  247.63  4985.6  248.62  4990.8  244.68  5005.6  243.66  5008.3  243.16
  5011.6  243.66    5019  248.85  5281.6  248.37  5328.8  248.74  5745.6  252.19
  6070.1  254.57  6093.3  247.28  6111.1  249.03  6122.6  254.31  6290.5  256.96
  6533.9  272.98  6899.3  281.42  6951.7  278.63  6980.5  271.62  6986.8  273.28
  7003.7  287.32  7118.1  309.01  7154.3  323.43  7247.4  336.77    7387   344.5
#Mann= 9 ,-1 , 0
  3387.6     .16       0    3659     .05       0  3913.2     .16       0
  4002.7     .12       0  5005.6     .07       0  5011.6     .12       0
  5281.6     .16       0  5328.8     .05       0  6533.9     .16       0
Bank Sta=4002.7,5745.6
XS Rating Curve= 0 ,0
Exp/Cntr=0.3,0.1

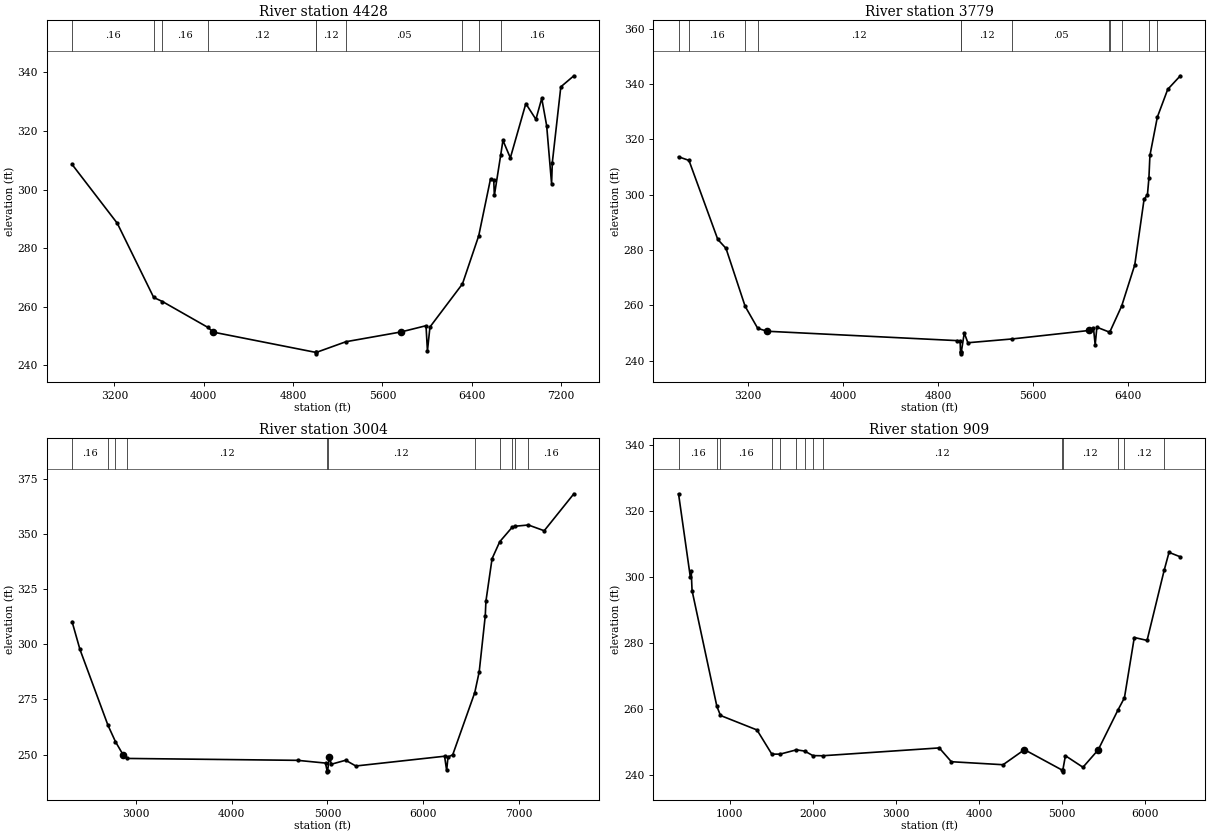
Type RM Length L Ch R = 1 ,4428    ,649,649,649
BEGIN DESCRIPTION:
BLISS CREEK 4.0
END DESCRIPTION:
XS GIS Cut Line= 3
      3651087.67     10527681.92       3653400.2     10526987.46
      3655240.46     10526022.19
#Sta/Elev= 30
    2821  308.61  3225.9  288.51  3551.8  263.19  3630.1   261.8  4035.5     253
  4086.4  251.34  5002.3  244.44    5005  243.94  5008.3  244.44  5273.2  248.08
  5765.6  251.41  5989.9  253.54  6002.7  244.96  6025.3  253.11  6316.2  267.82
  6461.8  284.24  6567.4  303.66  6596.2  303.31  6601.8  298.01  6658.1  311.69
  6678.7  316.81  6744.9  310.83  6883.5  329.36  6973.9  323.99    7026  331.16
  7070.1  321.83  7114.2     302  7120.7  309.22  7196.8  335.09  7313.6  338.87
#Mann= 10 ,-1 , 0
    2821     .16       0  3551.8     .05       0  3630.1     .16       0
  4035.5     .12       0  5002.3     .07       0  5008.3     .12       0
  5273.2     .05       0  6316.2     .16       0  6461.8     .05       0
  6658.1     .16       0
Bank Sta=4086.4,5765.6
XS Rating Curve= 0 ,0
Exp/Cntr=0.3,0.1

Type RM Length L Ch R = 1 ,3779    ,775,775,775
BEGIN DESCRIPTION:
BLISS CREEK 3.0
END DESCRIPTION:
XS GIS Cut Line= 3
      3651349.59      10528560.2      3653549.61     10527560.19
      3654949.61     10526410.18
#Sta/Elev= 30
  2614.4  313.72  2702.2  312.42  2945.1  283.87  3014.3  280.64  3175.5  259.71
  3281.8  251.74  3361.4  250.69  4965.1   247.3  4987.1  247.08  4990.7  243.03
  4993.4  242.53  4996.7  243.03  5022.2  250.08  5052.5  246.54  5423.2   247.9
  6075.7  250.98  6110.9  251.86  6125.3  245.78  6139.6  252.15  6245.2  250.38
  6248.3  250.39  6348.8  259.84  6458.9  274.68  6537.1   298.3  6565.8  300.07
  6577.9  305.93  6586.6  314.21  6649.2  328.07  6736.6  338.09  6842.8  342.99
#Mann= 12 ,-1 , 0
  2614.4     .05       0  2702.2     .16       0  3175.5     .05       0
  3281.8     .12       0  4990.7     .07       0  4996.7     .12       0
  5423.2     .05       0  6245.2     .16       0  6248.3     .08       0
  6348.8     .16       0  6577.9     .05       0  6649.2     .16       0
Bank Sta=3361.4,6075.7
XS Rating Curve= 0 ,0
Exp/Cntr=0.3,0.1

Type RM Length L Ch R = 1 ,3004    ,2095,2095,2095
BEGIN DESCRIPTION:
BLISS CREEK 2.0
END DESCRIPTION:
XS GIS Cut Line= 3
      3651499.62     10528710.19      3654073.81     10528091.63
      3655815.77     10526169.23
#Sta/Elev= 30
  2332.8   310.2  2415.1  297.61  2707.9  263.25  2786.4  255.81  2865.1  249.95
  2908.3  248.24    4688  247.38  4980.3  246.14  4996.4  242.67  4999.2  242.17
  5002.4  242.67    5021  248.69    5042  245.63  5190.7  247.42  5296.8  244.82
    6224  249.24  6245.7  242.78  6259.8  248.89  6309.2  249.91  6539.6   278.1
  6585.6  287.45  6649.1  312.88  6655.9  319.46  6720.1  338.72  6800.3  346.41
  6929.6  352.93  6955.6   353.4  7099.3  353.98  7264.8  351.38  7574.5  368.12
#Mann= 11 ,-1 , 0
  2332.8     .16       0  2707.9     .05       0  2786.4     .16       0
  2908.3     .12       0  4996.4     .07       0  5002.4     .12       0
  6539.6     .16       0  6800.3     .12       0  6929.6     .16       0
  6955.6     .05       0  7099.3     .16       0
Bank Sta=2865.1,5021
XS Rating Curve= 0 ,0
Exp/Cntr=0.3,0.1

Type RM Length L Ch R = 1 ,909     ,0,0,0
BEGIN DESCRIPTION:
BLISS CREEK 1.0
END DESCRIPTION:
XS GIS Cut Line= 4
      3651407.17     10528834.69      3654684.92      10528945.8
      3655664.09     10528216.63      3656309.93     10526827.72
#Sta/Elev= 30
   386.7  325.21   529.2  299.81   539.2  301.77   549.2  295.84   847.2  260.73
   890.8  257.93  1329.7  253.53    1508   246.2  1606.5  246.19  1804.1   247.5
  1902.9  247.12  2001.7  245.75  2117.6   245.7  3520.9  248.08  3666.2  243.89
  4288.1  242.98    4545  247.55    5000  241.32  5002.8  240.82    5006  241.32
  5037.6  245.71  5248.4  242.21  5431.5  247.49  5670.1  259.63    5747  263.29
  5865.5  281.59  6019.2  280.71  6224.6  301.98    6283  307.43  6418.9  306.07
#Mann= 14 ,-1 , 0
   386.7     .16       0   847.2     .05       0   890.8     .16       0
    1508     .12       0  1606.5     .05       0  1804.1     .07       0
  1902.9     .05       0  2001.7     .07       0  2117.6     .12       0
    5000     .07       0    5006     .12       0  5670.1     .16       0
    5747     .12       0  6224.6     .16       0
Bank Sta=4545,5431.5
XS Rating Curve= 0 ,0
Exp/Cntr=0.3,0.1

Chan Stop Cuts=-1
Use User Specified Reach Order=0
Composite Channel Slope=5