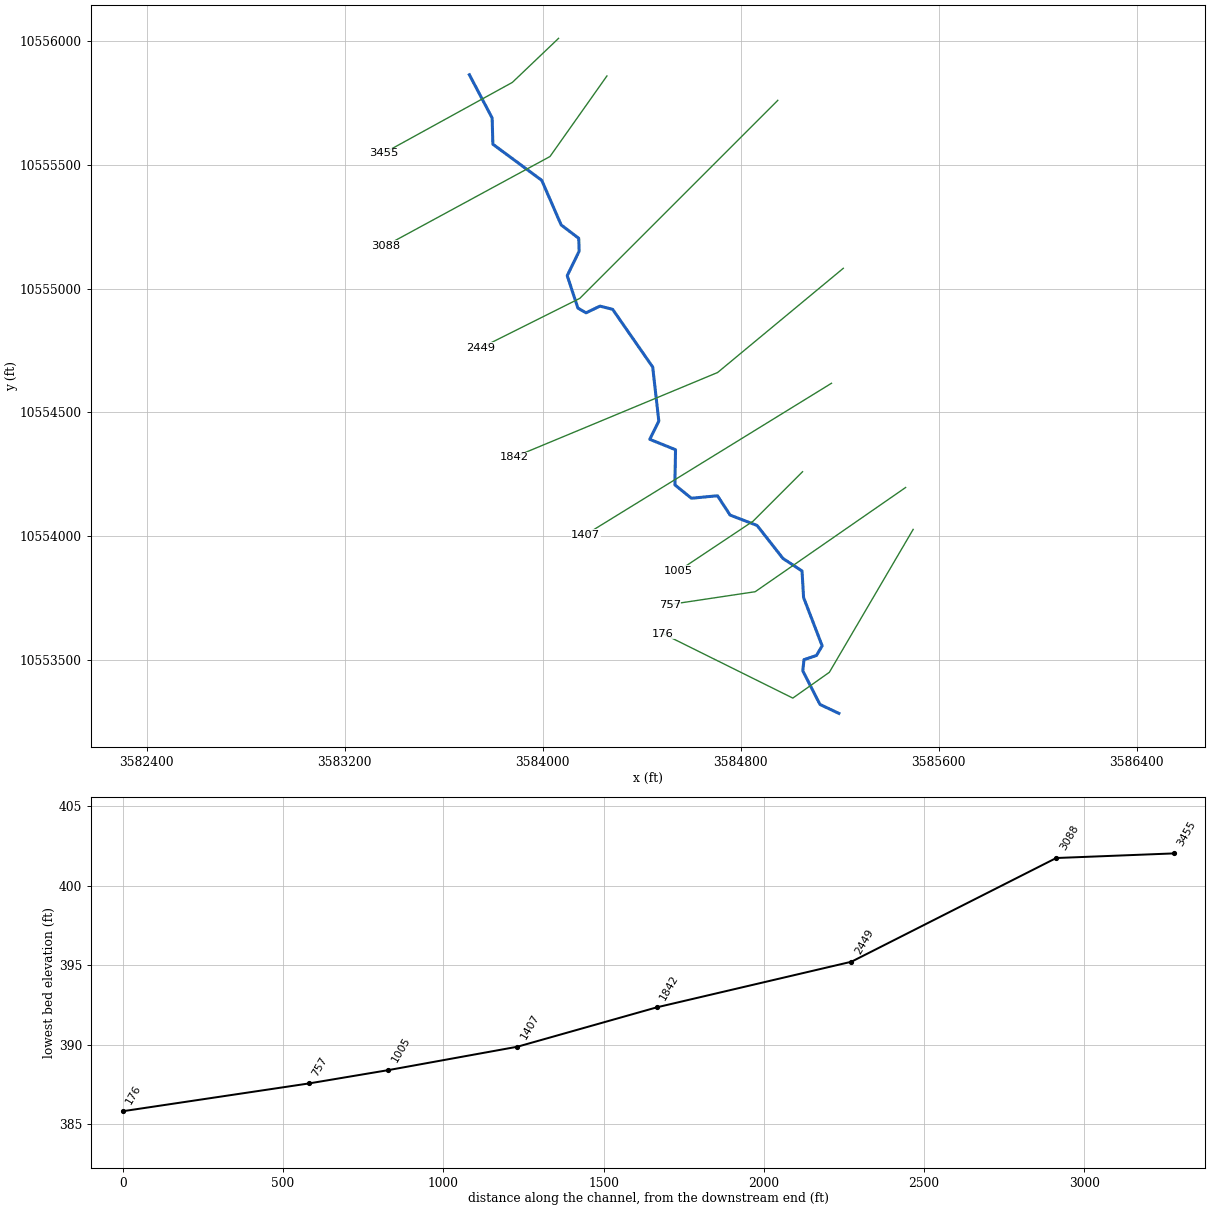
--- BOB BRANCH.prj (project) ---

Proj Title=BOB BRANCH Base Level Engineering
Current Plan=p01
Default Exp/Contr=0.3,0.1
English Units
Geom File=g01
Flow File=f01
Plan File=p01
BEGIN DESCRIPTION:
BOB BRANCH
END DESCRIPTION:

--- BOB BRANCH.p01 (plan) ---

Plan Title=Multiple Run
Short Identifier=Multiple
Geom File=g01
Flow File=f01
Subcritical Flow
K Sum by GR= 0
Std Step Tol= 0.01
Critical Tol= 0.01
Num of Std Step Trials= 20
Max Error Tol= 0.3
Flow Tol Ratio= 0.001
Split Flow NTrial= 30
Split Flow Tol= 0.02
Split Flow Ratio= 0.02
Log Output Level= 0
Friction Slope Method= 1
Unsteady Friction Slope Method= 2
Unsteady Bridges Friction Slope Method= 1
Parabolic Critical Depth
Global Vel Dist=  1 , 1 , 1
Global Log Level= 0
CheckData=True
Encroach Param= -1, 0, 0, 0
BEGIN DESCRIPTION:
Multiple Run
END DESCRIPTION:

--- BOB BRANCH.f01 (steady flow) ---

Flow Title=Multiple
Number of Profiles=7
Profile Names=10-year,25-year,50-year,1pct_min,100-year,1pct_plu,500-year
River Rch & RM= BOB BRANCH,Reach-1,3455
    1141    1581    1947    1750    2366    3200    3484
Boundary for River Rch & Prof#=BOB BRANCH,Reach-1,1
Up Type=0
Dn Type=3
Dn Slope=0.005
Boundary for River Rch & Prof#=BOB BRANCH,Reach-1,2
Up Type=0
Dn Type=3
Dn Slope=0.005
Boundary for River Rch & Prof#=BOB BRANCH,Reach-1,3
Up Type=0
Dn Type=3
Dn Slope=0.005
Boundary for River Rch & Prof#=BOB BRANCH,Reach-1,4
Up Type=0
Dn Type=3
Dn Slope=0.005
Boundary for River Rch & Prof#=BOB BRANCH,Reach-1,5
Up Type=0
Dn Type=3
Dn Slope=0.005
Boundary for River Rch & Prof#=BOB BRANCH,Reach-1,6
Up Type=0
Dn Type=3
Dn Slope=0.005
Boundary for River Rch & Prof#=BOB BRANCH,Reach-1,7
Up Type=0
Dn Type=3
Dn Slope=0.005

--- BOB BRANCH.g01 (geometry) ---

Geom Title=Existing Conditions

River Reach=BOB BRANCH,Reach-1
Reach XY= 30
      3583703.93     10555863.43      3583795.75     10555689.00
      3583798.75     10555583.00      3583996.25     10555437.00
      3584074.50     10555257.00      3584145.50     10555203.00
      3584147.25     10555151.00      3584099.00     10555052.00
      3584142.25     10554921.00      3584175.00     10554902.00
      3584231.25     10554929.00      3584282.50     10554916.00
      3584444.25     10554683.00      3584469.00     10554465.00
      3584432.50     10554391.00      3584536.50     10554349.00
      3584534.00     10554207.00      3584600.50     10554153.00
      3584706.00     10554163.00      3584757.00     10554085.00
      3584866.00     10554043.00      3584970.25     10553910.00
      3585047.50     10553859.00      3585053.75     10553752.00
      3585128.75     10553557.00      3585106.00     10553518.00
      3585055.50     10553501.00      3585050.50     10553456.00
      3585120.00     10553320.00      3585196.25     10553284.00

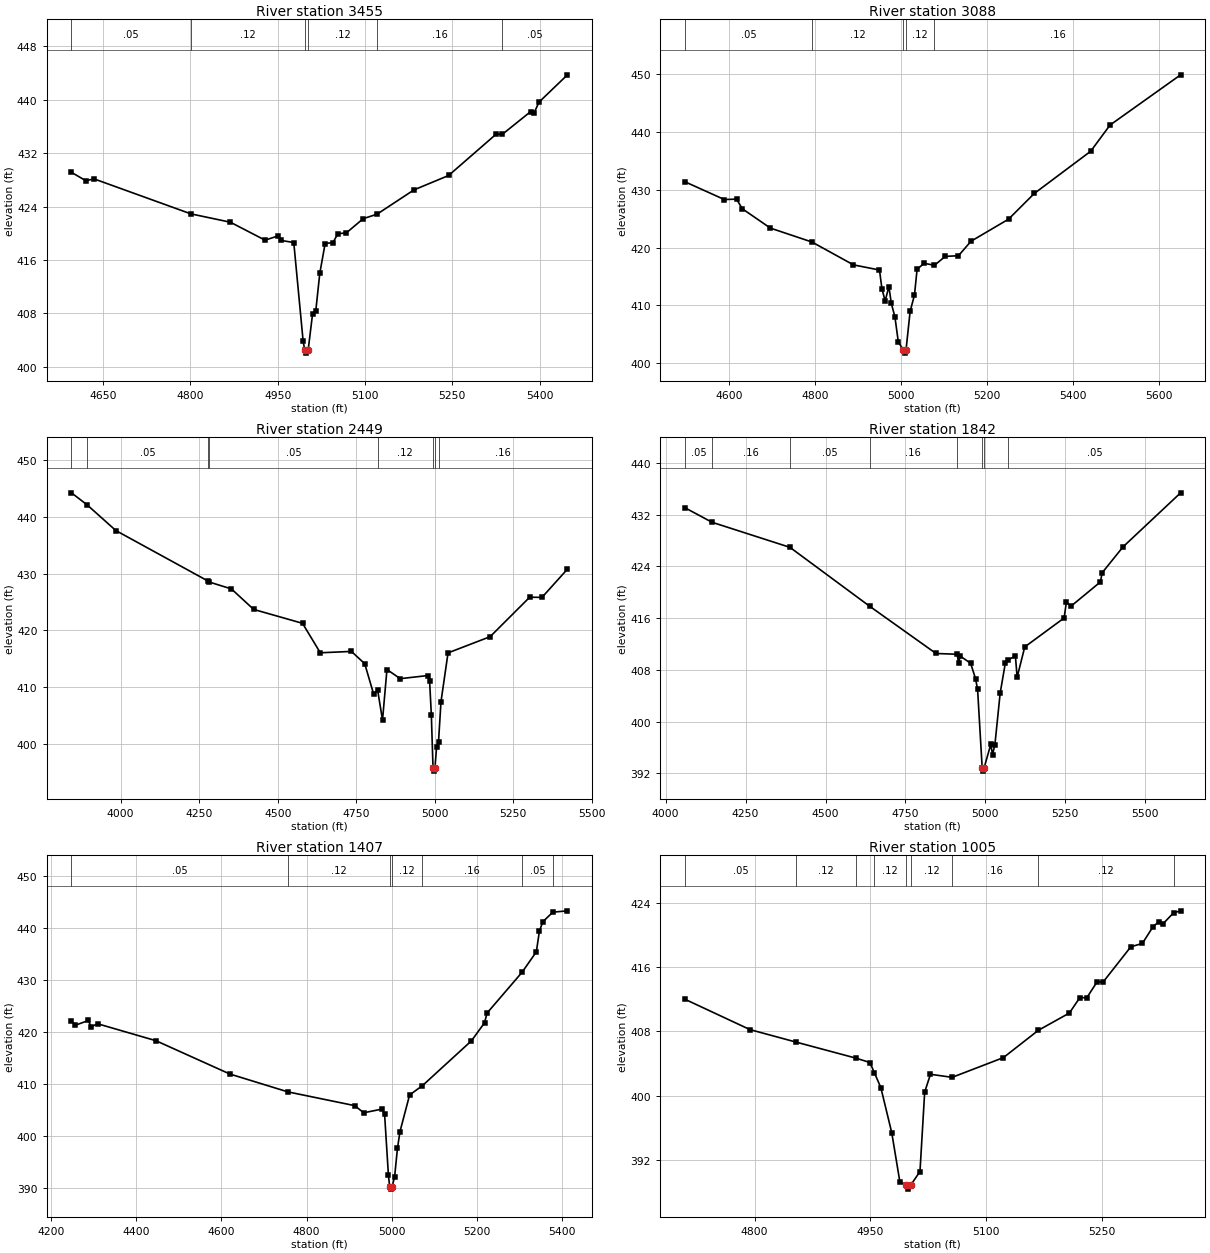
Type RM Length L Ch R = 1,3455,367,367,367
BEGIN DESCRIPTION:
BOB BRANCH 7.0
END DESCRIPTION:
XS GIS Cut Line= 3
      3584064.12     10556010.70      3583877.46     10555832.72
      3583356.65     10555546.27
#Sta/Elev= 30
  4595.7  429.12  4620.4  427.87  4634.6  428.14  4801.0  422.90  4868.8  421.65
  4928.4  418.96  4950.2  419.59  4955.9  418.92  4977.7  418.61  4993.8  403.84
  4996.5  402.54  4999.3  402.04  5002.5  402.54  5009.9  407.84  5015.6  408.42
  5022.4  413.99  5031.6  418.46  5045.2  418.61  5053.4  419.93  5068.0  420.05
  5097.0  422.18  5120.7  422.85  5184.2  426.49  5243.8  428.65  5325.3  434.83
  5336.3  434.83  5384.9  438.23  5390.6  438.00  5399.0  439.63  5448.0  443.73
#Mann=6,-1,0
  4595.7    0.05       0  4801.0    0.12       0  4996.5    0.07       0
  5002.5    0.12       0  5120.7    0.16       0  5336.3    0.05       0
Bank Sta=4996.5,5002.5
Exp/Cntr=0.3,0.1

Type RM Length L Ch R = 1,3088,639,639,639
BEGIN DESCRIPTION:
BOB BRANCH 6.0
END DESCRIPTION:
XS GIS Cut Line= 3
      3584259.39     10555858.74      3584029.37     10555533.24
      3583365.27     10555172.97
#Sta/Elev= 30
  4496.7  431.42  4589.2  428.32  4617.4  428.40  4631.0  426.72  4696.3  423.38
  4793.1  420.97  4889.5  417.02  4950.1  416.13  4955.8  412.89  4963.3  410.77
  4972.0  413.27  4977.7  410.34  4986.0  408.02  4993.9  403.70  5005.8  402.25
  5008.5  401.75  5011.8  402.25  5021.4  408.98  5031.5  411.79  5037.6  416.25
  5053.8  417.29  5078.1  416.95  5103.2  418.49  5133.9  418.60  5163.1  421.11
  5250.5  424.93  5310.4  429.38  5441.6  436.68  5486.6  441.21  5650.8  449.90
#Mann=5,-1,0
  4496.7    0.05       0  4793.1    0.12       0  5005.8    0.07       0
  5011.8    0.12       0  5078.1    0.16       0
Bank Sta=5005.8,5011.8
Exp/Cntr=0.3,0.1

Type RM Length L Ch R = 1,2449,607,607,607
BEGIN DESCRIPTION:
BOB BRANCH 5.0
END DESCRIPTION:
XS GIS Cut Line= 3
      3584949.63     10555760.21      3584149.61     10554960.19
      3583749.62     10554760.19
#Sta/Elev= 30
  3843.6  444.25  3893.6  442.12  3985.0  437.60  4279.5  428.67  4281.7  428.54
  4352.7  427.32  4423.5  423.71  4579.0  421.26  4635.6  416.07  4734.6  416.31
  4777.0  414.14  4805.3  408.80  4818.0  409.51  4833.6  404.21  4847.7  413.12
  4890.1  411.51  4977.8  412.06  4983.4  411.17  4989.0  405.12  4994.4  395.72
  4997.1  395.22  5000.4  395.72  5005.7  399.49  5011.8  400.37  5019.7  407.45
  5042.1  416.05  5176.2  418.91  5302.0  425.86  5341.2  425.83  5422.2  430.81
#Mann=8,-1,0
  3843.6    0.16       0  3893.6    0.05       0  4279.5    0.16       0
  4281.7    0.05       0  4818.0    0.12       0  4994.4    0.07       0
  5000.4    0.12       0  5011.8    0.16       0
Bank Sta=4994.4,5000.4
Exp/Cntr=0.3,0.1

Type RM Length L Ch R = 1,1842,435,435,435
BEGIN DESCRIPTION:
BOB BRANCH 4.0
END DESCRIPTION:
XS GIS Cut Line= 3
      3585214.29     10555081.87      3584706.45     10554660.84
      3583883.24     10554318.56
#Sta/Elev= 30
  4059.4  433.10  4145.0  430.83  4388.8  426.95  4637.6  417.86  4845.6  410.54
  4911.8  410.42  4916.1  409.12  4921.5  410.14  4953.9  409.02  4969.2  406.64
  4975.6  405.02  4990.0  392.85  4992.8  392.35  4996.0  392.85  5016.9  396.49
  5022.3  394.90  5029.7  396.41  5046.2  404.39  5062.2  409.01  5071.6  409.56
  5093.9  410.15  5099.3  406.86  5123.1  411.55  5246.3  416.03  5253.2  418.45
  5268.0  417.86  5359.5  421.59  5365.4  423.03  5430.4  427.02  5610.6  435.38
#Mann=8,-1,0
  4059.4    0.05       0  4145.0    0.16       0  4388.8    0.05       0
  4637.6    0.16       0  4911.8    0.12       0  4990.0    0.07       0
  4996.0    0.12       0  5071.6    0.05       0
Bank Sta=4990,4996
Exp/Cntr=0.3,0.1

Type RM Length L Ch R = 1,1407,402,402,402
BEGIN DESCRIPTION:
BOB BRANCH 3.0
END DESCRIPTION:
XS GIS Cut Line= 2
      3585166.54     10554617.45      3584173.57     10554006.06
#Sta/Elev= 30
  4247.3  422.18  4256.5  421.30  4287.3  422.21  4293.2  420.97  4308.6  421.58
  4445.8  418.33  4619.7  411.94  4755.9  408.52  4913.1  405.88  4934.5  404.51
  4977.0  405.21  4983.5  404.21  4992.4  392.66  4995.3  390.37  4998.1  389.87
  5001.3  390.37  5007.0  392.23  5013.7  397.67  5019.6  400.89  5042.3  407.93
  5072.6  409.72  5187.6  418.30  5218.4  421.76  5224.3  423.62  5306.7  431.45
  5340.2  435.36  5347.6  439.40  5355.7  441.15  5379.0  442.97  5413.4  443.23
#Mann=7,-1,0
  4247.3    0.05       0  4755.9    0.12       0  4995.3    0.07       0
  5001.3    0.12       0  5072.6    0.16       0  5306.7    0.05       0
  5379.0     0.1       0
Bank Sta=4995.3,5001.3
Exp/Cntr=0.3,0.1

Type RM Length L Ch R = 1,1005,248,248,248
BEGIN DESCRIPTION:
BOB BRANCH 2.0
END DESCRIPTION:
XS GIS Cut Line= 3
      3585049.59     10554260.17      3584849.61     10554060.19
      3584549.58     10553860.17
#Sta/Elev= 30
  4709.2  412.01  4794.0  408.22  4853.7  406.67  4932.0  404.66  4949.6  404.13
  4955.5  402.83  4963.7  401.02  4977.9  395.40  4988.5  389.25  4996.5  388.90
  4999.3  388.40  5002.5  388.90  5014.5  390.59  5020.6  400.46  5028.1  402.67
  5056.2  402.29  5122.7  404.74  5168.0  408.13  5208.3  410.28  5221.9  412.20
  5230.9  412.18  5244.4  414.18  5251.9  414.11  5288.0  418.51  5303.0  418.93
  5316.5  420.96  5324.0  421.62  5330.0  421.39  5343.4  422.73  5352.6  422.98
#Mann=9,-1,0
  4709.2    0.05       0  4853.7    0.12       0  4932.0    0.16       0
  4955.5    0.12       0  4996.5    0.07       0  5002.5    0.12       0
  5056.2    0.16       0  5168.0    0.12       0  5343.4    0.16       0
Bank Sta=4996.5,5002.5
Exp/Cntr=0.3,0.1

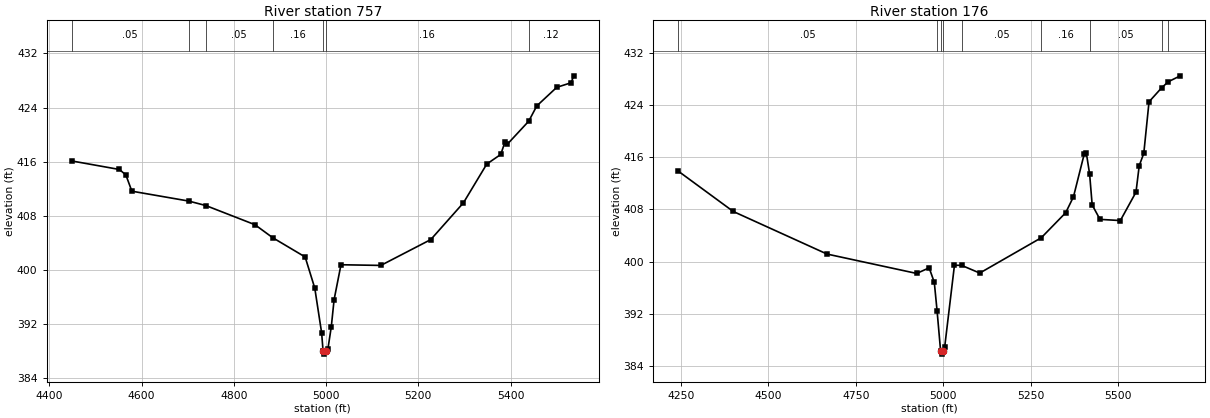
Type RM Length L Ch R = 1,757,581,581,581
BEGIN DESCRIPTION:
Mapping XS a57d48e2
END DESCRIPTION:
XS GIS Cut Line= 3
      3585466.02     10554196.44      3584858.36     10553775.43
      3584512.88     10553723.60
#Sta/Elev= 30
  4448.7  416.11  4552.0  414.85  4566.0  414.04  4579.0  411.64  4702.4  410.18
  4739.3  409.52  4845.8  406.69  4884.3  404.77  4954.7  401.92  4975.6  397.31
  4990.5  390.68  4993.5  388.06  4996.3  387.56  4999.5  388.06  5004.0  388.29
  5011.4  391.61  5017.5  395.62  5032.4  400.77  5118.8  400.67  5227.1  404.49
  5297.9  409.92  5348.5  415.65  5378.8  417.07  5387.8  418.88  5392.9  418.57
  5439.4  421.98  5456.9  424.24  5500.2  426.99  5531.1  427.66  5537.3  428.69
#Mann=7,-1,0
  4448.7    0.05       0  4702.4    0.16       0  4739.3    0.05       0
  4884.3    0.16       0  4993.5    0.07       0  4999.5    0.16       0
  5439.4    0.12       0
Bank Sta=4993.5,4999.5
Exp/Cntr=0.3,0.1

Type RM Length L Ch R = 1,176,0,0,0
BEGIN DESCRIPTION:
BOB BRANCH 1.0
END DESCRIPTION:
XS GIS Cut Line= 4
      3585496.36     10554027.13      3585157.84     10553449.90
      3585010.27     10553345.74      3584486.08     10553605.67
#Sta/Elev= 30
  4242.3  413.87  4399.6  407.68  4667.7  401.15  4923.7  398.18  4959.4  399.04
  4974.1  396.82  4982.0  392.48  4992.1  386.31  4994.8  385.81  4998.1  386.31
  5003.7  386.86  5031.7  399.44  5052.1  399.42  5104.0  398.24  5279.8  403.65
  5349.6  407.49  5371.9  409.94  5402.9  416.56  5408.5  416.69  5418.0  413.43
  5425.3  408.68  5447.7  406.47  5505.8  406.29  5550.5  410.64  5559.8  414.71
  5572.8  416.59  5587.8  424.50  5624.1  426.66  5643.2  427.59  5677.2  428.48
#Mann=9,-1,0
  4242.3    0.05       0  4982.0    0.16       0  4992.1    0.07       0
  4998.1    0.16       0  5052.1    0.05       0  5279.8    0.16       0
  5418.0    0.05       0  5624.1    0.16       0  5643.2    0.05       0
Bank Sta=4992.1,4998.1
Exp/Cntr=0.3,0.1

Chan Stop Cuts=-1