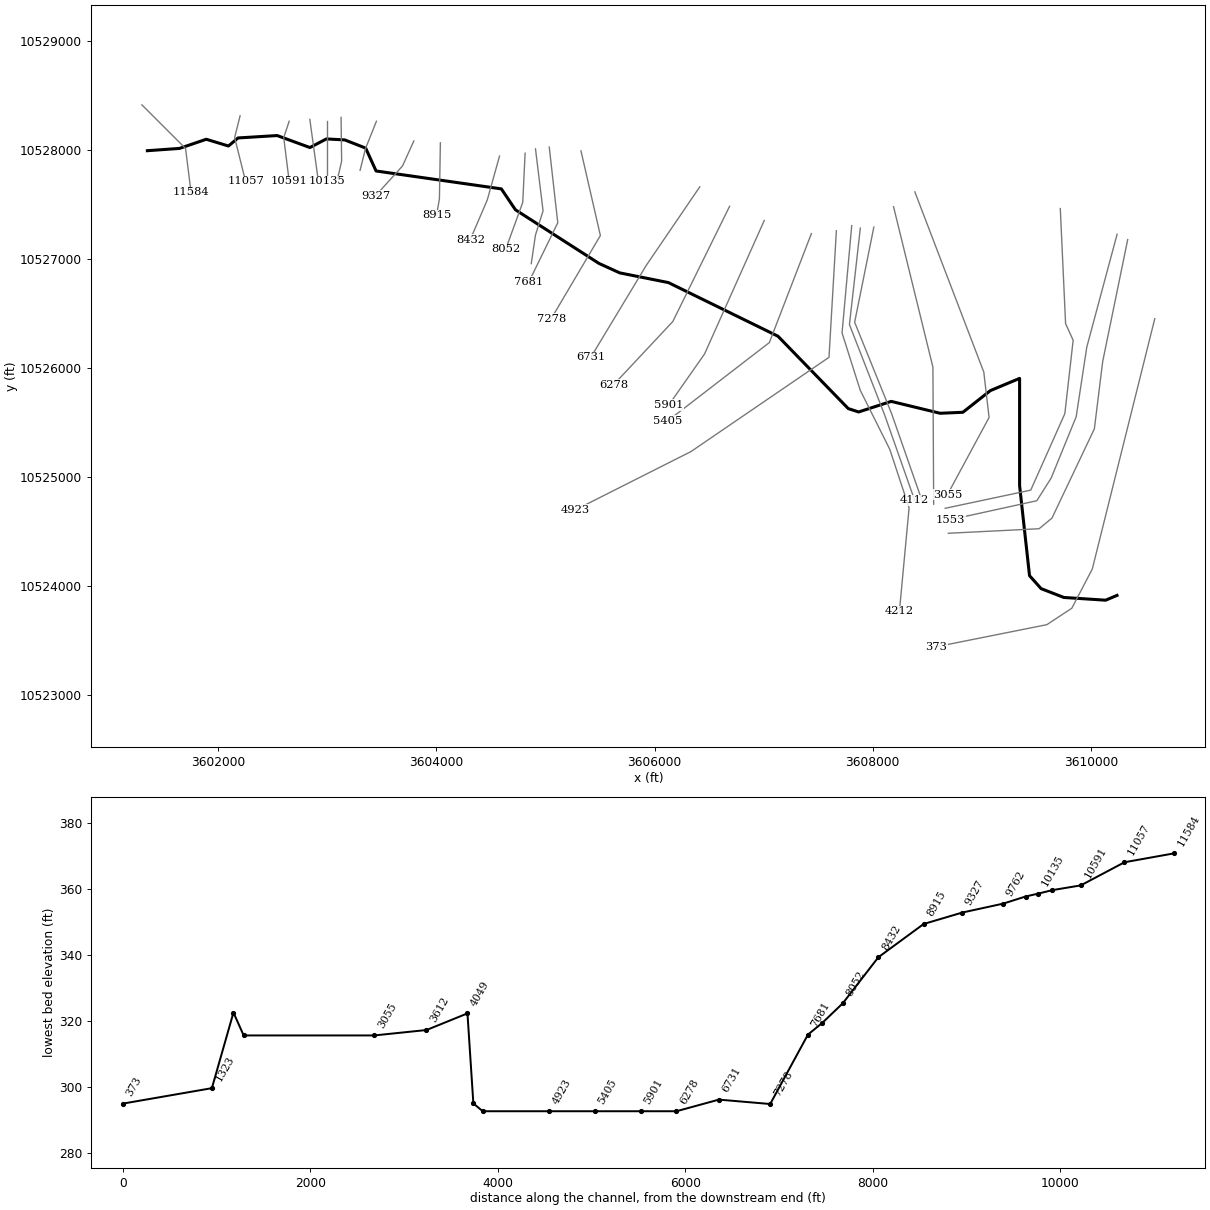
--- BOW BRANCH.prj (project) ---

Proj Title=BOW BRANCH Base Level Engineering
Current Plan=p01
Default Exp/Contr=0.3,0.1
English Units
Geom File=g01
Flow File=f01
Plan File=p01
Y Axis Title=Elevation
X Axis Title(PF)=Main Channel Distance
X Axis Title(XS)=Station
BEGIN DESCRIPTION:
BOW BRANCH
END DESCRIPTION:
DSS Export Rating Curves= 0
DSS Export Rating Curve Sorted= 0
DSS Export Volume Flow Curves= 0
DXF OffsetX= 0
DXF OffsetY= 0
DXF ScaleX= 1
DXF ScaleY= 10

--- BOW BRANCH.p01 (plan) ---

Plan Title=Multiple Run
Short Identifier=Multiple
Geom File=g01
Flow File=f01
Subcritical Flow
K Sum by GR= 0
Std Step Tol= 0.01
Critical Tol= 0.01
Num of Std Step Trials= 20
Max Error Tol= 0.3
Flow Tol Ratio= 0.001
Split Flow NTrial= 30
Split Flow Tol= 0.02
Split Flow Ratio= 0.02
Log Output Level= 0
Friction Slope Method= 1
Unsteady Friction Slope Method= 2
Unsteady Bridges Friction Slope Method= 1
Parabolic Critical Depth
Global Vel Dist=  1 , 1 , 1
Global Log Level= 0
CheckData=True
Encroach Param= -1, 0, 0, 0
BEGIN DESCRIPTION:
Multiple Run
END DESCRIPTION:

--- BOW BRANCH.f01 (steady flow) ---

Flow Title=Multiple
Number of Profiles=7
Profile Names=10-year,25-year,50-year,1pct_min,100-year,1pct_plu,500-year
River Rch & RM= BOW BRANCH,Reach-1,11584
    2059    2982    3785    3505    4740    6410    7411
River Rch & RM= BOW BRANCH,Reach-1,6278
    2706    3942    5023    4661    6303    8524    9900
Boundary for River Rch & Prof#=BOW BRANCH,Reach-1,1
Up Type=0
Dn Type=3
Dn Slope=0.005
Boundary for River Rch & Prof#=BOW BRANCH,Reach-1,2
Up Type=0
Dn Type=3
Dn Slope=0.005
Boundary for River Rch & Prof#=BOW BRANCH,Reach-1,3
Up Type=0
Dn Type=3
Dn Slope=0.005
Boundary for River Rch & Prof#=BOW BRANCH,Reach-1,4
Up Type=0
Dn Type=3
Dn Slope=0.005
Boundary for River Rch & Prof#=BOW BRANCH,Reach-1,5
Up Type=0
Dn Type=3
Dn Slope=0.005
Boundary for River Rch & Prof#=BOW BRANCH,Reach-1,6
Up Type=0
Dn Type=3
Dn Slope=0.005
Boundary for River Rch & Prof#=BOW BRANCH,Reach-1,7
Up Type=0
Dn Type=3
Dn Slope=0.005

--- BOW BRANCH.g01 (geometry) ---

Geom Title=Existing Conditions
Program Version=4.10

River Reach=BOW BRANCH      ,Reach-1
Reach XY= 30
       3601349.5       10527990.      3601644.25       10528011.
       3601889.5       10528095.      3602092.75       10528033.
      3602180.75       10528107.      3602539.25       10528129.
      3602839.75       10528019.      3602990.75       10528098.
        3603159.       10528089.      3603350.75       10528014.
      3603446.25       10527804.      3604594.76     10527639.73
        3604724.       10527448.       3605489.5       10526956.
       3605680.5       10526869.       3606126.5       10526780.
        3607131.       10526288.       3607775.5       10525624.
       3607870.5       10525593.      3608169.25       10525690.
        3608618.       10525581.      3608826.25       10525590.
       3609078.5       10525789.       3609346.5       10525901.
       3609346.5       10524917.       3609437.5       10524091.
      3609543.75       10523972.      3609752.25       10523891.
      3610135.25       10523866.       3610239.5       10523910.

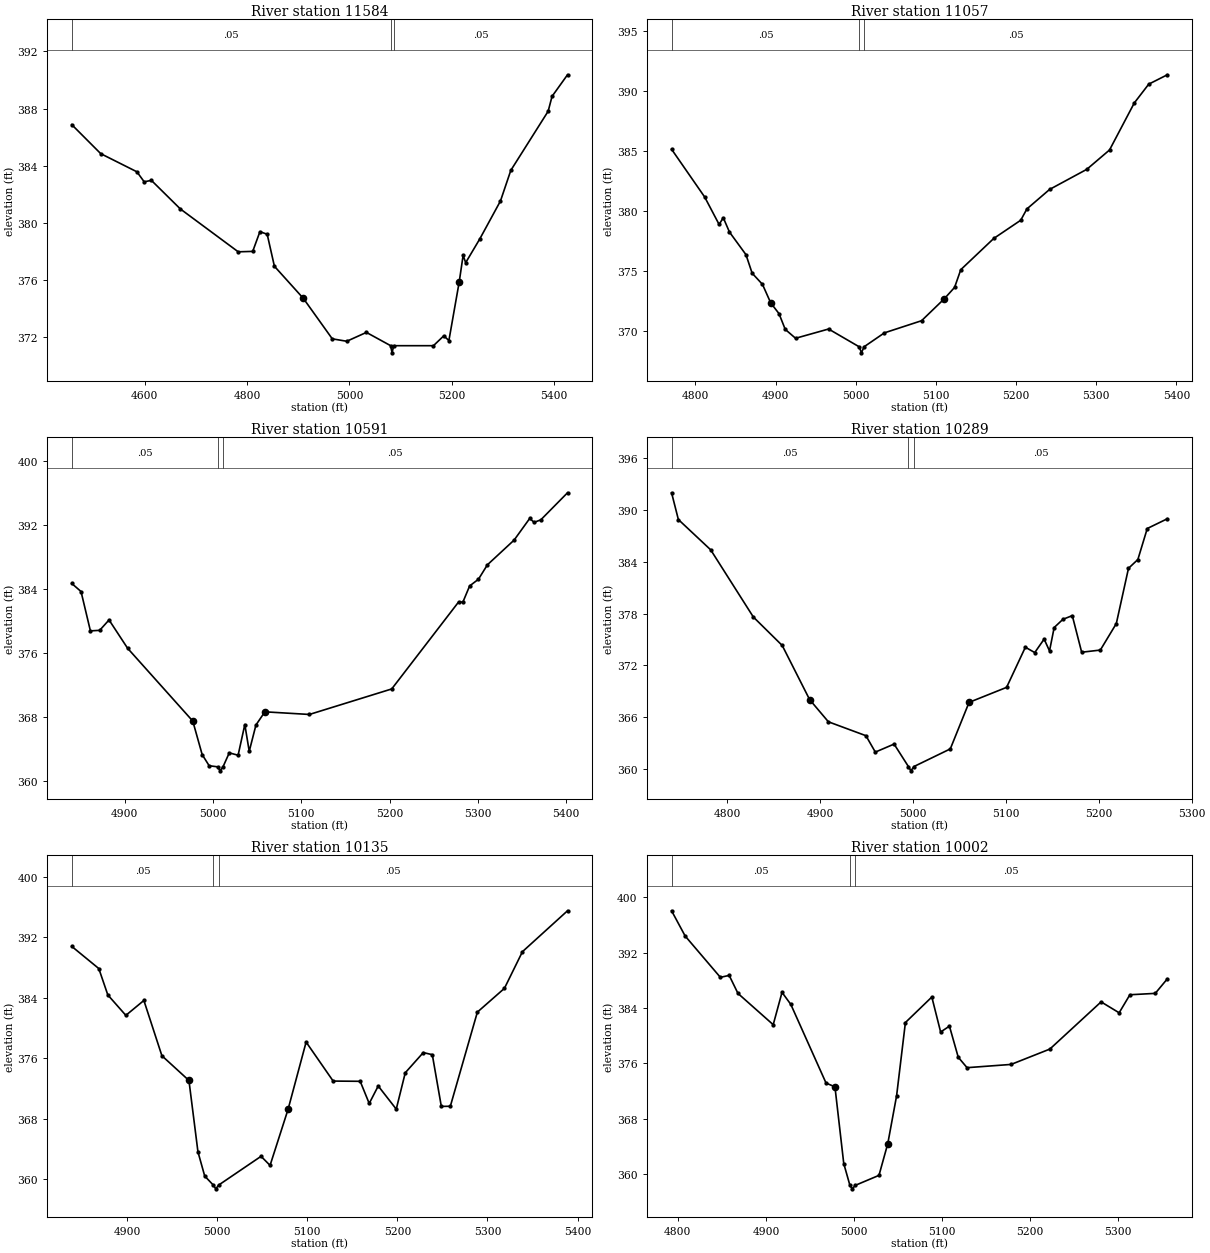
Type RM Length L Ch R = 1 ,11584   ,527,527,527
BEGIN DESCRIPTION:
BOW BRANCH 20.0
END DESCRIPTION:
XS GIS Cut Line= 3
      3601299.59     10528410.21      3601699.61     10528010.19
      3601749.61     10527610.22
#Sta/Elev= 30
  4457.3  386.87  4513.9  384.84  4584.6  383.57  4598.8  382.87  4612.9  382.97
  4669.5  380.97  4782.6  377.97  4810.9     378    4825  379.38  4839.2   379.2
  4853.3  376.96  4909.9  374.71  4966.4  371.88  4994.7  371.71  5033.1  372.33
  5080.5   371.4  5083.2   370.9  5086.5   371.4  5164.1   371.4  5184.3  372.09
  5194.3  371.76  5214.5  375.87  5222.1  377.72  5227.1  377.21  5254.8  378.88
  5295.1  381.53  5315.3  383.67  5388.3  387.81  5395.9  388.85  5426.1  390.36
#Mann= 3 ,-1 , 0
  4457.3     .05       0  5080.5    .035       0  5086.5     .05       0
Bank Sta=4909.9,5214.5
XS Rating Curve= 0 ,0
Exp/Cntr=0.3,0.1

Type RM Length L Ch R = 1 ,11057   ,466,466,466
BEGIN DESCRIPTION:
BOW BRANCH 19.0
END DESCRIPTION:
XS GIS Cut Line= 3
      3602199.62     10528310.23      3602149.61     10528110.19
      3602249.61      10527710.2
#Sta/Elev= 30
  4770.2  385.14  4811.5  381.17  4829.5  378.89  4834.7  379.45  4842.4  378.26
    4863  376.38  4870.7  374.84  4883.6  373.91  4893.9  372.37  4904.2  371.48
    4912  370.17  4924.9  369.43  4966.1   370.2  5004.3  368.72  5007.1  368.22
  5010.3  368.72  5035.7  369.88  5082.1  370.89  5110.4  372.71  5123.3  373.66
    5131  375.13  5172.2  377.73  5205.8  379.24  5213.5  380.18  5241.8   381.8
  5288.2  383.47  5316.6  385.08  5347.5  388.99  5365.5  390.55  5388.7  391.33
#Mann= 3 ,-1 , 0
  4770.2     .05       0  5004.3    .035       0  5010.3     .05       0
Bank Sta=4893.9,5110.4
XS Rating Curve= 0 ,0
Exp/Cntr=0.3,0.1

Type RM Length L Ch R = 1 ,10591   ,302,302,302
BEGIN DESCRIPTION:
BOW BRANCH 18.0
END DESCRIPTION:
XS GIS Cut Line= 3
      3602649.61     10528260.19      3602599.61     10528110.19
      3602649.61     10527710.21
#Sta/Elev= 30
  4840.2  384.64  4850.7  383.63  4861.3  378.71  4871.8  378.78  4882.4  380.08
  4903.4  376.54  4977.2  367.43  4987.8  363.25  4995.7  361.85  5005.4  361.71
  5008.1  361.21  5011.4  361.71  5018.5  363.46  5028.5  363.16  5036.1     367
  5041.1  363.65  5048.7  366.94  5058.8  368.59  5109.2  368.26  5202.4  371.45
    5278  382.31    5283  382.32  5290.6  384.33  5300.6  385.17  5310.7  386.97
    5341  390.07  5358.6  392.77  5363.6  392.28  5371.2   392.6  5401.4  395.98
#Mann= 3 ,-1 , 0
  4840.2     .05       0  5005.4    .035       0  5011.4     .05       0
Bank Sta=4977.2,5058.8
XS Rating Curve= 0 ,0
Exp/Cntr=0.3,0.1

Type RM Length L Ch R = 1 ,10289   ,154,154,154
BEGIN DESCRIPTION:
Mapping XS 1a142fc6
END DESCRIPTION:
XS GIS Cut Line= 2
      3602838.92      10528277.4      3602911.83     10527748.81
#Sta/Elev= 30
  4740.2  391.99  4747.5  388.89  4782.3  385.38  4828.2   377.6  4859.3   374.3
  4888.8  368.03    4909  365.46  4949.4  363.85  4959.5  361.95  4979.7  362.88
  4995.1  360.28  4997.8  359.78  5001.1  360.28  5040.2  362.32  5060.4  367.71
  5100.8  369.45    5121   374.1  5131.1  373.48  5141.2  375.04    5147  373.67
    5152  376.38  5161.4  377.33  5171.5  377.76  5181.6  373.52  5201.7  373.77
  5218.9  376.84    5232  383.24  5242.1  384.26  5252.2  387.85  5273.8  388.98
#Mann= 3 ,-1 , 0
  4740.2     .05       0  4995.1    .035       0  5001.1     .05       0
Bank Sta=4888.8,5060.4
XS Rating Curve= 0 ,0
Exp/Cntr=0.3,0.1

Type RM Length L Ch R = 1 ,10135   ,133,133,133
BEGIN DESCRIPTION:
BOW BRANCH 17.0
END DESCRIPTION:
XS GIS Cut Line= 3
      3602999.61      10528260.2      3602999.61     10528110.19
      3602999.61      10527710.2
#Sta/Elev= 30
  4838.8  390.76  4868.8  387.83  4878.8  384.34  4898.8  381.64  4918.8  383.61
  4938.8   376.3  4968.8  373.03  4978.8  363.59  4986.3  360.39  4995.8   359.2
  4998.6   358.7  5001.8   359.2  5048.8     363  5058.8   361.8  5078.8  369.22
  5098.8  378.11  5128.8  372.95  5158.8  372.92  5168.8  369.99  5178.8   372.3
  5198.8  369.24  5208.8  374.05  5228.8  376.72  5238.8  376.44  5248.8   369.6
  5258.8  369.62  5288.8  382.07  5318.8  385.21  5338.8  390.06  5388.8  395.47
#Mann= 3 ,-1 , 0
  4838.8     .05       0  4995.8    .035       0  5001.8     .05       0
Bank Sta=4968.8,5078.8
XS Rating Curve= 0 ,0
Exp/Cntr=0.3,0.1

Type RM Length L Ch R = 1 ,10002   ,240,240,240
BEGIN DESCRIPTION:
Mapping XS e32c8eae
END DESCRIPTION:
XS GIS Cut Line= 3
      3603125.38     10528295.62      3603130.59     10527894.62
      3603094.38     10527736.86
#Sta/Elev= 30
  4792.9  398.07  4808.3  394.42  4848.3  388.44  4858.3  388.72  4868.3  386.11
  4908.3  381.59  4918.3  386.27  4928.3  384.52  4968.3  373.14  4978.4   372.6
  4988.4   361.5  4995.4  358.34  4998.1  357.84  5001.4  358.34  5028.4  359.79
  5038.4  364.39  5048.4   371.3  5058.4   381.9  5088.4  385.59  5098.4  380.53
  5108.4  381.38  5118.4  376.88  5128.4  375.37  5178.4  375.84  5222.4  378.06
  5280.6  384.89  5301.1  383.31  5313.3  385.92  5342.1  386.12  5355.8  388.22
#Mann= 3 ,-1 , 0
  4792.9     .05       0  4995.4    .035       0  5001.4     .05       0
Bank Sta=4978.4,5038.4
XS Rating Curve= 0 ,0
Exp/Cntr=0.3,0.1

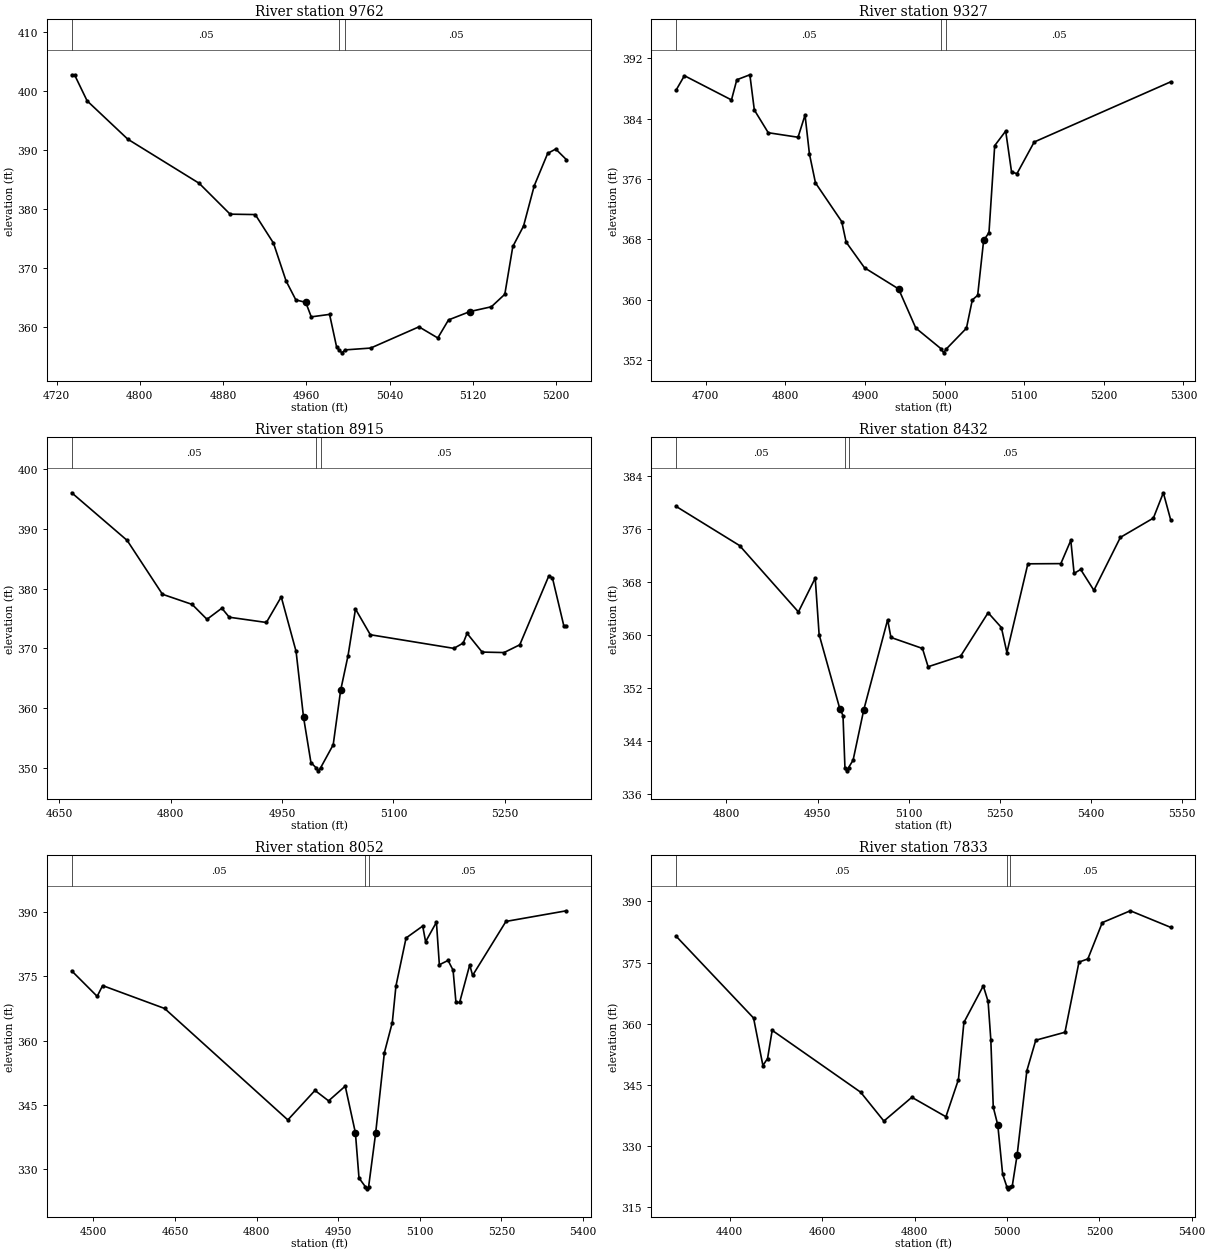
Type RM Length L Ch R = 1 ,9762    ,435,435,435
BEGIN DESCRIPTION:
BOW BRANCH 16.0
END DESCRIPTION:
XS GIS Cut Line= 3
      3603449.62     10528260.22      3603349.61     10528010.19
      3603299.62     10527810.23
#Sta/Elev= 30
  4734.5  402.81  4737.2  402.81  4749.3  398.39  4788.4  391.89    4857  384.41
  4886.7  379.18  4910.9  379.11  4928.4  374.27  4940.5  367.86  4949.9  364.64
  4959.4  364.23  4964.7  361.77  4982.3  362.19    4989  356.71  4991.4  356.17
  4994.1  355.67  4997.4  356.17  5021.8  356.48  5068.2  360.08  5086.3  358.19
  5096.6  361.25  5117.2  362.67  5137.8  363.48  5150.7   365.6  5158.4   373.7
  5168.7  377.16    5179     384  5191.9  389.48  5199.6  390.22  5209.9  388.42
#Mann= 3 ,-1 , 0
  4734.5     .05       0  4991.4    .035       0  4997.4     .05       0
Bank Sta=4959.4,5117.2
XS Rating Curve= 0 ,0
Exp/Cntr=0.3,0.1

Type RM Length L Ch R = 1 ,9327    ,412,412,412
BEGIN DESCRIPTION:
BOW BRANCH 15.0
END DESCRIPTION:
XS GIS Cut Line= 3
      3603792.78     10528079.73      3603688.61     10527849.68
       3603441.2     10527576.23
#Sta/Elev= 30
  4662.7  387.75  4673.2  389.67  4732.3  386.46    4739  389.13  4755.4  389.79
    4761  385.13  4778.5  382.12  4815.9  381.52  4824.7  384.46  4830.2  379.32
  4837.8  375.48  4870.8  370.35  4876.3  367.64  4899.4  364.24  4942.2  361.44
  4963.8  356.26    4996  353.48  4998.7  352.98    5002  353.48  5027.4  356.24
  5034.8  359.99  5041.5  360.59    5049  367.86  5055.7  368.89  5062.9  380.41
  5076.7  382.34  5084.1   376.9  5090.9  376.71  5112.5  380.89    5284  388.86
#Mann= 3 ,-1 , 0
  4662.7     .05       0    4996    .035       0    5002     .05       0
Bank Sta=4942.2,5049
XS Rating Curve= 0 ,0
Exp/Cntr=0.3,0.1

Type RM Length L Ch R = 1 ,8915    ,483,483,483
BEGIN DESCRIPTION:
BOW BRANCH 14.0
END DESCRIPTION:
XS GIS Cut Line= 3
      3604035.83     10528062.32      3604027.15     10527550.21
      3604001.11     10527398.31
#Sta/Elev= 30
  4666.7  396.01  4741.4  388.04  4788.9  379.04  4828.9  377.34  4848.9  374.85
  4868.9  376.71  4878.9   375.2  4928.9  374.32  4948.9   378.6  4968.9  369.48
  4978.9  358.51  4988.9   350.9  4995.9  350.01  4998.6  349.51  5001.9  350.01
  5018.9  353.87  5028.9  362.96  5038.9  368.79  5048.9  376.57  5068.9  372.27
  5181.4  369.99    5194  370.88  5199.2   372.5  5219.5  369.37    5249  369.29
  5270.2  370.59    5309  382.02  5314.1  381.82  5329.5  373.77    5333  373.77
#Mann= 3 ,-1 , 0
  4666.7     .05       0  4995.9    .035       0  5001.9     .05       0
Bank Sta=4978.9,5028.9
XS Rating Curve= 0 ,0
Exp/Cntr=0.3,0.1

Type RM Length L Ch R = 1 ,8432    ,380,380,380
BEGIN DESCRIPTION:
BOW BRANCH 13.0
END DESCRIPTION:
XS GIS Cut Line= 3
      3604578.35     10527940.78      3604465.52     10527537.18
      3604309.83     10527173.91
#Sta/Elev= 30
  4717.1  379.35  4821.6  373.44  4918.5  363.42  4946.2  368.53  4952.6  360.01
  4986.7   348.8  4991.9  347.79  4995.1  339.94  4997.8  339.44  5001.1  339.94
  5008.5  341.04  5026.1  348.65  5065.4  362.24  5070.8  359.57  5122.7  357.91
    5132  355.15  5185.6  356.76  5230.8   363.3  5252.6  361.07  5261.7  357.29
  5296.2  370.68  5350.5  370.71  5366.9  374.22  5372.3  369.23  5383.1  369.83
  5404.9  366.68  5448.5  374.67  5502.8  377.58  5519.2   381.4  5531.4  377.28
#Mann= 3 ,-1 , 0
  4717.1     .05       0  4995.1    .035       0  5001.1     .05       0
Bank Sta=4986.7,5026.1
XS Rating Curve= 0 ,0
Exp/Cntr=0.3,0.1

Type RM Length L Ch R = 1 ,8052    ,219,219,219
BEGIN DESCRIPTION:
BOW BRANCH 12.0
END DESCRIPTION:
XS GIS Cut Line= 3
      3604812.74      10527966.9      3604791.04     10527515.48
      3604634.78     10527085.75
#Sta/Elev= 30
  4460.1  376.26  4506.9  370.32  4516.9  372.83  4630.8   367.5  4857.3  341.53
  4907.2   348.4  4932.2  345.97  4962.8   349.4  4981.5  338.52  4988.1  327.99
  4999.8  325.97  5002.5  325.47  5005.8  325.97  5018.7  338.45  5034.7  357.17
  5049.3  364.22    5056  372.74  5074.6  383.92  5105.2   386.7  5110.5  383.05
  5130.4  387.59  5135.8  377.68  5151.8  378.69    5161  376.42  5166.3  368.94
    5173  368.89  5191.6  377.65  5196.9   375.2  5258.2  387.78  5369.3  390.26
#Mann= 3 ,-1 , 0
  4460.1     .05       0  4999.8    .035       0  5005.8     .05       0
Bank Sta=4981.5,5018.7
XS Rating Curve= 0 ,0
Exp/Cntr=0.3,0.1

Type RM Length L Ch R = 1 ,7833    ,152,152,152
BEGIN DESCRIPTION:
Mapping XS 096be499
END DESCRIPTION:
XS GIS Cut Line= 4
      3604907.87     10528006.79      3604977.31      10527438.2
      3604907.87     10527216.85      3604869.03     10526953.61
#Sta/Elev= 30
  4283.7  381.49  4451.5  361.41  4471.7  349.76  4481.8  351.48  4491.8  358.39
  4683.3  343.22  4733.6  336.14  4794.1  341.97  4867.9   337.2    4895  346.32
  4906.8  360.32  4948.8   369.3  4959.2  365.47  4965.1   356.1  4970.4  339.55
  4980.2  335.16  4990.7  323.11  4999.8  320.02  5002.5  319.52  5005.8  320.02
  5011.6  320.28  5022.1  327.86  5043.1  348.48  5062.4  355.97  5125.6  357.92
  5155.9  375.12  5175.2  375.91  5206.4  384.81  5267.1  387.71  5354.6  383.64
#Mann= 3 ,-1 , 0
  4283.7     .05       0  4999.8    .035       0  5005.8     .05       0
Bank Sta=4980.2,5022.1
XS Rating Curve= 0 ,0
Exp/Cntr=0.3,0.1

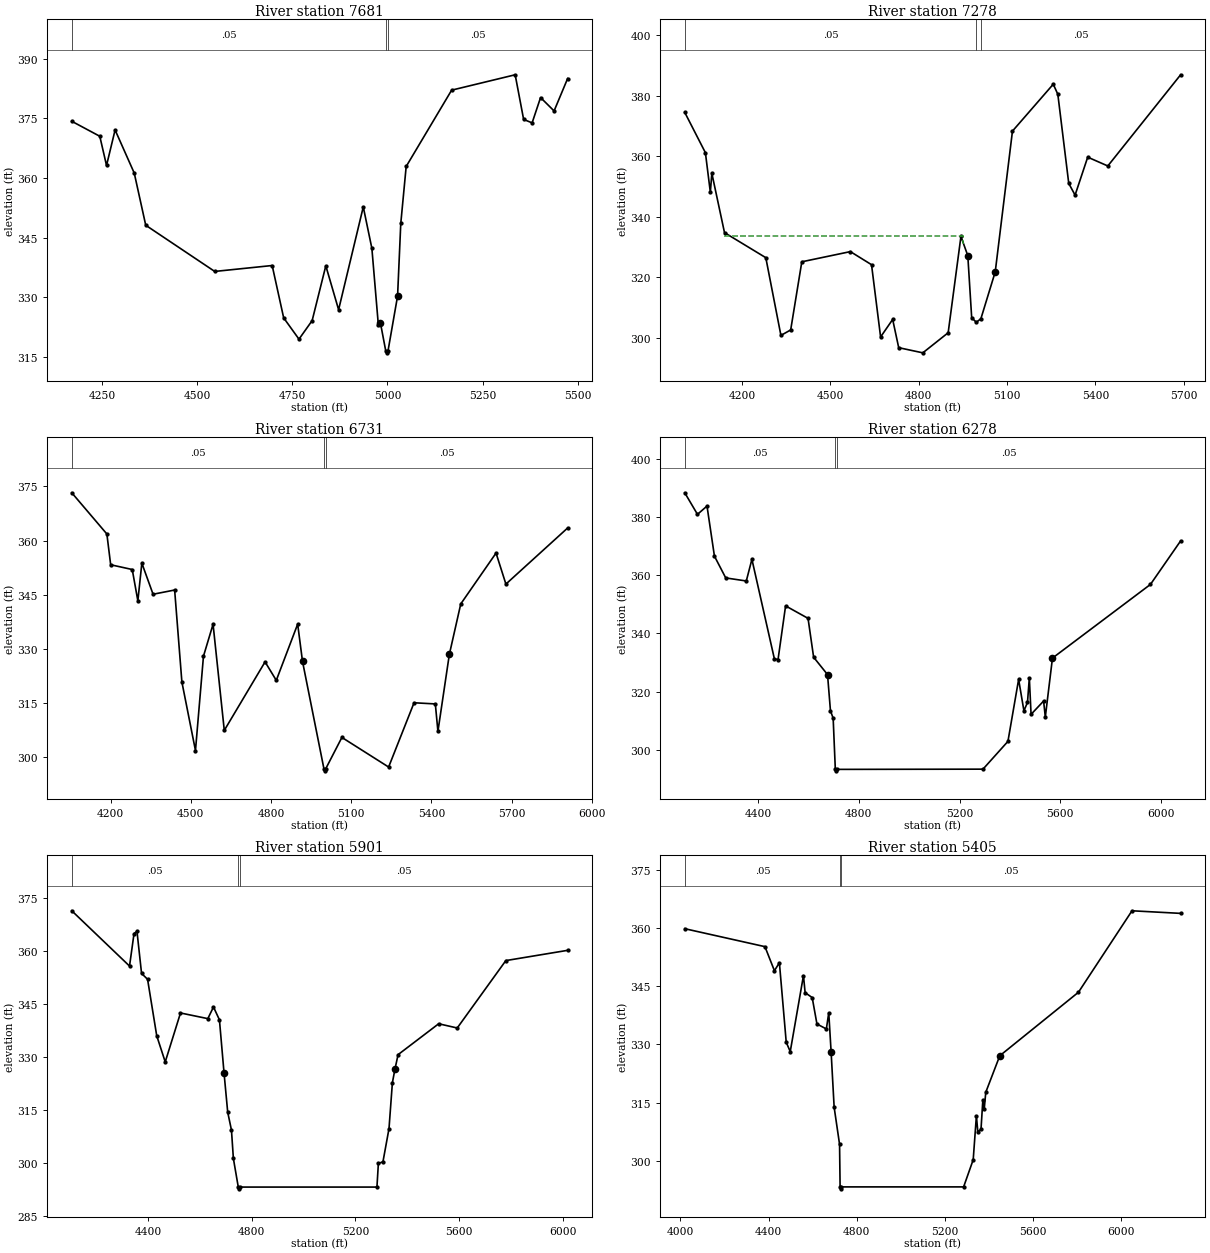
Type RM Length L Ch R = 1 ,7681    ,403,403,403
BEGIN DESCRIPTION:
BOW BRANCH 11.0
END DESCRIPTION:
XS GIS Cut Line= 3
       3605034.1      10528023.3      3605112.22     10527328.85
      3604847.47     10526786.33
#Sta/Elev= 30
  4170.7  374.26  4244.3  370.49    4262  363.14  4284.5  372.08  4334.8  361.23
    4365   348.1  4546.2  336.48  4697.1  337.97  4727.3   324.8  4767.5  319.44
  4802.1  324.11    4838   337.9  4871.6  326.85  4936.4  352.72    4959  342.28
  4975.9  323.12  4981.5  323.51  4995.4   316.5  4998.2     316  5001.4   316.5
  5026.5  330.28  5034.9  348.55  5049.1  362.89  5168.5  382.09  5335.4  385.96
  5357.6  374.73  5379.9  373.86  5402.1  380.23  5437.6  376.86  5473.2  385.02
#Mann= 3 ,-1 , 0
  4170.7     .05       0  4995.4    .035       0  5001.4     .05       0
Bank Sta=4981.5,5026.5
XS Rating Curve= 0 ,0
Exp/Cntr=0.3,0.1

Type RM Length L Ch R = 1 ,7278    ,547,547,547
BEGIN DESCRIPTION:
BOW BRANCH 10.0
END DESCRIPTION:
XS GIS Cut Line= 3
       3605324.9     10527988.57      3605502.85     10527211.66
      3605051.46     10526447.78
#Sta/Elev= 30
  4005.4  374.53  4075.5   361.2  4092.3   348.1  4097.4  354.36  4140.4  334.74
  4280.7  326.45    4332  300.73  4365.2  302.54    4403  325.09    4568  328.46
  4639.8  324.13  4670.6  300.21  4711.6  306.01  4732.1  296.67    4814  294.96
  4900.1  301.61  4943.5  333.48  4966.8  327.12    4980  306.58  4995.7  305.07
  5011.3  306.26    5060  321.77  5118.5  368.34  5257.1  383.86  5272.6  380.53
  5309.7  351.03  5331.2  347.16  5374.1  359.72  5442.4   356.8  5689.7  386.98
#Mann= 3 ,-1 , 0
  4005.4     .05       0  4995.7    .035       0  5011.3     .05       0
#XS Ineff= 1 ,-1
 4138.07 4952.16  333.77
Permanent Ineff=
       F
Bank Sta=4966.8,5060
XS Rating Curve= 0 ,0
Exp/Cntr=0.3,0.1

Type RM Length L Ch R = 1 ,6731    ,453,453,453
BEGIN DESCRIPTION:
BOW BRANCH 9.0
END DESCRIPTION:
XS GIS Cut Line= 3
      3606414.29      10527658.7      3605923.85     10526938.23
      3605416.07     10526096.25
#Sta/Elev= 30
  4055.1  373.21  4186.4  361.81  4200.6   353.3  4281.3  351.98  4302.3  343.33
  4317.2  353.74  4359.2  345.14  4439.9  346.31    4467  320.86  4517.8  301.91
  4547.7  327.99  4583.6  336.84  4625.6  307.48  4778.1  326.43  4820.1  321.32
  4900.1  336.88 4918.18  326.56  4998.5  296.79  5001.2  296.29  5004.5  296.79
  5065.5  305.53  5240.3  297.34  5335.4  315.12    5415   314.8  5424.7  307.21
  5467.4  328.49  5510.1  342.46  5642.1  356.53    5679  347.95  5909.9  363.47
#Mann= 3 ,-1 , 0
  4055.1     .05       0  4998.5    .035       0  5004.5     .05       0
#XS Ineff= 1 ,-1
 4438.64 4895.45  334.94
Permanent Ineff=
       F
Bank Sta=4918.18,5467.4
XS Rating Curve= 0 ,0
Exp/Cntr=0.3,0.1

Type RM Length L Ch R = 1 ,6278    ,377,377,377
BEGIN DESCRIPTION:
BOW BRANCH 8.0
END DESCRIPTION:
XS GIS Cut Line= 3
      3606687.42     10527479.53      3606166.59     10526422.25
      3605625.42     10525844.66
#Sta/Elev= 30
  4108.4  388.26  4158.9  380.85  4196.8   383.7  4226.3   366.5  4271.2  359.02
  4352.9  357.97  4375.2  365.41  4464.4  331.26    4479  330.98    4509  349.42
  4598.2  345.14  4620.4  331.79  4675.6  325.83  4687.3  313.37    4698  310.86
  4706.6  293.27  4709.4  292.77  4712.6  293.27  5293.3  293.35  5392.4  302.89
  5434.9  324.18  5455.9  313.38  5470.1  316.27  5477.4  324.72  5484.3  312.17
  5534.1  316.74  5540.9  311.25  5569.3  331.49  5958.6  356.79  6078.5  371.73
#Mann= 3 ,-1 , 0
  4108.4     .05       0  4706.6    .035       0  4712.6     .05       0
Bank Sta=4675.6,5569.3
XS Rating Curve= 0 ,0
Exp/Cntr=0.3,0.1

Type RM Length L Ch R = 1 ,5901    ,496,496,496
BEGIN DESCRIPTION:
BOW BRANCH 7.0
END DESCRIPTION:
XS GIS Cut Line= 3
      3607005.14     10527349.36      3606458.26     10526125.38
      3606130.13     10525656.62
#Sta/Elev= 30
  4105.8  371.43  4328.6  355.79  4345.9  364.96  4357.3  365.64    4375  353.71
  4398.2  352.05  4433.5  336.08  4466.3  328.67  4525.2  342.52  4630.6  340.92
  4652.5  344.21  4675.4  340.58  4693.2  325.53  4707.3  314.46  4721.8  309.39
  4729.2  301.36  4748.1  293.27  4750.9  292.77  4754.1  293.27    5283  293.27
  5288.5  299.94  5306.2  300.43  5329.5  309.81  5342.6   322.8  5352.7   326.7
  5364.5  330.73  5521.2  339.47  5592.7  338.27  5780.2  357.34  6018.6  360.24
#Mann= 3 ,-1 , 0
  4105.8     .05       0  4748.1    .035       0  4754.1     .05       0
Bank Sta=4693.2,5352.7
XS Rating Curve= 0 ,0
Exp/Cntr=0.3,0.1

Type RM Length L Ch R = 1 ,5405    ,482,482,482
BEGIN DESCRIPTION:
BOW BRANCH 6.0
END DESCRIPTION:
XS GIS Cut Line= 3
      3607437.43     10527229.56      3607052.01     10526229.55
      3606119.72      10525510.8
#Sta/Elev= 30
  4019.5  359.84  4383.2  355.21  4426.1  349.01  4448.7  351.06  4479.7  330.56
  4497.9  328.15  4557.8  347.75  4565.4  343.35  4597.5  342.08    4619  335.27
  4661.7  333.99  4672.6  338.18  4683.3  328.03    4697  313.81  4721.6  304.24
    4724  293.27  4726.8  292.77    4730  293.27  5284.2  293.27  5327.7  300.28
  5342.2  311.62  5348.6  307.45  5363.1  308.13  5371.3  315.56  5377.6  313.29
  5384.7  317.67  5448.2  327.08  5805.1  343.46  6047.9  364.46  6268.4  363.79
#Mann= 3 ,-1 , 0
  4019.5     .05       0    4724    .035       0    4730     .05       0
Bank Sta=4683.3,5448.2
XS Rating Curve= 0 ,0
Exp/Cntr=0.3,0.1

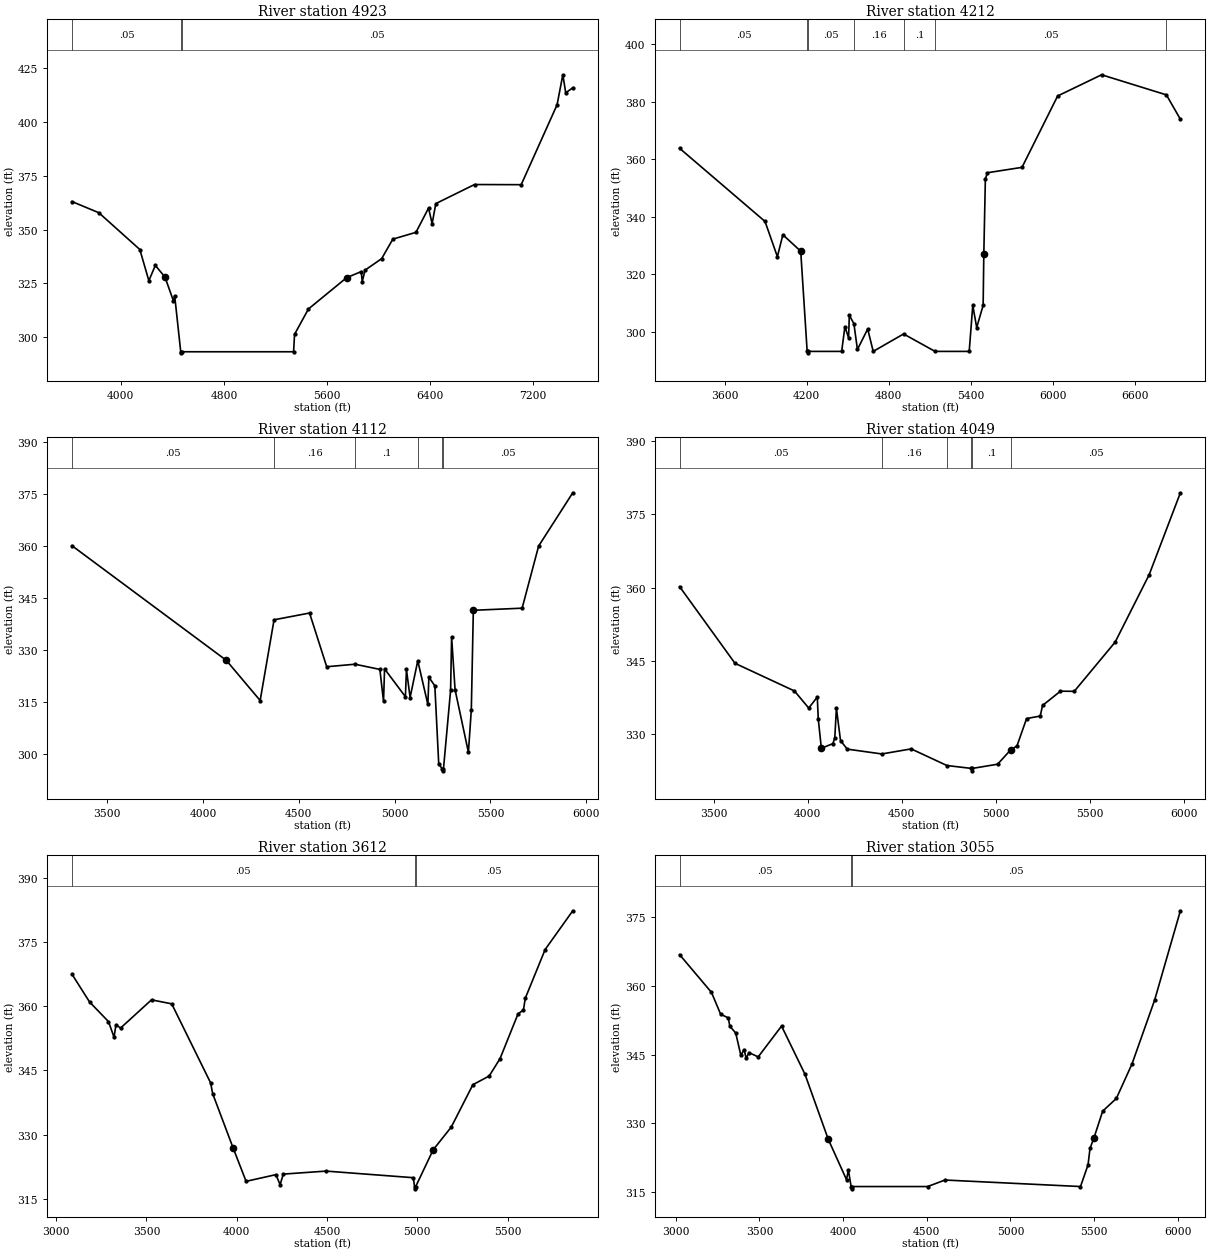
Type RM Length L Ch R = 1 ,4923    ,711,711,711
BEGIN DESCRIPTION:
Mapping XS d75469fe
END DESCRIPTION:
XS GIS Cut Line= 4
      3607666.59     10527255.56      3607598.88     10526094.13
      3606333.26     10525229.55      3605270.76     10524693.09
#Sta/Elev= 30
  3621.1  362.99  3829.4   357.8  4147.4  340.74  4217.5  326.26  4267.6  333.36
  4342.6  327.94  4407.8  316.96  4417.8  319.31  4464.9  293.27  4467.7  292.77
  4470.9  293.27  5340.7  293.27  5348.3  301.37    5456  313.13    5752  327.65
  5865.8  330.49  5873.6  325.83  5895.6  331.16  6024.3   336.5    6111  345.55
  6290.5  348.71  6388.2  359.96  6416.1  352.76  6444.6  362.05    6745   370.9
  7107.3  370.83  7385.6  407.89  7430.4  421.85  7452.8  413.49  7507.5   415.8
#Mann= 3 ,-1 , 0
  3621.1     .05       0  4464.9    .033       0  4470.9     .05       0
Bank Sta=4342.6,5752
XS Rating Curve= 0 ,0
Exp/Cntr=0.3,0.1

Type RM Length L Ch R = 1 ,4212    ,100,100,100
BEGIN DESCRIPTION:
BOW BRANCH 5.0
END DESCRIPTION:
XS GIS Cut Line= 6
      3607807.22     10527302.49      3607718.67     10526318.09
      3607885.34     10525792.05      3608156.17     10525250.38
      3608333.26     10524713.92      3608244.72     10523766.05
#Sta/Elev= 30
    3270  363.84  3894.8  338.43  3985.2  326.18  4025.3   333.8  4155.9  328.09
  4203.1  293.27  4205.8  292.77  4209.1  293.27  4455.5  293.27  4479.2  301.86
  4506.2  297.97  4511.5  305.85    4545  302.91  4570.8  293.94  4645.9  301.05
  4686.3  293.27  4908.3  299.33  5138.9  293.27  5388.6  293.27  5414.7  309.27
  5443.4  301.56  5490.6  309.28 5495.45  327.01  5506.9  353.27  5522.2  355.36
  5774.9  357.23  6035.6  382.03    6357   389.4  6831.2  382.42  6933.6  373.95
#Mann= 7 ,-1 , 0
    3270     .05       0  4203.1     .07       0  4209.1     .05       0
    4545     .16       0  4908.3      .1       0  5138.9     .05       0
  6831.2     .08       0
Bank Sta=4155.9,5495.45
XS Rating Curve= 0 ,0
Exp/Cntr=0.3,0.1

Type RM Length L Ch R = 1 ,4112    ,63,63,63
BEGIN DESCRIPTION:
BOW BRANCH 4.0
END DESCRIPTION:
XS GIS Cut Line= 4
      3607886.21     10527279.94      3607786.38     10526394.48
      3608107.56     10525569.82      3608384.97     10524780.94
#Sta/Elev= 30
    3317  360.05  4121.8     327  4298.5  315.41    4371  338.69  4556.1  340.64
  4645.7  325.15  4793.3  325.88    4923  324.38  4942.1  315.15  4947.5  324.54
  5056.2  316.51  5061.6  324.37  5080.7  316.28  5120.7  326.88  5173.4  314.27
  5178.7  322.13  5209.7  319.65    5230  297.19  5248.7  295.63  5251.4  295.13
  5254.7  295.63    5292  318.34  5297.3  333.72  5315.3  318.51  5384.9   300.5
  5400.1  312.78  5410.6  341.43  5665.1  342.04  5751.3  359.97  5929.3  375.32
#Mann= 6 ,-1 , 0
    3317     .05       0    4371     .16       0  4793.3      .1       0
  5120.7     .05       0  5248.7     .07       0  5254.7     .05       0
Bank Sta=4121.8,5410.6
XS Rating Curve= 0 ,0
Exp/Cntr=0.3,0.1

Type RM Length L Ch R = 1 ,4049    ,437,437,437
BEGIN DESCRIPTION:
BOW BRANCH 3.0
END DESCRIPTION:
XS GIS Cut Line= 4
      3608010.06     10527288.88      3607834.13     10526416.18
      3608172.67      10525578.5      3608459.11     10524758.23
#Sta/Elev= 30
  3319.7  360.17  3614.2  344.46  3930.4  338.79    4006  335.29  4051.7  337.54
  4056.8  333.06  4073.3  327.04  4134.5     328  4144.7  329.15  4153.3  335.25
  4175.3   328.6  4211.1  326.87  4394.7  325.88  4550.8  326.92  4740.8  323.51
  4870.7  322.92  4873.5  322.42  4876.7  322.92  5010.5  323.78  5079.3  326.69
  5080.2  326.69  5113.5  327.54  5164.6  333.14  5237.1  333.65  5249.4  335.82
  5344.7  338.75  5418.1  338.72  5635.5  348.81  5816.5  362.64  5982.3  379.42
#Mann= 6 ,-1 , 0
  3319.7     .05       0  4394.7     .16       0  4740.8      .1       0
  4870.7     .07       0  4876.7      .1       0  5080.2     .05       0
Bank Sta=4073.3,5079.3
XS Rating Curve= 0 ,0
Exp/Cntr=0.3,0.1

Type RM Length L Ch R = 1 ,3612    ,557,557,557
BEGIN DESCRIPTION:
BOW BRANCH 2.0
END DESCRIPTION:
XS GIS Cut Line= 3
      3608190.61     10527476.35      3608551.72     10526004.14
      3608558.66     10524747.21
#Sta/Elev= 30
  3087.8  367.45  3185.1  360.98  3289.8  356.41  3320.7  352.75    3331  355.68
  3356.6   354.9    3528  361.49  3639.9  360.55  3855.6  342.08  3866.4  339.62
  3979.6  326.95  4051.7  319.13  4216.5  320.69  4240.1  318.36  4257.6  320.82
  4494.7  321.52  4977.6  319.98  4984.6  317.88  4987.4  317.38  4990.6  317.88
  5087.6  326.49  5187.6  331.78  5307.6  341.69  5397.6   343.7  5457.6  347.74
  5557.6  358.22  5587.6  359.13  5597.6  361.85  5707.6  373.23  5860.6  382.27
#Mann= 3 ,-1 , 0
  3087.8     .05       0  4984.6    .035       0  4990.6     .05       0
Bank Sta=3979.6,5087.6
XS Rating Curve= 0 ,0
Exp/Cntr=0.3,0.1

Type RM Length L Ch R = 1 ,3055    ,1393,1393,1393
BEGIN DESCRIPTION:
Mapping XS 7d77a84d
END DESCRIPTION:
XS GIS Cut Line= 4
      3608386.17     10527611.92      3609018.12     10525959.13
      3609066.73     10525542.46      3608685.08     10524834.68
#Sta/Elev= 30
  3022.9  366.78  3213.3  358.56  3268.1  353.79  3313.8  353.01  3322.9  351.19
  3358.3   349.7  3388.8  344.84  3407.7  346.09  3420.9   344.2  3437.7  345.43
  3492.5   344.5  3632.1  351.22  3771.7  340.76  3911.3  326.54  4020.4  317.74
  4031.5  319.86  4047.9  316.24  4050.6  315.74  4053.9  316.24  4505.1  316.24
  4609.2  317.66    5419  316.24    5464  320.95  5475.8  324.55  5498.5  326.74
  5551.5  332.67  5633.4  335.45  5726.7  342.95    5862  356.87    6016  376.35
#Mann= 3 ,-1 , 0
  3022.9     .05       0  4047.9    .033       0  4053.9     .05       0
Bank Sta=3911.3,5498.5
XS Rating Curve= 0 ,0
Exp/Cntr=0.3,0.1

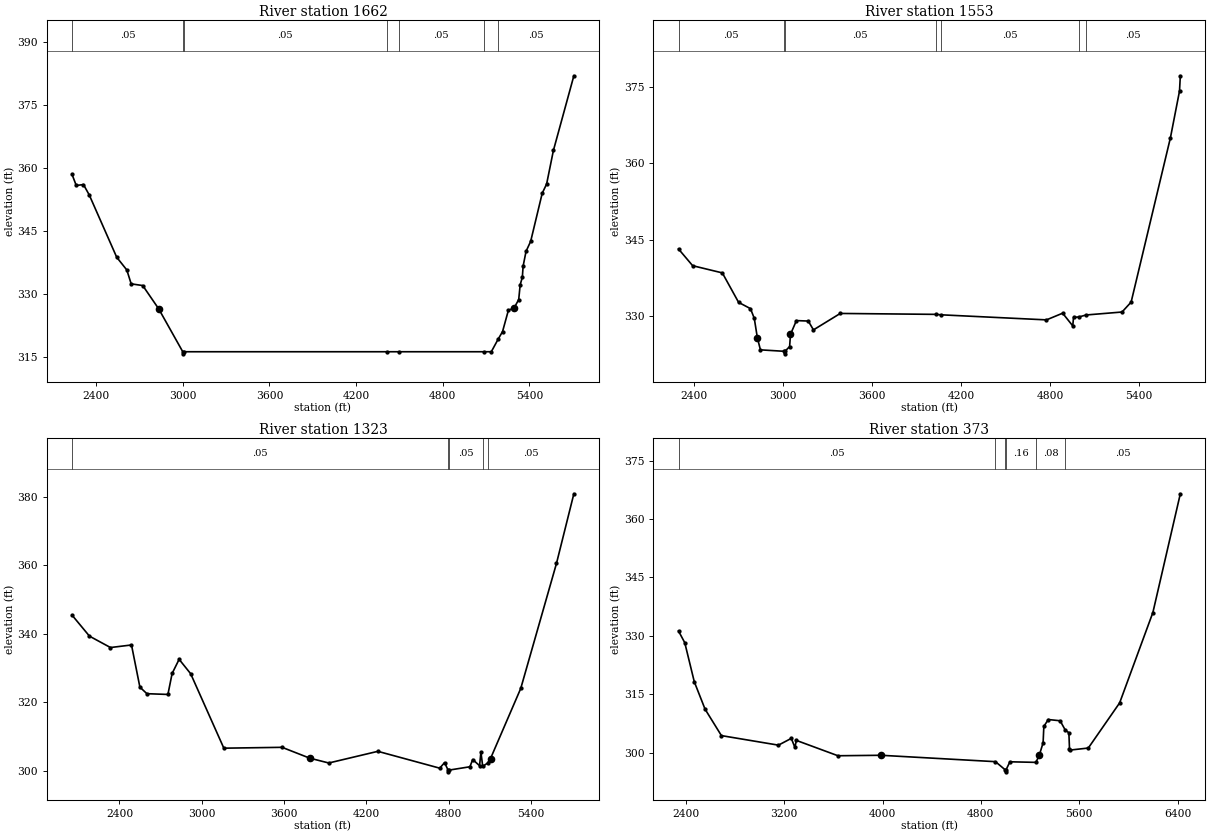
Type RM Length L Ch R = 1 ,1662    ,109,109,109
BEGIN DESCRIPTION:
Mapping XS 8cc27db6
END DESCRIPTION:
XS GIS Cut Line= 6
      3609719.51     10527459.13      3609768.12     10526403.57
      3609837.56     10526250.79      3609761.17     10525577.18
      3609448.67     10524875.79      3608664.25     10524709.19
#Sta/Elev= 30
  2233.5  358.49  2262.5  355.87  2312.5  356.09  2352.5  353.61  2542.7  338.76
  2612.6  335.73  2642.8  332.42  2722.8  332.02  2832.9  326.49    3000  316.24
  3002.8  315.74    3006  316.24  4412.6  316.24  4494.5  316.24  5082.9  316.24
  5136.6  316.24    5183  319.18  5214.3  321.04    5255  326.14    5294  326.66
  5326.3  328.67  5336.4  332.19  5351.5     334  5356.8  336.63  5377.1  340.17
  5409.1  342.55  5489.1  354.02  5519.6  356.22  5566.5  364.21  5708.2  382.02
#Mann= 7 ,-1 , 0
  2233.5     .05       0    3000    .033       0    3006     .05       0
  4412.6     .08       0  4494.5     .05       0  5082.9     .08       0
    5183     .05       0
Bank Sta=2832.9,5294
XS Rating Curve= 0 ,0
Exp/Cntr=0.3,0.1

Type RM Length L Ch R = 1 ,1553    ,230,230,230
BEGIN DESCRIPTION:
Mapping XS 3738bc30
END DESCRIPTION:
XS GIS Cut Line= 6
      3610240.35     10527223.06      3609962.56     10526188.29
      3609865.34     10525549.41      3609636.17     10524986.91
      3609504.23     10524778.57       3608714.2     10524605.28
#Sta/Elev= 30
  2295.4   343.2  2390.5  339.93  2590.5  338.52  2700.1  332.75  2780.1  331.52
  2805.7  329.63  2826.4  325.84  2847.1  323.45  3006.7  323.17  3009.5  322.67
  3012.7  323.17  3043.9   324.1  3049.7  326.49  3089.7  329.18  3169.7  329.09
  3204.5  327.36  3385.1  330.58  4026.8   330.4  4065.9  330.31  4774.6  329.32
  4883.5  330.63  4951.6  328.14  4956.8  329.79  4995.4  329.91  5041.8  330.28
  5283.7  330.86  5344.9   332.8  5609.8     365  5670.9  374.13  5676.4  377.12
#Mann= 7 ,-1 , 0
  2295.4     .05       0  3006.7     .07       0  3012.7     .05       0
  4026.8      .1       0  4065.9     .05       0  4995.4     .07       0
  5041.8     .05       0
Bank Sta=2826.4,3049.7
XS Rating Curve= 0 ,0
Exp/Cntr=0.3,0.1

Type RM Length L Ch R = 1 ,1323    ,950,950,950
BEGIN DESCRIPTION:
Mapping XS d6ba956b
END DESCRIPTION:
XS GIS Cut Line= 6
      3610337.57     10527174.45       3610108.4     10526056.35
      3610032.01     10525438.29      3609643.12     10524618.85
      3609525.06     10524521.63      3608693.18     10524480.03
#Sta/Elev= 30
  2054.5  345.45  2181.3  339.33  2334.5  336.01  2487.6  336.76  2548.8  324.46
  2599.9  322.55    2753  322.33  2783.6  328.44  2834.7  332.57  2918.7  328.38
  3160.6  306.66  3584.9  306.91  3786.5  303.75  3925.4  302.34    4283  305.74
    4734  300.83  4769.2  302.45  4794.9  300.26  4797.6  299.76  4800.9  300.26
  4954.1  301.24  4974.2  303.35  5024.2  301.55  5034.2  305.51  5047.2  301.36
  5082.3   302.3  5104.3  303.65  5324.6   324.1  5584.9  360.55  5711.5  380.85
#Mann= 5 ,-1 , 0
  2054.5     .05       0  4794.9     .03       0  4800.9     .05       0
  5047.2     .12       0  5082.3     .05       0
Bank Sta=3786.5,5104.3
XS Rating Curve= 0 ,0
Exp/Cntr=0.3,0.1

Type RM Length L Ch R = 1 ,373     ,0,0,0
BEGIN DESCRIPTION:
BOW BRANCH 1.0
END DESCRIPTION:
XS GIS Cut Line= 5
      3610585.82      10526448.7      3610012.91     10524151.84
      3609825.41     10523792.46      3609596.24     10523641.42
      3608580.61     10523438.29
#Sta/Elev= 30
  2340.1  331.22  2390.8  328.23  2468.2  318.21  2555.9  311.17    2689  304.38
  3152.8  301.93  3257.6  303.67  3286.8  301.35  3298.8  303.15  3637.2  299.21
  3987.6  299.33  4918.8  297.69  4998.6  295.58  5001.3  295.08  5004.6  295.58
  5036.3  297.66    5248  297.51  5276.3  299.43  5306.4  302.55  5312.4  306.74
  5348.6  308.51  5444.9  308.19  5486.9  305.79  5516.1  305.12  5521.1  301.03
  5526.5  300.67  5674.1  301.19  5929.1  312.78  6199.6  335.98  6422.9  366.46
#Mann= 6 ,-1 , 0
  2340.1     .05       0  4918.8     .16       0  4998.6     .07       0
  5004.6     .16       0    5248     .08       0  5486.9     .05       0
Bank Sta=3987.6,5276.3
XS Rating Curve= 0 ,0
Exp/Cntr=0.3,0.1

Chan Stop Cuts=-1
Use User Specified Reach Order=0
Composite Channel Slope=5