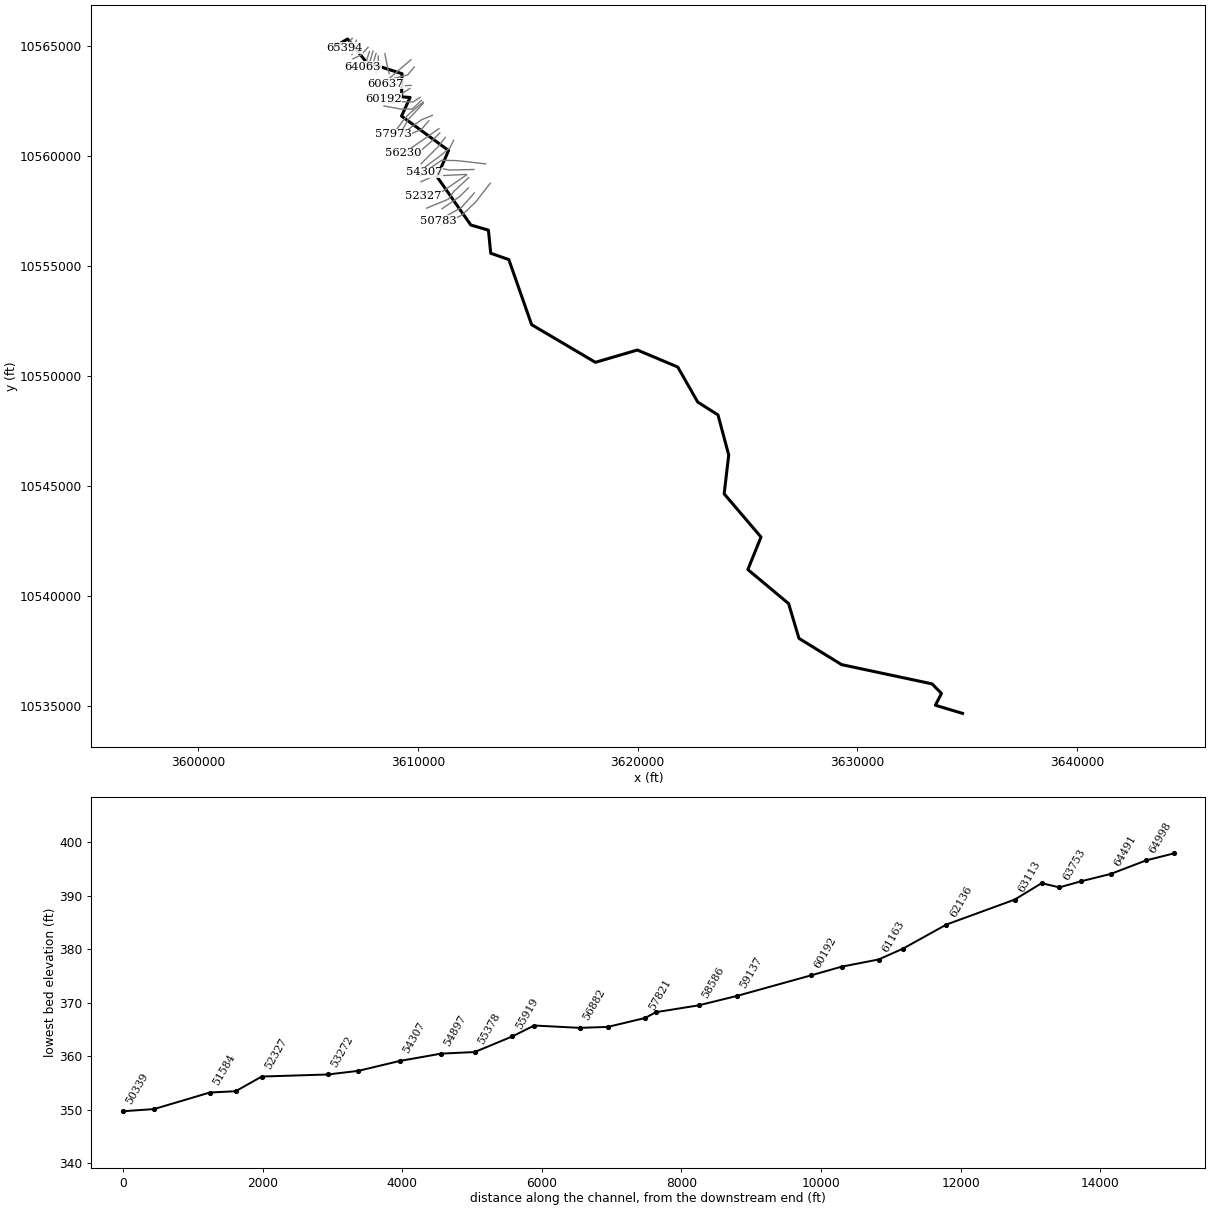
--- BROWNS CREEK.prj (project) ---

Proj Title=BROWNS CREEK Base Level Engineering
Current Plan=p01
Default Exp/Contr=0.3,0.1
English Units
Geom File=g01
Flow File=f01
Plan File=p01
Y Axis Title=Elevation
X Axis Title(PF)=Main Channel Distance
X Axis Title(XS)=Station
BEGIN DESCRIPTION:
BROWNS CREEK
END DESCRIPTION:
DSS Export Rating Curves= 0
DSS Export Rating Curve Sorted= 0
DSS Export Volume Flow Curves= 0
DXF OffsetX= 0
DXF OffsetY= 0
DXF ScaleX= 1
DXF ScaleY= 10

--- BROWNS CREEK.p01 (plan) ---

Plan Title=Multiple Run
Short Identifier=Multiple
Geom File=g01
Flow File=f01
Subcritical Flow
K Sum by GR= 0
Std Step Tol= 0.01
Critical Tol= 0.01
Num of Std Step Trials= 20
Max Error Tol= 0.3
Flow Tol Ratio= 0.001
Split Flow NTrial= 30
Split Flow Tol= 0.02
Split Flow Ratio= 0.02
Log Output Level= 0
Friction Slope Method= 1
Unsteady Friction Slope Method= 2
Unsteady Bridges Friction Slope Method= 1
Parabolic Critical Depth
Global Vel Dist=  1 , 1 , 1
Global Log Level= 0
CheckData=True
Encroach Param= -1, 0, 0, 0
BEGIN DESCRIPTION:
Multiple Run
END DESCRIPTION:

--- BROWNS CREEK.f01 (steady flow) ---

Flow Title=Multiple
Program Version=4.10
Number of Profiles= 7
Profile Names=10-year,25-year,50-year,1pct_min,100-year,1pct_plu,500-year
River Rch & RM=BROWNS CREEK,Reach-1         ,65394
     975    1328    1617    1436    1942    2627    2794
River Rch & RM=BROWNS CREEK,Reach-1         ,61510
    2146    3039    3797    3451    4667    6312    7036
River Rch & RM=BROWNS CREEK,Reach-1         ,54307
    2935    4203    5289    4838    6542    8848    9984
River Rch & RM=BROWNS CREEK,Reach-1         ,52327
    2935    4203    5289    4838    6542    8848    9984
River Rch & RM=BROWNS CREEK,Reach-1         ,47793
    3418    4918    6209    5693    7699   10412   11813
River Rch & RM=BROWNS CREEK,Reach-1         ,40470
    3962    5731    7260    6678    9031   12213   13941
River Rch & RM=BROWNS CREEK,Reach-1         ,33922
    4641    6744    8572    7905   10691   14458   16592
River Rch & RM=BROWNS CREEK,Reach-1         ,31732
    4641    6744    8572    7905   10691   14458   16592
River Rch & RM=BROWNS CREEK,Reach-1         ,28854
    7063   10397   13331   12391   16757   22662   26406
River Rch & RM=BROWNS CREEK,Reach-1         ,25028
    7604   11192   14348   13330   18027   24380   28381
River Rch & RM=BROWNS CREEK,Reach-1         ,19334
    7604   11192   14348   13330   18027   24380   28381
River Rch & RM=BROWNS CREEK,Reach-1         ,9343
    9561   14150   18213   16978   22961   31053   36390
River Rch & RM=BROWNS CREEK,Reach-1         ,5755
    9561   14150   18213   16978   22961   31053   36390
Boundary for River Rch & Prof#=BROWNS CREEK,Reach-1         , 1
Up Type= 0
Dn Type= 3
Dn Slope=0.002
Boundary for River Rch & Prof#=BROWNS CREEK,Reach-1         , 2
Up Type= 0
Dn Type= 3
Dn Slope=0.002
Boundary for River Rch & Prof#=BROWNS CREEK,Reach-1         , 3
Up Type= 0
Dn Type= 3
Dn Slope=0.002
Boundary for River Rch & Prof#=BROWNS CREEK,Reach-1         , 4
Up Type= 0
Dn Type= 3
Dn Slope=0.002
Boundary for River Rch & Prof#=BROWNS CREEK,Reach-1         , 5
Up Type= 0
Dn Type= 3
Dn Slope=0.002
Boundary for River Rch & Prof#=BROWNS CREEK,Reach-1         , 6
Up Type= 0
Dn Type= 3
Dn Slope=0.002
Boundary for River Rch & Prof#=BROWNS CREEK,Reach-1         , 7
Up Type= 0
Dn Type= 3
Dn Slope=0.002
DSS Import GetInterval= 0
DSS Import GetPeak= 0
DSS Import FillOption= 0

--- BROWNS CREEK.g01 (geometry) ---

Geom Title=Existing Conditions
Program Version=4.10

River Reach=BROWNS CREEK    ,Reach-1
Reach XY= 30
      3606199.25       10564982.       3606803.5       10565338.
       3607667.5       10564275.      3609281.75       10563757.
        3609261.       10562705.      3609648.75       10562675.
      3609258.75       10561828.      3611400.25       10560260.
        3610875.       10559067.        3612410.       10556871.
       3613212.5       10556637.        3613318.       10555586.
       3614141.5       10555297.       3615178.5       10552336.
      3618081.25       10550622.        3619992.       10551181.
        3621829.       10550409.        3622740.       10548810.
      3623660.25       10548229.      3624149.25       10546406.
      3623941.75       10544636.        3625619.       10542670.
       3625019.5       10541190.        3626874.       10539642.
       3627345.5       10538059.        3629286.       10536864.
      3633403.75       10535988.       3633831.5       10535553.
      3633554.25       10535015.       3634789.5       10534645.

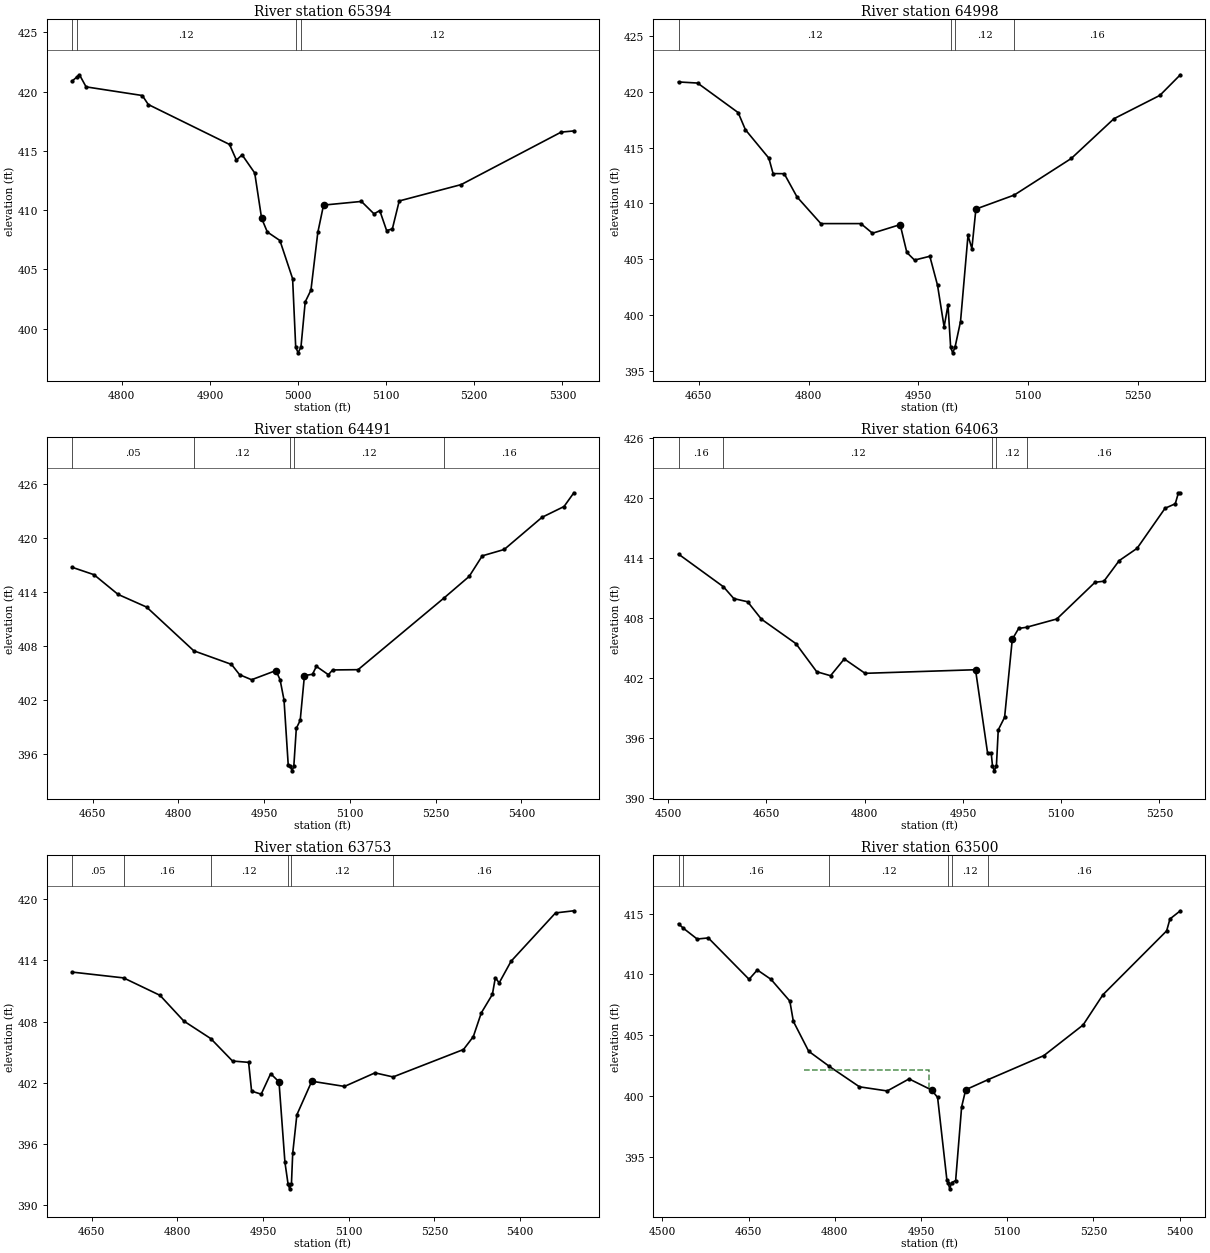
Type RM Length L Ch R = 1 ,65394   ,396,396,396
BEGIN DESCRIPTION:
BROWNS CREEK 108.0
END DESCRIPTION:
XS GIS Cut Line= 2
       3607015.5     10565366.62      3606650.91     10564929.11
#Sta/Elev= 30
  4743.5  420.89  4748.8  421.22  4751.9  421.42  4759.4   420.4  4823.2  419.67
    4830  418.91  4922.2  415.54    4930  414.22  4936.5  414.66  4950.8  413.13
  4958.6  409.31  4965.1  408.15  4979.4  407.43  4993.8  404.21  4997.3  398.45
    5000  397.95  5003.3  398.45  5008.1  402.25  5014.6  403.24  5022.4  408.11
  5028.9  410.42  5071.9  410.73  5086.2  409.68  5092.7  409.96  5100.5  408.27
    5107  408.41  5114.8  410.77  5185.1  412.15  5298.6  416.58    5313  416.68
#Mann= 4 ,-1 , 0
  4743.5     .05       0  4748.8     .12       0  4997.3     .07       0
  5003.3     .12       0
Bank Sta=4958.6,5028.9
XS Rating Curve= 0 ,0
Exp/Cntr=0.3,0.1

Type RM Length L Ch R = 1 ,64998   ,507,507,507
BEGIN DESCRIPTION:
BROWNS CREEK 107.0
END DESCRIPTION:
XS GIS Cut Line= 2
      3607202.95     10565277.99      3607000.38     10564623.52
#Sta/Elev= 30
  4622.5  420.86  4648.5  420.76  4703.9  418.12  4713.8  416.59  4745.8  414.05
  4751.6  412.67  4766.8  412.66  4784.2  410.59  4816.8   408.2  4871.4   408.2
  4887.3  407.34  4925.1  408.11  4934.2  405.62  4944.7  404.94  4965.6  405.28
  4976.1  402.69  4985.1  398.97  4990.4  400.93    4994  397.15  4996.8  396.65
    5000  397.15  5007.5  399.45  5017.7  407.14    5023  405.97  5028.5   409.5
  5080.8  410.75  5158.7  414.02  5216.9  417.57  5279.7  419.66  5307.6   421.5
#Mann= 4 ,-1 , 0
  4622.5     .12       0    4994     .07       0    5000     .12       0
  5080.8     .16       0
Bank Sta=4925.1,5028.5
XS Rating Curve= 0 ,0
Exp/Cntr=0.3,0.1

Type RM Length L Ch R = 1 ,64491   ,428,428,428
BEGIN DESCRIPTION:
BROWNS CREEK 106.0
END DESCRIPTION:
XS GIS Cut Line= 3
      3607734.93     10564958.81      3607405.04     10564602.87
       3607049.1     10564437.92
#Sta/Elev= 30
  4614.2  416.78  4652.6  415.95  4694.6  413.76  4744.5  412.35  4827.1  407.48
    4893  405.97  4907.2  404.82  4928.2  404.26  4970.7  405.28    4978  404.26
  4984.9     402  4992.2  394.82    4996  394.62  4998.8  394.12    5002  394.62
  5006.4  398.85  5013.2  399.74  5020.6  404.72  5034.7  404.87  5041.5  405.75
  5062.5  404.82  5069.9  405.35  5114.4  405.38  5264.9  413.37  5308.7  415.76
  5331.6  418.05    5370  418.76  5436.1  422.34  5474.6  423.54  5491.8  425.07
#Mann= 5 ,-1 , 0
  4614.2     .05       0  4827.1     .12       0    4996     .07       0
    5002     .12       0  5264.9     .16       0
Bank Sta=4970.7,5020.6
XS Rating Curve= 0 ,0
Exp/Cntr=0.3,0.1

Type RM Length L Ch R = 1 ,64063   ,310,310,310
BEGIN DESCRIPTION:
BROWNS CREEK 105.0
END DESCRIPTION:
XS GIS Cut Line= 3
      3607799.62     10564760.24      3607649.61     10564310.19
      3607499.63     10564060.22
#Sta/Elev= 30
  4515.9  414.42  4584.5  411.15  4600.3  409.97  4621.4  409.65  4642.4  407.91
  4695.1  405.46  4726.8  402.65  4747.9  402.25  4768.9  403.93  4800.6  402.49
  4969.2  402.85  4987.7  394.47  4993.2  394.47  4995.1  393.23  4997.8  392.73
  5001.1  393.23  5003.9  396.83  5013.6  398.09  5025.3  405.89    5035  406.98
  5047.1   407.1  5093.3  407.93  5151.6   411.6  5165.2  411.71  5188.5  413.77
  5215.8     415  5258.5  419.01  5274.1  419.46  5278.9  420.56  5281.8  420.56
#Mann= 5 ,-1 , 0
  4515.9     .16       0  4584.5     .12       0  4995.1     .07       0
  5001.1     .12       0  5047.1     .16       0
Bank Sta=4969.2,5025.3
XS Rating Curve= 0 ,0
Exp/Cntr=0.3,0.1

Type RM Length L Ch R = 1 ,63753   ,253,253,253
BEGIN DESCRIPTION:
BROWNS CREEK 104.0
END DESCRIPTION:
XS GIS Cut Line= 2
      3607962.77     10564787.97       3607715.5     10563944.67
#Sta/Elev= 30
  4615.5  412.85  4705.7  412.28  4769.5  410.57  4811.2  408.05  4858.4  406.33
  4896.5  404.13  4924.7     404  4929.9  401.18  4946.7  400.88  4963.3  402.89
  4977.9  402.09  4988.3   394.2  4993.7   392.1  4996.5   391.6  4999.7   392.1
  5001.9  395.07  5009.2  398.86  5035.3  402.15  5092.6  401.64    5146  402.97
  5177.7  402.57    5301  405.26  5318.2  406.52  5332.2  408.85  5351.6  410.66
  5356.8   412.3  5363.5  411.79  5384.3  413.91  5462.2  418.65  5494.3  418.86
#Mann= 6 ,-1 , 0
  4615.5     .05       0  4705.7     .16       0  4858.4     .12       0
  4993.7     .07       0  4999.7     .12       0  5177.7     .16       0
Bank Sta=4977.9,5035.3
XS Rating Curve= 0 ,0
Exp/Cntr=0.3,0.1

Type RM Length L Ch R = 1 ,63500   ,387,387,387
BEGIN DESCRIPTION:
Mapping XS 327a538c
END DESCRIPTION:
XS GIS Cut Line= 3
      3608100.79     10564681.21      3607934.12     10564134.31
      3607783.07     10563873.88
#Sta/Elev= 30
  4528.3  414.16  4536.3  413.81  4560.7  412.91  4580.1     413    4651   409.6
  4665.3  410.37  4689.1   409.6  4721.9  407.81    4728  406.15  4754.7  403.69
  4790.6  402.45    4843  400.77  4891.3  400.43  4929.3  401.42  4968.4  400.51
  4978.9   399.9    4995  393.15  4997.2  392.89    5000  392.39  5003.2  392.89
  5010.3  393.07  5020.7  399.12  5027.8  400.53  5065.8  401.34  5163.6  403.33
    5232  405.85  5266.6  408.34  5377.3  413.58  5383.1  414.56  5401.1  415.23
#Mann= 6 ,-1 , 0
  4528.3     .05       0  4536.3     .16       0  4790.6     .12       0
  4997.2     .07       0  5003.2     .12       0  5065.8     .16       0
#XS Ineff= 1 ,-1
 4746.36 4963.86  402.17
Permanent Ineff=
       F
Bank Sta=4968.4,5027.8
XS Rating Curve= 0 ,0
Exp/Cntr=0.3,0.1

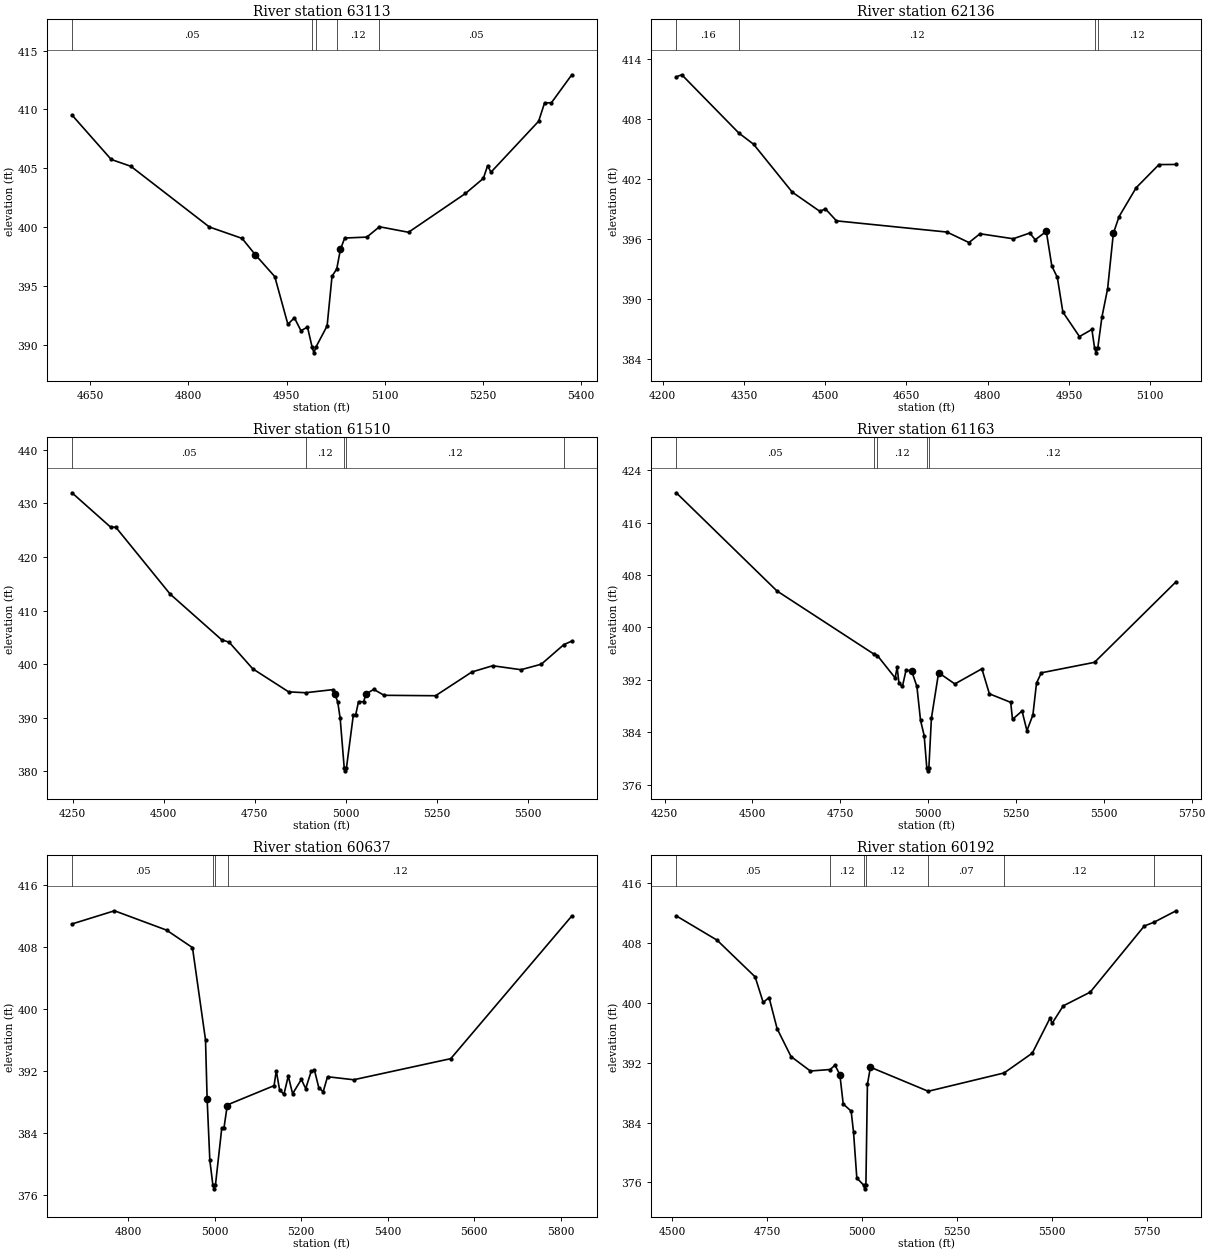
Type RM Length L Ch R = 1 ,63113   ,977,977,977
BEGIN DESCRIPTION:
BROWNS CREEK 103.0
END DESCRIPTION:
XS GIS Cut Line= 3
      3608199.61     10564560.19      3608199.61     10564160.19
      3608099.61      10563810.2
#Sta/Elev= 30
    4622  409.53    4682  405.75    4712  405.17    4832  400.01    4882  399.04
    4902  397.67    4932  395.79    4952  391.74    4962  392.29    4972  391.19
    4982   391.5    4989  389.81  4991.8  389.31    4995  389.81    5012   391.6
  5019.5  395.82  5026.7  396.44  5032.4  398.12  5038.9  399.07  5072.7  399.15
    5092  400.03  5136.4  399.56  5223.5  402.86  5250.8  404.14  5257.3  405.22
  5262.5  404.67  5335.3     409  5344.4  410.56  5354.8  410.57    5386  412.95
#Mann= 5 ,-1 , 0
    4622     .05       0    4989     .03       0    4995     .05       0
  5026.7     .12       0    5092     .05       0
Bank Sta=4902,5032.4
XS Rating Curve= 0 ,0
Exp/Cntr=0.3,0.1

Type RM Length L Ch R = 1 ,62136   ,626,626,626
BEGIN DESCRIPTION:
BROWNS CREEK 102.0
END DESCRIPTION:
XS GIS Cut Line= 3
       3608499.6     10564660.24      3608649.61     10563910.19
       3608699.6      10563760.2
#Sta/Elev= 30
    4225  412.26  4235.2  412.46  4340.6  406.63  4367.8  405.51  4439.2  400.72
  4490.2   398.8  4500.4  399.05  4520.8  397.85  4724.8  396.73  4765.5  395.68
  4785.9  396.56  4847.1  396.06  4877.7  396.63  4887.9  395.96  4908.3   396.8
  4918.5  393.33  4928.7  392.19  4938.9  388.73  4969.5  386.28  4992.5  386.99
  4997.4  385.15  5000.2  384.65  5003.4  385.15    5011  388.22  5021.5  391.05
  5032.1  396.59  5042.6  398.27  5074.2  401.16  5116.4  403.48    5148  403.49
#Mann= 4 ,-1 , 0
    4225     .16       0  4340.6     .12       0  4997.4     .07       0
  5003.4     .12       0
Bank Sta=4908.3,5032.1
XS Rating Curve= 0 ,0
Exp/Cntr=0.3,0.1

Type RM Length L Ch R = 1 ,61510   ,347,347,347
BEGIN DESCRIPTION:
BROWNS CREEK 101.0
END DESCRIPTION:
XS GIS Cut Line= 2
      3609687.32      10564392.6      3608645.65     10563496.76
#Sta/Elev= 30
  4247.8  431.95    4354  425.55  4368.3  425.53  4517.5  413.08  4659.1  404.56
    4680  404.09  4744.7  399.14  4843.4  394.84    4890  394.68  4964.1  395.25
  4970.7  394.45  4978.4  392.91    4985  389.93  4996.2  380.62    4999  380.12
  5002.2  380.62  5021.2  390.52  5027.8   390.6  5035.4  393.01  5049.3  393.01
  5056.3  394.44  5077.2  395.31  5105.7   394.2  5247.2  394.12  5347.1  398.55
  5404.1  399.71    5482  398.97    5538     400  5599.9  403.65  5621.7   404.3
#Mann= 5 ,-1 , 0
  4247.8     .05       0    4890     .12       0  4996.2     .07       0
  5002.2     .12       0  5599.9     .16       0
Bank Sta=4970.7,5056.3
XS Rating Curve= 0 ,0
Exp/Cntr=0.3,0.1

Type RM Length L Ch R = 1 ,61163   ,526,526,526
BEGIN DESCRIPTION:
BROWNS CREEK 100.0
END DESCRIPTION:
XS GIS Cut Line= 3
       3609838.4     10564064.52      3609541.51     10563705.12
      3608614.54     10563470.77
#Sta/Elev= 30
  4283.5  420.57    4570  405.58  4845.8  395.94  4855.7  395.72  4906.3   392.3
    4912  393.92  4917.2  391.47    4927     391  4937.3  393.47  4953.1  393.38
  4968.2     391  4978.5  385.84  4988.9  383.49  4996.3  378.61    4999  378.11
  5002.3  378.61  5009.5  386.14    5030   393.1  5076.2  391.38  5153.1  393.69
  5174.5  389.87  5235.1  388.57  5240.3  385.97  5267.4  387.25  5281.3  384.24
  5298.3  386.64  5308.6  391.52  5322.3  393.08  5473.6  394.68  5705.8  406.99
#Mann= 5 ,-1 , 0
  4283.5     .05       0  4845.8     .07       0  4855.7     .12       0
  4996.3     .07       0  5002.3     .12       0
Bank Sta=4953.1,5030
XS Rating Curve= 0 ,0
Exp/Cntr=0.3,0.1

Type RM Length L Ch R = 1 ,60637   ,445,445,445
BEGIN DESCRIPTION:
BROWNS CREEK 99.0
END DESCRIPTION:
XS GIS Cut Line= 3
      3609697.75     10563225.95      3609349.61     10563210.19
      3608549.63     10563310.19
#Sta/Elev= 30
  4670.4  410.92  4768.6  412.62  4888.8  410.13  4948.8  407.87  4978.9  395.98
 4982.61  388.42  4988.9  380.45  4995.9  377.28  4998.6  376.78  5001.9  377.28
  5016.4  384.57  5021.4  384.57    5029  387.47  5031.1  387.64  5137.3  390.08
  5142.4     392  5149.9  389.57    5160  388.95  5170.1  391.32  5180.1  389.04
  5200.3  390.88  5210.4   389.7    5223  391.92  5230.5  392.09  5240.6  389.82
  5250.7  389.29  5260.8  391.23  5321.2  390.84  5545.5  393.56  5825.1  411.95
#Mann= 4 ,-1 , 0
  4670.4     .05       0  4995.9     .03       0  5001.9     .05       0
  5031.1     .12       0
Bank Sta=4982.61,5029
XS Rating Curve= 0 ,0
Exp/Cntr=0.3,0.1

Type RM Length L Ch R = 1 ,60192   ,1055,1055,1055
BEGIN DESCRIPTION:
BROWNS CREEK 98.0
END DESCRIPTION:
XS GIS Cut Line= 4
      3609640.48     10563085.34      3609374.84     10562918.66
      3609135.26       10562752.      3608437.32     10562626.99
#Sta/Elev= 30
  4511.3  411.64  4618.6  408.39  4718.7  403.48  4739.9  400.06  4755.3  400.72
  4776.5  396.55    4813  392.83  4863.9  390.89    4916  391.09  4928.7  391.67
  4941.5  390.41  4950.3  386.49  4971.2  385.52  4977.5  382.69  4986.1  376.58
    5004  375.63  5006.8  375.13    5010  375.63    5014  389.09  5021.8   391.4
  5173.9  388.18  5373.5  390.63  5447.6  393.28  5494.5  397.99  5499.6  397.26
  5528.9   399.6    5600  401.44  5742.2  410.29    5767  410.77  5825.8  412.32
#Mann= 7 ,-1 , 0
  4511.3     .05       0    4916     .12       0    5004     .07       0
    5010     .12       0  5173.9     .07       0  5373.5     .12       0
    5767     .05       0
Bank Sta=4941.5,5021.8
XS Rating Curve= 0 ,0
Exp/Cntr=0.3,0.1

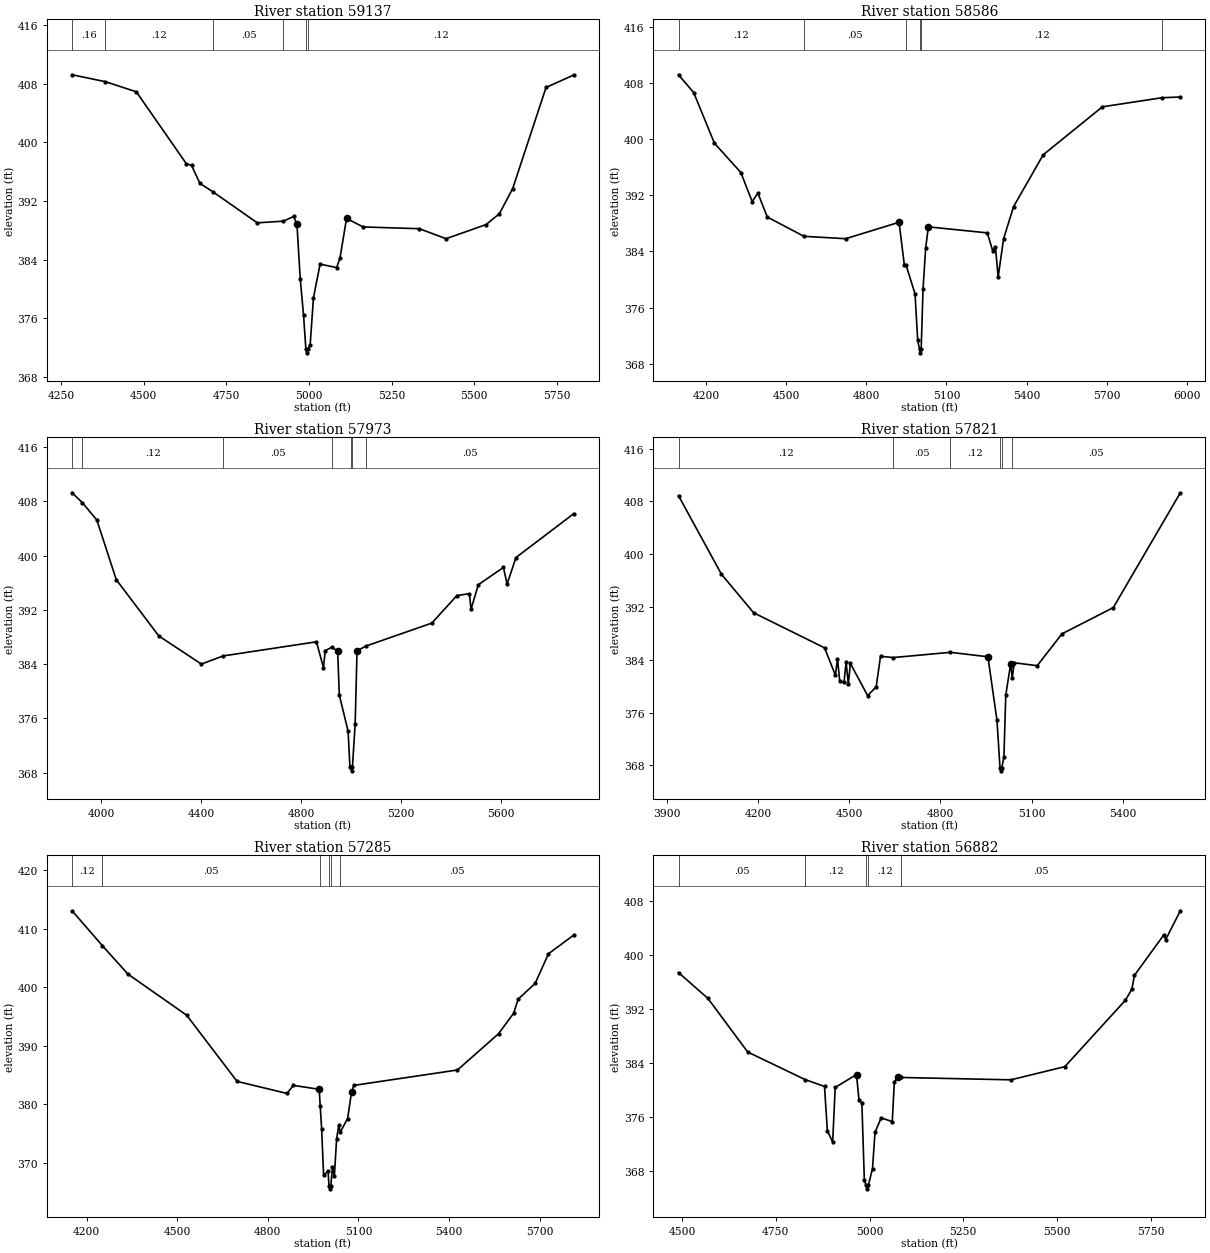
Type RM Length L Ch R = 1 ,59137   ,551,551,551
BEGIN DESCRIPTION:
BROWNS CREEK 97.0
END DESCRIPTION:
XS GIS Cut Line= 4
       3610109.2     10562679.07      3609781.09     10562470.75
      3609145.67     10562486.37      3608656.11     10562423.87
#Sta/Elev= 30
  4283.2  409.19  4383.9  408.25  4477.6  406.87  4629.2  397.05  4644.5  396.86
  4669.8   394.4  4710.8   393.2  4843.4  389.02  4922.4  389.25  4953.4  389.89
  4963.4  388.81  4973.4  381.37  4983.4  376.43  4990.4  371.81  4993.2  371.31
  4996.4  371.81  5003.4  372.43  5013.4  378.83  5033.4   383.4  5083.5  382.92
  5093.5  384.21  5113.5  389.63  5163.5  388.46  5333.7  388.22  5414.4  386.86
  5535.4  388.78  5575.7  390.26    5616  393.69  5716.8  407.46    5801  409.17
#Mann= 6 ,-1 , 0
  4283.2     .16       0  4383.9     .12       0  4710.8     .05       0
  4922.4     .12       0  4990.4     .07       0  4996.4     .12       0
Bank Sta=4963.4,5113.5
XS Rating Curve= 0 ,0
Exp/Cntr=0.3,0.1

Type RM Length L Ch R = 1 ,58586   ,613,613,613
BEGIN DESCRIPTION:
BROWNS CREEK 96.0
END DESCRIPTION:
XS GIS Cut Line= 4
      3610166.51     10562543.67      3609755.05     10562147.83
      3609218.59     10562147.83       3608458.2     10562288.45
#Sta/Elev= 30
  4095.7   409.2  4152.5  406.66  4230.2  399.44  4329.3  395.26  4371.7  391.11
  4393.1  392.32  4428.3  388.91  4565.7  386.16  4722.1  385.82  4922.1  388.16
  4942.1  382.06  4947.8  382.13  4982.1  377.95  4992.1  371.32  4999.1  370.04
  5001.8  369.54  5005.1  370.04  5012.1  378.69  5022.1  384.56  5032.1  387.51
  5252.9  386.65  5273.3  384.09  5283.4  384.66  5293.6  380.34  5313.9   385.8
  5351.6  390.41  5462.5  397.79  5684.3  404.63  5908.2  405.93  5976.4  406.03
#Mann= 6 ,-1 , 0
  4095.7     .12       0  4565.7     .05       0  4947.8     .12       0
  4999.1     .07       0  5005.1     .12       0  5908.2     .05       0
Bank Sta=4922.1,5032.1
XS Rating Curve= 0 ,0
Exp/Cntr=0.3,0.1

Type RM Length L Ch R = 1 ,57973   ,152,152,152
BEGIN DESCRIPTION:
BROWNS CREEK 95.0
END DESCRIPTION:
XS GIS Cut Line= 4
      3610244.62     10562465.53      3609624.84     10561949.91
      3609354.01     10561658.25      3608881.19     10561003.57
#Sta/Elev= 30
  3882.3  409.27  3923.4  407.82  3981.5  405.26  4059.6  396.45  4230.2  388.15
  4400.7  384.01  4488.6  385.21    4862  387.29  4890.3  383.47  4897.1  385.99
  4922.8  386.47    4947  385.96  4953.8  379.42    4989  374.11  4996.3  368.83
  5000.2  368.76  5002.9  368.26  5006.2  368.76  5017.3  375.14  5024.7  385.94
  5059.5  386.65  5324.7  390.05  5425.2  394.11  5475.5  394.39  5481.7  392.07
  5511.1  395.71  5611.7  398.26  5626.4   395.8    5662  399.72  5894.1   406.2
#Mann= 7 ,-1 , 0
  3882.3     .16       0  3923.4     .12       0  4488.6     .05       0
  4922.8     .12       0  5000.2     .07       0  5006.2     .12       0
  5059.5     .05       0
Bank Sta=4947,5024.7
XS Rating Curve= 0 ,0
Exp/Cntr=0.3,0.1

Type RM Length L Ch R = 1 ,57821   ,536,536,536
BEGIN DESCRIPTION:
BROWNS CREEK 94.0
END DESCRIPTION:
XS GIS Cut Line= 3
       3610249.6     10562410.17      3609549.61     10561660.19
      3609249.61     10561110.18
#Sta/Elev= 30
  3937.5  408.85  4078.9  396.95  4184.9  391.12  4418.4  385.81  4454.1  381.66
  4460.9  384.13  4468.3  380.78  4482.4  380.58  4489.3  383.66  4496.6  380.34
  4503.4  383.45  4560.1  378.58  4588.4   379.9  4602.6  384.53  4644.9  384.34
  4832.4  385.13  4956.3  384.46  4986.2  374.82    4996  367.68  4998.7  367.18
    5002  367.68    5009  369.23  5015.1  378.65  5031.3  383.42  5036.4  381.27
  5043.1  383.55  5118.6  383.11  5200.2  387.93  5369.2  391.91  5589.9   409.3
#Mann= 6 ,-1 , 0
  3937.5     .12       0  4644.9     .05       0  4832.4     .12       0
    4996     .07       0    5002     .12       0  5036.4     .05       0
Bank Sta=4956.3,5031.3
XS Rating Curve= 0 ,0
Exp/Cntr=0.3,0.1

Type RM Length L Ch R = 1 ,57285   ,403,403,403
BEGIN DESCRIPTION:
BROWNS CREEK 93.0
END DESCRIPTION:
XS GIS Cut Line= 3
      3610661.31     10561861.37       3610161.3     10561658.25
      3609255.02     10560996.77
#Sta/Elev= 30
  4151.6  413.05  4252.2  407.07  4336.9  402.21  4531.2  395.19    4698  383.88
  4863.3  381.82  4884.2   383.2  4969.9  382.53  4973.3  379.71  4978.1  375.72
  4984.6  367.84  4999.3  368.54  5002.4  366.01  5005.2  365.51  5008.4  366.01
  5013.9  369.21  5020.1  367.64  5027.7  374.09  5034.8   376.4  5039.5  375.19
  5064.1  377.52  5077.2  382.08    5085   383.2  5427.9  385.83  5563.9  392.03
  5614.1  395.55  5628.8  397.94  5685.1  400.63  5729.2   405.7  5813.3  408.91
#Mann= 6 ,-1 , 0
  4151.6     .12       0  4252.2     .05       0  4973.3     .12       0
  5002.4     .07       0  5008.4     .12       0  5039.5     .05       0
Bank Sta=4969.9,5077.2
XS Rating Curve= 0 ,0
Exp/Cntr=0.3,0.1

Type RM Length L Ch R = 1 ,56882   ,652,652,652
BEGIN DESCRIPTION:
BROWNS CREEK 92.0
END DESCRIPTION:
XS GIS Cut Line= 3
       3610499.6     10561610.18      3610149.61     10561210.19
      3609399.58     10560910.18
#Sta/Elev= 30
  4490.2  397.35  4568.5  393.53  4674.8  385.59  4827.9  381.51  4879.8  380.49
  4887.4  373.95  4901.6  372.25  4908.3  380.34  4965.2  382.25  4971.9  378.46
  4979.5  378.05  4986.1  366.68  4990.7  365.83  4993.4  365.33  4996.7  365.83
  5007.9  368.33  5014.6  373.69  5031.1  375.84  5060.7  375.28  5066.1  381.13
  5075.6  381.93  5085.2  381.82  5377.1  381.47  5521.2  383.42  5682.7  393.24
  5700.2   394.9    5707  396.94    5785   402.9  5790.4  402.24  5829.5   406.5
#Mann= 5 ,-1 , 0
  4490.2     .05       0  4827.9     .12       0  4990.7     .07       0
  4996.7     .12       0  5085.2     .05       0
Bank Sta=4965.2,5075.6
XS Rating Curve= 0 ,0
Exp/Cntr=0.3,0.1

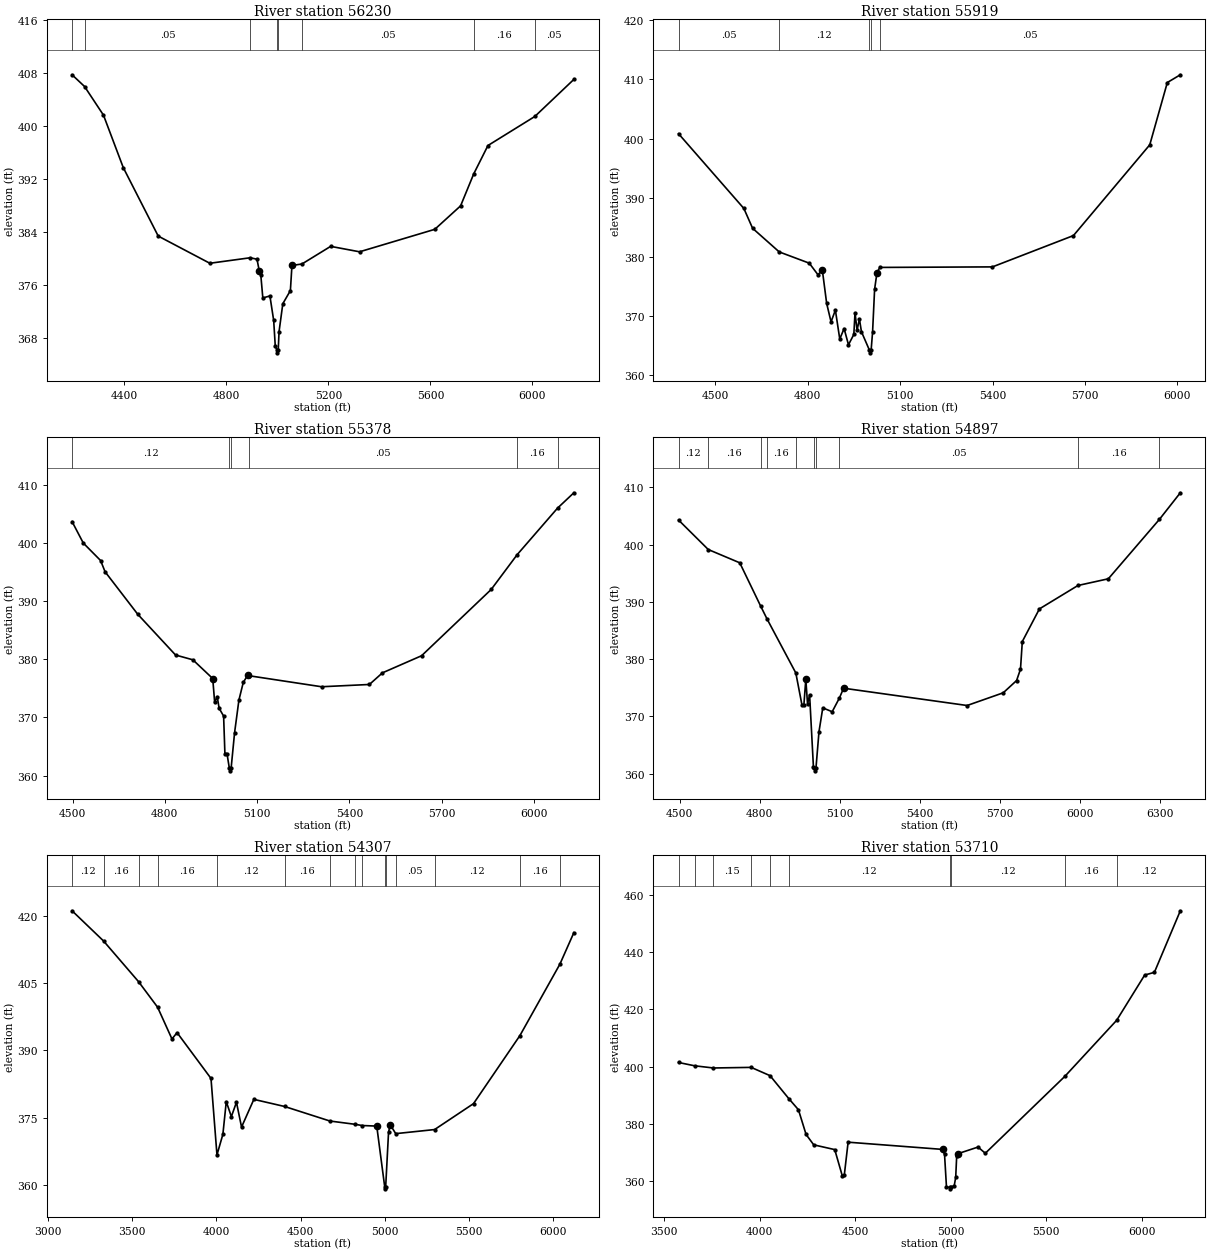
Type RM Length L Ch R = 1 ,56230   ,311,311,311
BEGIN DESCRIPTION:
BROWNS CREEK 91.0
END DESCRIPTION:
XS GIS Cut Line= 2
      3610963.41     10561257.22       3609348.8      10560132.2
#Sta/Elev= 30
  4194.7  407.71  4243.7  405.94  4317.9  401.62  4395.5  393.71  4532.6  383.38
    4735  379.28  4893.3  380.11    4920  379.89  4928.7  378.14  4934.8  377.54
  4942.8  374.05  4970.6  374.35  4985.4  370.65  4991.6  366.78  4997.3  366.27
    5000  365.77  5003.3  366.27  5006.4  368.95  5021.2  373.18  5050.9  375.16
    5057  378.95  5096.2  379.17  5208.8  381.83  5322.2  381.01  5617.2   384.4
  5718.4  387.94  5770.1  392.78  5825.7  397.04  6009.5  401.42  6162.6  407.01
#Mann= 8 ,-1 , 0
  4194.7     .12       0  4243.7     .05       0  4893.3     .12       0
  4997.3     .07       0  5003.3     .12       0  5096.2     .05       0
  5770.1     .16       0  6009.5     .05       0
Bank Sta=4928.7,5057
XS Rating Curve= 0 ,0
Exp/Cntr=0.3,0.1

Type RM Length L Ch R = 1 ,55919   ,541,541,541
BEGIN DESCRIPTION:
BROWNS CREEK 90.0
END DESCRIPTION:
XS GIS Cut Line= 3
      3610999.61     10561060.19      3610599.61     10560660.19
      3609799.62     10559960.19
#Sta/Elev= 30
  4380.8  400.81  4592.9  388.16  4621.2  384.81  4707.7  380.81  4805.1  378.91
  4833.4  376.95  4847.5  377.76  4861.6   372.1  4875.8  368.98  4889.9  370.97
  4904.1  366.08  4918.2  367.85  4932.4   365.1  4949.8  366.86  4953.6  370.53
  4960.3  367.54  4967.8  369.48  4974.5  367.31    5000  364.24  5002.7  363.74
    5006  364.24  5010.6  367.24  5017.2  374.49  5024.8  377.28    5034  378.19
  5399.7  378.28  5662.6  383.58  5910.3  398.93  5967.3  409.47  6009.5  410.78
#Mann= 5 ,-1 , 0
  4380.8     .05       0  4707.7     .12       0    5000     .07       0
    5006     .12       0    5034     .05       0
Bank Sta=4847.5,5024.8
XS Rating Curve= 0 ,0
Exp/Cntr=0.3,0.1

Type RM Length L Ch R = 1 ,55378   ,481,481,481
BEGIN DESCRIPTION:
BROWNS CREEK 89.0
END DESCRIPTION:
XS GIS Cut Line= 3
      3611249.62      10560860.2      3610949.61     10560460.19
       3610149.6     10559660.18
#Sta/Elev= 30
  4498.3  403.64  4534.8  399.95    4591  396.95  4605.6  395.02  4711.9  387.71
  4834.8  380.71    4891  379.89  4955.6  376.67  4961.9  372.58  4970.2  373.56
  4976.4  371.56    4991  370.22  4995.2  363.78  5001.9  363.78  5009.5  361.31
  5012.2  360.81  5015.5  361.31  5026.6  367.34  5040.7  372.96  5054.9     376
    5069  377.22  5073.8  377.15  5309.4  375.26    5465  375.65  5507.4  377.65
  5634.7  380.59    5861  391.98  5945.6  397.97  6076.6  405.95  6129.7  408.59
#Mann= 6 ,-1 , 0
  4498.3     .12       0  5009.5     .07       0  5015.5     .12       0
  5073.8     .05       0  5945.6     .16       0  6076.6     .12       0
Bank Sta=4955.6,5069
XS Rating Curve= 0 ,0
Exp/Cntr=0.3,0.1

Type RM Length L Ch R = 1 ,54897   ,590,590,590
BEGIN DESCRIPTION:
BROWNS CREEK 88.0
END DESCRIPTION:
XS GIS Cut Line= 4
      3611630.07     10560725.99      3611468.59     10560397.83
      3611109.22     10560090.54      3610275.92     10559465.56
#Sta/Elev= 30
  4495.6  404.31    4607  399.16    4725  396.84  4803.1   389.3  4826.7  387.08
  4935.1   377.6  4958.2  371.98  4965.3  372.01  4972.5   376.5    4979  372.18
  4986.7   373.8    5001  361.22  5004.6  361.01  5007.3  360.51  5010.6  361.01
  5021.9  367.36  5036.1  371.51  5071.3  370.83  5098.4  373.23  5114.1  374.94
  5576.9  371.92  5712.3  374.14  5762.3  376.28  5776.9  378.27  5783.7  383.09
  5847.8  388.79  5992.2  392.88  6106.1  394.05  6297.7  404.44  6375.8  409.07
#Mann= 10 ,-1 , 0
  4495.6     .12       0    4607     .16       0  4803.1     .05       0
  4826.7     .16       0  4935.1     .12       0  5004.6     .07       0
  5010.6     .12       0  5098.4     .05       0  5992.2     .16       0
  6297.7     .12       0
Bank Sta=4972.5,5114.1
XS Rating Curve= 0 ,0
Exp/Cntr=0.3,0.1

Type RM Length L Ch R = 1 ,54307   ,597,597,597
BEGIN DESCRIPTION:
BROWNS CREEK 87.0
END DESCRIPTION:
XS GIS Cut Line= 4
      3613088.38     10559653.04      3611812.34     10559798.87
      3611088.38      10559819.7      3610286.27     10559278.01
#Sta/Elev= 30
  3144.5  421.06  3331.1  414.34  3538.8  405.28  3651.8  399.59  3737.1  392.51
  3767.3  393.93  3968.6  383.73    4004   366.7  4039.1  371.29  4059.2  378.57
  4089.4  375.23  4119.6  378.43  4149.8   372.9  4222.8  379.07  4404.7  377.49
  4673.8  374.25  4822.9  373.52  4865.3  373.25  4951.8  373.12  4998.8  359.65
  5001.6  359.15  5004.8  359.65  5021.8  371.77  5031.8  373.42  5064.3  371.44
    5295  372.35  5525.7  378.12  5800.8  393.26  6038.1  409.17    6121  416.19
#Mann= 15 ,-1 , 0
  3144.5     .12       0  3331.1     .16       0  3538.8     .12       0
  3651.8     .16       0    4004     .12       0  4404.7     .16       0
  4673.8     .12       0  4822.9     .16       0  4865.3     .12       0
  4998.8     .07       0  5004.8     .12       0  5064.3     .05       0
    5295     .12       0  5800.8     .16       0  6038.1     .12       0
Bank Sta=4951.8,5031.8
XS Rating Curve= 0 ,0
Exp/Cntr=0.3,0.1

Type RM Length L Ch R = 1 ,53710   ,438,438,438
BEGIN DESCRIPTION:
BROWNS CREEK 86.0
END DESCRIPTION:
XS GIS Cut Line= 4
      3612557.17     10559397.83      3611458.17     10559371.79
      3610885.26     10559475.95      3610033.54     10559065.67
#Sta/Elev= 30
  3575.5  401.41  3659.1  400.26    3758  399.49  3955.6   399.7  4054.5  396.81
  4153.3  388.75  4203.2  384.91  4243.2  376.28  4283.3  372.65  4393.3  370.99
  4433.3  361.72  4443.3  362.11  4463.3  373.58  4957.9  371.06  4968.1  369.31
  4978.3  357.86  4995.6  357.79  4998.3  357.29  5001.6  357.79  5018.9   358.4
  5026.6  361.35  5031.7  368.75  5039.2  369.59  5143.5  371.88  5181.5  369.71
  5597.9  396.56  5869.1  416.13  6015.9  431.94  6066.7  432.88  6202.5  454.38
#Mann= 10 ,-1 , 0
  3575.5     .12       0  3659.1     .16       0    3758     .15       0
  3955.6     .16       0  4054.5     .05       0  4153.3     .12       0
  4995.6     .07       0  5001.6     .12       0  5597.9     .16       0
  5869.1     .12       0
Bank Sta=4957.9,5039.2
XS Rating Curve= 0 ,0
Exp/Cntr=0.3,0.1

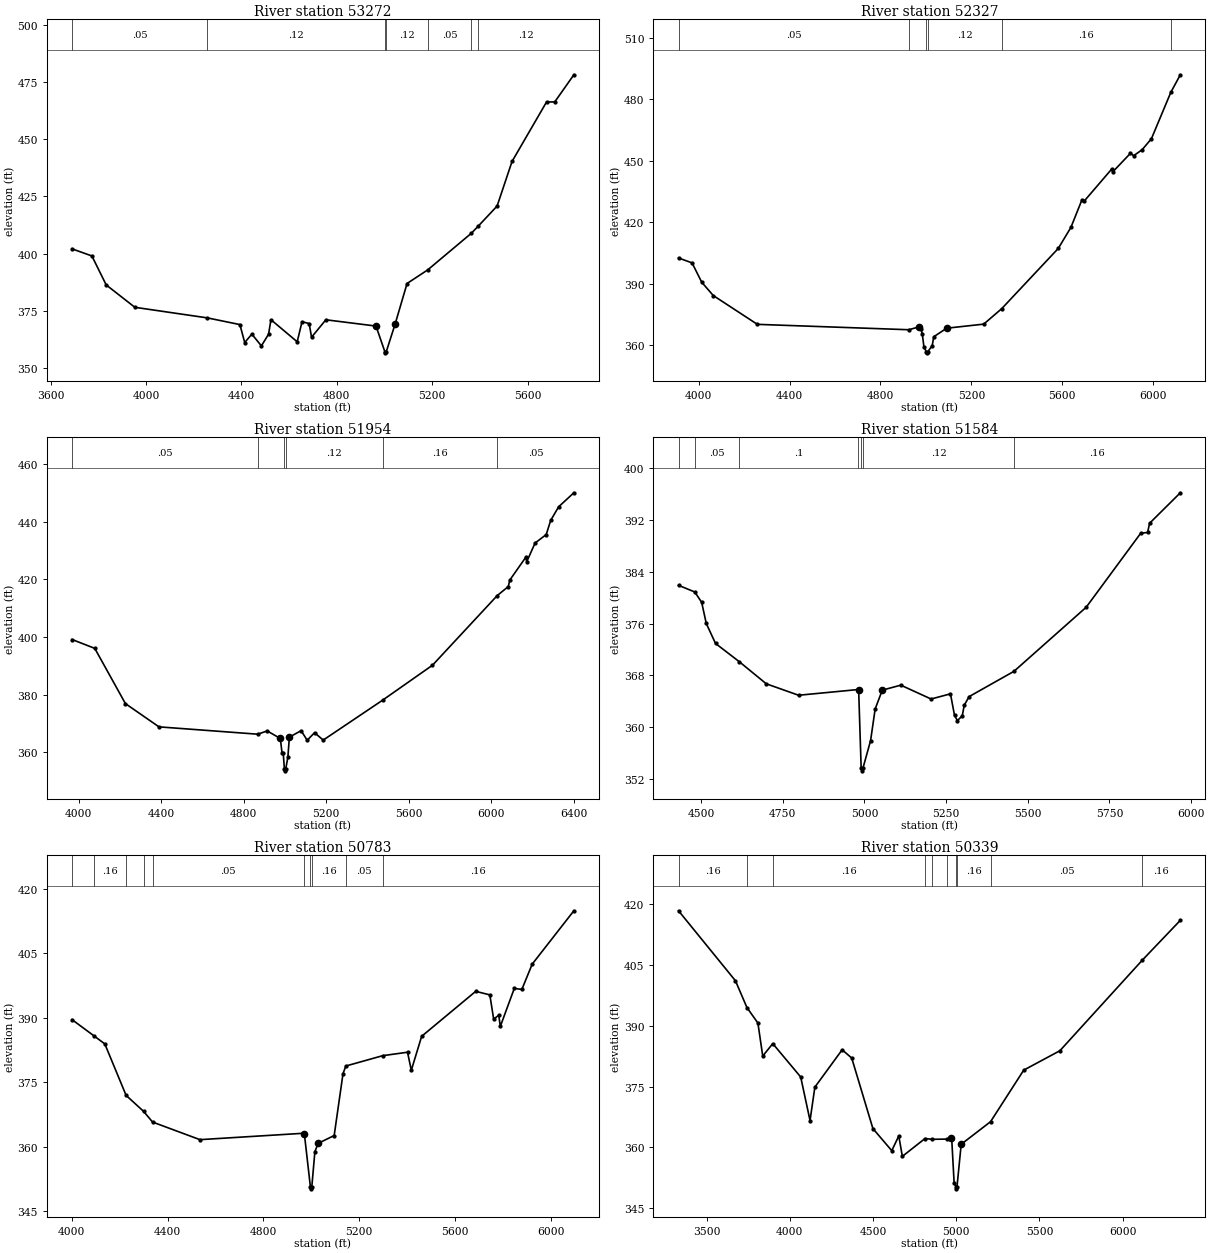
Type RM Length L Ch R = 1 ,53272   ,945,945,945
BEGIN DESCRIPTION:
BROWNS CREEK 85.0
END DESCRIPTION:
XS GIS Cut Line= 3
      3612192.57     10559173.87      3610729.01     10559100.95
      3610145.67     10558840.54
#Sta/Elev= 30
  3689.9  402.09    3773  398.99    3833  386.32  3953.2  376.53  4257.7  371.89
  4393.7  368.97  4413.8  361.12  4443.8  364.79  4483.8  359.65  4513.9  364.76
  4523.9   371.1    4634  361.44  4654.1   370.2  4684.1  369.44  4694.1  363.45
  4754.2  371.07  4964.4  368.32  5001.5  357.11  5004.2  356.61  5007.5  357.11
  5044.5  369.16  5094.6  386.94  5181.1  392.88  5364.3  408.92    5394  412.13
  5472.2  420.81  5534.9  440.34  5679.7  466.36  5713.9  466.36  5794.1  478.24
#Mann= 7 ,-1 , 0
  3689.9     .05       0  4257.7     .12       0  5001.5     .07       0
  5007.5     .12       0  5181.1     .05       0  5364.3     .16       0
    5394     .12       0
Bank Sta=4964.4,5044.5
XS Rating Curve= 0 ,0
Exp/Cntr=0.3,0.1

Type RM Length L Ch R = 1 ,52327   ,373,373,373
BEGIN DESCRIPTION:
BROWNS CREEK 84.0
END DESCRIPTION:
XS GIS Cut Line= 3
      3612218.58     10559153.03      3611130.05     10558403.04
      3610265.45     10558210.33
#Sta/Elev= 30
  3911.7  402.56  3971.2  400.15  4013.7  390.72  4064.4  384.22  4258.5  370.14
  4925.3  367.51  4969.2  368.91    4978  367.85  4984.1  365.47  4991.2  359.26
  5002.1  356.73  5004.8  356.23  5008.1  356.73  5027.7  359.72  5034.8  364.11
  5091.6  368.26  5254.5  370.25  5333.9  377.84  5582.4  407.22  5638.1  417.51
  5686.7  430.98  5695.1  430.14  5817.1  445.92  5822.2  444.61    5900  453.66
  5914.3  452.52  5951.2  455.39  5992.2  460.77  6077.6  483.45  6119.4  492.01
#Mann= 6 ,-1 , 0
  3911.7     .05       0  4925.3     .12       0  5002.1     .07       0
  5008.1     .12       0  5333.9     .16       0  6077.6      .1       0
Bank Sta=4969.2,5091.6
XS Rating Curve= 0 ,0
Exp/Cntr=0.3,0.1

Type RM Length L Ch R = 1 ,51954   ,370,370,370
BEGIN DESCRIPTION:
BROWNS CREEK 83.0
END DESCRIPTION:
XS GIS Cut Line= 4
      3612317.54     10559028.03      3611640.47     10558403.04
      3611395.67     10558048.87      3610395.68     10557637.41
#Sta/Elev= 30
  3967.9  399.11    4078  396.03  4226.6  376.84  4389.3  368.76  4868.6  366.21
  4914.1  367.35  4977.9  364.72  4985.8  359.81  4991.8  359.74  4997.6  353.98
  5000.4  353.48  5003.6  353.98  5014.4  358.21  5021.6  365.18  5078.4  367.43
  5108.1  364.12  5143.9  366.73  5185.8  364.16  5474.2  378.05  5715.7  390.18
  6029.7  414.38  6083.4  417.51  6090.2  419.72  6167.5  427.63  6172.9  426.17
  6213.1  432.63  6267.2  435.57  6288.8  440.49  6327.4  445.22  6401.2  450.09
#Mann= 6 ,-1 , 0
  3967.9     .05       0  4868.6     .12       0  4997.6     .07       0
  5003.6     .12       0  5474.2     .16       0  6029.7     .05       0
Bank Sta=4977.9,5021.6
XS Rating Curve= 0 ,0
Exp/Cntr=0.3,0.1

Type RM Length L Ch R = 1 ,51584   ,801,801,801
BEGIN DESCRIPTION:
BROWNS CREEK 82.0
END DESCRIPTION:
XS GIS Cut Line= 3
      3612299.64     10558560.22      3611899.61     10558160.19
      3611099.57     10557610.16
#Sta/Elev= 30
  4430.6  381.91  4480.3  380.88  4501.4  379.29  4515.5  376.02  4543.8  372.93
    4617  370.09  4699.3  366.69  4798.3  364.92    4980   365.8  4982.2   365.7
  4989.8  353.74  4992.5  353.24  4995.8  353.74  5018.7  357.91  5032.7   362.8
  5054.5  365.71  5111.3  366.48    5204  364.34  5263.3  365.14  5275.7  361.82
  5284.5  361.01  5299.4  361.73  5305.5  363.38  5320.4  364.71  5457.8  368.62
  5678.9  378.52  5845.8  389.95    5867  390.08  5873.1   391.5  5967.2  396.21
#Mann= 7 ,-1 , 0
  4430.6     .12       0  4480.3     .05       0    4617      .1       0
    4980     .12       0  4989.8     .07       0  4995.8     .12       0
  5457.8     .16       0
Bank Sta=4982.2,5054.5
XS Rating Curve= 0 ,0
Exp/Cntr=0.3,0.1

Type RM Length L Ch R = 1 ,50783   ,444,444,444
BEGIN DESCRIPTION:
BROWNS CREEK 81.0
END DESCRIPTION:
XS GIS Cut Line= 3
      3612572.05     10558331.17      3611999.13     10557680.13
      3610932.98     10557069.04
#Sta/Elev= 30
  4000.9  389.56  4092.3  385.79  4137.7  383.91  4226.6  371.92    4300  368.17
  4337.2   365.7    4535   361.6  4968.2  363.09  4971.3  362.92  4996.4  350.64
  4999.2  350.14  5002.4  350.64  5015.2  358.81  5028.9  360.74  5095.8  362.56
  5132.7  376.98  5144.5  378.76  5298.7  381.17  5402.2  381.97    5418  377.77
  5461.2  385.68  5687.1  396.16  5746.1  395.33  5761.9   389.7  5783.4  390.58
  5789.7  387.97  5848.2  396.84  5879.8  396.61    5923   402.5    6097  414.93
#Mann= 10 ,-1 , 0
  4000.9     .12       0  4092.3     .16       0  4226.6     .05       0
    4300     .16       0  4337.2     .05       0  4968.2     .16       0
  4996.4     .07       0  5002.4     .16       0  5144.5     .05       0
  5298.7     .16       0
Bank Sta=4971.3,5028.9
XS Rating Curve= 0 ,0
Exp/Cntr=0.3,0.1

Type RM Length L Ch R = 1 ,50339   ,649,649,649
BEGIN DESCRIPTION:
BROWNS CREEK 80.0
END DESCRIPTION:
XS GIS Cut Line= 4
      3613295.98     10558772.98      3612629.34      10557911.9
       3611997.4     10557314.67      3611039.02     10556870.21
#Sta/Elev= 30
  3331.8  418.43  3673.8  401.14  3742.8  394.52  3808.7   390.7  3837.7  382.53
  3897.9  385.62  4065.8  377.37  4121.9  366.61  4150.9  374.86  4314.8  384.09
  4372.4  382.05  4499.7  364.62    4613  359.17  4655.1  362.81  4676.5  357.76
  4812.8  362.17  4854.8  361.98    4944  362.03  4966.6  362.18  4973.4  361.93
  4987.6   351.2  4998.8  350.24  5001.5  349.74  5004.8  350.24  5030.1  360.75
  5206.5  366.33  5405.7  379.06  5622.9  383.85  6118.9  406.26  6346.7  416.07
#Mann= 10 ,-1 , 0
  3331.8     .16       0  3742.8     .12       0  3897.9     .16       0
  4812.8     .05       0  4854.8     .12       0    4944     .16       0
  4998.8     .07       0  5004.8     .16       0  5206.5     .05       0
  6118.9     .16       0
Bank Sta=4966.6,5030.1
XS Rating Curve= 0 ,0
Exp/Cntr=0.3,0.1