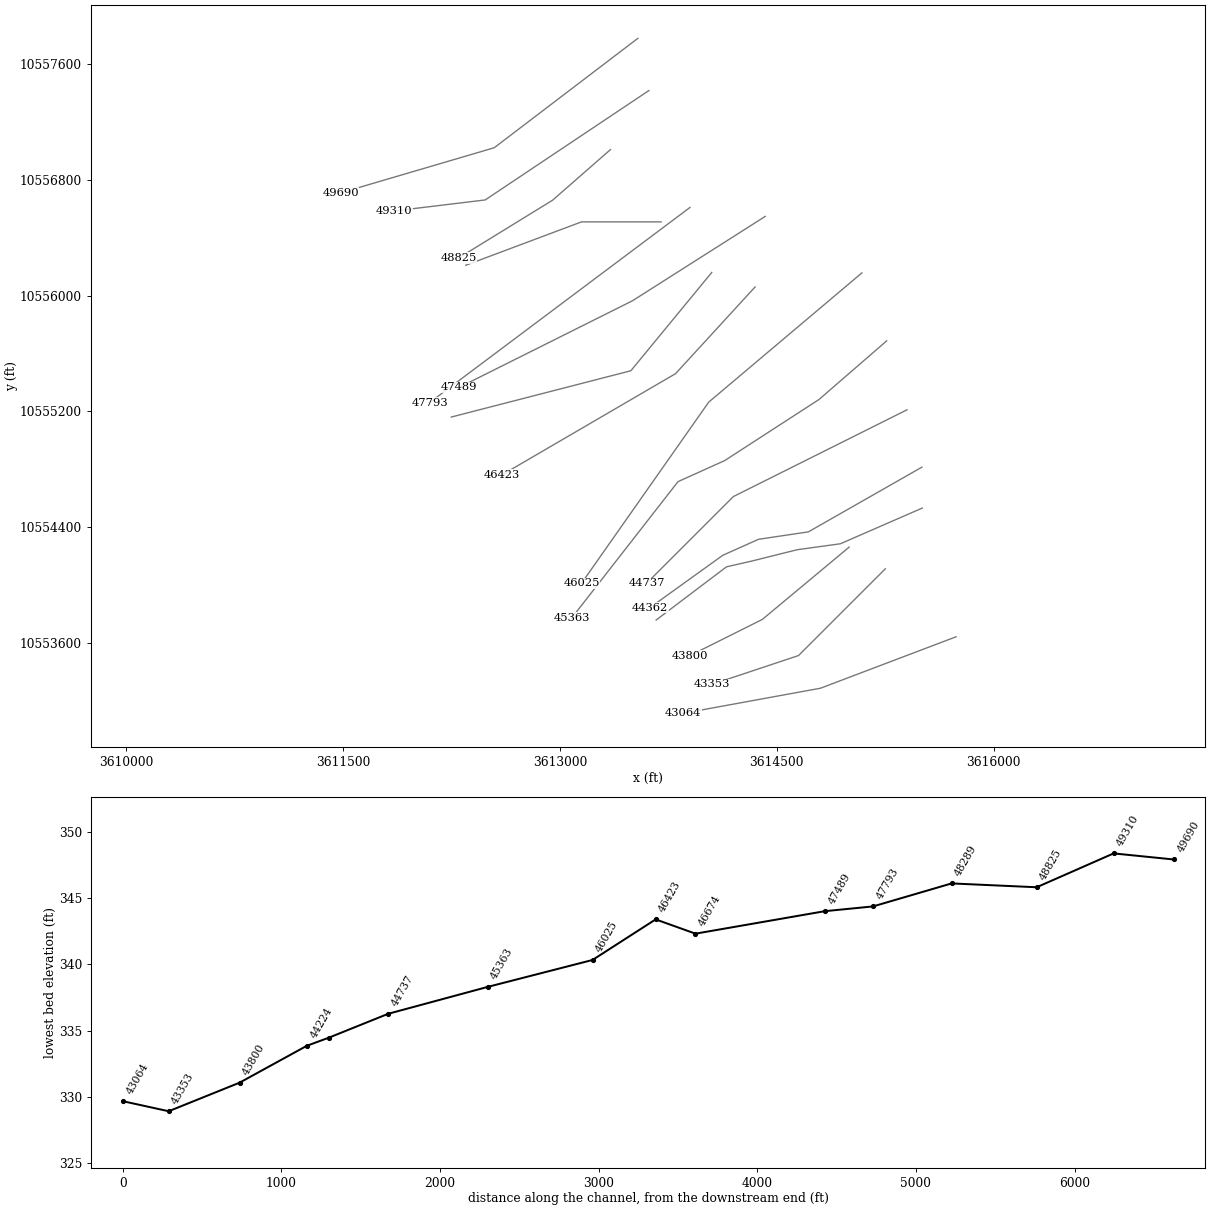
HEC-RAS study BROWNS CREEK.prj: BROWNS CREEK Base Level Engineering

--- BROWNS CREEK.g01 (geometry) --- (continued)

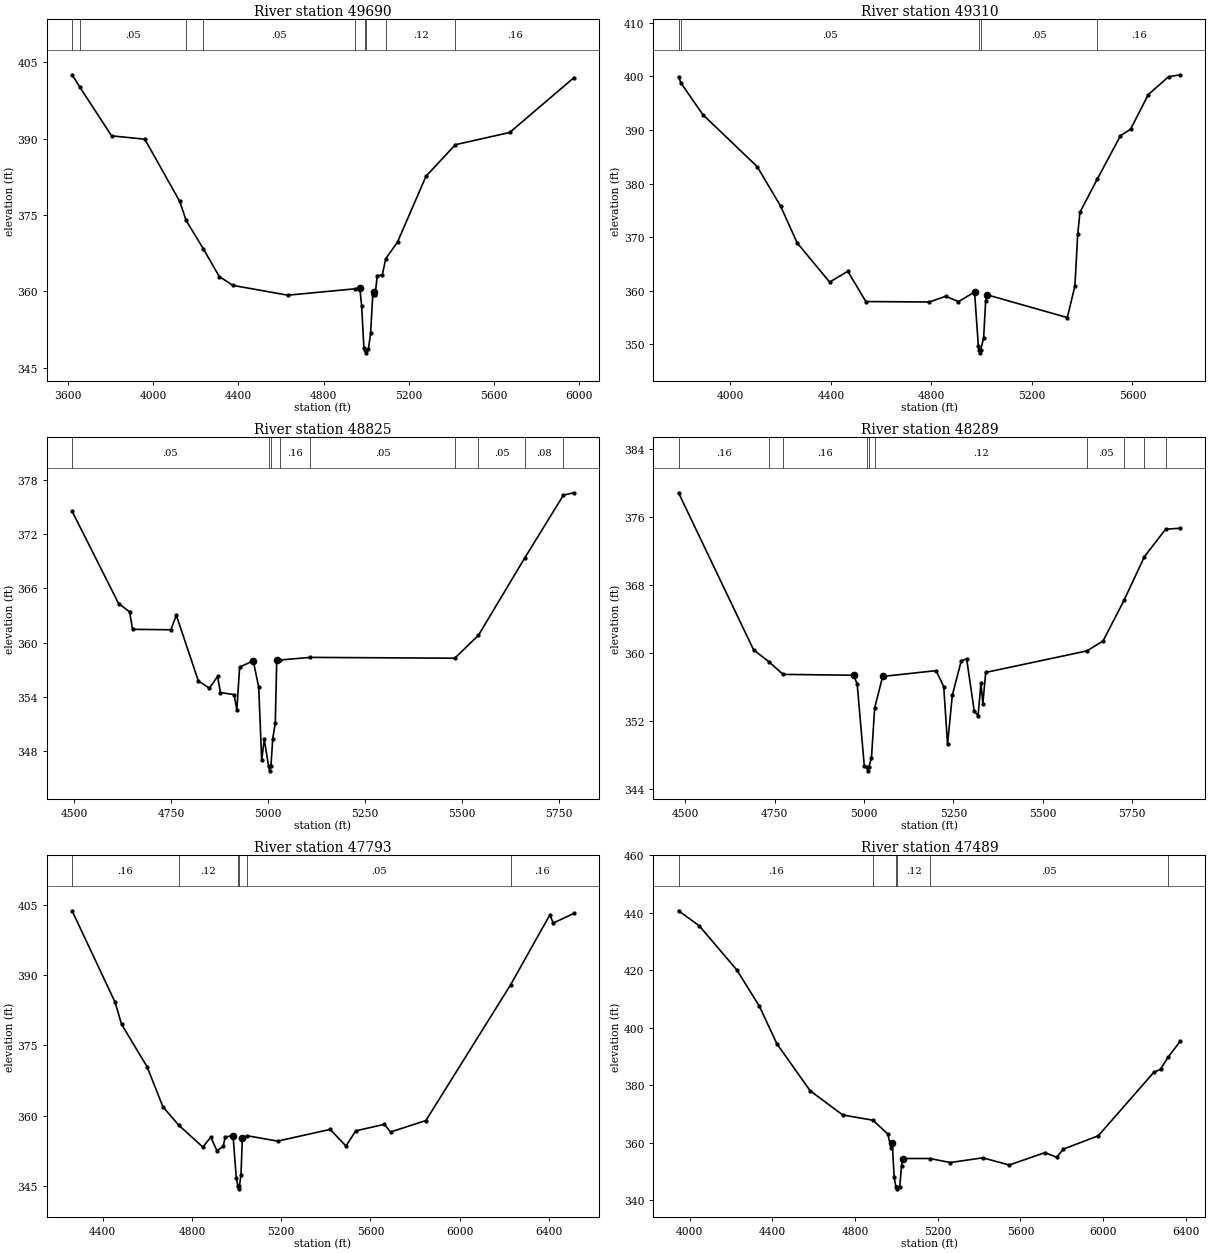
Type RM Length L Ch R = 1 ,49690   ,380,380,380
BEGIN DESCRIPTION:
BROWNS CREEK 79.0
END DESCRIPTION:
XS GIS Cut Line= 3
      3613539.04     10557779.93      3612546.01     10557023.01
       3611484.1     10556710.68
#Sta/Elev= 30
  3618.8  402.54  3653.7  400.22  3804.2  390.55  3960.2  389.89  4124.4  377.66
  4154.1  373.93  4235.1  368.36  4309.6  362.93  4373.9  361.18  4631.6  359.26
  4948.3  360.52  4969.6  360.66  4978.3  357.08  4988.7  348.87  4994.7  348.44
  4997.4  347.94  5000.7  348.44  5009.6  348.65    5020  351.74  5030.4  359.31
  5036.3  359.79  5041.5  359.38  5051.3  363.08  5074.8  363.21  5091.2  366.41
  5146.8  369.72  5280.2  382.61    5418  388.81  5673.1  391.21  5974.3  401.96
#Mann= 9 ,-1 , 0
  3618.8     .16       0  3653.7     .05       0  4154.1     .08       0
  4235.1     .05       0  4948.3     .16       0  4994.7     .07       0
  5000.7     .16       0  5091.2     .12       0    5418     .16       0
Bank Sta=4969.6,5036.3
XS Rating Curve= 0 ,0
Exp/Cntr=0.3,0.1

Type RM Length L Ch R = 1 ,49310   ,485,485,485
BEGIN DESCRIPTION:
BROWNS CREEK 78.0
END DESCRIPTION:
XS GIS Cut Line= 3
      3613615.47     10557418.85      3612483.51      10556661.9
      3611853.13      10556585.7
#Sta/Elev= 30
    3794  399.88  3804.1  398.72  3890.9  392.85  4107.1  383.15  4200.2  375.77
  4266.3   368.9  4395.4   361.6  4467.5  363.62  4539.5  357.97  4791.8  357.89
  4857.8  358.96  4907.8  357.95  4971.9  359.75  4986.9  349.74    4990   348.9
  4992.7   348.4    4996   348.9    5008  351.18  5016.1  358.11    5023  359.21
    5341  354.98  5371.2  360.87  5382.3  370.49  5391.3  374.63  5459.5  380.76
  5552.5  388.91  5592.8  390.14  5663.3   396.6  5743.9  399.93  5790.7  400.29
#Mann= 5 ,-1 , 0
    3794     .16       0  3804.1     .05       0    4990     .03       0
    4996     .05       0  5459.5     .16       0
Bank Sta=4971.9,5023
XS Rating Curve= 0 ,0
Exp/Cntr=0.3,0.1

Type RM Length L Ch R = 1 ,48825   ,536,536,536
BEGIN DESCRIPTION:
BROWNS CREEK 77.0
END DESCRIPTION:
XS GIS Cut Line= 3
      3613349.58     10557010.16      3612949.61     10556660.19
      3612299.59     10556260.18
#Sta/Elev= 30
  4494.1  374.52  4614.1  364.32  4642.6   363.4  4650.2  361.47  4748.9  361.42
  4763.1  363.02  4820.1  355.75  4848.6  354.97  4869.4  356.27    4877  354.49
  4912.1  354.26  4919.3  352.57  4926.4  357.29  4961.5     358  4975.7  355.08
  4983.3  347.02    4990  349.32  5001.2  346.34    5004  345.84  5007.2  346.34
  5011.8  349.38  5018.4   351.1  5022.2  358.09  5030.6  358.08  5108.4  358.37
  5481.5  358.28  5542.6  360.81  5662.6  369.39  5761.9  376.29  5788.8  376.55
#Mann= 9 ,-1 , 0
  4494.1     .05       0  5001.2     .03       0  5007.2     .05       0
  5030.6     .16       0  5108.4     .05       0  5481.5     .08       0
  5542.6     .05       0  5662.6     .08       0  5761.9     .05       0
Bank Sta=4961.5,5022.2
XS Rating Curve= 0 ,0
Exp/Cntr=0.3,0.1

Type RM Length L Ch R = 1 ,48289   ,496,496,496
BEGIN DESCRIPTION:
BROWNS CREEK 76.0
END DESCRIPTION:
XS GIS Cut Line= 3
      3613699.62     10556510.19      3613149.61     10556510.19
      3612349.62     10556210.19
#Sta/Elev= 30
  4480.6  378.85  4690.6  360.37  4733.4  358.97  4773.2  357.48  4970.6  357.38
  4980.6  356.34  5000.6  346.66  5007.6  346.63  5010.4  346.13  5013.6  346.63
  5020.6  347.67  5029.5  353.54    5052  357.24  5201.5  357.92  5222.8  356.03
  5233.5  349.26  5246.9  355.03  5271.8  359.06  5286.9  359.31  5308.3  353.14
    5319  352.63    5327  356.47  5332.3  354.03  5340.3  357.71  5623.3  360.24
  5668.7  361.41  5727.4  366.19  5784.3  371.32  5843.7  374.56    5885  374.68
#Mann= 10 ,-1 , 0
  4480.6     .16       0  4733.4     .12       0  4773.2     .16       0
  5007.6     .07       0  5013.6     .16       0  5029.5     .12       0
  5623.3     .05       0  5727.4     .08       0  5784.3     .12       0
  5843.7     .05       0
Bank Sta=4970.6,5052
XS Rating Curve= 0 ,0
Exp/Cntr=0.3,0.1

Type RM Length L Ch R = 1 ,47793   ,304,304,304
BEGIN DESCRIPTION:
BROWNS CREEK 75.0
END DESCRIPTION:
XS GIS Cut Line= 3
      3613899.58     10556610.17      3613299.61     10556160.19
      3612099.58     10555260.17
#Sta/Elev= 30
  4262.2  403.76  4454.9  384.25    4484  379.54  4598.6  370.44  4669.5  361.92
  4740.7  357.98  4848.6   353.3    4884  355.43  4912.2  352.49  4940.3  353.52
  4948.6  355.46    4984  355.74  4998.6  346.68    5006  344.89  5008.8  344.39
    5012  344.89  5019.5  347.25  5025.7  355.25  5046.7  355.73    5184  354.58
  5419.5  357.08  5490.3  353.53    5534  356.77  5662.2  358.16  5690.3  356.53
  5848.6  358.97  6228.6  387.96  6404.9  402.92  6419.5  401.13  6512.2   403.2
#Mann= 6 ,-1 , 0
  4262.2     .16       0  4740.7     .12       0    5006     .07       0
    5012     .12       0  5046.7     .05       0  6228.6     .16       0
Bank Sta=4984,5025.7
XS Rating Curve= 0 ,0
Exp/Cntr=0.3,0.1

Type RM Length L Ch R = 1 ,47489   ,815,815,815
BEGIN DESCRIPTION:
BROWNS CREEK 74.0
END DESCRIPTION:
XS GIS Cut Line= 3
      3614419.58     10556548.13      3613501.69     10555964.36
      3612303.97     10555365.49
#Sta/Elev= 30
  3946.3  440.74    4046  435.55    4228  420.17  4337.3  407.55  4421.9  394.49
  4582.8  378.15  4740.3  369.72  4886.5   367.9  4958.8  363.06    4974  358.17
  4979.9  360.12  4989.2  348.08  4998.1  344.53  5000.9  344.03  5004.1  344.53
  5016.4  344.79  5024.7  352.08  5031.6  354.58  5161.1  354.58  5260.7  353.18
  5417.3  354.82  5545.8  352.32  5718.4  356.62    5775  355.03  5807.9  357.86
  5976.3  362.48  6244.6  384.53  6277.4   385.6  6313.3  389.76  6373.2   395.4
#Mann= 6 ,-1 , 0
  3946.3     .16       0  4886.5     .12       0  4998.1     .07       0
  5004.1     .12       0  5161.1     .05       0  6313.3     .16       0
Bank Sta=4979.9,5031.6
XS Rating Curve= 0 ,0
Exp/Cntr=0.3,0.1

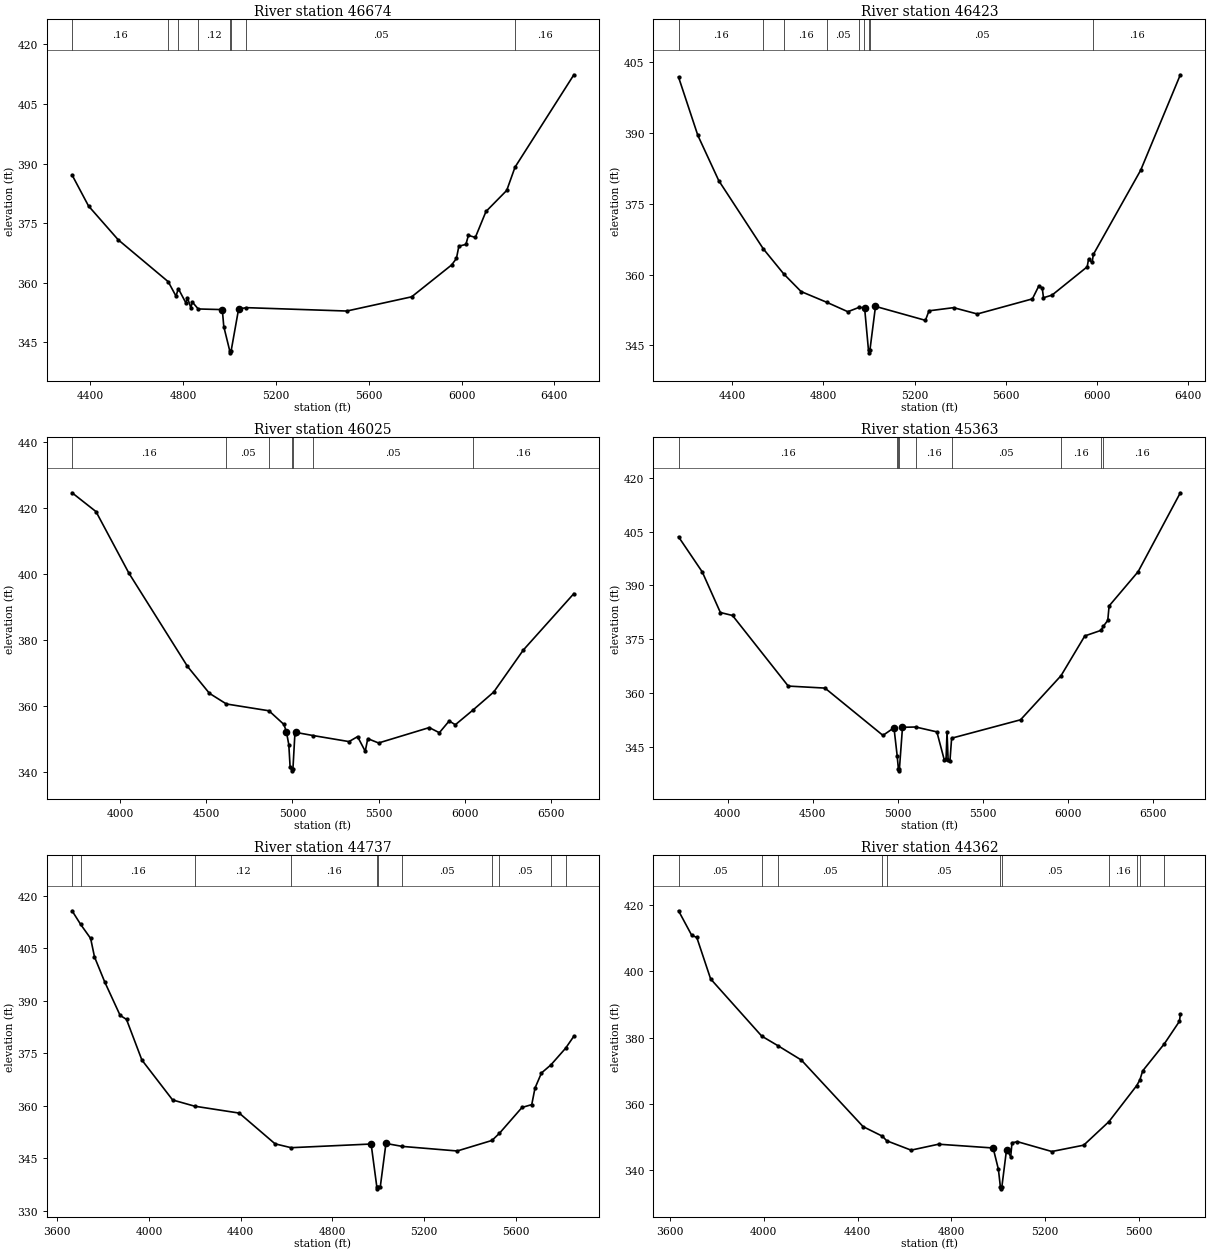
Type RM Length L Ch R = 1 ,46674   ,251,251,251
BEGIN DESCRIPTION:
BROWNS CREEK 73.0
END DESCRIPTION:
XS GIS Cut Line= 3
      3614049.62      10556160.2      3613490.73      10555480.4
      3612249.62     10555160.19
#Sta/Elev= 30
    4322  387.12    4393  379.31  4520.8   370.8  4736.2  360.25  4769.7  356.62
  4779.8  358.49  4812.8  354.86  4819.2  356.22  4833.6  353.66    4840  355.13
  4865.5  353.38  4969.2  353.22  4975.6  348.95  5001.3  342.83  5004.1  342.33
  5007.3  342.83  5039.5  353.38  5072.7  353.71  5505.5  352.86    5785  356.44
  5957.1  364.46  5977.8  366.09  5988.4  369.19  6018.7  369.64  6029.4  371.91
  6059.4   371.4  6105.2  377.93  6194.6  383.24  6230.3  389.09  6483.8  412.36
#Mann= 8 ,-1 , 0
    4322     .16       0  4736.2     .12       0  4779.8     .16       0
  4865.5     .12       0  5001.3     .07       0  5007.3     .12       0
  5072.7     .05       0  6230.3     .16       0
Bank Sta=4969.2,5039.5
XS Rating Curve= 0 ,0
Exp/Cntr=0.3,0.1

Type RM Length L Ch R = 1 ,46423   ,398,398,398
BEGIN DESCRIPTION:
BROWNS CREEK 72.0
END DESCRIPTION:
XS GIS Cut Line= 3
      3614349.62      10556060.2      3613799.61     10555460.19
      3612599.61     10554760.19
#Sta/Elev= 30
  4163.6  401.88  4248.4  389.51  4340.3  379.92  4535.6  365.47    4626  360.12
  4701.6  356.41  4816.3  354.09    4907  352.13  4955.5  353.04  4978.1  352.97
  4980.5  352.97  4997.7  343.91  5000.5  343.41  5003.7  343.91  5028.4  353.26
  5247.6   350.3  5263.3  352.32  5371.2  352.99  5475.4  351.65  5717.3  354.85
  5744.5   357.5  5760.3  357.21    5766   355.1  5803.3  355.64  5957.9  361.65
  5963.7  363.25  5979.4  362.57  5984.9  364.27  6192.7  382.13  6366.8  402.37
#Mann= 9 ,-1 , 0
  4163.6     .16       0  4535.6     .05       0    4626     .16       0
  4816.3     .05       0  4955.5     .16       0  4978.1     .05       0
  4997.7     .03       0  5003.7     .05       0  5984.9     .16       0
Bank Sta=4980.5,5028.4
XS Rating Curve= 0 ,0
Exp/Cntr=0.3,0.1

Type RM Length L Ch R = 1 ,46025   ,662,662,662
BEGIN DESCRIPTION:
BROWNS CREEK 71.0
END DESCRIPTION:
XS GIS Cut Line= 3
      3615087.92     10556157.46      3614028.92     10555263.39
      3613149.59     10554010.16
#Sta/Elev= 30
  3718.7  424.56  3857.8  418.86    4049  400.22  4389.6  371.97  4517.1  363.82
  4615.8  360.59  4863.2  358.53    4950   354.4  4964.3  352.24  4978.6  348.27
    4986  341.63  4996.5  340.84  4999.2  340.34  5002.5  340.84  5013.8  351.37
  5021.5  351.96  5119.7  351.03  5328.4   349.2  5378.4   350.7  5422.8  346.27
  5437.6  350.09  5500.4  348.78    5795  353.44  5853.7  351.89  5910.9  355.45
  5946.6   354.3  6048.9  358.74  6169.7   364.2  6342.3  376.96  6635.6  394.02
#Mann= 7 ,-1 , 0
  3718.7     .16       0  4615.8     .05       0  4863.2     .16       0
  4996.5     .07       0  5002.5     .16       0  5119.7     .05       0
  6048.9     .16       0
Bank Sta=4964.3,5021.5
XS Rating Curve= 0 ,0
Exp/Cntr=0.3,0.1

Type RM Length L Ch R = 1 ,45363   ,626,626,626
BEGIN DESCRIPTION:
BROWNS CREEK 70.0
END DESCRIPTION:
XS GIS Cut Line= 5
      3615259.09     10555687.05      3614790.37     10555280.82
      3614139.32     10554858.94      3613816.41     10554713.11
      3613082.01     10553770.37
#Sta/Elev= 30
  3712.4  403.54  3851.7  393.75    3958  382.44  4029.3  381.61  4356.4  361.93
  4571.9  361.37  4912.3  348.18    4977  350.31  4995.9  342.44  5002.9   338.8
  5005.7   338.3  5008.9   338.8    5027  350.44  5104.5  350.52  5228.8  349.16
  5272.7  341.26  5282.9  341.71  5288.4  349.15  5294.7  341.44  5305.6  341.13
  5315.4   347.4  5719.9  352.53  5957.6  364.83  6097.1  375.91  6192.7  377.47
    6206  378.61  6231.9  380.24  6239.7  384.27  6410.2  393.83  6657.8  415.82
#Mann= 9 ,-1 , 0
  3712.4     .16       0  4995.9     .12       0  5002.9     .07       0
  5008.9     .12       0  5104.5     .16       0  5315.4     .05       0
  5957.6     .16       0  6192.7     .05       0    6206     .16       0
Bank Sta=4977,5027
XS Rating Curve= 0 ,0
Exp/Cntr=0.3,0.1

Type RM Length L Ch R = 1 ,44737   ,375,375,375
BEGIN DESCRIPTION:
BROWNS CREEK 69.0
END DESCRIPTION:
XS GIS Cut Line= 3
      3615399.64      10555210.2      3614199.61     10554610.19
      3613599.61     10554010.19
#Sta/Elev= 30
  3664.3  415.74  3701.3  411.89  3745.4  407.83  3762.2  402.55  3806.9  395.39
    3874  385.85  3901.9  384.69    3969  373.09  4103.2  361.67  4199.4  359.89
  4393.9  357.92  4550.4  349.13  4620.3  348.03  4969.6  349.08  4994.6  336.77
  4997.3  336.27  5000.6  336.77  5009.5   336.8  5034.3  349.24  5105.5   348.4
  5345.4  347.09    5497   350.1  5529.9  352.16  5628.2  359.53  5670.7  360.34
  5684.8  365.05  5713.1  369.38  5754.2  371.69  5818.6  376.47  5854.5  379.89
#Mann= 11 ,-1 , 0
  3664.3     .05       0  3701.3     .16       0  4199.4     .12       0
  4620.3     .16       0  4994.6     .07       0  5000.6     .16       0
  5105.5     .05       0    5497     .08       0  5529.9     .05       0
  5754.2     .16       0  5818.6     .05       0
Bank Sta=4969.6,5034.3
XS Rating Curve= 0 ,0
Exp/Cntr=0.3,0.1

Type RM Length L Ch R = 1 ,44362   ,138,138,138
BEGIN DESCRIPTION:
BROWNS CREEK 68.0
END DESCRIPTION:
XS GIS Cut Line= 5
      3615502.73     10554813.56      3614717.97     10554365.86
      3614373.18      10554314.4      3614126.16     10554203.76
      3613623.23     10553841.96
#Sta/Elev= 30
  3635.8  418.19  3692.1   410.8  3713.7  410.17  3772.8  397.67    3991  380.45
  4060.9  377.53  4160.2  373.24  4423.8  353.19  4506.4   350.3  4524.6  348.93
  4628.6  346.11    4746   347.9  4978.9  346.76  5001.4  340.35    5010  334.96
  5012.8  334.46    5016  334.96  5036.2   346.3  5053.9  344.16  5059.4  348.32
  5082.6  348.66  5229.5   345.7  5365.7  347.61  5473.2  354.69  5591.7  365.53
  5605.3  367.24  5617.4  369.98  5710.2  378.17  5774.5  384.93  5778.1  386.97
#Mann= 11 ,-1 , 0
  3635.8     .05       0    3991     .16       0  4060.9     .05       0
  4506.4     .12       0  4524.6     .05       0    5010     .03       0
    5016     .05       0  5473.2     .16       0  5591.7     .08       0
  5605.3     .12       0  5710.2     .05       0
Bank Sta=4978.9,5036.2
XS Rating Curve= 0 ,0
Exp/Cntr=0.3,0.1

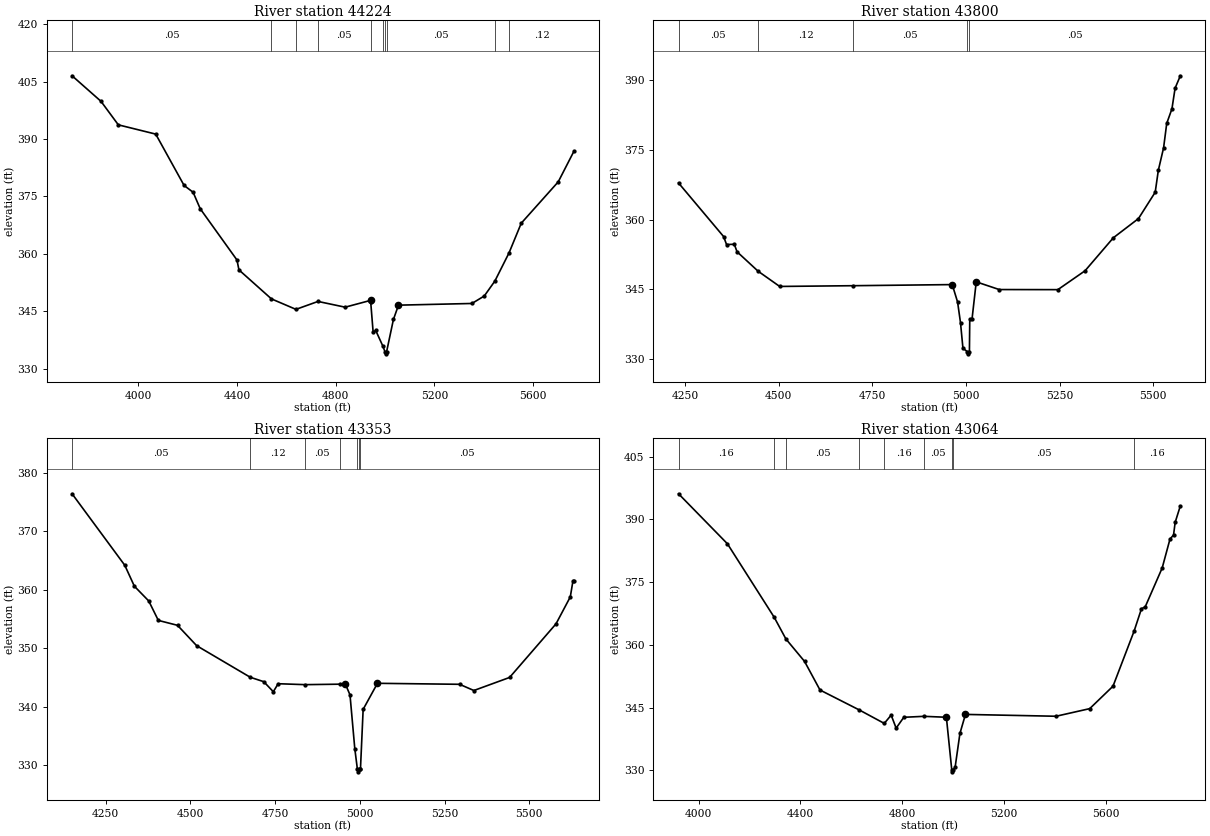
Type RM Length L Ch R = 1 ,44224   ,424,424,424
BEGIN DESCRIPTION:
Mapping XS e890ab5a
END DESCRIPTION:
XS GIS Cut Line= 6
      3615505.33     10554530.53      3614939.26     10554283.52
      3614640.78     10554242.35      3614332.01     10554165.16
      3614151.89     10554123.99      3613665.57     10553756.03
#Sta/Elev= 30
  3732.7  406.56  3849.8  399.88    3920  393.73  4071.4  391.31  4186.3  377.88
  4222.8   376.1  4251.7  371.78  4400.4  358.39  4408.4   355.8  4539.9  348.22
  4639.2  345.48  4728.6  347.55  4838.4  346.05  4941.4  347.83  4941.8  347.51
  4951.8  339.47  4962.1  339.98  4990.6  335.95  5000.1  334.35  5002.9  333.85
  5006.1  334.35  5033.9  342.84  5054.4  346.58  5351.7  347.02  5401.7  348.97
  5444.6  352.87  5502.1  360.26  5551.5  368.01  5701.3  378.83  5764.5  386.79
#Mann= 10 ,-1 , 0
  3732.7     .05       0  4539.9     .16       0  4639.2     .12       0
  4728.6     .05       0  4941.8     .08       0  4990.6     .05       0
  5000.1     .03       0  5006.1     .05       0  5444.6     .16       0
  5502.1     .12       0
Bank Sta=4941.4,5054.4
XS Rating Curve= 0 ,0
Exp/Cntr=0.3,0.1

Type RM Length L Ch R = 1 ,43800   ,447,447,447
BEGIN DESCRIPTION:
BROWNS CREEK 67.0
END DESCRIPTION:
XS GIS Cut Line= 3
      3614999.57     10554260.16      3614399.61     10553760.19
       3613899.6     10553510.19
#Sta/Elev= 30
  4232.5   367.9  4352.9  356.34  4360.7  354.63  4381.5  354.68  4388.7  353.07
  4444.9  348.88  4502.6  345.59  4698.1  345.75  4963.4  345.99  4977.7  342.23
  4985.5  337.75    4992  332.26  5003.3  331.56  5006.1  331.06  5009.3  331.56
  5010.2  338.58  5016.3  338.58  5027.5  346.58  5088.9  344.92  5245.5   344.9
  5318.1  348.97  5393.6  356.08  5460.7  360.22  5505.4   365.9  5513.8  370.64
  5527.8  375.48  5536.2  380.75  5550.1  383.88  5558.5  388.33  5572.5  391.01
#Mann= 5 ,-1 , 0
  4232.5     .05       0  4444.9     .12       0  4698.1     .05       0
  5003.3     .03       0  5009.3     .05       0
Bank Sta=4963.4,5027.5
XS Rating Curve= 0 ,0
Exp/Cntr=0.3,0.1

Type RM Length L Ch R = 1 ,43353   ,289,289,289
BEGIN DESCRIPTION:
BROWNS CREEK 66.0
END DESCRIPTION:
XS GIS Cut Line= 3
      3615249.64     10554110.22      3614649.61     10553510.19
      3614049.64      10553310.2
#Sta/Elev= 30
  4150.7  376.42  4306.3   364.2  4334.6  360.62    4377   358.1  4405.3  354.78
  4461.9  353.94  4518.4  350.46  4676.7  345.06  4716.4  344.31  4744.7  342.59
  4758.9  343.96  4838.1   343.8  4940.2  343.88  4956.8  343.97    4971  342.05
  4985.1  332.88  4992.7   329.4  4995.5   328.9  4998.7   329.4  5000.4   329.4
  5001.9   329.4  5009.8  339.58    5052  344.03  5294.4  343.86  5336.6   342.8
    5442  345.03    5579  354.19  5621.2   358.8  5629.1  361.55  5631.7  361.55
#Mann= 7 ,-1 , 0
  4150.7     .05       0  4676.7     .12       0  4838.1     .05       0
  4940.2     .12       0  4992.7     .07       0  4998.7     .12       0
  5000.4     .05       0
Bank Sta=4956.8,5052
XS Rating Curve= 0 ,0
Exp/Cntr=0.3,0.1

Type RM Length L Ch R = 1 ,43064   ,654,654,654
BEGIN DESCRIPTION:
BROWNS CREEK 65.0
END DESCRIPTION:
XS GIS Cut Line= 3
      3615739.03     10553640.14      3614801.49     10553284.22
      3613849.59     10553110.19
#Sta/Elev= 30
  3921.1  396.14    4113  384.19    4297  366.59  4342.7  361.43  4415.9  356.07
  4476.7  349.22  4631.7  344.43    4729  341.24  4756.1  343.22  4775.6  340.11
  4805.7   342.7  4884.4  342.93  4972.9  342.71    4994  330.16  4996.7  329.66
    5000  330.16  5007.2  330.74  5026.1  338.84  5047.8  343.39  5403.6  342.95
  5535.8  344.77  5627.3  350.14  5710.1  363.31  5739.1  368.67  5753.5  369.08
  5820.4  378.41  5850.9  385.29    5865   386.3  5871.3   389.3  5891.6  393.24
#Mann= 9 ,-1 , 0
  3921.1     .16       0    4297     .12       0  4342.7     .05       0
  4631.7     .12       0    4729     .16       0  4884.4     .05       0
    4994     .03       0    5000     .05       0  5710.1     .16       0
Bank Sta=4972.9,5047.8
XS Rating Curve= 0 ,0
Exp/Cntr=0.3,0.1