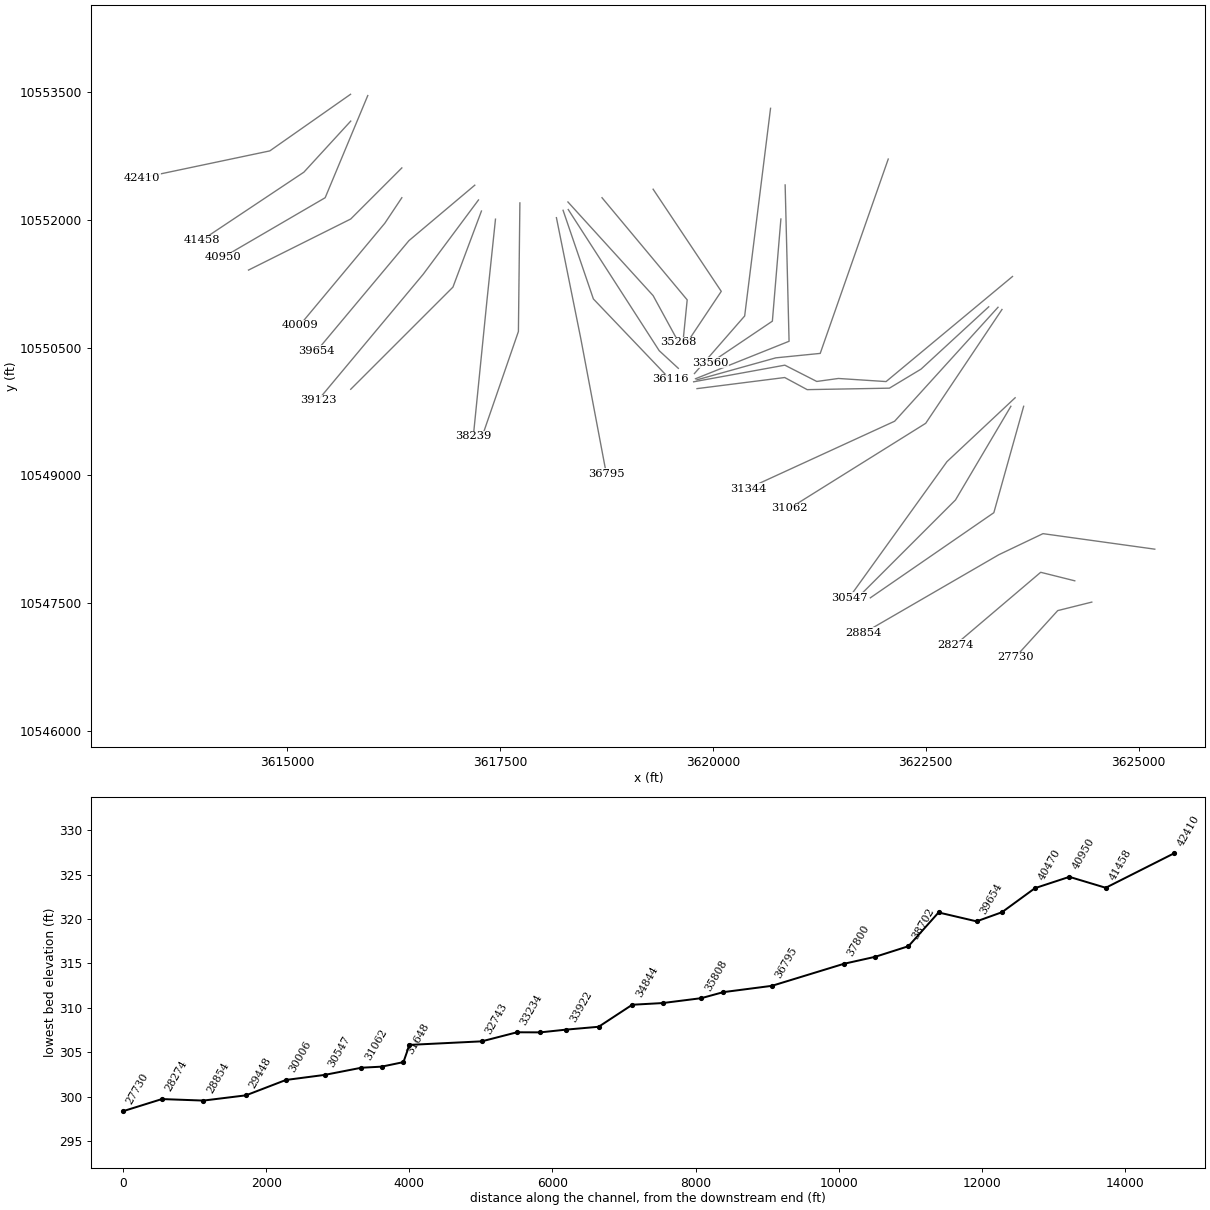
HEC-RAS study BROWNS CREEK.prj: BROWNS CREEK Base Level Engineering

--- BROWNS CREEK.g01 (geometry) --- (continued)

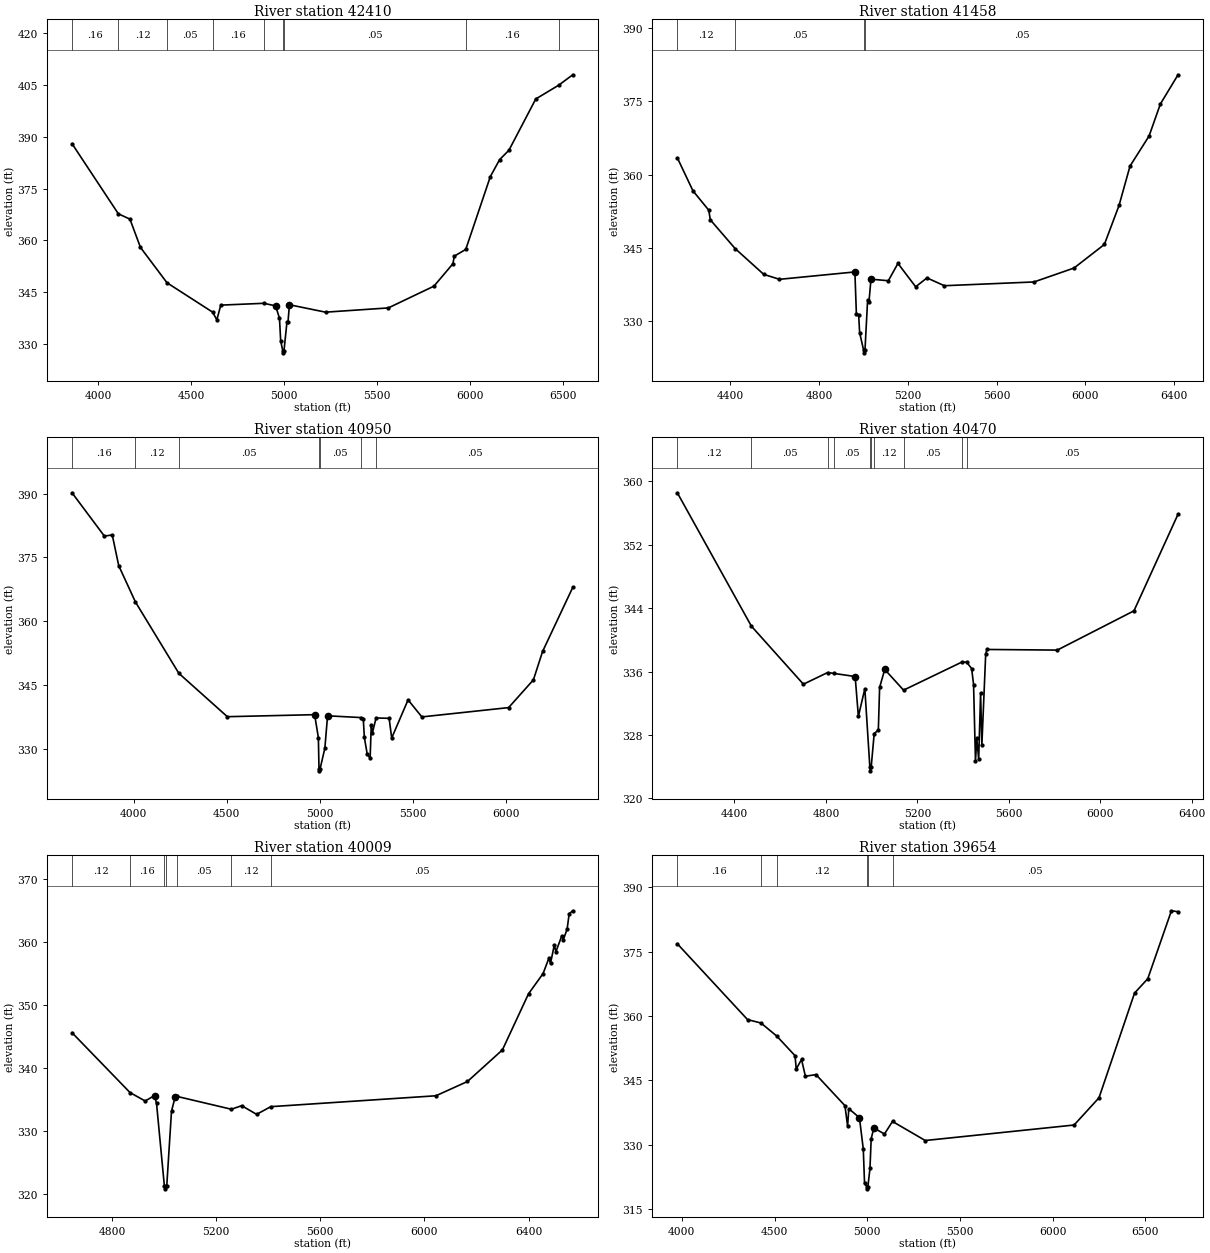
Type RM Length L Ch R = 1 ,42410   ,952,952,952
BEGIN DESCRIPTION:
BROWNS CREEK 64.0
END DESCRIPTION:
XS GIS Cut Line= 3
      3615747.63     10553475.17      3614799.61     10552810.19
       3613299.8      10552494.3
#Sta/Elev= 30
  3860.7  388.02  4109.7  367.69  4171.9  366.15  4228.6  357.94  4371.1   347.7
  4615.8   339.2  4639.1  336.96    4660  341.22  4891.1  341.75  4954.6  341.01
  4975.5  337.42    4982  330.84  4993.5  327.89  4996.2  327.39  4999.5  327.89
  5015.6  336.26  5021.2  336.26  5028.9  341.33  5223.1  339.18  5560.3  340.41
  5805.6  346.72  5907.8  353.24  5914.6  355.41  5976.4  357.36  6108.7   378.5
  6158.5   383.4  6208.4  386.11  6352.7  400.98  6475.8  404.97  6551.4  407.99
#Mann= 9 ,-1 , 0
  3860.7     .16       0  4109.7     .12       0  4371.1     .05       0
  4615.8     .16       0  4891.1     .12       0  4993.5     .03       0
  4999.5     .05       0  5976.4     .16       0  6475.8     .05       0
Bank Sta=4954.6,5028.9
XS Rating Curve= 0 ,0
Exp/Cntr=0.3,0.1

Type RM Length L Ch R = 1 ,41458   ,508,508,508
BEGIN DESCRIPTION:
BROWNS CREEK 63.0
END DESCRIPTION:
XS GIS Cut Line= 3
      3615749.63     10553160.21      3615199.61     10552560.19
       3613999.6     10551760.18
#Sta/Elev= 30
  4161.1  363.42  4231.7  356.65  4302.6  352.71    4310  350.72  4421.6  344.85
  4550.5  339.57  4621.4  338.56  4961.2  340.07    4968  331.39  4978.1  331.35
  4982.6  327.66  5000.6  324.02  5003.4  323.52  5006.6  324.02  5018.6  334.39
  5024.6  333.94  5033.7  338.59  5111.8  338.27  5155.3  341.81    5235  337.03
    5286  338.85  5364.2  337.25  5768.3  338.02  5948.6  340.87  6085.3  345.69
  6151.4  353.67    6201  361.74  6286.6  367.86  6337.7  374.43  6417.3   380.4
#Mann= 4 ,-1 , 0
  4161.1     .12       0  4421.6     .05       0  5000.6     .03       0
  5006.6     .05       0
Bank Sta=4961.2,5033.7
XS Rating Curve= 0 ,0
Exp/Cntr=0.3,0.1

Type RM Length L Ch R = 1 ,40950   ,480,480,480
BEGIN DESCRIPTION:
BROWNS CREEK 62.0
END DESCRIPTION:
XS GIS Cut Line= 3
      3615949.61     10553460.18      3615449.61     10552260.19
      3614249.64     10551560.21
#Sta/Elev= 30
  3669.8  390.18  3843.7  379.98  3885.9  380.27  3920.6  373.03  4010.3  364.49
  4243.5   347.7    4504  337.49  4972.7  337.97  4992.9  332.56  4996.2  325.25
  4998.9  324.75  5002.2  325.25  5027.7  330.08  5042.2   337.7  5219.8  337.29
    5234  337.06  5239.8  332.62  5255.5   328.6  5270.8  327.76    5277  335.54
  5282.8  333.66  5302.8  337.19  5372.9  337.11  5386.6  332.47  5474.6  341.45
  5548.6  337.44  6014.6  339.63  6147.8  346.17    6197  352.84    6359  367.91
#Mann= 7 ,-1 , 0
  3669.8     .16       0  4010.3     .12       0  4243.5     .05       0
  4996.2     .03       0  5002.2     .05       0  5219.8     .16       0
  5302.8     .05       0
Bank Sta=4972.7,5042.2
XS Rating Curve= 0 ,0
Exp/Cntr=0.3,0.1

Type RM Length L Ch R = 1 ,40470   ,461,461,461
BEGIN DESCRIPTION:
BROWNS CREEK 61.0
END DESCRIPTION:
XS GIS Cut Line= 3
      3616349.58     10552610.16      3615749.61     10552010.19
      3614549.64      10551410.2
#Sta/Elev= 30
  4150.2  358.53  4474.1  341.72  4701.7   334.4  4807.6  335.87    4835  335.76
    4928  335.37  4942.1  330.35  4970.4  333.83  4992.2  323.98  4994.9  323.48
  4998.2  323.98  5011.3  328.18  5029.4  328.62    5035     334  5057.4  336.26
  5139.8  333.65  5393.3  337.17  5415.1   337.2  5437.5  336.37  5445.9  334.36
  5454.3  324.68  5459.9  327.56  5468.3  324.94  5476.7  333.26  5482.2  326.73
    5499  338.22  5504.6  338.78  5812.1   338.7  6147.5  343.65  6340.3  355.83
#Mann= 10 ,-1 , 0
  4150.2     .12       0  4474.1     .05       0  4807.6     .16       0
    4835     .05       0  4992.2     .03       0  4998.2     .05       0
  5011.3     .12       0  5139.8     .05       0  5393.3     .16       0
  5415.1     .05       0
Bank Sta=4928,5057.4
XS Rating Curve= 0 ,0
Exp/Cntr=0.3,0.1

Type RM Length L Ch R = 1 ,40009   ,355,355,355
BEGIN DESCRIPTION:
BROWNS CREEK 60.0
END DESCRIPTION:
XS GIS Cut Line= 3
       3616349.6     10552260.17      3616149.61     10551960.19
       3615149.6     10550760.18
#Sta/Elev= 30
  4646.9  345.57  4869.6  336.06  4927.8  334.72  4963.9  335.59  4971.4  334.34
  5001.4  321.27  5004.2  320.77  5007.4  321.27  5010.7  321.27  5028.9  333.11
  5043.2   335.4  5048.9  335.46  5258.9  333.41  5298.4  333.98  5355.6   332.6
  5410.1  333.82  6044.2  335.55  6165.3  337.82  6299.4  342.83  6399.6  351.74
  6455.6  354.96  6477.7  357.38  6484.2   356.6  6498.5  359.45    6505  358.45
  6527.2  360.92  6533.7  360.36    6548  362.04  6555.8  364.47  6569.5  364.93
#Mann= 7 ,-1 , 0
  4646.9     .12       0  4869.6     .16       0  5001.4     .07       0
  5007.4     .16       0  5048.9     .05       0  5258.9     .12       0
  5410.1     .05       0
Bank Sta=4963.9,5043.2
XS Rating Curve= 0 ,0
Exp/Cntr=0.3,0.1

Type RM Length L Ch R = 1 ,39654   ,531,531,531
BEGIN DESCRIPTION:
BROWNS CREEK 59.0
END DESCRIPTION:
XS GIS Cut Line= 3
      3617205.97     10552407.46      3616433.44     10551756.44
      3615349.62     10550460.21
#Sta/Elev= 30
  3975.8  376.84  4354.3  359.18  4426.7  358.38  4511.9  355.34  4610.4  350.77
    4617  347.66  4645.6  349.89  4666.4  345.97  4723.6  346.36  4879.6  339.12
  4893.9  334.35  4900.5  338.42  4957.7  336.32  4978.5  329.02  4985.3  321.02
  4997.3  320.24    5000  319.74  5003.3  320.24  5014.6   324.5  5021.1  331.42
  5035.4  333.92  5092.7  332.52  5136.1  335.44  5312.6     331  6115.2  334.61
  6249.5  340.96  6441.1  365.35  6512.4   368.7  6639.9  384.53  6675.7  384.31
#Mann= 6 ,-1 , 0
  3975.8     .16       0  4426.7     .05       0  4511.9     .12       0
  4997.3     .07       0  5003.3     .12       0  5136.1     .05       0
Bank Sta=4957.7,5035.4
XS Rating Curve= 0 ,0
Exp/Cntr=0.3,0.1

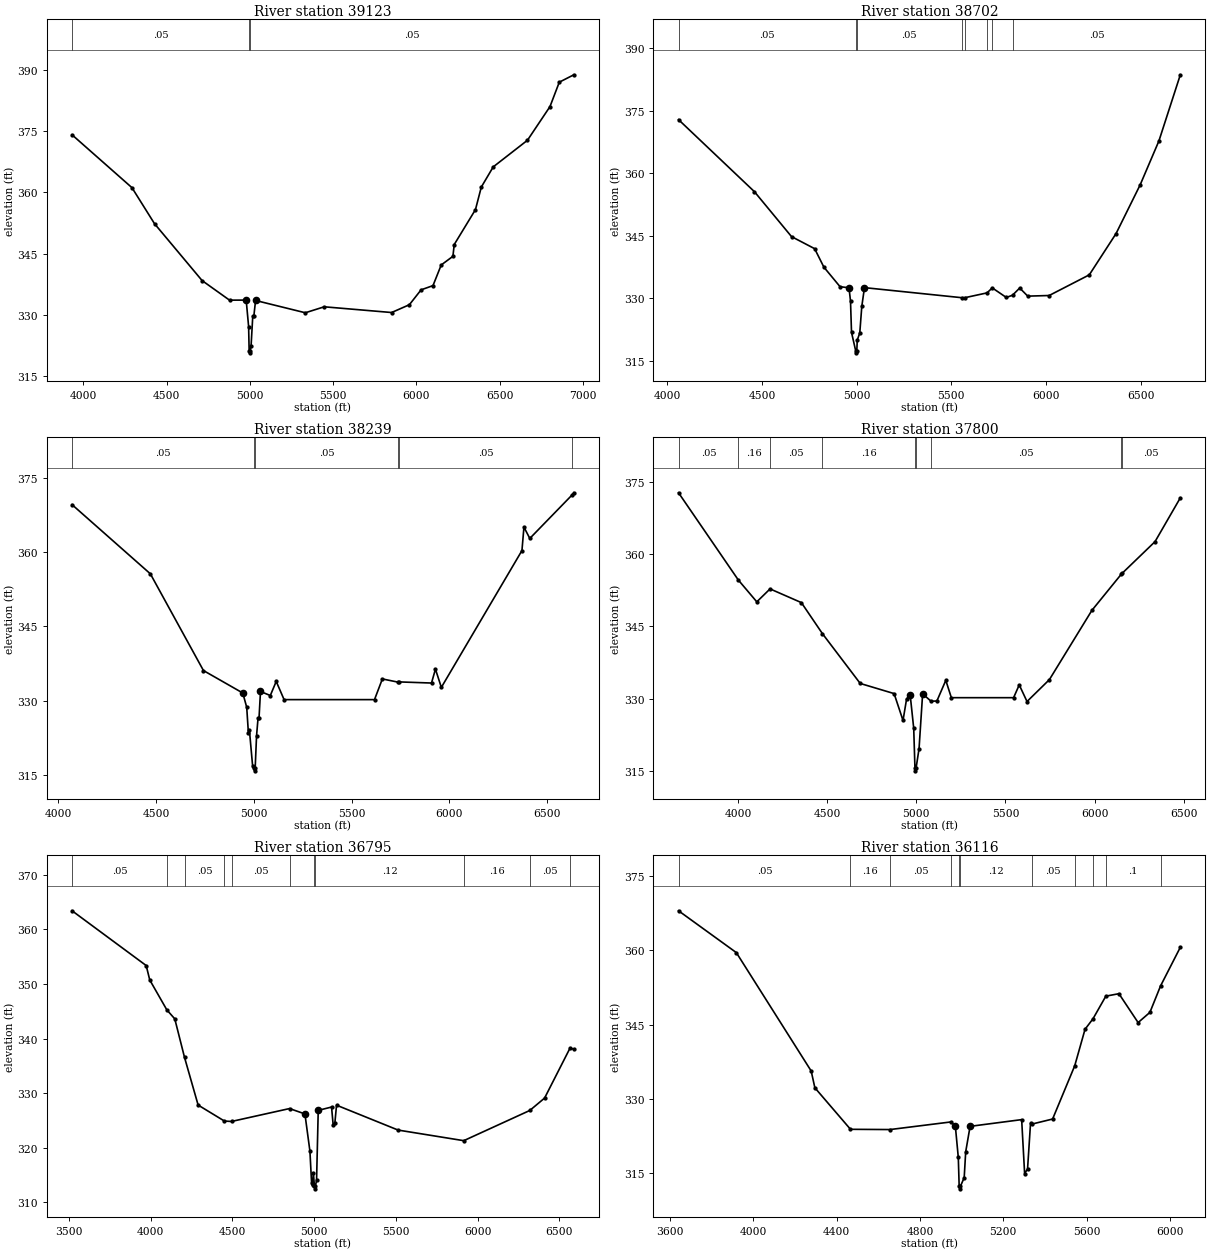
Type RM Length L Ch R = 1 ,39123   ,421,421,421
BEGIN DESCRIPTION:
BROWNS CREEK 58.0
END DESCRIPTION:
XS GIS Cut Line= 3
      3617249.41     10552233.88      3616599.61     10551360.19
       3615365.7     10549881.41
#Sta/Elev= 30
  3931.8  374.11  4291.7  361.17  4427.2  352.35    4713  338.43  4877.8  333.64
  4977.9  333.65  4992.5  327.18  4995.7  321.24  4998.5  320.74  5001.7  321.24
  5007.1  322.31  5017.5  329.74  5023.9  329.74  5034.3  333.56  5333.2  330.55
  5446.9  332.01  5851.7  330.61  5958.4  332.52  6028.7  336.16  6100.3   337.2
  6149.7  342.25    6220  344.37  6227.8  347.25  6355.4   355.8  6390.5  361.32
  6462.1  366.26  6667.8  372.78  6803.1  381.02  6859.1     387  6946.6  388.81
#Mann= 3 ,-1 , 0
  3931.8     .05       0  4995.7     .03       0  5001.7     .05       0
Bank Sta=4977.9,5034.3
XS Rating Curve= 0 ,0
Exp/Cntr=0.3,0.1

Type RM Length L Ch R = 1 ,38702   ,463,463,463
BEGIN DESCRIPTION:
BROWNS CREEK 57.0
END DESCRIPTION:
XS GIS Cut Line= 3
      3617284.12     10552103.64      3616949.61     10551210.19
      3615749.59     10550010.17
#Sta/Elev= 30
  4059.2  372.91  4460.2  355.62  4656.1  344.84  4778.3  341.94  4827.1  337.51
  4912.6  332.81  4959.8  332.56  4967.8  329.37  4973.1  321.85  4995.1  317.44
  4997.8  316.94  5001.1  317.44  5003.4  319.99  5016.8  321.72  5027.4  328.09
  5041.5  332.59  5554.6  330.18  5572.3  330.18  5689.2  331.33  5716.7  332.53
    5791  330.23  5823.7  330.77  5861.7   332.5  5904.2  330.55  6017.3   330.7
  6229.4  335.66  6370.9  345.58  6498.1  357.26  6597.1  367.79  6710.3  383.68
#Mann= 8 ,-1 , 0
  4059.2     .05       0  4995.1     .03       0  5001.1     .05       0
  5554.6      .1       0  5572.3     .08       0  5689.2      .1       0
  5716.7     .08       0  5823.7     .05       0
Bank Sta=4959.8,5041.5
XS Rating Curve= 0 ,0
Exp/Cntr=0.3,0.1

Type RM Length L Ch R = 1 ,38239   ,439,439,439
BEGIN DESCRIPTION:
BROWNS CREEK 56.0
END DESCRIPTION:
XS GIS Cut Line= 3
      3617449.06     10552008.22      3617349.61     10551060.19
      3617188.64     10549456.07
#Sta/Elev= 30
  4071.2  369.68  4471.4  355.67  4742.9  336.07    4944  331.52  4964.1  328.62
  4972.8  323.35  4977.8  324.02  4994.3  316.72  5001.3  316.25  5004.1  315.75
  5007.3  316.25  5014.4  322.87  5021.9  326.37  5026.9  326.37  5034.5  331.83
  5084.7  331.01  5114.9  333.87  5155.1  330.18  5617.4  330.18  5657.6  334.37
  5735.5  333.74  5742.7  333.77  5908.8  333.54    5929  336.36  5959.1  332.66
  6371.2  360.38  6381.4  365.13  6411.4  362.84  6626.3   371.6  6636.6  372.09
#Mann= 6 ,-1 , 0
  4071.2     .05       0  5001.3     .03       0  5007.3     .05       0
  5735.5     .16       0  5742.7     .05       0  6626.3     .08       0
Bank Sta=4944,5034.5
XS Rating Curve= 0 ,0
Exp/Cntr=0.3,0.1

Type RM Length L Ch R = 1 ,37800   ,1005,1005,1005
BEGIN DESCRIPTION:
BROWNS CREEK 55.0
END DESCRIPTION:
XS GIS Cut Line= 3
      3617735.52     10552199.17      3617718.16     10550688.74
      3617292.81      10549456.1
#Sta/Elev= 30
  3666.7  372.81  4002.1  354.66  4105.7  350.12    4180  352.81  4355.7  349.96
    4474  343.49  4685.8  333.14  4875.8  331.03  4925.8  325.44  4945.8  329.91
  4965.8  330.81  4985.8  323.82  4992.8  315.46  4995.5  314.96  4998.8  315.46
  5015.8   319.6  5035.8  330.98  5083.1  329.44  5115.8  329.49  5165.8  333.79
  5196.9  330.18    5546  330.18  5577.7  332.84  5621.3  329.38  5746.9  333.94
  5985.1  348.34  6150.3  355.88  6154.2  356.03  6339.4  362.65  6481.2  371.76
#Mann= 9 ,-1 , 0
  3666.7     .05       0  4002.1     .16       0    4180     .05       0
    4474     .16       0  4992.8     .07       0  4998.8     .16       0
  5083.1     .05       0  6150.3     .08       0  6154.2     .05       0
Bank Sta=4965.8,5035.8
XS Rating Curve= 0 ,0
Exp/Cntr=0.3,0.1

Type RM Length L Ch R = 1 ,36795   ,679,679,679
BEGIN DESCRIPTION:
BROWNS CREEK 54.0
END DESCRIPTION:
XS GIS Cut Line= 3
      3618164.35     10552025.85      3618449.61     10550610.19
      3618750.97     10549014.31
#Sta/Elev= 30
  3520.4   363.4  3973.6  353.37  3995.4  350.73  4099.9  345.25  4148.4  343.61
  4207.9  336.56  4291.2  327.82  4452.1  324.89  4495.5  324.82  4850.1  327.18
  4944.2   326.2  4974.7   319.4  4984.9  313.57  4990.7  313.11  4995.8  315.44
  5002.2  312.98    5005  312.48  5008.2  312.98  5015.4  314.03  5025.6  326.85
    5107  327.46  5117.2  324.08  5127.3  324.55  5137.5   327.8  5514.1  323.24
  5915.3   321.3    6319  326.83  6409.6   329.1  6565.8  338.29  6588.6  338.03
#Mann= 11 ,-1 , 0
  3520.4     .05       0  4099.9     .16       0  4207.9     .05       0
  4452.1     .16       0  4495.5     .05       0  4850.1     .12       0
  5002.2     .07       0  5008.2     .12       0  5915.3     .16       0
    6319     .05       0  6565.8     .08       0
Bank Sta=4944.2,5025.6
XS Rating Curve= 0 ,0
Exp/Cntr=0.3,0.1

Type RM Length L Ch R = 1 ,36116   ,308,308,308
BEGIN DESCRIPTION:
BROWNS CREEK 53.0
END DESCRIPTION:
XS GIS Cut Line= 3
      3618242.48     10552112.65      3618598.37     10551071.03
      3619500.99       10550125.
#Sta/Elev= 30
  3641.7  368.01  3919.1  359.55  4278.4   335.6    4296  332.21    4467  323.81
  4656.7  323.76  4948.9   325.3  4970.2  324.47  4984.4  318.12  4988.6  312.27
  4991.4  311.77  4994.6  312.27  5012.7  314.04  5019.9  319.26    5041  324.41
  5288.5  325.77  5302.7  314.86  5316.8  315.79    5331  324.99  5336.1  324.85
    5437  325.89  5543.1  336.65  5592.7  344.05  5630.8  346.16  5692.5  350.74
  5755.3  351.24  5847.4   345.4    5904  347.46  5955.1  352.81    6050  360.63
#Mann= 11 ,-1 , 0
  3641.7     .05       0    4467     .16       0  4656.7     .05       0
  4948.9     .12       0  4988.6     .07       0  4994.6     .12       0
  5336.1     .05       0  5543.1      .1       0  5630.8     .16       0
  5692.5      .1       0  5955.1     .05       0
Bank Sta=4970.2,5041
XS Rating Curve= 0 ,0
Exp/Cntr=0.3,0.1

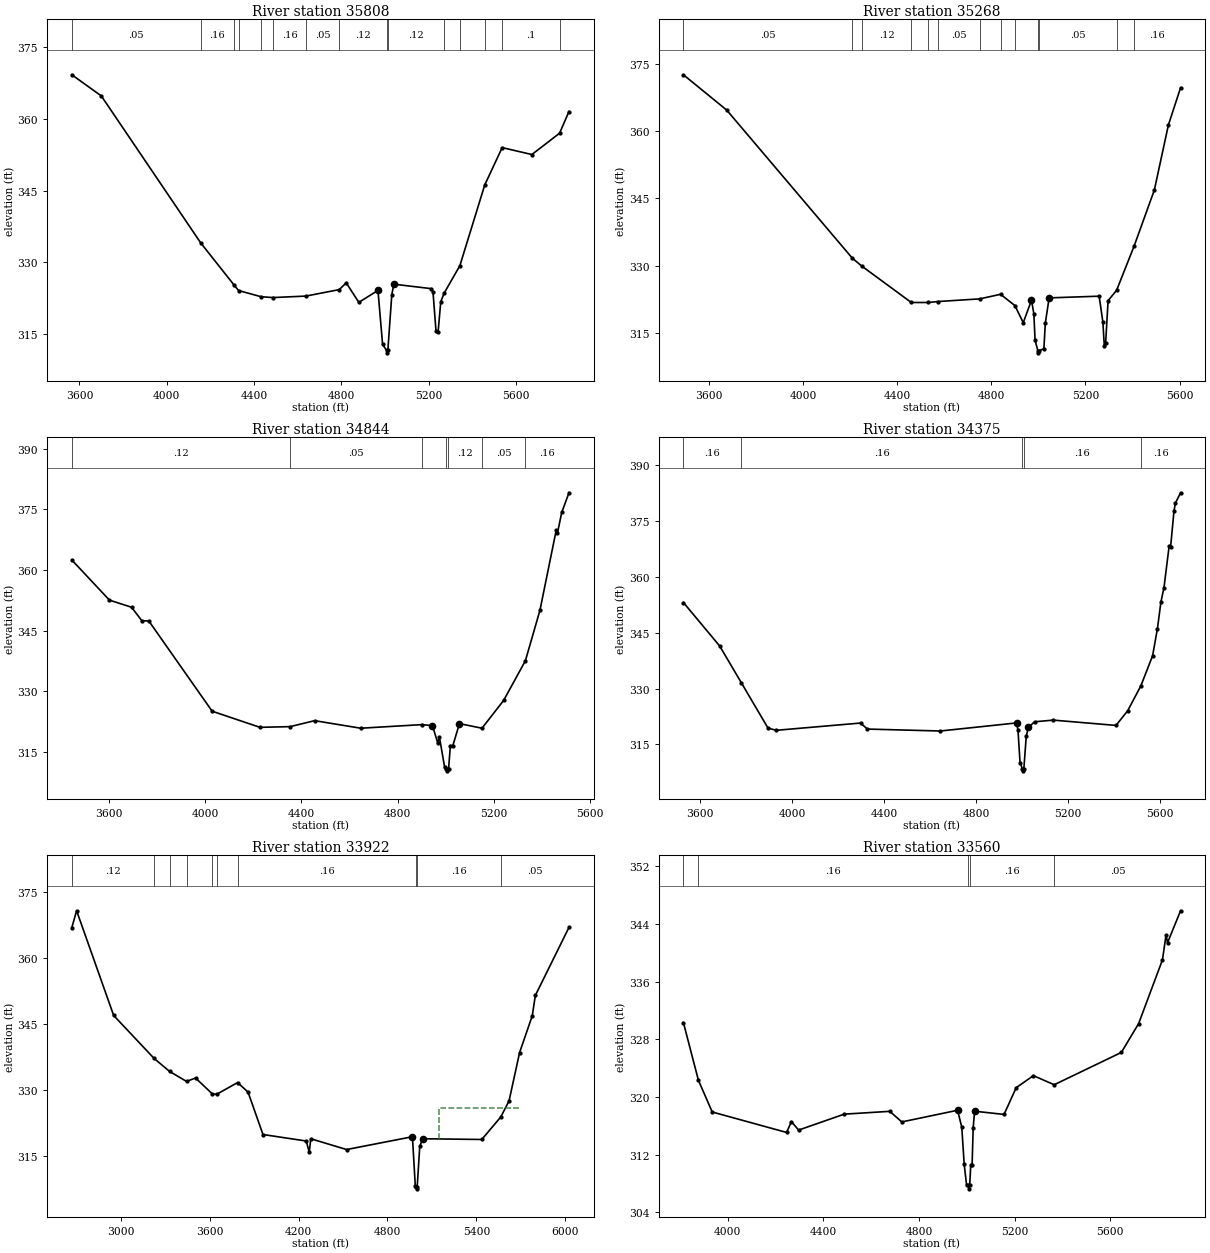
Type RM Length L Ch R = 1 ,35808   ,540,540,540
BEGIN DESCRIPTION:
BROWNS CREEK 52.0
END DESCRIPTION:
XS GIS Cut Line= 3
      3618303.25     10552121.34      3619370.94     10550463.39
      3619595.57     10550256.03
#Sta/Elev= 30
  3565.1  369.24  3700.1  364.82  4155.8  334.07    4308  325.29  4329.1  324.12
  4432.5  322.82  4487.1  322.65  4637.8  322.96  4789.9  324.31  4822.4  325.72
  4879.9  321.65  4967.7  324.14  4988.8  312.87  5006.9  311.59  5009.7  311.09
  5012.9  311.59  5031.1  323.27  5040.3  325.45  5212.6  324.51  5219.8  323.83
  5233.7  315.59    5243  315.37  5255.4  321.79  5270.8  323.56    5343  329.33
  5456.8  346.19  5536.7  354.01  5672.7  352.56  5799.8  357.02  5842.8  361.56
#Mann= 15 ,-1 , 0
  3565.1     .05       0  4155.8     .16       0    4308     .05       0
  4329.1     .16       0  4432.5     .05       0  4487.1     .16       0
  4637.8     .05       0  4789.9     .12       0  5006.9     .07       0
  5012.9     .12       0  5270.8     .05       0    5343      .1       0
  5456.8     .16       0  5536.7      .1       0  5799.8     .05       0
Bank Sta=4967.7,5040.3
XS Rating Curve= 0 ,0
Exp/Cntr=0.3,0.1

Type RM Length L Ch R = 1 ,35268   ,424,424,424
BEGIN DESCRIPTION:
BROWNS CREEK 51.0
END DESCRIPTION:
XS GIS Cut Line= 3
       3618299.6      10552210.2      3619299.61     10551110.19
       3619599.6      10550560.2
#Sta/Elev= 30
  3491.1  372.57  3675.2  364.69  4208.8  331.67  4248.5  329.92  4459.8  321.77
  4531.9  321.77  4574.2  321.99  4750.7  322.58    4839   323.6  4900.2  321.08
  4935.5  317.26  4970.6  322.28  4980.6  319.27  4985.8  313.37  4997.5  311.04
  5000.2  310.54  5003.5  311.04  5023.3  311.47  5029.4  317.18  5045.6   322.8
  5258.2  323.18  5273.9  317.45    5280  312.15  5285.7   312.7  5296.2  322.18
  5332.4   324.5  5406.2  334.28  5492.7  346.84  5552.5  361.37  5604.2  369.67
#Mann= 13 ,-1 , 0
  3491.1     .05       0  4208.8     .16       0  4248.5     .12       0
  4459.8     .16       0  4531.9     .12       0  4574.2     .05       0
  4750.7     .08       0    4839     .12       0  4900.2     .05       0
  4997.5     .03       0  5003.5     .05       0  5332.4     .05       0
  5406.2     .16       0
Bank Sta=4970.6,5045.6
XS Rating Curve= 0 ,0
Exp/Cntr=0.3,0.1

Type RM Length L Ch R = 1 ,34844   ,469,469,469
BEGIN DESCRIPTION:
BROWNS CREEK 50.0
END DESCRIPTION:
XS GIS Cut Line= 3
      3618699.58     10552260.22      3619699.61     10551060.19
      3619649.61     10550560.17
#Sta/Elev= 30
  3446.8  362.49    3603  352.57  3694.8  350.81  3737.8  347.45  3766.4  347.43
  4029.4   325.1  4227.9  321.11  4353.1  321.28    4455  322.76  4646.4  320.89
  4900.3  321.78  4944.5  321.53  4966.6  317.21  4973.1  318.77  4995.2  311.18
  5002.6  310.85  5005.4  310.35  5008.6  310.85  5011.4  310.85  5018.9  316.61
    5029  316.57  5056.6  322.03  5150.1  320.89    5240  327.76  5330.3  337.56
  5390.8  350.05  5458.6  369.91  5463.6  369.16  5481.2  374.25  5511.4  379.12
#Mann= 7 ,-1 , 0
  3446.8     .12       0  4353.1     .05       0  4900.3     .12       0
  5002.6     .07       0  5008.6     .12       0  5150.1     .05       0
  5330.3     .16       0
Bank Sta=4944.5,5056.6
XS Rating Curve= 0 ,0
Exp/Cntr=0.3,0.1

Type RM Length L Ch R = 1 ,34375   ,453,453,453
BEGIN DESCRIPTION:
BROWNS CREEK 49.0
END DESCRIPTION:
XS GIS Cut Line= 3
       3619299.6      10552360.2      3620099.61     10551160.19
      3619699.64     10550560.23
#Sta/Elev= 30
  3527.3  353.13  3685.1  341.43  3779.7  331.52  3895.4  319.36  3931.4  318.77
    4298  320.72    4328   319.1    4645  318.58    4977  320.75  4983.1  318.87
  4992.1   310.1  5002.6  308.37  5005.3  307.87  5008.6  308.37  5019.1  317.13
  5028.1  319.53  5055.2  321.05  5136.3  321.51  5409.7  320.08  5460.8  324.05
  5517.9  330.73    5569  338.83    5590  346.11    5605  353.21  5618.5  357.16
  5641.1   368.4  5647.1  367.96  5662.1  377.77  5668.1  379.85  5690.6  382.63
#Mann= 5 ,-1 , 0
  3527.3     .16       0  3779.7     .16       0  5002.6     .07       0
  5008.6     .16       0  5517.9     .16       0
Bank Sta=4977,5028.1
XS Rating Curve= 0 ,0
Exp/Cntr=0.3,0.1

Type RM Length L Ch R = 1 ,33922   ,362,362,362
BEGIN DESCRIPTION:
BROWNS CREEK 48.0
END DESCRIPTION:
XS GIS Cut Line= 3
      3620678.23      10553310.3      3620374.41     10550871.03
      3619784.91     10550194.84
#Sta/Elev= 30
  2669.7     367    2702  370.82    2952     347  3224.7  337.23    3330  334.25
    3444  331.99  3504.6  332.77  3618.1  329.15  3646.9  329.06  3788.4  331.73
  3858.9  329.57  3959.7  319.91  4251.9  318.43  4272.1  315.84  4282.2  318.95
    4524  316.49  4968.4  319.41  4987.6  308.26  4994.7  308.05  4997.4  307.55
  5000.7  308.05  5017.8  317.23    5038  318.95  5436.3  318.78  5564.5   323.9
  5620.5  327.57  5691.7  338.57  5777.1  346.93    5798  351.56  6024.9  367.04
#Mann= 10 ,-1 , 0
  2669.7     .12       0  3224.7     .16       0    3330     .12       0
    3444     .16       0  3618.1     .12       0  3646.9     .16       0
  3788.4     .16       0  4994.7     .07       0  5000.7     .16       0
  5564.5     .05       0
#XS Ineff= 1 ,-1
    5150    5700  326.03
Permanent Ineff=
       F
Bank Sta=4968.4,5038
XS Rating Curve= 0 ,0
Exp/Cntr=0.3,0.1

Type RM Length L Ch R = 1 ,33560   ,326,326,326
BEGIN DESCRIPTION:
BROWNS CREEK 47.0
END DESCRIPTION:
XS GIS Cut Line= 3
      3620799.61     10552010.17      3620699.61     10550810.19
      3619974.28     10550321.39
#Sta/Elev= 30
  3814.8   330.3  3877.5   322.3  3935.2   317.9  4246.3  315.06  4266.3  316.57
  4296.4  315.39  4487.1   317.6  4677.8  317.99  4727.9  316.52  4961.2  318.14
  4978.8  315.77  4988.8  310.67  4998.9  307.75  5005.9  307.74  5008.7  307.24
  5011.9  307.74  5016.4  310.61    5022  310.61  5026.4  315.71  5032.5  318.01
  5155.4  317.56  5206.3  321.27  5278.3  322.94  5365.2  321.68    5646  326.16
  5718.4  330.17    5818  339.01    5833  342.49    5839  341.37  5893.6  345.81
#Mann= 5 ,-1 , 0
  3814.8     .16       0  3877.5     .16       0  5005.9     .03       0
  5011.9     .16       0  5365.2     .05       0
Bank Sta=4961.2,5032.5
XS Rating Curve= 0 ,0
Exp/Cntr=0.3,0.1

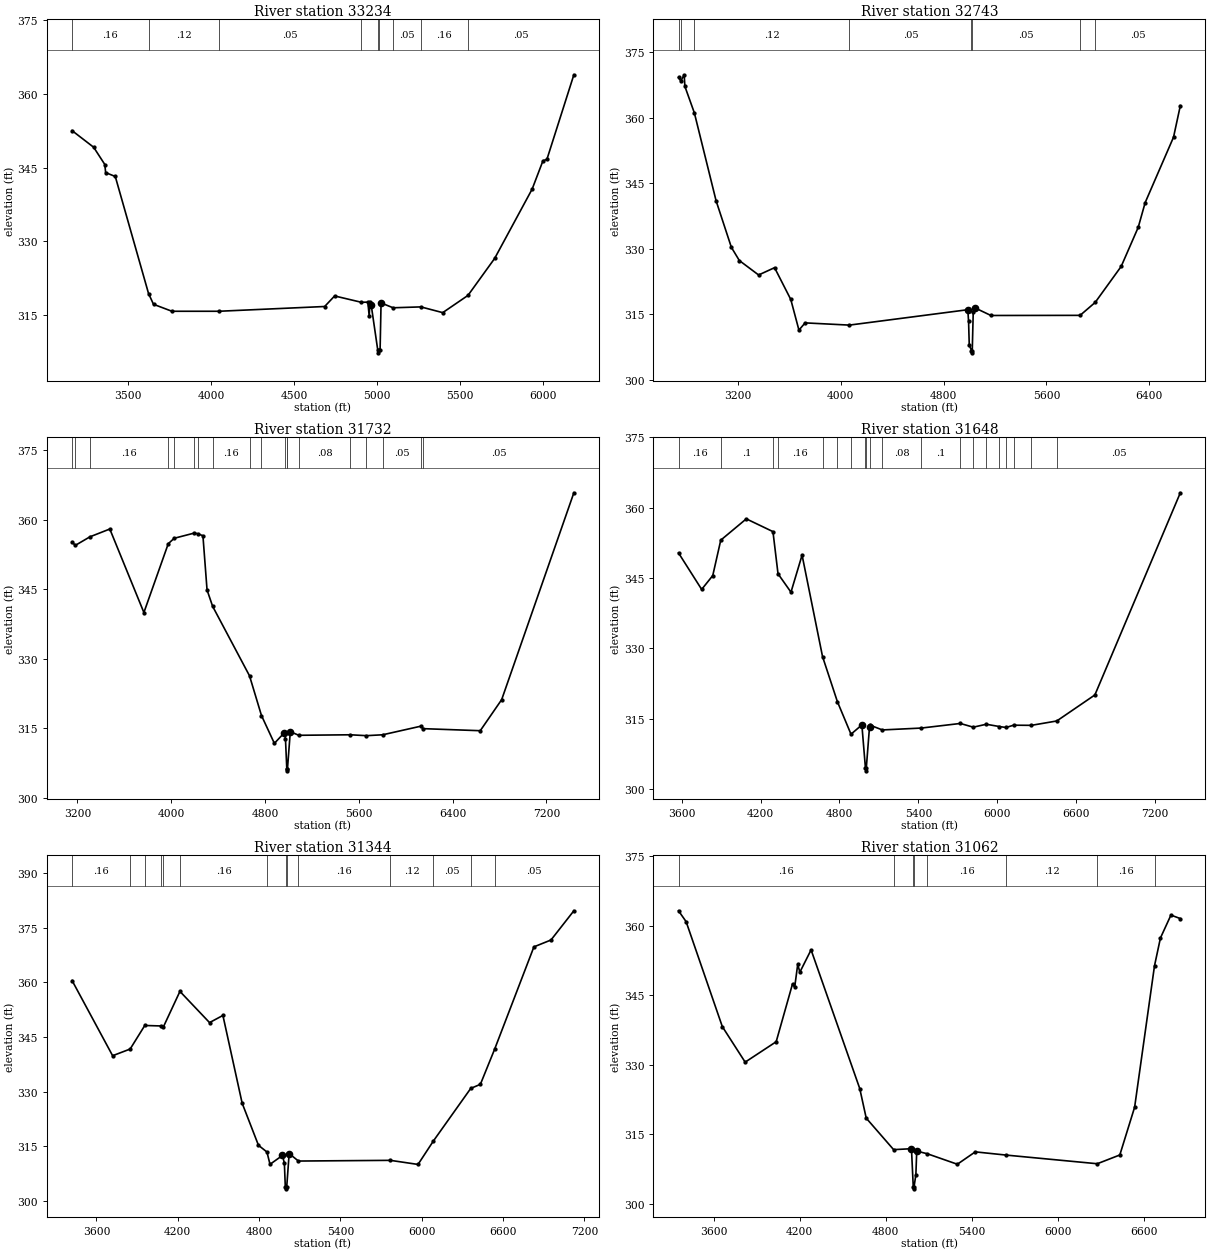
Type RM Length L Ch R = 1 ,33234   ,491,491,491
BEGIN DESCRIPTION:
BROWNS CREEK 46.0
END DESCRIPTION:
XS GIS Cut Line= 3
      3620849.61     10552410.22      3620895.75       10550574.
      3619796.89     10550133.68
#Sta/Elev= 30
  3163.2  352.52  3293.3  349.13  3360.3  345.62  3365.3  343.97  3423.3  343.18
  3623.6  319.33  3653.4  317.14  3764.4  315.72  4046.7  315.72  4683.7  316.69
  4743.7  318.84  4904.6  317.55  4943.8  317.58  4951.7  314.77  4956.7  317.68
  4963.8  317.01  5003.6  307.75  5006.4  307.25  5009.6  307.75  5017.4  307.81
  5023.2  317.42  5095.5  316.43  5262.9  316.61  5394.4  315.44  5546.4  318.95
  5706.9  326.48  5932.7  340.61  5997.7  346.37  6021.6  346.67  6183.8   363.9
#Mann= 9 ,-1 , 0
  3163.2     .16       0  3623.6     .12       0  4046.7     .05       0
  4904.6     .16       0  5003.6     .07       0  5009.6     .16       0
  5095.5     .05       0  5262.9     .16       0  5546.4     .05       0
Bank Sta=4963.8,5023.2
XS Rating Curve= 0 ,0
Exp/Cntr=0.3,0.1

Type RM Length L Ch R = 1 ,32743   ,1011,1011,1011
BEGIN DESCRIPTION:
Mapping XS 0eb96b44
END DESCRIPTION:
XS GIS Cut Line= 4
      3622059.92     10552714.39      3621261.32     10550431.44
      3620740.49     10550379.35      3619814.02     10550120.84
#Sta/Elev= 30
  2737.3  369.18  2755.1  368.37  2781.3   369.8  2786.6  367.15  2860.5  361.08
  3029.5  340.99  3148.4  330.35  3210.4  327.33  3360.3  324.03  3484.4   325.7
  3610.5  318.44    3674  311.43  3722.1  313.08    4066  312.57  4987.7  316.09
  4993.8   313.4  4999.1  308.01  5016.5  306.73  5019.3  306.23  5022.5  306.73
  5030.1  315.66  5040.7  316.55  5167.7  314.77  5861.5   314.8  5978.9  317.76
  6181.2  325.99  6313.6  334.92  6367.6  340.57  6588.3  355.53  6641.2  362.74
#Mann= 8 ,-1 , 0
  2737.3     .12       0  2755.1     .16       0  2860.5     .12       0
    4066     .05       0  5016.5     .03       0  5022.5     .05       0
  5861.5     .16       0  5978.9     .05       0
Bank Sta=4987.7,5040.7
XS Rating Curve= 0 ,0
Exp/Cntr=0.3,0.1

Type RM Length L Ch R = 1 ,31732   ,84,84,84
BEGIN DESCRIPTION:
BROWNS CREEK 45.0
END DESCRIPTION:
XS GIS Cut Line= 6
      3623518.84     10551334.94      3622034.58     10550100.56
      3621474.68     10550137.02      3621220.78     10550101.87
      3620845.78     10550293.27      3619775.42     10550097.95
#Sta/Elev= 30
  3154.4  355.21    3182  354.48  3307.1  356.33  3476.3  358.01  3767.1  339.99
  3974.8  354.83  4025.3  356.01  4197.4  357.14  4227.2  356.99  4270.7  356.56
  4305.8  344.86  4353.4  341.33    4668  326.34    4770  317.77  4880.1  311.76
  4965.8  314.07  4974.8  312.72    4986  306.33  4988.7  305.83    4992  306.33
    5016  314.28  5088.4   313.5  5527.4  313.61  5665.2  313.42  5804.1  313.61
  6126.7  315.45  6151.7  314.93  6636.3  314.49  6818.9  321.19  7434.8  365.83
#Mann= 19 ,-1 , 0
  3154.4     .16       0    3182      .1       0  3307.1     .16       0
  3974.8     .08       0  4025.3      .1       0  4197.4     .15       0
  4227.2     .08       0  4353.4     .16       0    4668     .05       0
    4770     .16       0  4974.8     .12       0    4986     .03       0
    4992     .12       0  5088.4     .08       0  5527.4     .05       0
  5665.2     .08       0  5804.1     .05       0  6126.7     .16       0
  6151.7     .05       0
Bank Sta=4965.8,5016
XS Rating Curve= 0 ,0
Exp/Cntr=0.3,0.1

Type RM Length L Ch R = 1 ,31648   ,304,304,304
BEGIN DESCRIPTION:
BROWNS CREEK 44.0
END DESCRIPTION:
XS GIS Cut Line= 6
      3623239.32     10550978.59      3622445.06     10550246.83
       3622073.7      10550023.1      3621108.42     10550005.74
      3620844.53      10550148.1      3619814.85     10550017.66
#Sta/Elev= 30
  3575.8  350.34  3751.7  342.57  3836.1  345.52    3897  353.07  4091.3  357.61
    4294  354.89  4332.5   345.9    4431  341.98  4515.5  349.88    4671  328.26
  4783.8  318.66  4887.6   311.7  4970.3  313.68  4997.7  304.39  5000.4  303.89
  5003.7  304.39  5028.5  313.29  5034.2  313.61  5125.8  312.61  5422.3  313.01
  5718.8  313.99  5817.6   313.2  5916.5  313.82  6015.3  313.34    6067  313.13
  6123.7  313.62  6259.6  313.59  6452.7  314.52  6742.6  320.07  7392.5  363.17
#Mann= 20 ,-1 , 0
  3575.8     .16       0    3897      .1       0    4294     .08       0
  4332.5     .16       0    4671     .05       0  4783.8     .16       0
  4887.6     .12       0  4997.7     .07       0  5003.7     .12       0
  5034.2     .12       0  5125.8     .08       0  5422.3      .1       0
  5718.8     .08       0  5817.6     .05       0  5916.5     .16       0
  6015.3     .12       0    6067     .16       0  6123.7     .12       0
  6259.6     .16       0  6452.7     .05       0
Bank Sta=4970.3,5028.5
XS Rating Curve= 0 ,0
Exp/Cntr=0.3,0.1

Type RM Length L Ch R = 1 ,31344   ,282,282,282
BEGIN DESCRIPTION:
BROWNS CREEK 43.0
END DESCRIPTION:
XS GIS Cut Line= 3
      3623348.68     10550973.37      3622135.16     10549634.85
       3620412.9     10548843.96
#Sta/Elev= 30
  3420.6  360.48  3719.8  339.87    3849   341.7  3957.1  348.16  4075.2  348.03
  4094.3  347.77  4216.3   357.5  4434.8  348.95  4533.4  350.91  4675.4  326.85
  4795.7  315.32  4858.4  313.47  4880.8   310.1  4972.7  312.53  4986.9  310.41
  4993.7  303.94  4998.1  303.88  5000.9  303.38  5004.1  303.88  5022.1  313.05
  5090.6     311  5768.9  311.19  5972.8  310.07    6087  316.54  6361.8  330.91
  6432.9  332.03  6537.8  341.64  6827.8  369.71  6953.7  371.59  7122.5   379.6
#Mann= 14 ,-1 , 0
  3420.6     .16       0    3849      .1       0  3957.1     .08       0
  4075.2      .1       0  4094.3     .08       0  4216.3     .16       0
  4858.4     .12       0  4998.1     .07       0  5004.1     .12       0
  5090.6     .16       0  5768.9     .12       0    6087     .05       0
  6361.8     .16       0  6537.8     .05       0
Bank Sta=4972.7,5022.1
XS Rating Curve= 0 ,0
Exp/Cntr=0.3,0.1

Type RM Length L Ch R = 1 ,31062   ,515,515,515
BEGIN DESCRIPTION:
BROWNS CREEK 42.0
END DESCRIPTION:
XS GIS Cut Line= 3
      3623395.23      10550947.4      3622499.61     10549610.19
      3620899.63      10548610.2
#Sta/Elev= 30
  3356.3   363.2  3409.2  360.85  3661.4  338.23  3820.5  330.57  4036.6  334.97
  4150.7  347.46  4165.7  346.77  4186.7  351.63  4201.7  349.97  4279.8  354.77
    4619  324.87    4664   318.5  4854.9  311.71  4979.3  311.91  4991.6  303.76
  4994.4  303.26  4997.6  303.76    5010  306.34  5015.9   311.4  5089.9  310.82
  5298.9  308.56  5423.9  311.23  5640.8  310.53  6273.9  308.67  6430.9  310.56
  6534.1  320.86  6672.6  351.35    6714  357.34  6787.1  362.27  6852.5  361.52
#Mann= 8 ,-1 , 0
  3356.3     .16       0  4854.9     .12       0  4991.6     .07       0
  4997.6     .12       0  5089.9     .16       0  5640.8     .12       0
  6273.9     .16       0  6672.6     .05       0
Bank Sta=4979.3,5015.9
XS Rating Curve= 0 ,0
Exp/Cntr=0.3,0.1

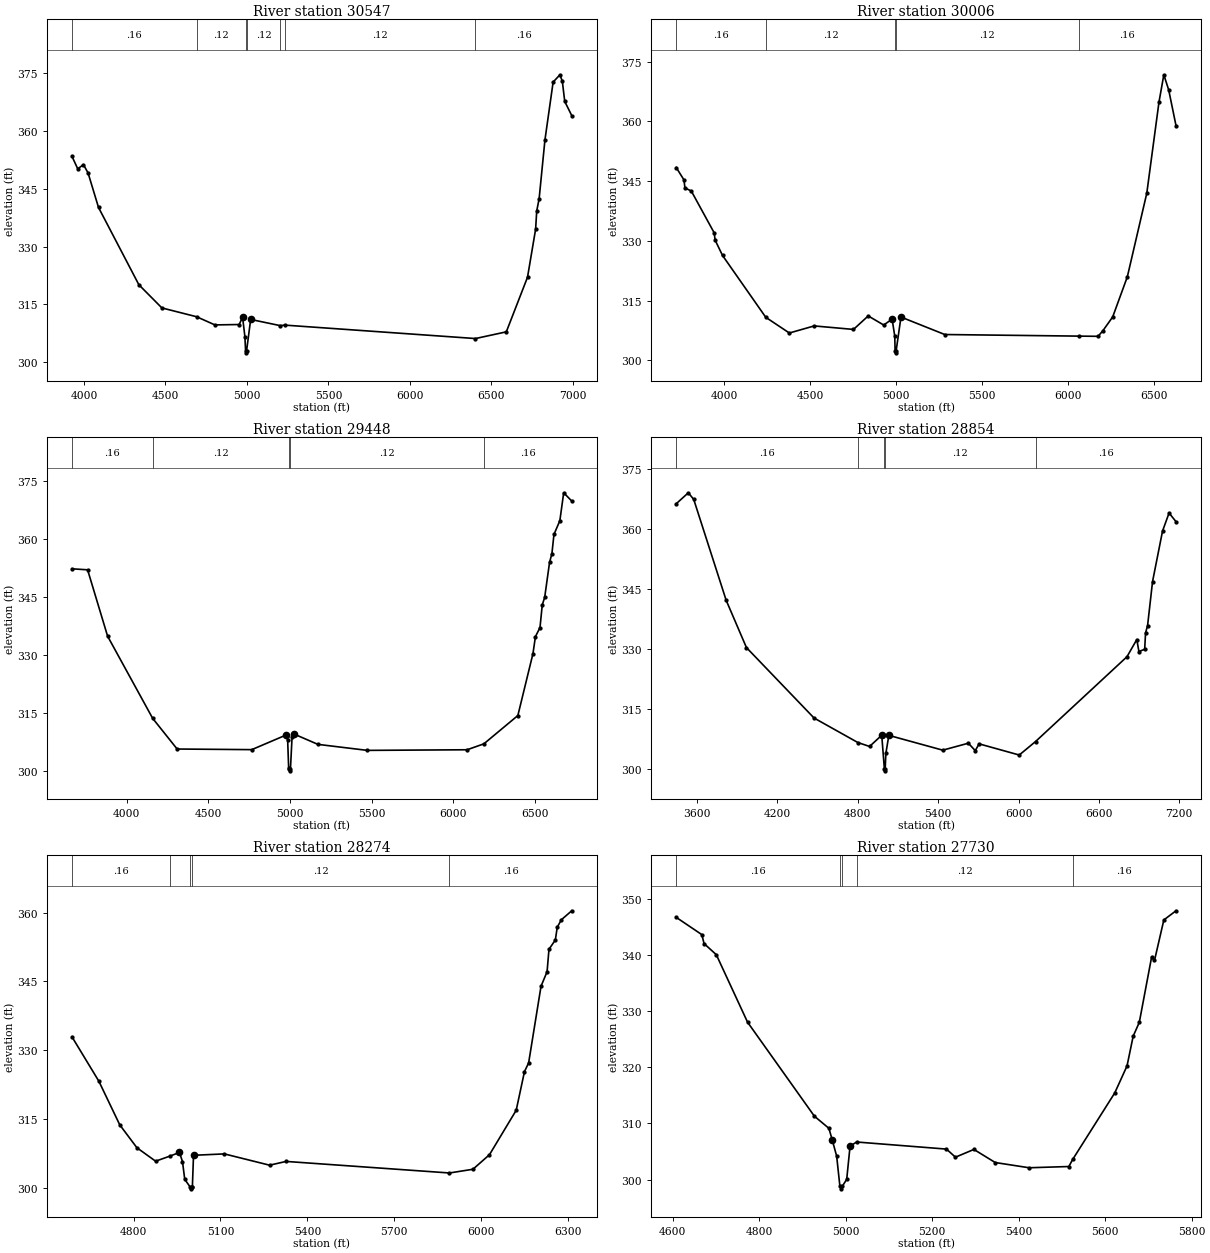
Type RM Length L Ch R = 1 ,30547   ,541,541,541
BEGIN DESCRIPTION:
BROWNS CREEK 41.0
END DESCRIPTION:
XS GIS Cut Line= 3
      3623549.59     10549910.17      3622749.61     10549160.19
      3621599.59     10547560.17
#Sta/Elev= 30
  3926.3  353.46  3961.7  350.22  3996.9  351.31  4025.2  349.13  4089.2  340.19
  4336.8  320.13    4478  314.11  4691.2  311.82  4803.5   309.7  4952.3   309.8
  4973.3  311.68  4987.5  306.67  4991.8  302.95  4994.5  302.45  4997.8  302.95
  5022.9  311.12  5205.7   309.5  5231.3  309.65  6402.3  306.16  6591.8   307.9
  6721.9  322.08  6771.6  334.55  6778.4  339.28  6793.2  342.47  6828.8  357.71
  6879.1  372.74  6920.9  374.63  6935.6  372.92  6950.3  367.71  6993.3  364.04
#Mann= 7 ,-1 , 0
  3926.3     .16       0  4691.2     .12       0  4991.8     .07       0
  4997.8     .12       0  5205.7     .16       0  5231.3     .12       0
  6402.3     .16       0
Bank Sta=4973.3,5022.9
XS Rating Curve= 0 ,0
Exp/Cntr=0.3,0.1

Type RM Length L Ch R = 1 ,30006   ,558,558,558
BEGIN DESCRIPTION:
BROWNS CREEK 40.0
END DESCRIPTION:
XS GIS Cut Line= 3
      3623499.61     10549810.18      3622849.61     10548710.19
      3621699.63     10547560.21
#Sta/Elev= 30
  3721.5  348.43  3766.4  345.32  3772.2  343.31  3809.3  342.51    3942  332.03
  3947.8  330.17  3990.7  326.33    4242   310.8  4378.9  306.86  4523.2  308.64
  4751.5  307.76  4837.2  311.15    4927  308.87    4976  310.34  4991.4  306.07
  4993.3  302.38    4996  301.88  4999.3  302.38  5027.5  310.87    5282  306.48
  6059.4  306.08    6173  306.03  6201.3  307.47  6257.8  310.91  6342.7  320.97
  6455.8  341.97  6526.5  364.81  6554.8  371.72  6583.1  367.92  6625.5  358.97
#Mann= 5 ,-1 , 0
  3721.5     .16       0    4242     .12       0  4993.3     .07       0
  4999.3     .12       0  6059.4     .16       0
Bank Sta=4976,5027.5
XS Rating Curve= 0 ,0
Exp/Cntr=0.3,0.1

Type RM Length L Ch R = 1 ,29448   ,594,594,594
BEGIN DESCRIPTION:
BROWNS CREEK 39.0
END DESCRIPTION:
XS GIS Cut Line= 3
       3623649.6     10549810.17      3623299.61     10548560.19
      3621849.65     10547560.21
#Sta/Elev= 30
  3666.1  352.29  3761.8  352.03  3884.2   334.9  4160.2  313.69  4309.9  305.78
  4766.8  305.62  4977.7  309.41  4986.5  308.01  4992.5  300.98  4997.6  300.65
  5000.3  300.15  5003.6  300.65  5013.5  308.95  5022.3   309.7  5171.7  306.98
  5474.3  305.43  6085.2  305.59  6187.6  307.12  6395.6  314.42  6488.2  330.42
  6503.1  334.77  6531.2  337.14    6545  342.96  6559.9  344.93  6589.6  353.92
  6604.1  356.22  6616.7  361.17  6652.7   364.7  6676.2  371.91  6725.5  369.78
#Mann= 5 ,-1 , 0
  3666.1     .16       0  4160.2     .12       0  4997.6     .07       0
  5003.6     .12       0  6187.6     .16       0
Bank Sta=4977.7,5022.3
XS Rating Curve= 0 ,0
Exp/Cntr=0.3,0.1

Type RM Length L Ch R = 1 ,28854   ,580,580,580
BEGIN DESCRIPTION:
BROWNS CREEK 38.0
END DESCRIPTION:
XS GIS Cut Line= 4
      3625189.03      10548131.8      3623876.58     10548314.08
      3623358.35     10548066.69      3621773.09     10547147.45
#Sta/Elev= 30
  3444.1  366.26  3534.4     369  3574.8  367.35  3817.1  342.15  3968.5  330.34
  4473.3  312.75  4800.3  306.63  4887.9  305.65  4978.7  308.45  4998.4  300.06
  5001.1  299.56  5004.4  300.06  5009.6  303.92  5031.7  308.42  5434.4  304.72
  5625.3  306.46  5677.2   304.6  5705.6   306.3  6005.4  303.51    6127  306.87
    6810  328.06  6883.3  332.35    6899  329.36  6942.1  329.91  6948.7  334.03
  6963.6  335.79  7000.9  346.84  7075.4  359.44  7124.2  363.95  7175.9  361.79
#Mann= 5 ,-1 , 0
  3444.1     .16       0  4800.3     .12       0  4998.4     .07       0
  5004.4     .12       0    6127     .16       0
Bank Sta=4978.7,5031.7
XS Rating Curve= 0 ,0
Exp/Cntr=0.3,0.1

Type RM Length L Ch R = 1 ,28274   ,544,544,544
BEGIN DESCRIPTION:
BROWNS CREEK 37.0
END DESCRIPTION:
XS GIS Cut Line= 3
      3624249.65     10547760.18      3623849.61     10547860.19
      3622849.61     10547010.19
#Sta/Elev= 30
  4587.5  332.89  4680.3  323.21  4752.5  313.68  4811.7  308.69  4876.2  305.76
  4925.9  306.88  4958.6  307.67  4968.9  305.67  4976.7   301.8  4994.3  300.23
    4997  299.73  5000.3  300.23  5003.1  300.23    5007  307.05  5113.5  307.35
  5269.5  304.89  5326.6  305.71  5890.2  303.19  5971.3     304  6028.4  307.18
  6120.6  316.87  6149.2  325.31  6163.5   327.2  6206.3  343.93  6227.2   347.1
  6233.7  351.99  6255.7  354.02  6262.3  356.81  6276.6  358.44  6312.3  360.39
#Mann= 5 ,-1 , 0
  4587.5     .16       0  4925.9     .12       0  4994.3     .07       0
  5000.3     .12       0  5890.2     .16       0
Bank Sta=4958.6,5007
XS Rating Curve= 0 ,0
Exp/Cntr=0.3,0.1

Type RM Length L Ch R = 1 ,27730   ,571,571,571
BEGIN DESCRIPTION:
BROWNS CREEK 36.0
END DESCRIPTION:
XS GIS Cut Line= 3
      3624449.58     10547510.18      3624049.61     10547410.19
       3623549.6     10546860.18
#Sta/Elev= 30
  4608.2  346.65  4667.4  343.58  4672.6  341.98  4700.9  340.01  4773.1  328.01
  4927.7  311.28  4961.2  309.13  4968.9  307.08  4979.2  304.17  4986.6  298.86
  4989.3  298.36  4992.6  298.86  5002.4  300.04  5010.2  305.97  5025.4  306.69
    5233  305.43  5253.9  303.99  5296.5  305.37  5345.8  303.04  5424.2  302.11
  5516.1  302.33    5525   303.6  5622.2  315.42  5650.6  320.23  5664.8  325.51
    5679  327.99  5707.4  339.58  5714.1  338.98  5735.7  346.19  5763.8  347.82
#Mann= 5 ,-1 , 0
  4608.2     .16       0  4986.6     .07       0  4992.6     .16       0
  5025.4     .12       0    5525     .16       0
Bank Sta=4968.9,5010.2
XS Rating Curve= 0 ,0
Exp/Cntr=0.3,0.1