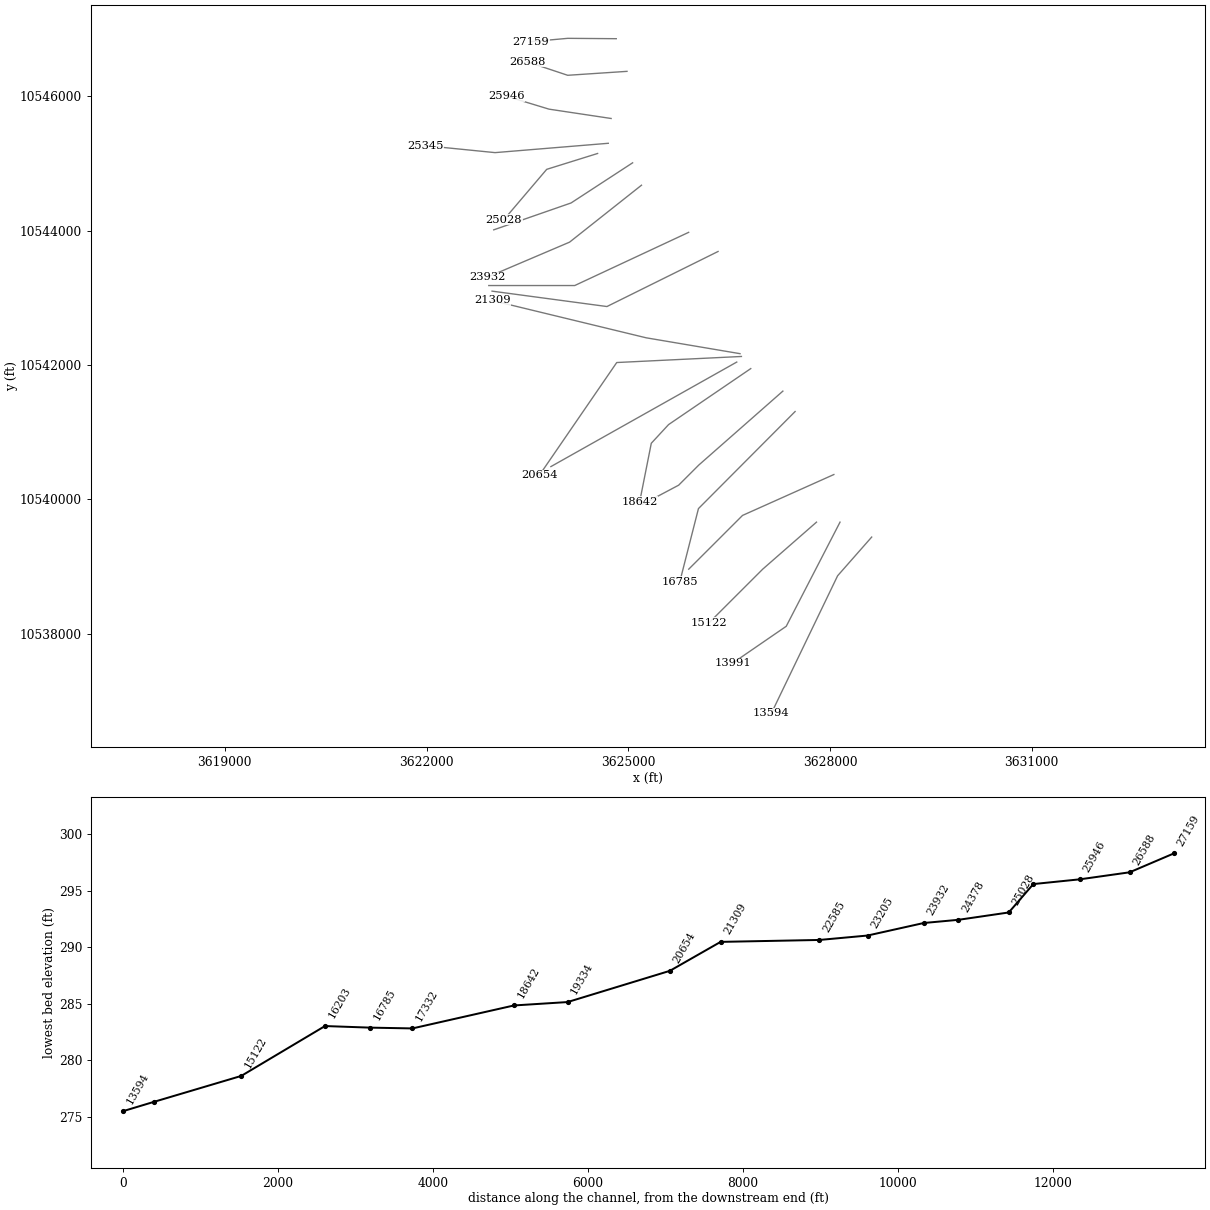
HEC-RAS study BROWNS CREEK.prj: BROWNS CREEK Base Level Engineering

--- BROWNS CREEK.g01 (geometry) --- (continued)

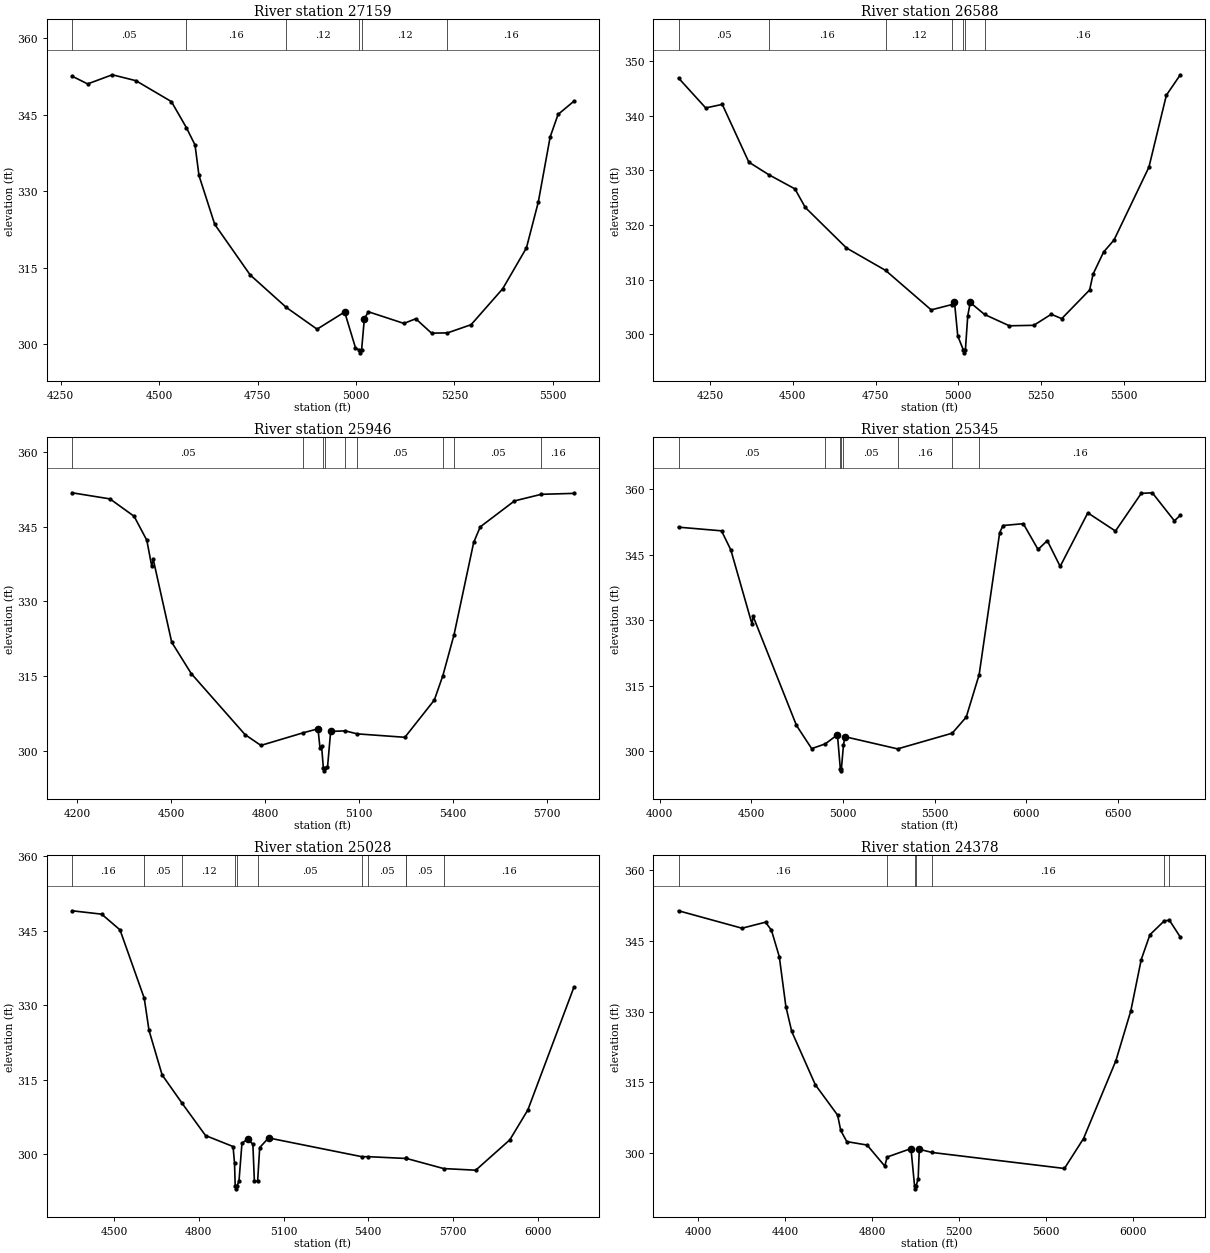
Type RM Length L Ch R = 1 ,27159   ,571,571,571
BEGIN DESCRIPTION:
BROWNS CREEK 35.0
END DESCRIPTION:
XS GIS Cut Line= 3
      3624821.85     10546854.88      3624099.61     10546860.19
      3623549.64     10546810.19
#Sta/Elev= 30
    4279  352.53  4318.5  351.01  4381.2   352.8  4441.2  351.64  4531.3  347.54
  4569.4  342.43  4591.3  339.04  4601.3  333.06  4641.3  323.48  4731.3  313.56
  4823.4  307.17  4901.3  302.92  4971.3  306.29  4998.8  299.28  5008.3  298.78
  5011.1  298.28  5014.3  298.78  5021.3   304.9  5031.4  306.34  5121.8  304.05
  5151.9  304.96    5192  302.14  5232.5  302.19  5292.5   303.8  5372.8  310.85
    5433  318.85  5463.2  327.85  5493.3  340.61  5513.4  345.03  5553.5  347.61
#Mann= 6 ,-1 , 0
    4279     .05       0  4569.4     .16       0  4823.4     .12       0
  5008.3     .07       0  5014.3     .12       0  5232.5     .16       0
Bank Sta=4971.3,5021.3
XS Rating Curve= 0 ,0
Exp/Cntr=0.3,0.1

Type RM Length L Ch R = 1 ,26588   ,642,642,642
BEGIN DESCRIPTION:
BROWNS CREEK 34.0
END DESCRIPTION:
XS GIS Cut Line= 3
      3624981.57     10546368.77      3624099.61     10546310.19
      3623499.57      10546510.2
#Sta/Elev= 30
  4154.7  346.91  4236.8  341.44  4286.9  342.09  4367.1  331.52  4427.4  329.22
  4506.5  326.62  4537.5  323.24  4662.1  315.81  4780.4   311.7  4918.3  304.47
  4979.7  305.43  4988.5  305.97  4998.5  299.69  5015.6  297.11  5018.3  296.61
  5021.6  297.11  5028.6  303.34  5036.1  305.83  5079.6  303.63  5154.5  301.56
  5228.3  301.65    5281  303.67  5312.7  302.87    5397  308.12  5407.5  311.03
  5439.2  315.06  5470.8  317.27  5576.2   330.6  5628.9  343.77  5671.1  347.51
#Mann= 7 ,-1 , 0
  4154.7     .05       0  4427.4     .16       0  4780.4     .12       0
  4979.7     .05       0  5015.6     .03       0  5021.6     .05       0
  5079.6     .16       0
Bank Sta=4988.5,5036.1
XS Rating Curve= 0 ,0
Exp/Cntr=0.3,0.1

Type RM Length L Ch R = 1 ,25946   ,601,601,601
BEGIN DESCRIPTION:
BROWNS CREEK 33.0
END DESCRIPTION:
XS GIS Cut Line= 3
      3624745.46     10545667.39      3623821.89     10545806.27
      3623183.84     10546000.46
#Sta/Elev= 30
  4184.1  351.77  4305.1  350.54  4382.1  347.05  4422.6  342.24    4438  337.13
  4443.1   338.4    4502  321.79  4564.2  315.51  4736.1  303.25  4786.6  301.09
  4921.4  303.62  4968.7  304.42    4975  300.62  4980.1  300.96  4985.9  296.49
  4988.6  295.99  4991.9  296.49    4999  296.66  5009.1   303.9  5055.7  304.01
  5093.4  303.41  5245.9  302.72  5339.9   310.2  5367.1   315.1  5402.6  323.26
  5465.4  341.81  5486.3  344.93  5595.6  350.14  5680.9  351.46    5785  351.65
#Mann= 9 ,-1 , 0
  4184.1     .05       0  4921.4     .12       0  4985.9     .07       0
  4991.9     .12       0  5055.7     .16       0  5093.4     .05       0
  5367.1     .12       0  5402.6     .05       0  5680.9     .16       0
Bank Sta=4968.7,5009.1
XS Rating Curve= 0 ,0
Exp/Cntr=0.3,0.1

Type RM Length L Ch R = 1 ,25345   ,317,317,317
BEGIN DESCRIPTION:
BROWNS CREEK 32.0
END DESCRIPTION:
XS GIS Cut Line= 3
      3624703.26     10545298.25      3623019.24     10545159.36
      3621977.57     10545263.53
#Sta/Elev= 30
  4103.4  351.27  4337.8  350.43  4388.5  346.08  4504.5  329.06  4509.5  330.96
  4746.6  305.95  4829.5  300.65  4903.8  301.73    4970  303.82  4985.7  296.07
  4988.4  295.57  4991.7  296.07  5002.7  301.37  5010.1  303.38  5298.1  300.59
  5596.1  304.18  5672.4  307.85  5742.8  317.55  5854.9  350.03  5873.2  351.65
  5983.7  352.06  6064.1  346.17  6114.4  348.19  6184.7   342.3  6335.5  354.54
  6486.2  350.38  6626.9  358.99  6687.2  359.13  6807.8  352.71    6840  354.01
#Mann= 8 ,-1 , 0
  4103.4     .05       0  4903.8     .07       0  4985.7     .07       0
  4991.7     .07       0  5002.7     .05       0  5298.1     .16       0
  5596.1     .05       0  5742.8     .16       0
Bank Sta=4970,5010.1
XS Rating Curve= 0 ,0
Exp/Cntr=0.3,0.1

Type RM Length L Ch R = 1 ,25028   ,650,650,650
BEGIN DESCRIPTION:
BROWNS CREEK 31.0
END DESCRIPTION:
XS GIS Cut Line= 3
      3624544.11     10545146.55      3623787.17     10544910.44
      3623149.59     10544160.17
#Sta/Elev= 30
    4351     349  4455.8  348.32  4520.8  345.16  4606.7   331.4  4623.5  324.95
    4670  315.98  4740.5   310.3  4823.8  303.78  4921.3  301.57  4926.5   298.2
  4928.9  293.56  4931.6  293.06  4934.9  293.56  4942.3  294.63  4952.8  302.24
  4973.8  303.11  4991.5     302  4996.8  294.62  5008.3  294.62  5015.7  301.37
  5047.1   303.3    5378  299.52  5400.8  299.53  5533.9  299.17  5534.5  299.19
  5667.1  297.14  5780.9  296.81  5901.7  302.92  5965.4  308.92  6128.5   333.6
#Mann= 11 ,-1 , 0
    4351     .16       0  4606.7     .05       0  4740.5     .12       0
  4928.9     .07       0  4934.9     .12       0  5008.3     .05       0
    5378     .16       0  5400.8     .05       0  5533.9     .16       0
  5534.5     .05       0  5667.1     .16       0
Bank Sta=4973.8,5047.1
XS Rating Curve= 0 ,0
Exp/Cntr=0.3,0.1

Type RM Length L Ch R = 1 ,24378   ,446,446,446
BEGIN DESCRIPTION:
BROWNS CREEK 30.0
END DESCRIPTION:
XS GIS Cut Line= 3
      3625064.97     10545007.67      3624149.61     10544410.19
      3622999.59     10544010.18
#Sta/Elev= 30
  3908.1   351.4  4200.3   347.7  4308.6  348.98  4335.9  347.28  4372.1  341.66
  4402.4  331.09  4429.4  325.79  4538.1  314.48  4640.7  308.04  4654.9  304.81
  4682.9  302.43  4776.4   301.7  4857.9  297.23  4868.8  299.16  4978.5  300.95
  4995.2  292.91    4998  292.41  5001.2  292.91  5011.5  294.51  5016.8   300.8
  5076.3  300.12  5685.1  296.73  5773.1  303.08  5922.3  319.62  5990.8  330.17
  6038.8  341.05  6078.8  346.32  6145.3  349.28  6168.8  349.38  6218.8  345.81
#Mann= 7 ,-1 , 0
  3908.1     .16       0  4868.8     .12       0  4995.2     .07       0
  5001.2     .12       0  5076.3     .16       0  6145.3     .05       0
  6168.8     .16       0
Bank Sta=4978.5,5016.8
XS Rating Curve= 0 ,0
Exp/Cntr=0.3,0.1

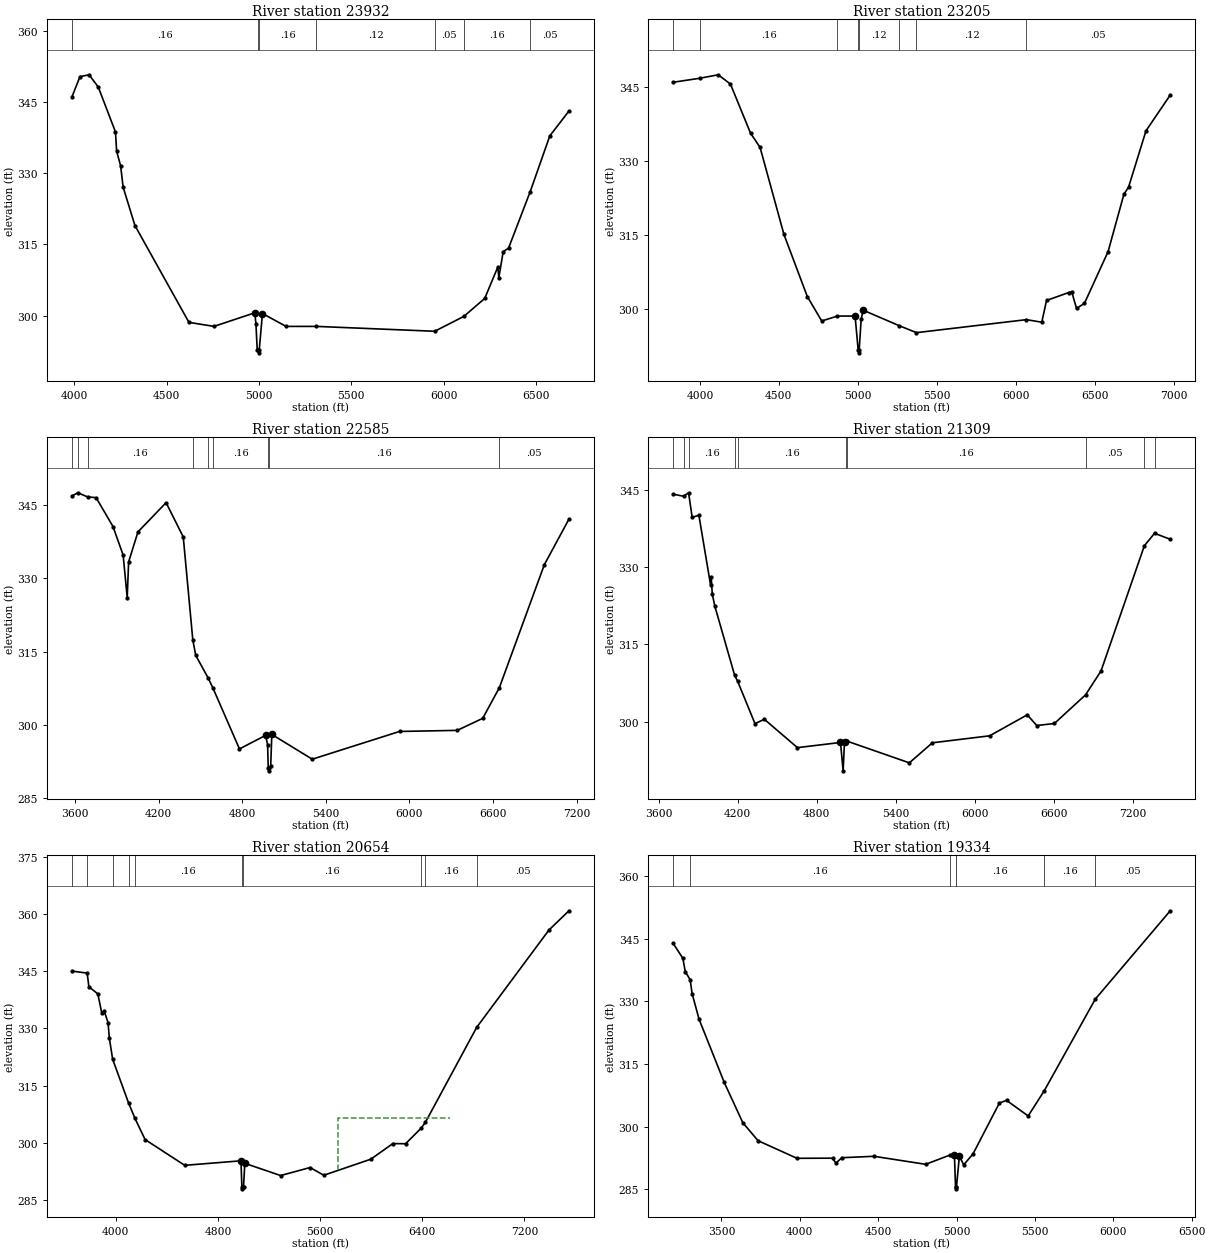
Type RM Length L Ch R = 1 ,23932   ,727,727,727
BEGIN DESCRIPTION:
BROWNS CREEK 29.0
END DESCRIPTION:
XS GIS Cut Line= 3
      3625196.85      10544674.3      3624127.45      10543827.1
      3622905.21     10543306.27
#Sta/Elev= 30
  3985.9  346.07  4029.9   350.4  4079.6   350.8  4129.2   348.2  4222.2  338.75
  4228.6  334.69  4250.3  331.56  4263.8  327.09  4327.9  318.98  4620.3  298.56
  4755.8  297.71    4977  300.58  4983.4  298.13  4990.2   292.7  4994.8  292.63
  4997.6  292.13  5000.8  292.63  5018.6  300.42  5146.8  297.71  5310.9  297.71
  5951.6  296.68    6110  299.83  6222.7  303.62  6293.5  310.23    6299  307.99
  6322.6  313.47  6351.6  314.22    6469  326.14  6575.1   337.9  6678.8  343.15
#Mann= 7 ,-1 , 0
  3985.9     .16       0  4994.8     .07       0  5000.8     .16       0
  5310.9     .12       0  5951.6     .05       0    6110     .16       0
    6469     .05       0
Bank Sta=4977,5018.6
XS Rating Curve= 0 ,0
Exp/Cntr=0.3,0.1

Type RM Length L Ch R = 1 ,23205   ,620,620,620
BEGIN DESCRIPTION:
BROWNS CREEK 28.0
END DESCRIPTION:
XS GIS Cut Line= 3
      3625898.31     10543972.95      3624203.83     10543181.27
      3622926.03     10543181.27
#Sta/Elev= 30
  3830.6  345.97  3998.6  346.78  4116.1  347.49  4193.4   345.6  4320.9  335.62
    4381  332.75    4532  315.09  4680.2  302.45  4771.6  297.49  4871.1  298.49
  4982.8  298.49  5002.6  291.52  5005.4  291.02  5008.6  291.52  5021.2  297.82
    5034  299.68  5260.9  296.55  5371.7  295.12  6068.1  297.76  6165.1  297.24
  6195.1  301.65  6335.1  303.26  6355.1  303.38  6385.1  300.05  6435.1  301.06
  6585.1  311.58  6685.1  323.21  6715.1  324.71  6825.1  336.12  6978.7  343.38
#Mann= 8 ,-1 , 0
  3830.6     .05       0  3998.6     .16       0  4871.1     .12       0
  5002.6     .07       0  5008.6     .12       0  5260.9     .16       0
  5371.7     .12       0  6068.1     .05       0
Bank Sta=4982.8,5034
XS Rating Curve= 0 ,0
Exp/Cntr=0.3,0.1

Type RM Length L Ch R = 1 ,22585   ,1276,1276,1276
BEGIN DESCRIPTION:
BROWNS CREEK 27.0
END DESCRIPTION:
XS GIS Cut Line= 3
      3626335.76     10543688.21        3624683.     10542868.77
      3622974.65     10543097.94
#Sta/Elev= 30
  3576.4  346.79  3618.8  347.46  3689.7  346.62  3750.7  346.46  3871.9  340.56
  3944.7  334.74  3973.9  326.02    3984  333.33  4051.2  339.47    4253  345.44
  4376.2  338.43  4444.9  317.35  4465.9  314.23  4553.1   309.7  4587.8  307.65
  4779.7  295.11  4967.3  297.88  4981.5  295.97  4986.6  291.13  4989.4  290.63
  4992.6  291.13  5003.9  291.58    5012  298.07  5302.2  293.01    5929  298.68
  6342.7   298.9  6525.9  301.36  6645.4  307.63  6968.3  332.77  7144.8  342.07
#Mann= 9 ,-1 , 0
  3576.4     .16       0  3618.8     .05       0  3689.7     .16       0
  4444.9     .05       0  4553.1     .16       0  4587.8     .16       0
  4986.6     .07       0  4992.6     .16       0  6645.4     .05       0
Bank Sta=4967.3,5012
XS Rating Curve= 0 ,0
Exp/Cntr=0.3,0.1

Type RM Length L Ch R = 1 ,21309   ,655,655,655
BEGIN DESCRIPTION:
BROWNS CREEK 26.0
END DESCRIPTION:
XS GIS Cut Line= 3
      3626662.21     10542167.38      3625266.33     10542403.49
      3622974.71     10542959.04
#Sta/Elev= 30
  3709.8  344.11  3789.8   343.7  3826.9  344.38  3854.4   339.6  3905.1  340.03
  3993.9   326.5    3999  327.97  4006.6  324.77  4026.8  322.34  4176.3  309.01
  4199.3  307.84  4331.1  299.61  4402.1  300.46  4653.3  294.96  4980.2  295.96
  5000.2  290.46  5010.6  296.08  5022.8   296.3  5030.9  296.21  5502.8  292.01
  5677.8   295.9    6112  297.25    6398  301.32  6470.1  299.25  6603.8  299.64
  6840.5  305.19  6958.3  309.85    7287  334.11  7364.3  336.52  7483.5  335.36
#Mann= 10 ,-1 , 0
  3709.8     .16       0  3789.8     .05       0  3826.9     .16       0
  4176.3     .05       0  4199.3     .16       0  5022.8     .05       0
  5030.9     .16       0  6840.5     .05       0    7287     .16       0
  7364.3     .05       0
Bank Sta=4980.2,5010.6
XS Rating Curve= 0 ,0
Exp/Cntr=0.3,0.1

Type RM Length L Ch R = 1 ,20654   ,1320,1320,1320
BEGIN DESCRIPTION:
BROWNS CREEK 25.0
END DESCRIPTION:
XS GIS Cut Line= 3
        3626683.     10542125.71      3624828.83     10542035.44
      3623676.17     10540355.04
#Sta/Elev= 30
  3655.1  345.06  3775.3  344.53  3788.6  340.95  3858.7  339.08  3888.8  334.16
  3908.8  334.55  3938.8  331.54  3948.8  327.47  3974.9  321.91    4099  310.49
  4149.1  306.43  4229.2  300.83  4539.5  294.07  4980.1  295.26  4987.1   288.4
  4989.8   287.9  4993.1   288.4  5000.1  288.45  5010.1   294.6  5290.4  291.39
  5521.4  293.49    5629  291.47  5996.5  295.67  6169.8  299.78  6269.7  299.74
  6391.1  303.81  6425.3  305.39    6827  330.31  7392.1  355.82  7549.2  360.89
#Mann= 10 ,-1 , 0
  3655.1     .16       0  3775.3     .05       0  3974.9     .16       0
    4099     .05       0  4149.1     .16       0  4987.1     .07       0
  4993.1     .16       0  6391.1     .05       0  6425.3     .16       0
    6827     .05       0
#XS Ineff= 1 ,-1
 5738.64 6616.48  306.58
Permanent Ineff=
       F
Bank Sta=4980.1,5010.1
XS Rating Curve= 0 ,0
Exp/Cntr=0.3,0.1

Type RM Length L Ch R = 1 ,19334   ,692,692,692
BEGIN DESCRIPTION:
BROWNS CREEK 24.0
END DESCRIPTION:
XS GIS Cut Line= 2
      3626613.59      10542042.4      3623849.67     10540486.83
#Sta/Elev= 30
  3191.8   343.9  3253.7  340.31  3269.3  337.11  3300.3   335.2  3312.7  331.89
    3357  325.75  3517.9   310.6  3636.4  300.96  3733.3  296.67  3981.8  292.45
  4208.7  292.48  4230.4   291.3    4268  292.59  4473.2  292.93  4802.9  291.01
  4959.8  293.25  4980.5  293.35  4986.5  292.98  4993.5  285.64  4996.2  285.14
  4999.5  285.64  5018.1  292.97  5045.5  290.89  5104.8  293.49  5273.3  305.68
  5319.2  306.31  5456.9  302.58  5560.2  308.66  5884.9  330.53  6363.4  351.69
#Mann= 7 ,-1 , 0
  3191.8     .16       0  3300.3     .16       0  4959.8     .16       0
  4993.5     .07       0  4999.5     .16       0  5560.2     .16       0
  5884.9     .05       0
Bank Sta=4980.5,5018.1
XS Rating Curve= 0 ,0
Exp/Cntr=0.3,0.1

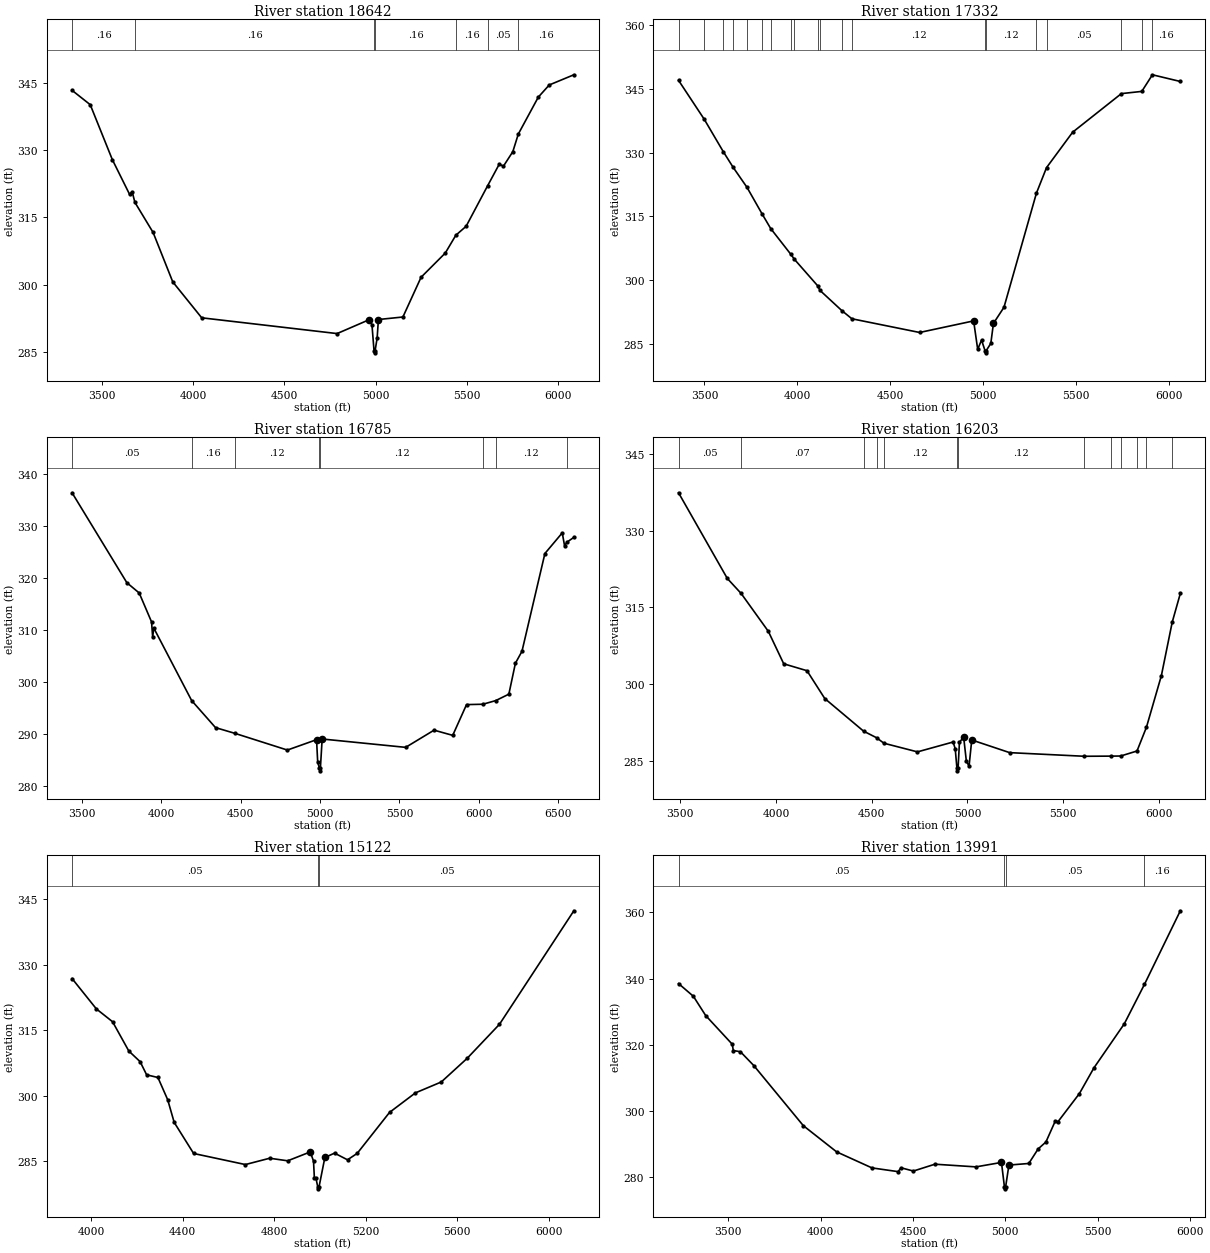
Type RM Length L Ch R = 1 ,18642   ,1310,1310,1310
BEGIN DESCRIPTION:
BROWNS CREEK 23.0
END DESCRIPTION:
XS GIS Cut Line= 4
      3626821.86     10541945.14      3625599.67     10541111.83
      3625342.72     10540834.05      3625169.11     10539959.04
#Sta/Elev= 30
  3336.2  343.29  3435.7   340.1  3556.8  327.87  3651.6  320.11  3665.7  320.68
  3680.5  318.35  3780.3  311.64    3888  300.64  4046.6  292.64  4788.5  289.13
  4965.4  292.24  4979.6  291.06  4990.8  285.34  4993.5  284.84  4996.8  285.34
    5008  288.16  5014.8  292.26  5149.1  292.82  5248.7  301.67  5381.3  307.06
  5439.2  311.03  5495.5  313.02    5613  322.02  5676.9  326.84  5700.2  326.42
  5751.4  329.64  5781.6  333.57    5891  341.78    5951  344.49  6085.9  346.76
#Mann= 7 ,-1 , 0
  3336.2     .16       0  3680.5     .16       0  4990.8     .03       0
  4996.8     .16       0  5439.2     .16       0    5613     .05       0
  5781.6     .16       0
Bank Sta=4965.4,5014.8
XS Rating Curve= 0 ,0
Exp/Cntr=0.3,0.1

Type RM Length L Ch R = 1 ,17332   ,547,547,547
BEGIN DESCRIPTION:
BROWNS CREEK 22.0
END DESCRIPTION:
XS GIS Cut Line= 4
      3627299.63     10541610.21      3626049.61     10540510.19
      3625749.61     10540210.19      3625211.61     10539924.77
#Sta/Elev= 30
  3360.9  347.05    3499  337.88  3601.7  330.22  3654.4  326.55  3729.1  321.82
  3809.8  315.59  3856.4  312.12  3965.2  306.01  3983.8  304.87  4111.1  298.52
  4120.6  297.57  4238.4  292.79  4293.1  290.84  4657.4  287.61  4947.8  290.34
  4969.6  283.64  4990.4  285.81  5009.2  283.31    5012  282.81  5015.2  283.31
  5040.2  285.03  5054.3  289.75  5110.9  293.54  5285.6  320.47  5339.8  326.47
  5480.4  334.83  5742.3  343.92    5852  344.44  5909.2  348.36  6059.3  346.78
#Mann= 20 ,-1 , 0
  3360.9     .16       0    3499     .05       0  3601.7     .16       0
  3654.4     .05       0  3729.1     .16       0  3809.8     .05       0
  3856.4     .16       0  3965.2     .05       0  3983.8     .16       0
  4111.1     .05       0  4120.6     .16       0  4238.4     .05       0
  4293.1     .12       0  5009.2     .07       0  5015.2     .12       0
  5285.6     .16       0  5339.8     .05       0  5742.3     .16       0
    5852     .05       0  5909.2     .16       0
Bank Sta=4947.8,5054.3
XS Rating Curve= 0 ,0
Exp/Cntr=0.3,0.1

Type RM Length L Ch R = 1 ,16785   ,582,582,582
BEGIN DESCRIPTION:
BROWNS CREEK 21.0
END DESCRIPTION:
XS GIS Cut Line= 3
      3627481.59     10541306.24      3626044.11     10539861.83
      3625766.81     10538773.41
#Sta/Elev= 30
  3437.9  336.41    3783   319.1  3860.8  317.12  3938.6  311.55  3945.6  308.63
  3952.7  310.37  4191.2  296.41  4341.6   291.2  4464.5  290.09  4794.2  286.88
    4978  288.88  4985.1  284.61  4996.2  283.38    4999  282.88  5002.2  283.38
  5013.3  289.01  5539.3   287.4  5718.3  290.71  5835.8  289.71  5922.8  295.63
  6025.5   295.7  6106.6   296.4  6189.4  297.64  6230.7   303.6    6272  305.89
  6416.5  324.72  6525.8  328.69  6540.3  326.22  6556.2  326.92  6598.9  327.83
#Mann= 8 ,-1 , 0
  3437.9     .05       0  4191.2     .16       0  4464.5     .12       0
  4996.2     .07       0  5002.2     .12       0  6025.5     .05       0
  6106.6     .12       0  6556.2     .16       0
Bank Sta=4978,5013.3
XS Rating Curve= 0 ,0
Exp/Cntr=0.3,0.1

Type RM Length L Ch R = 1 ,16203   ,1081,1081,1081
BEGIN DESCRIPTION:
BROWNS CREEK 20.0
END DESCRIPTION:
XS GIS Cut Line= 3
      3628058.01     10540368.78      3626699.61     10539760.19
      3625899.59     10538960.17
#Sta/Elev= 30
  3491.7  337.42  3746.3  320.66  3818.6  317.72  3960.4  310.32  4040.9  303.96
  4162.3  302.61  4255.1  297.17  4457.6  290.79  4525.4   289.5  4564.1  288.42
  4739.1  286.73  4925.4  288.66  4936.4  287.31  4945.2  283.52  4947.9  283.02
  4951.2  283.52  4958.3  288.58  4980.2  289.66  4994.3  284.96  5008.5  283.92
  5022.6  289.06  5220.6  286.58  5610.1  285.87  5751.5   285.9  5800.1  285.92
  5885.4   286.9  5934.7  291.55  6012.6  301.64  6069.3  312.11  6111.6  317.72
#Mann= 13 ,-1 , 0
  3491.7     .05       0  3818.6     .07       0  4457.6     .12       0
  4525.4     .07       0  4564.1     .12       0  4945.2     .07       0
  4951.2     .12       0  5610.1     .07       0  5751.5     .05       0
  5800.1     .12       0  5885.4     .16       0  5934.7     .12       0
  6069.3     .16       0
Bank Sta=4980.2,5022.6
XS Rating Curve= 0 ,0
Exp/Cntr=0.3,0.1

Type RM Length L Ch R = 1 ,15122   ,1131,1131,1131
BEGIN DESCRIPTION:
BROWNS CREEK 18.0
END DESCRIPTION:
XS GIS Cut Line= 3
      3627799.65     10539660.22      3626999.61     10538960.19
      3626199.63     10538160.21
#Sta/Elev= 30
  3915.8  326.84  4022.1  319.88  4092.9  316.94    4164  310.22  4213.4  307.78
  4241.9  304.76  4291.2  304.15  4333.9  299.06  4362.4  293.85  4447.4  286.72
  4673.7  284.18    4780  285.63  4858.8  285.04  4957.5  287.08  4971.7  284.97
  4975.5  281.03  4982.4  281.03    4990  279.11  4992.8  278.61    4996  279.11
  5021.3   285.8  5063.7   286.8  5120.3  285.27  5162.7  286.74  5304.1  296.14
  5417.3  300.62  5530.4  303.12  5643.5  308.54    5785  316.36  6110.2  342.39
#Mann= 3 ,-1 , 0
  3915.8     .05       0    4990     .03       0    4996     .05       0
Bank Sta=4957.5,5021.3
XS Rating Curve= 0 ,0
Exp/Cntr=0.3,0.1

Type RM Length L Ch R = 1 ,13991   ,397,397,397
BEGIN DESCRIPTION:
BROWNS CREEK 16.0
END DESCRIPTION:
XS GIS Cut Line= 3
      3628149.61     10539660.19      3627349.61     10538110.19
      3626549.61     10537560.19
#Sta/Elev= 30
  3231.7  338.48  3312.1  334.62  3378.5   328.8  3522.4   320.1    3528   318.2
  3566.7  317.83  3638.8  313.65  3906.9  295.44    4087  287.51  4278.3  282.65
  4419.5  281.52  4435.8  282.68  4502.5   281.7  4618.9  283.77  4840.9  282.96
    4979  284.31  4995.3  276.81  4998.1  276.31  5001.3  276.81  5019.3  283.51
  5126.8  283.99  5177.6  288.41  5219.5  290.49  5270.3  296.86  5285.1  296.66
  5400.7  305.16  5479.3  312.94  5643.7  326.29  5752.9  338.25  5946.8  360.52
#Mann= 4 ,-1 , 0
  3231.7     .05       0  4995.3     .03       0  5001.3     .05       0
  5752.9     .16       0
Bank Sta=4979,5019.3
XS Rating Curve= 0 ,0
Exp/Cntr=0.3,0.1

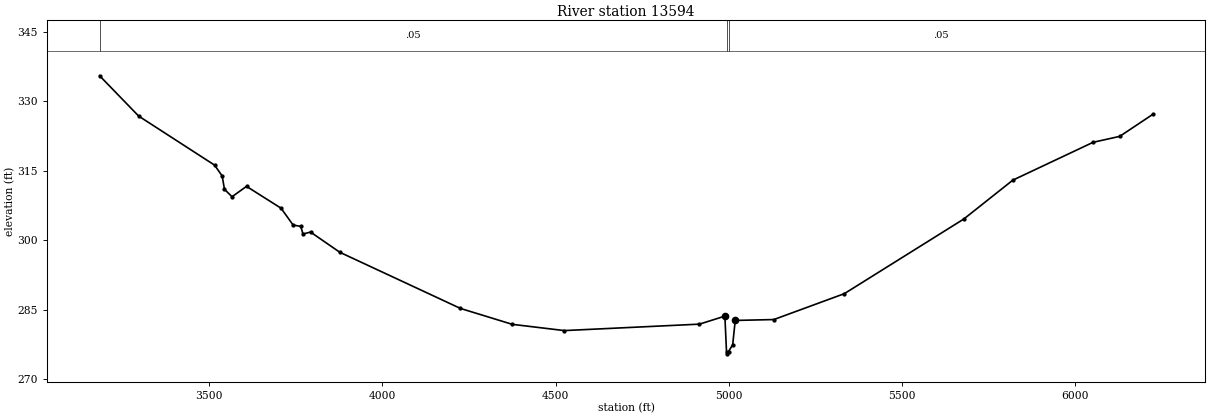
Type RM Length L Ch R = 1 ,13594   ,544,544,544
BEGIN DESCRIPTION:
BROWNS CREEK 15.0
END DESCRIPTION:
XS GIS Cut Line= 3
      3628620.49     10539438.21      3628113.56     10538861.83
      3627127.92     10536814.19
#Sta/Elev= 30
  3183.6  335.51  3296.3  326.81  3515.5  316.22  3537.3  313.89    3544     311
  3565.8   309.4  3607.6  311.64  3707.2  306.93  3742.3  303.28  3764.1  303.01
  3770.7  301.36  3792.5  301.77    3877  297.41  4225.2  285.29  4374.7  281.86
  4524.9  280.51  4915.1   281.9  4988.5  283.63  4993.2  275.99    4996  275.49
  4999.2  275.99  5011.1  277.48  5018.4   282.7  5129.8  282.89  5333.4  288.48
  5678.4   304.6  5819.7  312.98  6051.5  321.15  6128.3  322.43  6223.7  327.18
#Mann= 3 ,-1 , 0
  3183.6     .05       0  4993.2     .03       0  4999.2     .05       0
Bank Sta=4988.5,5018.4
XS Rating Curve= 0 ,0
Exp/Cntr=0.3,0.1