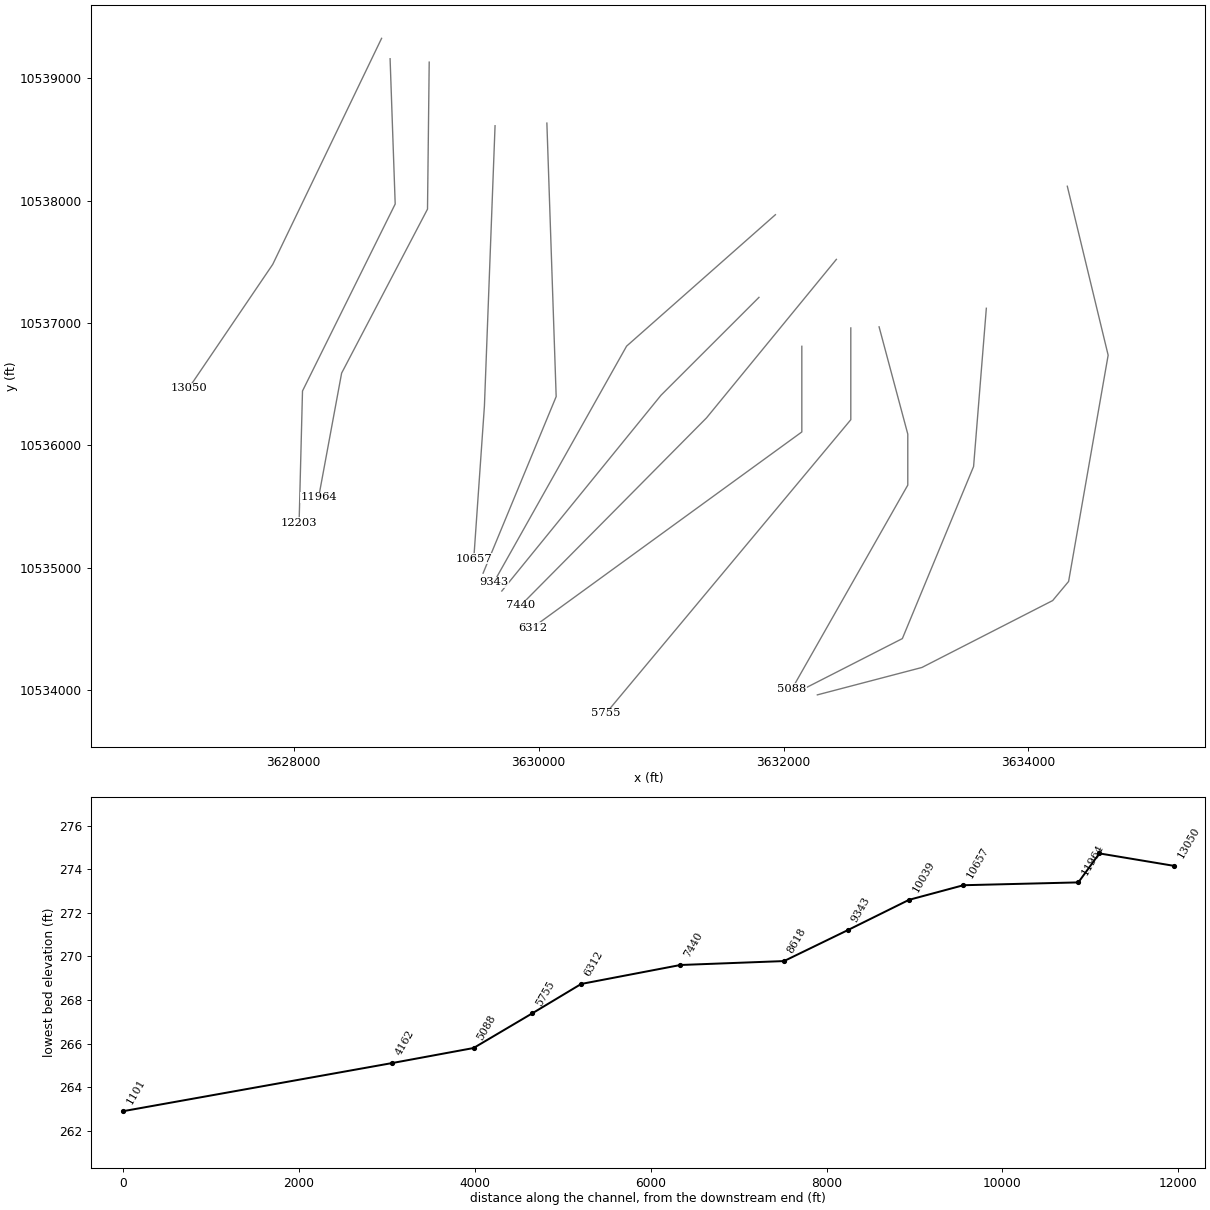
HEC-RAS study BROWNS CREEK.prj: BROWNS CREEK Base Level Engineering

--- BROWNS CREEK.g01 (geometry) --- (continued)

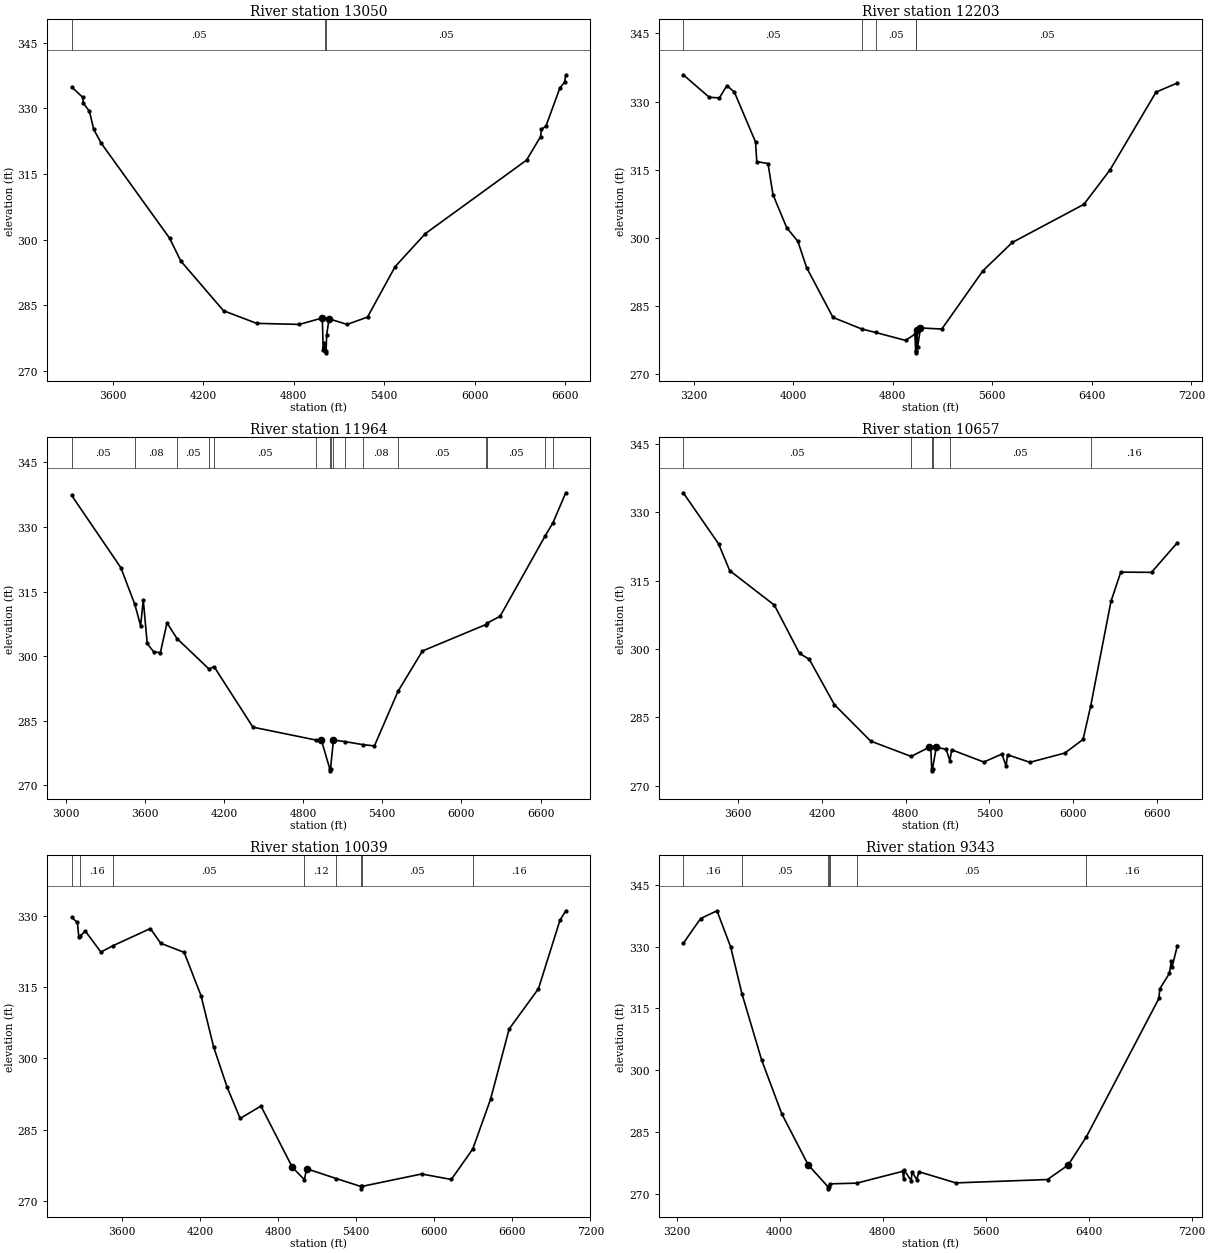
Type RM Length L Ch R = 1 ,13050   ,847,847,847
BEGIN DESCRIPTION:
BROWNS CREEK 14.0
END DESCRIPTION:
XS GIS Cut Line= 3
      3628717.73     10539327.11      3627828.83     10537479.88
      3627141.32     10536465.97
#Sta/Elev= 30
  3328.2  334.84  3400.7  332.52  3406.3  331.12    3446  329.29  3474.2  325.18
    3525  321.97  3977.6  300.31    4051  295.14  4334.7  283.77  4554.4  280.89
    4837  280.65  4989.4  282.12  4995.4  274.79    5001   276.3  5008.6  274.66
  5011.4  274.16  5014.6  274.66    5018  278.15  5033.8  281.93  5153.8  280.65
    5289  282.32  5471.6  293.82  5672.3  301.38  6343.1  318.15    6436  323.52
    6442  325.17  6471.9  325.94  6564.8  334.69  6594.7   335.9  6603.2  337.64
#Mann= 3 ,-1 , 0
  3328.2     .05       0  5008.6     .03       0  5014.6     .05       0
Bank Sta=4989.4,5033.8
XS Rating Curve= 0 ,0
Exp/Cntr=0.3,0.1

Type RM Length L Ch R = 1 ,12203   ,239,239,239
BEGIN DESCRIPTION:
BROWNS CREEK 13.0
END DESCRIPTION:
XS GIS Cut Line= 4
      3628787.17      10539160.4      3628828.83     10537972.94
      3628071.89     10536445.16      3628044.11     10535368.73
#Sta/Elev= 30
  3116.6   335.9  3325.4  330.94    3407  330.82    3467  333.53  3527.1  332.09
  3697.2  321.11  3707.2  316.79  3797.2  316.38  3837.3  309.54  3947.3  302.27
  4037.4  299.25  4107.4  293.49  4319.5  282.52  4550.8  279.97  4662.5  279.21
  4902.4  277.46  4977.5  278.83  4983.6  275.23  4986.3  274.73  4989.6  275.23
  4992.1  279.74  4999.8  276.08  5022.1   280.2  5193.9  279.97  5524.3  292.79
  5760.1  299.01  6334.9  307.39    6545  314.96  6915.1  332.09  7086.6  334.09
#Mann= 5 ,-1 , 0
  3116.6     .05       0  4550.8     .08       0  4662.5     .05       0
  4983.6     .03       0  4989.6     .05       0
Bank Sta=4992.1,5022.1
XS Rating Curve= 0 ,0
Exp/Cntr=0.3,0.1

Type RM Length L Ch R = 1 ,11964   ,1307,1307,1307
BEGIN DESCRIPTION:
BROWNS CREEK 12.0
END DESCRIPTION:
XS GIS Cut Line= 4
      3629106.61     10539132.65      3629092.72     10537931.27
      3628391.33     10536590.99      3628203.84     10535577.15
#Sta/Elev= 30
  3045.8  337.28  3418.3  320.53  3524.2  312.03  3568.3  307.06  3588.3  313.07
  3618.3  302.94  3668.3  300.97  3718.3  300.84  3768.3  307.72  3844.1  304.09
  4086.1  297.03  4125.2  297.56  4419.6  283.53  4894.9  280.56    4938  280.58
  5001.7   273.9  5004.4   273.4  5007.7   273.9  5030.1  280.55  5114.7  280.19
  5255.7  279.47  5340.4  279.18  5519.1  291.83  5704.3   301.2  6185.7  307.34
  6191.2   307.6  6293.3  309.26  6634.6  327.89  6693.7  330.94    6791   337.9
#Mann= 16 ,-1 , 0
  3045.8     .05       0  3524.2     .08       0  3844.1     .05       0
  4086.1     .08       0  4125.2     .05       0  4894.9     .12       0
  5001.7     .07       0  5007.7     .12       0  5030.1     .08       0
  5114.7     .05       0  5255.7     .08       0  5519.1     .05       0
  6185.7     .08       0  6191.2     .05       0  6634.6     .08       0
  6693.7     .05       0
Bank Sta=4938,5030.1
XS Rating Curve= 0 ,0
Exp/Cntr=0.3,0.1

Type RM Length L Ch R = 1 ,10657   ,618,618,618
BEGIN DESCRIPTION:
BROWNS CREEK 10.0
END DESCRIPTION:
XS GIS Cut Line= 3
      3629644.37     10538612.71      3629557.57      10536323.2
      3629470.76     10535075.37
#Sta/Elev= 30
    3206  334.25  3458.7  323.06  3538.8  317.18    3859  309.61  4039.1  299.03
  4109.2  297.73  4289.3  287.79  4549.5  279.79  4839.8  276.43  4969.8  278.46
  4979.8   278.5  4986.8  273.77  4989.6  273.27  4992.8  273.77  5019.8  278.44
  5089.9     278    5117   275.5  5129.9  277.89  5360.1   275.2  5490.2  276.95
  5520.2  274.32  5530.2   276.8  5690.6  275.14  5941.2  277.17  6071.6  280.15
  6126.5  287.48    6272  310.44  6342.2  316.85  6562.7   316.8    6748  323.32
#Mann= 6 ,-1 , 0
    3206     .05       0  4839.8     .12       0  4986.8     .07       0
  4992.8     .12       0    5117     .05       0  6126.5     .16       0
Bank Sta=4969.8,5019.8
XS Rating Curve= 0 ,0
Exp/Cntr=0.3,0.1

Type RM Length L Ch R = 1 ,10039   ,696,696,696
BEGIN DESCRIPTION:
BROWNS CREEK 9.0
END DESCRIPTION:
XS GIS Cut Line= 3
      3630067.55     10538634.42       3630143.5     10536399.15
      3629546.73     10534956.04
#Sta/Elev= 30
  3212.6  329.62  3256.9  328.55  3266.9  325.58  3276.3  325.65  3316.9  326.77
    3437  322.34  3532.7   323.7  3817.2  327.28  3897.2  324.18  4077.3  322.27
  4207.4  313.13  4303.2  302.46  4407.5  293.96  4507.6  287.39  4667.7  289.99
  4907.8  277.17  5001.8  274.51  5017.9  276.83  5247.8  274.75  5435.1   273.1
  5437.9   272.6  5441.1   273.1  5902.5  275.72  6130.9  274.57  6295.8  280.97
  6432.8  291.44  6575.2  306.16  6800.7  314.64  6966.2  329.03  7010.8  331.01
#Mann= 8 ,-1 , 0
  3212.6     .05       0  3276.3     .16       0  3532.7     .05       0
  5001.8     .12       0  5247.8     .05       0  5435.1     .03       0
  5441.1     .05       0  6295.8     .16       0
Bank Sta=4907.8,5017.9
XS Rating Curve= 0 ,0
Exp/Cntr=0.3,0.1

Type RM Length L Ch R = 1 ,9343    ,725,725,725
BEGIN DESCRIPTION:
BROWNS CREEK 8.0
END DESCRIPTION:
XS GIS Cut Line= 3
      3631933.85     10537885.68      3630718.59     10536811.48
      3629634.06     10534881.02
#Sta/Elev= 30
  3252.6  330.78  3387.1  336.79  3514.3  338.67  3620.5  329.89  3708.1  318.54
  3861.4  302.42  4017.9  289.37  4222.8  277.01  4376.2  271.71    4379  271.21
  4382.2  271.71    4393  272.42    4599  272.59  4956.3  275.46  4963.2  273.62
  4968.9  275.69  5022.5  273.17  5028.2  275.31  5065.9  273.45  5081.8  275.36
  5368.1  272.65  6080.4  273.47    6241  276.99    6383  283.88  6945.6  317.42
  6952.1  319.72  7026.6  323.46  7042.5   326.6  7048.2  325.11  7088.8  330.23
#Mann= 7 ,-1 , 0
  3252.6     .16       0  3708.1     .05       0  4376.2     .03       0
  4382.2     .05       0    4393     .12       0    4599     .05       0
    6383     .16       0
Bank Sta=4222.8,6241
XS Rating Curve= 0 ,0
Exp/Cntr=0.3,0.1

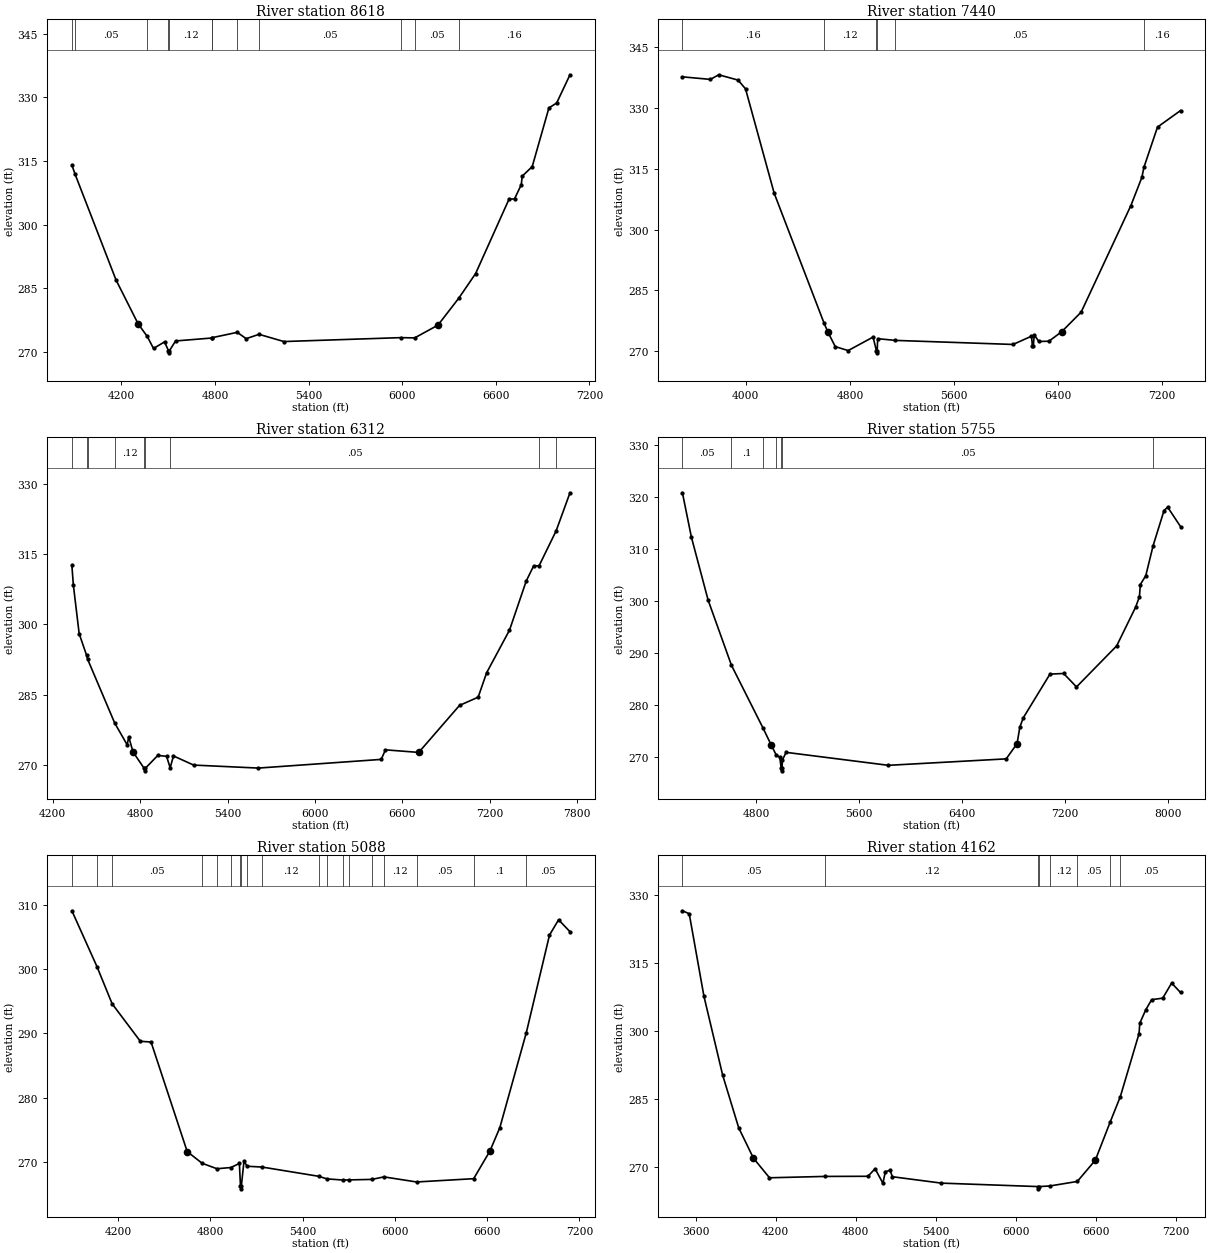
Type RM Length L Ch R = 1 ,8618    ,1178,1178,1178
BEGIN DESCRIPTION:
BROWNS CREEK 7.0
END DESCRIPTION:
XS GIS Cut Line= 3
      3631799.64     10537210.22      3630999.61     10536410.19
      3629699.59     10534810.16
#Sta/Elev= 30
  3883.1  314.03  3903.6  311.87    4166  286.96  4307.4  276.64  4366.2  273.65
  4406.4  270.82  4477.1  272.37  4502.4  270.29  4505.1  269.79  4508.4  270.29
  4547.8  272.59  4779.6  273.28  4783.4  273.37  4943.1  274.62  5000.4  273.13
  5082.8  274.15  5242.2  272.45  5989.7  273.37  6080.5  273.31  6229.9  276.32
  6363.9   282.7  6471.2  288.47  6685.3  305.99  6720.5  306.05  6763.6  309.37
  6770.1  311.41    6834  313.66    6941  327.48  6990.6  328.64  7076.1  335.29
#Mann= 12 ,-1 , 0
  3883.1     .16       0  3903.6     .05       0  4366.2     .12       0
  4502.4     .07       0  4508.4     .12       0  4779.6     .07       0
  4783.4     .05       0  4943.1     .12       0  5082.8     .05       0
  5989.7     .08       0  6080.5     .05       0  6363.9     .16       0
Bank Sta=4307.4,6229.9
XS Rating Curve= 0 ,0
Exp/Cntr=0.3,0.1

Type RM Length L Ch R = 1 ,7440    ,1128,1128,1128
BEGIN DESCRIPTION:
BROWNS CREEK 6.0
END DESCRIPTION:
XS GIS Cut Line= 3
      3632431.82     10537520.59      3631371.51     10536225.41
      3629855.52      10534694.3
#Sta/Elev= 30
  3512.2  337.74  3727.4  337.11  3791.3  338.25  3939.8  336.94  3997.3  334.78
  4217.6  309.01  4599.3  277.08  4629.6  274.79    4687  271.15  4786.1  270.17
  4977.7   273.5  5003.5  270.11  5006.2  269.61  5009.5  270.11  5012.9  273.11
    5149  272.68  6053.7  271.68  6195.2  273.72  6202.3  271.37  6209.3  271.28
  6216.4  274.04  6251.7  272.41  6329.6  272.48  6428.6  274.86    6577  279.66
  6958.9  305.94  7043.7  312.92  7059.7  315.43  7163.9  325.34  7340.7  329.41
#Mann= 6 ,-1 , 0
  3512.2     .16       0  4599.3     .12       0  5003.5     .07       0
  5009.5     .12       0    5149     .05       0  7059.7     .16       0
Bank Sta=4629.6,6428.6
XS Rating Curve= 0 ,0
Exp/Cntr=0.3,0.1

Type RM Length L Ch R = 1 ,6312    ,557,557,557
BEGIN DESCRIPTION:
BROWNS CREEK 4.0
END DESCRIPTION:
XS GIS Cut Line= 3
      3632149.61     10536810.19      3632149.61     10536110.19
       3629949.6     10534510.18
#Sta/Elev= 30
  4331.2  312.56  4341.2   308.4  4381.2     298  4432.2  293.38  4438.7  292.59
  4625.5  278.92  4711.2  274.27  4721.2  276.01  4751.2  272.76  4828.2  269.24
    4831  268.74  4834.2  269.24  4921.2  272.03  4981.2  271.84  5006.2  269.39
  5028.7  271.92  5167.2  269.97    5612  269.33  6455.1  271.18  6484.5  273.22
  6712.8  272.67    6993   282.7  7120.9  284.45  7179.2  289.67  7336.1  298.75
  7451.3  309.26  7501.5  312.43  7539.3  312.49  7656.4  319.94  7751.5  328.06
#Mann= 9 ,-1 , 0
  4331.2     .16       0  4432.2     .05       0  4438.7     .16       0
  4625.5     .12       0  4828.2     .07       0  4834.2     .12       0
  5006.2     .05       0  7539.3     .16       0  7656.4     .05       0
Bank Sta=4751.2,6712.8
XS Rating Curve= 0 ,0
Exp/Cntr=0.3,0.1

Type RM Length L Ch R = 1 ,5755    ,667,667,667
BEGIN DESCRIPTION:
BROWNS CREEK 3.0
END DESCRIPTION:
XS GIS Cut Line= 3
      3632549.61     10536960.19      3632549.61     10536210.19
      3630549.61     10533810.19
#Sta/Elev= 30
  4223.8   320.8  4293.8  312.27  4423.8  300.18  4605.2  287.67  4851.6  275.57
  4913.8  272.39    4953  270.45    4981  269.99  4992.3  267.89    4995  267.39
  4998.3  267.89  5001.8  269.49  5030.4  270.94  5825.8  268.45  6742.2  269.69
  6826.8  272.62  6848.3  275.81  6876.2  277.63  7082.6  285.97  7188.7  286.09
  7288.9  283.51  7601.3  291.39  7749.7  298.88  7778.3  300.84  7785.5  303.18
  7827.8  304.88  7885.2  310.67  7969.7  317.39  7998.3  318.03  8097.9  314.31
#Mann= 7 ,-1 , 0
  4223.8     .05       0  4605.2      .1       0  4851.6     .12       0
    4953     .05       0  4992.3     .03       0  4998.3     .05       0
  7885.2     .16       0
Bank Sta=4913.8,6826.8
XS Rating Curve= 0 ,0
Exp/Cntr=0.3,0.1

Type RM Length L Ch R = 1 ,5088    ,926,926,926
BEGIN DESCRIPTION:
BROWNS CREEK 2.0
END DESCRIPTION:
XS GIS Cut Line= 4
      3632780.62      10536969.2        3633015.     10536092.48
        3633015.     10535675.81      3632068.81     10534009.14
#Sta/Elev= 30
  3898.5   309.1  4061.8   300.4  4160.5  294.61  4343.8  288.78  4413.6  288.66
  4648.8   271.6  4746.1  269.78  4842.2  268.93  4932.9  269.12  4988.3  269.75
  4995.3   266.3    4998   265.8  5001.3   266.3  5018.3  270.11  5038.5  269.32
  5136.6  269.19  5505.3  267.75  5557.7  267.35  5662.4  267.17  5698.2  267.19
  5849.8  267.27    5929  267.66  6141.1  266.87  6512.5  267.38  6617.9  271.67
  6682.8  275.33  6855.2  290.13  7005.8  305.31    7065   307.7  7139.2  305.84
#Mann= 19 ,-1 , 0
  3898.5     .05       0  4061.8      .1       0  4160.5     .05       0
  4746.1     .07       0  4842.2     .12       0  4932.9     .05       0
  4995.3     .03       0  5001.3     .05       0  5038.5     .16       0
  5136.6     .12       0  5505.3     .05       0  5557.7     .12       0
  5662.4     .05       0  5698.2     .12       0  5849.8      .1       0
    5929     .12       0  6141.1     .05       0  6512.5      .1       0
  6855.2     .05       0
Bank Sta=4648.8,6617.9
XS Rating Curve= 0 ,0
Exp/Cntr=0.3,0.1

Type RM Length L Ch R = 1 ,4162    ,3061,3061,3061
BEGIN DESCRIPTION:
Mapping XS e0efb680
END DESCRIPTION:
XS GIS Cut Line= 4
      3633656.49     10537121.07      3633552.32     10535827.72
      3632970.73     10534421.47      3632155.12     10534004.99
#Sta/Elev= 30
  3500.4  326.46  3551.5  325.81  3661.8  307.61  3802.3  290.19  3922.6  278.57
    4033  271.88  4153.4  267.55  4569.9  267.85  4891.9  267.88  4945.2  269.55
  5003.8  266.34  5022.3  268.92    5057  269.17  5075.5  267.78  5442.6  266.37
  6166.6  265.61  6169.4  265.11  6172.6  265.61  6255.2  265.74  6461.6  266.74
  6596.7  271.43  6709.3  279.94  6784.5  285.48  6924.5  299.36  6930.1  301.64
  6974.5  304.59    7019  306.85  7102.2  307.18  7168.9  310.51  7235.5  308.43
#Mann= 8 ,-1 , 0
  3500.4     .05       0  4569.9     .12       0  6166.6     .07       0
  6172.6     .12       0  6255.2     .12       0  6461.6     .05       0
  6709.3      .1       0  6784.5     .05       0
Bank Sta=4033,6596.7
XS Rating Curve= 0 ,0
Exp/Cntr=0.3,0.1

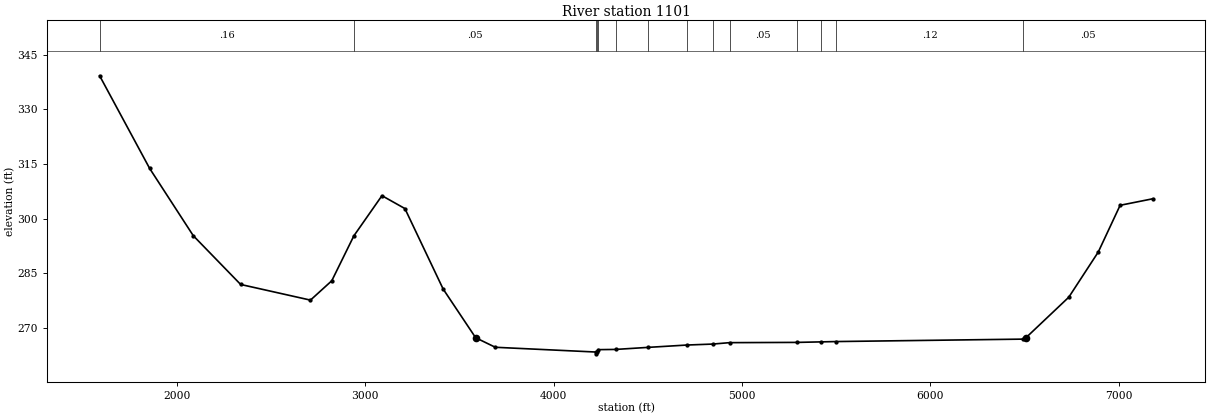
Type RM Length L Ch R = 1 ,1101    ,0,0,0
BEGIN DESCRIPTION:
BROWNS CREEK 1.0
END DESCRIPTION:
XS GIS Cut Line= 6
      3634317.74     10538118.24      3634651.28     10536737.44
      3634328.36     10534888.48      3634198.16     10534732.23
      3633130.45     10534185.36      3632276.31     10533961.41
#Sta/Elev= 30
  1589.7   339.2  1855.2  313.78    2087  295.31  2338.3  281.94    2709  277.64
  2822.2  282.95  2939.5  295.28  3088.6   306.3  3210.5  302.76  3413.5  280.68
  3586.1  267.32  3690.5   264.7  4222.6   263.4  4225.3   262.9  4228.6   263.4
  4236.8  264.05  4329.2  264.11  4500.6  264.67  4709.3  265.32  4844.5  265.58
    4934  265.97    5292  266.04  5418.3  266.18  5499.9  266.27  6492.8  266.94
  6505.6  267.22  6735.3  278.45  6891.7  290.84  7007.7  303.66    7181  305.45
#Mann= 14 ,-1 , 0
  1589.7     .16       0  2939.5     .05       0  4222.6     .03       0
  4228.6     .05       0  4236.8      .1       0  4329.2     .05       0
  4500.6     .16       0  4709.3     .05       0  4844.5     .12       0
    4934     .05       0    5292     .12       0  5418.3     .05       0
  5499.9     .12       0  6492.8     .05       0
Bank Sta=3586.1,6505.6
XS Rating Curve= 0 ,0
Exp/Cntr=0.3,0.1

Chan Stop Cuts=-1
Use User Specified Reach Order=0
Composite Channel Slope=5