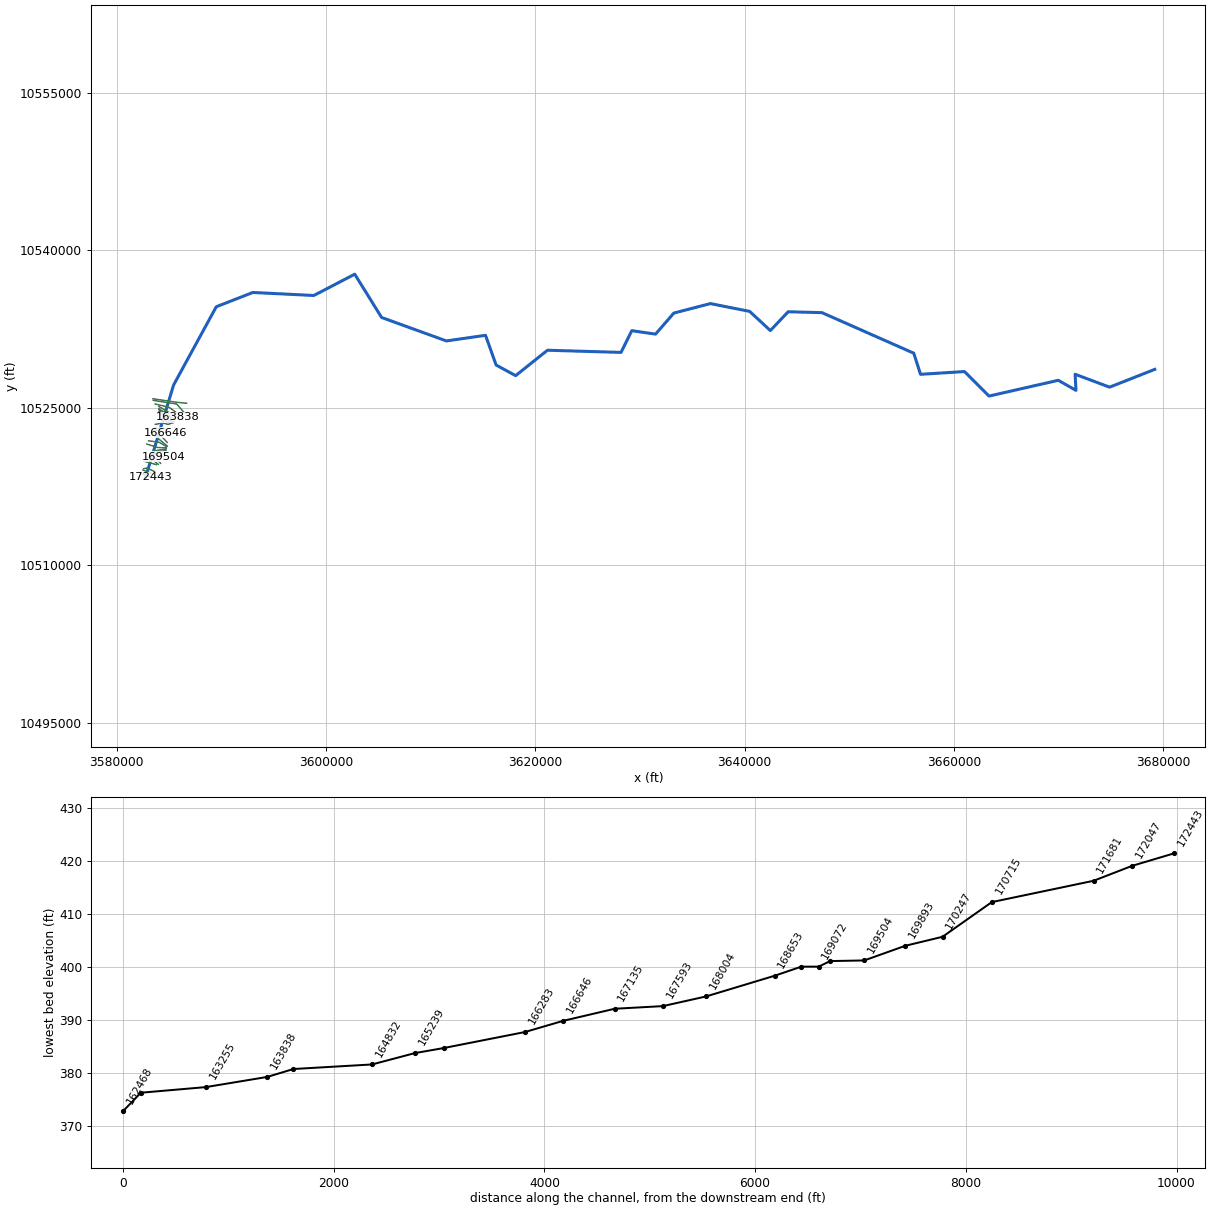
--- BUFFALO CREEK.prj (project) ---

Proj Title=BUFFALO CREEK Base Level Engineering
Current Plan=p01
Default Exp/Contr=0.3,0.1
English Units
Geom File=g01
Flow File=f01
Plan File=p01
Y Axis Title=Elevation
X Axis Title(PF)=Main Channel Distance
X Axis Title(XS)=Station
BEGIN DESCRIPTION:
BUFFALO CREEK
END DESCRIPTION:
DSS Export Rating Curves= 0
DSS Export Rating Curve Sorted= 0
DSS Export Volume Flow Curves= 0
DXF OffsetX= 0
DXF OffsetY= 0
DXF ScaleX= 1
DXF ScaleY= 10

--- BUFFALO CREEK.p01 (plan) ---

Plan Title=Multiple Run
Program Version=4.10
Short Identifier=Multiple
Geom File=g01
Flow File=f01
Subcritical Flow
K Sum by GR= 0
Std Step Tol= 0.01
Critical Tol= 0.01
Num of Std Step Trials= 20
Max Error Tol= 0.3
Flow Tol Ratio= 0.001
Split Flow NTrial= 30
Split Flow Tol= 0.02
Split Flow Ratio= 0.02
Log Output Level= 0
Friction Slope Method= 1
Unsteady Friction Slope Method= 2
Unsteady Bridges Friction Slope Method= 1
Parabolic Critical Depth
Global Vel Dist= 1 , 1 , 1
Global Log Level= 0
CheckData=True
Encroach Param=-1 ,0,0, 0
BEGIN DESCRIPTION:
Multiple Run
END DESCRIPTION:
Computation Interval=1HOUR
Output Interval=1HOUR
Run HTab= 0
Run UNet= 0
Run PostProcess= 0
Run WQNet= 0
UNET Theta= 1
UNET Theta Warmup= 1
UNET ZTol= 0.02
UNET ZSATol= 0.05
UNET MxIter= 20
UNET MaxInSteps= 0
UNET DtIC= 0
UNET DtMin= 0
UNET MaxCRTS= 20
UNET WFStab= 2
UNET SFStab= 1
UNET WFX= 1
UNET SFX= 1
UNET DSS MLevel= 4
UNET DZMax Abort= 100
UNET Convert EG Bridges= 0
UNET Use Existing IB Tables=-1
UNET Froude Reduction=False
UNET Froude Limit= 1
UNET Froude Power= 10
UNET Time Slicing=0,0, 5
UNET Junction Losses=0
Instantaneous Interval=1HOUR
Write IC File= 0
Write IC File at Sim End=0
Echo Input=False
Echo Parameters=False
Echo Output=False
Write Detailed= 0
WQ AD Non Conservative
WQ ULTIMATE=-1
WQ Max Comp Step=1HOUR
WQ Output Interval=15MIN
WQ Output Selected Increments= 0
WQ Output face flow=0
WQ Output face velocity=0
WQ Output face area=0
WQ Output face dispersion=0
WQ Output cell volume=0
WQ Output cell surface area=0
WQ Output cell continuity=0
WQ Output cumulative cell continuity=0
WQ Output face conc=0
WQ Output face dconc_dx=0
WQ Output face courant=0
WQ Output face peclet=0
WQ Output face adv mass=0
WQ Output face disp mass=0
WQ Output cell mass=0
WQ Output cell source sink temp=0
WQ Output cell source sink nsm=0
WQ Output MaxMinRange=-1
WQ Daily Max Min Mean=-1
WQ Daily Range=0
WQ Daily Time=0
WQ Create Restart=0
WQ Fixed Restart=0
WQ System Summary=0
WQ Use Fixed Temperature=0
Sorting and Armoring Iterations= 10
XS Update Threshold= 0.02
Hydraulics Update Threshold= 0.02
Energy Slope Method= 1
Volume Change Method= 0
XS Weighting Method= 0
Number of US Weighted Cross Sections= 1
Number of DS Weighted Cross Sections= 1
Upstream XS Weight=0.25
Main XS Weight=0.5
Downstream XS Weight=0.25
Number of DS XS's Weighted with US Boundary= 1
Upstream Boundary Weight= 1
Weight of XSs Associated with US Boundary= 0
Number of US XS's Weighted with DS Boundary= 1
Downstream Boundary Weight= 0.5
Weight of XSs Associated with DS Boundary= 0.5
Sediment Output Level= 4
Mass or Volume Output= 0
Output Increment Type= 1
Profile and TS Output Increment= 10
XS Output Flag= 0
XS Output Increment= 10
Disregard all LS=0
Disregard all Conn=0
Disregard all Breaches=0
Disregard all Pumps=0

--- BUFFALO CREEK.f01 (steady flow) ---

Flow Title=Multiple
Program Version=4.10
Number of Profiles= 7
Profile Names=10-year,25-year,50-year,1pct_min,100-year,1pct_plu,500-year
River Rch & RM=BUFFALO CREEK,Reach-1         ,172443
    1430    2005    2489    2254    3048    4122    4555
River Rch & RM=BUFFALO CREEK,Reach-1         ,165514
    2245    3225    4070    3739    5057    6839    7789
River Rch & RM=BUFFALO CREEK,Reach-1         ,165239
    2985    4343    5527    5115    6918    9355   10816
River Rch & RM=BUFFALO CREEK,Reach-1         ,164086
    2985    4343    5527    5115    6918    9355   10816
River Rch & RM=BUFFALO CREEK,Reach-1         ,162468
    3068    4460    5671    5244    7092    9591   11069
River Rch & RM=BUFFALO CREEK,Reach-1         ,157702
    3545    5169    6586    6098    8247   11153   12904
River Rch & RM=BUFFALO CREEK,Reach-1         ,153441
    4104    5993    7643    7078    9573   12946   14986
River Rch & RM=BUFFALO CREEK,Reach-1         ,153000
    4104    5993    7643    7078    9573   12946   14986
River Rch & RM=BUFFALO CREEK,Reach-1         ,149139
    7174   10702   13847   12994   17573   23765   28240
River Rch & RM=BUFFALO CREEK,Reach-1         ,144465
    7174   10702   13847   12994   17573   23765   28240
River Rch & RM=BUFFALO CREEK,Reach-1         ,143913
    7174   10702   13847   12994   17573   23765   28240
River Rch & RM=BUFFALO CREEK,Reach-1         ,139462
    7405   11040   14278   13391   18109   24491   29068
River Rch & RM=BUFFALO CREEK,Reach-1         ,135672
   12133   18156   23547   22113   29905   40443   48093
River Rch & RM=BUFFALO CREEK,Reach-1         ,134200
   12133   18156   23547   22113   29905   40443   48093
River Rch & RM=BUFFALO CREEK,Reach-1         ,132042
   11811   17618   22797   21359   28885   39064   46237
River Rch & RM=BUFFALO CREEK,Reach-1         ,126272
   11853   17640   22790   21315   28827   38985   45984
River Rch & RM=BUFFALO CREEK,Reach-1         ,119869
   12475   18584   24027   22487   30411   41128   48571
River Rch & RM=BUFFALO CREEK,Reach-1         ,118595
   12475   18584   24027   22487   30411   41128   48571
River Rch & RM=BUFFALO CREEK,Reach-1         ,113863
   12303   18289   23611   22064   29839   40353   47510
River Rch & RM=BUFFALO CREEK,Reach-1         ,111119
   17575   26309   34138   32045   43338   58609   69600
River Rch & RM=BUFFALO CREEK,Reach-1         ,109213
   17575   26309   34138   32045   43338   58609   69600
River Rch & RM=BUFFALO CREEK,Reach-1         ,101512
   17827   26596   34432   32242   43604   58969   69679
River Rch & RM=BUFFALO CREEK,Reach-1         ,99992
   17827   26596   34432   32242   43604   58969   69679
River Rch & RM=BUFFALO CREEK,Reach-1         ,91053
   17827   26596   34432   32242   43604   58969   69679
River Rch & RM=BUFFALO CREEK,Reach-1         ,84746
   17864   26600   34391   32159   43491   58817   69298
River Rch & RM=BUFFALO CREEK,Reach-1         ,75093
   21898   32695   42363   39692   53678   72593   85832
River Rch & RM=BUFFALO CREEK,Reach-1         ,71946
   21627   32243   41733   39059   52822   71436   84282
River Rch & RM=BUFFALO CREEK,Reach-1         ,69702
   21609   32168   41595   38888   52591   71124   83731
River Rch & RM=BUFFALO CREEK,Reach-1         ,60581
   21609   32168   41595   38888   52591   71124   83731
River Rch & RM=BUFFALO CREEK,Reach-1         ,59151
   21729   32345   41823   39101   52879   71513   84185
River Rch & RM=BUFFALO CREEK,Reach-1         ,53734
   21217   31460   40573   37839   51173   69206   81092
River Rch & RM=BUFFALO CREEK,Reach-1         ,47156
   21217   31460   40573   37839   51173   69206   81092
River Rch & RM=BUFFALO CREEK,Reach-1         ,43458
   21119   31286   40325   37586   50831   68743   80458
River Rch & RM=BUFFALO CREEK,Reach-1         ,37714
   21015   31114   40089   37357   50522   68325   79939
River Rch & RM=BUFFALO CREEK,Reach-1         ,34089
   21015   31114   40089   37357   50522   68325   79939
River Rch & RM=BUFFALO CREEK,Reach-1         ,32219
   23751   35194   45387   42338   57257   77433   90778
River Rch & RM=BUFFALO CREEK,Reach-1         ,28480
   23365   34558   44509   41465   56076   75837   88680
River Rch & RM=BUFFALO CREEK,Reach-1         ,19521
   23318   34474   44390   41346   55916   75620   88395
River Rch & RM=BUFFALO CREEK,Reach-1         ,18260
   23058   34051   43812   40780   55150   74583   87070
River Rch & RM=BUFFALO CREEK,Reach-1         ,14676
   22571   33250   42709   39685   53669   72581   84445
Boundary for River Rch & Prof#=BUFFALO CREEK,Reach-1         , 1
Up Type= 0
Dn Type= 3
Dn Slope=0.0023
Boundary for River Rch & Prof#=BUFFALO CREEK,Reach-1         , 2
Up Type= 0
Dn Type= 3
Dn Slope=0.0023
Boundary for River Rch & Prof#=BUFFALO CREEK,Reach-1         , 3
Up Type= 0
Dn Type= 3
Dn Slope=0.0023
Boundary for River Rch & Prof#=BUFFALO CREEK,Reach-1         , 4
Up Type= 0
Dn Type= 3
Dn Slope=0.0023
Boundary for River Rch & Prof#=BUFFALO CREEK,Reach-1         , 5
Up Type= 0
Dn Type= 3
Dn Slope=0.0023
Boundary for River Rch & Prof#=BUFFALO CREEK,Reach-1         , 6
Up Type= 0
Dn Type= 3
Dn Slope=0.0023
Boundary for River Rch & Prof#=BUFFALO CREEK,Reach-1         , 7
Up Type= 0
Dn Type= 3
Dn Slope=0.0023
DSS Import GetInterval= 0
DSS Import GetPeak= 0
DSS Import FillOption= 0

--- BUFFALO CREEK.g01 (geometry) ---

Geom Title=Existing Conditions
Program Version=4.10

River Reach=BUFFALO CREEK   ,Reach-1
Reach XY= 30
        3582772.       10518375.        3585453.       10527189.
       3589528.5       10534639.        3593020.       10535999.
       3598849.5       10535712.       3602756.5       10537740.
      3605323.25       10533617.      3611510.75       10531383.
       3615247.5       10531917.       3616259.5       10529090.
      3618124.75       10528077.       3621165.5       10530498.
      3628190.25       10530291.      3629219.25       10532361.
        3631488.       10532033.      3633236.75       10534037.
       3636724.5       10534941.      3640478.25       10534197.
      3642454.75       10532370.      3644157.25       10534163.
      3647388.75       10534077.       3656152.5       10530215.
        3656801.       10528204.      3660998.25       10528467.
      3663339.75       10526131.        3669959.       10527634.
       3671648.5       10526676.      3671564.25       10528211.
       3674859.5       10526980.        3679176.       10528677.

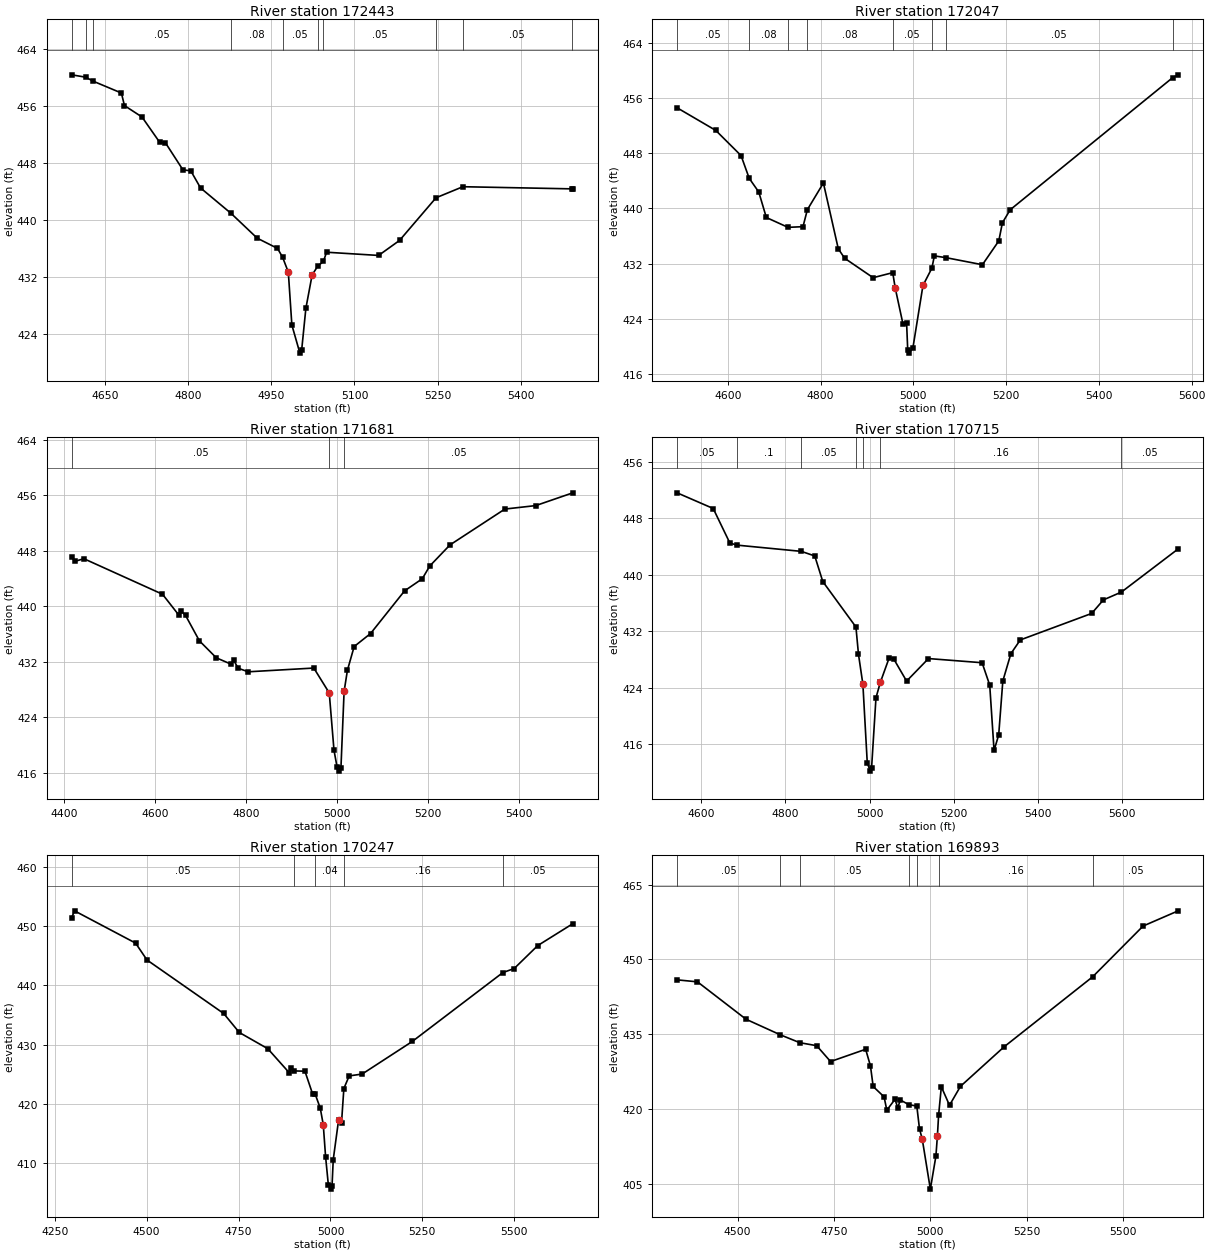
Type RM Length L Ch R = 1 ,172443  ,396,396,396
BEGIN DESCRIPTION:
BUFFALO CREEK 166.0
END DESCRIPTION:
XS GIS Cut Line= 2
       3582439.5     10518704.12      3583295.68      10518411.5
#Sta/Elev= 30
  4589.5  460.36  4614.7  460.03  4628.5  459.46  4679.2  457.81  4684.7  456.05
  4716.4  454.45  4748.1  450.93  4758.7  450.84  4790.4  447.03  4804.4  446.92
  4822.1  444.51  4877.4  440.93  4924.4  437.47    4961  436.04  4970.1  434.83
  4980.6  432.71    4987   425.3  5001.5  421.36  5004.8  421.86  5012.3  427.64
  5023.6  432.32  5033.5  433.52    5044  434.23  5049.7   435.5  5143.6  435.05
  5181.4  437.15  5247.3  443.13  5295.8  444.68  5492.3  444.38  5494.3  444.39
#Mann= 10 ,-1 , 0
  4589.5     .05       0  4614.7     .08       0  4628.5     .05       0
  4877.4     .08       0  4970.1     .05       0  5033.5     .08       0
    5044     .05       0  5247.3     .08       0  5295.8     .05       0
  5492.3      .1       0
Bank Sta=4980.6,5023.6
XS Rating Curve= 0 ,0
Exp/Cntr=0.3,0.1

Type RM Length L Ch R = 1 ,172047  ,366,366,366
BEGIN DESCRIPTION:
BUFFALO CREEK 165.0
END DESCRIPTION:
XS GIS Cut Line= 2
      3582515.42     10519094.76      3583523.16     10518704.67
#Sta/Elev= 30
  4490.4   454.6  4573.8  451.32  4628.3  447.67  4645.9  444.37  4666.5  442.39
  4682.8  438.69  4729.6  437.26  4761.9  437.36  4771.3  439.82  4805.9  443.69
    4838  434.15  4851.7  432.78  4913.1  429.96  4955.4  430.69  4960.7  428.49
  4977.4  423.27  4985.3  423.42  4987.7  419.52  4990.4  419.02  4998.9  419.77
  5020.6  428.83  5039.8  431.34  5045.2  433.12  5069.8  432.87  5148.8  431.84
  5184.1  435.29  5191.9  437.92  5208.7  439.81  5558.9  458.96    5571  459.38
#Mann= 8 ,-1 , 0
  4490.4     .05       0  4645.9     .08       0  4729.6      .1       0
  4771.3     .08       0  4955.4     .05       0  5039.8     .08       0
  5069.8     .05       0  5558.9      .1       0
Bank Sta=4960.7,5020.6
XS Rating Curve= 0 ,0
Exp/Cntr=0.3,0.1

Type RM Length L Ch R = 1 ,171681  ,966,966,966
BEGIN DESCRIPTION:
BUFFALO CREEK 164.0
END DESCRIPTION:
XS GIS Cut Line= 3
      3582613.15     10519224.96      3582927.78     10519279.21
       3583633.1     10518942.83
#Sta/Elev= 30
  4417.5  447.12  4424.1  446.44  4444.3  446.82  4616.9   441.7  4653.3  438.65
  4658.4  439.24  4667.6  438.64    4698  434.98  4735.2  432.53  4767.9  431.61
  4773.5  432.16  4783.1  431.03  4805.3  430.52  4949.3  431.06  4983.2  427.47
  4993.6  419.21  5000.4  416.79  5005.7   416.2  5008.9   416.7  5015.8  427.68
  5023.1  430.74  5037.9  434.16    5074  436.04  5148.7  442.19  5187.5  443.93
  5204.1  445.78  5248.4  448.81    5369  453.98  5436.8  454.48  5518.2  456.32
#Mann= 3 , 0 , 0
  4417.5     .05       0  4983.2     .04       0  5015.8     .05       0
Bank Sta=4983.2,5015.8
XS Rating Curve= 0 ,0
Exp/Cntr=0.3,0.1

Type RM Length L Ch R = 1 ,170715  ,468,468,468
BEGIN DESCRIPTION:
BUFFALO CREEK 163.0
END DESCRIPTION:
XS GIS Cut Line= 2
      3582664.81     10519918.95      3583810.61     10519599.52
#Sta/Elev= 30
  4543.1  451.59  4628.8  449.37  4668.2   444.5  4684.2  444.19    4838   443.3
  4869.9  442.65  4888.9  439.03  4967.6  432.59  4973.7  428.71  4984.1  424.49
  4994.5  413.36  5001.6  412.18  5004.8  412.68  5015.2  422.57  5025.6  424.76
  5046.4   428.2  5056.8  428.12  5087.9  424.93  5139.8  428.12  5267.1  427.53
  5285.2  424.36  5295.5  415.11  5306.5   417.3  5316.3  424.94  5335.5  428.82
  5357.8  430.76  5527.2  434.51  5555.1  436.43  5597.9  437.54  5732.6  443.65
#Mann= 7 ,-1 , 0
  4543.1     .05       0  4684.2      .1       0    4838     .05       0
  4967.6     .04       0  4984.1     .05       0  5025.6     .16       0
  5597.9     .05       0
#XS Ineff= 1 ,-1
 5149.32  5448.4  427.02
Permanent Ineff=
       F
Bank Sta=4984.1,5025.6
XS Rating Curve= 0 ,0
Exp/Cntr=0.3,0.1

Type RM Length L Ch R = 1 ,170247  ,354,354,354
BEGIN DESCRIPTION:
BUFFALO CREEK 162.0
END DESCRIPTION:
XS GIS Cut Line= 3
      3582852.27     10520335.63      3583227.26     10520231.47
      3583991.13     10519627.31
#Sta/Elev= 30
  4296.2  451.43  4303.8  452.56  4469.9  447.12    4501  444.27  4709.6  435.25
  4752.1  432.05  4829.7  429.31  4887.5  425.29  4893.9  426.05  4902.2  425.57
  4930.6  425.52  4951.6  421.66    4958  421.74  4972.4  419.27  4980.5  416.48
  4986.8   411.1  4994.4  406.28    5001  405.64  5004.3  406.14  5007.6  410.61
  5022.1  417.26  5030.1   416.8  5036.5   422.6    5051  424.73  5086.2  425.04
  5222.5  430.53    5469  442.15  5499.8  442.83  5563.9   446.7  5659.3  450.39
#Mann= 5 ,-1 , 0
  4296.2     .05       0  4902.2     .16       0    4958     .04       0
  5036.5     .16       0    5469     .05       0
Bank Sta=4980.5,5022.1
XS Rating Curve= 0 ,0
Exp/Cntr=0.3,0.1

Type RM Length L Ch R = 1 ,169893  ,389,389,389
BEGIN DESCRIPTION:
BUFFALO CREEK 161.0
END DESCRIPTION:
XS GIS Cut Line= 3
      3583213.39     10520537.01      3583636.98     10520300.91
      3584213.03     10519724.86
#Sta/Elev= 30
  4343.1   445.9    4396   445.5  4521.9     438  4611.1  434.87  4661.3   433.3
  4705.1   432.7  4741.1  429.52  4832.1  431.98  4844.6  428.64  4851.6  424.52
  4879.9  422.44    4887  419.77  4908.2  421.95  4915.3  420.28  4922.3  421.81
  4943.6  420.89  4964.8  420.59  4971.8  415.99  4978.9  413.98  4999.9  403.94
  5014.3  410.55 5018.18  414.57  5021.3  418.74  5028.4  424.46  5049.6  420.75
  5077.9  424.54    5191  432.46  5420.7   446.5  5551.7  456.69  5642.7  459.74
#Mann= 7 ,-1 , 0
  4343.1     .05       0  4611.1     .08       0  4661.3     .05       0
  4943.6     .16       0  4964.8     .04       0  5021.3     .16       0
  5420.7     .05       0
Bank Sta=4978.9,5018.18
XS Rating Curve= 0 ,0
Exp/Cntr=0.3,0.1

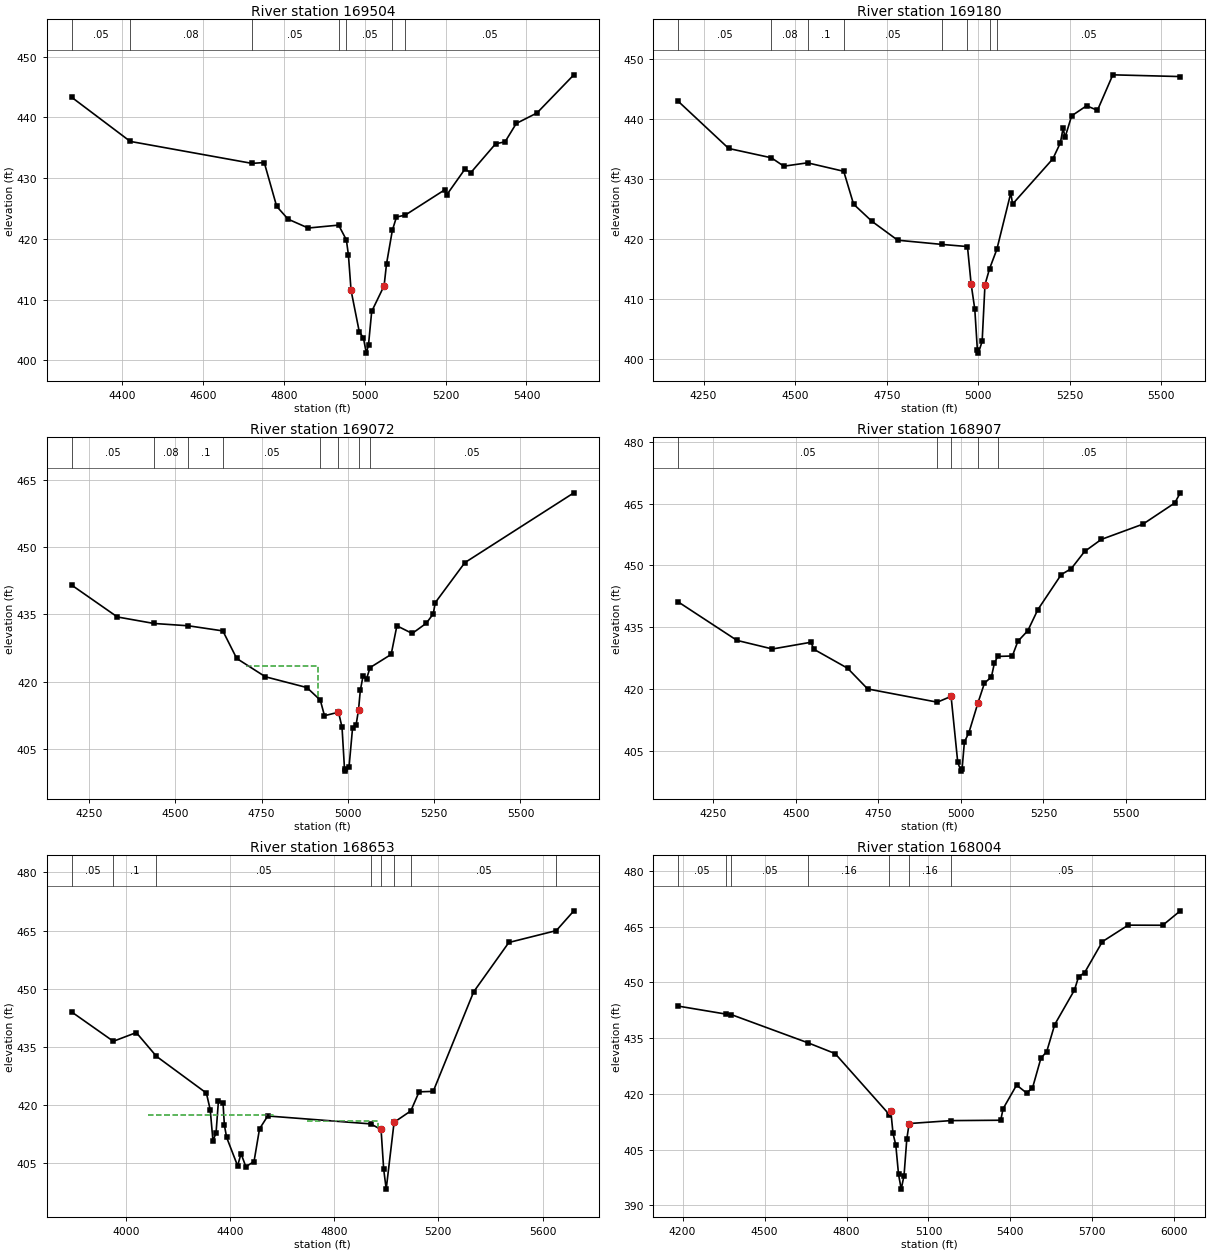
Type RM Length L Ch R = 1 ,169504  ,324,324,324
BEGIN DESCRIPTION:
BUFFALO CREEK 160.0
END DESCRIPTION:
XS GIS Cut Line= 2
      3583303.67     10520606.46       3584518.9     10520349.53
#Sta/Elev= 30
  4275.1  443.32  4419.8  436.06  4720.9  432.44  4751.3  432.58    4782  425.36
  4810.3  423.25    4860  421.79  4935.3  422.27  4954.4  419.84  4959.5  417.38
    4966  411.53  4986.4  404.69  4996.6  403.71  5003.8  401.18  5009.2  402.55
  5017.1  408.05  5047.8  412.28  5053.8   415.9  5068.2  421.41  5078.4   423.6
  5100.1  423.92  5197.9  428.09    5203  427.28  5247.6  431.48  5262.4  430.92
  5323.7  435.67    5347  435.99  5374.8  439.02  5425.9  440.74  5517.2  447.03
#Mann= 7 ,-1 , 0
  4275.1     .05       0  4419.8     .08       0  4720.9     .05       0
  4935.3     .16       0  4954.4     .05       0  5068.2     .16       0
  5100.1     .05       0
Bank Sta=4966,5047.8
XS Rating Curve= 0 ,0
Exp/Cntr=0.3,0.1

Type RM Length L Ch R = 1 ,169180  ,108,108,108
BEGIN DESCRIPTION:
Mapping XS fb611fe9
END DESCRIPTION:
XS GIS Cut Line= 3
      3583282.22     10520659.75      3584171.09     10520729.19
      3584639.82      10520628.5
#Sta/Elev= 30
  4180.7  442.98  4318.5  435.13  4434.9  433.58    4469  432.18  4533.7  432.74
  4632.6  431.33  4659.5  425.86  4709.7     423  4779.9  419.86  4902.1  419.15
  4970.5   418.8  4980.5  412.56  4990.5  408.37  4997.6  401.56  5000.3  401.06
  5010.6  403.04  5018.3  412.45  5030.7  415.09  5050.7  418.33  5088.7   427.7
  5093.8  425.88  5203.7  433.41  5224.2  436.07  5231.7  438.54  5236.9  436.96
  5254.9  440.56  5295.8  442.24  5325.4  441.48  5367.4  447.39  5551.7   447.1
#Mann= 8 ,-1 , 0
  4180.7     .05       0  4434.9     .08       0  4533.7      .1       0
  4632.6     .05       0  4902.1     .16       0  4970.5     .05       0
  5030.7     .16       0  5050.7     .05       0
Bank Sta=4980.5,5018.3
XS Rating Curve= 0 ,0
Exp/Cntr=0.3,0.1

Type RM Length L Ch R = 1 ,169072  ,165,165,165
BEGIN DESCRIPTION:
Mapping XS 06ee0776
END DESCRIPTION:
XS GIS Cut Line= 2
      3583299.61     10520684.06      3584730.17     10520947.95
#Sta/Elev= 30
  4199.9  441.53  4332.1  434.43    4438  432.98  4537.8  432.46  4637.6  431.32
  4677.8  425.17  4760.8  421.08  4881.2  418.67    4920  415.86  4932.1  412.38
  4972.7  413.17  4982.9  409.84  4990.1  400.51  4992.8  400.01  5003.2  400.89
  5013.4   409.6  5023.6  410.28  5030.8  413.73  5035.9  418.03  5043.9  421.26
  5054.1  420.66  5064.2  423.13  5125.3  426.07  5141.9  432.46  5186.3  430.75
  5226.9  433.02  5247.3  435.12  5252.9  437.61  5338.8  446.56  5654.6  462.15
#Mann= 8 ,-1 , 0
  4199.9     .05       0    4438     .08       0  4537.8      .1       0
  4637.6     .05       0    4920     .16       0  4972.7     .05       0
  5030.8     .16       0  5064.2     .05       0
#XS Ineff= 1 ,-1
 4705.68  4913.3 423.567
Permanent Ineff=
       F
Bank Sta=4972.7,5030.8
XS Rating Curve= 0 ,0
Exp/Cntr=0.3,0.1

Type RM Length L Ch R = 1 ,168907  ,254,254,254
BEGIN DESCRIPTION:
BUFFALO CREEK 159.0
END DESCRIPTION:
XS GIS Cut Line= 3
       3583296.7     10520710.63      3583657.82     10520925.91
      3584746.36     10521092.31
#Sta/Elev= 30
  4143.3  441.14  4321.3  431.79  4428.8   429.7  4545.6  431.34  4554.2  429.64
  4656.6  425.02  4717.3  419.99  4928.5  416.77  4970.2  418.18  4990.4  402.14
  5000.3  400.01  5003.5  400.51  5010.6  407.12    5024  409.31  5051.1  416.46
  5071.3  421.39  5092.5  422.92  5101.7  426.37  5111.8  427.89  5155.9     428
  5172.5  431.56  5202.8  434.16  5233.2  439.27    5304  447.78  5334.4  449.23
  5374.8   453.4  5425.4  456.33  5551.7  460.05    5648  465.19  5664.9  467.66
#Mann= 5 ,-1 , 0
  4143.3     .05       0  4928.5     .16       0  4970.2     .05       0
  5051.1     .16       0  5111.8     .05       0
Bank Sta=4970.2,5051.1
XS Rating Curve= 0 ,0
Exp/Cntr=0.3,0.1

Type RM Length L Ch R = 1 ,168653  ,649,649,649
BEGIN DESCRIPTION:
BUFFALO CREEK 158.0
END DESCRIPTION:
XS GIS Cut Line= 3
      3582893.97     10521564.79      3583900.87     10521238.41
       3584768.9     10521196.75
#Sta/Elev= 30
  3792.6  443.98  3952.2  436.43  4040.3  438.68  4117.7  432.55  4309.3  423.08
  4324.1  418.79  4334.7  410.73  4346.5  412.82  4355.7  421.08  4373.2   420.6
  4378.5  414.78  4387.2  411.62  4429.3   404.3  4442.5  407.46  4460.8  404.07
  4492.3  405.41  4513.4  413.84  4544.9  417.16  4939.9  415.12    4980  413.68
    4990  403.47  4999.7  398.29    5030  415.53  5094.2  418.47    5126  423.39
  5180.2  423.51  5335.4  449.18  5470.5  461.92  5652.8  464.99  5720.1  470.09
#Mann= 8 ,-1 , 0
  3792.6     .05       0  3952.2      .1       0  4117.7     .05       0
  4939.9     .16       0    4980     .05       0    5030     .16       0
  5094.2     .05       0  5652.8      .1       0
#XS Ineff= 2 ,-1
 4085.23 4566.76  417.48 4696.26 4969.52   415.9
Permanent Ineff=
       F       F
Bank Sta=4980,5030
XS Rating Curve= 0 ,0
Exp/Cntr=0.3,0.1

Type RM Length L Ch R = 1 ,168004  ,411,411,411
BEGIN DESCRIPTION:
BUFFALO CREEK 157.0
END DESCRIPTION:
XS GIS Cut Line= 3
      3583060.61     10521870.35      3584074.48     10521731.47
      3584774.87     10521315.39
#Sta/Elev= 30
    4184  443.63  4357.9  441.49  4378.9  441.33  4660.7  433.71  4758.3  430.86
    4957  414.43    4962  415.54  4970.3  409.38  4980.4  406.28  4990.5  398.35
  5000.3   394.4  5010.6  398.05  5020.7  407.83  5029.2  412.04    5182  412.83
  5364.5  412.93  5373.3  416.04  5422.7  422.39    5459  420.28  5480.8  421.58
  5511.6   429.6    5533  431.41  5562.2  438.66  5634.3  447.93  5649.9  451.58
  5671.4   452.6  5736.7  460.97  5831.1  465.41  5957.7  465.38    6022  469.26
#Mann= 7 ,-1 , 0
    4184     .05       0  4357.9     .08       0  4378.9     .05       0
  4660.7     .16       0    4957     .05       0  5029.2     .16       0
    5182     .05       0
Bank Sta=4962,5029.2
XS Rating Curve= 0 ,0
Exp/Cntr=0.3,0.1

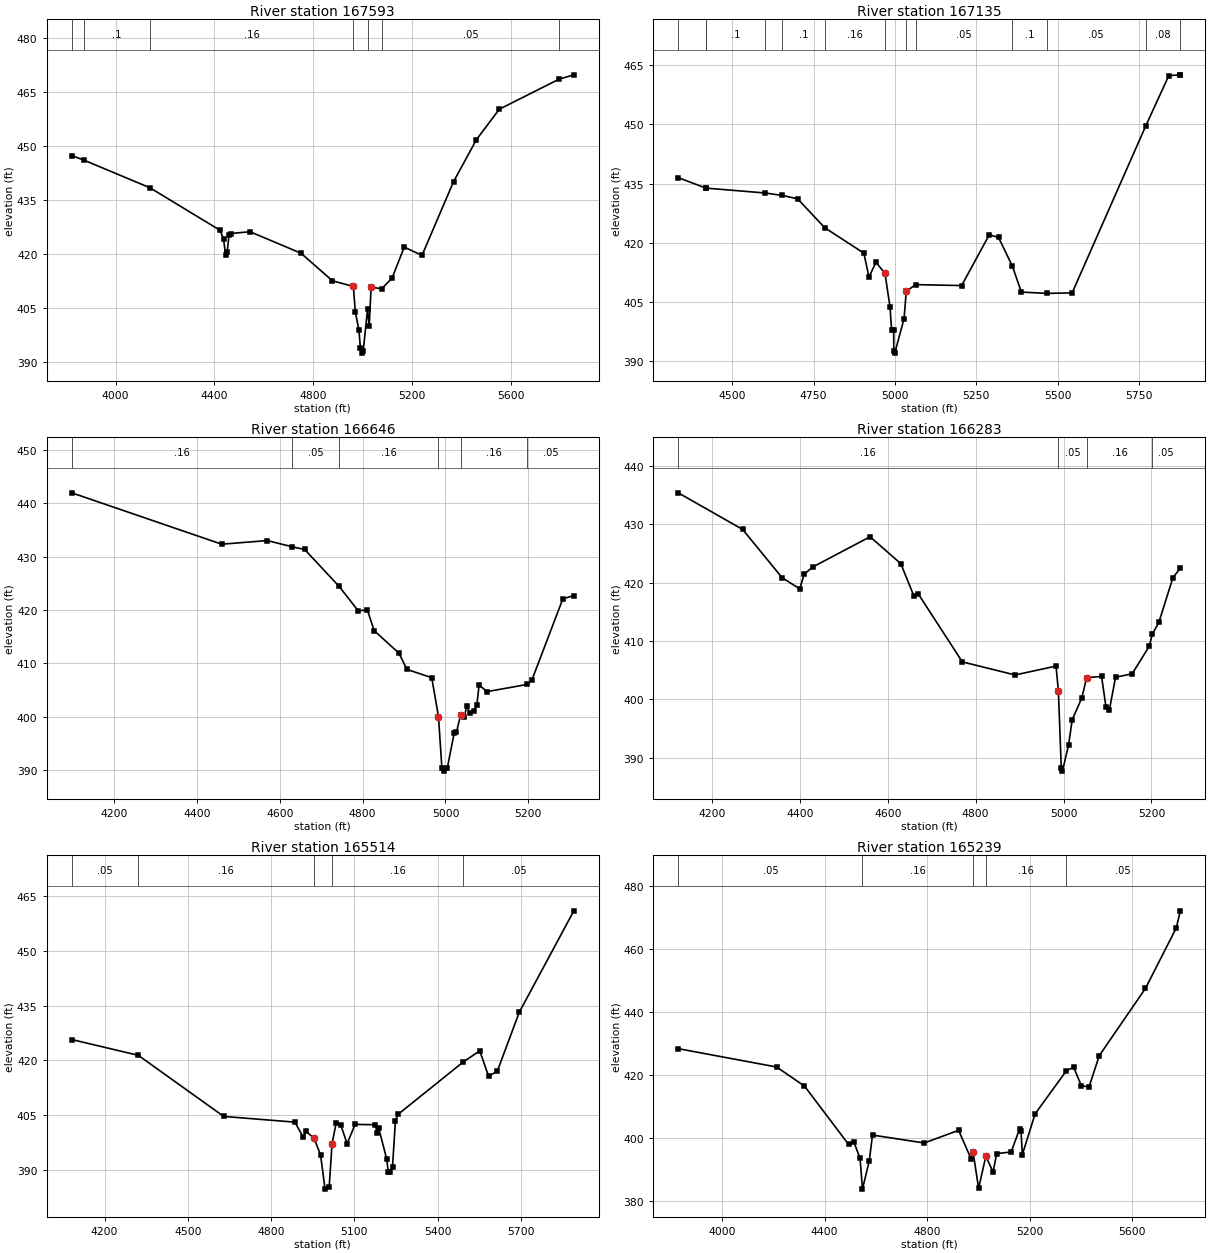
Type RM Length L Ch R = 1 ,167593  ,458,458,458
BEGIN DESCRIPTION:
BUFFALO CREEK 156.0
END DESCRIPTION:
XS GIS Cut Line= 2
      3583275.85     10522662.04      3584852.25     10521377.31
#Sta/Elev= 30
  3822.3  447.38  3870.4  446.16  4138.9  438.46  4422.9  426.66  4437.3  424.15
  4445.2   419.8  4451.6  420.57  4459.3  425.31    4466  425.76  4544.3  426.26
  4750.4  420.31  4878.2  412.64  4962.9  411.07  4970.8  403.95  4985.2  399.09
  4991.6  393.89  4999.3  392.57  5002.6  393.07  5020.4  404.78  5026.9  399.98
  5034.7  410.86  5077.6  410.45  5119.5  413.37    5169     422  5240.8  419.69
  5368.6  440.15  5461.3  451.81  5553.9  460.25  5796.5  468.61  5855.9   469.8
#Mann= 7 ,-1 , 0
  3822.3     .05       0  3870.4      .1       0  4138.9     .16       0
  4962.9     .05       0  5020.4     .16       0  5077.6     .05       0
  5796.5      .1       0
Bank Sta=4962.9,5034.7
XS Rating Curve= 0 ,0
Exp/Cntr=0.3,0.1

Type RM Length L Ch R = 1 ,167135  ,489,489,489
BEGIN DESCRIPTION:
BUFFALO CREEK 155.0
END DESCRIPTION:
XS GIS Cut Line= 3
      3583680.37     10522691.55      3584249.61     10522360.19
      3584849.58     10521710.22
#Sta/Elev= 30
  4334.1  436.49  4418.8  433.85  4420.3  433.83  4601.5   432.6  4654.5  431.97
  4701.1  431.12  4784.2  423.82  4904.6  417.38  4920.4  411.31  4941.9  415.07
  4969.6  412.24  4984.9  403.82  4989.9  398.01  4996.2  398.01  4996.8  392.57
  4999.6  392.07  5028.2   400.8    5035  407.72  5063.8  409.41  5205.1  409.17
  5290.2  422.03  5318.5  421.36    5361  414.11  5388.8  407.52  5466.4  407.19
  5544.8  407.31  5770.9  449.55  5841.9  462.31  5876.4  462.51  5877.3  462.51
#Mann= 13 ,-1 , 0
  4334.1      .1       0  4418.8     .08       0  4420.3      .1       0
  4601.5     .15       0  4654.5      .1       0  4784.2     .16       0
  4969.6     .05       0    5035     .16       0  5063.8     .05       0
    5361      .1       0  5466.4     .05       0  5770.9     .08       0
  5876.4      .1       0
#XS Ineff= 1 ,-1
 5346.48 5625.68  412.93
Permanent Ineff=
       F
Bank Sta=4969.6,5035
XS Rating Curve= 0 ,0
Exp/Cntr=0.3,0.1

Type RM Length L Ch R = 1 ,166646  ,363,363,363
BEGIN DESCRIPTION:
BUFFALO CREEK 154.0
END DESCRIPTION:
XS GIS Cut Line= 3
      3583498.08     10522882.51      3584192.54     10522847.79
      3584674.32     10522661.15
#Sta/Elev= 30
  4097.9  441.96  4459.9  432.33    4570  433.01  4629.2  431.86  4660.1  431.34
  4743.1  424.43  4789.3  419.86  4811.5  419.99  4827.9  416.13  4887.7   411.9
  4906.9  408.86  4966.8  407.31  4983.1  400.03  4991.3  390.47  4996.5  389.79
  5004.6  390.45  5021.3  397.03  5026.6  397.12  5036.7  400.34  5045.8  399.86
  5051.2  402.07  5058.2  400.76  5068.9  401.13  5075.8  402.18  5081.1  405.94
  5100.3  404.69  5197.2  406.04  5208.3   406.8  5283.4  422.09  5309.9  422.69
#Mann= 6 ,-1 , 0
  4097.9     .16       0  4629.2     .05       0  4743.1     .16       0
  4983.1     .05       0  5036.7     .16       0  5197.2     .05       0
Bank Sta=4983.1,5036.7
XS Rating Curve= 0 ,0
Exp/Cntr=0.3,0.1

Type RM Length L Ch R = 1 ,166283  ,769,769,769
BEGIN DESCRIPTION:
BUFFALO CREEK 153.0
END DESCRIPTION:
XS GIS Cut Line= 3
      3583663.04      10523086.5      3584444.28     10523077.82
      3584774.18     10522930.23
#Sta/Elev= 30
  4123.1   435.4  4269.7  429.12  4359.7  420.83  4399.7  418.94  4409.7  421.45
  4429.7   422.7  4559.7  427.87  4629.7  423.25  4659.7  417.66  4669.7  418.03
  4769.7  406.41  4889.7  404.17  4982.9  405.69  4988.3  401.45  4994.9  388.18
  4997.6  387.68  5011.5  392.18  5019.8  396.51  5041.7  400.25  5052.5   403.7
  5086.6  403.92  5096.5  398.73  5104.3  398.15  5118.4  403.77  5156.2  404.37
  5195.1  409.09    5202  411.16    5217  413.19    5249  420.85  5265.8   422.5
#Mann= 4 ,-1 , 0
  4123.1     .16       0  4988.3     .05       0  5052.5     .16       0
    5202     .05       0
Bank Sta=4988.3,5052.5
XS Rating Curve= 0 ,0
Exp/Cntr=0.3,0.1

Type RM Length L Ch R = 1 ,165514  ,275,275,275
BEGIN DESCRIPTION:
BUFFALO CREEK 152.0
END DESCRIPTION:
XS GIS Cut Line= 4
      3583702.04     10523433.71      3584422.57     10523572.61
      3584930.39     10523433.72      3585451.25     10523607.34
#Sta/Elev= 30
    4082  425.72  4321.7  421.39  4629.5  404.62  4886.2  403.05  4915.5  398.96
  4926.8  400.53  4955.2  398.59  4978.6  394.06  4994.6  384.67  5009.7  385.39
  5020.1  397.19  5034.5  402.71  5051.2  402.34  5074.2  397.13    5103  402.43
  5175.6  402.34  5182.9  399.95  5188.1   401.4    5217   392.9  5222.6   389.3
  5227.8  389.36  5237.8  390.73  5248.2  403.25  5257.1  405.15  5491.8  419.51
  5552.3  422.62  5583.9  415.66  5615.5  417.03  5694.7  433.22  5891.3  461.04
#Mann= 5 ,-1 , 0
    4082     .05       0  4321.7     .16       0  4955.2     .05       0
  5020.1     .16       0  5491.8     .05       0
Bank Sta=4955.2,5020.1
XS Rating Curve= 0 ,0
Exp/Cntr=0.3,0.1

Type RM Length L Ch R = 1 ,165239  ,407,407,407
BEGIN DESCRIPTION:
BUFFALO CREEK 151.0
END DESCRIPTION:
XS GIS Cut Line= 4
      3584053.66     10524675.03      3584539.76     10523928.51
       3584834.9     10523633.38      3585485.31      10523672.4
#Sta/Elev= 30
  3828.4  428.27  4212.5  422.45  4321.2   416.4  4493.2  397.91  4514.4  398.55
  4538.2  393.47  4547.5  383.71    4574  392.66  4586.7  400.86  4788.6  398.35
    4923  402.37  4972.5  393.12  4979.6  395.34  5000.8  383.96  5029.1  394.12
  5057.3  389.16  5071.5  394.96  5128.1  395.51  5161.4  402.93  5166.6  402.08
  5171.6  394.67  5221.5   407.6  5343.2  421.23  5371.7  422.42  5401.8  416.53
  5431.9  416.12  5471.9  426.06  5652.3  447.41  5772.5  466.58  5788.2     472
#Mann= 5 ,-1 , 0
  3828.4     .05       0  4547.5     .16       0  4979.6     .05       0
  5029.1     .16       0  5343.2     .05       0
#XS Ineff= 1 ,-1
 4431.82 4900.57   400.9
Permanent Ineff=
       F
Bank Sta=4979.6,5029.1
XS Rating Curve= 0 ,0
Exp/Cntr=0.3,0.1

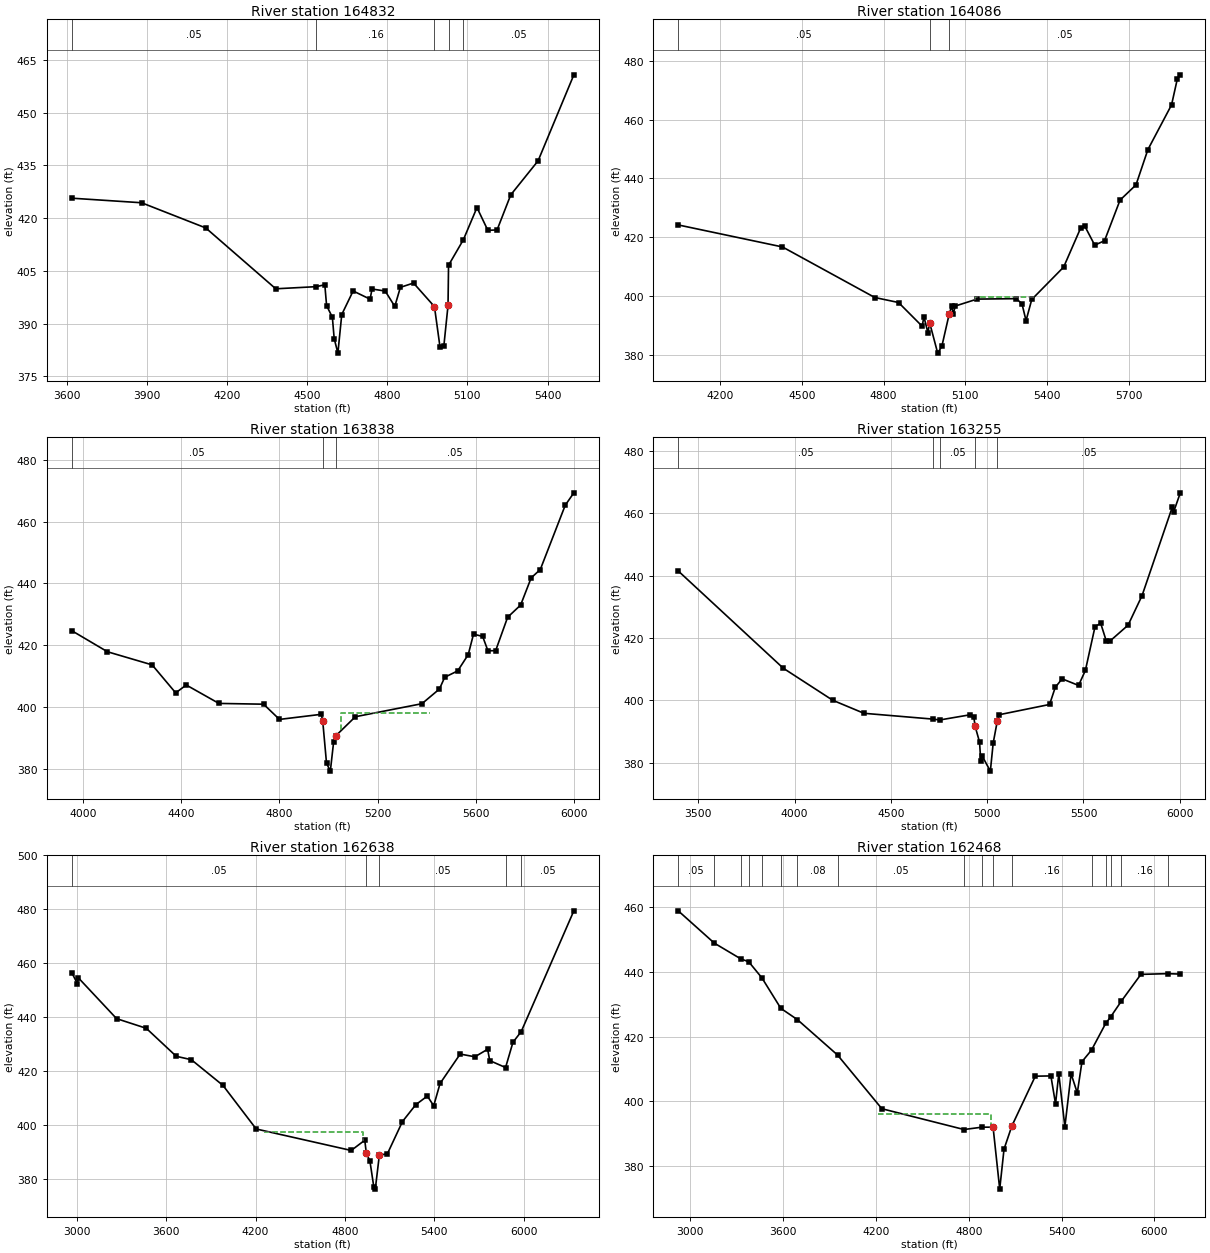
Type RM Length L Ch R = 1 ,164832  ,746,746,746
BEGIN DESCRIPTION:
BUFFALO CREEK 150.0
END DESCRIPTION:
XS GIS Cut Line= 3
      3584036.28     10524866.02      3584986.81     10523820.01
      3585445.71     10523729.09
#Sta/Elev= 30
  3617.5  425.67    3879  424.37  4119.6   417.2  4381.8  399.88  4534.2  400.49
  4565.6  401.04  4572.3  395.08  4593.9  391.79  4600.7  385.73  4614.6  381.57
  4629.1  392.55  4671.7  399.26  4735.2  396.93  4742.6  399.82  4791.9  399.24
  4827.8  394.87  4848.7  400.29    4898  401.52  4976.4  394.81  4997.4   383.2
  5011.6  383.59 5027.27  395.14  5029.2  406.57  5084.7  413.83  5135.7     423
  5176.5  416.51  5211.1  416.64  5262.3  426.62  5364.7   436.3  5498.7  460.78
#Mann= 5 ,-1 , 0
  3617.5     .05       0  4534.2     .16       0  4976.4     .05       0
  5029.2     .16       0  5084.7     .05       0
#XS Ineff= 1 ,-1
 4544.32 4869.32  399.65
Permanent Ineff=
       F
Bank Sta=4976.4,5027.27
XS Rating Curve= 0 ,0
Exp/Cntr=0.3,0.1

Type RM Length L Ch R = 1 ,164086  ,248,248,248
BEGIN DESCRIPTION:
BUFFALO CREEK 149.0
END DESCRIPTION:
XS GIS Cut Line= 2
      3584066.67      10524918.1      3585594.45     10523889.45
#Sta/Elev= 30
  4046.7  424.22    4429  416.75  4767.8  399.59  4854.8  397.89  4941.7  389.82
  4947.8  393.11  4962.7   387.6  4968.8  391.07  4998.5  380.71  5013.7  383.02
  5040.8  394.02  5049.7  396.69  5055.7  394.02  5062.9  396.69  5142.7  399.05
  5286.6   399.2  5307.6  397.46  5322.6  391.74  5343.6  398.93  5460.6  409.93
  5523.6  423.31  5538.6  423.73  5574.5  417.36  5610.5  418.86  5667.5  432.66
  5725.9  437.81  5769.5  449.78  5856.4  464.98  5877.4  473.72  5888.5  475.17
#Mann= 3 , 0 , 0
  4046.7     .05       0  4968.8     .04       0  5040.8     .05       0
#XS Ineff= 1 ,-1
 5135.23 5359.09  399.65
Permanent Ineff=
       F
Bank Sta=4968.8,5040.8
XS Rating Curve= 0 ,0
Exp/Cntr=0.3,0.1

Type RM Length L Ch R = 1 ,163838  ,583,583,583
BEGIN DESCRIPTION:
BUFFALO CREEK 148.0
END DESCRIPTION:
XS GIS Cut Line= 2
      3584040.65     10525139.44       3585802.8     10524106.46
#Sta/Elev= 30
  3955.5  424.71  4100.8  417.88  4282.5  413.63  4378.3  404.56  4421.2  407.12
  4554.2  401.15  4735.9   400.9  4800.5  395.97  4970.5  397.62  4976.3  395.57
  4991.9  381.79  5007.4  379.22  5020.7  388.59  5029.1  390.62  5109.2  396.84
  5380.1  401.06  5451.2  405.81  5472.8  409.63  5525.5  411.68  5568.4  416.95
  5589.9  423.59  5627.1  422.85  5648.6   418.2  5679.9  418.23  5728.7  429.06
  5781.5     433  5824.5  441.82  5861.6  444.52  5963.2  465.36  5998.1  469.36
#Mann= 3 ,-1 , 0
  3955.5     .05       0  4976.3     .04       0  5029.1     .05       0
#XS Ineff= 1 ,-1
 5052.56 5414.77     398
Permanent Ineff=
       F
Bank Sta=4976.3,5029.1
XS Rating Curve= 0 ,0
Exp/Cntr=0.3,0.1

Type RM Length L Ch R = 1 ,163255  ,617,617,617
BEGIN DESCRIPTION:
BUFFALO CREEK 147.0
END DESCRIPTION:
XS GIS Cut Line= 3
      3583689.09     10525378.16      3585025.87     10525061.33
      3586019.77     10524332.18
#Sta/Elev= 30
  3396.4  441.54  3941.6  410.33  4198.5  400.04  4360.5  395.86  4717.9     394
  4754.3  393.72  4910.5  395.37  4931.3  394.52  4937.5  391.71  4960.6  386.65
  4966.8  380.65  4973.3  382.26  5016.7   377.3  5031.6  386.38  5052.5  393.27
  5060.1  395.37  5324.2  398.69  5353.5  404.15    5389  406.93  5474.7   404.8
  5510.2  409.64  5560.3  423.71  5589.6  424.72  5618.2  419.14  5639.8  419.15
  5731.7  424.14  5804.3  433.63  5961.6  462.09  5967.8   460.4  6002.9  466.61
#Mann= 5 ,-1 , 0
  3396.4     .05       0  4717.9     .08       0  4754.3     .05       0
  4937.5     .04       0  5052.5     .05       0
Bank Sta=4937.5,5052.5
XS Rating Curve= 0 ,0
Exp/Cntr=0.3,0.1

Type RM Length L Ch R = 1 ,162638  ,170,170,170
BEGIN DESCRIPTION:
BUFFALO CREEK 146.0
END DESCRIPTION:
XS GIS Cut Line= 3
       3583506.8     10525721.05       3585750.7     10525373.83
      3586471.03     10524545.01
#Sta/Elev= 30
  2966.7  456.52    3005  452.41    3010  454.67  3267.3  439.48  3466.6   435.9
  3667.8  425.51  3768.9  424.25  3981.1  414.72  4204.1  398.55  4841.6  390.58
  4932.6  394.38  4942.8  389.68  4967.4  386.59  4993.3  377.02  5003.2  376.24
  5030.5  388.88  5084.4  389.35  5185.6  401.32  5274.5  407.54  5352.4  410.76
  5395.1  407.17  5437.8  415.43  5572.7  426.34  5671.4  425.33  5756.9  428.12
  5771.1  423.92  5877.3  421.34  5926.9  430.72  5982.2  434.66  6335.4  479.47
#Mann= 5 ,-1 , 0
  2966.7     .05       0  4942.8     .04       0  5030.5     .05       0
  5877.3     .08       0  5982.2     .05       0
#XS Ineff= 1 ,-1
 4257.73 4923.08  397.47
Permanent Ineff=
       F
Bank Sta=4942.8,5030.5
XS Rating Curve= 0 ,0
Exp/Cntr=0.3,0.1

Type RM Length L Ch R = 1 ,162468  ,287,287,287
BEGIN DESCRIPTION:
BUFFALO CREEK 145.0
END DESCRIPTION:
XS GIS Cut Line= 3
      3583476.41      10525877.3      3585807.12     10525534.42
      3586692.49     10525451.96
#Sta/Elev= 30
  2922.4  458.94  3155.6  448.94  3326.3  444.07    3378  443.16  3463.3  438.17
  3585.6  428.73  3692.7  425.24  3951.9  414.29  4238.4  397.65  4769.5  391.21
  4885.9  391.94  4957.3  391.93  5000.2  372.75    5028  385.13  5078.6   392.3
  5230.2  407.73  5330.9  407.81    5361  399.16  5381.9  408.46  5421.3  392.06
  5461.5  408.46  5501.6  402.54  5531.8  412.22  5593.4  415.81  5684.9  424.06
  5716.5  426.04  5786.3  430.97  5912.6  439.26  6085.3  439.48  6167.4  439.35
#Mann= 17 ,-1 , 0
  2922.4     .05       0  3155.6     .08       0  3326.3      .1       0
    3378     .05       0  3463.3     .08       0  3585.6     .05       0
  3692.7     .08       0  3951.9     .05       0  4769.5     .08       0
  4885.9     .05       0  4957.3     .04       0  5078.6     .16       0
  5593.4      .1       0  5684.9     .16       0  5716.5     .05       0
  5786.3     .16       0  6085.3     .05       0
#XS Ineff= 2 ,-1
 4215.64  4942.1  396.03 5302.27 5572.73  400.18
Permanent Ineff=
       F       F
Bank Sta=4957.3,5078.6
XS Rating Curve= 0 ,0
Exp/Cntr=0.3,0.1