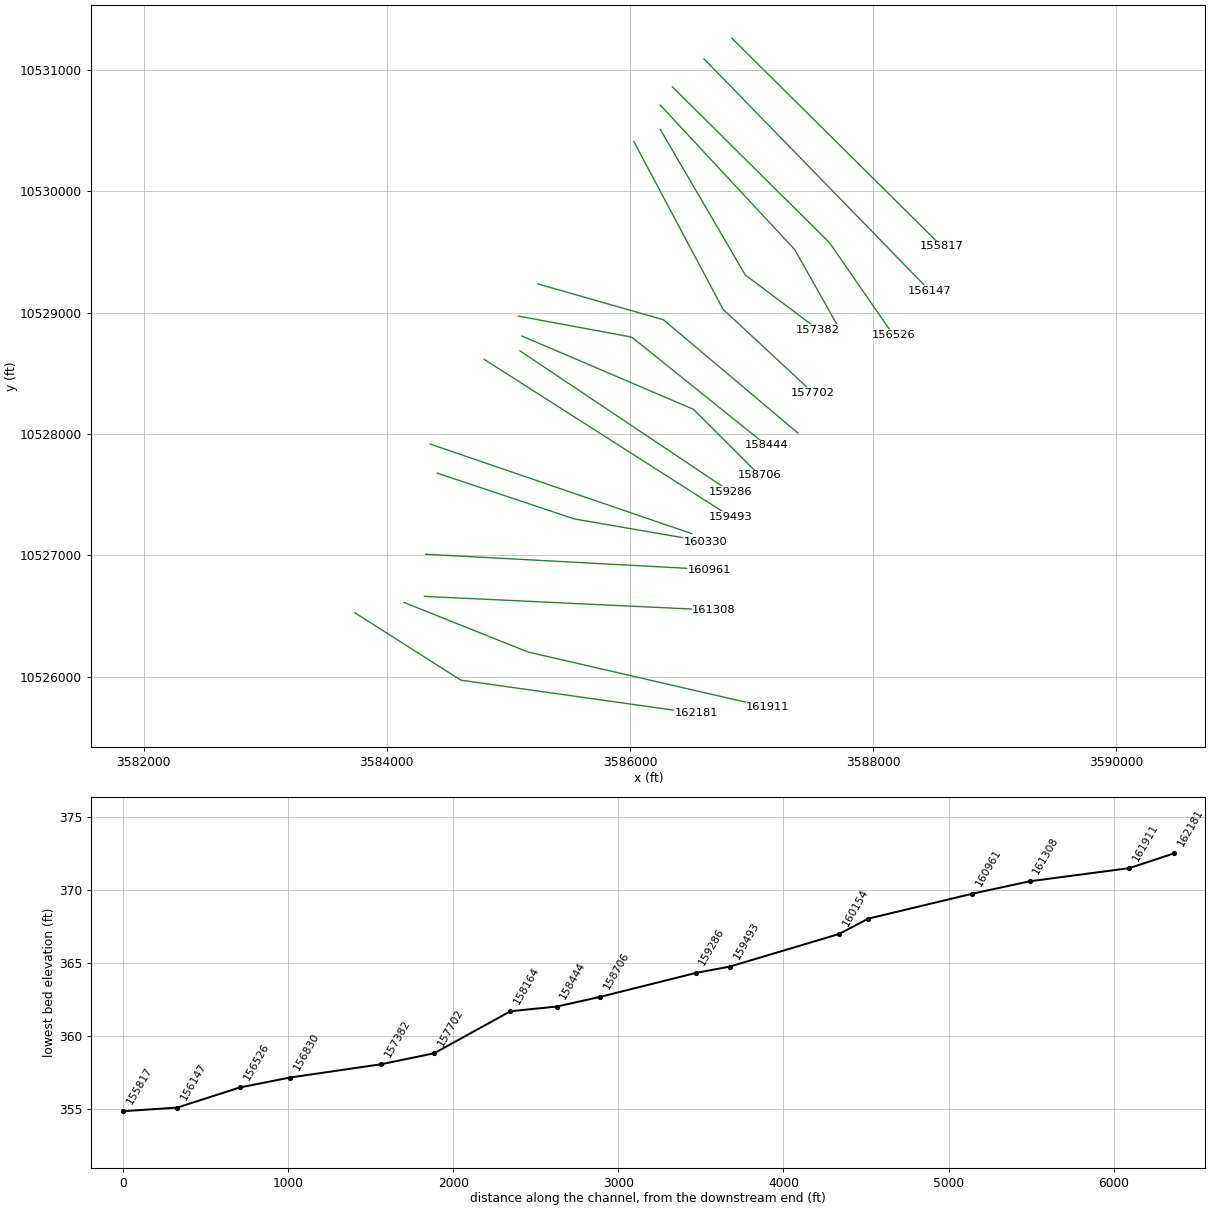
HEC-RAS study BUFFALO CREEK.prj: BUFFALO CREEK Base Level Engineering

--- BUFFALO CREEK.g01 (geometry) --- (continued)

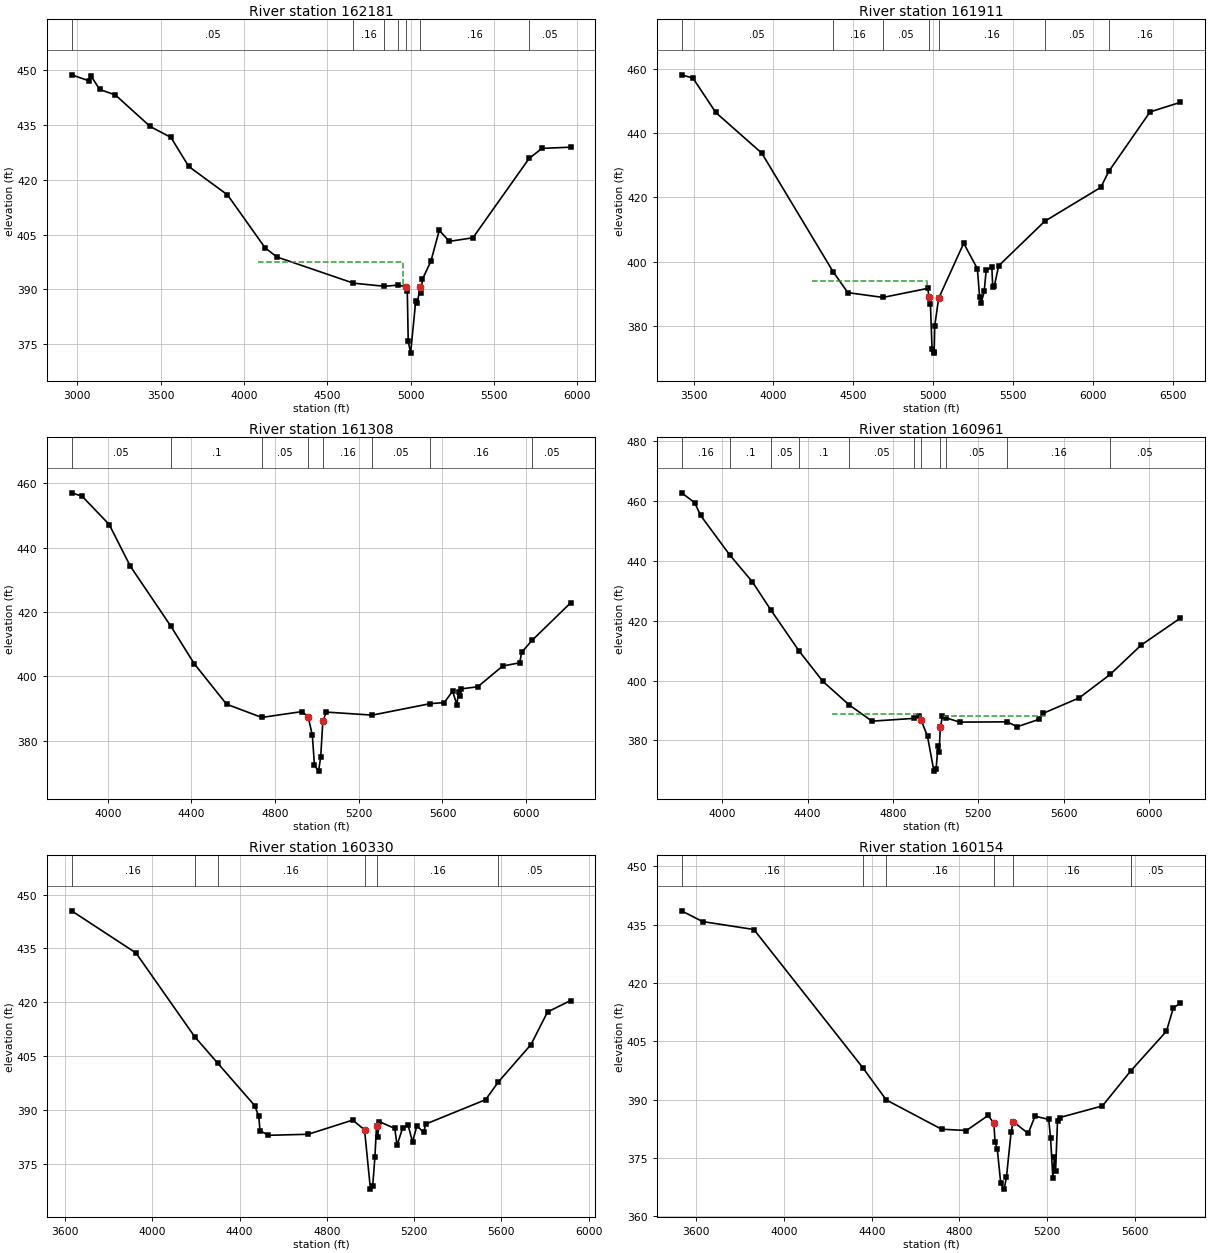
Type RM Length L Ch R = 1 ,162181  ,270,270,270
BEGIN DESCRIPTION:
BUFFALO CREEK 144.0
END DESCRIPTION:
XS GIS Cut Line= 3
      3583736.79     10526528.35      3584609.21     10525972.79
      3586549.33     10525699.34
#Sta/Elev= 30
  2965.7  448.76  3067.2  447.16  3082.5  448.43  3134.1  444.75  3228.1  443.25
  3437.2   434.6  3561.6  431.61  3668.5  423.65  3901.1  415.86  4126.4  401.37
  4197.5  398.84  4656.8  391.66  4843.1  390.81  4922.9  391.13  4969.9  390.71
    4980  389.43  4985.5  375.76  4999.9  372.49  5030.5  386.73  5040.6  386.16
  5056.7   390.7  5061.7   388.9  5070.9  392.74  5121.4  397.65  5171.9  406.12
  5232.5  403.12  5373.8   404.1  5710.8  425.83  5787.9   428.6  5959.3  428.93
#Mann= 7 ,-1 , 0
  2965.7     .05       0  4656.8     .16       0  4843.1     .05       0
  4922.9     .16       0  4969.9     .04       0  5056.7     .16       0
  5710.8     .05       0
#XS Ineff= 1 ,-1
 4082.95 4953.98  397.55
Permanent Ineff=
       F
Bank Sta=4969.9,5056.7
XS Rating Curve= 0 ,0
Exp/Cntr=0.3,0.1

Type RM Length L Ch R = 1 ,161911  ,603,603,603
BEGIN DESCRIPTION:
Mapping XS 5ca5c14c
END DESCRIPTION:
XS GIS Cut Line= 3
      3584141.48       10526613.      3585161.43     10526205.01
      3587135.43     10525749.48
#Sta/Elev= 30
  3424.7  458.22  3496.1   457.2  3638.8  446.48  3926.9  433.81  4372.9  396.91
  4465.5  390.34  4685.6  388.84  4967.5  391.67  4972.9  389.02  4983.2  386.72
  4993.4   372.7  5003.5  371.48  5006.7  371.98  5010.2  380.05  5034.5  388.53
  5191.5  405.73  5277.1  397.79  5291.1  389.04  5301.3   387.2  5319.8  390.69
  5332.1  397.24  5367.7   398.4  5373.2  392.24  5383.4   392.4  5410.5   398.7
  5699.4  412.59  6050.5  423.16  6099.6  428.09  6358.4  446.65  6549.1  449.66
#Mann= 7 ,-1 , 0
  3424.7     .05       0  4372.9     .16       0  4685.6     .05       0
  4972.9     .04       0  5034.5     .16       0  5699.4     .05       0
  6099.6     .16       0
#XS Ineff= 2 ,-1
 4239.16 4964.16393.8811 5206.82 5515.91  394.42
Permanent Ineff=
       F       F
Bank Sta=4972.9,5034.5
XS Rating Curve= 0 ,0
Exp/Cntr=0.3,0.1

Type RM Length L Ch R = 1 ,161308  ,347,347,347
BEGIN DESCRIPTION:
BUFFALO CREEK 143.0
END DESCRIPTION:
XS GIS Cut Line= 2
       3584309.7     10526662.89      3586692.53     10526550.04
#Sta/Elev= 30
  3826.8  456.99  3876.8  455.94  4006.9  447.13    4107  434.26  4302.1   415.5
  4412.4  403.99  4567.5  391.37  4735.9  387.25  4927.9  389.06    4958  387.46
    4978  381.68    4988  372.37  5007.8  370.58    5018  375.11  5028.1  386.13
  5044.8  388.91  5264.3  387.97  5541.3  391.53  5608.7  391.87  5648.7   395.4
  5668.8   391.2  5677.3  395.29  5682.3  393.92  5688.8  396.11  5768.9  396.77
  5888.1  403.22  5969.1  404.21  5979.1   407.5  6029.7  411.26  6212.3  422.79
#Mann= 8 ,-1 , 0
  3826.8     .05       0  4302.1      .1       0  4735.9     .05       0
    4958     .04       0  5028.1     .16       0  5264.3     .05       0
  5541.3     .16       0  6029.7     .05       0
#XS Ineff= 2 ,-1
  4445.3 4932.81388.5406 5043.77  5468.2388.6314
Permanent Ineff=
       F       F
Bank Sta=4958,5028.1
XS Rating Curve= 0 ,0
Exp/Cntr=0.3,0.1

Type RM Length L Ch R = 1 ,160961  ,631,631,631
BEGIN DESCRIPTION:
BUFFALO CREEK 142.0
END DESCRIPTION:
XS GIS Cut Line= 2
      3584318.41     10527010.11      3586653.52     10526884.24
#Sta/Elev= 30
  3809.7  462.77    3871  459.49  3898.6  455.24  4034.6  442.08  4141.4  433.02
  4228.7  423.54  4362.1  409.73  4471.9  399.74  4594.6  391.91  4702.2  386.43
  4901.1  387.38  4922.5  388.24  4932.5  386.83  4962.6  381.31  4992.4  369.73
  5002.6  370.33  5011.8  378.08  5016.8   376.1  5022.7  384.42  5032.7  388.04
    5050  387.52  5112.8  386.12  5336.5   386.2  5382.8  384.56  5483.3     387
  5503.3  389.01  5673.6  394.22  5818.4  402.04    5964  411.86  6148.2  420.91
#Mann= 11 ,-1 , 0
  3809.7     .16       0  4034.6      .1       0  4228.7     .05       0
  4362.1      .1       0  4594.6     .05       0  4901.1     .16       0
  4932.5     .05       0  5022.7     .16       0    5050     .05       0
  5336.5     .16       0  5818.4     .05       0
#XS Ineff= 2 ,-1
  4514.2  4926.7  388.84  5039.2  5526.7  388.24
Permanent Ineff=
       F       F
Bank Sta=4932.5,5022.7
XS Rating Curve= 0 ,0
Exp/Cntr=0.3,0.1

Type RM Length L Ch R = 1 ,160330  ,176,176,176
BEGIN DESCRIPTION:
BUFFALO CREEK 141.0
END DESCRIPTION:
XS GIS Cut Line= 3
      3584413.92     10527678.51      3585542.37     10527300.91
      3586623.12     10527114.27
#Sta/Elev= 30
  3629.9  445.48  3924.9  433.75  4193.6  410.48  4299.3  403.09    4469  391.28
    4488  388.24  4493.3  384.29  4532.2     383  4714.3  383.29  4918.5  387.24
  4972.7   384.5  4999.5  368.02  5009.9  368.84    5020  376.86  5027.4  385.51
  5032.5  382.45  5040.3  386.81  5111.3  384.91  5121.5  380.22  5147.1     385
  5172.2  385.81  5192.5  381.18  5212.8  385.65  5243.3  383.81  5253.4  386.14
  5527.4  392.91  5586.5   397.9  5735.2  408.24  5811.6  417.34  5916.6   420.5
#Mann= 6 ,-1 , 0
  3629.9     .16       0  4193.6      .1       0  4299.3     .16       0
  4972.7     .05       0  5027.4     .16       0  5586.5     .05       0
#XS Ineff= 2 ,-1
 4357.33 4826.09383.9133 5056.82 5343.75383.0735
Permanent Ineff=
       F       F
Bank Sta=4972.7,5027.4
XS Rating Curve= 0 ,0
Exp/Cntr=0.3,0.1

Type RM Length L Ch R = 1 ,160154  ,661,661,661
BEGIN DESCRIPTION:
BUFFALO CREEK 140.0
END DESCRIPTION:
XS GIS Cut Line= 2
      3584357.46     10527917.23      3586510.22     10527179.39
#Sta/Elev= 30
  3532.4  438.56  3627.9   435.8  3862.4  433.75  4360.1  398.13    4466  389.92
  4718.6  382.38  4831.9  382.05    4931  385.93    4957  383.91  4962.3  379.07
  4972.3  377.35  4988.3  368.44  5003.8  366.97  5014.2  369.99  5035.8  381.77
  5045.5  384.32  5113.4  381.29  5144.6  385.74  5207.2   384.9  5215.5  380.11
    5226  369.95  5233.2  375.23  5238.5  371.69  5247.2  384.48  5257.8  385.39
  5452.1  388.37  5580.6  397.34    5744  407.58  5775.7   413.6  5808.1  414.83
#Mann= 6 ,-1 , 0
  3532.4     .16       0  4360.1     .05       0    4466     .16       0
    4957     .05       0  5045.5     .16       0  5580.6     .05       0
#XS Ineff= 1 ,-1
 5204.55 5281.25  380.03
Permanent Ineff=
       F
Bank Sta=4957,5045.5
XS Rating Curve= 0 ,0
Exp/Cntr=0.3,0.1

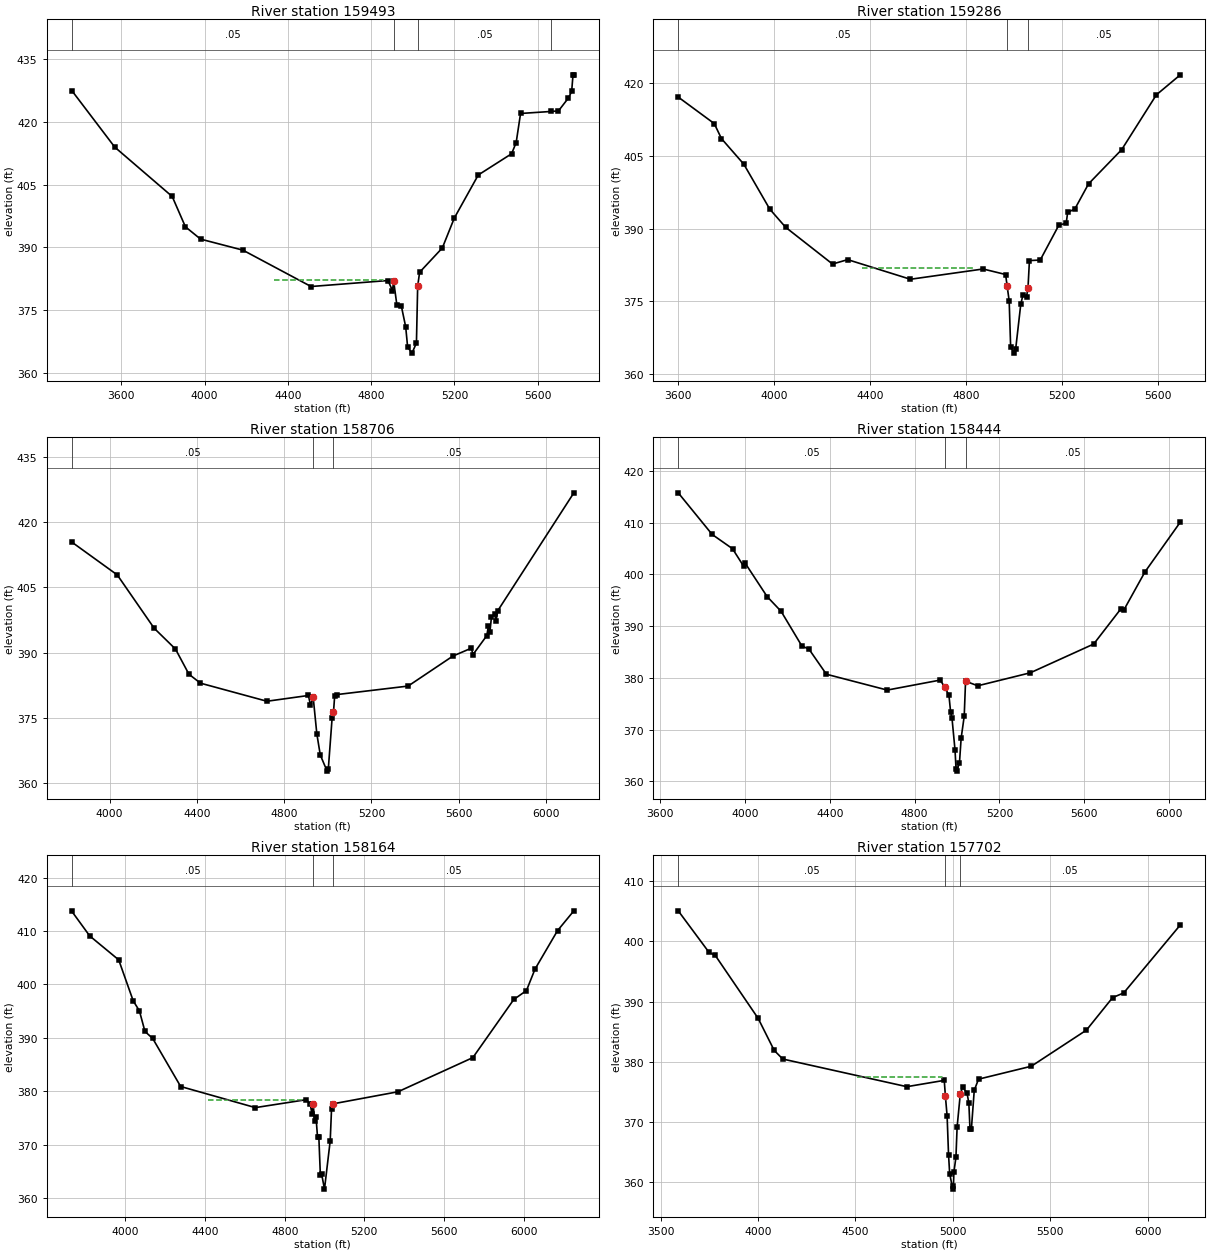
Type RM Length L Ch R = 1 ,159493  ,207,207,207
BEGIN DESCRIPTION:
BUFFALO CREEK 139.0
END DESCRIPTION:
XS GIS Cut Line= 2
      3584800.19     10528616.01      3586831.42     10527318.28
#Sta/Elev= 30
  3362.7  427.46  3569.1  413.94  3844.9  402.15  3908.3  394.91  3981.1  391.97
  4184.1  389.34  4511.5  380.65  4880.9  382.08  4902.3  379.67  4908.2  381.89
  4923.5  376.23  4944.6  376.06  4965.8  371.02  4975.1   366.2    4996  364.74
  5017.4  367.16  5023.3  380.69  5032.6  384.05  5141.7  389.86  5199.2     397
  5314.3  407.29  5474.3  412.36  5496.2  415.04  5517.3  421.98  5663.5  422.46
  5699.2  422.59  5747.4   425.7  5762.6  427.25  5769.1  431.21  5773.1  431.21
#Mann= 4 ,-1 , 0
  3362.7     .05       0  4908.2     .04       0  5023.3     .05       0
  5663.5      .1       0
#XS Ineff= 1 ,-1
 4334.66 4854.55  382.23
Permanent Ineff=
       F
Bank Sta=4908.2,5023.3
XS Rating Curve= 0 ,0
Exp/Cntr=0.3,0.1

Type RM Length L Ch R = 1 ,159286  ,580,580,580
BEGIN DESCRIPTION:
BUFFALO CREEK 138.0
END DESCRIPTION:
XS GIS Cut Line= 2
      3585095.33     10528685.45      3586831.39     10527522.29
#Sta/Elev= 30
  3602.1  417.13    3752  411.66    3782  408.56  3875.1  403.28  3983.1  394.01
  4049.2  390.26  4244.3  382.68  4307.3  383.59  4568.5  379.54  4871.1  381.66
  4964.7  380.52  4970.7  378.23  4979.5   375.1  4985.7  365.47  5000.5   364.3
  5006.7  365.21  5027.7  374.36  5036.7  376.29  5051.7  375.98  5057.8  377.68
  5063.8  383.39  5108.8  383.51  5186.8  390.75  5216.8  391.07  5222.9  393.33
  5252.9  394.05  5309.9  399.23    5448   406.3  5592.1  417.59  5691.8  421.72
#Mann= 3 , 0 , 0
  3602.1     .05       0  4970.7     .04       0  5057.8     .05       0
#XS Ineff= 1 ,-1
  4367.9 4828.12   381.9
Permanent Ineff=
       F
Bank Sta=4970.7,5057.8
XS Rating Curve= 0 ,0
Exp/Cntr=0.3,0.1

Type RM Length L Ch R = 1 ,158706  ,262,262,262
BEGIN DESCRIPTION:
BUFFALO CREEK 137.0
END DESCRIPTION:
XS GIS Cut Line= 3
      3585112.65       10528807.      3586523.27     10528203.69
      3587065.18     10527661.77
#Sta/Elev= 30
  3826.8  415.47  4035.2   407.9  4204.2  395.61    4302   390.8  4363.6  385.01
  4416.3  382.94  4721.1  378.77  4911.1   380.1  4920.7  377.89  4932.9  379.72
  4949.7  371.26  4965.5  366.39  4996.7  362.66  5002.4  363.21  5019.9  375.02
    5026   376.2  5031.4  379.96  5041.6  380.31    5368  382.27    5573  389.18
  5657.9  391.01    5665  389.52  5728.6   393.9  5735.7  396.08  5742.7  394.71
  5749.8  398.15    5764  398.88    5771  397.23  5778.1  399.59  6127.4  426.82
#Mann= 3 , 0 , 0
  3826.8     .05       0  4932.9     .04       0    5026     .05       0
#XS Ineff= 1 ,-1
  4660.8 4860.23  379.36
Permanent Ineff=
       F
Bank Sta=4932.9,5026
XS Rating Curve= 0 ,0
Exp/Cntr=0.3,0.1

Type RM Length L Ch R = 1 ,158444  ,280,280,280
BEGIN DESCRIPTION:
BUFFALO CREEK 136.0
END DESCRIPTION:
XS GIS Cut Line= 3
      3585082.28     10528971.92      3586015.46     10528798.31
      3587122.25     10527908.53
#Sta/Elev= 30
  3684.5  415.77  3844.5  407.73  3940.6  404.97  3993.3  401.58  3998.4   402.3
    4104  395.72    4170  392.87  4267.3  386.22  4302.3  385.52  4383.6  380.72
  4670.8  377.66  4920.4  379.59  4941.2  378.32    4962  376.63    4970  373.37
  4976.4  372.23  4990.8     366  4995.3   362.5    4998     362  5011.6  363.58
  5019.6  368.39    5034  372.59  5040.4  379.37    5098  378.49    5346     381
  5645.2  386.56  5773.2  393.35  5787.6  393.15  5886.8  400.48  6053.8  410.11
#Mann= 3 , 0 , 0
  3684.5     .05       0  4941.2     .03       0  5040.4     .05       0
#XS Ineff= 1 ,-1
 4415.34 4916.48  379.07
Permanent Ineff=
       F
Bank Sta=4941.2,5040.4
XS Rating Curve= 0 ,0
Exp/Cntr=0.3,0.1

Type RM Length L Ch R = 1 ,158164  ,462,462,462
BEGIN DESCRIPTION:
BUFFALO CREEK 135.0
END DESCRIPTION:
XS GIS Cut Line= 3
      3585242.87     10529236.68      3586275.87     10528941.54
      3587382.64     10528008.38
#Sta/Elev= 30
  3730.3   413.7  3820.5  409.08  3966.1   404.6  4038.9  396.93  4070.1  395.05
  4097.9   391.2  4136.9  389.88  4277.3  380.89  4652.5  376.94  4907.6  378.42
  4928.4  377.69  4936.2  375.75  4942.7   377.7  4950.5  374.38    4957  375.23
  4964.8  371.41  4971.3  371.48  4979.1  364.26  4985.6  364.47  4999.7  361.68
  5028.5  370.74  5035.1  376.65  5042.8  377.65  5369.2  379.91    5745   386.3
  5950.5  397.18  6014.2  398.85  6057.1  402.86  6170.3  410.07  6252.3  413.78
#Mann= 3 ,-1 , 0
  3730.3     .05       0  4942.7     .04       0  5042.8     .05       0
#XS Ineff= 1 ,-1
 4413.64  4889.2   378.4
Permanent Ineff=
       F
Bank Sta=4942.7,5042.8
XS Rating Curve= 0 ,0
Exp/Cntr=0.3,0.1

Type RM Length L Ch R = 1 ,157702  ,320,320,320
BEGIN DESCRIPTION:
Mapping XS af444e75
END DESCRIPTION:
XS GIS Cut Line= 3
      3586032.83     10530408.52      3586766.32     10529028.34
      3587508.49     10528338.26
#Sta/Elev= 30
    3591  405.09  3748.6   398.2  3781.3  397.66  4001.1   387.2  4083.3  381.88
  4127.3  380.44    4764  375.84  4956.1  376.89  4961.8  374.32  4970.7  370.98
  4978.1  364.52  4983.8  361.39  4999.8   358.8  5003.1   359.3  5005.7  361.67
    5016  364.09  5022.1  369.16  5038.4  374.62    5050  375.72  5072.6  374.84
  5082.3   373.1    5088  368.88  5095.3   368.8    5110  375.24    5132  377.09
  5402.8  379.24  5685.7  385.25  5820.1  390.66  5876.8  391.43  6167.4  402.74
#Mann= 3 , 0 , 0
    3591     .05       0  4961.8     .04       0  5038.4     .05       0
#XS Ineff= 1 ,-1
 4509.09 4943.75  377.41
Permanent Ineff=
       F
Bank Sta=4961.8,5038.4
XS Rating Curve= 0 ,0
Exp/Cntr=0.3,0.1

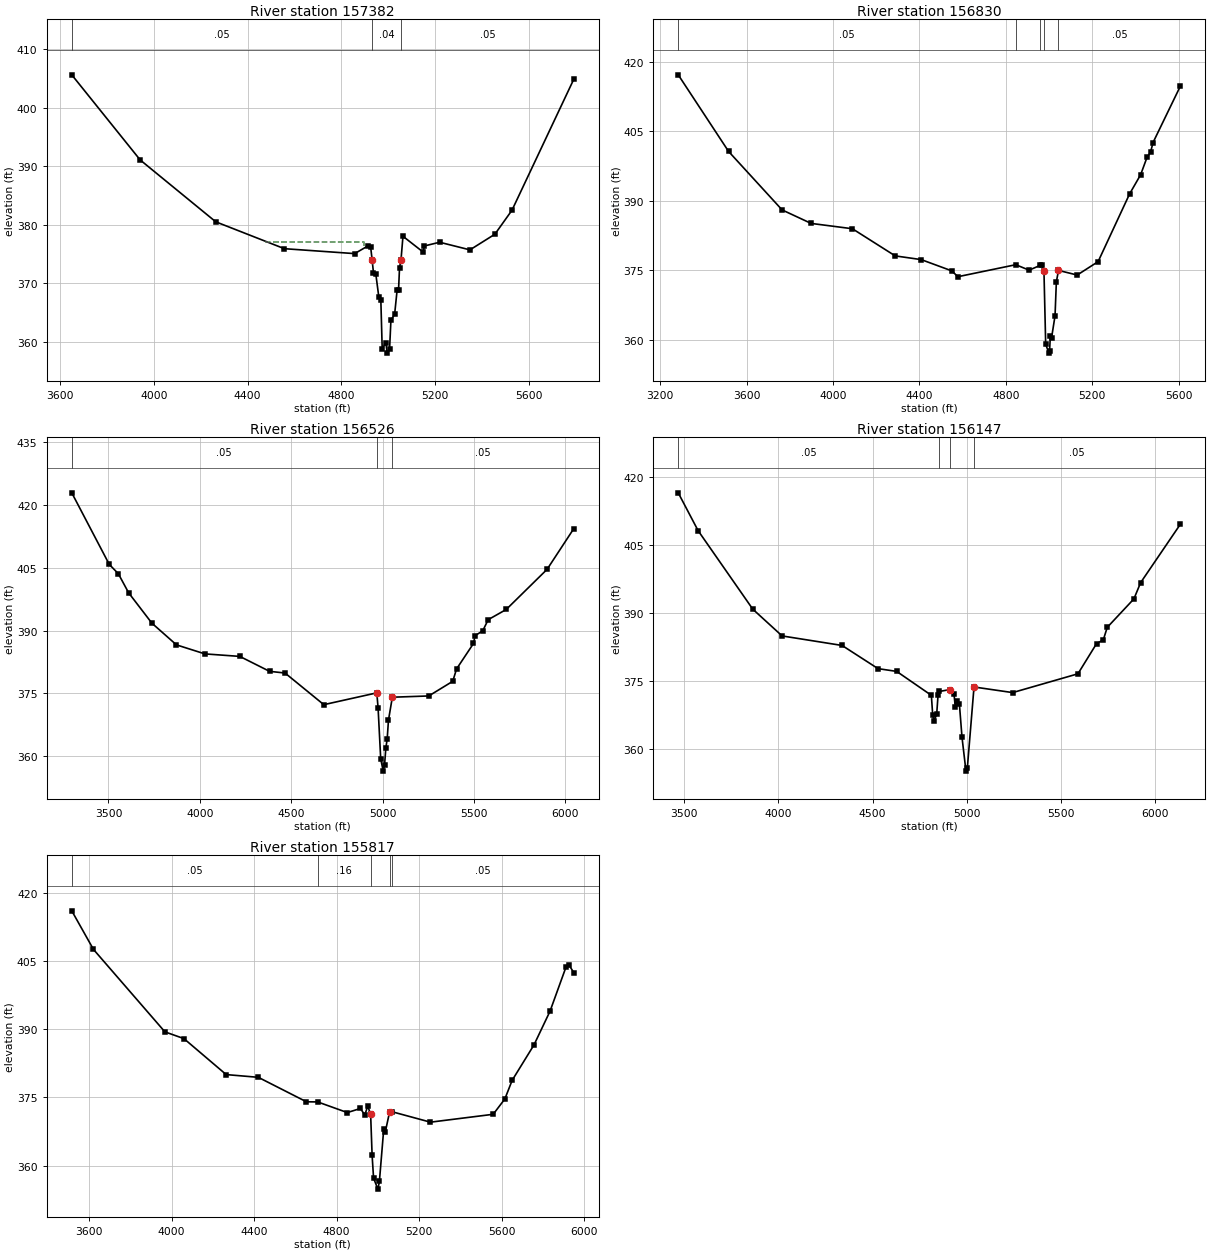
Type RM Length L Ch R = 1 ,157382  ,552,552,552
BEGIN DESCRIPTION:
BUFFALO CREEK 134.0
END DESCRIPTION:
XS GIS Cut Line= 3
      3586249.59     10530510.22      3586949.61     10529310.19
      3587549.62     10528860.18
#Sta/Elev= 30
  3650.8  405.59  3942.3  391.05  4264.4  380.48  4556.7  375.89  4856.1  375.05
  4914.8  376.41  4924.3  376.19  4930.5     374  4936.3  371.78  4946.2  371.59
    4959  367.68  4967.7  367.15  4973.5  358.82  4989.2   359.8  4994.8  358.05
  5004.9  358.71  5010.7  363.69  5026.4  364.66  5037.2  368.88  5043.2  368.88
  5047.4  372.66  5053.6  373.96    5062  378.01  5147.4  375.33  5153.6  376.36
  5218.2  376.99  5347.4  375.69  5453.6  378.36  5526.5  382.46  5790.1  404.86
#Mann= 3 , 0 , 0
  3650.8     .05       0  4930.5     .04       0  5053.6     .05       0
#XS Ineff= 1 ,-1
 4474.43 4897.73  377.03
Permanent Ineff=
       F
Bank Sta=4930.5,5053.6
XS Rating Curve= 0 ,0
Exp/Cntr=0.3,0.1

Type RM Length L Ch R = 1 ,156830  ,304,304,304
BEGIN DESCRIPTION:
BUFFALO CREEK 133.0
END DESCRIPTION:
XS GIS Cut Line= 3
      3586249.64     10530710.15       3587356.6     10529518.79
      3587699.63     10528910.16
#Sta/Elev= 30
  3283.3  417.19  3516.6  400.65  3764.3  388.04  3898.6  385.13  4089.7  383.98
  4288.1  378.12  4408.3  377.32    4550  374.89  4578.3  373.63  4846.3  376.22
  4908.1  375.04  4958.5  376.06  4968.8  376.14  4976.8  374.81  4984.8  359.06
  4999.5  357.14  5002.8  357.64  5006.4  360.85  5012.2  360.49  5028.1   365.2
  5034.2  372.49    5044  374.99  5130.7  373.99  5227.5  376.88  5373.4   391.5
  5424.5  395.64  5454.3  399.42  5470.2  400.45  5481.9  402.58  5608.2  414.73
#Mann= 5 ,-1 , 0
  3283.3     .05       0  4846.3     .16       0  4958.5     .05       0
  4976.8     .04       0    5044     .05       0
#XS Ineff= 1 ,-1
 4447.16  4948.3  375.49
Permanent Ineff=
       F
Bank Sta=4976.8,5044
XS Rating Curve= 0 ,0
Exp/Cntr=0.3,0.1

Type RM Length L Ch R = 1 ,156526  ,379,379,379
BEGIN DESCRIPTION:
BUFFALO CREEK 132.0
END DESCRIPTION:
XS GIS Cut Line= 3
      3586349.58     10530860.22      3587643.06     10529575.22
      3588168.23     10528815.67
#Sta/Elev= 30
  3299.3  422.88  3504.4   405.8  3553.9  403.58  3610.5  399.01  3737.7  391.77
  3872.1  386.59  4027.7  384.44  4218.6  383.84  4381.2  380.28  4466.1  379.87
  4678.2  372.32  4968.1  375.14  4975.2  371.45  4989.4  359.39  5003.2  356.46
  5010.5  357.96  5017.6  362.06  5024.7  364.04  5031.8  368.59    5053   374.1
  5252.4   374.4  5383.5   377.9  5404.4  380.85    5497  386.93  5505.6  388.78
  5547.7  389.96  5577.5  392.61  5676.1  395.04  5899.8  404.63    6046  414.36
#Mann= 3 , 0 , 0
  3299.3     .05       0  4968.1     .04       0    5053     .05       0
#XS Ineff= 1 ,-1
 4509.38 4954.83  373.79
Permanent Ineff=
       F
Bank Sta=4968.1,5053
XS Rating Curve= 0 ,0
Exp/Cntr=0.3,0.1

Type RM Length L Ch R = 1 ,156147  ,330,330,330
BEGIN DESCRIPTION:
BUFFALO CREEK 131.0
END DESCRIPTION:
XS GIS Cut Line= 2
      3586610.05       10531090.       3588467.7     10529180.26
#Sta/Elev= 30
  3469.1  416.53  3574.8  408.16  3864.7  390.84  4020.3  384.93  4338.4  382.83
  4529.3  377.71  4628.3   377.1  4812.2  371.82  4819.4  367.49  4826.4  366.19
  4840.5  367.59  4847.7  371.85  4854.7  372.67  4911.3  373.09  4932.6  372.01
  4939.6  369.13  4946.7  370.64  4960.9  369.94    4975  362.51  4995.9  355.08
  5003.3  355.82  5038.6  373.66  5243.6  372.42  5590.1  376.57  5689.1  383.25
  5724.6  384.06  5745.7  386.83  5887.2  393.12  5922.6  396.69  6133.3  409.58
#Mann= 4 ,-1 , 0
  3469.1     .05       0  4854.7     .16       0  4911.3     .04       0
  5038.6     .05       0
#XS Ineff= 1 ,-1
 4734.09 4883.24  372.87
Permanent Ineff=
       F
Bank Sta=4911.3,5038.6
XS Rating Curve= 0 ,0
Exp/Cntr=0.3,0.1

Type RM Length L Ch R = 1 ,155817  ,1007,1007,1007
BEGIN DESCRIPTION:
BUFFALO CREEK 130.0
END DESCRIPTION:
XS GIS Cut Line= 2
      3586840.08     10531259.27      3588567.33     10529545.04
#Sta/Elev= 30
  3516.4  416.01  3621.5  407.53  3967.9   389.4  4059.9  387.92  4264.9  380.01
  4420.5  379.41  4653.9  374.03  4708.2     374  4851.9  371.66  4915.5  372.56
  4936.7  371.11  4950.9   373.1    4965  371.24  4972.1  362.25  4979.2  357.25
  5000.1  354.83  5007.4  356.51  5028.6  368.09  5035.7  367.34  5056.9  371.81
  5070.5  371.82  5254.9  369.55  5558.9  371.28  5615.5  374.65  5650.9  378.75
  5756.9  386.55  5834.7  393.97  5912.5  403.73  5926.6  404.09  5949.9   402.4
#Mann= 5 ,-1 , 0
  3516.4     .05       0  4708.2     .16       0    4965     .04       0
  5056.9     .16       0  5070.5     .05       0
Bank Sta=4965,5056.9
XS Rating Curve= 0 ,0
Exp/Cntr=0.3,0.1