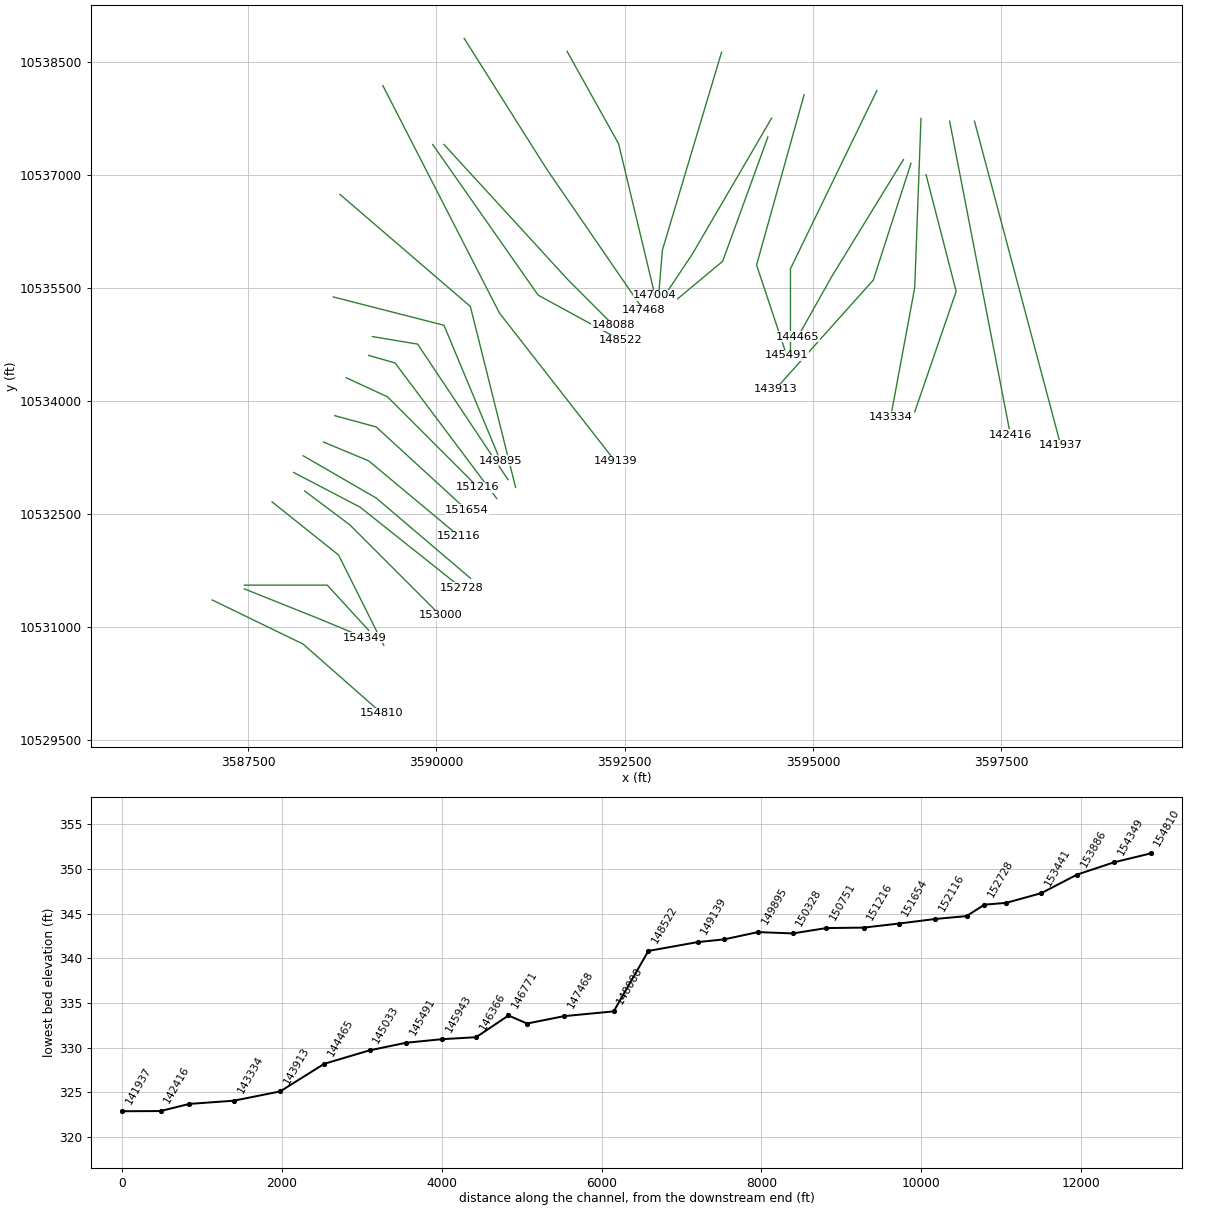
HEC-RAS study BUFFALO CREEK.prj: BUFFALO CREEK Base Level Engineering

--- BUFFALO CREEK.g01 (geometry) --- (continued)

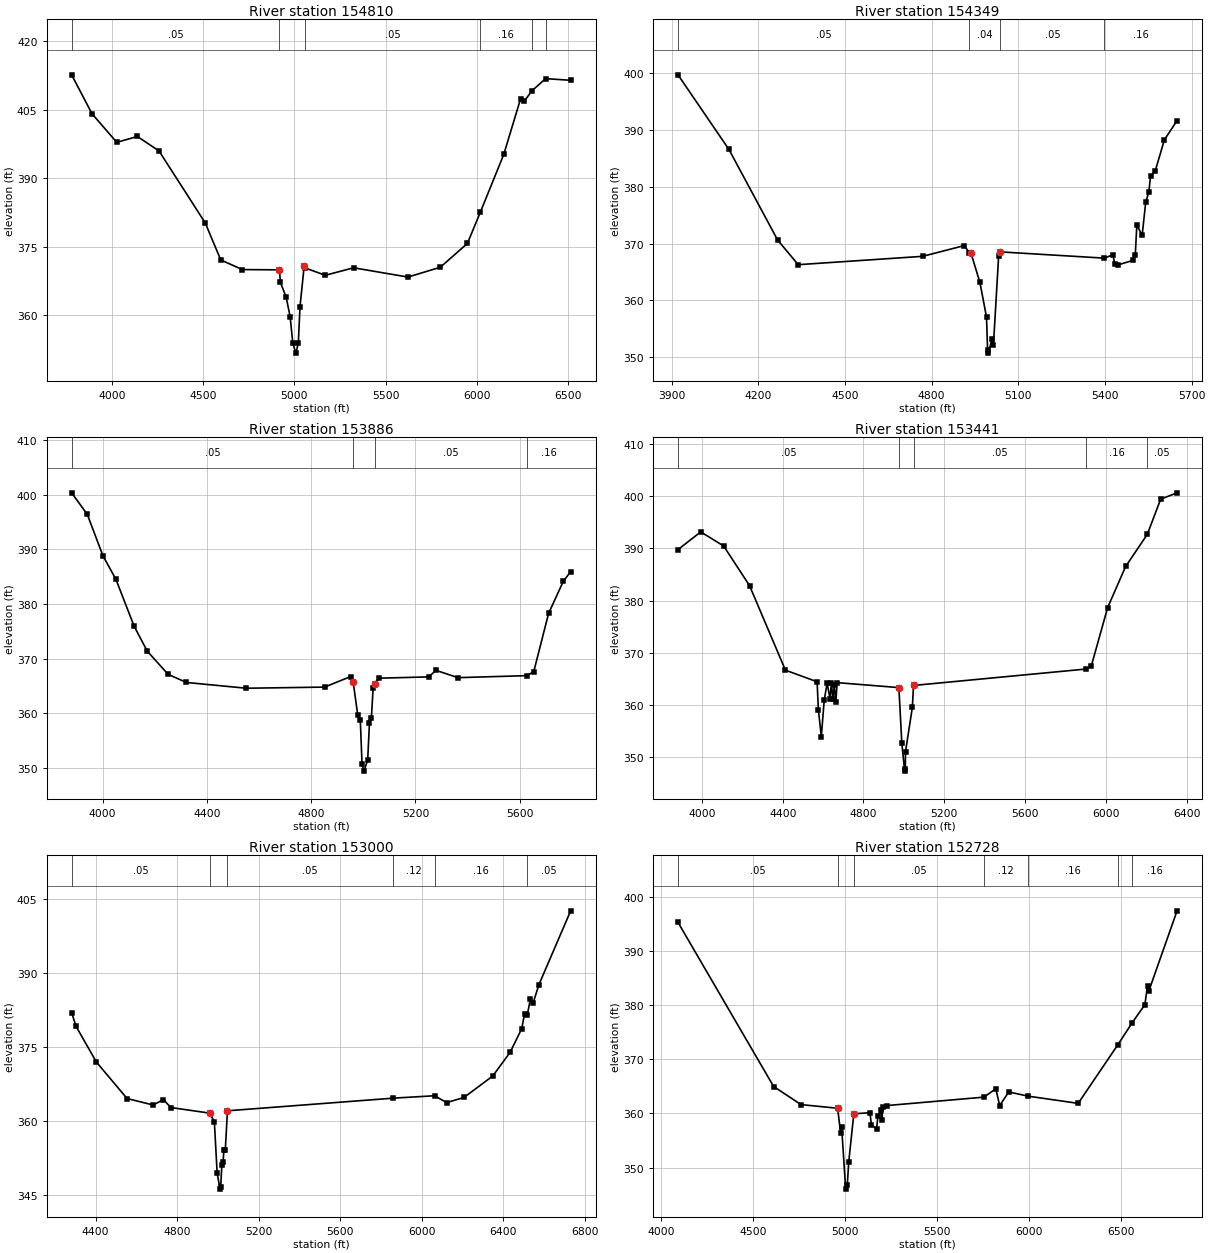
Type RM Length L Ch R = 1 ,154810  ,461,461,461
BEGIN DESCRIPTION:
BUFFALO CREEK 129.0
END DESCRIPTION:
XS GIS Cut Line= 3
      3587022.38     10531363.42        3588229.     10530777.47
      3589274.79     10529857.52
#Sta/Elev= 30
  3780.2  412.64  3892.2  404.11  4027.6  397.87  4140.4  399.15  4258.8     396
  4512.5  380.22  4597.2  372.14  4715.6  370.03  4918.7  369.97  4924.2  367.23
  4955.5  364.01  4977.7  359.64  4991.9  353.96  5008.7  351.75  5022.2  353.91
  5031.5  361.91  5054.1  370.72  5059.6  370.39  5169.7  368.78  5325.3  370.42
  5623.2  368.39  5800.6  370.55  5948.7  375.76  6020.1  382.64  6147.9  395.23
  6239.9  407.39  6260.8  406.89  6301.3  409.12  6377.2  411.81  6514.4  411.44
#Mann= 6 ,-1 , 0
  3780.2     .05       0  4918.7     .04       0  5059.6     .05       0
  6020.1     .16       0  6301.3     .05       0  6377.2     .16       0
Bank Sta=4918.7,5054.1
XS Rating Curve= 0 ,0
Exp/Cntr=0.3,0.1

Type RM Length L Ch R = 1 ,154349  ,463,463,463
BEGIN DESCRIPTION:
BUFFALO CREEK 128.0
END DESCRIPTION:
XS GIS Cut Line= 3
      3587449.57      10531510.2      3588449.61     10531110.19
      3589049.63     10530860.18
#Sta/Elev= 30
  3922.5  399.65  4098.9  386.53  4267.2  370.63  4338.5  366.29  4769.4  367.76
  4913.4  369.65  4930.9  368.35  4936.3  368.33  4967.3  363.18  4990.2  357.08
  4993.9  351.25  4996.6  350.75  5008.8   353.2  5014.2  352.26  5032.1  367.75
    5038  368.54  5398.1  367.44    5428  368.04  5433.5  366.45  5443.7  366.23
  5497.9  367.06    5505  367.96  5510.4  373.27  5528.8  371.45  5541.2  377.31
  5552.1  379.09    5558  381.91  5573.7   382.7  5605.7  388.22  5649.6  391.61
#Mann= 4 ,-1 , 0
  3922.5     .05       0  4930.9     .04       0    5038     .05       0
  5398.1     .16       0
Bank Sta=4936.3,5038
XS Rating Curve= 0 ,0
Exp/Cntr=0.3,0.1

Type RM Length L Ch R = 1 ,153886  ,445,445,445
BEGIN DESCRIPTION:
BUFFALO CREEK 127.0
END DESCRIPTION:
XS GIS Cut Line= 3
      3587449.64     10531560.19      3588549.61     10531560.19
       3589099.6     10530960.19
#Sta/Elev= 30
  3881.5  400.37  3941.5  396.43  4001.5  388.85  4051.5   384.5  4121.5   375.9
  4171.5  371.36  4251.5  367.11  4321.5  365.62  4551.5  364.56  4851.5  364.77
  4951.5   366.7  4961.5  365.63    4979  359.58  4988.6  358.74  4995.3  350.63
  5002.5  349.37  5016.9  351.42  5023.7  358.17  5031.1  359.12  5037.9  364.67
  5045.3  365.42  5059.5   366.4  5250.6  366.64    5279  367.83  5363.5   366.5
  5628.7  366.87  5653.9  367.62  5710.6  378.26  5767.4  384.18  5795.4  385.92
#Mann= 4 ,-1 , 0
  3881.5     .05       0  4961.5     .04       0  5045.3     .05       0
  5628.7     .16       0
Bank Sta=4961.5,5045.3
XS Rating Curve= 0 ,0
Exp/Cntr=0.3,0.1

Type RM Length L Ch R = 1 ,153441  ,441,441,441
BEGIN DESCRIPTION:
BUFFALO CREEK 126.0
END DESCRIPTION:
XS GIS Cut Line= 3
      3587816.69     10532665.48      3588699.61     10531960.19
      3589299.62     10530760.17
#Sta/Elev= 30
  3881.5  389.76  3994.1  393.15  4107.7  390.45  4235.8  382.85  4413.5  366.65
  4570.4  364.43  4576.8  359.04  4591.3  353.93  4605.7  360.91  4620.1  364.14
  4634.5  361.18  4640.9  364.12  4648.9  361.12  4655.3  363.86  4663.3  360.52
  4669.7  364.26  4975.5  363.31  4989.9   352.7  5004.1   347.3  5007.3   347.8
  5008.3  351.03  5042.3  359.55  5047.9  363.72  5900.5  366.86  5928.3  367.43
  6009.4  378.65  6098.8  386.54  6205.5  392.66  6272.1  399.43  6353.2  400.64
#Mann= 5 ,-1 , 0
  3881.5     .05       0  4975.5     .04       0  5047.9     .05       0
  5900.5     .16       0  6205.5     .05       0
Bank Sta=4975.5,5047.9
XS Rating Curve= 0 ,0
Exp/Cntr=0.3,0.1

Type RM Length L Ch R = 1 ,153000  ,272,272,272
BEGIN DESCRIPTION:
BUFFALO CREEK 125.0
END DESCRIPTION:
XS GIS Cut Line= 3
      3588249.59      10532810.2      3588849.61     10532360.19
      3590049.63     10531160.17
#Sta/Elev= 30
  4282.3  382.02  4304.2  379.21  4404.2  371.96  4554.2  364.59  4682.3  363.27
  4732.3  364.37  4768.8  362.76  4960.4  361.62  4982.3  359.81  4995.9  349.44
  5010.2  346.21  5013.4  346.71  5018.8  351.04    5025  351.73  5029.2  354.23
  5035.9  354.23  5046.5   362.1  5858.4  364.66  6062.3  365.15  6121.3  363.76
  6206.1   364.8  6347.5  369.16  6432.4  373.96    6489  378.72  6503.1  381.68
    6517  381.58  6531.4  384.68  6545.5  384.01  6573.8   387.7  6729.4  402.66
#Mann= 6 ,-1 , 0
  4282.3     .05       0  4960.4     .04       0  5046.5     .05       0
  5858.4     .12       0  6062.3     .16       0    6517     .05       0
Bank Sta=4960.4,5046.5
XS Rating Curve= 0 ,0
Exp/Cntr=0.3,0.1

Type RM Length L Ch R = 1 ,152728  ,223,223,223
BEGIN DESCRIPTION:
Mapping XS 626b89b1
END DESCRIPTION:
XS GIS Cut Line= 3
      3588103.73     10533055.96       3588986.5       10532595.
      3590330.28      10531525.2
#Sta/Elev= 30
  4090.7  395.25  4610.8  364.95  4759.7  361.61  4958.5  360.94  4974.9  356.43
  4980.5   357.4  5002.4  346.01  5011.1  346.73  5019.1  351.08  5046.8  359.92
  5134.9  360.11  5141.7  357.93  5170.1  357.07  5178.1   359.6  5192.5  360.55
  5198.9  358.83  5205.6  361.12  5227.8  361.44  5754.4  362.99  5818.8  364.54
  5839.6  361.44  5889.2  363.95  5992.8  363.18  6266.5  361.84  6480.4  372.56
  6558.8  376.65  6629.2  380.06  6643.6  383.54    6650  382.52  6804.2  397.38
#Mann= 7 ,-1 , 0
  4090.7     .05       0  4958.5     .04       0  5046.8     .05       0
  5754.4     .12       0  5992.8     .16       0  6480.4     .05       0
  6558.8     .16       0
Bank Sta=4958.5,5046.8
XS Rating Curve= 0 ,0
Exp/Cntr=0.3,0.1

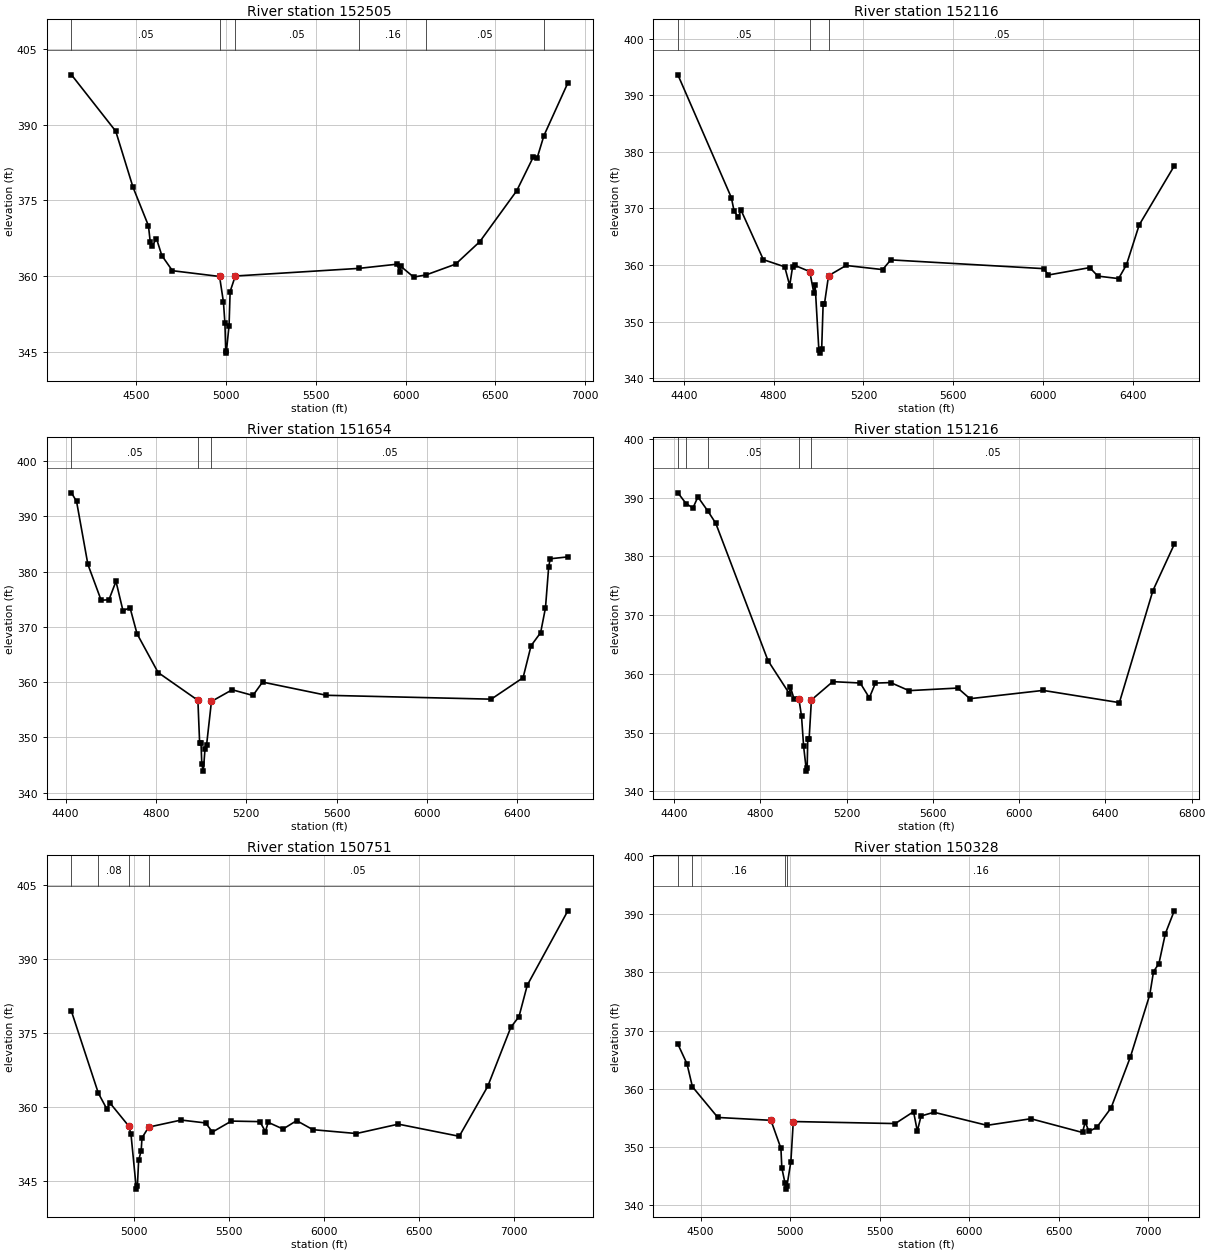
Type RM Length L Ch R = 1 ,152505  ,389,389,389
BEGIN DESCRIPTION:
BUFFALO CREEK 124.0
END DESCRIPTION:
XS GIS Cut Line= 3
      3588229.83     10533277.76       3589199.6     10532716.77
      3590452.07      10531651.3
#Sta/Elev= 30
    4139  399.87  4385.5   388.7  4481.6  377.61  4567.7  369.97  4577.7  366.74
  4589.3     366  4612.4  367.43  4642.3  364.06  4701.2  361.06  4963.8  359.92
  4985.4  354.85  4993.6   350.7  4998.1  345.23  5000.9  344.73  5016.7   350.2
  5022.7  356.94  5051.4  360.01  5739.4  361.52  5952.4  362.35  5966.7  360.76
  5973.3  361.93  6044.7   359.8  6114.4  360.23  6278.6  362.36  6413.7  366.83
    6619   376.9  6711.3  383.59  6732.1  383.32  6770.5  387.82  6903.7  398.26
#Mann= 6 ,-1 , 0
    4139     .05       0  4963.8     .04       0  5051.4     .05       0
  5739.4     .16       0  6114.4     .05       0  6770.5     .16       0
Bank Sta=4963.8,5051.4
XS Rating Curve= 0 ,0
Exp/Cntr=0.3,0.1

Type RM Length L Ch R = 1 ,152116  ,462,462,462
BEGIN DESCRIPTION:
BUFFALO CREEK 123.0
END DESCRIPTION:
XS GIS Cut Line= 3
      3588499.64     10533460.18      3589099.61     10533210.19
      3590299.59      10532210.2
#Sta/Elev= 30
  4373.3  393.62  4611.6   371.9  4624.1  369.46  4642.5  368.48  4654.9  369.67
  4754.1  360.94  4849.4  359.67  4871.6  356.35  4884.1  359.59  4893.3  359.94
    4961  358.83  4979.4  354.97  4984.8  356.48  5001.6  344.91  5008.4  344.41
  5014.1  345.17  5020.6  353.14  5026.5  353.14  5044.7   358.1  5122.9  359.91
  5285.6  359.18    5322   360.9  6002.8  359.35  6024.9  358.23  6208.5  359.53
  6244.9  358.03  6337.3  357.59  6372.5  360.05  6429.1  367.08  6585.3  377.51
#Mann= 3 , 0 , 0
  4373.3     .05       0    4961     .04       0  5044.7     .05       0
Bank Sta=4961,5044.7
XS Rating Curve= 0 ,0
Exp/Cntr=0.3,0.1

Type RM Length L Ch R = 1 ,151654  ,438,438,438
BEGIN DESCRIPTION:
BUFFALO CREEK 122.0
END DESCRIPTION:
XS GIS Cut Line= 3
      3588649.57      10533810.2      3589199.61     10533660.19
       3590399.6      10532560.2
#Sta/Elev= 30
  4425.8  394.24  4448.3  392.68  4498.4   381.3  4557.1  374.81  4591.7  374.89
  4622.8  378.23  4653.9   372.9    4685  373.47  4716.1  368.74  4809.4  361.73
  4985.6   356.7  4993.3  348.96  4999.3  348.96    5003  345.12  5009.6  343.89
  5017.2  347.94    5024  348.59  5045.6   356.5  5137.4  358.61  5229.3  357.58
  5271.9     360  5554.9  357.61  6284.4  356.91  6425.6  360.79    6461  366.58
  6503.3  368.94  6524.8  373.43    6539  380.86  6545.8  382.31  6623.8  382.65
#Mann= 3 , 0 , 0
  4425.8     .05       0  4985.6     .04       0  5045.6     .05       0
Bank Sta=4985.6,5045.6
XS Rating Curve= 0 ,0
Exp/Cntr=0.3,0.1

Type RM Length L Ch R = 1 ,151216  ,465,465,465
BEGIN DESCRIPTION:
BUFFALO CREEK 121.0
END DESCRIPTION:
XS GIS Cut Line= 3
      3588800.19     10534313.93      3589349.61     10534060.19
      3590549.58     10532860.22
#Sta/Elev= 30
  4417.1  390.81  4454.8  388.99  4486.9  388.22  4509.8  390.11  4556.4  387.69
  4592.7  385.63    4835  362.25  4933.7  356.65  4939.2  357.73  4956.2  355.68
  4978.2  355.77  4990.6  352.75  5000.3  347.64  5013.3  343.44  5016.6  343.94
  5019.5  348.94  5025.8  348.94  5036.4  355.56  5135.4  358.67  5262.7  358.44
  5305.1  355.92  5333.4  358.43  5404.1  358.51    5489  357.14  5715.3  357.58
  5771.8  355.77  6111.2  357.18  6464.8   355.1  6620.3  374.16  6719.3  382.04
#Mann= 5 ,-1 , 0
  4417.1     .05       0  4454.8     .08       0  4556.4     .05       0
  4978.2     .04       0  5036.4     .05       0
Bank Sta=4978.2,5036.4
XS Rating Curve= 0 ,0
Exp/Cntr=0.3,0.1

Type RM Length L Ch R = 1 ,150751  ,423,423,423
BEGIN DESCRIPTION:
BUFFALO CREEK 120.0
END DESCRIPTION:
XS GIS Cut Line= 3
      3589099.65     10534610.18      3589449.61     10534510.19
      3590799.63     10532710.16
#Sta/Elev= 30
    4671  379.38  4812.5  362.82  4858.2  359.55  4872.5  360.89  4972.6  356.16
  4984.3  354.53  5012.6  343.39  5018.1  343.99  5024.6   349.2  5038.1  351.18
  5042.3  353.78  5077.7  355.95  5248.5  357.38  5377.7  356.79  5413.1  354.95
  5513.1  357.17  5663.1  357.06  5692.3  355.05  5706.8  356.92    5785  355.56
  5856.8  357.26  5942.3  355.43  6171.4  354.65  6392.3  356.55  6713.1  354.09
  6863.1   364.2    6985  376.18  7027.7  378.32  7071.4  384.69    7285  399.75
#Mann= 4 ,-1 , 0
    4671     .05       0  4812.5     .08       0  4972.6     .04       0
  5077.7     .05       0
Bank Sta=4972.6,5077.7
XS Rating Curve= 0 ,0
Exp/Cntr=0.3,0.1

Type RM Length L Ch R = 1 ,150328  ,433,433,433
BEGIN DESCRIPTION:
BUFFALO CREEK 119.0
END DESCRIPTION:
XS GIS Cut Line= 3
      3589149.61     10534860.19      3589749.61     10534760.19
       3590949.6      10532960.2
#Sta/Elev= 30
  4373.3  367.67    4424   364.3  4454.4  360.36  4596.3  355.09  4892.9   354.6
  4948.6  349.79  4953.7  346.43  4971.4  343.82  4978.8  342.79    4982  343.29
  5004.1  347.49  5017.6  354.39    5587  354.04  5689.2  356.08  5710.2  352.76
  5731.2  355.34  5803.3  355.98  6099.3  353.74  6344.2  354.87  6632.6  352.51
  6647.6   354.3  6668.7  352.69  6712.2  353.39  6791.9  356.71    6900  365.47
  7008.2  376.15  7029.2  380.12  7059.3   381.5  7095.3  386.64  7144.9  390.55
#Mann= 4 ,-1 , 0
  4373.3     .05       0  4454.4     .16       0  4971.4     .07       0
    4982     .16       0
Bank Sta=4892.9,5017.6
XS Rating Curve= 0 ,0
Exp/Cntr=0.3,0.1

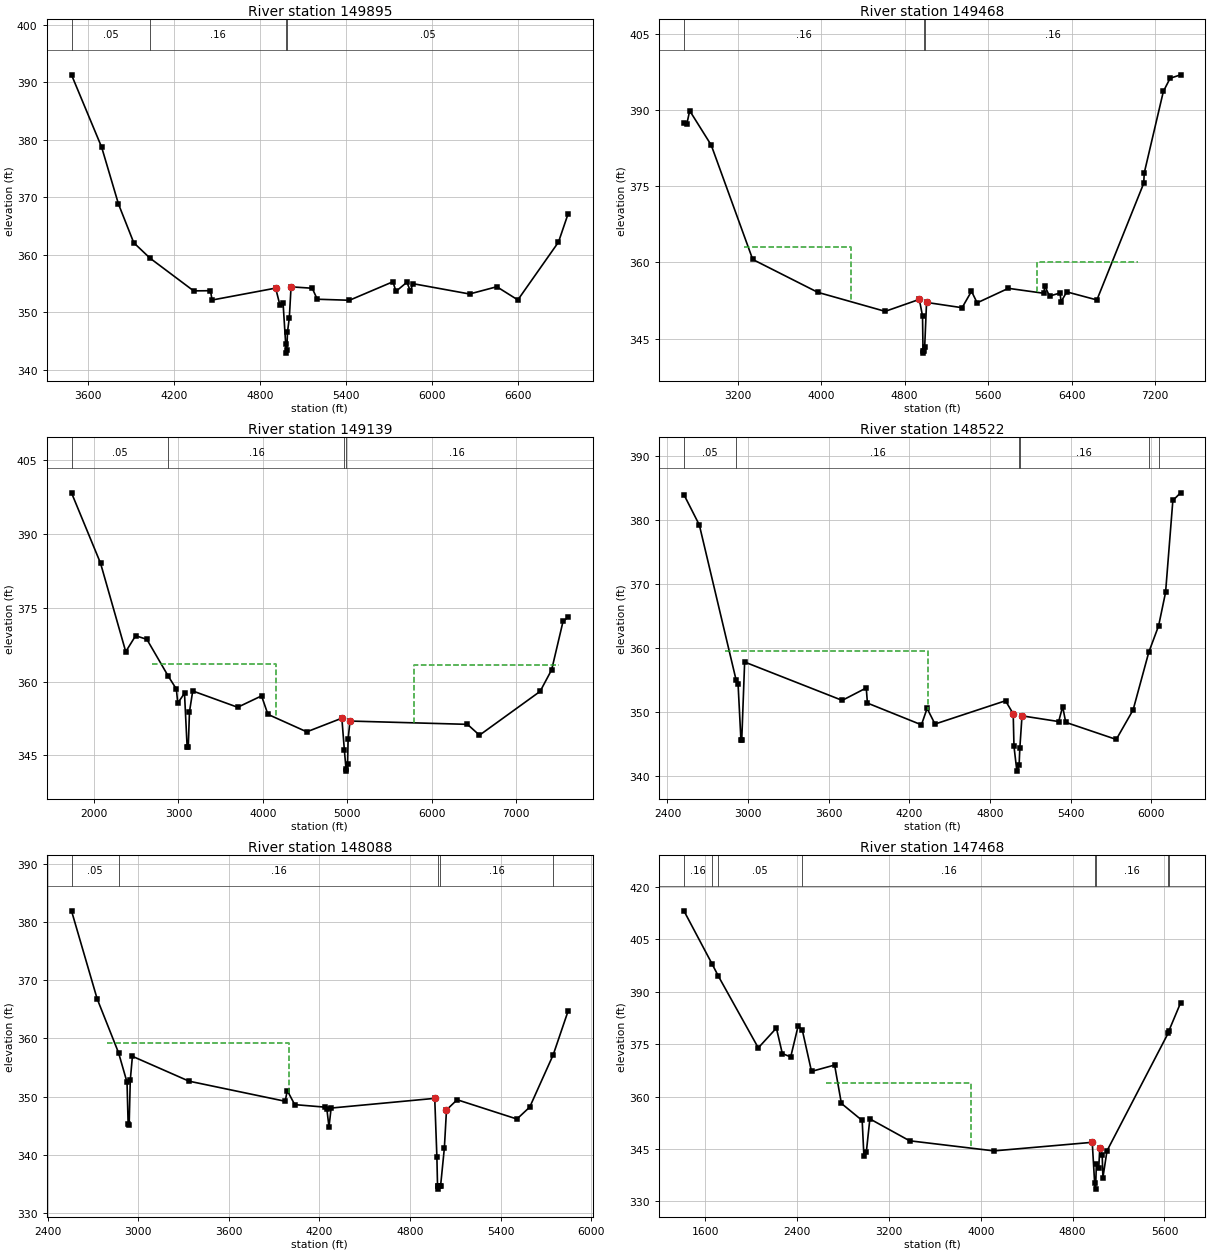
Type RM Length L Ch R = 1 ,149895  ,427,427,427
BEGIN DESCRIPTION:
BUFFALO CREEK 118.0
END DESCRIPTION:
XS GIS Cut Line= 3
      3588628.35     10535386.84      3590099.61     10535010.19
      3590849.61     10533210.19
#Sta/Elev= 30
  3484.4  391.27    3695   378.7  3812.2  368.85  3919.2  362.11  4032.8  359.43
  4337.5  353.75  4454.8  353.78  4466.3  352.16  4910.2  354.23  4939.3  351.33
  4961.8   351.7  4980.1  344.61    4985  342.94  4988.3  343.44  4992.8   346.6
  5005.8  349.12  5017.7  354.45  5165.6  354.21  5200.8   352.3  5425.6  352.12
  5728.9  355.33  5750.6  353.67    5827  355.25  5850.8  353.71  5869.2     355
  6264.6  353.21  6454.8  354.47  6601.6  352.18  6885.4  362.22  6953.1  367.17
#Mann= 4 ,-1 , 0
  3484.4     .05       0  4032.8     .16       0  4980.1     .07       0
  4988.3     .05       0
Bank Sta=4910.2,5017.7
XS Rating Curve= 0 ,0
Exp/Cntr=0.3,0.1

Type RM Length L Ch R = 1 ,149468  ,329,329,329
BEGIN DESCRIPTION:
BUFFALO CREEK 117.0
END DESCRIPTION:
XS GIS Cut Line= 3
      3588718.59     10536747.95      3590449.61     10535260.19
      3591049.61     10532860.17
#Sta/Elev= 30
  2686.1  387.43  2713.8  387.28  2741.6  389.88  2947.9   383.1  3345.1  360.58
  3968.4   354.1  4613.6  350.35  4940.6  352.71  4971.2  349.43  4975.9  342.62
  4978.7  342.12  4981.9  342.62  4991.8   343.3  5009.8  352.11    5350  351.07
  5440.2  354.31  5494.3  352.03  5793.2  354.89  6133.4  353.91  6141.1  355.39
  6187.5  353.36    6288  353.97  6298.3  352.26  6352.4  354.19    6641   352.6
  7089.4  375.58  7094.6  377.63  7277.6  393.69    7342  396.28  7442.5  396.96
#Mann= 3 ,-1 , 0
  2686.1     .16       0  4981.9     .07       0  4991.8     .16       0
#XS Ineff= 2 ,-1
 3257.95 4284.09  362.98 6067.05 7038.64  360.13
Permanent Ineff=
       F       F
Bank Sta=4940.6,5009.8
XS Rating Curve= 0 ,0
Exp/Cntr=0.3,0.1

Type RM Length L Ch R = 1 ,149139  ,617,617,617
BEGIN DESCRIPTION:
BUFFALO CREEK 116.0
END DESCRIPTION:
XS GIS Cut Line= 3
      3589288.03      10538192.4      3590836.64     10535171.57
      3592371.38     10533206.27
#Sta/Elev= 30
  1731.8  398.34    2076  384.05  2374.8  366.08  2492.2  369.32  2625.4  368.58
  2880.5  361.06  2974.9  358.49  2991.5  355.63  3071.5  357.64  3102.5  346.75
  3116.5  346.81  3130.3  353.86  3169.1   358.1  3701.8  354.79  3984.8   357.1
  4060.4  353.35  4521.2   349.8    4937  352.57  4966.8  346.07    4986  342.32
  4988.7  341.82  5004.4  343.27  5011.2  348.32  5033.4  351.99  6425.8  351.32
  6568.7  349.12  7287.8  358.02  7424.3  362.41  7559.1  372.22    7620  373.09
#Mann= 4 ,-1 , 0
  1731.8     .05       0  2880.5     .16       0  4966.8     .07       0
    4986     .16       0
#XS Ineff= 2 ,-1
 2686.36 4153.98  363.58 5792.61 7514.77  363.28
Permanent Ineff=
       F       F
Bank Sta=4937,5033.4
XS Rating Curve= 0 ,0
Exp/Cntr=0.3,0.1

Type RM Length L Ch R = 1 ,148522  ,434,434,434
BEGIN DESCRIPTION:
BUFFALO CREEK 115.0
END DESCRIPTION:
XS GIS Cut Line= 3
      3589949.58     10537410.23      3591349.61     10535410.19
      3592449.65     10534810.17
#Sta/Elev= 30
  2522.2  383.94  2636.9  379.21  2910.7  355.01  2925.1  354.38  2946.4  345.66
  2952.5  345.72  2973.9  357.84  3699.7  351.86  3878.5   353.8  3887.2  351.44
  4289.1  348.05    4331  350.61  4389.9  348.17  4914.3   351.8  4971.6  349.77
  4977.3   344.7  4998.9  340.83  5015.3  341.71    5021  344.44  5037.1  349.45
  5309.6  348.56  5339.5  350.89  5362.2  348.44  5738.1  345.77  5863.4  350.37
  5979.7  359.34  6053.3   363.5    6105  368.71  6159.1  383.03  6216.6  384.22
#Mann= 6 ,-1 , 0
  2522.2     .05       0  2910.7     .16       0  5015.3     .07       0
    5021     .16       0  5979.7      .1       0  6053.3     .05       0
#XS Ineff= 1 ,-1
 2829.55 4336.36  359.59
Permanent Ineff=
       F
Bank Sta=4971.6,5037.1
XS Rating Curve= 0 ,0
Exp/Cntr=0.3,0.1

Type RM Length L Ch R = 1 ,148088  ,620,620,620
BEGIN DESCRIPTION:
BUFFALO CREEK 114.0
END DESCRIPTION:
XS GIS Cut Line= 3
      3590099.64     10537410.16      3591749.61     10535610.19
       3592349.6     10535010.19
#Sta/Elev= 30
  2557.5  381.98  2727.3  366.84  2869.2  357.54  2925.3  352.47  2932.7  345.29
  2939.5  345.16  2946.9  352.82    2961  356.93  3335.9  352.65  3972.9  349.19
  3987.1  351.02  4036.4  348.61    4235  348.18  4249.2  347.85  4263.3  344.75
  4277.5  348.02  4963.8  349.69    4978  339.67  4982.4  334.56  4985.2  334.06
  4988.4  334.56  4995.9  334.67  5002.8  334.67  5027.6  341.13  5041.7   347.7
  5112.4  349.45  5508.4  346.13  5593.2  348.19  5748.8   357.2  5847.8  364.76
#Mann= 5 ,-1 , 0
  2557.5     .05       0  2869.2     .16       0  4988.4     .07       0
  4995.9     .16       0  5748.8      .1       0
#XS Ineff= 1 ,-1
 2790.34 3995.45  359.29
Permanent Ineff=
       F
Bank Sta=4963.8,5041.7
XS Rating Curve= 0 ,0
Exp/Cntr=0.3,0.1

Type RM Length L Ch R = 1 ,147468  ,464,464,464
BEGIN DESCRIPTION:
BUFFALO CREEK 113.0
END DESCRIPTION:
XS GIS Cut Line= 3
        3590367.     10538820.04      3591462.94      10537083.9
      3592749.63     10535210.16
#Sta/Elev= 30
  1414.3  413.08  1661.8  397.76    1715  394.37  2062.1  373.91  2219.8  379.56
  2271.5  372.28  2344.5  371.32  2408.1  380.02  2444.5  379.14  2525.7  367.18
  2726.9     369  2785.9  358.03    2967  353.15  2982.2  342.91  3003.4  344.19
    3034  353.61    3380  347.35  4114.8  344.46    4971  346.91    4992  335.16
  5000.1  333.53  5006.9  340.75  5027.8  339.61  5036.6  345.26  5057.6  343.35
  5063.7  336.78  5099.5  344.48  5631.4  378.06  5638.2  378.75  5740.4  386.77
#Mann= 8 ,-1 , 0
  1414.3     .16       0  1661.8      .1       0    1715     .05       0
  2444.5     .16       0    4992     .07       0  5000.1     .16       0
  5631.4      .1       0  5638.2     .05       0
#XS Ineff= 1 ,-1
 2647.73 3917.61  363.93
Permanent Ineff=
       F
Bank Sta=4971,5036.6
XS Rating Curve= 0 ,0
Exp/Cntr=0.3,0.1

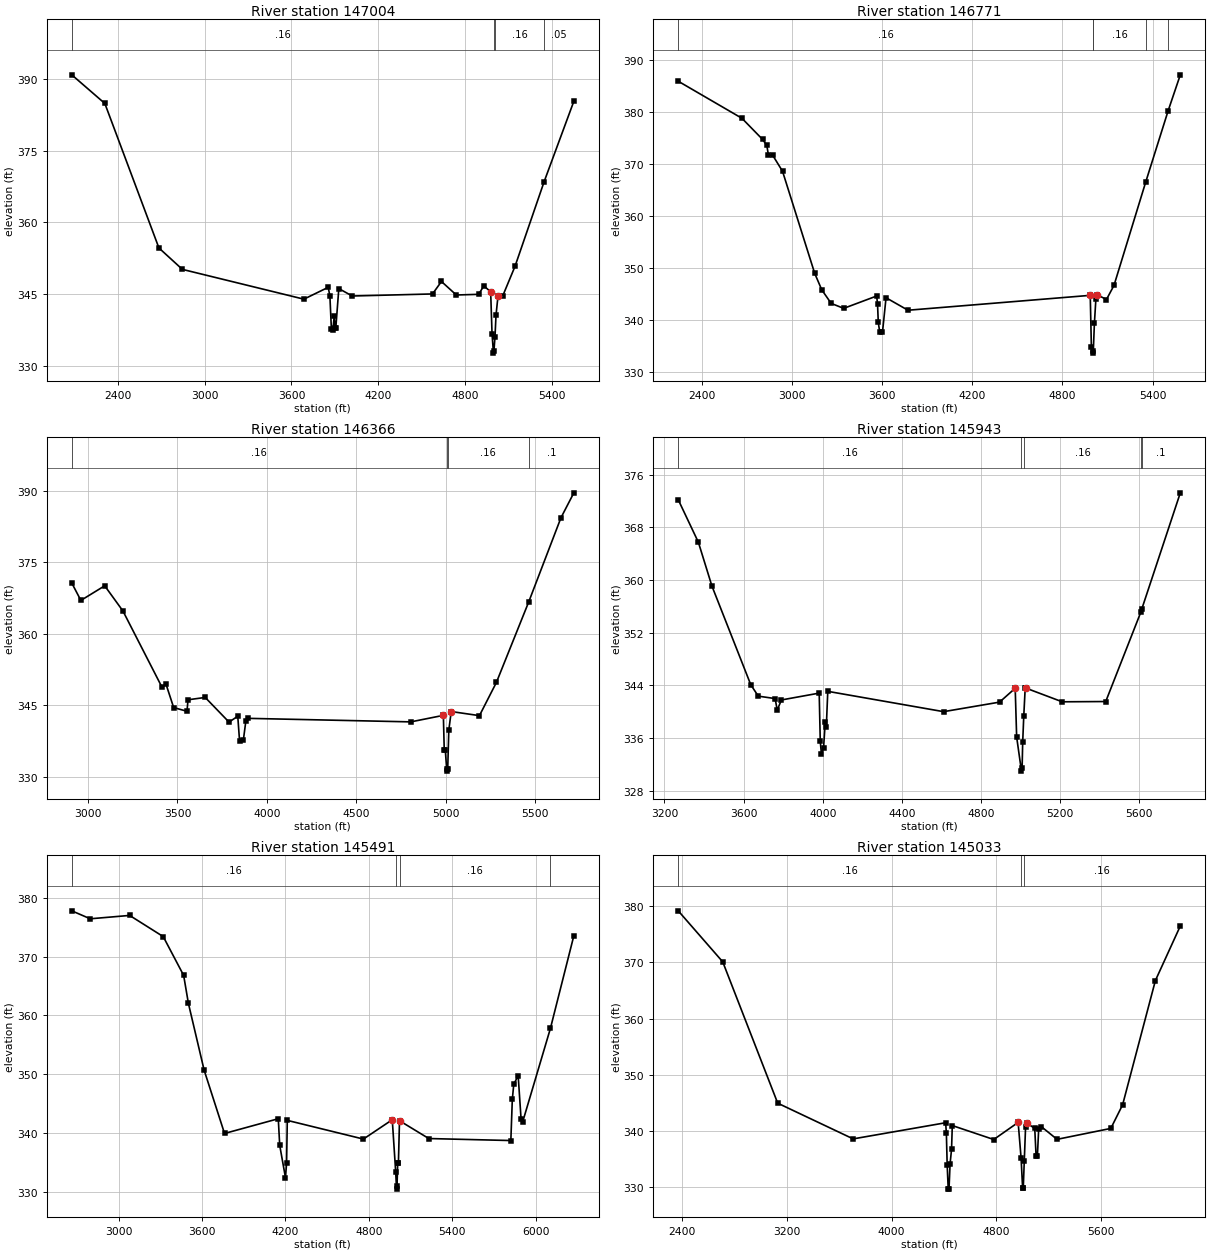
Type RM Length L Ch R = 1 ,147004  ,233,233,233
BEGIN DESCRIPTION:
BUFFALO CREEK 112.0
END DESCRIPTION:
XS GIS Cut Line= 3
      3591734.19     10538646.42       3592417.8     10537420.27
      3592899.62     10535410.15
#Sta/Elev= 30
  2081.2  390.82  2309.8  384.84  2683.7  354.66  2845.8  350.19  3685.8  343.97
  3853.8  346.44  3865.6  344.67  3875.9  337.76  3886.2  337.55  3895.8  340.47
    3901  338.05  3906.7  338.03  3927.3  346.18  4019.9  344.63  4575.1  345.06
  4636.8  347.66  4739.7  344.84    4894  344.98    4930  346.75  4977.1   345.5
  4986.5  336.76  4996.5   332.7  4999.8   333.2    5007  336.13    5014  340.62
  5027.6  344.56  5061.1  344.69  5145.2  350.81  5346.4  368.48  5552.1   385.3
#Mann= 4 ,-1 , 0
  2081.2     .16       0  4999.8     .08       0    5007     .16       0
  5346.4     .05       0
Bank Sta=4977.1,5027.6
XS Rating Curve= 0 ,0
Exp/Cntr=0.3,0.1

Type RM Length L Ch R = 1 ,146771  ,405,405,405
BEGIN DESCRIPTION:
BUFFALO CREEK 111.0
END DESCRIPTION:
XS GIS Cut Line= 3
      3593784.99     10538635.57      3592999.61     10536010.19
      3592949.61      10535410.2
#Sta/Elev= 30
  2242.4  385.83  2666.6  378.71  2804.2  374.64  2832.1  373.51    2843  371.59
  2870.4  371.65  2936.6  368.54  3150.9  348.92  3197.9  345.76  3260.7  343.15
    3344   342.2  3563.2  344.57    3569  343.12  3574.2  339.49  3584.1  337.59
  3602.1  337.62  3625.8  344.24  3771.9  341.84  4985.2   344.7  4992.8  334.72
  5002.6   333.6  5005.8   334.1  5012.8   339.3  5022.9  344.05  5032.9  344.79
  5093.1   343.9  5143.3  346.61    5354  366.42  5503.7  380.15  5584.8  387.06
#Mann= 5 ,-1 , 0
  2242.4     .16       0  5002.6     .07       0  5005.8     .16       0
    5354      .1       0  5503.7     .05       0
Bank Sta=4985.2,5032.9
XS Rating Curve= 0 ,0
Exp/Cntr=0.3,0.1

Type RM Length L Ch R = 1 ,146366  ,423,423,423
BEGIN DESCRIPTION:
BUFFALO CREEK 110.0
END DESCRIPTION:
XS GIS Cut Line= 3
       3594449.6     10537760.17      3593399.61     10535960.19
      3592999.59     10535360.15
#Sta/Elev= 30
  2909.6  370.67  2960.4  367.01  3093.6  370.08  3195.3   364.8  3414.4  348.73
  3435.9  349.45  3478.9  344.51  3553.3  343.74  3559.1  346.15  3655.1  346.64
  3788.2  341.46    3837   342.7  3846.9  337.56  3868.4  337.74  3882.1  341.67
  3895.7  342.25  4803.7  341.51  4985.6  342.88  4990.6  335.54  4996.5  335.54
    5004  331.67  5006.7  331.17    5010  331.67    5016  339.75  5029.5  343.68
  5187.2  342.82  5281.9  349.79  5462.2  366.67  5642.4  384.35  5714.6   389.6
#Mann= 4 ,-1 , 0
  2909.6     .16       0    5004     .04       0    5010     .16       0
  5462.2      .1       0
#XS Ineff= 1 ,-1
 3408.81 3577.84  346.07
Permanent Ineff=
       F
Bank Sta=4985.6,5029.5
XS Rating Curve= 0 ,0
Exp/Cntr=0.3,0.1

Type RM Length L Ch R = 1 ,145943  ,452,452,452
BEGIN DESCRIPTION:
BUFFALO CREEK 109.0
END DESCRIPTION:
XS GIS Cut Line= 3
      3594399.61     10537510.18      3593799.61     10535860.19
      3593199.63      10535360.2
#Sta/Elev= 30
  3269.9  372.21  3371.6  365.75  3440.1  359.09  3636.3  344.09  3674.2  342.35
  3759.4  341.98    3770  340.23  3791.3  341.77  3982.1  342.81  3987.5  335.48
  3993.5   333.5  4004.1  334.49  4012.7   338.4  4018.1   337.7  4025.4  343.08
  4610.6  339.99  4893.3  341.44  4972.4  343.55  4979.7  336.14  5004.1  330.95
  5007.3  331.45  5010.3  335.39  5015.6  339.28  5022.9  343.58  5025.6  343.58
  5209.8  341.49  5429.8  341.53  5608.1   355.2  5611.4  355.54  5806.6  373.26
#Mann= 5 ,-1 , 0
  3269.9     .16       0  5004.1     .04       0  5015.6     .16       0
  5608.1     .16       0  5611.4      .1       0
#XS Ineff= 1 ,-1
 5031.82  5514.2  343.33
Permanent Ineff=
       F
Bank Sta=4972.4,5025.6
XS Rating Curve= 0 ,0
Exp/Cntr=0.3,0.1

Type RM Length L Ch R = 1 ,145491  ,458,458,458
BEGIN DESCRIPTION:
BUFFALO CREEK 108.0
END DESCRIPTION:
XS GIS Cut Line= 3
       3594880.9     10538071.28      3594249.61     10535810.19
      3594649.62     10534610.17
#Sta/Elev= 30
  2663.1  377.75    2796   376.4  3079.5  376.97  3321.1  373.38  3468.1   366.8
  3502.3  362.05  3615.2  350.75  3762.2  339.99  4148.9  342.49  4159.3  337.98
  4200.8  332.49  4208.6  334.94  4213.8  342.21  4761.5  339.04  4969.1  342.32
  4993.6  333.52    5000  330.55  5003.3  331.05  5008.1  334.94  5013.3  334.94
  5021.2  342.15    5232  339.13  5822.3  338.79  5832.9  345.78  5843.4  348.34
    5875  349.79  5896.1  342.36  5906.6  341.89  6106.9   357.8  6275.6  373.53
#Mann= 4 ,-1 , 0
  2663.1     .16       0  4993.6     .04       0  5021.2     .16       0
  6106.9     .05       0
#XS Ineff= 1 ,-1
 5865.91    6025  345.77
Permanent Ineff=
       F
Bank Sta=4969.1,5021.2
XS Rating Curve= 0 ,0
Exp/Cntr=0.3,0.1

Type RM Length L Ch R = 1 ,145033  ,568,568,568
BEGIN DESCRIPTION:
BUFFALO CREEK 107.0
END DESCRIPTION:
XS GIS Cut Line= 3
      3595846.61     10538125.55      3594699.61     10535760.19
      3594699.61     10534560.18
#Sta/Elev= 30
    2373  379.17  2712.4   370.1  3131.5  344.98    3707  338.63  4412.3   341.5
  4417.8  339.62  4423.9  333.99  4431.9   329.7  4437.9   329.7  4446.1  334.21
  4457.2  336.76    4463     341    4779  338.52  4965.2  341.56  4987.7  335.18
    4999  329.97  5004.3  329.97  5011.8  334.65  5021.8  340.76  5031.8  341.43
  5091.8  340.49  5101.8  335.64  5111.8  335.54  5121.8   340.4  5141.8  340.81
  5261.8  338.55  5671.8  340.49  5761.8  344.69  6011.8  366.78  6201.8  376.48
#Mann= 3 ,-1 , 0
    2373     .16       0  4987.7     .04       0  5011.8     .16       0
Bank Sta=4965.2,5031.8
XS Rating Curve= 0 ,0
Exp/Cntr=0.3,0.1

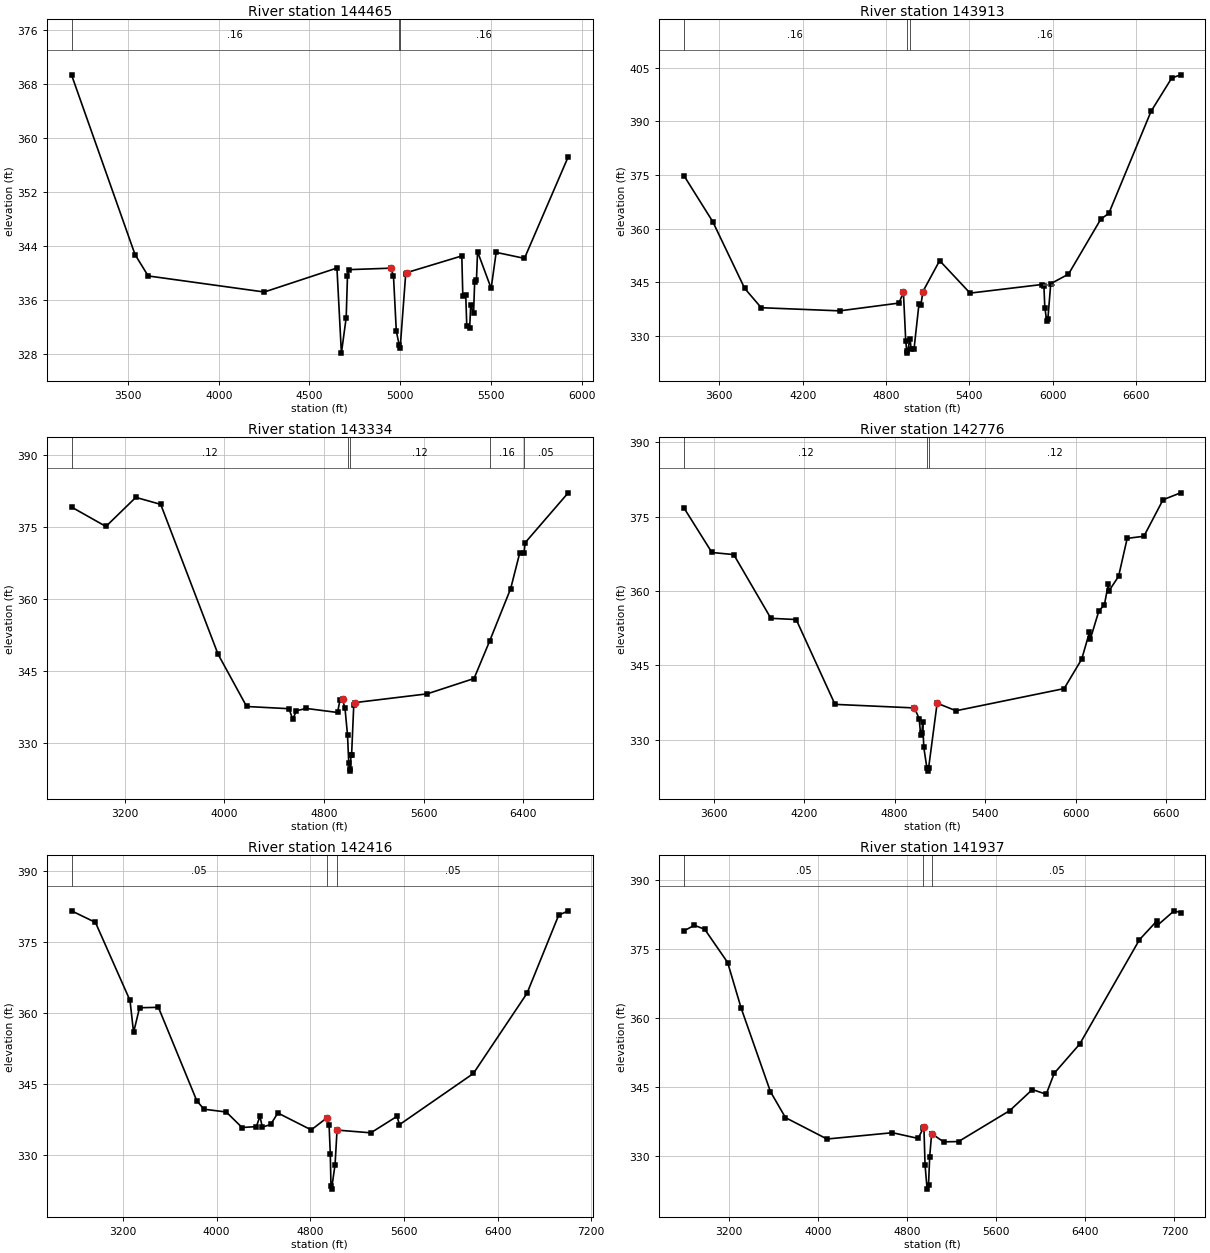
Type RM Length L Ch R = 1 ,144465  ,552,552,552
BEGIN DESCRIPTION:
BUFFALO CREEK 106.0
END DESCRIPTION:
XS GIS Cut Line= 3
      3596199.62     10537210.21      3595249.61     10535660.19
      3594799.59     10534860.16
#Sta/Elev= 30
  3189.2   369.4  3539.2  342.78  3611.5  339.62    4251  337.24  4651.3  340.79
  4675.8  328.19  4702.2  333.44  4709.3  339.58  4715.2  340.55  4948.5  340.77
  4962.7  339.63  4978.2  331.46  4993.6  329.46  4999.5  328.95  5030.1  339.93
  5036.8  340.12    5339  342.58  5344.7  336.59  5360.6  336.86  5366.4  332.25
  5382.3  331.84    5388  335.25    5404  334.14  5409.7  338.69  5419.9  339.06
  5425.7  343.22  5500.6  337.79  5528.3  343.11  5684.1  342.22  5925.1  357.26
#Mann= 3 ,-1 , 0
  3189.2     .16       0  4993.6     .04       0  4999.5     .16       0
#XS Ineff= 1 ,-1
 5336.93  5551.7  342.28
Permanent Ineff=
       F
Bank Sta=4948.5,5036.8
XS Rating Curve= 0 ,0
Exp/Cntr=0.3,0.1

Type RM Length L Ch R = 1 ,143913  ,579,579,579
BEGIN DESCRIPTION:
BUFFALO CREEK 105.0
END DESCRIPTION:
XS GIS Cut Line= 3
      3596299.62     10537160.23      3595799.61     10535610.19
      3594499.63     10534160.21
#Sta/Elev= 30
  3344.3  374.84  3552.7  361.89  3782.2  343.23  3901.2  337.82  4465.8  336.94
  4892.9  339.12  4924.9  342.16  4941.5  328.62  4948.7   325.6  4951.5   325.1
    4973  329.14  4980.1  326.35    5001  326.13  5036.9  338.86  5051.1  338.64
  5065.3  342.36  5185.7  351.01  5404.7  341.91    5922  344.32  5936.3     344
    5943  337.86  5957.2  334.01  5964.7  334.53  5985.6  344.55  6113.4  347.22
  6346.7  362.67  6403.5  364.22  6707.7  392.82  6856.5  402.14  6920.4  403.05
#Mann= 3 ,-1 , 0
  3344.3     .16       0  4948.7     .04       0    4973     .16       0
#XS Ineff= 1 ,-1
 5929.55 6018.18  344.16
Permanent Ineff=
       F
Bank Sta=4924.9,5065.3
XS Rating Curve= 0 ,0
Exp/Cntr=0.3,0.1

Type RM Length L Ch R = 1 ,143334  ,558,558,558
BEGIN DESCRIPTION:
BUFFALO CREEK 104.0
END DESCRIPTION:
XS GIS Cut Line= 3
      3596432.56      10537756.6      3596349.61     10535510.19
      3596031.09     10533796.18
#Sta/Elev= 30
  2770.7  379.18  3047.3  375.13  3287.5   381.2  3487.6  379.74  3947.9  348.49
  4178.1  337.55  4518.3  337.09  4548.3  334.88  4578.3  336.68  4658.4  337.14
  4908.6   336.3  4928.6     339  4948.6  339.02  4968.6  337.14  4988.6  331.58
  4998.6  325.83  5008.4  324.06  5011.6  324.56  5016.1  327.34  5021.2  327.34
    5039  337.96    5045  338.35  5628.9  340.19  6005.3  343.39  6129.8  351.15
    6300  362.18  6371.4  369.49  6406.8  369.52  6415.8  371.73    6762  382.15
#Mann= 5 ,-1 , 0
  2770.7     .12       0  4988.6     .03       0  5011.6     .12       0
  6129.8     .16       0  6406.8     .05       0
Bank Sta=4948.6,5045
XS Rating Curve= 0 ,0
Exp/Cntr=0.3,0.1

Type RM Length L Ch R = 1 ,142776  ,360,360,360
BEGIN DESCRIPTION:
BUFFALO CREEK 103.0
END DESCRIPTION:
XS GIS Cut Line= 3
      3596499.61     10537010.18      3596899.61     10535460.19
       3596349.6     10533860.16
#Sta/Elev= 30
  3402.9  376.79  3588.8  367.78  3733.4  367.36  3979.6  354.51  4147.5  354.26
  4404.7  337.16  4931.4  336.44  4962.4   334.3  4972.7     331  4980.8  331.34
  4985.9  333.61  4993.4  328.49    5014  324.31    5019   323.7  5024.8  324.23
  5081.8   337.4  5206.8  335.87  5923.6  340.34    6040  346.26  6091.6   351.7
  6096.9  350.28  6154.1  356.02  6190.6  357.23  6216.6  361.42  6221.9   360.1
  6284.4  362.95  6341.6  370.63  6452.4  371.05  6579.3  378.41  6695.6  379.81
#Mann= 3 ,-1 , 0
  3402.9     .12       0    5014     .04       0  5024.8     .12       0
Bank Sta=4931.4,5081.8
XS Rating Curve= 0 ,0
Exp/Cntr=0.3,0.1

Type RM Length L Ch R = 1 ,142416  ,479,479,479
BEGIN DESCRIPTION:
BUFFALO CREEK 102.0
END DESCRIPTION:
XS GIS Cut Line= 2
      3596812.76     10537720.82      3597619.95     10533554.69
#Sta/Elev= 30
  2760.2  381.53  2964.6  379.09    3260  362.65  3290.5   355.9  3341.4  361.11
  3502.6   361.2  3830.4  341.53  3891.5  339.74  4082.1  339.15  4217.4  335.88
  4339.7  336.07  4370.2  338.27  4390.6  335.96  4461.9  336.52    4523  338.94
  4808.2  335.38  4940.6  337.88    4961  336.37  4971.2  330.31  4977.1  323.52
    4982   322.9  5011.9  328.06  5028.9  335.34  5317.5  334.76  5541.6  338.24
    5562  336.48  6193.5  347.26  6651.9  364.16  6922.5  380.62  7003.8  381.51
#Mann= 3 , 0 , 0
  2760.2     .05       0  4940.6     .04       0  5028.9     .05       0
Bank Sta=4940.6,5028.9
XS Rating Curve= 0 ,0
Exp/Cntr=0.3,0.1

Type RM Length L Ch R = 1 ,141937  ,833,833,833
BEGIN DESCRIPTION:
BUFFALO CREEK 101.0
END DESCRIPTION:
XS GIS Cut Line= 2
      3597142.62     10537720.81      3598288.45     10533415.27
#Sta/Elev= 30
  2799.7  378.99  2893.5  380.22  2986.6  379.35  3192.3  372.13  3312.7  362.27
  3576.4  344.05    3711  338.42  4083.5  333.77    4671  335.14    4901   333.9
  4946.8  336.12  4952.7  336.42  4963.1   328.1  4981.5  322.88  4994.1   323.7
  5004.5  329.94  5021.9  334.84  5027.1  334.87  5128.7  333.15  5263.2  333.22
  5723.7  339.96  5925.5  344.52  6049.6   343.5  6122.1  348.07  6350.4  354.41
  6886.4  377.09  7041.8  381.15    7047   380.2  7197.2  383.36  7255.1  382.98
#Mann= 3 ,-1 , 0
  2799.7     .05       0  4946.8     .04       0  5027.1     .05       0
Bank Sta=4952.7,5021.9
XS Rating Curve= 0 ,0
Exp/Cntr=0.3,0.1