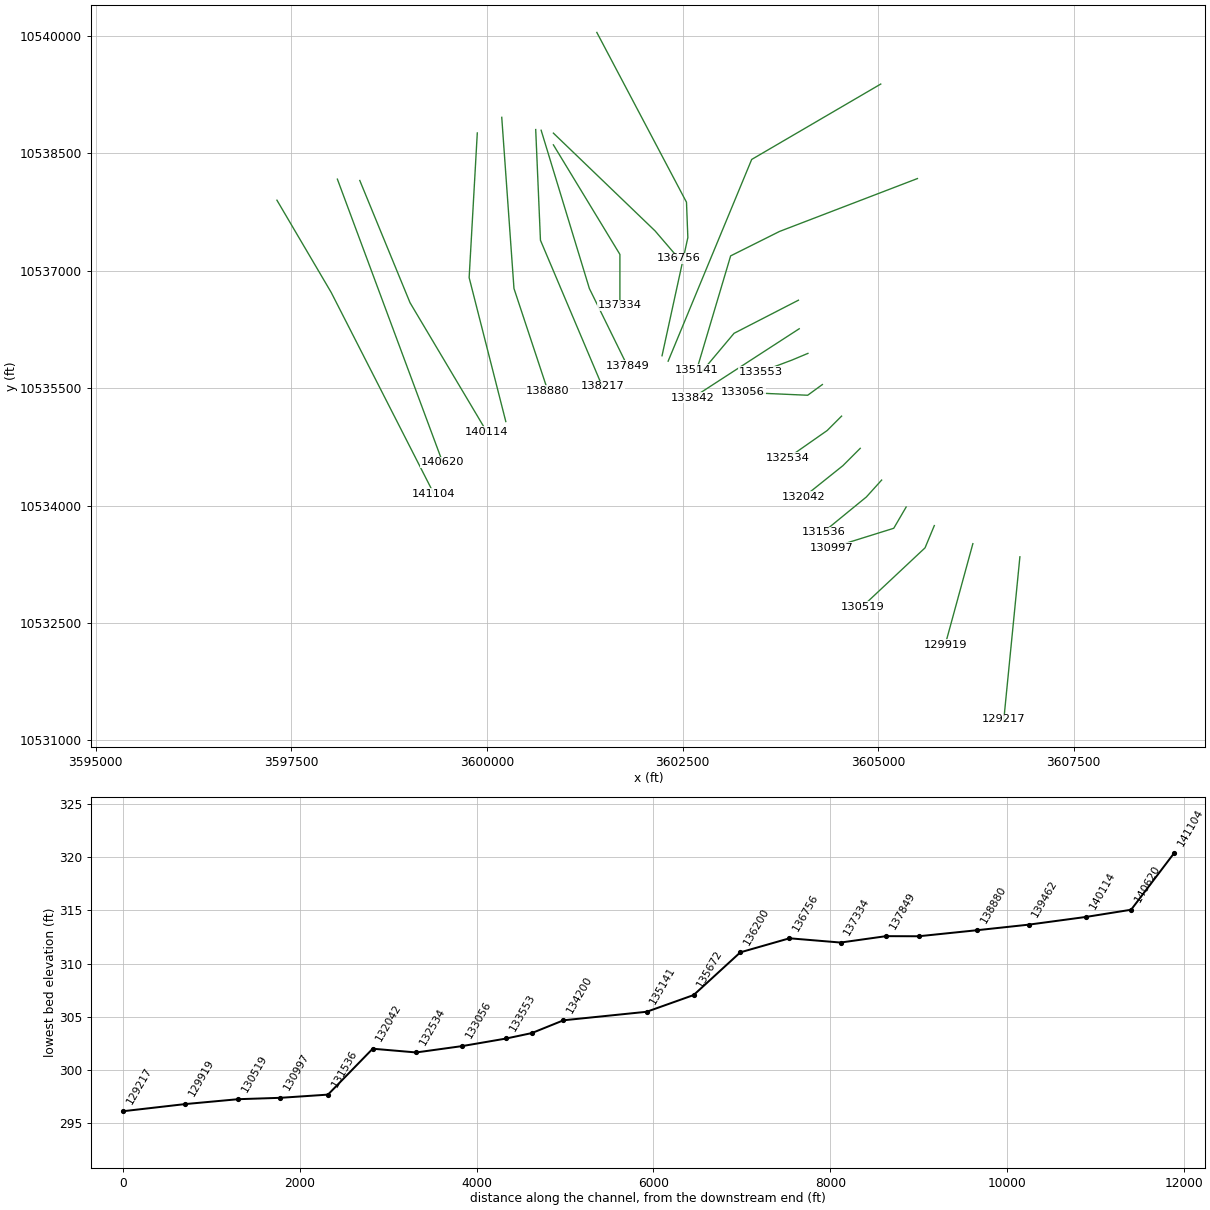
HEC-RAS study BUFFALO CREEK.prj: BUFFALO CREEK Base Level Engineering

--- BUFFALO CREEK.g01 (geometry) --- (continued)

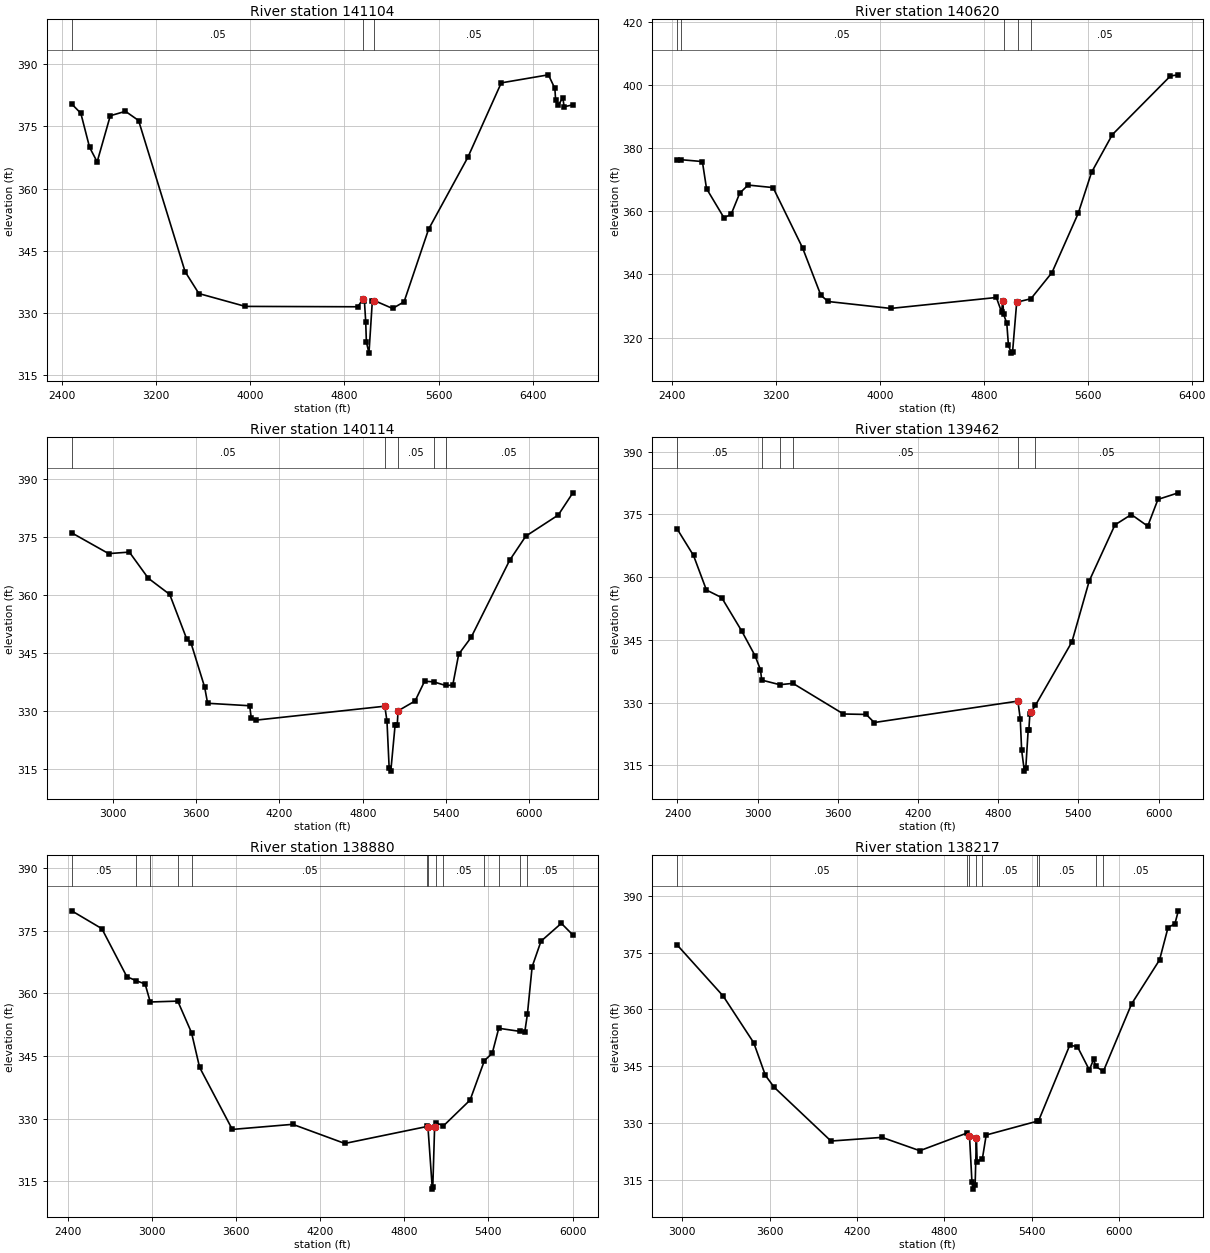
Type RM Length L Ch R = 1 ,141104  ,484,484,484
BEGIN DESCRIPTION:
BUFFALO CREEK 100.0
END DESCRIPTION:
XS GIS Cut Line= 3
      3597316.24     10537903.07      3598010.68     10536722.53
      3599320.89     10534154.16
#Sta/Elev= 30
  2486.3  380.42  2563.5   378.2  2637.8  369.97  2702.2  366.47  2813.5  377.59
  2942.3  378.66  3053.7  376.44  3448.2     340  3565.3  334.71  3959.6  331.61
  4913.8  331.52  4958.7  333.41  4970.2  332.94  4981.2  327.92  4986.8  323.05
  5008.8  320.34  5037.3  332.89  5053.5  333.03  5209.1  331.11  5306.7  332.71
  5514.7  350.21  5848.2  367.58  6131.5  385.52  6531.6  387.46  6586.5  384.17
  6592.7  381.45    6615  380.09  6653.8  381.97  6665.1  379.76  6739.2  380.22
#Mann= 3 , 0 , 0
  2486.3     .05       0  4958.7     .04       0  5053.5     .05       0
Bank Sta=4958.7,5053.5
XS Rating Curve= 0 ,0
Exp/Cntr=0.3,0.1

Type RM Length L Ch R = 1 ,140620  ,506,506,506
BEGIN DESCRIPTION:
BUFFALO CREEK 99.0
END DESCRIPTION:
XS GIS Cut Line= 2
       3598088.8     10538172.19      3599433.78     10534553.77
#Sta/Elev= 30
    2437  376.29  2465.4  376.41  2631.2  375.82  2663.2  367.23  2797.3     358
  2852.7  359.08  2919.2  365.81  2983.2  368.36  3175.9  367.56  3402.7  348.47
  3543.8  333.42  3599.2  331.43  4082.1  329.23  4895.8   332.7  4935.6  328.14
  4945.8  331.73  4951.1  327.43  4976.1  324.52  4988.9  317.48  5011.6  315.05
  5020.9  315.56  5052.9  331.41  5061.9   331.3    5162   332.3  5324.4  340.62
  5526.2  359.38    5629   372.4    5789  384.35    6237  402.98  6297.3  403.33
#Mann= 5 ,-1 , 0
    2437     .15       0  2465.4     .05       0  4951.1     .04       0
  5061.9     .08       0    5162     .05       0
Bank Sta=4945.8,5052.9
XS Rating Curve= 0 ,0
Exp/Cntr=0.3,0.1

Type RM Length L Ch R = 1 ,140114  ,652,652,652
BEGIN DESCRIPTION:
BUFFALO CREEK 98.0
END DESCRIPTION:
XS GIS Cut Line= 3
      3598375.27     10538154.81      3599017.63     10536592.32
       3599997.9     10534944.07
#Sta/Elev= 30
  2705.5  376.01  2971.1  370.64  3120.3  371.03  3256.3  364.28  3410.9  360.08
  3532.2  348.65  3564.7  347.44    3662  336.14  3683.6  331.93  3986.3  331.29
  3997.5  328.18  4029.6  327.56    4959  331.17  4974.6  327.31  4990.2  315.28
  5002.1  314.38    5033  326.25  5048.6  326.39  5054.4  329.97  5177.1  332.53
  5245.3  337.63  5310.9  337.47  5396.7  336.53  5447.9  336.61    5491  344.63
  5580.3  348.97  5856.9  368.87  5973.7  375.15  6207.5  380.62  6312.6  386.36
#Mann= 5 ,-1 , 0
  2705.5     .05       0    4959     .04       0  5054.4     .05       0
  5310.9      .1       0  5396.7     .05       0
Bank Sta=4959,5054.4
XS Rating Curve= 0 ,0
Exp/Cntr=0.3,0.1

Type RM Length L Ch R = 1 ,139462  ,582,582,582
BEGIN DESCRIPTION:
BUFFALO CREEK 97.0
END DESCRIPTION:
XS GIS Cut Line= 3
        3599877.     10538762.43      3599772.83      10536913.5
      3600241.34     10535074.19
#Sta/Elev= 30
  2397.8   371.5  2520.2  365.17  2616.7  356.92  2730.6  355.11  2880.8  347.13
    2981   341.2    3021  337.87  3030.6   335.4  3165.7   334.3  3264.2  334.62
    3642   327.3  3812.3  327.19  3872.4  325.26  4947.6  330.38  4965.1  326.12
  4975.4  318.64  4995.8  313.65  5006.4  314.32  5024.2  323.43  5029.4  323.53
  5037.3  327.39  5047.7  327.77  5078.6  329.37  5351.4  344.51  5481.1  359.08
  5673.4  372.47  5796.1  374.96  5918.8  372.18  5995.4  378.57  6147.7  380.14
#Mann= 6 ,-1 , 0
  2397.8     .05       0  3030.6     .08       0  3165.7      .1       0
  3264.2     .05       0  4947.6     .04       0  5078.6     .05       0
Bank Sta=4947.6,5047.7
XS Rating Curve= 0 ,0
Exp/Cntr=0.3,0.1

Type RM Length L Ch R = 1 ,138880  ,663,663,663
BEGIN DESCRIPTION:
BUFFALO CREEK 96.0
END DESCRIPTION:
XS GIS Cut Line= 3
       3600189.5     10538962.14      3600345.75     10536774.61
      3600779.57     10535464.47
#Sta/Elev= 30
  2429.2  379.74    2644  375.47  2822.2  363.98    2891  362.98  2952.5  362.24
  2989.1  357.92  3185.2  358.13  3283.3  350.59  3340.8  342.29  3574.1  327.42
  4005.2  328.64  4376.1  324.06  4963.8  328.13    4969  328.05  5000.4  313.13
  5003.7  313.63  5016.7     328  5027.1     329  5079.9  328.28  5269.5  334.44
  5371.9   343.9  5427.5  345.64  5473.9  351.63  5624.4  350.89  5659.3   350.7
    5678  354.94    5712  366.36  5775.2  372.47  5920.2  376.75  6002.4  373.96
#Mann= 13 ,-1 , 0
  2429.2     .05       0    2891     .08       0  2989.1      .1       0
  3185.2     .08       0  3283.3     .05       0  4963.8     .16       0
    4969     .07       0  5027.1     .16       0  5079.9     .05       0
  5371.9     .08       0  5473.9      .1       0  5624.4     .15       0
    5678     .05       0
Bank Sta=4969,5016.7
XS Rating Curve= 0 ,0
Exp/Cntr=0.3,0.1

Type RM Length L Ch R = 1 ,138217  ,368,368,368
BEGIN DESCRIPTION:
BUFFALO CREEK 95.0
END DESCRIPTION:
XS GIS Cut Line= 3
      3600623.53     10538805.83      3600684.29     10537390.93
       3601474.1      10535524.9
#Sta/Elev= 30
  2963.9     377  3279.8  363.53    3490  351.18  3570.1  342.57  3630.2  339.45
  4020.5  325.25  4370.8  326.22  4630.7   322.7  4955.9  327.38  4971.9  326.69
    4989  314.34  4995.3  312.56  5010.7  313.65  5019.2  325.95  5024.7  319.83
  5060.7  320.62  5086.7  326.84  5437.2  330.49  5446.9  330.63  5660.3  350.51
  5713.1  350.19    5795  344.03  5825.1  346.81  5838.9  344.96  5891.5  343.65
  6085.8  361.46  6277.6  373.05  6335.8  381.59  6383.2  382.59  6406.4  386.01
#Mann= 9 ,-1 , 0
  2963.9     .05       0  4955.9     .16       0  4971.9     .07       0
  5019.2     .16       0  5060.7     .05       0  5437.2     .08       0
  5446.9     .05       0  5838.9     .08       0  5891.5     .05       0
Bank Sta=4971.9,5019.2
XS Rating Curve= 0 ,0
Exp/Cntr=0.3,0.1

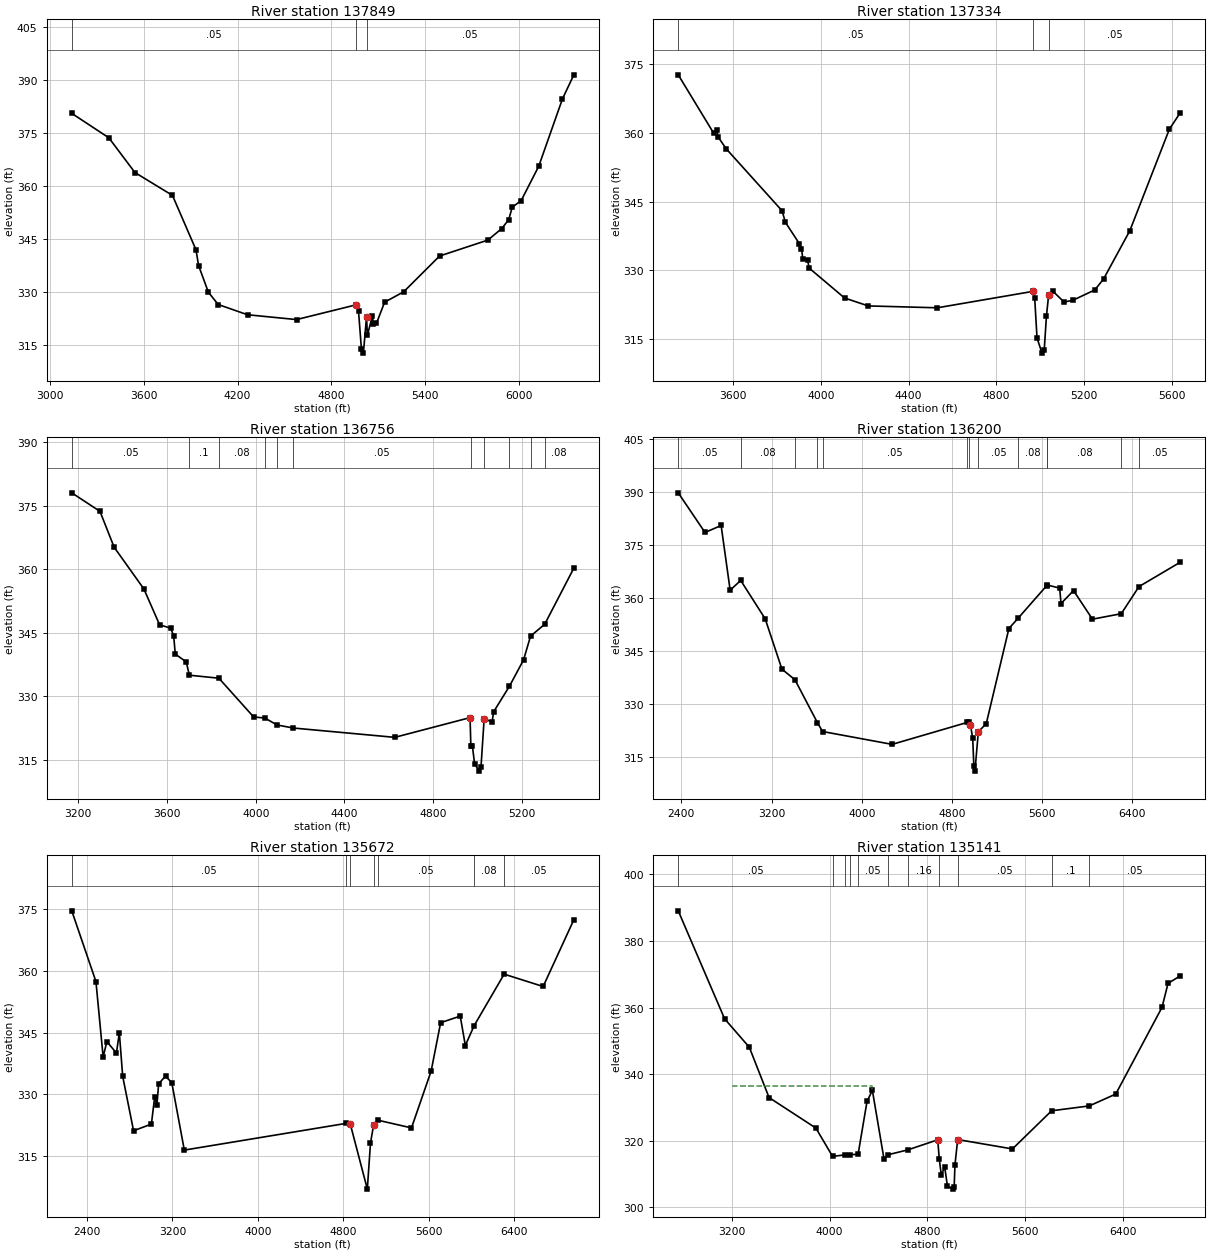
Type RM Length L Ch R = 1 ,137849  ,515,515,515
BEGIN DESCRIPTION:
BUFFALO CREEK 94.0
END DESCRIPTION:
XS GIS Cut Line= 3
      3600692.96     10538797.22      3601309.29     10536774.61
      3601794.98      10535785.9
#Sta/Elev= 30
  3138.3  380.61  3375.6  373.69  3542.9  363.82  3783.3  357.33    3934  341.89
  3950.6  337.42  4013.3  329.86  4076.1  326.37  4264.2  323.46  4577.8  322.09
  4960.8  326.29  4975.1  324.45  4993.7  313.73  5006.2  312.57  5026.5  322.92
  5031.7  317.63  5064.5  323.22  5069.8   320.8  5090.1  321.04  5142.4  327.04
    5264  329.96  5494.4  340.13  5803.6  344.65  5892.7  347.93  5937.3  350.46
  5959.6  353.98  6017.1  355.87  6129.5  365.61  6281.3  384.72  6354.3  391.55
#Mann= 3 , 0 , 0
  3138.3     .05       0  4960.8     .04       0  5026.5     .05       0
Bank Sta=4960.8,5026.5
XS Rating Curve= 0 ,0
Exp/Cntr=0.3,0.1

Type RM Length L Ch R = 1 ,137334  ,578,578,578
BEGIN DESCRIPTION:
BUFFALO CREEK 93.0
END DESCRIPTION:
XS GIS Cut Line= 3
       3600849.6     10538610.21      3601699.61     10537210.19
      3601699.61     10536560.14
#Sta/Elev= 30
  3350.4  372.69  3511.3     360  3525.9  360.58  3532.6   359.1  3569.4  356.53
  3823.4  343.04  3838.8   340.5  3902.8  335.82    3912  334.78  3918.3  332.49
  3939.7  332.27  3947.1  330.52  4108.3     324  4216.1  322.27  4530.8  321.86
    4965  325.43  4974.7  324.04  4985.3  315.29    5008  311.97  5018.3  312.75
  5028.3  320.06  5038.3  324.66  5058.3  325.45  5108.3  323.13  5148.3  323.49
  5248.3  325.75  5288.3  328.12  5408.3  338.68  5588.3  360.81  5638.3  364.44
#Mann= 3 , 0 , 0
  3350.4     .05       0    4965     .04       0  5038.3     .05       0
Bank Sta=4965,5038.3
XS Rating Curve= 0 ,0
Exp/Cntr=0.3,0.1

Type RM Length L Ch R = 1 ,136756  ,556,556,556
BEGIN DESCRIPTION:
BUFFALO CREEK 92.0
END DESCRIPTION:
XS GIS Cut Line= 3
      3600849.59     10538760.21      3602149.61     10537510.19
      3602449.63     10537160.17
#Sta/Elev= 30
  3170.3  378.11  3297.5  373.73  3361.4  365.26  3495.6   355.4  3566.4  346.94
  3615.8  346.15  3629.9  344.37  3637.1  340.02  3686.5  338.18  3700.7  335.03
  3833.8  334.32  3990.6  325.16  4040.7  324.92  4096.2  323.27  4169.9  322.55
  4627.1  320.35  4966.7  325.01  4970.3   318.3  4977.1   318.3  4987.5  313.99
  5009.2  312.37  5016.1  313.43  5030.3  324.75    5066  323.97  5073.1   326.4
  5144.1   332.4  5208.1  338.66  5239.5  344.26  5303.3  347.06  5434.8  360.33
#Mann= 11 ,-1 , 0
  3170.3     .05       0  3700.7      .1       0  3833.8     .08       0
  4040.7     .05       0  4096.2     .08       0  4169.9     .05       0
  4970.3     .04       0  5030.3     .05       0  5144.1     .08       0
  5239.5      .1       0  5303.3     .08       0
Bank Sta=4966.7,5030.3
XS Rating Curve= 0 ,0
Exp/Cntr=0.3,0.1

Type RM Length L Ch R = 1 ,136200  ,528,528,528
BEGIN DESCRIPTION:
BUFFALO CREEK 91.0
END DESCRIPTION:
XS GIS Cut Line= 4
      3601404.76     10540047.21      3602550.61     10537877.04
      3602567.97     10537425.65      3602238.12     10535915.27
#Sta/Elev= 30
  2372.3  389.68  2609.8  378.48  2752.6  380.45  2832.6  362.17  2926.2  364.93
  3143.3  354.08  3291.7  339.87    3407  336.87  3607.1   324.7  3652.5  322.24
  4268.7  318.61  4937.1  324.83  4953.3  324.95  4963.3   324.1  4983.4  320.31
  4993.4  312.46  5003.1  311.05  5033.4  322.19  5103.5  324.47  5304.2  351.34
  5389.2  354.37  5639.5  363.46  5645.9  363.62  5754.6  362.76  5766.2   358.4
  5877.4  362.06    6045  353.98  6300.7  355.53  6457.7  363.19  6824.1  370.08
#Mann= 13 ,-1 , 0
  2372.3     .05       0  2926.2     .08       0    3407     .05       0
  3607.1     .08       0  3652.5     .05       0  4937.1      .1       0
  4953.3     .04       0  5033.4     .05       0  5389.2     .08       0
  5639.5      .1       0  5645.9     .08       0  6300.7      .1       0
  6457.7     .05       0
Bank Sta=4963.3,5033.4
XS Rating Curve= 0 ,0
Exp/Cntr=0.3,0.1

Type RM Length L Ch R = 1 ,135672  ,531,531,531
BEGIN DESCRIPTION:
BUFFALO CREEK 90.0
END DESCRIPTION:
XS GIS Cut Line= 3
      3605033.23     10539387.44      3603383.95     10538423.91
      3602316.23     10535845.77
#Sta/Elev= 30
  2258.1  374.49  2484.4  357.35  2551.8  339.05  2586.6  342.81  2676.2  340.01
  2703.4  344.95  2734.8  334.38  2836.5  321.19  3003.5   322.8  3034.1  329.32
  3055.6  327.46  3071.3  332.59  3135.8  334.41  3194.4  332.85  3311.8   316.5
  4823.4  322.96    4865  322.88  5025.2  307.04  5054.7  318.17    5084   322.6
  5124.7  323.74  5438.6  321.88  5622.6  335.65  5711.5  347.38    5895  348.97
  5942.8  341.85  6025.2  346.66  6306.1  359.14  6671.3  356.15  6958.7  372.33
#Mann= 7 ,-1 , 0
  2258.1     .05       0  4823.4     .08       0    4865     .04       0
    5084      .1       0  5124.7     .05       0  6025.2     .08       0
  6306.1     .05       0
#XS Ineff= 1 ,-1
 2667.61    3125  333.94
Permanent Ineff=
       F
Bank Sta=4865,5084
XS Rating Curve= 0 ,0
Exp/Cntr=0.3,0.1

Type RM Length L Ch R = 1 ,135141  ,941,941,941
BEGIN DESCRIPTION:
BUFFALO CREEK 89.0
END DESCRIPTION:
XS GIS Cut Line= 4
      3605502.23     10538179.72      3603739.85     10537503.78
      3603114.85     10537191.28      3602681.16     10535734.07
#Sta/Elev= 30
  2761.5  389.05  3140.8  356.62  3342.7  348.09  3504.4  332.97  3887.3  323.81
    4024  315.29  4128.4  315.78  4168.5  315.83  4232.7  315.93  4305.6  331.82
  4349.4  335.14  4445.1   314.4  4473.6  315.76  4637.7  317.24  4884.1  320.28
  4896.4  314.58  4913.1  309.71  4941.1   312.1  4963.5  306.34  5007.9  305.47
  5018.3  305.97  5024.9  312.77  5047.3  320.36    5495  317.54  5815.6     329
  6123.4  330.46  6340.1  334.02  6718.4  360.05  6767.9  367.28  6868.2  369.52
#Mann= 11 ,-1 , 0
  2761.5     .05       0    4024     .16       0  4128.4     .05       0
  4168.5     .12       0  4232.7     .05       0  4473.6     .12       0
  4637.7     .16       0  4896.4     .03       0  5047.3     .05       0
  5815.6      .1       0  6123.4     .05       0
#XS Ineff= 1 ,-1
  3201.7 4349.43  336.55
Permanent Ineff=
       F
Bank Sta=4884.1,5047.3
XS Rating Curve= 0 ,0
Exp/Cntr=0.3,0.1

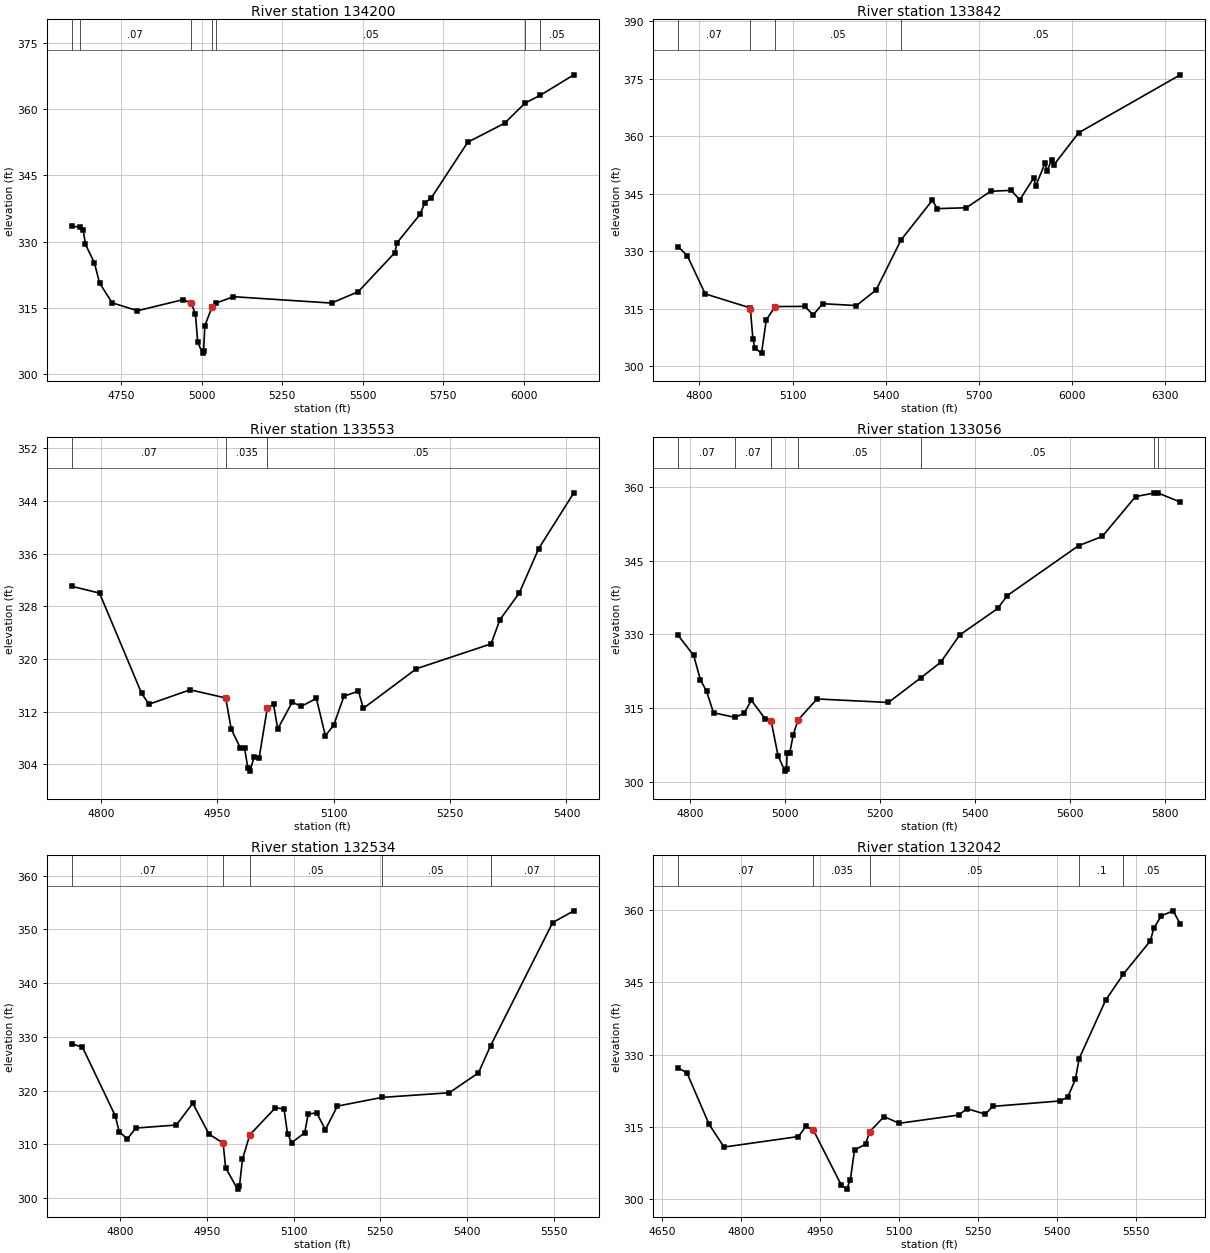
Type RM Length L Ch R = 1 ,134200  ,358,358,358
BEGIN DESCRIPTION:
BUFFALO CREEK 88.0
END DESCRIPTION:
XS GIS Cut Line= 3
      3603981.17     10536624.98      3603158.25     10536201.69
      3602750.28      10535715.6
#Sta/Elev= 30
    4596  333.46  4621.6  333.31  4631.5  332.72  4638.2   329.4    4666  325.22
  4682.5  320.57  4721.3   316.1  4800.2  314.29    4943  316.83 4967.61  315.94
  4980.1  313.62  4987.4  307.13  5002.3  304.67  5005.6  305.17  5009.6   310.9
  5031.7  315.13  5043.1  315.99  5098.3  317.48  5403.1  316.03  5486.1  318.61
    5600  327.49  5606.5  329.71  5678.1  336.16  5692.4  338.73  5713.2  339.91
  5826.4  352.55  5940.8  356.85  6004.6  361.44  6050.8  363.16    6156  367.84
#Mann= 7 ,-1 , 0
    4596     .07       0  4621.6     .07       0  4965.2     .03       0
  5031.7     .07       0  5043.1     .05       0  6004.6     .08       0
  6050.8     .05       0
Bank Sta=4967.61,5031.7
XS Rating Curve= 0 ,0
Exp/Cntr=0.3,0.1

Type RM Length L Ch R = 1 ,133842  ,289,289,289
BEGIN DESCRIPTION:
BUFFALO CREEK 87.0
END DESCRIPTION:
XS GIS Cut Line= 2
      3603991.35     10536259.98      3602635.28      10535381.4
#Sta/Elev= 30
  4731.9   331.2  4761.4  328.78  4818.8   318.9  4961.4  315.31  4963.9  315.05
  4972.3  307.08    4979  304.72  4999.9  303.47  5015.3  312.13  5043.8   315.6
  5139.1  315.65  5166.3  313.43  5196.6  316.34  5305.4  315.86  5368.7  319.92
  5448.9  332.95    5550  343.32  5565.2  341.11  5658.8  341.33  5737.3  345.63
  5803.9  345.87    5831  343.38  5876.4  349.15  5882.4     347  5912.7  353.03
  5918.6  350.86  5933.8  353.86  5939.8  352.39  6020.8  360.88  6347.7  375.96
#Mann= 4 ,-1 , 0
  4731.9     .07       0  4961.4    .035       0  5043.8     .05       0
  5448.9     .05       0
Bank Sta=4963.9,5043.8
XS Rating Curve= 0 ,0
Exp/Cntr=0.3,0.1

Type RM Length L Ch R = 1 ,133553  ,497,497,497
BEGIN DESCRIPTION:
BUFFALO CREEK 86.0
END DESCRIPTION:
XS GIS Cut Line= 3
      3604102.65     10535945.34      3603899.61     10535860.19
      3603499.59     10535710.18
#Sta/Elev= 30
  4762.1  331.05  4797.9  330.02  4852.2  314.77  4861.7  313.13  4914.7  315.32
  4960.6  314.08  4967.7  309.35  4979.6  306.45  4984.9  306.45  4989.1  303.46
  4991.8  302.96  4997.4  305.15  5003.6  304.92  5014.3  312.59  5022.3  313.09
  5027.7  309.37  5046.4  313.45  5057.9   312.8  5077.5  314.01  5089.1  308.35
  5099.8  309.93  5113.1  314.35  5131.8  315.12    5138   312.5  5206.6  318.53
  5302.7   322.3  5314.2  325.97  5339.2  330.05  5364.1  336.77  5409.5  345.26
#Mann= 3 , 0 , 0
  4762.1     .07       0  4960.6    .035       0  5014.3     .05       0
Bank Sta=4960.6,5014.3
XS Rating Curve= 0 ,0
Exp/Cntr=0.3,0.1

Type RM Length L Ch R = 1 ,133056  ,522,522,522
BEGIN DESCRIPTION:
BUFFALO CREEK 85.0
END DESCRIPTION:
XS GIS Cut Line= 3
      3604287.26     10535547.11      3604099.61     10535410.19
      3603275.41     10535446.48
#Sta/Elev= 30
    4775  329.79  4807.6  325.73  4821.6   320.8  4834.7  318.46  4849.3   314.1
  4895.1  313.15  4914.2  314.04  4928.9  316.65  4957.8  312.91  4970.6  312.46
  4985.3  305.33  4999.7  302.25    5003  302.75  5004.2  305.93  5009.8  305.93
  5017.3  309.68  5027.3  312.63  5067.4   316.9  5217.5  316.19  5286.7  321.25
  5327.6  324.34  5367.6  329.88  5447.7  335.27  5467.7  337.87  5617.9  348.01
  5667.9  349.89    5738  357.98  5777.4  358.72  5784.6  358.75  5832.3  356.87
#Mann= 7 ,-1 , 0
    4775     .07       0  4895.1     .07       0  4970.6    .035       0
  5027.3     .05       0  5286.7     .05       0  5777.4     .15       0
  5784.6     .05       0
Bank Sta=4970.6,5027.3
XS Rating Curve= 0 ,0
Exp/Cntr=0.3,0.1

Type RM Length L Ch R = 1 ,132534  ,492,492,492
BEGIN DESCRIPTION:
BUFFALO CREEK 84.0
END DESCRIPTION:
XS GIS Cut Line= 3
      3604532.63      10535143.4      3604349.61     10534960.19
       3603849.6     10534610.18
#Sta/Elev= 30
  4715.9  328.68  4734.4  328.07    4791  315.34  4798.1  312.35  4812.2  310.96
  4826.4  313.01  4897.1  313.58  4925.4  317.63  4953.6  311.87  4977.9  310.23
  4982.3  305.63  5002.9  301.65  5006.2  302.15  5011.5  307.23  5024.1  311.75
  5068.6   316.8  5083.4  316.56  5089.5  311.93  5096.9  310.31  5119.2  312.14
  5125.3  315.65  5140.1  315.82  5154.9  312.72  5175.8   317.1  5253.2  318.72
  5369.4  319.58    5420  323.28  5440.9   328.3  5548.6  351.26  5585.2  353.44
#Mann= 5 ,-1 , 0
  4715.9     .07       0  4977.9    .035       0  5024.1     .05       0
  5253.2     .05       0  5440.9     .07       0
Bank Sta=4977.9,5024.1
XS Rating Curve= 0 ,0
Exp/Cntr=0.3,0.1

Type RM Length L Ch R = 1 ,132042  ,506,506,506
BEGIN DESCRIPTION:
BUFFALO CREEK 83.0
END DESCRIPTION:
XS GIS Cut Line= 3
      3604771.14     10534731.72      3604549.61     10534510.19
      3604049.61     10534110.19
#Sta/Elev= 30
  4680.3  327.17  4696.6  326.25    4739  315.46  4767.3  310.75  4908.7  312.94
  4922.9   315.1    4937  314.27  4990.1  302.82  5000.5     302  5007.2  303.99
  5015.2  310.15    5036  311.33    5044  313.96  5071.2  317.08    5100   315.7
  5213.7  317.42  5228.1  318.76  5263.3   317.6  5277.7  319.21  5405.8  320.35
  5420.2  321.17  5434.6  324.83  5441.8  329.17  5492.2  341.33  5525.9  346.75
  5577.1  353.66  5583.5  356.29  5597.9  358.86  5620.3   359.9  5633.9  357.13
#Mann= 5 ,-1 , 0
  4680.3     .07       0    4937    .035       0    5044     .05       0
  5441.8      .1       0  5525.9     .05       0
Bank Sta=4937,5044
XS Rating Curve= 0 ,0
Exp/Cntr=0.3,0.1

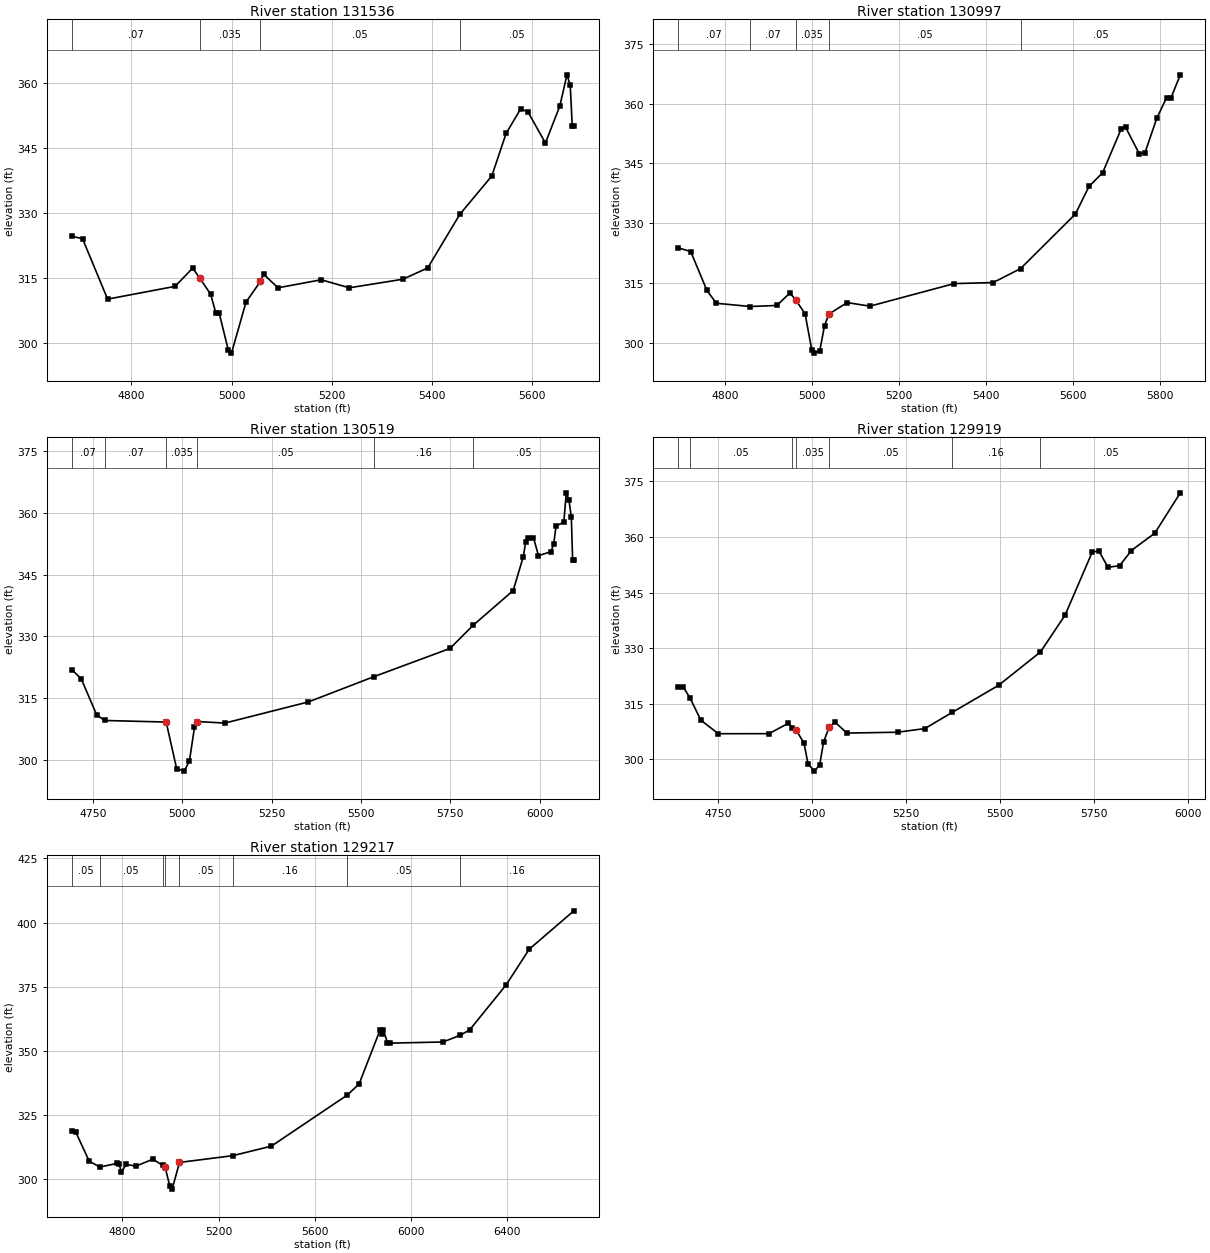
Type RM Length L Ch R = 1 ,131536  ,539,539,539
BEGIN DESCRIPTION:
BUFFALO CREEK 82.0
END DESCRIPTION:
XS GIS Cut Line= 3
      3605044.56     10534326.03      3604849.61     10534110.19
      3604299.59     10533660.18
#Sta/Elev= 30
  4681.1  324.69  4702.6  324.12  4752.6  310.16  4887.1  313.11  4922.3  317.32
  4936.5  314.99  4958.1  311.31  4968.6  306.89  4975.2  306.89  4993.5  298.33
  4999.7  297.69  5028.7  309.49  5057.4  314.24  5063.8  315.91  5092.5  312.78
  5178.7  314.63  5234.7  312.78  5341.6  314.76  5391.1  317.37    5455  329.72
  5518.9   338.6  5547.6  348.47  5576.3  354.06  5590.7  353.49  5625.9  346.21
  5654.6  354.77  5668.9  361.97  5675.4  359.58  5679.4  350.23  5682.6  350.23
#Mann= 4 ,-1 , 0
  4681.1     .07       0  4936.5    .035       0  5057.4     .05       0
    5455     .05       0
Bank Sta=4936.5,5057.4
XS Rating Curve= 0 ,0
Exp/Cntr=0.3,0.1

Type RM Length L Ch R = 1 ,130997  ,478,478,478
BEGIN DESCRIPTION:
BUFFALO CREEK 81.0
END DESCRIPTION:
XS GIS Cut Line= 3
      3605358.03     10533981.76      3605199.61     10533710.19
      3604399.56     10533460.17
#Sta/Elev= 30
  4693.1  323.83  4721.8  322.87    4759  313.11  4780.5  309.91  4858.1  309.09
  4919.4  309.35  4949.6  312.49  4962.4  310.81  4984.3  307.26  4999.6  298.22
  5004.4  297.39    5018  297.98    5029  304.31  5038.9  307.19  5080.8  310.07
  5133.2  309.18  5326.5  314.84  5416.1   315.1    5479  318.61  5604.7  332.28
  5636.1  339.23  5667.5  342.69  5709.5  353.54  5719.9  354.12  5751.4  347.44
  5764.5  347.66  5791.7  356.34  5814.2  361.51  5824.2  361.44  5845.7  367.24
#Mann= 5 ,-1 , 0
  4693.1     .07       0  4858.1     .07       0  4962.4    .035       0
  5038.9     .05       0    5479     .05       0
Bank Sta=4962.4,5038.9
XS Rating Curve= 0 ,0
Exp/Cntr=0.3,0.1

Type RM Length L Ch R = 1 ,130519  ,600,600,600
BEGIN DESCRIPTION:
BUFFALO CREEK 80.0
END DESCRIPTION:
XS GIS Cut Line= 3
      3605718.05     10533744.44      3605599.61     10533460.19
      3604799.62      10532710.2
#Sta/Elev= 30
  4690.9  321.92  4717.2  319.72  4760.5  310.96  4783.1  309.57    4955  309.19
  4984.2  297.88  5005.7  297.26  5020.1  299.77  5034.2   307.9  5041.1  309.32
  5119.2  308.94  5352.7  314.08  5536.4  320.23  5748.9  327.08  5813.1  332.66
  5925.7  341.16    5954  349.39  5960.9  353.03  5968.2  353.85  5982.3  354.05
  5996.5  349.63  6031.7  350.62    6039  352.52  6045.8  356.89  6067.3  357.75
  6074.2  364.91  6081.5  363.26  6088.3  359.03    6092   348.6  6095.4   348.6
#Mann= 6 ,-1 , 0
  4690.9     .07       0  4783.1     .07       0    4955    .035       0
  5041.1     .05       0  5536.4     .16       0  5813.1     .05       0
Bank Sta=4955,5041.1
XS Rating Curve= 0 ,0
Exp/Cntr=0.3,0.1

Type RM Length L Ch R = 1 ,129919  ,702,702,702
BEGIN DESCRIPTION:
BUFFALO CREEK 79.0
END DESCRIPTION:
XS GIS Cut Line= 2
      3606210.59     10533513.23      3605858.08     10532224.47
#Sta/Elev= 30
  4643.8  319.53  4657.3  319.52  4674.8  316.58  4704.2  310.53  4750.6   306.9
  4885.4  306.91  4937.2  309.74  4947.4  308.57    4958  307.86  4978.7  304.26
  4989.1   298.8  5005.9   296.8  5020.2  298.45  5030.5  304.61  5045.8  308.83
  5061.6  309.96  5092.7  307.07  5227.5   307.3  5300.1  308.29  5372.7  312.64
  5496.1  319.95  5607.8  328.97  5673.3  338.92  5745.9  356.01  5763.5  356.16
  5787.4  351.82  5818.5  352.25  5849.6  356.35  5911.8  361.01  5979.9  371.92
#Mann= 7 ,-1 , 0
  4643.8     .07       0  4674.8     .05       0  4947.4      .1       0
    4958    .035       0  5045.8     .05       0  5372.7     .16       0
  5607.8     .05       0
Bank Sta=4958,5045.8
XS Rating Curve= 0 ,0
Exp/Cntr=0.3,0.1

Type RM Length L Ch R = 1 ,129217  ,462,462,462
BEGIN DESCRIPTION:
BUFFALO CREEK 78.0
END DESCRIPTION:
XS GIS Cut Line= 2
      3606811.83      10533345.7       3606606.6     10531268.92
#Sta/Elev= 30
  4589.3  318.87  4604.9  318.55  4661.4   307.1  4705.4  304.72  4775.7  306.12
  4785.8   305.8  4795.8  302.81  4815.9   305.8  4856.1  305.08  4926.4   307.8
  4966.8  305.38  4976.7  304.87  4996.8  297.33  5006.6  296.13    5037  306.53
  5258.1  309.16  5418.8  312.87  5734.5  332.78  5783.4  337.07    5871  358.18
  5879.5  356.74  5884.5  358.12  5901.2  353.22  5911.2  353.01  6132.3  353.46
  6202.9  356.03  6242.8  358.13    6395  375.74    6491  389.63  6676.2  404.56
#Mann= 8 ,-1 , 0
  4589.3     .05       0  4705.4     .05       0  4966.8     .12       0
  4976.7    .035       0    5037     .05       0  5258.1     .16       0
  5734.5     .05       0  6202.9     .16       0
Bank Sta=4976.7,5037
XS Rating Curve= 0 ,0
Exp/Cntr=0.3,0.1