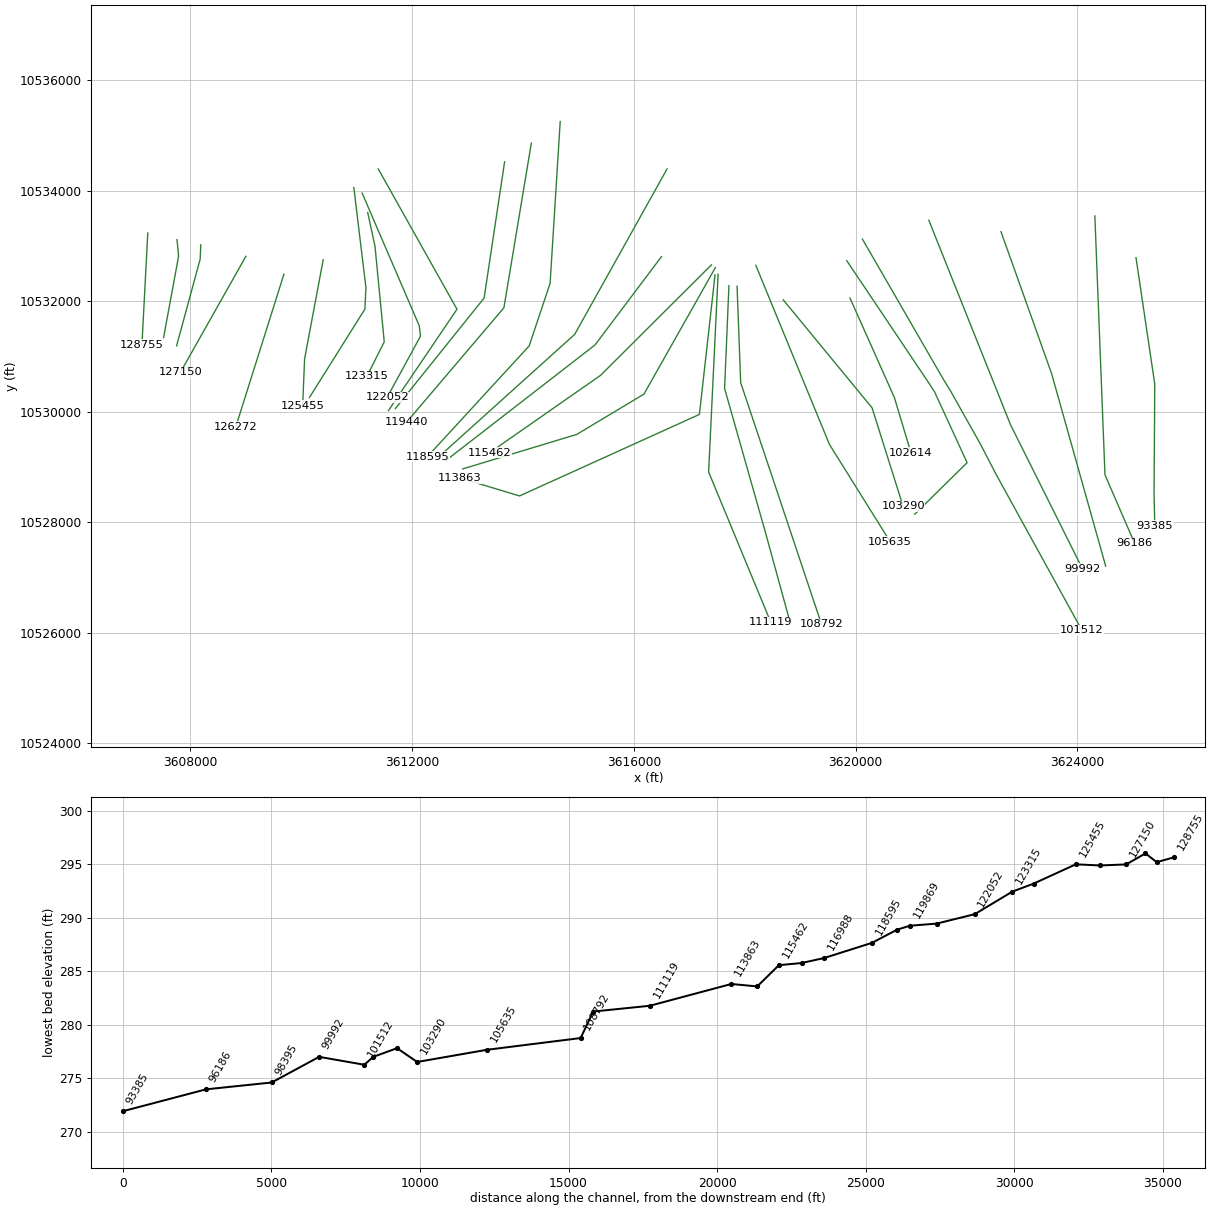
HEC-RAS study BUFFALO CREEK.prj: BUFFALO CREEK Base Level Engineering

--- BUFFALO CREEK.g01 (geometry) --- (continued)

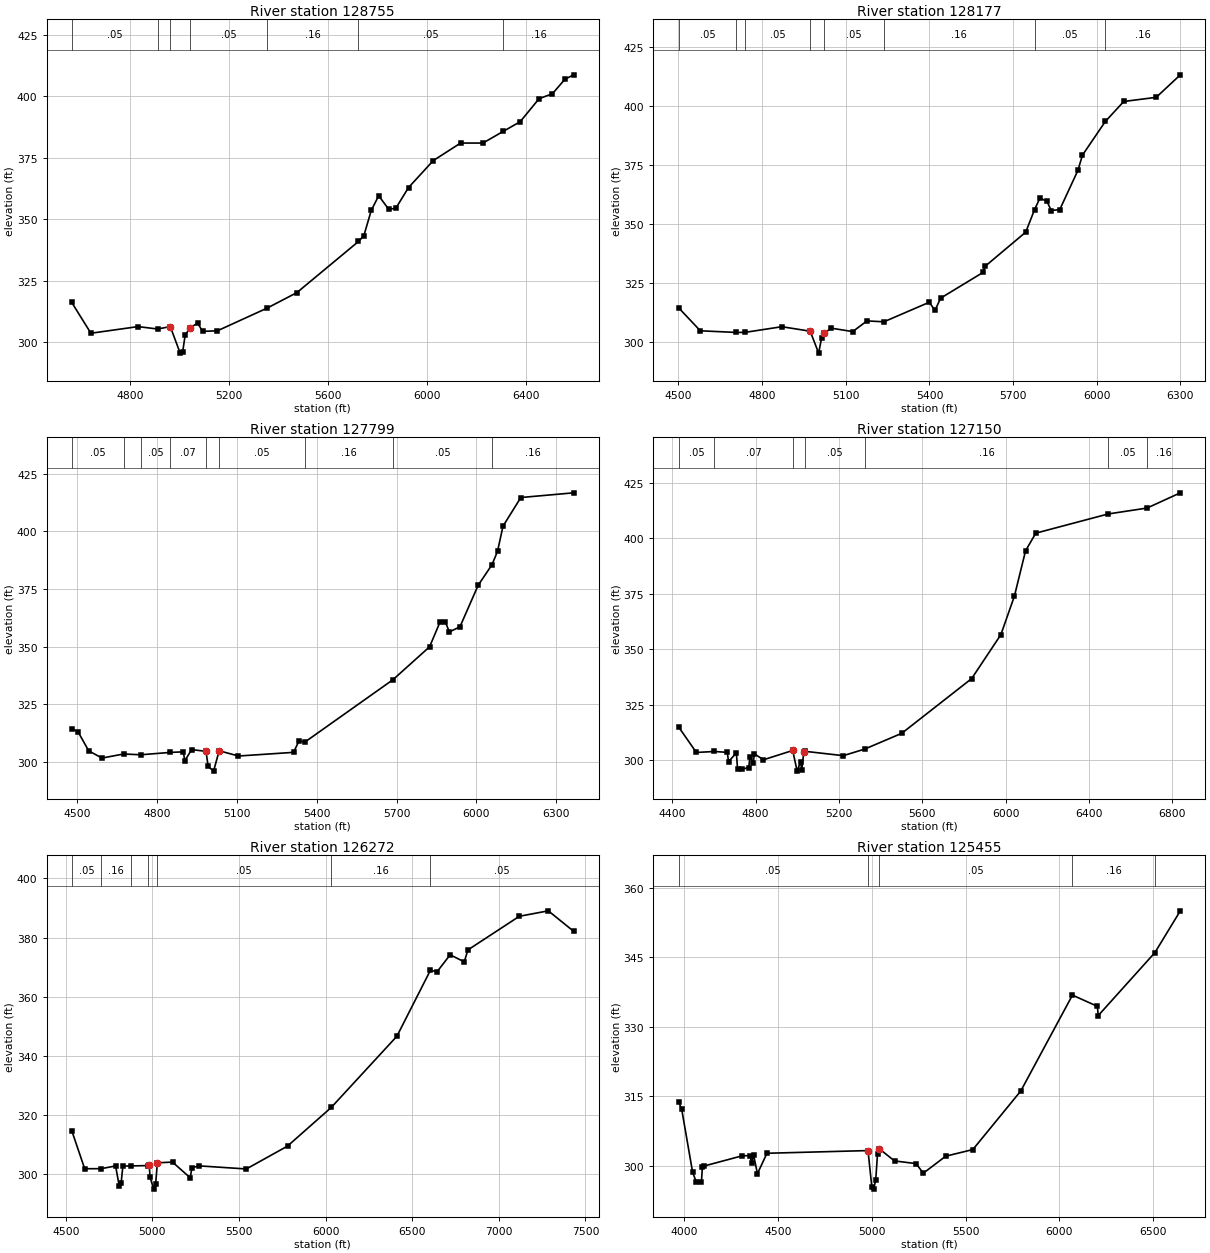
Type RM Length L Ch R = 1 ,128755  ,578,578,578
BEGIN DESCRIPTION:
BUFFALO CREEK 77.0
END DESCRIPTION:
XS GIS Cut Line= 2
      3607232.83     10533237.36      3607127.44      10531214.9
#Sta/Elev= 30
  4565.3  316.24  4642.6  303.74  4832.8  306.44  4911.7  305.46    4963  306.44
  5002.8  295.66  5013.1  296.24  5023.1  303.07  5043.1  305.87  5073.2  307.91
  5093.2  304.49  5153.3  304.74  5353.5  313.94  5473.7  320.24  5722.4  341.02
  5744.1  343.38  5774.1  353.68  5804.1  359.61  5844.2  354.13  5872.8  354.48
  5924.3  362.93  6024.4   373.9  6134.6  381.02  6224.7  381.02  6306.4  385.75
  6374.9  389.69  6451.4  399.06  6505.1  401.05  6555.2   406.9  6590.5  408.74
#Mann= 7 ,-1 , 0
  4565.3     .05       0  4911.7     .07       0    4963    .035       0
  5043.1     .05       0  5353.5     .16       0  5722.4     .05       0
  6306.4     .16       0
Bank Sta=4963,5043.1
XS Rating Curve= 0 ,0
Exp/Cntr=0.3,0.1

Type RM Length L Ch R = 1 ,128177  ,378,378,378
BEGIN DESCRIPTION:
BUFFALO CREEK 76.0
END DESCRIPTION:
XS GIS Cut Line= 3
      3607759.94       10533118.      3607789.33     10532820.62
      3607518.09     10531345.07
#Sta/Elev= 30
  4500.3   314.5  4578.5  304.69    4708  303.99  4739.3  304.03  4870.7  306.42
  4972.4  304.52  5002.7  295.21  5013.1  301.55  5023.2  303.63  5047.6  305.81
  5124.9  304.35  5175.8  308.88  5236.8  308.51  5399.4   316.8  5419.8  313.34
  5440.1  318.55  5592.6   329.5  5598.7  331.98  5745.1  346.55  5776.6  356.06
    5796  361.01  5821.1  359.63  5836.7  355.74  5867.2  356.13  5932.3  372.79
  5948.5  379.23  6030.7  393.55  6096.7  402.01    6213  403.77  6299.4  413.32
#Mann= 8 ,-1 , 0
  4500.3     .05       0    4708      .1       0  4739.3     .05       0
  4972.4    .035       0  5023.2     .05       0  5236.8     .16       0
  5776.6     .05       0  6030.7     .16       0
Bank Sta=4972.4,5023.2
XS Rating Curve= 0 ,0
Exp/Cntr=0.3,0.1

Type RM Length L Ch R = 1 ,127799  ,649,649,649
BEGIN DESCRIPTION:
BUFFALO CREEK 75.0
END DESCRIPTION:
XS GIS Cut Line= 3
      3608189.37     10533023.91      3608177.78     10532764.19
      3607752.73     10531194.09
#Sta/Elev= 30
  4479.1  314.41  4502.8  313.06  4542.9  304.81  4592.9   301.7  4674.3  303.46
  4738.6  303.12  4849.7  304.15  4898.6  304.39    4904  300.52  4929.7  305.34
  4983.8  304.62  4991.9  298.05  5012.3  296.03  5033.3  304.86  5105.8  302.58
    5313  304.17  5333.7  309.23  5354.5  308.54  5686.2  335.62  5824.3  349.92
  5864.1  360.79  5882.8  360.89  5898.8  356.36  5938.7  358.63  6007.1  376.62
  6058.9   385.5  6079.7   391.3  6100.4  402.22  6167.4  414.63  6365.7  416.67
#Mann= 9 ,-1 , 0
  4479.1     .05       0  4674.3      .1       0  4738.6     .05       0
  4849.7     .07       0  4983.8    .035       0  5033.3     .05       0
  5354.5     .16       0  5686.2     .05       0  6058.9     .16       0
Bank Sta=4983.8,5033.3
XS Rating Curve= 0 ,0
Exp/Cntr=0.3,0.1

Type RM Length L Ch R = 1 ,127150  ,878,878,878
BEGIN DESCRIPTION:
BUFFALO CREEK 74.0
END DESCRIPTION:
XS GIS Cut Line= 2
      3609001.97     10532814.91      3607821.87     10530715.56
#Sta/Elev= 30
  4430.3  314.97    4516  303.41  4602.8  303.85  4664.6  303.45  4670.3   299.3
    4708  303.18  4713.7  295.98  4735.4  295.94  4767.3  296.58    4773  301.45
  4788.9  298.82  4794.7  302.79    4838  300.11  4978.3  304.31  4999.7     295
  5015.9  299.21  5021.6   295.5  5031.8  303.74  5037.6  303.92  5221.2  301.97
  5323.8  304.93  5501.7  312.04    5837  336.68  5977.3  356.48  6042.3  373.83
  6095.9  394.31    6145  402.23  6492.5  410.88  6678.9  413.54  6838.6   420.4
#Mann= 7 ,-1 , 0
  4430.3     .05       0  4602.8     .07       0  4978.3    .035       0
  5037.6     .05       0  5323.8     .16       0  6492.5     .05       0
  6678.9     .16       0
Bank Sta=4978.3,5031.8
XS Rating Curve= 0 ,0
Exp/Cntr=0.3,0.1

Type RM Length L Ch R = 1 ,126272  ,817,817,817
BEGIN DESCRIPTION:
BUFFALO CREEK 73.0
END DESCRIPTION:
XS GIS Cut Line= 2
      3609688.48      10532491.6      3608820.16     10529728.21
#Sta/Elev= 30
  4534.9  314.68  4609.5   301.8  4704.1  301.82  4787.9  302.74  4808.9  296.01
  4819.7  296.86  4829.9   302.7  4877.9  302.75  4976.4  302.87  4981.7  303.08
  4987.1  298.91  5007.8   294.9  5019.3  296.78    5029  303.81  5116.5  304.04
    5219  298.73  5228.2  302.15  5270.1  302.77  5542.7  301.72  5780.3  309.46
  6032.5  322.52  6411.7  346.63  6605.2  368.95  6643.3  368.43    6719  374.18
  6800.5   371.8  6821.5  375.83  7118.3  387.21  7285.6  389.06  7431.5  382.15
#Mann= 7 ,-1 , 0
  4534.9     .05       0  4704.1     .16       0  4877.9     .05       0
  4976.4     .03       0    5029     .05       0  6032.5     .16       0
  6605.2     .05       0
Bank Sta=4981.7,5029
XS Rating Curve= 0 ,0
Exp/Cntr=0.3,0.1

Type RM Length L Ch R = 1 ,125455  ,1422,1422,1422
BEGIN DESCRIPTION:
BUFFALO CREEK 72.0
END DESCRIPTION:
XS GIS Cut Line= 3
      3610397.33     10532754.21      3610061.46     10530958.64
      3610026.74     10530107.96
#Sta/Elev= 30
  3968.2  313.85  3985.3  312.22  4043.5  298.64  4063.9  296.48  4090.5  296.55
  4095.6  299.75  4104.5  299.99  4306.1  302.17  4348.7  302.25  4358.7  300.72
  4369.1  302.32  4389.4  298.34  4440.3  302.74  4979.5  303.32  4999.8  295.56
  5009.7  295.01  5020.8  297.04  5030.3   302.6  5040.5  303.68    5121  301.09
  5236.4  300.51  5274.5  298.44  5394.3  302.11    5539  303.54  5794.9  316.17
  6070.6  336.83  6203.4  334.42  6208.4  332.43  6510.9  346.01  6646.3     355
#Mann= 5 ,-1 , 0
  3968.2     .05       0  4979.5     .03       0  5040.5     .05       0
  6070.6     .16       0  6510.9     .05       0
Bank Sta=4979.5,5040.5
XS Rating Curve= 0 ,0
Exp/Cntr=0.3,0.1

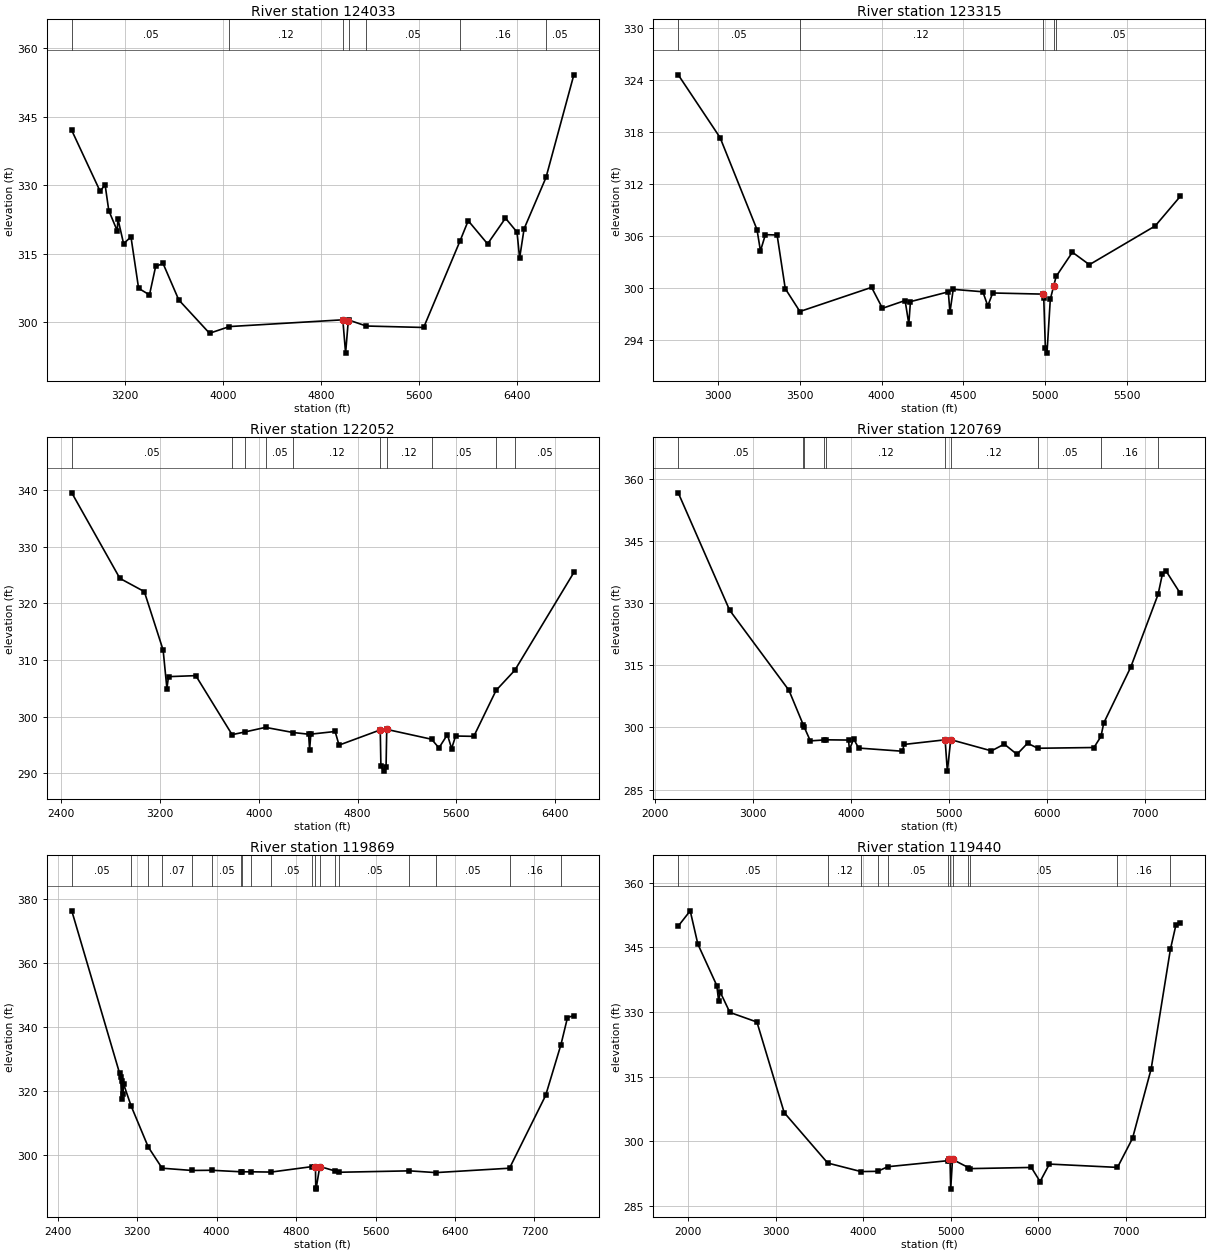
Type RM Length L Ch R = 1 ,124033  ,718,718,718
BEGIN DESCRIPTION:
BUFFALO CREEK 71.0
END DESCRIPTION:
XS GIS Cut Line= 4
      3610949.61     10534060.19      3611167.95     10532250.25
      3611149.61     10531860.19      3610149.58     10530260.15
#Sta/Elev= 30
  2764.9  341.99  2996.6  328.65  3036.9  330.11  3067.1  324.44  3136.6  319.97
  3141.6  322.68  3187.9  317.19  3248.4  318.66  3310.7   307.4  3399.5  305.96
  3449.8  312.18  3510.3  312.85  3638.9  304.85    3890  297.55  4052.6  299.02
  4978.5   300.5  5001.2   293.2  5022.7  300.14  5028.6  300.43  5169.9  299.14
  5638.8  298.82    5936  317.79  6002.6  322.21  6160.7  317.13  6306.9  322.77
  6401.2  319.71  6422.4  314.02    6459  320.44  6637.9  331.68  6865.3  354.17
#Mann= 7 ,-1 , 0
  2764.9     .05       0  4052.6     .12       0  4978.5     .05       0
  5028.6     .12       0  5169.9     .05       0    5936     .16       0
  6637.9     .05       0
Bank Sta=4978.5,5022.7
XS Rating Curve= 0 ,0
Exp/Cntr=0.3,0.1

Type RM Length L Ch R = 1 ,123315  ,1263,1263,1263
BEGIN DESCRIPTION:
BUFFALO CREEK 70.0
END DESCRIPTION:
XS GIS Cut Line= 4
      3611199.61     10533610.17       3611331.5     10532999.13
      3611498.36      10531266.6      3611184.36     10530641.38
#Sta/Elev= 30
    2759  324.61  3014.6  317.35  3239.8  306.73    3261  304.26    3291  306.14
  3362.6   306.1  3412.4   299.9  3501.8  297.26  3939.4  300.05  4005.9  297.63
  4144.1  298.53  4166.7  295.82  4176.7   298.4  4407.8  299.53  4417.8  297.16
  4437.9  299.82  4618.7  299.54  4648.9  297.91    4679   299.4  4983.3  299.27
  4990.5  298.83  5000.5  293.07  5010.3  292.45  5030.6  298.68  5050.7  300.17
  5066.1  301.31  5165.4  304.11  5269.2  302.67  5671.2  307.15  5824.3  310.57
#Mann= 5 ,-1 , 0
    2759     .05       0  3501.8     .12       0  4983.3     .05       0
  5050.7     .12       0  5066.1     .05       0
Bank Sta=4983.3,5050.7
XS Rating Curve= 0 ,0
Exp/Cntr=0.3,0.1

Type RM Length L Ch R = 1 ,122052  ,1283,1283,1283
BEGIN DESCRIPTION:
BUFFALO CREEK 69.0
END DESCRIPTION:
XS GIS Cut Line= 4
      3611099.62     10533960.17      3612128.89     10531560.15
      3612152.33     10531370.04      3611549.62      10530260.2
#Sta/Elev= 30
  2485.6  339.56  2875.3  324.43  3073.1  322.09  3225.5  311.74    3256  304.95
    3269  307.05  3489.9  307.23  3783.9  296.79  3888.9  297.27  4054.7  298.08
  4280.3  297.16  4403.6  296.87  4411.5  294.11  4421.7  296.88  4618.2  297.35
  4650.1  294.94  4983.7  297.63  4989.1   291.2  5012.5  290.34  5030.8  291.15
  5036.3  297.72  5399.3  295.98  5459.1  294.45  5527.4  296.79  5561.7  294.33
    5594  296.55  5741.3  296.49  5921.7  304.62  6073.4  308.18  6551.5  325.47
#Mann= 10 ,-1 , 0
  2485.6     .05       0  3783.9     .07       0  3888.9     .12       0
  4054.7     .05       0  4280.3     .12       0  4983.7     .05       0
  5036.3     .12       0  5399.3     .05       0  5921.7     .16       0
  6073.4     .05       0
Bank Sta=4983.7,5036.3
XS Rating Curve= 0 ,0
Exp/Cntr=0.3,0.1

Type RM Length L Ch R = 1 ,120769  ,900,900,900
BEGIN DESCRIPTION:
BUFFALO CREEK 68.0
END DESCRIPTION:
XS GIS Cut Line= 3
      3611391.11     10534396.52      3612810.39     10531857.42
      3611574.04     10530022.41
#Sta/Elev= 30
  2236.9  356.64  2760.9  328.32  3366.2  308.97  3512.5  300.62  3523.5     300
  3584.5  296.76  3728.4  296.99  3743.5  297.02    3974  296.96    3983  294.64
  4026.4  297.22  4077.1  295.03  4524.4  294.26  4540.3   295.9  4959.3  297.02
  4981.9  289.46  5016.6  297.06  5431.8  294.35  5563.1  295.98    5692  293.51
    5800  296.19  5904.5  294.98  6477.6  295.16  6549.1  297.84  6577.3  301.07
  6852.4  314.54  7131.4   332.1  7176.3   337.1  7212.3  337.79  7358.4  332.35
#Mann= 10 ,-1 , 0
  2236.9     .05       0  3512.5     .16       0  3523.5     .12       0
  3728.4     .05       0  3743.5     .12       0  4959.3     .05       0
  5016.6     .12       0  5904.5     .05       0  6549.1     .16       0
  7131.4     .05       0
Bank Sta=4959.3,5016.6
XS Rating Curve= 0 ,0
Exp/Cntr=0.3,0.1

Type RM Length L Ch R = 1 ,119869  ,429,429,429
BEGIN DESCRIPTION:
BUFFALO CREEK 67.0
END DESCRIPTION:
XS GIS Cut Line= 3
      3613669.77     10534526.72      3613299.61     10532060.19
      3611699.61     10530060.19
#Sta/Elev= 30
  2541.1  376.35    3023  325.47  3033.1  324.26  3042.8  317.47  3047.9  323.03
  3053.3  318.89  3063.4  322.09  3138.6   315.3  3310.9  302.45  3450.8  295.81
  3750.2   295.1  3949.7  295.16  4249.1  294.68  4259.4  294.68  4348.9  294.68
  4548.5   294.6  4961.2  296.31  4994.8  296.34  4997.7  289.76  5000.5  289.26
  5038.5  296.34  5193.4  294.93  5234.9  294.54  5940.9  294.98  6207.6  294.43
  6948.9  295.81  7312.4  318.57  7466.9  334.51  7532.5  342.94  7596.5  343.58
#Mann= 19 ,-1 , 0
  2541.1     .05       0  3138.6      .1       0  3310.9     .05       0
  3450.8     .07       0  3750.2     .12       0  3949.7     .05       0
  4249.1     .12       0  4259.4     .05       0  4348.9     .07       0
  4548.5     .05       0  4961.2     .16       0  4994.8     .05       0
  5038.5     .16       0  5193.4     .12       0  5234.9     .05       0
  5940.9     .16       0  6207.6     .05       0  6948.9     .16       0
  7466.9     .05       0
Bank Sta=4994.8,5038.5
XS Rating Curve= 0 ,0
Exp/Cntr=0.3,0.1

Type RM Length L Ch R = 1 ,119440  ,845,845,845
BEGIN DESCRIPTION:
BUFFALO CREEK 66.0
END DESCRIPTION:
XS GIS Cut Line= 3
      3614151.54     10534865.23      3613656.75     10531883.47
      3611899.59     10529810.16
#Sta/Elev= 30
  1884.4  349.91  2021.3  353.45  2108.7  345.73  2325.4  336.11  2345.7  332.63
  2365.9  334.53  2474.4  329.89  2784.3  327.65  3095.8  306.64  3593.6  294.94
  3974.3  292.96    4165  293.02  4279.9  294.09  4968.7  295.49  4985.5  295.89
    4992  295.44  4999.5  288.89  5020.6  295.98  5028.3   295.7  5200.9   293.9
  5224.2  293.65  5921.4  293.92  6021.4  290.64  6127.9   294.7  6906.4  293.93
  7078.1  300.66  7291.3  316.77  7511.5  344.53  7574.7  350.18  7624.7  350.73
#Mann= 12 ,-1 , 0
  1884.4     .05       0  3593.6     .12       0  3974.3     .05       0
    4165     .12       0  4279.9     .05       0  4968.7      .5       0
    4992     .07       0  5028.3     .16       0  5200.9     .12       0
  5224.2     .05       0  6906.4     .16       0  7511.5     .05       0
Bank Sta=4985.5,5020.6
XS Rating Curve= 0 ,0
Exp/Cntr=0.3,0.1

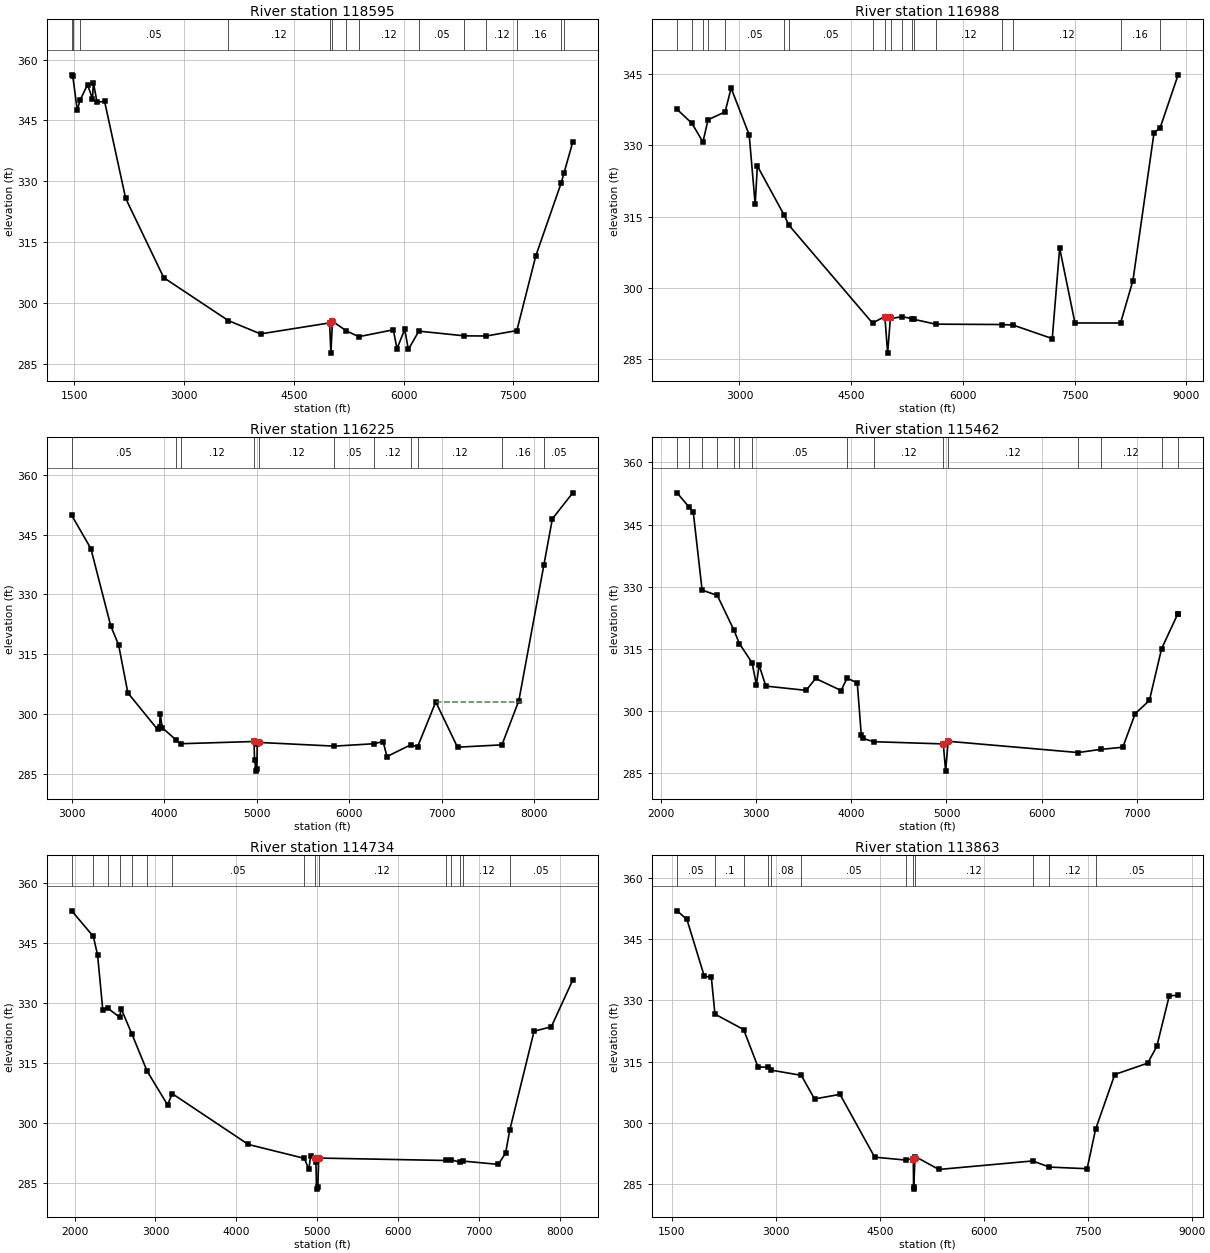
Type RM Length L Ch R = 1 ,118595  ,1607,1607,1607
BEGIN DESCRIPTION:
BUFFALO CREEK 65.0
END DESCRIPTION:
XS GIS Cut Line= 4
      3614672.37     10535255.91      3614490.08     10532326.17
      3614112.48     10531193.36      3612276.55     10529188.17
#Sta/Elev= 30
  1463.8  356.25  1478.5  355.89  1539.7  347.56    1577  349.98  1679.9  353.81
  1747.5  350.35  1760.1  354.27  1810.2   349.5  1913.1   349.7  2200.9  325.81
  2721.9  306.25  3604.3  295.68  4044.5   292.4  4988.1  295.11  5006.1  287.66
  5027.4  295.52  5218.7  293.13  5387.3  291.71  5859.3  293.41  5909.3  288.74
  6015.3  293.52  6064.7  288.56  6208.1  293.08  6829.7  291.92  7130.9  291.88
  7547.4  293.22  7806.1   311.6  8154.6  329.65  8193.8  332.16    8312   339.7
#Mann= 14 ,-1 , 0
  1463.8     .16       0  1478.5     .08       0    1577     .05       0
  3604.3     .12       0  4988.1     .05       0  5027.4     .12       0
  5218.7     .16       0  5387.3     .12       0  6208.1     .05       0
  6829.7     .16       0  7130.9     .12       0  7547.4     .16       0
  8154.6     .05       0  8193.8     .16       0
Bank Sta=4988.1,5027.4
XS Rating Curve= 0 ,0
Exp/Cntr=0.3,0.1

Type RM Length L Ch R = 1 ,116988  ,763,763,763
BEGIN DESCRIPTION:
BUFFALO CREEK 64.0
END DESCRIPTION:
XS GIS Cut Line= 3
      3616599.43     10534396.45      3614932.79      10531401.7
      3612484.87     10529188.15
#Sta/Elev= 30
  2162.5  337.56  2362.6  334.61  2509.8  330.68    2578  335.36  2807.5  337.03
  2888.5  342.03    3131  332.18  3211.1  317.58  3240.7  325.64  3599.8  315.31
  3663.9  313.18  4786.7  292.57  4952.5  293.95  4989.9  286.24  5027.9  293.85
  5033.6  293.54  5186.5   293.9  5323.1  293.49  5349.4  293.33  5633.4  292.34
    6530  292.26  6675.8  292.14    7200   289.3  7299.4  308.35  7504.9  292.59
  8117.3  292.58  8283.5  301.53  8566.7  332.65  8648.5  333.67  8890.1  344.83
#Mann= 18 ,-1 , 0
  2162.5      .1       0  2362.6     .08       0  2509.8     .05       0
    2578     .08       0  2807.5     .05       0  3599.8     .16       0
  3663.9     .05       0  4786.7     .12       0  4952.5     .05       0
  5033.6     .12       0  5186.5     .16       0  5323.1     .12       0
  5349.4     .16       0  5633.4     .12       0    6530     .05       0
  6675.8     .12       0  8117.3     .16       0  8648.5     .05       0
#XS Ineff= 1 ,-1
 7297.73 8371.59  304.71
Permanent Ineff=
       F
Bank Sta=4952.5,5027.9
XS Rating Curve= 0 ,0
Exp/Cntr=0.3,0.1

Type RM Length L Ch R = 1 ,116225  ,763,763,763
BEGIN DESCRIPTION:
BUFFALO CREEK 63.0
END DESCRIPTION:
XS GIS Cut Line= 3
      3616499.59     10532810.17      3615299.61     10531210.19
      3612599.61     10529110.19
#Sta/Elev= 30
  2998.7  349.82    3206  341.49  3420.5  322.16    3506  317.37    3606  305.37
  3926.8  296.23  3948.7  296.75    3956  300.17  3976.8  296.66    4125  293.63
  4176.8  292.63  4970.5  293.19  4976.8  288.55  4995.3  285.77  5001.8  286.27
  5005.9  292.45  5020.4  292.96  5840.5  292.03  6268.8  292.63  6366.9  293.18
  6409.4  289.43  6667.6  292.37  6740.3  291.86    6937  303.11  7172.2  291.76
  7652.9  292.35  7835.5   303.4  8107.2  337.47  8198.4  348.96  8419.2  355.46
#Mann= 11 ,-1 , 0
  2998.7     .05       0    4125     .16       0  4176.8     .12       0
  4970.5     .05       0  5020.4     .12       0  5840.5     .05       0
  6268.8     .12       0  6667.6     .05       0  6740.3     .12       0
  7652.9     .16       0  8107.2     .05       0
#XS Ineff= 1 ,-1
  6935.8 7886.36  303.13
Permanent Ineff=
       F
Bank Sta=4970.5,5020.4
XS Rating Curve= 0 ,0
Exp/Cntr=0.3,0.1

Type RM Length L Ch R = 1 ,115462  ,728,728,728
BEGIN DESCRIPTION:
BUFFALO CREEK 62.0
END DESCRIPTION:
XS GIS Cut Line= 3
      3617399.61     10532660.19      3615399.61     10530660.19
      3613399.64     10529260.21
#Sta/Elev= 30
  2166.6  352.68  2294.3   349.2  2336.3  348.14  2429.8  329.23    2590  327.93
  2764.6  319.58  2821.8  316.33    2955  311.72    3001  306.42  3029.3  311.14
    3100  306.08  3524.2  305.04  3623.2  307.92  3891.9  305.01  3954.7  308.01
  4061.7  306.84  4104.1  294.28  4118.2  293.48  4233.6  292.67  4966.7  292.13
  4991.2  285.57  5017.3  292.77  6384.1  290.05  6621.5  290.81  6854.4  291.33
  6984.7  299.42  7134.2  302.61  7262.4  315.09  7432.7  323.49  7436.3  323.58
#Mann= 15 ,-1 , 0
  2166.6     .05       0  2294.3     .08       0  2429.8      .1       0
    2590     .08       0  2764.6     .05       0  2821.8     .08       0
    2955     .05       0  3954.7     .07       0  4233.6     .12       0
  4966.7     .05       0  5017.3     .12       0  6384.1     .05       0
  6621.5     .12       0  7262.4     .16       0  7432.7     .05       0
Bank Sta=4966.7,5017.3
XS Rating Curve= 0 ,0
Exp/Cntr=0.3,0.1

Type RM Length L Ch R = 1 ,114734  ,871,871,871
BEGIN DESCRIPTION:
Mapping XS cf5e046a
END DESCRIPTION:
XS GIS Cut Line= 4
      3617471.83      10532612.6      3616182.79     10530320.97
      3614971.85      10529591.8      3612914.62     10528966.82
#Sta/Elev= 30
    1965  353.16  2232.1  346.76  2284.5  342.14  2349.5   328.3  2408.1  328.86
  2556.2  326.58  2576.4  328.66  2708.9  322.35  2897.5  313.05  3149.5  304.65
    3207  307.45  4147.7  294.75  4840.5  291.27    4896  288.49  4917.3  291.83
  4975.6  291.39  4983.2  290.26  4990.9  283.58  5006.6   284.2  5018.3  291.35
  6589.7  290.74  6649.9  290.96  6761.6  290.32  6801.7  290.59  7236.4  289.77
    7327  292.56  7379.2  298.35  7679.5  323.06  7892.5  324.17  8157.9  335.86
#Mann= 15 ,-1 , 0
    1965     .05       0  2232.1     .08       0  2408.1      .1       0
  2556.2     .08       0  2708.9     .05       0  2897.5     .16       0
    3207     .05       0  4840.5     .12       0  4975.6     .05       0
  5018.3     .12       0  6589.7     .16       0  6649.9     .12       0
  6761.6     .05       0  6801.7     .12       0  7379.2     .05       0
Bank Sta=4975.6,5018.3
XS Rating Curve= 0 ,0
Exp/Cntr=0.3,0.1

Type RM Length L Ch R = 1 ,113863  ,2744,2744,2744
BEGIN DESCRIPTION:
Mapping XS fa41c79c
END DESCRIPTION:
XS GIS Cut Line= 4
      3617465.44      10532481.3      3617183.32     10529953.11
      3613938.96     10528477.42      3612864.79     10528802.92
#Sta/Elev= 30
  1573.6  351.89  1715.6   349.8  1967.1  335.86  2067.8  335.68  2120.4  326.62
    2534  322.85  2741.9   313.7  2882.6  313.63  2930.9  312.92  3366.1  311.65
    3557  305.87  3924.9  306.99  4425.1  291.63    4871  290.92  4977.5   291.3
    4983  290.96  4986.4  284.31  4989.2  283.81    5006   291.5  5011.5  291.77
    5352  288.62  6703.9   290.7  6947.3   289.2  7491.3   288.8  7612.5  298.43
    7890  311.85  8364.5  314.63    8496  318.71  8676.4  331.11  8804.1  331.22
#Mann= 12 ,-1 , 0
  1573.6     .05       0  2120.4      .1       0    2534     .08       0
  2882.6     .05       0  2930.9     .08       0  3366.1     .05       0
    4871     .12       0  4977.5     .07       0  5011.5     .12       0
  6703.9     .16       0  6947.3     .12       0  7612.5     .05       0
Bank Sta=4977.5,5006
XS Rating Curve= 0 ,0
Exp/Cntr=0.3,0.1

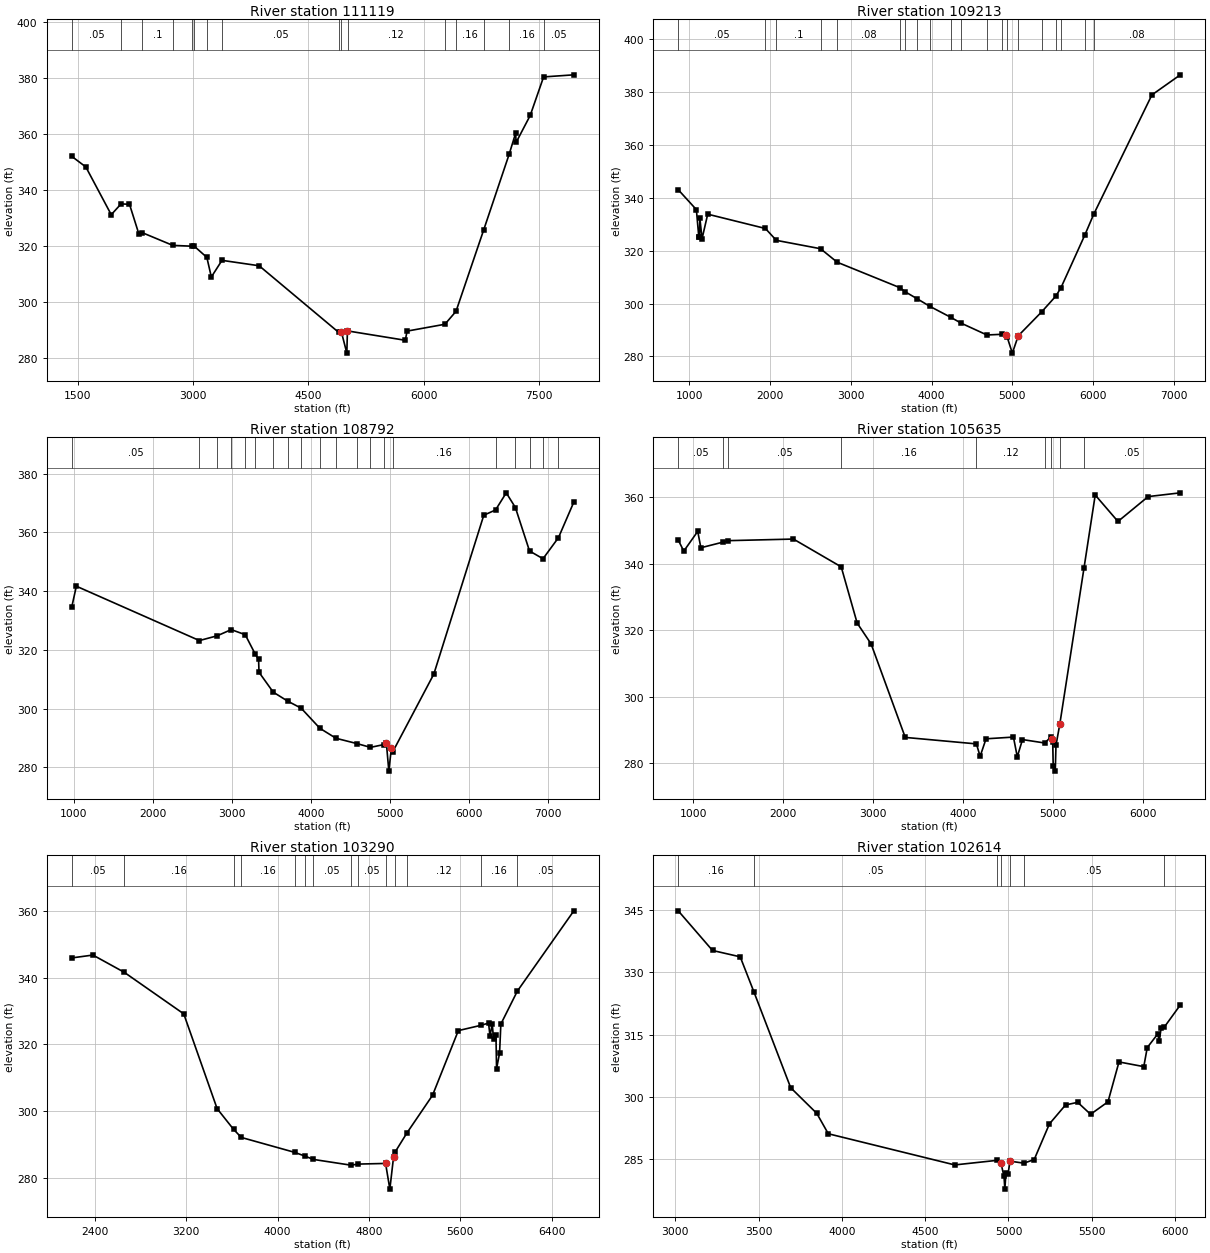
Type RM Length L Ch R = 1 ,111119  ,1906,1906,1906
BEGIN DESCRIPTION:
BUFFALO CREEK 61.0
END DESCRIPTION:
XS GIS Cut Line= 3
      3617520.46     10532492.85      3617349.61     10528910.19
      3618470.98     10526190.75
#Sta/Elev= 30
    1423  352.06  1605.9  348.27  1936.2  331.22  2063.8  335.07  2173.6  334.94
  2296.7  324.22  2338.3  324.81  2736.3  320.26  2980.4  319.97  3007.2  320.17
  3179.4  315.97  3237.7  308.96  3376.2  314.91  3859.3  312.98  4893.3  289.19
  4929.6  289.26  4999.5  281.77  5007.2   289.7  5009.7   289.7  5759.4  286.36
  5783.4  289.64  6274.7  292.08  6419.2   296.7  6778.5  325.74  7110.5  352.84
  7194.7  360.37  7200.1  357.01  7383.9  366.67  7557.9  380.43  7951.3  381.18
#Mann= 16 ,-1 , 0
    1423     .05       0  2063.8     .08       0  2338.3      .1       0
  2736.3     .08       0  2980.4      .1       0  3007.2     .05       0
  3179.4     .08       0  3376.2     .05       0  4893.3     .12       0
  4929.6     .07       0  5009.7     .12       0  6274.7     .05       0
  6419.2     .16       0  6778.5     .05       0  7110.5     .16       0
  7557.9     .05       0
Bank Sta=4929.6,5007.2
XS Rating Curve= 0 ,0
Exp/Cntr=0.3,0.1

Type RM Length L Ch R = 1 ,109213  ,421,421,421
BEGIN DESCRIPTION:
BUFFALO CREEK 60.0
END DESCRIPTION:
XS GIS Cut Line= 4
      3617715.77     10532284.47      3617637.65     10530422.53
      3618376.36     10527809.68      3618806.66     10526234.24
#Sta/Elev= 30
   865.8   343.1  1090.3  335.56  1120.3  325.17  1128.7   325.1  1133.7  332.27
  1160.3  324.53  1230.4  333.84  1944.4  328.42  2079.5  323.93  2626.3  320.76
  2832.6  315.65  3606.6  306.03  3676.3  304.41  3823.3  301.79  3977.2  298.97
  4235.1  294.83  4367.2  292.56  4685.1   288.1  4872.6  288.36  4926.7  288.23
  4934.9  287.37  4999.5  281.23  5072.9   287.8  5363.5  296.89  5538.3  302.84
  5601.4  306.01    5897  325.98  6005.2  333.74  6726.4     379  7077.8   386.6
#Mann= 20 ,-1 , 0
   865.8     .05       0  1944.4     .08       0  2079.5      .1       0
  2626.3     .08       0  2832.6     .08       0  3606.6      .1       0
  3676.3     .08       0  3823.3      .1       0  3977.2     .08       0
  4235.1     .05       0  4367.2     .08       0  4685.1      .1       0
  4872.6     .08       0  4934.9     .07       0  5072.9     .08       0
  5363.5     .08       0  5538.3     .05       0  5601.4     .08       0
    5897     .05       0  6005.2     .08       0
Bank Sta=4926.7,5072.9
XS Rating Curve= 0 ,0
Exp/Cntr=0.3,0.1

Type RM Length L Ch R = 1 ,108792  ,3157,3157,3157
BEGIN DESCRIPTION:
BUFFALO CREEK 59.0
END DESCRIPTION:
XS GIS Cut Line= 3
      3617862.47     10532274.13      3617927.58      10530529.3
      3619385.75     10526154.77
#Sta/Elev= 30
   974.6  334.65  1032.7  341.71  2590.5   323.2  2816.4  324.83  2993.4  326.93
  3170.7   325.2  3299.7  318.48    3340  316.84  3345.3  312.41    3525  305.65
    3708  302.59  3879.2  300.18  4116.3  293.33  4320.5  289.93  4587.7  288.11
  4756.6  286.84  4926.4  287.79  4958.1  288.28  4989.4  278.75  5021.3  286.63
  5038.7  285.32  5558.9  311.79  6191.4  365.87  6340.5  367.67    6476   373.5
  6591.5   368.5  6770.5   353.7  6941.4  351.06  7137.4  358.26  7331.8  370.37
#Mann= 20 ,-1 , 0
   974.6     .05       0  2590.5     .08       0  2816.4     .05       0
  2993.4     .08       0  3170.7     .05       0  3299.7     .08       0
    3525     .05       0    3708     .08       0  3879.2     .05       0
  4116.3     .08       0  4320.5     .08       0  4587.7     .12       0
  4756.6     .16       0  4926.4     .07       0  5038.7     .16       0
  6340.5     .08       0  6591.5     .05       0  6770.5     .16       0
  6941.4     .05       0  7137.4     .08       0
Bank Sta=4958.1,5021.3
XS Rating Curve= 0 ,0
Exp/Cntr=0.3,0.1

Type RM Length L Ch R = 1 ,105635  ,2345,2345,2345
BEGIN DESCRIPTION:
BUFFALO CREEK 58.0
END DESCRIPTION:
XS GIS Cut Line= 3
      3618201.02     10532651.69      3619529.14     10529409.51
       3620622.9     10527651.68
#Sta/Elev= 30
   835.4  347.07     897  343.75  1051.8  349.68  1086.6  344.76  1337.1  346.48
  1387.9  346.89  2114.4  347.37  2644.8  339.02  2821.7  322.13  2976.5  315.87
  3355.7  287.78  4145.7  285.83    4187  282.09  4252.6  287.36  4556.9  287.88
  4599.4  281.95  4657.2  287.13  4903.9   286.1  4977.1  288.03    4986  287.43
  4992.5  286.51  4998.3  279.22  5021.1  277.65  5029.1  285.39  5071.5  291.77
  5339.8  338.61  5464.6   360.6  5717.2  352.66  6052.5  360.13  6409.4  361.26
#Mann= 9 ,-1 , 0
   835.4     .05       0  1337.1     .16       0  1387.9     .05       0
  2644.8     .16       0  4145.7     .12       0  4903.9     .16       0
  4977.1     .07       0  5071.5     .16       0  5339.8     .05       0
Bank Sta=4986,5071.5
XS Rating Curve= 0 ,0
Exp/Cntr=0.3,0.1

Type RM Length L Ch R = 1 ,103290  ,676,676,676
BEGIN DESCRIPTION:
BUFFALO CREEK 57.0
END DESCRIPTION:
XS GIS Cut Line= 3
      3618695.78     10532026.73      3620297.37     10530073.57
      3620857.26     10528289.73
#Sta/Elev= 30
  2198.8  345.98    2384  346.84  2657.7  341.67  3179.2  329.17  3471.3  300.69
    3615  294.48  3683.1  292.04  4148.9  287.57  4243.1   286.4  4312.7  285.44
  4644.2   283.7    4703  284.03  4946.1  284.23  4983.5  276.51  5016.2  286.23
  5032.1   287.8  5133.2   293.4  5357.1   304.7    5583  324.14  5783.4  325.75
  5847.6   326.4  5860.1  322.52    5880  326.11  5891.6   321.5  5912.4   322.8
  5917.7  312.68    5944  317.37  5955.3   326.1  6099.9  336.02  6594.3  360.13
#Mann= 14 ,-1 , 0
  2198.8     .05       0  2657.7     .16       0    3615     .05       0
  3683.1     .16       0  4148.9     .05       0  4243.1     .16       0
  4312.7     .05       0  4644.2     .07       0    4703     .05       0
  4946.1     .04       0  5032.1     .05       0  5133.2     .12       0
  5783.4     .16       0  6099.9     .05       0
Bank Sta=4946.1,5016.2
XS Rating Curve= 0 ,0
Exp/Cntr=0.3,0.1

Type RM Length L Ch R = 1 ,102614  ,800,800,800
BEGIN DESCRIPTION:
BUFFALO CREEK 56.0
END DESCRIPTION:
XS GIS Cut Line= 3
      3619899.62     10532060.16      3620699.61     10530260.19
      3620999.62     10529260.16
#Sta/Elev= 30
  3017.6  344.84  3223.4  335.29  3389.6  333.76  3471.1  325.39  3692.6  302.23
  3849.2  296.05  3918.3  291.14  4677.5  283.63  4932.6  284.74  4955.2  284.01
    4973  280.88  4978.2   277.8  4984.6  281.61  4997.8  281.56  5009.1  284.54
  5092.3  284.05  5154.4  284.93  5245.7  293.51  5342.3  298.07  5415.4  298.71
  5492.8  295.83  5597.2  298.83  5663.3  308.44  5812.1  307.31    5833   311.9
  5895.6  315.16  5905.2  313.47  5916.5  316.71    5934  316.76  6031.4  322.16
#Mann= 7 ,-1 , 0
  3017.6     .16       0  3471.1     .05       0  4932.6     .07       0
  4955.2     .05       0  5009.1     .16       0  5092.3     .05       0
    5934     .16       0
Bank Sta=4955.2,5009.1
XS Rating Curve= 0 ,0
Exp/Cntr=0.3,0.1

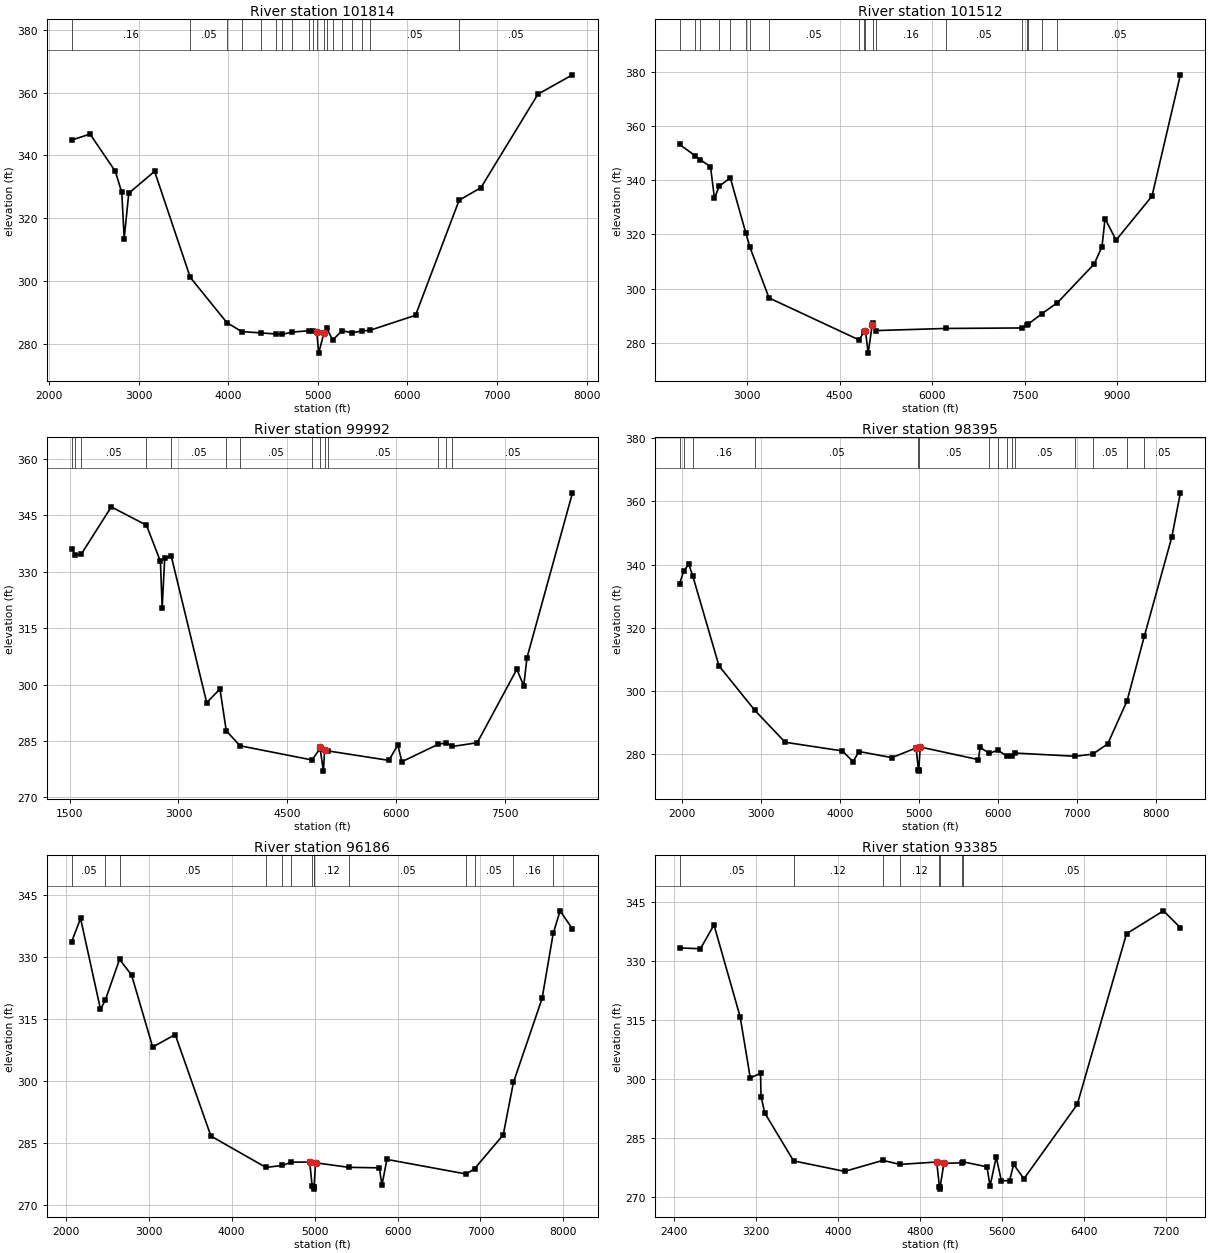
Type RM Length L Ch R = 1 ,101814  ,302,302,302
BEGIN DESCRIPTION:
BUFFALO CREEK 55.0
END DESCRIPTION:
XS GIS Cut Line= 5
      3619841.72     10532736.39      3621328.27     10530511.98
      3621425.93     10530360.07      3622011.87     10529079.69
      3621067.84     10528146.51
#Sta/Elev= 30
  2250.9  344.86  2455.4  346.78  2737.7  334.92  2809.8   328.2  2836.9  313.49
  2887.9  327.93  3176.2   334.9  3574.8   301.1  3982.9  286.72  4148.5  283.86
  4367.5  283.42  4526.5   283.1  4597.5  282.96  4712.5  283.69  4904.6  284.13
  4942.3  283.89  4987.7   283.6  5008.6  276.99  5066.3   283.3  5098.6  284.84
  5165.5  281.19  5271.5  284.16  5377.5  283.47  5490.9  284.03  5580.8  284.26
    6090  289.05  6576.8  325.71  6820.3   329.7  7456.7  359.49  7842.4  365.65
#Mann= 19 ,-1 , 0
  2250.9     .16       0  3574.8     .05       0  3982.9     .08       0
  4148.5     .08       0  4367.5     .08       0  4526.5     .05       0
  4597.5     .08       0  4712.5     .05       0  4904.6     .08       0
  4942.3     .16       0  4987.7     .05       0  5066.3     .08       0
  5098.6      .1       0  5165.5     .05       0  5271.5     .08       0
  5377.5     .05       0  5490.9     .08       0  5580.8     .05       0
  6576.8     .05       0
Bank Sta=4987.7,5066.3
XS Rating Curve= 0 ,0
Exp/Cntr=0.3,0.1

Type RM Length L Ch R = 1 ,101512  ,1520,1520,1520
BEGIN DESCRIPTION:
BUFFALO CREEK 54.0
END DESCRIPTION:
XS GIS Cut Line= 6
      3620123.82     10533127.04       3621595.2     10530569.49
      3621725.41     10530356.82      3622254.92     10529410.64
       3622532.7     10528872.44      3624082.19      10526046.9
#Sta/Elev= 30
  1909.3  353.19    2165  348.97  2245.8  347.55  2409.9  344.99  2474.6   333.3
  2549.8  337.78  2730.8  340.87  2979.7  320.72  3046.7   315.4  3358.1   296.6
  4817.8   281.1  4892.8  283.95    4906  284.18  4919.9  284.48  4964.4  276.25
  5030.1  286.77    5036  287.31  5098.8  284.57  6224.7  285.35  7450.8  285.53
  7541.5  286.63  7560.3  287.01  7779.4  290.82    8031  294.85  8626.5  309.14
    8752  315.52  8801.5  325.85  8980.1  317.91  9561.8  334.14 10021.7  378.86
#Mann= 19 ,-1 , 0
  1909.3     .05       0    2165     .08       0  2245.8     .05       0
  2549.8     .08       0  2730.8     .05       0  2979.7     .08       0
  3046.7     .16       0  3358.1     .05       0  4817.8     .12       0
  4892.8     .05       0    4906     .05       0    5036     .12       0
  5098.8     .16       0  6224.7     .05       0  7450.8     .16       0
  7541.5     .05       0  7560.3     .16       0  7779.4     .08       0
    8031     .05       0
Bank Sta=4919.9,5030.1
XS Rating Curve= 0 ,0
Exp/Cntr=0.3,0.1

Type RM Length L Ch R = 1 ,99992   ,1597,1597,1597
BEGIN DESCRIPTION:
BUFFALO CREEK 53.0
END DESCRIPTION:
XS GIS Cut Line= 3
      3621321.76      10533468.8      3622793.12     10529770.88
      3624094.54     10527155.02
#Sta/Elev= 30
  1528.5  336.15  1580.7   334.4  1661.8  334.75  2073.8  347.29  2558.5  342.42
    2751  332.81  2775.3  320.51  2810.3   333.6  2901.4  334.11  3388.9  295.21
  3571.9  298.83  3658.7  287.72  3848.4  283.73  4839.8  279.96  4944.2  282.79
  4949.6  283.28  4997.9  276.99  5014.1  282.56  5055.2  282.38  5900.1  279.85
  6022.7  283.97  6078.8   279.5  6583.5  284.16    6691   284.5  6776.4  283.56
  7117.5  284.54  7663.1   304.1  7758.3  299.69    7803  307.16  8430.1  351.03
#Mann= 14 ,-1 , 0
  1528.5     .05       0  1580.7     .16       0  1661.8     .05       0
  2558.5     .16       0  2901.4     .05       0  3658.7     .16       0
  3848.4     .05       0  4839.8     .16       0  4944.2     .07       0
  5014.1     .16       0  5055.2     .05       0  6583.5     .07       0
    6691     .12       0  6776.4     .05       0
Bank Sta=4949.6,5014.1
XS Rating Curve= 0 ,0
Exp/Cntr=0.3,0.1

Type RM Length L Ch R = 1 ,98395   ,2209,2209,2209
BEGIN DESCRIPTION:
BUFFALO CREEK 52.0
END DESCRIPTION:
XS GIS Cut Line= 3
      3622623.85     10533260.45      3623535.31     10530695.36
      3624511.88     10527205.74
#Sta/Elev= 30
  1964.3  333.93  2017.7  338.01    2081  340.09  2132.6  336.27  2463.4  307.92
  2917.6  293.84  3301.8  283.73    4028  280.98  4161.4  277.59  4238.7   280.8
  4654.7  278.86  4961.9  281.94    4990  275.09  4992.8  274.59    4996  275.09
  5013.2  282.23  5751.1  278.23  5771.8  282.12  5890.7  280.18  5993.5  281.23
  6110.5  279.39  6175.7   279.4  6208.2  280.32  6980.6  279.29    7200  279.97
  7389.6  283.22  7634.8  296.86    7853  317.27  8201.7   348.7  8310.2  362.71
#Mann= 15 ,-1 , 0
  1964.3     .16       0  2017.7     .05       0  2132.6     .16       0
  2917.6     .05       0    4990     .03       0    4996     .05       0
  5890.7     .07       0  5993.5     .05       0  6110.5     .12       0
  6175.7     .07       0  6208.2     .05       0  6980.6     .07       0
    7200     .05       0  7634.8     .16       0    7853     .05       0
Bank Sta=4961.9,5013.2
XS Rating Curve= 0 ,0
Exp/Cntr=0.3,0.1

Type RM Length L Ch R = 1 ,96186   ,2801,2801,2801
BEGIN DESCRIPTION:
Mapping XS 2bd4acb0
END DESCRIPTION:
XS GIS Cut Line= 3
      3624316.55     10533546.94      3624498.85     10528859.42
       3625032.1     10527623.84
#Sta/Elev= 30
  2072.6  333.71  2179.4   339.3  2419.6  317.35  2476.1  319.49  2649.5  329.42
  2794.7  325.61  3048.5  308.25  3320.3  311.26  3750.6  286.76  4414.1  279.19
  4610.2  279.66  4721.5  280.45  4941.5  280.49  4970.9  274.79  4988.6  274.45
  4991.3  273.95  4994.6  274.45  5011.6  280.31  5413.5  279.21  5782.2  279.09
  5812.2  274.87  5872.2  281.12  6829.9  277.59  6929.1  278.88  7274.7  287.05
  7397.2  299.69  7743.1  319.98  7876.9  335.66  7959.9  341.13  8109.4  336.75
#Mann= 14 ,-1 , 0
  2072.6     .05       0  2476.1     .08       0  2649.5     .05       0
  4414.1     .07       0  4610.2     .12       0  4721.5     .16       0
  4970.9     .12       0  4988.6     .07       0  4994.6     .12       0
  5413.5     .05       0  6829.9     .07       0  6929.1     .05       0
  7397.2     .16       0  7876.9     .05       0
Bank Sta=4941.5,5011.6
XS Rating Curve= 0 ,0
Exp/Cntr=0.3,0.1

Type RM Length L Ch R = 1 ,93385   ,2332,2332,2332
BEGIN DESCRIPTION:
BUFFALO CREEK 51.0
END DESCRIPTION:
XS GIS Cut Line= 4
      3625058.74     10532791.72      3625397.28     10530500.05
      3625384.26     10528520.88      3625397.28     10527935.08
#Sta/Elev= 30
  2457.9  333.22  2661.6  333.03    2793  339.08  3048.1  315.72  3146.8   300.2
  3246.8  301.33  3251.9  295.42  3288.3  291.25  3568.9  279.08  4066.7  276.41
  4439.5  279.21  4605.8  278.19  4964.3  278.79  4991.3   272.4  4994.1   271.9
  4997.3   272.4  5034.3  278.44  5207.5  278.61  5217.2  278.86  5454.3  277.57
  5484.3  272.66  5544.3  280.07  5594.3  274.05  5674.3  274.02  5714.3  278.19
  5814.3  274.53  6334.3  293.43  6814.4  336.83  7174.4  342.66  7339.6  338.39
#Mann= 8 ,-1 , 0
  2457.9     .05       0  3568.9     .12       0  4439.5     .16       0
  4605.8     .12       0  4991.3     .07       0  4997.3     .12       0
  5207.5     .16       0  5217.2     .05       0
Bank Sta=4964.3,5034.3
XS Rating Curve= 0 ,0
Exp/Cntr=0.3,0.1