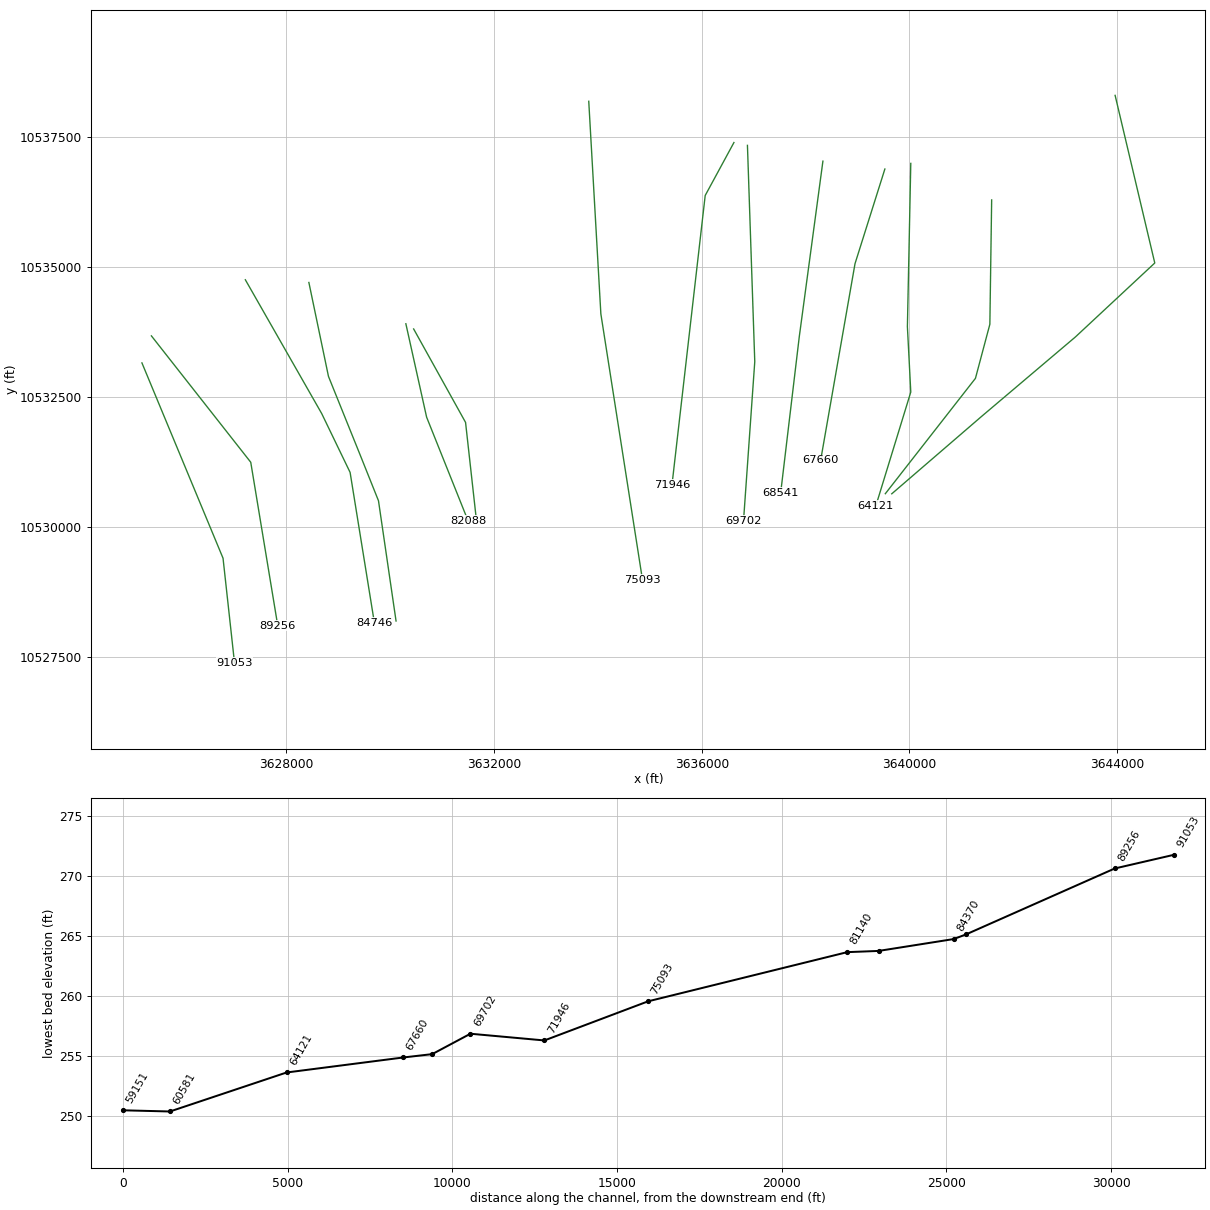
HEC-RAS study BUFFALO CREEK.prj: BUFFALO CREEK Base Level Engineering

--- BUFFALO CREEK.g01 (geometry) --- (continued)

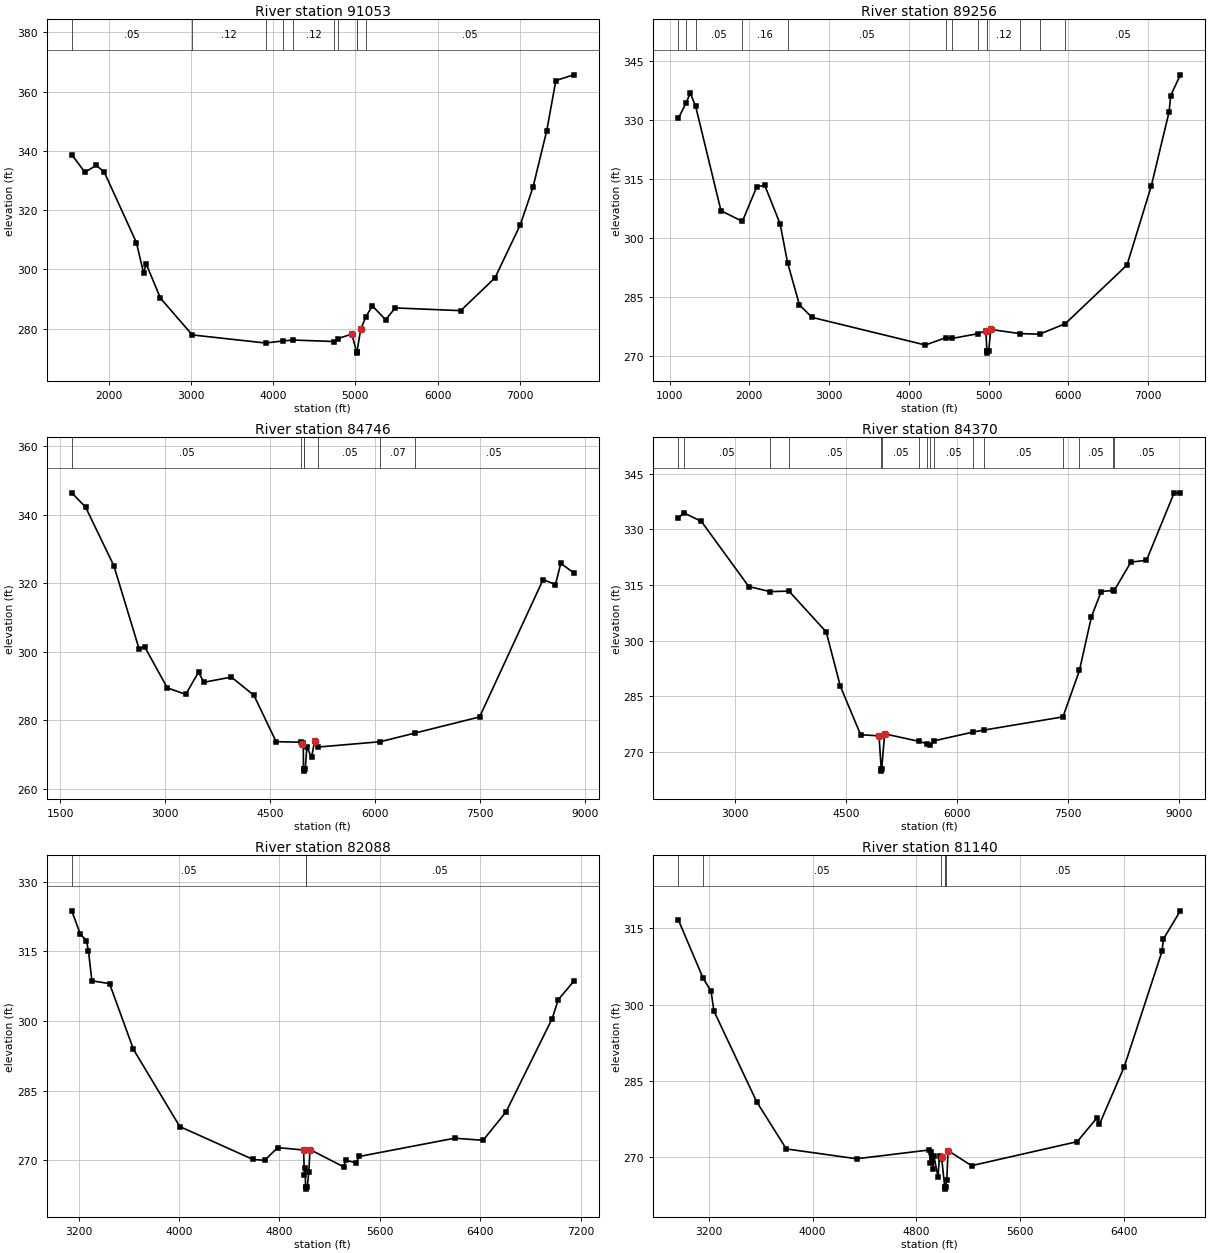
Type RM Length L Ch R = 1 ,91053   ,1797,1797,1797
BEGIN DESCRIPTION:
BUFFALO CREEK 50.0
END DESCRIPTION:
XS GIS Cut Line= 3
        3625215.     10533156.28      3626777.49     10529393.28
      3626998.84     10527375.08
#Sta/Elev= 30
  1550.2  338.79  1709.7  332.83  1849.1  335.16  1946.6  332.79  2336.7   309.1
    2423  298.87  2455.5  301.87  2628.7  290.32  3016.2   277.9  3906.9  275.18
  4117.8  275.87  4239.8  276.18  4743.1  275.68  4786.5  276.64  4956.7   278.2
  5013.8  272.26  5016.6  271.76  5019.8  272.26  5064.6  279.82  5126.6  283.92
  5205.8  287.74  5368.2  283.01  5484.3  287.02  6281.7   286.1  6699.1  297.21
    7006  315.09  7159.8  327.68  7327.9  346.88  7438.6  363.79    7655  365.71
#Mann= 10 ,-1 , 0
  1550.2     .05       0  3016.2     .12       0  3906.9     .05       0
  4117.8      .1       0  4239.8     .12       0  4743.1     .16       0
  4786.5     .12       0  5013.8     .07       0  5019.8     .12       0
  5126.6     .05       0
Bank Sta=4956.7,5064.6
XS Rating Curve= 0 ,0
Exp/Cntr=0.3,0.1

Type RM Length L Ch R = 1 ,89256   ,4510,4510,4510
BEGIN DESCRIPTION:
BUFFALO CREEK 49.0
END DESCRIPTION:
XS GIS Cut Line= 3
      3625397.29     10533677.12      3627311.35     10531242.23
      3627832.18     10528091.22
#Sta/Elev= 30
  1111.2  330.52  1205.8  334.31  1259.9  336.89  1326.9  333.52  1644.4  306.92
  1912.6  304.19  2093.5  313.04  2192.9  313.39  2385.4  303.59  2479.2  293.67
  2627.6  282.93  2784.8  279.74  4206.5  272.69  4465.3  274.57    4538  274.35
  4867.2  275.58  4964.9  276.34  4977.7  271.12  4980.5  270.62  4983.7  271.12
    5001  271.17  5025.9  276.65  5394.1  275.59  5638.2  275.45  5959.8  278.12
  6734.2  293.08  7038.3  313.24  7261.2   332.1  7281.5  336.24  7402.1  341.55
#Mann= 13 ,-1 , 0
  1111.2     .05       0  1205.8     .08       0  1326.9     .05       0
  1912.6     .16       0  2479.2     .05       0  4465.3     .12       0
    4538     .05       0  4867.2     .12       0  4977.7     .07       0
  4983.7     .12       0  5394.1     .16       0  5638.2     .12       0
  5959.8     .05       0
Bank Sta=4964.9,5025.9
XS Rating Curve= 0 ,0
Exp/Cntr=0.3,0.1

Type RM Length L Ch R = 1 ,84746   ,376,376,376
BEGIN DESCRIPTION:
BUFFALO CREEK 48.0
END DESCRIPTION:
XS GIS Cut Line= 4
      3627207.19     10534757.83      3628678.53     10532179.73
      3629225.41     10531046.92      3629694.01     10528144.22
#Sta/Elev= 30
  1665.2  346.41  1862.9  342.23  2266.1  325.12  2626.1  300.86  2706.8  301.42
  3029.4  289.45  3292.9  287.55  3475.8  294.05  3550.7  291.07  3943.9   292.6
  4266.5  287.27  4583.3  273.73  4939.6  273.57  4955.1  273.12  4970.7  273.21
  4974.3  265.63  4977.1  265.13  4980.3  265.63  4999.5  265.75  5021.8  272.18
  5089.3  269.15  5134.5  274.06  5187.8  272.17  6070.3  273.72  6563.9  276.24
  7488.7  280.95  8395.8  321.08  8572.5  319.61  8647.9  325.83  8831.8  323.07
#Mann= 7 ,-1 , 0
  1665.2     .05       0  4939.6     .16       0  4974.3     .07       0
  4980.3     .16       0  5187.8     .05       0  6070.3     .07       0
  6563.9     .05       0
Bank Sta=4955.1,5134.5
XS Rating Curve= 0 ,0
Exp/Cntr=0.3,0.1

Type RM Length L Ch R = 1 ,84370   ,2282,2282,2282
BEGIN DESCRIPTION:
BUFFALO CREEK 47.0
END DESCRIPTION:
XS GIS Cut Line= 5
      3628431.15     10534705.73      3628808.74     10532895.88
      3629433.74      10531346.4      3629772.28     10530500.05
      3630110.62     10528183.78
#Sta/Elev= 30
  2242.3  333.06  2311.5  334.49  2551.2  332.18  3191.2  314.58  3477.4  313.21
  3733.7  313.34  4236.3  302.32  4426.9  287.66  4701.1  274.56  4949.1  274.27
  4978.5  265.24  4981.2  264.74  4984.5  265.24  5024.6  274.81  5492.9  272.75
  5597.1  272.14  5639.5  271.76  5693.7  272.93  6218.8  275.29  6361.2  275.81
    7431  279.39  7652.9  291.91  7815.3  306.45  7946.7  313.22  8104.3  313.54
  8116.8  313.33    8348  321.17  8557.9  321.67    8927   339.7  9014.3  339.88
#Mann= 16 ,-1 , 0
  2242.3     .08       0  2311.5     .05       0  3477.4     .08       0
  3733.7     .05       0  4978.5     .03       0  4984.5     .05       0
  5492.9     .08       0  5597.1      .1       0  5639.5     .08       0
  5693.7     .05       0  6218.8     .08       0  6361.2     .05       0
    7431     .08       0  7652.9     .05       0  8104.3     .08       0
  8116.8     .05       0
Bank Sta=4949.1,5024.6
XS Rating Curve= 0 ,0
Exp/Cntr=0.3,0.1

Type RM Length L Ch R = 1 ,82088   ,948,948,948
BEGIN DESCRIPTION:
BUFFALO CREEK 46.0
END DESCRIPTION:
XS GIS Cut Line= 3
       3630299.6     10533910.23      3630699.61     10532110.19
       3631499.6     10530110.21
#Sta/Elev= 30
  3145.3  323.76  3213.2  318.75  3261.9  317.32  3278.5  315.11  3305.4  308.68
  3446.3  308.06  3637.1  293.86  4005.8  277.24  4589.7  270.14  4681.9  269.96
  4785.7   272.7  4991.9  272.19  4998.7   266.7  5004.1  268.35  5007.8  264.25
  5010.5  263.75  5013.8  264.25  5021.6  264.26  5033.7  267.55  5043.1  272.28
  5312.4  268.53  5327.2  270.02  5410.6  269.39  5434.9  270.79  6195.5  274.73
  6421.7  274.28  6604.8  280.41  6972.3  300.52  7020.8   304.6  7143.3  308.55
#Mann= 3 ,-1 , 0
  3145.3     .05       0  5007.8     .03       0  5013.8     .05       0
Bank Sta=4991.9,5043.1
XS Rating Curve= 0 ,0
Exp/Cntr=0.3,0.1

Type RM Length L Ch R = 1 ,81140   ,6047,6047,6047
BEGIN DESCRIPTION:
BUFFALO CREEK 45.0
END DESCRIPTION:
XS GIS Cut Line= 3
      3630449.59     10533810.22      3631449.61     10532010.19
      3631649.61     10530210.22
#Sta/Elev= 30
  2965.1  316.64  3155.3  305.19  3216.8  302.62  3238.5  298.74  3569.1  280.83
  3796.8  271.57    4339  269.63  4898.4  271.36  4907.6  268.87  4913.3  270.87
  4929.3  267.69    4935  270.15  4967.1  266.07  4978.5  270.14  4989.8  269.64
  4994.5  269.88  5018.4  264.15  5021.1  263.65  5024.4  264.15  5025.3  264.15
  5034.3  265.38  5044.4  271.24  5225.5  268.27  6040.5     273  6191.4  277.66
  6211.5  276.41  6402.7  287.74  6694.5  310.51  6704.5   312.9  6835.3  318.46
#Mann= 6 ,-1 , 0
  2965.1     .16       0  3155.3     .05       0  4989.8     .16       0
  5018.4     .07       0  5024.4     .16       0  5025.3     .05       0
Bank Sta=4994.5,5044.4
XS Rating Curve= 0 ,0
Exp/Cntr=0.3,0.1

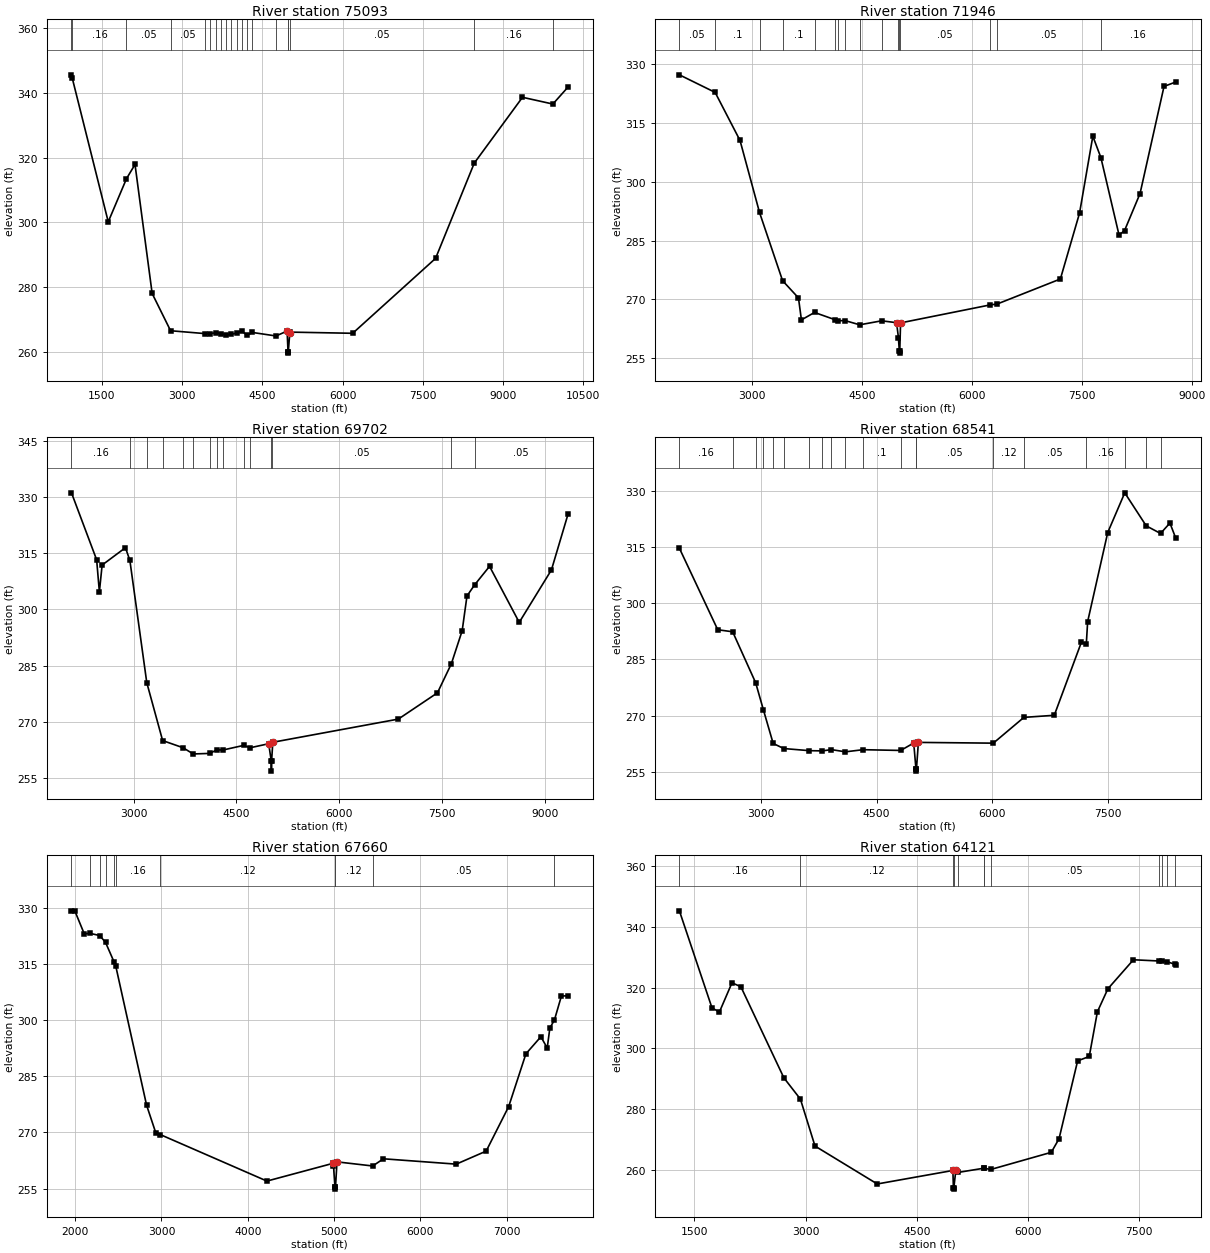
Type RM Length L Ch R = 1 ,75093   ,3147,3147,3147
BEGIN DESCRIPTION:
BUFFALO CREEK 44.0
END DESCRIPTION:
XS GIS Cut Line= 3
      3633822.94     10538196.38      3634056.24     10534100.03
      3634857.66     10528980.06
#Sta/Elev= 30
   930.4  345.66   945.3   344.6  1617.7  300.18  1959.2  313.53  2118.5  317.93
    2439  278.01  2783.7  266.48  3429.2  265.59    3528  265.62  3627.6  265.83
    3724  265.61  3822.1  265.14  3920.1  265.33  4018.2   265.8  4116.2  266.41
  4214.3  265.06  4312.3  265.95  4755.1  264.86  4963.1  266.38  4980.1  260.05
  4982.9  259.55  4986.1  260.05  5013.2  265.89  5023.4  266.05  6189.5  265.69
  7739.8  288.87  8463.2  318.34  9365.3  338.71  9933.4  336.62 10215.7  341.85
#Mann= 20 ,-1 , 0
   930.4     .05       0   945.3     .16       0  1959.2     .05       0
  2783.7     .05       0  3429.2     .12       0    3528     .05       0
  3627.6     .12       0    3724     .07       0  3822.1     .05       0
  3920.1     .07       0  4018.2      .1       0  4116.2     .05       0
  4214.3     .12       0  4312.3     .05       0  4755.1     .12       0
  4980.1     .07       0  4986.1     .12       0  5023.4     .05       0
  8463.2     .16       0  9933.4     .05       0
Bank Sta=4963.1,5013.2
XS Rating Curve= 0 ,0
Exp/Cntr=0.3,0.1

Type RM Length L Ch R = 1 ,71946   ,2244,2244,2244
BEGIN DESCRIPTION:
BUFFALO CREEK 43.0
END DESCRIPTION:
XS GIS Cut Line= 3
      3636619.68     10537401.35      3636066.32     10536381.43
      3635426.19     10530804.72
#Sta/Elev= 30
  2010.3  327.24    2498  322.76  2837.6   310.5  3103.4  292.16  3418.4  274.75
  3634.9  270.37  3675.2  264.76    3854  266.66  4130.4  264.83  4172.6  264.55
  4271.8  264.58  4470.2  263.51    4770  264.53  4973.7  264.05  4998.6  260.26
  5010.9  256.79  5013.7  256.29  5016.9  256.79  5028.1     264  6254.8   268.6
  6343.2  268.79  7208.3  275.19    7470     292  7651.1  311.59  7760.9  306.15
  8008.6   286.4    8084  287.54  8295.3  296.98  8622.5  324.29    8784  325.42
#Mann= 16 ,-1 , 0
  2010.3     .05       0    2498      .1       0  3103.4     .05       0
  3418.4      .1       0    3854     .07       0  4130.4      .1       0
  4172.6     .05       0  4271.8     .12       0  4470.2     .05       0
    4770     .12       0  4998.6     .05       0  5010.9     .03       0
  5016.9     .05       0  6254.8     .08       0  6343.2     .05       0
  7760.9     .16       0
Bank Sta=4973.7,5028.1
XS Rating Curve= 0 ,0
Exp/Cntr=0.3,0.1

Type RM Length L Ch R = 1 ,69702   ,1161,1161,1161
BEGIN DESCRIPTION:
BUFFALO CREEK 42.0
END DESCRIPTION:
XS GIS Cut Line= 3
      3636880.12     10537347.09      3637021.18     10533180.47
      3636804.17     10530109.74
#Sta/Elev= 30
    2093   331.1  2460.1  313.24  2500.1  304.67  2540.2  311.83  2880.4  316.46
  2945.1  313.09  3192.1  280.45  3423.4     265  3722.3  263.09  3869.7  261.43
  4114.1  261.58  4212.5  262.51  4310.5  262.51  4604.6  263.71  4702.6  263.09
  4971.6  264.16  5008.6  259.61  5011.3  256.85  5014.6  259.61  5031.6  264.55
  6863.8  270.73  7435.2  277.74  7637.9  285.48  7796.1  294.31  7866.3  303.58
  7976.8  306.52  8195.7  311.49    8629  296.54  9099.3  310.54  9340.4  325.35
#Mann= 15 ,-1 , 0
    2093     .16       0  2945.1     .05       0  3192.1      .1       0
  3423.4     .07       0  3722.3     .12       0  3869.7     .05       0
  4114.1     .12       0  4212.5      .1       0  4310.5     .05       0
  4604.6      .1       0  4702.6     .05       0  5008.6     .03       0
  5014.6     .05       0  7637.9     .16       0  7976.8     .05       0
Bank Sta=4971.6,5031.6
XS Rating Curve= 0 ,0
Exp/Cntr=0.3,0.1

Type RM Length L Ch R = 1 ,68541   ,881,881,881
BEGIN DESCRIPTION:
BUFFALO CREEK 41.0
END DESCRIPTION:
XS GIS Cut Line= 3
      3638334.11     10537043.29      3637878.39     10533657.91
      3637520.49     10530653.77
#Sta/Elev= 30
  1941.1  314.75  2438.7  292.95  2632.2  292.41  2930.8  278.77  3030.3  271.59
  3157.8  262.55  3295.2  261.19  3627.4  260.62  3794.9  260.56  3913.8   260.9
    4095  260.31  4323.9  260.88  4812.7  260.68  4981.4  262.67  5010.6  255.65
  5013.4  255.15  5016.6  255.65  5041.9  262.83    6014  262.63    6411  269.52
  6804.9  270.08  7157.4  289.65  7220.6  289.18  7237.9  295.13  7498.5  318.95
  7719.3  329.56  7997.7  320.73  8183.5   318.7  8305.4  321.48  8382.4  317.36
#Mann= 20 ,-1 , 0
  1941.1     .16       0  2632.2     .05       0  2930.8     .07       0
  3030.3      .1       0  3157.8     .05       0  3295.2     .07       0
  3627.4     .12       0  3794.9     .12       0  3913.8     .05       0
    4095     .05       0  4323.9      .1       0  4812.7     .12       0
  5010.6     .03       0  5016.6     .05       0    6014     .12       0
    6411     .05       0  7220.6     .16       0  7719.3     .05       0
  7997.7     .16       0  8183.5     .05       0
Bank Sta=4981.4,5041.9
XS Rating Curve= 0 ,0
Exp/Cntr=0.3,0.1

Type RM Length L Ch R = 1 ,67660   ,3539,3539,3539
BEGIN DESCRIPTION:
BUFFALO CREEK 40.0
END DESCRIPTION:
XS GIS Cut Line= 3
       3639527.7     10536891.44       3638952.6      10535068.5
      3638291.02     10531283.39
#Sta/Elev= 30
  1957.1  329.18  1997.9  329.04  2105.4  323.02  2168.9  323.18  2284.7  322.58
  2351.9  320.74  2451.3  315.49  2469.8  314.47  2827.5  277.28  2935.1  269.82
  2984.5  269.45  4222.2  257.02  4983.6  261.73  4993.7  261.13  5010.8  255.37
  5013.5  254.87  5016.8  255.37  5034.3  262.15  5448.1  261.05  5572.4  262.97
  6416.3  261.54  6763.1  265.02    7024  276.91  7223.8     291  7397.2  295.56
  7470.7  292.56  7501.2  297.88  7554.3  300.04  7635.2  306.44  7711.1  306.49
#Mann= 11 ,-1 , 0
  1957.1      .1       0  2168.9     .16       0  2284.7     .12       0
  2351.9     .16       0  2451.3     .12       0  2469.8     .16       0
  2984.5     .12       0  5010.8     .07       0  5016.8     .12       0
  5448.1     .05       0  7554.3     .16       0
Bank Sta=4983.6,5034.3
XS Rating Curve= 0 ,0
Exp/Cntr=0.3,0.1

Type RM Length L Ch R = 1 ,64121   ,3540,3540,3540
BEGIN DESCRIPTION:
BUFFALO CREEK 39.0
END DESCRIPTION:
XS GIS Cut Line= 4
      3640026.82     10536999.88      3639961.72     10533853.22
      3640026.82     10532594.54      3639354.07     10530402.66
#Sta/Elev= 30
  1296.7  345.35  1736.5  313.36  1836.5  311.98  2006.5  321.63  2126.6  320.32
  2706.7  290.31  2929.9  283.29  3126.8  267.82    3967  255.32  4987.8  259.77
  4994.8  254.12  4997.6  253.62  5000.8  254.12  5027.8  259.86  5062.1  259.14
  5402.1   260.5    5403  260.49    5501  260.11  6315.7  265.75  6420.3  270.21
  6671.4   295.9  6828.2  297.34  6938.5  312.09  7079.8  319.65  7424.5  329.22
    7774  328.81  7809.9  328.93  7877.8  328.61  7981.7  327.72  7997.2  327.59
#Mann= 12 ,-1 , 0
  1296.7     .16       0  2929.9     .12       0  4994.8     .07       0
  5000.8     .12       0  5062.1     .16       0  5402.1     .05       0
    5403     .16       0    5501     .05       0    7774     .08       0
  7809.9     .05       0  7877.8     .08       0  7981.7     .05       0
Bank Sta=4987.8,5027.8
XS Rating Curve= 0 ,0
Exp/Cntr=0.3,0.1

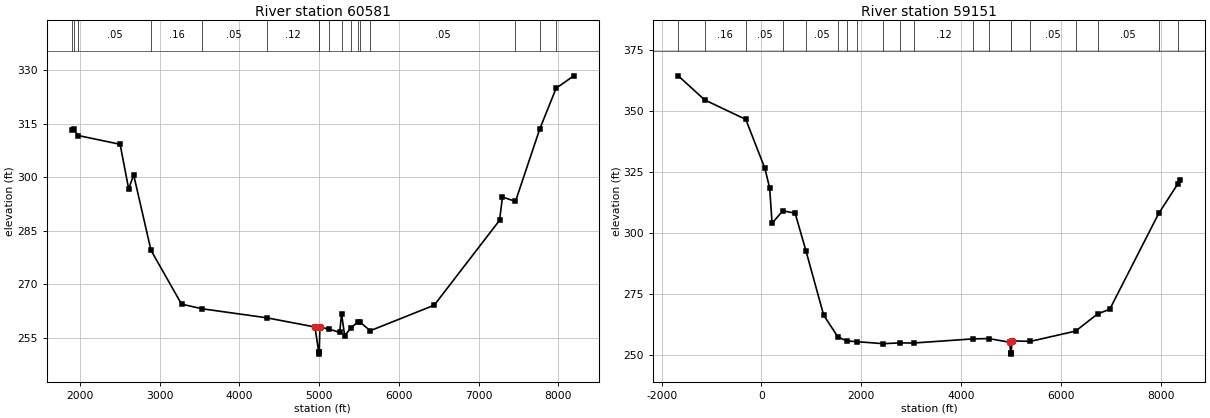
Type RM Length L Ch R = 1 ,60581   ,1430,1430,1430
BEGIN DESCRIPTION:
BUFFALO CREEK 38.0
END DESCRIPTION:
XS GIS Cut Line= 4
      3641584.98     10536296.08      3641550.26     10533900.24
      3641272.48     10532858.57      3639536.34     10530636.31
#Sta/Elev= 30
  1899.9  313.11  1922.1  313.43    1980  311.67  2505.9  309.21  2613.3   296.7
  2675.9  300.64  2892.9  279.49  3275.9  264.39  3530.3   263.1  4343.4  260.56
  4948.1  257.98  4996.8  250.87  4999.6  250.37  5002.8  250.87  5010.2  257.97
  5124.7  257.38  5258.5  256.47  5282.3  261.68  5320.6  255.55  5404.8  257.83
  5487.9  259.43    5518  259.27  5640.8  256.93  6443.5  264.09  7262.8  287.89
    7299  294.41  7462.6  293.22  7766.9  313.51  7971.9  324.94  8194.1  328.41
#Mann= 17 ,-1 , 0
  1899.9     .05       0  1922.1     .08       0    1980     .05       0
  2892.9     .16       0  3530.3     .05       0  4343.4     .12       0
  4996.8     .07       0  5002.8     .12       0  5124.7     .07       0
  5282.3     .12       0  5404.8     .05       0  5487.9     .07       0
    5518     .12       0  5640.8     .05       0  7462.6     .12       0
  7766.9     .05       0  7971.9     .08       0
Bank Sta=4948.1,5010.2
XS Rating Curve= 0 ,0
Exp/Cntr=0.3,0.1

Type RM Length L Ch R = 1 ,59151   ,286,286,286
BEGIN DESCRIPTION:
BUFFALO CREEK 37.0
END DESCRIPTION:
XS GIS Cut Line= 5
      3643963.45       10538310.      3644727.34     10535080.79
      3643199.57     10533657.18      3641385.33     10532120.72
      3639660.65     10530634.68
#Sta/Elev= 30
 -1667.1   364.3 -1138.1  354.46  -313.3  346.47    69.4  326.42   164.7  318.43
   213.2  304.02   428.7   309.1   675.6  308.11     892  292.71  1247.2  266.41
  1531.6  257.53  1707.4  255.87    1919  255.55  2439.4  254.75  2767.6  255.06
  3050.3  255.02  4241.7  256.71  4553.3  256.83  4971.4  255.35    4997  250.97
  4999.7  250.47    5003  250.97    5022   255.9  5388.5  255.68  6296.8   259.9
  6736.1  266.94  6979.6  268.81  7959.8  307.99    8345  320.15  8393.5  321.87
#Mann= 20 ,-1 , 0
 -1667.1     .05       0 -1138.1     .16       0  -313.3     .05       0
   428.7     .05       0     892     .05       0  1531.6     .08       0
  1707.4     .05       0    1919     .08       0  2439.4     .05       0
  2767.6     .07       0  3050.3     .12       0  4241.7     .05       0
  4553.3     .08       0    4997     .07       0    5003     .08       0
  5388.5     .05       0  6296.8     .08       0  6736.1     .05       0
  7959.8     .05       0    8345     .08       0
Bank Sta=4971.4,5022
XS Rating Curve= 0 ,0
Exp/Cntr=0.3,0.1