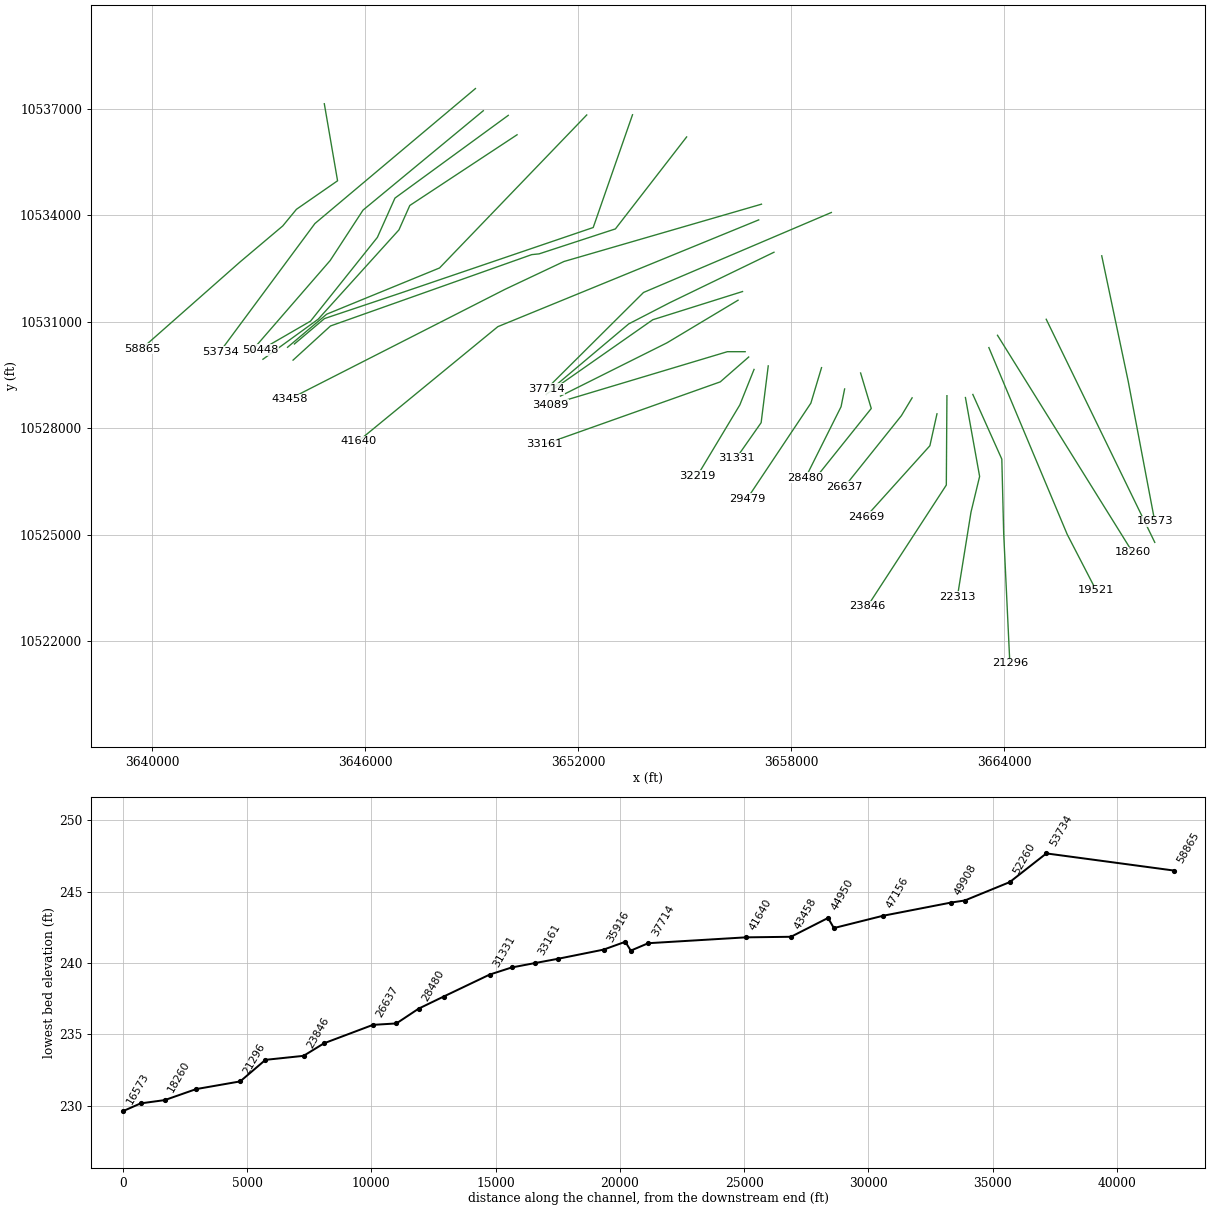
HEC-RAS study BUFFALO CREEK.prj: BUFFALO CREEK Base Level Engineering

--- BUFFALO CREEK.g01 (geometry) --- (continued)

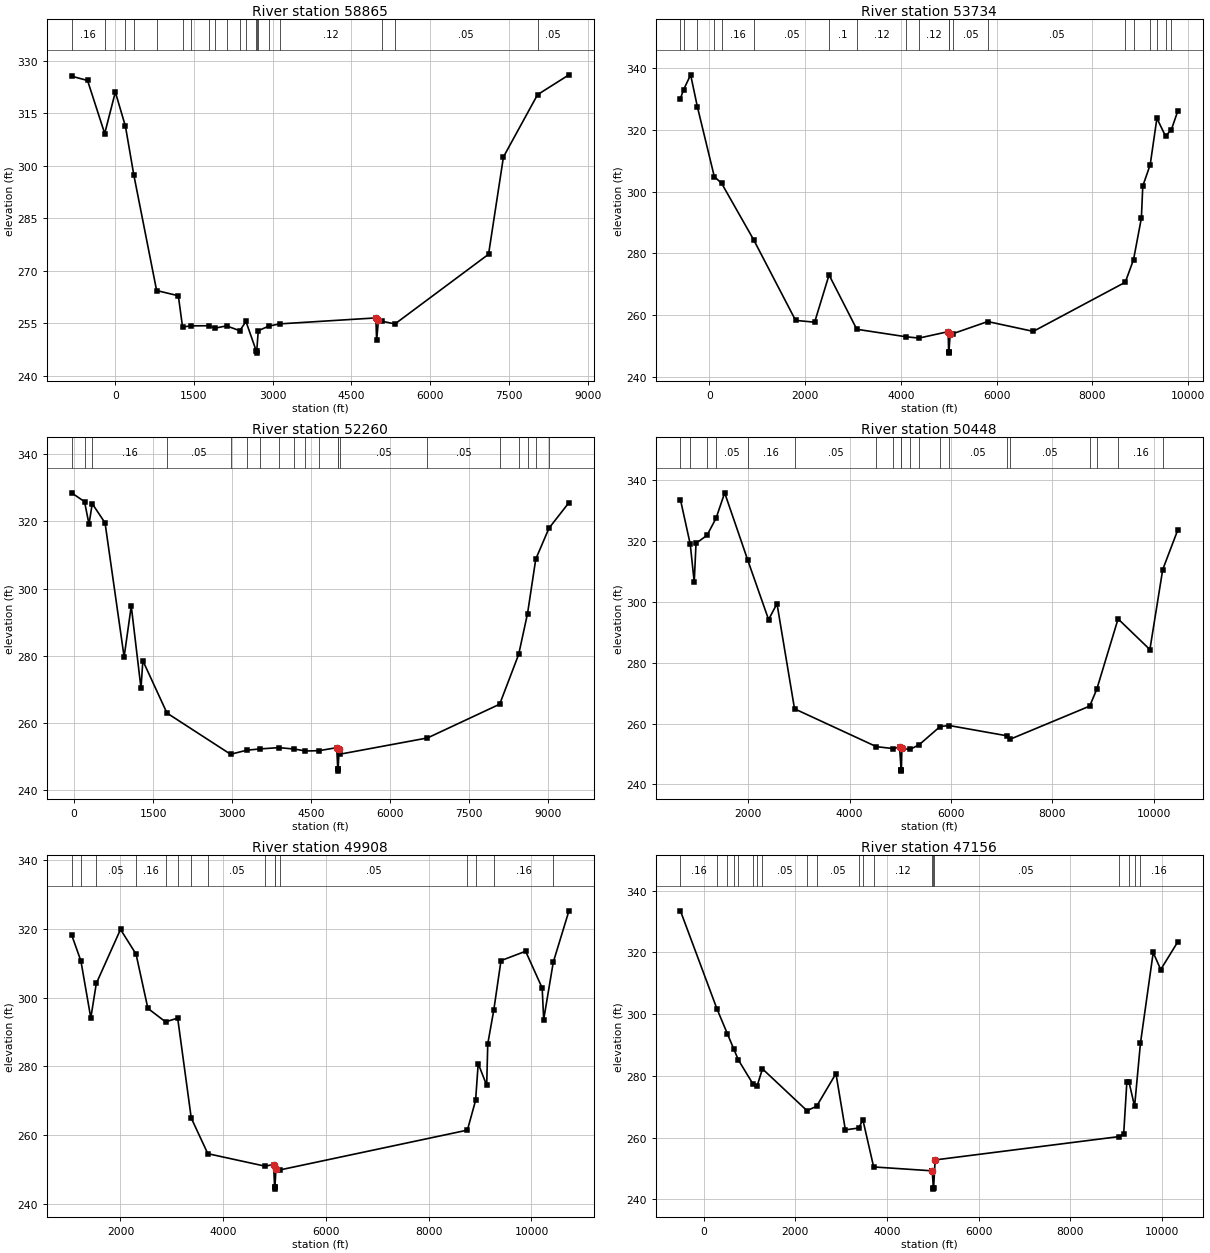
Type RM Length L Ch R = 1 ,58865   ,5131,5131,5131
BEGIN DESCRIPTION:
BUFFALO CREEK 36.0
END DESCRIPTION:
XS GIS Cut Line= 6
      3644852.78     10537144.99      3645226.04     10534974.89
      3644068.06     10534171.07      3643682.64     10533702.32
      3642479.51      10532686.7       3639719.1      10530249.2
#Sta/Elev= 30
  -831.6  325.59  -526.6  324.35  -199.7   309.2     2.7  321.06   195.8  311.22
   354.4   297.4   789.1  264.36  1202.6  262.87  1283.5  253.92  1436.2  254.27
  1781.7   254.3    1905  253.63  2121.7  254.26  2373.8  252.88    2491  255.53
  2689.9  246.98  2692.6  246.48  2695.9  246.98  2725.4  252.88  2926.5  254.21
  3141.4  254.84  4965.7  256.54    4980  250.11  5015.1  255.96    5074  255.62
    5329  254.81  7112.3  274.72  7395.9  302.52  8045.5   320.3  8643.9  325.97
#Mann= 20 ,-1 , 0
  -831.6     .16       0  -199.7     .05       0   195.8     .05       0
   354.4     .16       0   789.1     .05       0  1283.5     .05       0
  1436.2     .12       0  1781.7     .05       0    1905     .08       0
  2121.7     .05       0  2373.8      .1       0    2491     .05       0
  2689.9     .07       0  2695.9     .05       0  2725.4      .1       0
  2926.5     .12       0  3141.4     .12       0    5074     .16       0
    5329     .05       0  8045.5     .05       0
Bank Sta=4965.7,5015.1
XS Rating Curve= 0 ,0
Exp/Cntr=0.3,0.1

Type RM Length L Ch R = 1 ,53734   ,1474,1474,1474
BEGIN DESCRIPTION:
BUFFALO CREEK 35.0
END DESCRIPTION:
XS GIS Cut Line= 3
      3649107.09     10537572.95      3644588.89      10533770.9
      3641919.99     10530164.63
#Sta/Elev= 30
  -607.2  330.11  -542.1  332.92    -394  337.78  -252.4   327.4   101.2  304.79
   251.2  302.71   921.7  284.41  1798.7  258.28  2196.7  257.69  2497.6  272.99
  3077.5   255.4  4113.7  252.96  4377.4  252.55  4985.2  254.63  4996.5  248.18
  4999.2  247.68  5002.5  248.18  5028.1  253.86  5095.7  254.03  5812.2   257.9
    6764  254.72  8686.4  270.63  8858.9  277.97  9022.4  291.39  9051.7  301.77
  9206.7  308.67  9346.9  323.72    9527  317.93  9648.3  319.98  9784.3  326.11
#Mann= 20 ,-1 , 0
  -607.2      .1       0  -542.1     .05       0  -252.4     .16       0
   101.2     .05       0   251.2     .16       0   921.7     .05       0
  2497.6      .1       0  3077.5     .12       0  4113.7     .05       0
  4377.4     .12       0  4996.5     .07       0  5002.5     .12       0
  5095.7     .05       0  5812.2     .05       0  8686.4     .08       0
  8858.9     .16       0  9206.7     .05       0  9346.9     .16       0
    9527     .12       0  9648.3     .05       0
Bank Sta=4985.2,5028.1
XS Rating Curve= 0 ,0
Exp/Cntr=0.3,0.1

Type RM Length L Ch R = 1 ,52260   ,1812,1812,1812
BEGIN DESCRIPTION:
BUFFALO CREEK 34.0
END DESCRIPTION:
XS GIS Cut Line= 4
       3649328.5       10536948.      3645943.06      10534148.5
      3645018.58     10532729.23      3642818.08      10530190.2
#Sta/Elev= 30
   -48.7  328.53   198.1   325.9     283  319.19   344.5   325.3   587.8  319.58
   949.9  279.66  1085.4  294.83  1270.4  270.35  1305.6  278.56  1763.9  262.96
  2971.8  250.69  3280.2   251.9  3534.8  252.29  3887.4  252.66  4182.4  252.25
    4394  251.67  4648.8  251.75  4987.7  252.66  5007.6  246.17  5010.4  245.67
  5013.6  246.17  5033.1  252.13    5044   250.7  6711.3  255.55  8082.3   265.6
  8442.7  280.41  8611.3  292.59  8767.6   308.8  9018.9  318.01    9398  325.62
#Mann= 20 ,-1 , 0
   -48.7     .16       0   198.1     .05       0   344.5     .16       0
  1763.9     .05       0  2971.8     .05       0  3280.2     .12       0
  3534.8      .1       0  3887.4      .1       0  4182.4     .05       0
    4394     .16       0  4648.8     .12       0  5007.6     .07       0
  5013.6     .12       0    5044     .05       0  6711.3     .05       0
  8082.3     .05       0  8442.7     .05       0  8611.3     .08       0
  8767.6     .16       0  9018.9     .05       0
Bank Sta=4987.7,5033.1
XS Rating Curve= 0 ,0
Exp/Cntr=0.3,0.1

Type RM Length L Ch R = 1 ,50448   ,540,540,540
BEGIN DESCRIPTION:
BUFFALO CREEK 33.0
END DESCRIPTION:
XS GIS Cut Line= 5
      3650031.56     10536817.75      3646841.49     10534487.04
       3646346.7     10533380.27       3644465.3     10531021.05
      3643060.29     10530207.55
#Sta/Elev= 30
   666.5  333.64     860  318.97   938.6  306.49   974.1  319.25  1190.5  321.88
  1369.5  327.51  1538.7  335.84  1994.2  313.69  2404.4  294.18  2569.7  299.42
  2915.4  264.86  4527.9  252.43  4852.8   251.8  4986.3  252.25  5016.1  244.88
  5018.9  244.38  5022.1  244.88  5030.9  251.87  5189.5  251.49  5373.4  253.07
  5784.9  259.03  5962.9  259.37  7112.8  255.96  7166.3  254.87  8733.5  265.75
  8872.8  271.29  9292.7  294.41  9919.6  284.33 10172.7  310.62 10470.7  323.69
#Mann= 20 ,-1 , 0
   666.5     .05       0     860     .16       0  1190.5     .05       0
  1369.5     .05       0  1994.2     .16       0  2915.4     .05       0
  4527.9      .1       0  4852.8     .05       0  5016.1     .03       0
  5022.1     .05       0  5189.5     .16       0  5373.4     .05       0
  5784.9      .1       0  5962.9     .05       0  7112.8     .08       0
  7166.3     .05       0  8733.5     .16       0  8872.8     .05       0
  9292.7     .16       0 10172.7     .05       0
Bank Sta=4986.3,5030.9
XS Rating Curve= 0 ,0
Exp/Cntr=0.3,0.1

Type RM Length L Ch R = 1 ,49908   ,2752,2752,2752
BEGIN DESCRIPTION:
BUFFALO CREEK 32.0
END DESCRIPTION:
XS GIS Cut Line= 5
      3650278.97     10536270.88      3647259.03     10534278.71
      3646953.47     10533591.21      3644679.42     10531074.52
      3643125.39     10529947.14
#Sta/Elev= 30
  1047.8  318.35  1230.4  310.66  1422.9  294.07  1529.8  304.12    2001  319.86
  2303.4  312.67  2533.8  296.87  2877.7  292.94  3113.7  294.03  3377.7  264.94
  3700.4  254.56    4813  250.93  4981.4   251.4  5000.3  244.74    5003  244.24
  5006.3  244.74  5025.9  249.99  5097.8  249.81  8752.6  261.42  8912.7  270.08
  8963.1  280.78  9128.5  274.48  9149.4  286.55  9265.8   296.3  9406.8  310.77
  9886.2   313.5 10208.5  302.79 10237.9  293.61 10424.6  310.32 10729.8  325.27
#Mann= 16 ,-1 , 0
  1047.8     .05       0  1230.4     .16       0  1529.8     .05       0
  2303.4     .16       0  2877.7     .05       0  3113.7     .16       0
  3377.7     .12       0  3700.4     .05       0    4813     .16       0
  5000.3     .07       0  5006.3     .16       0  5097.8     .05       0
  8752.6     .16       0  8912.7     .05       0  9265.8     .16       0
 10424.6     .05       0
Bank Sta=4981.4,5025.9
XS Rating Curve= 0 ,0
Exp/Cntr=0.3,0.1

Type RM Length L Ch R = 1 ,47156   ,1973,1973,1973
BEGIN DESCRIPTION:
BUFFALO CREEK 28.0
END DESCRIPTION:
XS GIS Cut Line= 4
      3652239.96     10536828.65       3648096.7     10532518.73
      3644919.62     10531216.64      3643818.23     10530284.37
#Sta/Elev= 30
  -505.1  333.47   293.7  301.65   517.9  293.71   658.7  288.72   759.9  285.14
  1082.9  277.26  1171.3  276.87  1285.3  282.27  2256.5  268.73  2466.6  270.15
  2888.9  280.74    3094  262.51  3390.1  263.12  3475.5  265.83  3711.6   250.5
  4982.3  249.24  4989.3  249.29  5014.6  243.81  5017.3  243.31  5020.6  243.81
  5053.1  252.77  9055.8  260.31  9167.4  261.04  9237.6  278.13  9280.8  278.17
  9406.2  270.15  9533.4  290.51  9812.2  319.97  9975.9  314.44 10349.9  323.44
#Mann= 20 ,-1 , 0
  -505.1     .16       0   293.7     .12       0   517.9     .16       0
   658.7     .05       0   759.9     .16       0  1082.9     .05       0
  1171.3     .16       0  1285.3     .05       0  2256.5      .1       0
  2466.6     .05       0  3390.1     .08       0  3475.5     .05       0
  3711.6     .12       0  4982.3     .05       0  5014.6     .03       0
  5020.6     .05       0  9055.8     .16       0  9280.8     .05       0
  9406.2     .05       0  9533.4     .16       0
Bank Sta=4989.3,5053.1
XS Rating Curve= 0 ,0
Exp/Cntr=0.3,0.1

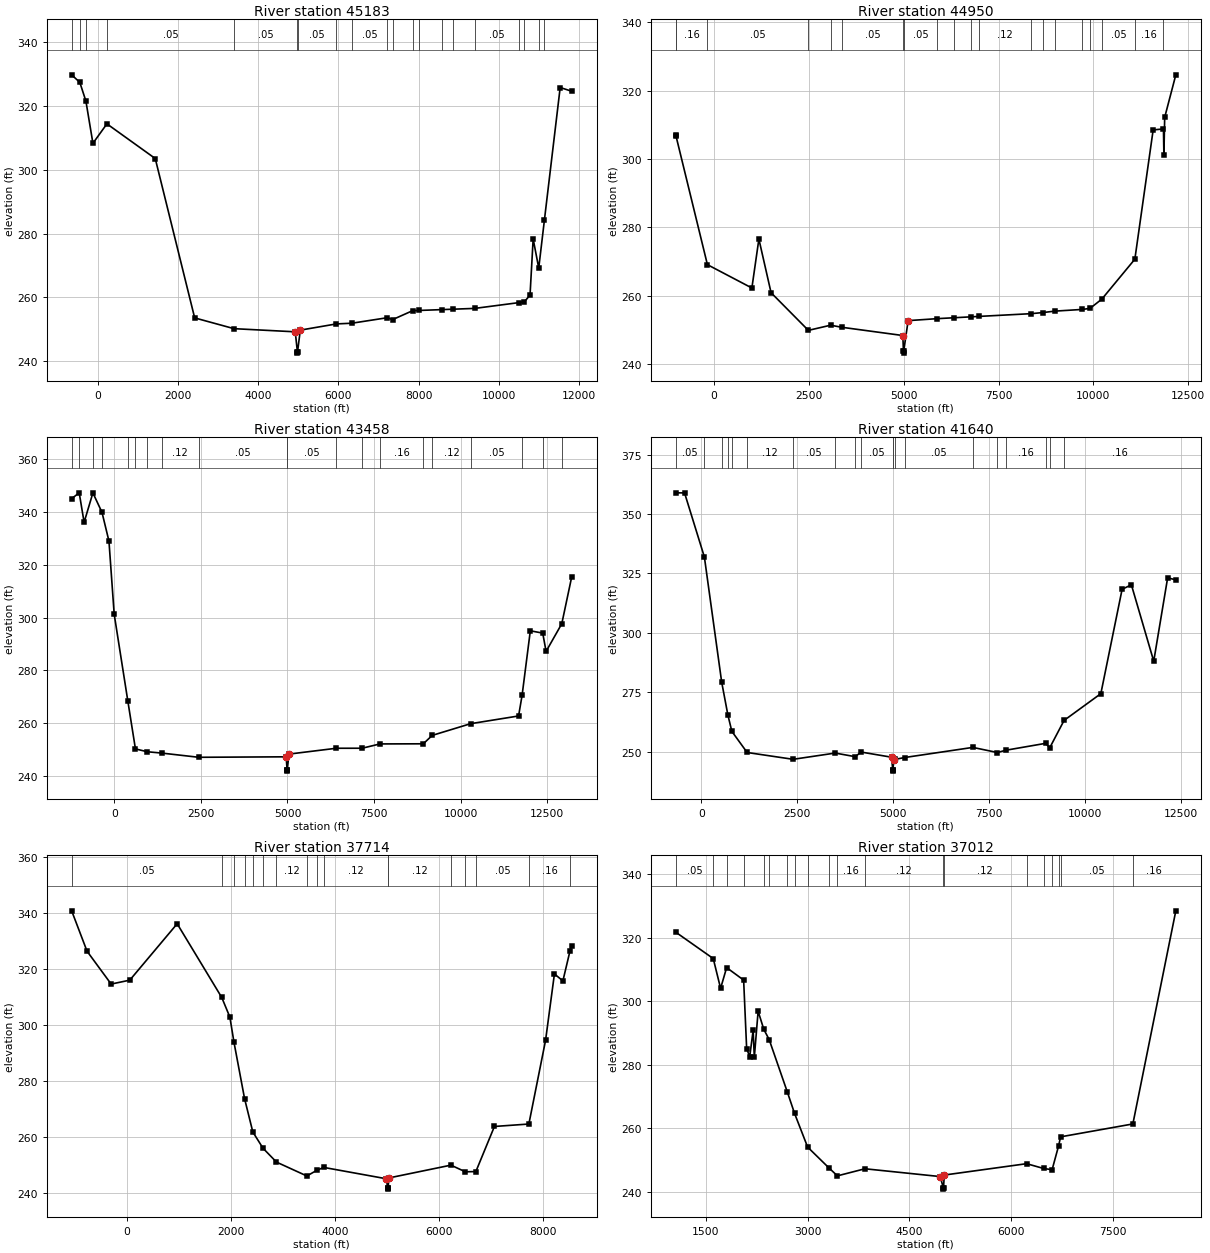
Type RM Length L Ch R = 1 ,45183   ,233,233,233
BEGIN DESCRIPTION:
BUFFALO CREEK 30.0
END DESCRIPTION:
XS GIS Cut Line= 5
      3653528.99     10536835.12      3652422.22     10533658.05
      3646992.54     10531809.09      3644857.12     10531092.95
      3644010.75     10530376.79
#Sta/Elev= 30
  -648.5  329.82  -445.3  327.45    -293  321.54  -118.8  308.32   229.8  314.43
  1434.7  303.54  2417.1  253.51  3397.6  250.13  4924.2  249.14  4976.3  242.95
    4979  242.45  4982.3  242.95  5049.6  249.67  5949.1  251.62    6335  251.84
  7219.9  253.57  7349.6  252.97  7848.5  255.77  8014.9  255.85  8573.1  256.11
  8853.4  256.24  9396.6  256.49 10488.6  258.29   10632  258.53 10775.4  260.66
 10853.4   278.3 10992.4  269.15 11133.8  284.23 11526.8  325.84 11812.7  324.67
#Mann= 20 ,-1 , 0
  -648.5     .16       0  -445.3     .16       0    -293     .16       0
   229.8     .05       0  3397.6     .05       0  4976.3     .03       0
  4982.3     .05       0  5949.1     .12       0    6335     .05       0
  7219.9     .12       0  7349.6     .05       0  7848.5     .12       0
  8014.9     .05       0  8573.1     .05       0  8853.4     .12       0
  9396.6     .05       0 10488.6     .12       0   10632     .16       0
 10992.4     .08       0 11133.8     .16       0
Bank Sta=4924.2,5049.6
XS Rating Curve= 0 ,0
Exp/Cntr=0.3,0.1

Type RM Length L Ch R = 1 ,44950   ,1492,1492,1492
BEGIN DESCRIPTION:
BUFFALO CREEK 29.0
END DESCRIPTION:
XS GIS Cut Line= 6
      3655052.44     10536210.14      3653047.22     10533618.99
      3650898.79     10532915.86      3650691.75      10532894.6
      3645026.39     10530884.61      3643973.16      10529922.4
#Sta/Elev= 30
 -1010.8  306.92   -1005  306.64  -178.1  269.05   994.4  262.22  1179.1  276.53
  1500.5  260.84  2483.9  249.82    3070  251.33  3363.5  250.73  4975.5  248.31
  4991.1  243.66  4993.9  243.16  4997.1  243.66  5114.5  252.67  5883.4  253.25
  6318.7  253.51    6774  253.78  6974.9   253.9    8363  254.71  8672.9  255.04
  8982.9  255.45  9706.1  255.95  9910.7  256.25 10222.6  258.97 11092.8  270.65
 11575.4  308.48 11847.1  308.77 11858.5  301.07 11879.8  312.16   12173   324.6
#Mann= 20 ,-1 , 0
 -1010.8     .05       0   -1005     .16       0  -178.1     .05       0
  2483.9     .12       0    3070     .12       0  3363.5     .05       0
  4991.1     .03       0  4997.1     .05       0  5883.4     .12       0
  6318.7     .05       0    6774     .12       0  6974.9     .12       0
    8363     .08       0  8672.9     .08       0  8982.9     .08       0
  9706.1     .08       0  9910.7     .05       0 10222.6     .05       0
 11092.8     .16       0 11847.1     .05       0
#XS Ineff= 1 ,-1
 -654.55 1190.91  269.04
Permanent Ineff=
       F
Bank Sta=4975.5,5114.5
XS Rating Curve= 0 ,0
Exp/Cntr=0.3,0.1

Type RM Length L Ch R = 1 ,43458   ,1818,1818,1818
BEGIN DESCRIPTION:
BUFFALO CREEK 27.0
END DESCRIPTION:
XS GIS Cut Line= 4
      3657159.19      10534315.6      3651599.31     10532701.02
      3649945.66     10531919.77      3643864.97     10528820.83
#Sta/Elev= 30
 -1233.4  345.05 -1015.3  347.24    -874  336.06  -620.2  347.22  -356.7  339.82
  -156.1  328.94    -5.1  301.27     391  268.23   608.6  250.26   949.8  249.18
  1364.2  248.68  2438.6  247.08  4963.7  247.26    4989  242.34  4991.7  241.84
    4995  242.34    5043  248.29  6411.8   250.5  7156.5  250.51  7672.4  252.14
  8924.5  252.19  9181.1  255.37 10292.6  259.81 11676.7  262.73 11778.5  270.55
 12015.8  294.99 12374.2  294.11 12471.5  287.19 12925.1  297.67 13209.9  315.32
#Mann= 20 ,-1 , 0
 -1233.4     .05       0 -1015.3     .12       0  -620.2     .05       0
  -356.7     .16       0     391     .05       0   608.6     .16       0
   949.8     .05       0  1364.2     .12       0  2438.6     .05       0
    4989     .03       0    4995     .05       0  6411.8     .05       0
  7156.5     .12       0  7672.4     .16       0  8924.5     .16       0
  9181.1     .12       0 10292.6     .05       0 11778.5     .16       0
 12374.2     .16       0 12925.1     .05       0
Bank Sta=4963.7,5043
XS Rating Curve= 0 ,0
Exp/Cntr=0.3,0.1

Type RM Length L Ch R = 1 ,41640   ,3926,3926,3926
BEGIN DESCRIPTION:
BUFFALO CREEK 26.0
END DESCRIPTION:
XS GIS Cut Line= 3
      3657081.07     10533872.89      3649737.33     10530865.08
      3645805.03     10527635.91
#Sta/Elev= 30
  -664.8  358.88  -437.6  358.85    79.1  331.86   529.5  279.24   691.8  265.35
   794.6  258.52  1192.5  249.64    2391  246.77  3487.3   249.4  4009.6  247.87
  4159.2  249.83    4956  247.65  4985.4   242.3  4988.2   241.8  4991.4   242.3
  5010.1  246.49  5046.2  246.74  5297.4  247.53  7071.9  251.78  7713.1  249.62
  7924.3  250.57    8965  253.48  9076.9  251.67  9448.8  263.14 10406.2  274.39
 10960.2  318.29 11201.7   320.2   11784  288.04 12146.3  323.13 12359.3  322.27
#Mann= 20 ,-1 , 0
  -664.8     .05       0    79.1     .16       0   529.5     .12       0
   691.8     .16       0   794.6     .05       0  1192.5     .12       0
    2391     .05       0  3487.3     .05       0  4009.6     .16       0
  4159.2     .05       0  4985.4     .03       0  4991.4     .05       0
  5046.2     .07       0  5297.4     .05       0  7071.9     .12       0
  7713.1     .05       0  7924.3     .16       0    8965     .16       0
  9076.9     .05       0  9448.8     .16       0
Bank Sta=4956,5010.1
XS Rating Curve= 0 ,0
Exp/Cntr=0.3,0.1

Type RM Length L Ch R = 1 ,37714   ,702,702,702
BEGIN DESCRIPTION:
BUFFALO CREEK 25.0
END DESCRIPTION:
XS GIS Cut Line= 3
      3659125.37     10534081.23      3653838.89     10531828.62
      3651104.58     10529107.33
#Sta/Elev= 30
 -1054.9  340.87  -759.7  326.44  -296.4  314.69    61.5  316.09   971.8  336.25
  1828.3  309.89  1984.1  302.88  2062.9  293.89  2266.7  273.71  2425.1   261.8
    2622  255.98  2879.6  251.05  3463.1  246.09  3648.5  248.05    3785  249.16
  4979.8  245.13  5019.2  241.89    5022  241.39  5025.2  241.89  5036.4  245.38
  6230.2  249.96  6508.3  247.58  6709.3  247.67  7065.8  263.79  7727.2  264.66
  8048.6  294.62  8218.3  318.31    8381  315.82  8518.5  326.63  8549.2  328.31
#Mann= 17 ,-1 , 0
 -1054.9     .05       0  1828.3     .12       0  2062.9     .16       0
  2266.7     .12       0  2425.1     .16       0    2622     .05       0
  2879.6     .12       0  3463.1     .16       0  3648.5     .05       0
    3785     .12       0  5019.2     .07       0  5025.2     .12       0
  6230.2     .16       0  6508.3     .12       0  6709.3     .05       0
  7727.2     .16       0  8518.5     .05       0
Bank Sta=4979.8,5036.4
XS Rating Curve= 0 ,0
Exp/Cntr=0.3,0.1

Type RM Length L Ch R = 1 ,37012   ,220,220,220
BEGIN DESCRIPTION:
BUFFALO CREEK 24.0
END DESCRIPTION:
XS GIS Cut Line= 4
      3657510.77     10532961.44      3654581.08     10531542.16
      3653422.22     10530943.21      3651275.27     10529134.56
#Sta/Elev= 30
  1059.7  321.75    1611  313.46  1719.2  304.08  1808.2  310.61  2058.8  306.69
  2103.1  285.14  2148.2  282.55  2198.9  290.89    2216  282.34  2272.2  296.88
  2356.4  291.15  2435.1  287.95  2704.2  271.35  2809.1  264.71  3001.6  254.11
    3320  247.46  3440.4  245.05  3846.1  247.28  4957.3  244.82  4998.6  241.37
  5001.3  240.87  5004.6  241.37  5014.6   245.3  6228.4  248.88  6478.8  247.37
    6604  246.98  6700.6  254.58  6729.1  257.33  7793.9  261.39  8426.8  328.49
#Mann= 20 ,-1 , 0
  1059.7     .05       0    1611     .16       0  1808.2     .05       0
  2058.8     .16       0  2356.4     .12       0  2435.1     .16       0
  2704.2     .12       0  2809.1     .16       0  3001.6     .05       0
    3320     .12       0  3440.4     .16       0  3846.1     .12       0
  4998.6     .07       0  5004.6     .12       0  6228.4     .16       0
  6478.8     .12       0    6604     .16       0  6700.6     .12       0
  6729.1     .05       0  7793.9     .16       0
Bank Sta=4957.3,5014.6
XS Rating Curve= 0 ,0
Exp/Cntr=0.3,0.1

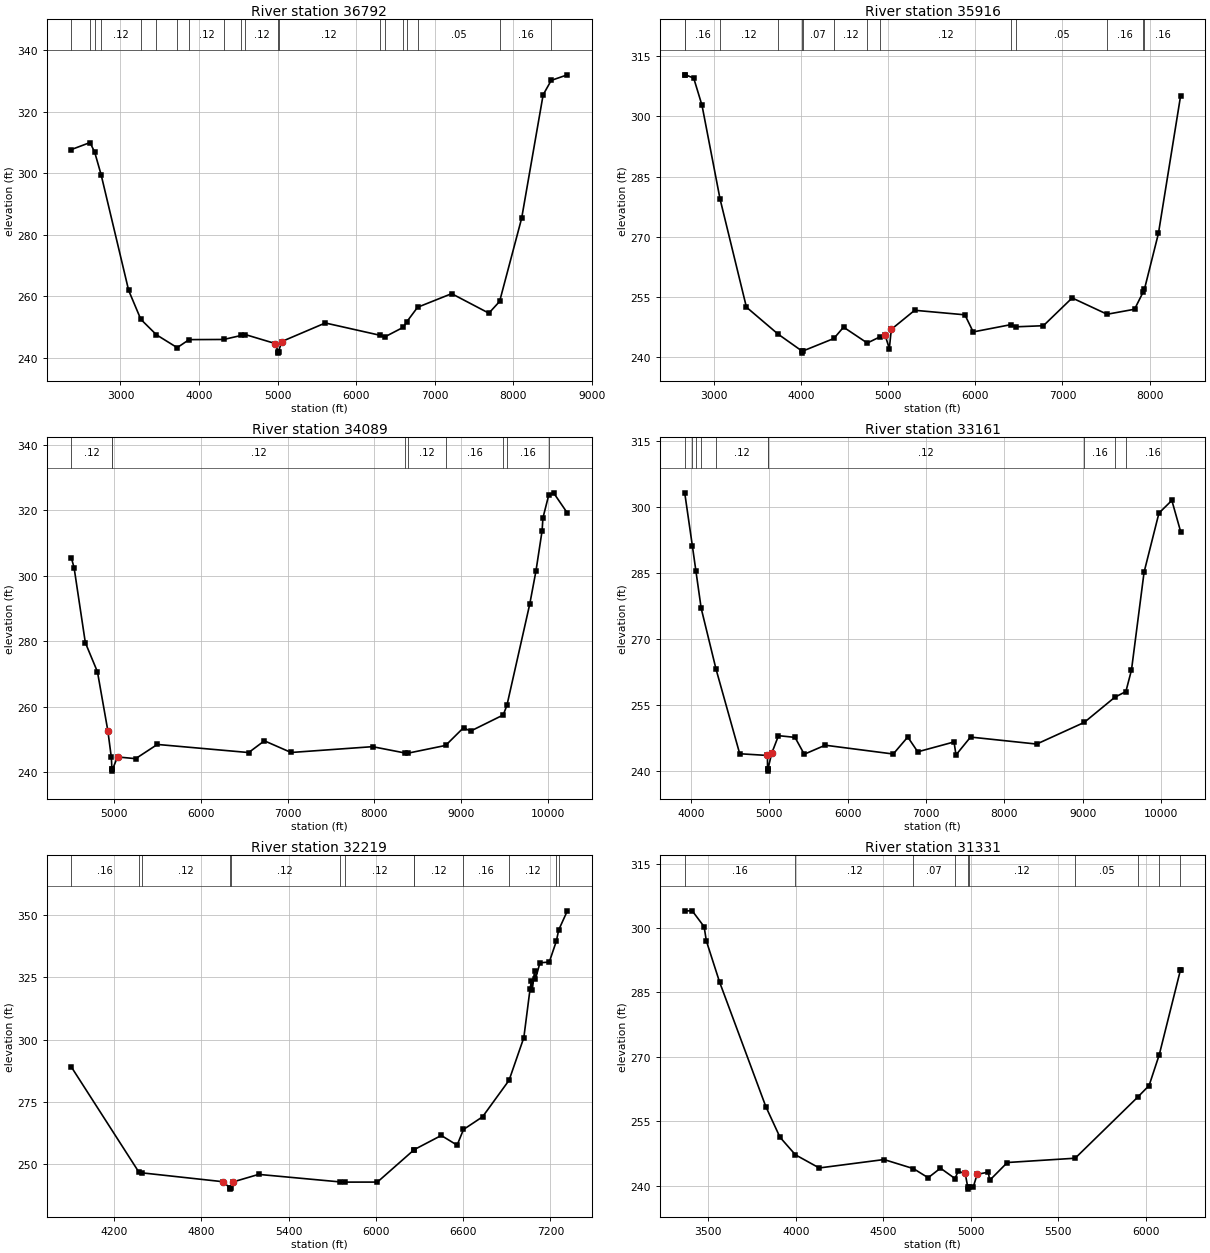
Type RM Length L Ch R = 1 ,36792   ,876,876,876
BEGIN DESCRIPTION:
BUFFALO CREEK 23.0
END DESCRIPTION:
XS GIS Cut Line= 3
      3656625.38     10531854.67      3654099.61     10531060.19
      3651099.64     10528960.21
#Sta/Elev= 30
  2376.2  307.68  2612.2  309.94  2671.3  306.85  2753.2  299.52    3104  261.87
  3258.6  252.48  3457.6  247.45  3721.5  243.27  3873.1  245.88  4313.3  245.93
    4537  247.24  4587.1  247.53  4970.2   244.6  5004.8  241.99  5007.5  241.49
  5010.8  241.99  5052.3  245.26    5606  251.29  6304.6  247.28  6361.1  246.74
  6599.1   249.9  6640.8  251.62  6780.3   256.4  7213.7  260.82  7687.2  254.48
  7823.7  258.29    8104  285.31  8377.7  325.47  8480.3  330.15  8685.9  331.96
#Mann= 20 ,-1 , 0
  2376.2     .05       0  2612.2     .12       0  2671.3     .16       0
  2753.2     .12       0  3258.6     .05       0  3457.6     .12       0
  3721.5     .16       0  3873.1     .12       0  4313.3     .07       0
    4537     .16       0  4587.1     .12       0  5004.8     .07       0
  5010.8     .12       0  6304.6     .16       0  6361.1     .12       0
  6599.1     .05       0  6640.8     .12       0  6780.3     .05       0
  7823.7     .16       0  8480.3     .05       0
Bank Sta=4970.2,5052.3
XS Rating Curve= 0 ,0
Exp/Cntr=0.3,0.1

Type RM Length L Ch R = 1 ,35916   ,1827,1827,1827
BEGIN DESCRIPTION:
BUFFALO CREEK 22.0
END DESCRIPTION:
XS GIS Cut Line= 3
      3656499.63      10531610.2      3654499.61     10530410.19
      3651499.61     10528910.19
#Sta/Elev= 30
  2668.2  310.32  2677.1  310.38  2771.2  309.57  2866.5  302.76  3072.8  279.45
  3375.7  252.41  3738.4  245.69  4014.1  241.44  4016.9  240.94  4020.1  241.44
  4378.4  244.59  4489.4  247.42  4761.5  243.46    4910  245.03  4965.6  245.46
  5014.6  242.06  5036.9  246.87  5305.3  251.63  5881.1   250.5  5976.1  246.23
  6406.8  248.04  6469.9  247.51  6781.1  247.78  7110.9  254.71  7511.9  250.64
  7826.4  251.89  7928.3  256.31  7939.8  256.88  8100.4  270.82  8354.7  305.17
#Mann= 14 ,-1 , 0
  2668.2     .05       0  2677.1     .16       0  3072.8     .12       0
  3738.4     .07       0  4014.1     .07       0  4020.1     .07       0
  4378.4     .12       0  4761.5     .07       0    4910     .12       0
  6406.8     .16       0  6469.9     .05       0  7511.9     .16       0
  7928.3     .05       0  7939.8     .16       0
Bank Sta=4965.6,5036.9
XS Rating Curve= 0 ,0
Exp/Cntr=0.3,0.1

Type RM Length L Ch R = 1 ,34089   ,928,928,928
BEGIN DESCRIPTION:
BUFFALO CREEK 21.0
END DESCRIPTION:
XS GIS Cut Line= 3
      3656699.63     10530160.19      3656199.61     10530160.19
      3651199.59     10528660.18
#Sta/Elev= 30
  4505.7  305.38  4535.7  302.56  4665.7  279.58  4805.7  270.65  4925.7   252.6
  4965.7  244.47  4972.7   240.8  4975.5   240.3  4978.7   240.8    5037  244.64
  5245.8  244.11  5496.4  248.46    6550  245.98    6731  249.57    7039     246
  7978.6  247.78  8353.7  245.84  8392.7  245.82  8821.7  248.16  9027.9  253.57
  9108.8  252.53  9485.9  257.47  9528.5   260.4  9791.7  291.34  9863.1  301.41
  9934.4  313.79    9944  317.72 10011.4  324.76 10066.7   325.4 10225.9  319.23
#Mann= 9 ,-1 , 0
  4505.7     .12       0  4972.7     .07       0  4978.7     .12       0
  8353.7     .05       0  8392.7     .12       0  8821.7     .16       0
  9485.9     .05       0  9528.5     .16       0 10011.4     .05       0
Bank Sta=4925.7,5037
XS Rating Curve= 0 ,0
Exp/Cntr=0.3,0.1

Type RM Length L Ch R = 1 ,33161   ,942,942,942
BEGIN DESCRIPTION:
BUFFALO CREEK 20.0
END DESCRIPTION:
XS GIS Cut Line= 3
      3656799.59     10530010.17      3655999.61     10529310.19
      3651038.86     10527547.79
#Sta/Elev= 30
  3921.8  303.25  4019.4  291.19  4065.3   285.4  4131.9  277.01  4322.2  263.12
  4623.6  243.95  4977.7  243.56  4978.5   240.5  4981.2     240  4984.5   240.5
  5031.1  244.02  5118.3  248.06    5329  247.67  5447.1  243.84  5714.2  245.89
  6582.4  243.89  6767.7  247.75    6895  244.39  7358.1  246.63  7383.2  243.68
  7568.8  247.74  8412.6  246.15  9019.3  251.07    9411  256.81  9550.8  258.08
  9622.4  262.99    9783  285.21  9972.6  298.64 10137.3  301.53 10249.3  294.45
#Mann= 10 ,-1 , 0
  3921.8     .12       0  4019.4     .16       0  4065.3     .12       0
  4131.9     .16       0  4322.2     .12       0  4978.5     .07       0
  4984.5     .12       0  9019.3     .16       0    9411     .05       0
  9550.8     .16       0
Bank Sta=4977.7,5031.1
XS Rating Curve= 0 ,0
Exp/Cntr=0.3,0.1

Type RM Length L Ch R = 1 ,32219   ,888,888,888
BEGIN DESCRIPTION:
BUFFALO CREEK 19.0
END DESCRIPTION:
XS GIS Cut Line= 3
      3656949.61      10529660.2      3656549.61     10528660.19
      3655349.62     10526660.21
#Sta/Elev= 30
  3906.6  288.86  4367.5  246.78  4389.7  246.26  4951.3  242.66  4994.3  240.19
    4997  239.69  5000.3  240.19  5018.6  242.61  5193.6  245.63  5751.2  242.61
  5788.7  242.52  6009.9  242.53  6261.6  255.53  6263.5  255.62  6449.2  261.32
    6558  257.41  6601.7  263.73  6732.9  268.84  6915.2  283.57  7016.7  300.76
  7059.5  320.38  7069.2  323.64    7075   320.1  7090.6  327.78  7096.4  324.33
  7127.5  330.92  7191.6  331.22  7239.9  339.58  7256.5  344.17    7316  351.87
#Mann= 13 ,-1 , 0
  3906.6     .16       0  4367.5     .07       0  4389.7     .12       0
  4994.3     .07       0  5000.3     .12       0  5751.2     .07       0
  5788.7     .12       0  6261.6     .16       0  6263.5     .12       0
  6601.7     .16       0  6915.2     .12       0  7239.9     .16       0
  7256.5     .12       0
Bank Sta=4951.3,5018.6
XS Rating Curve= 0 ,0
Exp/Cntr=0.3,0.1

Type RM Length L Ch R = 1 ,31331   ,1852,1852,1852
BEGIN DESCRIPTION:
BUFFALO CREEK 18.0
END DESCRIPTION:
XS GIS Cut Line= 3
      3657349.61     10529760.23      3657149.61     10528160.19
      3656449.58     10527160.15
#Sta/Elev= 30
  3365.3  303.99  3408.2  304.01  3476.2  300.31  3488.8  297.02  3564.4  287.43
  3828.9  258.39  3909.5  251.28  3997.6  247.19  4133.8  244.12  4504.1  246.08
  4672.3  243.96  4756.1  241.84  4826.6  244.07  4909.5  241.65  4927.4  243.33
  4967.7  242.85  4982.2  239.69    4985  239.19  4988.2  239.69  5014.4  239.74
  5035.8  242.63  5099.9  243.15  5107.3  241.23  5208.4  245.39    5596  246.39
  5953.4  260.62  6018.4  263.32  6076.5   270.5  6197.1  290.16  6198.5  290.16
#Mann= 10 ,-1 , 0
  3365.3     .16       0  3997.6     .12       0  4672.3     .07       0
  4909.5     .12       0  4982.2     .07       0  4988.2     .12       0
    5596     .05       0  5953.4     .16       0  6076.5      .1       0
  6197.1     .12       0
Bank Sta=4967.7,5035.8
XS Rating Curve= 0 ,0
Exp/Cntr=0.3,0.1

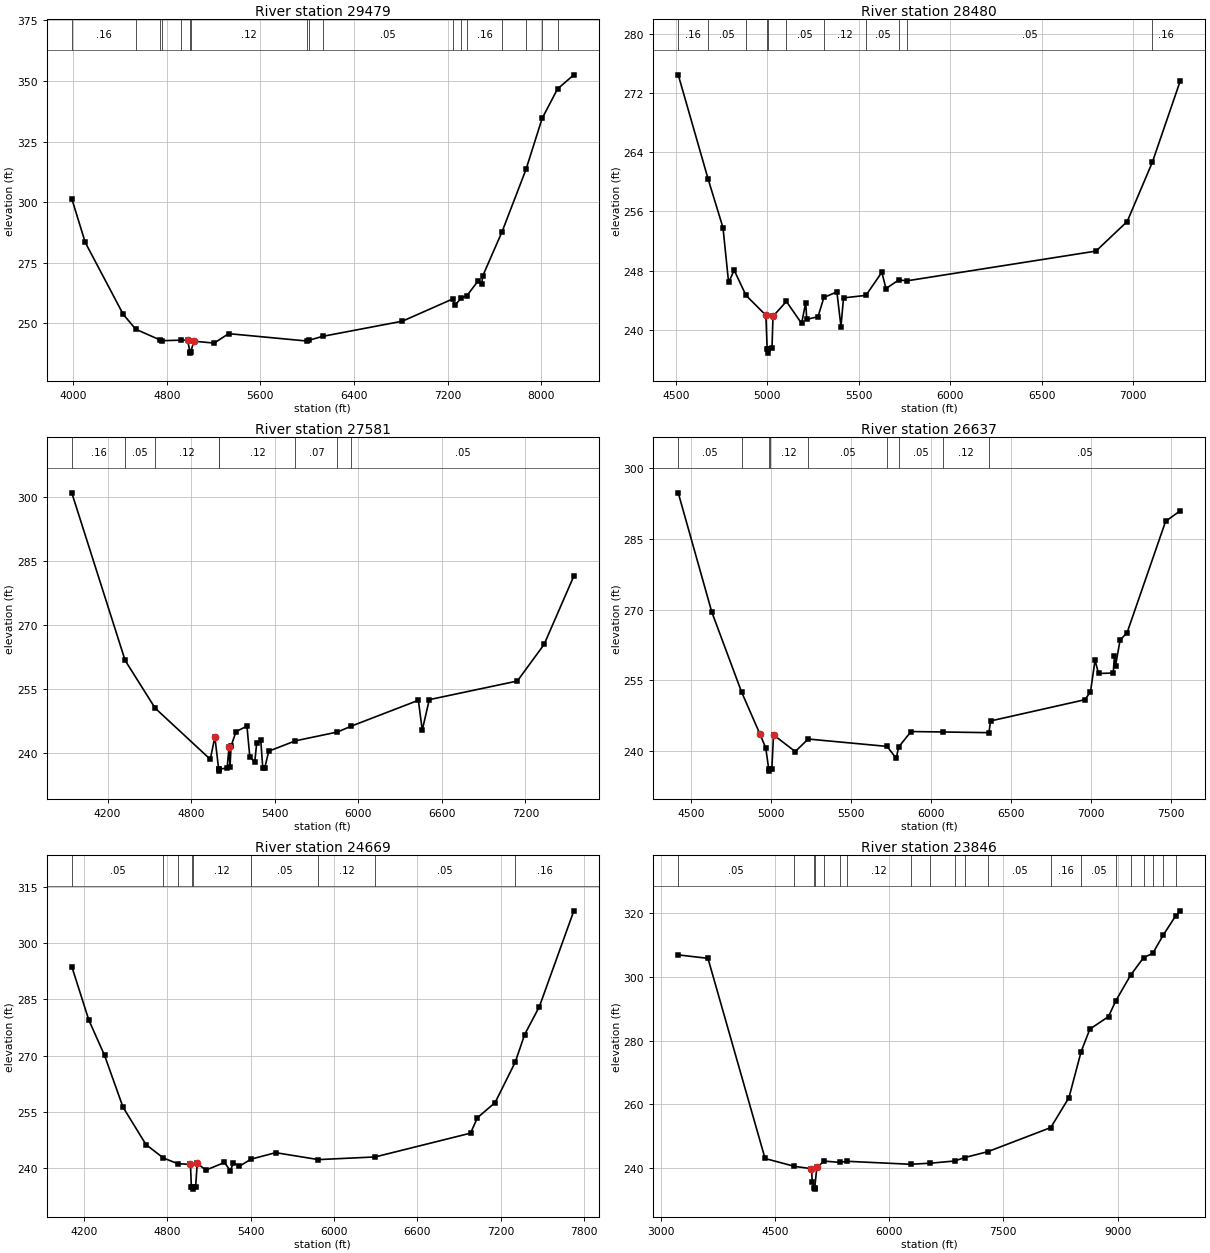
Type RM Length L Ch R = 1 ,29479   ,999,999,999
BEGIN DESCRIPTION:
BUFFALO CREEK 17.0
END DESCRIPTION:
XS GIS Cut Line= 3
      3658849.61     10529710.19      3658549.61     10528710.19
      3656749.62     10526010.21
#Sta/Elev= 30
  3988.6  301.42  4103.4  283.38    4428  253.67  4534.8  247.53  4744.6  243.04
  4761.5  242.78  4917.9     243  4977.8  243.03  4998.3  238.15  5001.1  237.65
  5004.3  238.15  5032.6  242.56  5205.4   241.8  5328.6  245.69  5998.1  242.64
  6016.3  242.98  6132.3  244.58  6812.9  250.83  7242.6     260  7260.6  257.32
  7316.4  260.45  7363.7  261.34  7461.9  267.59  7491.9  266.16  7497.9  269.36
  7664.5  287.78  7868.9  313.49  8006.7  334.54  8138.3   346.7  8277.6  352.53
#Mann= 17 ,-1 , 0
  3988.6     .16       0  4534.8     .05       0  4744.6     .16       0
  4761.5     .05       0  4917.9     .12       0  4998.3     .07       0
  5004.3     .12       0  5998.1     .05       0  6016.3     .12       0
  6132.3     .05       0  7242.6     .16       0  7316.4     .05       0
  7363.7     .16       0  7664.5     .05       0  7868.9     .16       0
  8006.7     .05       0  8138.3     .16       0
Bank Sta=4977.8,5032.6
XS Rating Curve= 0 ,0
Exp/Cntr=0.3,0.1

Type RM Length L Ch R = 1 ,28480   ,899,899,899
BEGIN DESCRIPTION:
BUFFALO CREEK 16.0
END DESCRIPTION:
XS GIS Cut Line= 3
      3659499.61      10529110.2      3659399.61     10528610.19
       3658399.6     10526610.18
#Sta/Elev= 30
  4513.2   274.5    4676  260.44    4758   253.8  4788.6  246.39  4819.2  248.03
  4883.9  244.63  4992.5  241.94  4999.7  237.31  5002.5  236.81  5005.7  237.31
  5025.9  237.46  5031.5  241.79  5104.7  243.81    5188  240.83  5210.4  243.66
    5216  241.39  5277.5  241.73  5309.8  244.35  5380.9   245.1  5403.2  240.41
  5417.2  244.29  5539.8  244.63  5626.9  247.77  5649.2  245.55  5720.1  246.73
  5763.5   246.6    6798  250.63  6968.5  254.63  7105.9  262.64  7259.2   273.7
#Mann= 11 ,-1 , 0
  4513.2     .16       0    4676     .05       0  4883.9     .12       0
  4999.7     .07       0  5005.7     .12       0  5104.7     .05       0
  5309.8     .12       0  5539.8     .05       0  5720.1     .08       0
  5763.5     .05       0  7105.9     .16       0
Bank Sta=4992.5,5031.5
XS Rating Curve= 0 ,0
Exp/Cntr=0.3,0.1

Type RM Length L Ch R = 1 ,27581   ,944,944,944
BEGIN DESCRIPTION:
BUFFALO CREEK 15.0
END DESCRIPTION:
XS GIS Cut Line= 3
       3659949.6     10529560.21      3660249.61     10528560.19
      3658649.61     10526560.19
#Sta/Elev= 30
  3942.9  300.91  4326.2  261.67  4541.6  250.51  4937.4  238.54  4970.4  243.77
  4997.6  236.27  5000.3  235.77  5003.6  236.27  5058.2  236.47  5072.6  241.46
    5079   236.7    5087  241.65  5122.2     245  5200.7  246.32  5221.5  239.09
  5256.7  237.85  5271.1  242.45  5299.9  243.03  5314.3   236.6  5328.7  236.54
  5357.5  240.44  5548.4  242.86  5850.2  244.92  5950.7  246.31  6431.7  252.35
  6459.7  245.36  6510.1   252.5  7142.4  256.86  7334.5  265.42  7548.2  281.43
#Mann= 8 ,-1 , 0
  3942.9     .16       0  4326.2     .05       0  4541.6     .12       0
  4997.6     .07       0  5003.6     .12       0  5548.4     .07       0
  5850.2     .12       0  5950.7     .05       0
Bank Sta=4970.4,5072.6
XS Rating Curve= 0 ,0
Exp/Cntr=0.3,0.1

Type RM Length L Ch R = 1 ,26637   ,1968,1968,1968
BEGIN DESCRIPTION:
BUFFALO CREEK 14.0
END DESCRIPTION:
XS GIS Cut Line= 3
      3661399.62      10528860.2      3661099.61     10528360.19
      3659499.58     10526360.16
#Sta/Elev= 30
    4417   294.8  4626.9   269.5  4813.3  252.51  4928.2  243.58  4965.1  240.59
  4983.5  236.17  4986.3  235.67  4989.5  236.17  5003.3  236.18  5013.7  243.37
  5149.8  239.83  5230.8  242.49    5725  240.92  5782.1  238.39  5797.3  240.78
  5874.9  244.08  6073.6  243.99  6363.3  243.84  6372.8  246.33  6963.5  250.84
  6998.7  252.49  7027.5  259.25  7049.1  256.42  7141.2  256.51  7149.2  260.22
  7155.6  258.04  7184.4  263.55  7227.6  265.04  7469.3  288.74  7561.4     291
#Mann= 9 ,-1 , 0
    4417     .05       0  4813.3     .12       0  4983.5     .07       0
  4989.5     .12       0  5230.8     .05       0    5725     .07       0
  5797.3     .05       0  6073.6     .12       0  6363.3     .05       0
Bank Sta=4928.2,5013.7
XS Rating Curve= 0 ,0
Exp/Cntr=0.3,0.1

Type RM Length L Ch R = 1 ,24669   ,823,823,823
BEGIN DESCRIPTION:
BUFFALO CREEK 13.0
END DESCRIPTION:
XS GIS Cut Line= 3
      3662099.61     10528410.18      3661899.61     10527510.19
      3660099.59     10525510.17
#Sta/Elev= 30
  4112.9   293.8  4235.8  279.48  4348.5  270.11  4481.7  256.25  4646.9  246.27
  4772.8  242.67  4874.2  241.19    4967  240.97  4973.4  235.06  4980.6  234.88
  4983.4  234.38  4986.6  234.88  5004.1  234.96  5015.6  241.29  5077.1  239.44
  5211.6  241.49  5254.2  239.29  5275.9  241.45  5317.8  240.46  5403.5  242.39
  5580.1  244.11    5888  242.26  6295.5  242.97  6982.3  249.32  7031.6  253.43
  7159.4   257.5    7304  268.29  7371.7  275.64  7477.8  283.12  7725.6  308.66
#Mann= 9 ,-1 , 0
  4112.9     .05       0  4772.8     .07       0  4874.2     .12       0
  4980.6     .07       0  4986.6     .12       0  5403.5     .05       0
    5888     .12       0  6295.5     .05       0    7304     .16       0
Bank Sta=4967,5015.6
XS Rating Curve= 0 ,0
Exp/Cntr=0.3,0.1

Type RM Length L Ch R = 1 ,23846   ,1533,1533,1533
BEGIN DESCRIPTION:
BUFFALO CREEK 12.0
END DESCRIPTION:
XS GIS Cut Line= 3
      3662379.72     10528920.53      3662362.36     10526403.19
      3660140.83     10522984.13
#Sta/Elev= 30
  3229.2  306.82  3619.6  305.75  4369.6  243.09  4754.8  240.63  4979.6   239.9
  4989.6  235.75  5016.6     234  5019.3   233.5  5022.6     234  5049.6  240.29
  5146.5  242.27    5349  241.88  5447.1  242.21  6281.4  241.28  6541.8  241.62
  6858.5   242.3  6989.7  243.37  7297.5  245.24  8122.2  252.77  8361.5  262.16
  8521.2  276.55  8636.1   283.6  8880.8  287.51  8975.9  292.42  9169.8  300.43
  9341.9  305.98  9461.4  307.29    9598  312.96  9763.5  319.07    9824  320.62
#Mann= 20 ,-1 , 0
  3229.2     .05       0  4754.8     .12       0  5016.6     .07       0
  5022.6     .12       0  5146.5     .05       0    5349     .07       0
  5447.1     .12       0  6281.4     .05       0  6541.8     .05       0
  6858.5     .05       0  6989.7     .12       0  7297.5     .05       0
  8122.2     .16       0  8521.2     .05       0  8975.9     .16       0
  9169.8     .05       0  9341.9     .16       0  9461.4     .12       0
    9598     .16       0  9763.5     .05       0
Bank Sta=4979.6,5049.6
XS Rating Curve= 0 ,0
Exp/Cntr=0.3,0.1

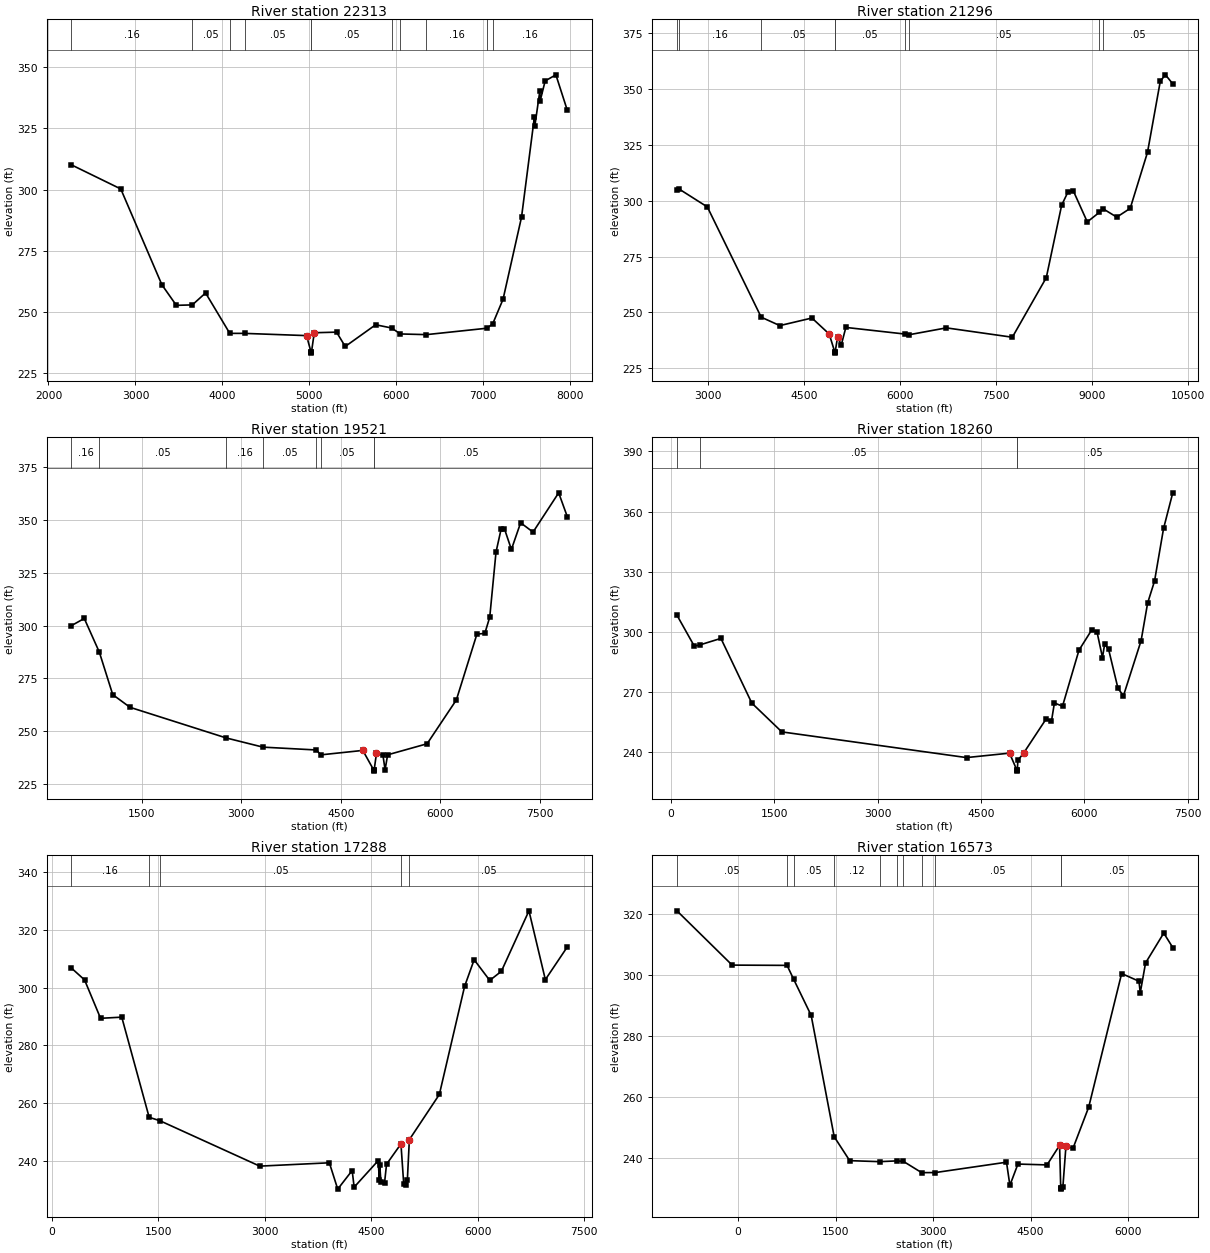
Type RM Length L Ch R = 1 ,22313   ,1017,1017,1017
BEGIN DESCRIPTION:
BUFFALO CREEK 11.0
END DESCRIPTION:
XS GIS Cut Line= 4
      3662900.56     10528868.44      3663299.86     10526646.24
       3663056.8      10525639.3      3662674.85     10523260.82
#Sta/Elev= 30
  2264.3  310.08  2831.5  300.25  3304.5  261.12  3470.6  252.73  3654.5  252.91
  3806.9  257.79  4085.3  241.29  4255.8  241.28  4968.1  240.37  5019.1  233.72
  5021.8  233.22  5025.1  233.72    5057  241.54  5313.4  241.79    5413  235.93
  5762.8   244.8  5946.6  243.48  6046.6  241.05  6346.5  240.77  7043.5  243.39
  7108.8  245.14  7228.2  255.21  7440.9  288.77  7588.9  329.65  7593.9  325.98
  7650.8  340.11  7655.9  336.32  7712.7  344.36  7835.9  346.84  7966.9  332.39
#Mann= 11 ,-1 , 0
  2264.3     .16       0  3654.5     .05       0  4085.3     .12       0
  4255.8     .05       0  5019.1     .03       0  5025.1     .05       0
  5946.6     .07       0  6046.6     .05       0  6346.5     .16       0
  7043.5     .05       0  7108.8     .16       0
Bank Sta=4968.1,5057
XS Rating Curve= 0 ,0
Exp/Cntr=0.3,0.1

Type RM Length L Ch R = 1 ,21296   ,1775,1775,1775
BEGIN DESCRIPTION:
BUFFALO CREEK 10.0
END DESCRIPTION:
XS GIS Cut Line= 4
      3663108.89     10528955.26      3663924.86     10527132.36
      3663976.94     10525049.02      3664150.55     10521385.81
#Sta/Elev= 30
  2510.3  304.76  2538.9  305.35  2985.4  297.23    3827  247.82  4118.1  244.05
  4619.7  247.45  4889.8  240.27  4976.8  232.21  4979.6  231.71  4982.8  232.21
  5019.8  238.73  5079.8  235.55  5149.9  243.23  6066.7  240.28  6137.2  239.95
  6720.5  243.03  7751.6  238.83  8282.2  265.53  8522.5  298.03  8622.6  304.03
  8702.7  304.56  8922.9  290.52  9110.8  294.78  9171.3  296.38  9383.4  292.66
  9593.7  296.59    9864   321.7 10064.2  353.62 10144.3  356.44 10258.8  352.41
#Mann= 9 ,-1 , 0
  2510.3     .05       0  2538.9     .16       0    3827     .05       0
  4976.8     .03       0  4982.8     .05       0  6066.7     .08       0
  6137.2     .05       0  9110.8     .08       0  9171.3     .05       0
Bank Sta=4889.8,5019.8
XS Rating Curve= 0 ,0
Exp/Cntr=0.3,0.1

Type RM Length L Ch R = 1 ,19521   ,1261,1261,1261
BEGIN DESCRIPTION:
BUFFALO CREEK 9.0
END DESCRIPTION:
XS GIS Cut Line= 3
      3663560.26     10530274.74      3665765.13      10525014.3
      3666580.89     10523434.86
#Sta/Elev= 30
   437.5  299.98     631  303.36   858.4  287.41  1060.5  267.34  1320.7  261.35
  2774.7  246.84    3328  242.51    4134  241.17  4198.9  238.86  4833.8  240.96
  4998.8  231.67  5001.5  231.17  5004.8  231.67  5039.8  239.56  5137.4  238.73
  5169.9  231.82  5208.3  238.88    5804  244.11  6245.4  264.84  6555.5  295.96
  6674.9   296.3  6749.2  304.01  6843.8  334.76  6920.8  345.61  6970.7  345.78
  7075.9  335.99  7215.2  348.61  7402.5   344.2  7789.2  362.77    7919  351.53
#Mann= 8 ,-1 , 0
   437.5     .16       0   858.4     .05       0  2774.7     .16       0
    3328     .05       0    4134     .08       0  4198.9     .05       0
  4998.8     .03       0  5004.8     .05       0
Bank Sta=4833.8,5039.8
XS Rating Curve= 0 ,0
Exp/Cntr=0.3,0.1

Type RM Length L Ch R = 1 ,18260   ,972,972,972
BEGIN DESCRIPTION:
BUFFALO CREEK 8.0
END DESCRIPTION:
XS GIS Cut Line= 2
      3663803.32     10530621.96      3667605.02     10524511.46
#Sta/Elev= 30
    86.3  308.25   338.2  292.81   420.9  293.43   724.4  296.67  1172.8  264.37
  1608.4  249.99  4289.1  237.16  4913.6  239.38  5020.1   230.9  5022.9   230.4
  5026.1   230.9  5035.1  235.77  5123.7  239.69  5443.6  256.38  5522.7  255.45
  5565.1  264.42  5682.7  262.82  5921.6  290.78  6104.6  300.78  6183.7  299.83
  6262.8  287.12  6293.5  293.73  6351.3  291.24  6488.2  271.66  6567.3  268.04
  6823.5  295.56  6917.9  314.29  7018.3  325.27  7149.3  351.54  7282.9  369.34
#Mann= 4 ,-1 , 0
    86.3     .16       0   420.9     .05       0  5020.1     .03       0
  5026.1     .05       0
Bank Sta=4913.6,5123.7
XS Rating Curve= 0 ,0
Exp/Cntr=0.3,0.1

Type RM Length L Ch R = 1 ,17288   ,715,715,715
BEGIN DESCRIPTION:
BUFFALO CREEK 7.0
END DESCRIPTION:
XS GIS Cut Line= 2
      3665174.87     10531073.31       3668230.4     10524788.63
#Sta/Elev= 30
   273.4   306.8   458.1   302.7   683.6  289.39   982.4  289.79  1368.5  255.07
  1519.5  253.89  2927.3  238.14  3908.2   239.3  4026.3  230.17  4229.6  236.62
  4257.7  230.85    4596  240.03    4613  233.49  4618.6  238.46  4635.5   232.6
  4686.2  232.38  4714.3   238.8  4917.3  245.84  4956.9  231.78  4991.4  231.59
  5007.5  233.24  5035.9  247.33  5458.4  262.98  5814.3  300.45  5948.9   309.7
  6168.9  302.53  6332.4  305.68  6721.4  326.65  6952.5   302.8  7261.5  314.12
#Mann= 5 ,-1 , 0
   273.4     .16       0  1368.5     .12       0  1519.5     .05       0
  4917.3     .03       0  5035.9     .05       0
Bank Sta=4917.3,5035.9
XS Rating Curve= 0 ,0
Exp/Cntr=0.3,0.1

Type RM Length L Ch R = 1 ,16573   ,1051,1051,1051
BEGIN DESCRIPTION:
BUFFALO CREEK 6.0
END DESCRIPTION:
XS GIS Cut Line= 3
      3666737.35     10532861.53      3667483.88     10529319.86
      3668230.42     10525378.84
#Sta/Elev= 30
  -941.8  321.09   -92.2  303.25   753.1  303.16   852.6  298.67    1124  286.71
  1478.4  246.83  1716.7  238.98  2176.5  238.65  2443.7   238.9  2543.2  238.74
  2824.1  235.04  3033.3  235.06    4130  238.47  4182.3  230.87  4305.8  237.86
  4753.6  237.58    4947     244  4964.4  230.12  4967.1  229.62  4970.4  230.12
  4997.9   230.4  5044.7  243.69  5154.4   243.1  5394.8  256.55    5902  300.48
  6168.4  297.95  6188.7  294.16  6270.1  303.95  6550.1  313.77  6688.8  309.03
#Mann= 11 ,-1 , 0
  -941.8     .05       0   753.1     .16       0   852.6     .05       0
  1478.4     .12       0  2176.5     .07       0  2443.7     .12       0
  2543.2     .05       0  2824.1     .07       0  3033.3     .05       0
  4964.4     .03       0  4970.4     .05       0
Bank Sta=4947,5044.7
XS Rating Curve= 0 ,0
Exp/Cntr=0.3,0.1