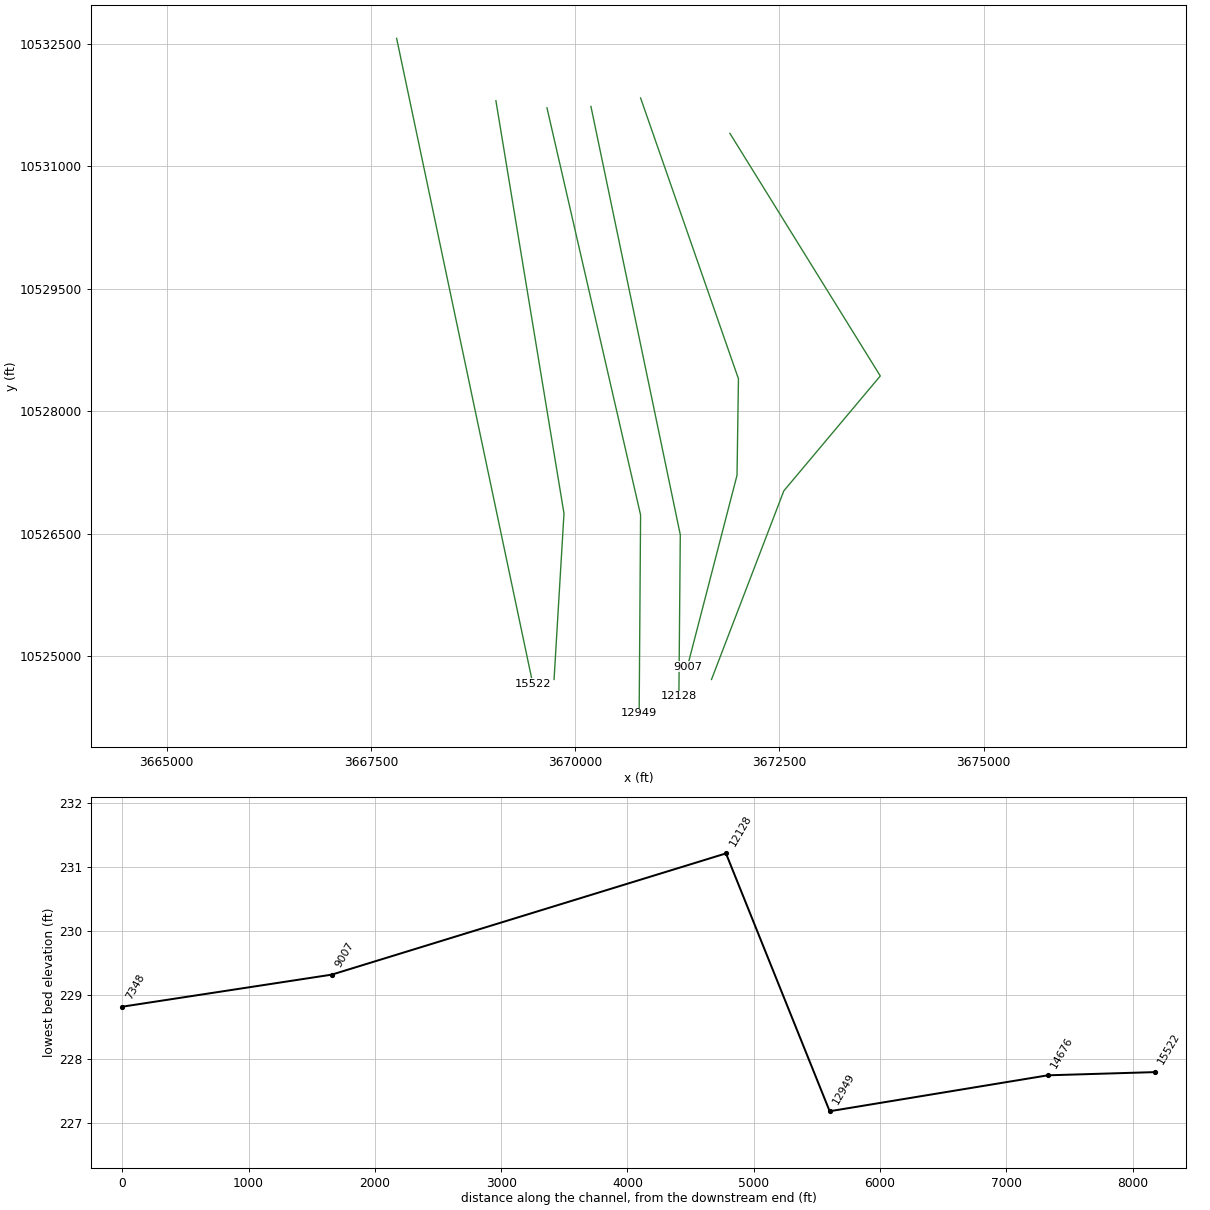
HEC-RAS study BUFFALO CREEK.prj: BUFFALO CREEK Base Level Engineering

--- BUFFALO CREEK.g01 (geometry) --- (continued)

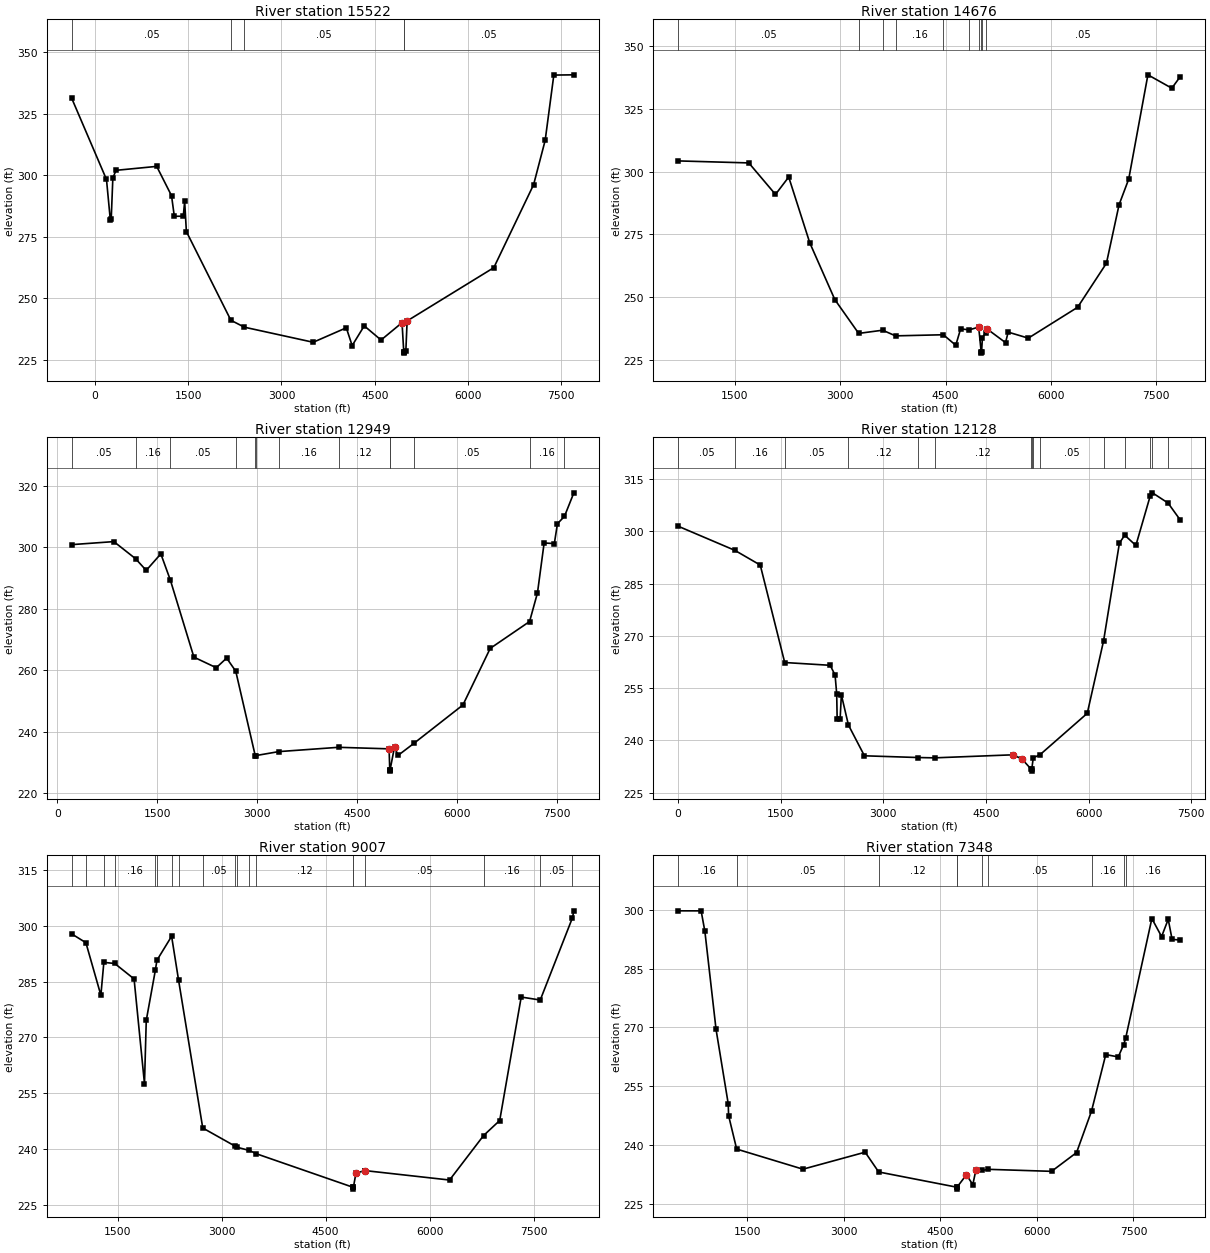
Type RM Length L Ch R = 1 ,15522   ,846,846,846
BEGIN DESCRIPTION:
BUFFALO CREEK 5.0
END DESCRIPTION:
XS GIS Cut Line= 2
      3667813.74     10532566.42      3669480.42     10524667.03
#Sta/Elev= 30
  -371.3  331.21     187  298.29   248.3  281.95   263.1  282.28   289.2   298.9
   340.3  302.01   994.4  303.61    1233   291.7  1277.6  283.34  1421.8   283.4
    1444  289.39  1471.6  277.15  2187.1  241.14  2404.6  238.33  3510.8  232.21
    4043  238.08  4137.4  230.86  4331.4  238.87  4602.1  233.12  4939.3  240.16
    4967   228.3  4969.7   227.8    4973   228.3  5000.7  228.74  5021.1  240.87
  6415.3   262.5  7054.9  296.19  7240.9  314.17    7380  340.68    7702  340.78
#Mann= 5 ,-1 , 0
  -371.3     .05       0  2187.1     .07       0  2404.6     .05       0
    4967     .03       0    4973     .05       0
Bank Sta=4939.3,5021.1
XS Rating Curve= 0 ,0
Exp/Cntr=0.3,0.1

Type RM Length L Ch R = 1 ,14676   ,1727,1727,1727
BEGIN DESCRIPTION:
BUFFALO CREEK 4.0
END DESCRIPTION:
XS GIS Cut Line= 3
      3669029.03     10531802.48      3669862.36     10526750.41
      3669740.83     10524719.18
#Sta/Elev= 30
     691  304.23  1696.7  303.43  2076.9  290.89  2265.4  297.81  2565.9  271.61
    2923  249.03  3262.4   235.6  3603.9  236.87  3787.4  234.62  4469.5  235.06
    4646  230.87  4715.5  237.41  4838.3  237.01    4973  238.11  5007.9  228.25
  5010.6  227.75  5013.9  228.25  5026.2  233.96  5071.8   235.8  5087.4  237.48
  5355.5  231.92    5393  236.11  5679.8  233.71  6382.6  245.99  6793.3  263.52
  6973.6  286.81    7111     297  7384.4  338.48    7725  333.16  7846.2  337.79
#Mann= 10 ,-1 , 0
     691     .05       0  3262.4     .16       0  3603.9     .12       0
  3787.4     .16       0  4469.5     .12       0  4838.3     .16       0
    4973     .12       0  5007.9     .07       0  5013.9     .12       0
  5071.8     .05       0
Bank Sta=4973,5087.4
XS Rating Curve= 0 ,0
Exp/Cntr=0.3,0.1

Type RM Length L Ch R = 1 ,12949   ,821,821,821
BEGIN DESCRIPTION:
BUFFALO CREEK 3.0
END DESCRIPTION:
XS GIS Cut Line= 3
      3669654.02      10531715.7      3670799.86     10526733.05
       3670782.5     10524303.81
#Sta/Elev= 30
   214.6  300.79   846.6  301.77  1172.5  296.22  1333.1  292.42  1552.4  297.79
  1696.7  289.19  2049.2  264.23  2385.3  260.79  2540.9  263.92    2678  259.66
  2970.8  232.19  2985.1  232.26  3323.1  233.53  4221.9  234.93  4981.4  234.43
  4991.1  227.69  4993.9  227.19  4997.1  227.69  5063.4  235.13  5114.8  232.28
  5352.5  236.19  6090.2  248.68  6500.2  267.07  7091.7   275.8  7210.2  285.11
  7310.2  301.32  7463.6  301.14  7510.2  307.58    7616  309.99  7756.6  317.62
#Mann= 13 ,-1 , 0
   214.6     .05       0  1172.5     .16       0  1696.7     .05       0
    2678     .12       0  2970.8     .16       0  2985.1     .12       0
  3323.1     .16       0  4221.9     .12       0  4991.1     .07       0
  4997.1     .12       0  5352.5     .05       0  7091.7     .16       0
    7616     .05       0
Bank Sta=4981.4,5063.4
XS Rating Curve= 0 ,0
Exp/Cntr=0.3,0.1

Type RM Length L Ch R = 1 ,12128   ,3121,3121,3121
BEGIN DESCRIPTION:
BUFFALO CREEK 2.0
END DESCRIPTION:
XS GIS Cut Line= 3
      3670192.21      10531733.1      3671285.97     10526489.99
      3671268.61     10524510.84
#Sta/Elev= 30
     3.7  301.49   830.1  294.58  1201.9  290.35  1559.3  262.38  2223.8  261.58
  2294.9  258.78  2318.7  253.46  2325.5  246.25  2368.7  246.12  2386.8  253.11
  2490.6  244.42  2723.9  235.61  3512.4  235.11  3747.8  235.02  4889.6  235.89
  5022.4  234.76  5162.4  231.71  5165.1  231.21  5168.4  231.71  5190.3  235.03
  5289.7  235.93  5979.5   247.8    6218  268.62  6449.5  296.68  6527.3  298.92
  6689.5  295.97  6900.4  310.27  6932.1  311.08  7159.8  308.15  7338.9  303.26
#Mann= 15 ,-1 , 0
     3.7     .05       0   830.1     .16       0  1559.3     .05       0
  2490.6     .12       0  3512.4     .16       0  3747.8     .12       0
  5162.4     .07       0  5168.4     .12       0  5190.3     .16       0
  5289.7     .05       0    6218     .16       0  6527.3     .05       0
  6900.4     .16       0  6932.1     .05       0  7159.8     .16       0
Bank Sta=4889.6,5022.4
XS Rating Curve= 0 ,0
Exp/Cntr=0.3,0.1

Type RM Length L Ch R = 1 ,9007    ,1659,1659,1659
BEGIN DESCRIPTION:
Mapping XS 7f069446
END DESCRIPTION:
XS GIS Cut Line= 4
      3670799.86     10531836.64      3671997.77     10528399.14
      3671980.41     10527218.58      3671372.81       10524875.
#Sta/Elev= 30
   839.8  297.78  1043.5  295.43  1259.6  281.33  1302.5  290.16  1459.4  289.85
  1738.5  285.71  1888.6  257.61  1914.4   274.6  2045.2  288.01  2068.2  290.72
  2279.9  297.15  2380.4  285.37  2729.1  245.72  3197.2  240.83  3219.5  240.58
  3401.1  239.69  3503.6   238.8    4896  229.82  4898.8  229.32    4902  229.82
    4939  233.62  5069.1  234.29  5069.8  234.29  6289.2  231.76  6780.1   243.7
  7012.4  247.73  7322.5  280.85  7597.1  280.05  8061.4   302.1  8081.8  303.98
#Mann= 19 ,-1 , 0
   839.8     .05       0  1043.5     .16       0  1302.5     .12       0
  1459.4     .16       0  2045.2     .12       0  2068.2     .16       0
  2279.9     .12       0  2380.4     .16       0  2729.1     .05       0
  3197.2     .16       0  3219.5     .12       0  3401.1     .16       0
  3503.6     .12       0    4896     .07       0    4902     .12       0
  5069.8     .05       0  6780.1     .16       0  7597.1     .05       0
  8061.4     .16       0
Bank Sta=4939,5069.1
XS Rating Curve= 0 ,0
Exp/Cntr=0.3,0.1

Type RM Length L Ch R = 1 ,7348    ,0,0,0
BEGIN DESCRIPTION:
BUFFALO CREEK 1.0
END DESCRIPTION:
XS GIS Cut Line= 4
      3671893.59     10531402.64      3673733.88     10528433.86
      3672553.33     10527027.61       3671667.9     10524718.55
#Sta/Elev= 30
   426.6   299.7   782.4  299.69   840.7  294.45  1014.4  269.48  1203.4  250.57
  1209.3  247.53  1334.6  239.02  2364.7   233.9  3331.1  238.23  3541.4  233.19
  4752.8  229.32  4755.6  228.82  4758.8  229.32  4904.1  232.45  5004.3  229.98
  5053.7  233.81  5153.9  233.59  5247.2  233.86  6228.1  233.35  6616.4  238.13
  6848.5  248.68  7070.2  263.09  7264.3  262.49  7347.9  265.61  7378.7  267.22
  7786.6  297.73  7937.7  293.14  8040.8  297.54  8100.9  292.42  8228.6  292.27
#Mann= 10 ,-1 , 0
   426.6     .16       0  1334.6     .05       0  3541.4     .12       0
  4752.8     .07       0  4758.8     .12       0  5153.9     .16       0
  5247.2     .05       0  6848.5     .16       0  7347.9     .05       0
  7378.7     .16       0
Bank Sta=4904.1,5053.7
XS Rating Curve= 0 ,0
Exp/Cntr=0.3,0.1

Chan Stop Cuts=-1
Use User Specified Reach Order=0
Composite Channel Slope=5