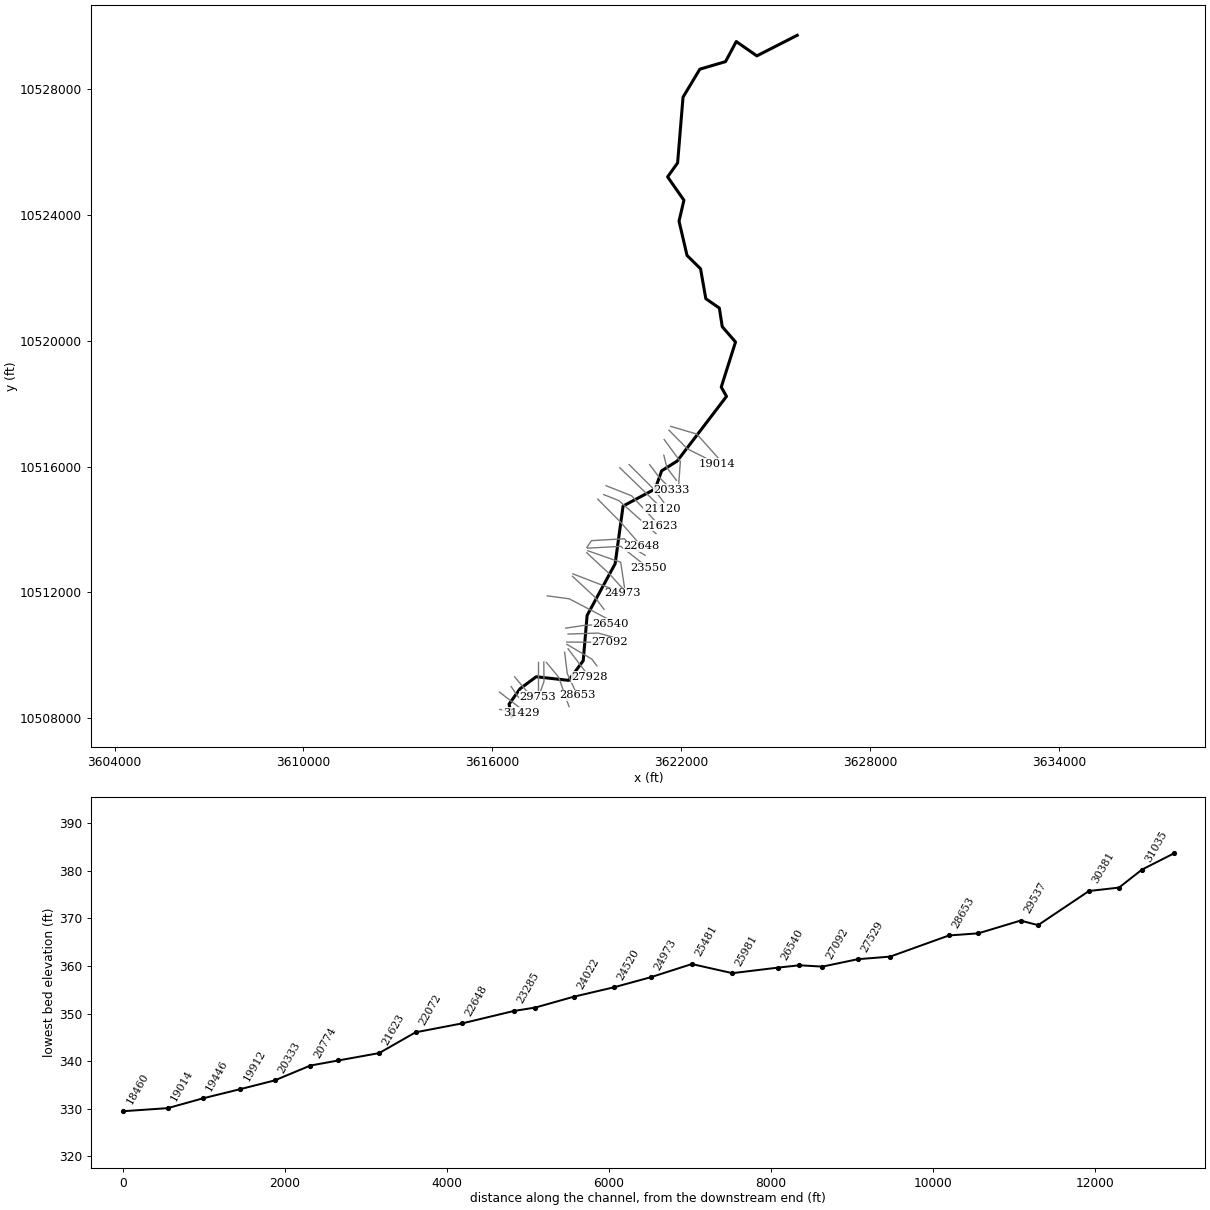
--- CANE BRANCH.prj (project) ---

Proj Title=CANE BRANCH Base Level Engineering
Current Plan=p01
Default Exp/Contr=0.3,0.1
English Units
Geom File=g01
Flow File=f01
Plan File=p01
Y Axis Title=Elevation
X Axis Title(PF)=Main Channel Distance
X Axis Title(XS)=Station
BEGIN DESCRIPTION:
CANE BRANCH
END DESCRIPTION:
DSS Export Rating Curves= 0
DSS Export Rating Curve Sorted= 0
DSS Export Volume Flow Curves= 0
DXF OffsetX= 0
DXF OffsetY= 0
DXF ScaleX= 1
DXF ScaleY= 10

--- CANE BRANCH.p01 (plan) ---

Plan Title=Multiple Run
Short Identifier=Multiple
Geom File=g01
Flow File=f01
Subcritical Flow
K Sum by GR= 0
Std Step Tol= 0.01
Critical Tol= 0.01
Num of Std Step Trials= 20
Max Error Tol= 0.3
Flow Tol Ratio= 0.001
Split Flow NTrial= 30
Split Flow Tol= 0.02
Split Flow Ratio= 0.02
Log Output Level= 0
Friction Slope Method= 1
Unsteady Friction Slope Method= 2
Unsteady Bridges Friction Slope Method= 1
Parabolic Critical Depth
Global Vel Dist=  1 , 1 , 1
Global Log Level= 0
CheckData=True
Encroach Param= -1, 0, 0, 0
BEGIN DESCRIPTION:
Multiple Run
END DESCRIPTION:

--- CANE BRANCH.f01 (steady flow) ---

Flow Title=Multiple
Program Version=4.10
Number of Profiles= 7
Profile Names=10-year,25-year,50-year,1pct_min,100-year,1pct_plu,500-year
River Rch & RM=CANE BRANCH,Reach-1         ,31429
    1369    1900    2342    2103    2844    3846    4183
River Rch & RM=CANE BRANCH,Reach-1         ,22648
    1792    2517    3128    2829    3826    5174    5710
River Rch & RM=CANE BRANCH,Reach-1         ,19014
    2132    3021    3776    3433    4642    6278    7002
River Rch & RM=CANE BRANCH,Reach-1         ,18460
    2132    3021    3776    3433    4642    6278    7002
River Rch & RM=CANE BRANCH,Reach-1         ,15844
    2282    3242    4058    3695    4997    6758    7561
River Rch & RM=CANE BRANCH,Reach-1         ,15672
    2430    3459    4336    3953    5345    7229    8105
River Rch & RM=CANE BRANCH,Reach-1         ,14941
    2430    3459    4336    3953    5345    7229    8105
River Rch & RM=CANE BRANCH,Reach-1         ,12596
    2961    4248    5353    4902    6629    8965   10145
River Rch & RM=CANE BRANCH,Reach-1         ,5910
    3127    4488    5656    5179    7003    9471   10714
Boundary for River Rch & Prof#=CANE BRANCH,Reach-1         , 1
Up Type= 0
Dn Type= 3
Dn Slope=0.009
Boundary for River Rch & Prof#=CANE BRANCH,Reach-1         , 2
Up Type= 0
Dn Type= 3
Dn Slope=0.009
Boundary for River Rch & Prof#=CANE BRANCH,Reach-1         , 3
Up Type= 0
Dn Type= 3
Dn Slope=0.009
Boundary for River Rch & Prof#=CANE BRANCH,Reach-1         , 4
Up Type= 0
Dn Type= 3
Dn Slope=0.009
Boundary for River Rch & Prof#=CANE BRANCH,Reach-1         , 5
Up Type= 0
Dn Type= 3
Dn Slope=0.009
Boundary for River Rch & Prof#=CANE BRANCH,Reach-1         , 6
Up Type= 0
Dn Type= 3
Dn Slope=0.009
Boundary for River Rch & Prof#=CANE BRANCH,Reach-1         , 7
Up Type= 0
Dn Type= 3
Dn Slope=0.009
DSS Import GetInterval= 0
DSS Import GetPeak= 0
DSS Import FillOption= 0

--- CANE BRANCH.g01 (geometry) ---

Geom Title=Existing Conditions
Program Version=4.10

River Reach=CANE BRANCH     ,Reach-1
Reach XY= 30
       3616619.5       10508060.      3616532.25       10508449.
      3616880.25       10508938.        3617395.       10509320.
        3618428.       10509205.      3618889.25       10509830.
      3619012.75       10511269.      3619903.25       10512910.
        3620155.       10514743.       3621175.5       10515287.
       3621380.5       10515863.        3621874.       10516173.
        3623441.       10518227.       3623274.5       10518523.
      3623727.75       10519955.      3623305.75       10520443.
      3623214.25       10521033.        3622784.       10521332.
        3622617.       10522281.        3622187.       10522706.
       3621933.5       10523795.       3622088.5       10524460.
      3621570.25       10525202.      3621887.75       10525646.
        3622060.       10527734.       3622594.5       10528624.
      3623410.25       10528863.      3623751.75       10529502.
       3624404.5       10529046.      3625687.75       10529700.

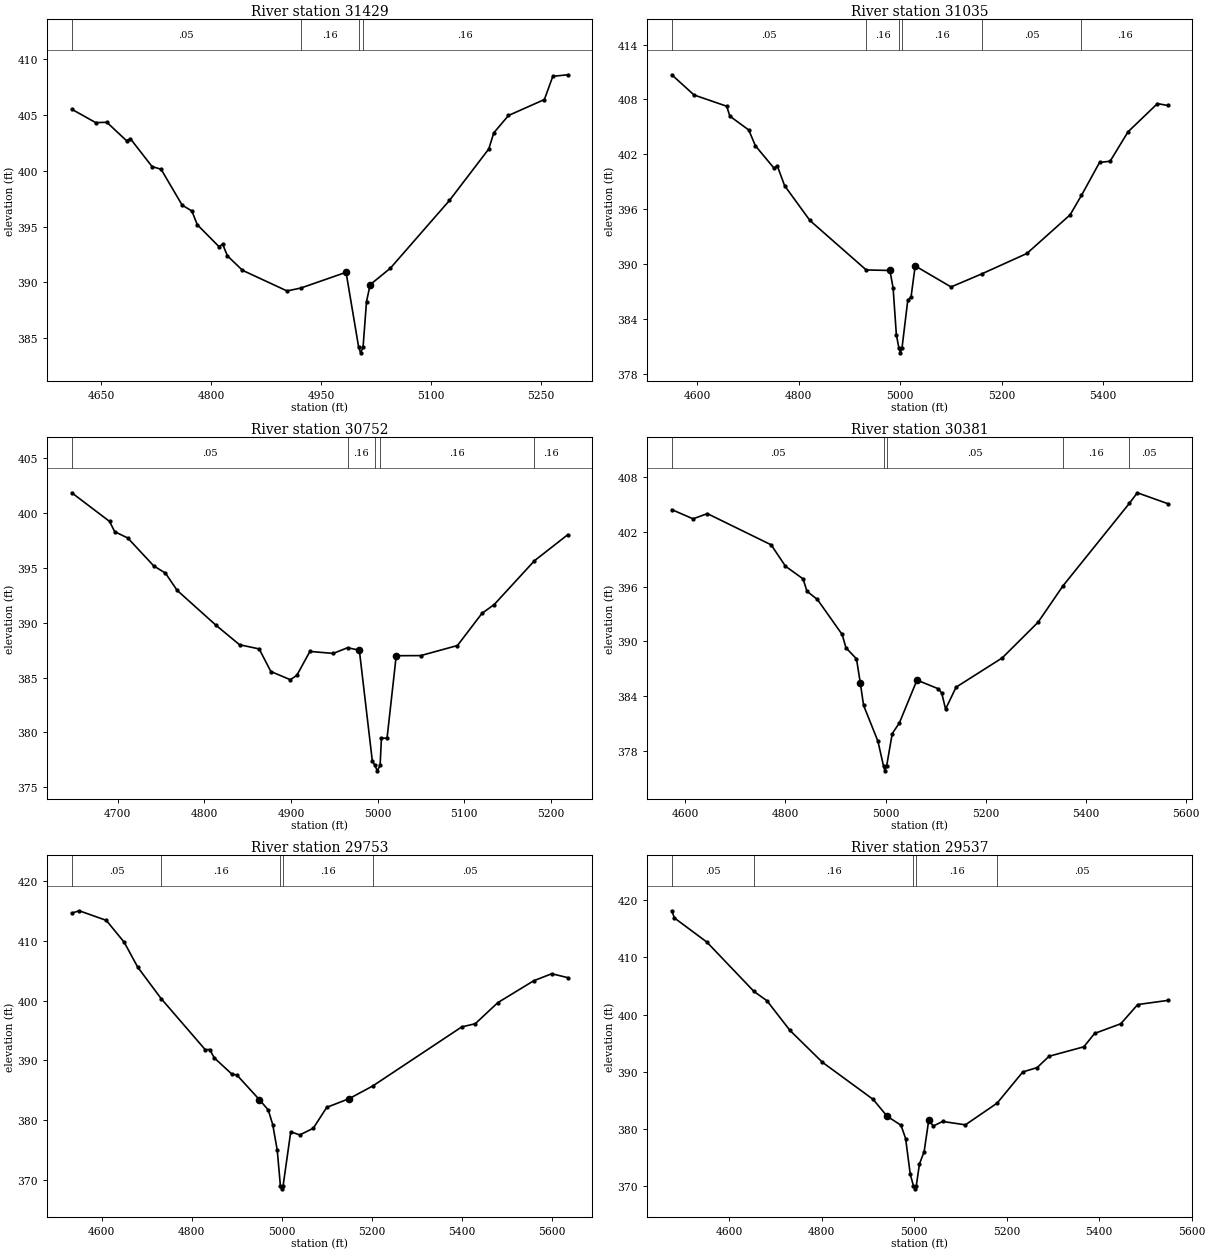
Type RM Length L Ch R = 1 ,31429   ,394,394,394
BEGIN DESCRIPTION:
CANE BRANCH 60.0
END DESCRIPTION:
XS GIS Cut Line= 3
      3616243.06     10508282.85      3616489.63     10508223.81
      3616909.77     10508171.73
#Sta/Elev= 30
  4609.8  405.52  4642.5  404.32  4657.7  404.35  4684.5   402.7  4689.7  402.89
  4719.4  400.38  4731.7  400.14  4760.5  396.92  4773.7   396.4  4781.1  395.17
  4810.6  393.21  4815.8  393.41  4822.2  392.38  4842.8  391.08  4903.6  389.23
  4922.5  389.49  4984.2   390.9  5001.4  384.18  5004.1  383.68  5007.4  384.18
  5012.1  388.28  5017.1  389.79  5044.7  391.27  5125.3  397.34    5179  401.96
  5185.8   403.4  5205.9  404.96  5254.9  406.39  5266.4  408.47  5286.7  408.61
#Mann= 4 ,-1 , 0
  4609.8     .05       0  4922.5     .16       0  5001.4     .07       0
  5007.4     .16       0
Bank Sta=4984.2,5017.1
XS Rating Curve= 0 ,0
Exp/Cntr=0.3,0.1

Type RM Length L Ch R = 1 ,31035   ,283,283,283
BEGIN DESCRIPTION:
Mapping XS a46fd135
END DESCRIPTION:
XS GIS Cut Line= 2
      3616229.19     10508831.48      3617002.88     10508234.72
#Sta/Elev= 30
  4550.1  410.69    4594  408.48  4658.3  407.25  4664.6  406.16  4701.8  404.65
  4714.8  402.93  4751.6  400.47  4757.9  400.75  4772.4  398.56  4822.3  394.75
  4933.2  389.34  4979.9  389.28  4986.2  387.38  4992.6  382.27  4997.7  380.77
  5000.5  380.27  5003.7  380.77  5015.2  386.06  5021.5  386.35  5029.7  389.78
  5100.4  387.48  5160.6   388.9  5249.8  391.14    5335  395.37  5357.3  397.49
    5393   401.1  5413.8  401.23  5449.1  404.45  5507.1  407.54  5527.2  407.33
#Mann= 6 ,-1 , 0
  4550.1     .05       0  4933.2     .16       0  4997.7     .07       0
  5003.7     .16       0  5160.6     .05       0  5357.3     .16       0
Bank Sta=4979.9,5029.7
XS Rating Curve= 0 ,0
Exp/Cntr=0.3,0.1

Type RM Length L Ch R = 1 ,30752   ,371,371,371
BEGIN DESCRIPTION:
CANE BRANCH 59.0
END DESCRIPTION:
XS GIS Cut Line= 3
      3616599.59     10509010.22      3616799.61     10508710.19
      3616949.59     10508560.21
#Sta/Elev= 30
  4646.8  401.85  4690.4  399.24  4696.4   398.3  4711.4  397.73  4741.5  395.18
    4755  394.52  4768.5  392.95  4813.6  389.75  4840.6  387.99  4863.2  387.61
  4876.7  385.55  4899.2   384.8  4906.7   385.2  4921.8  387.38  4948.8   387.2
  4965.3  387.72  4978.9  387.49  4993.9  377.38  4996.9  376.99  4999.6  376.49
  5002.9  376.99  5004.4  379.47  5010.9  379.47  5021.5  386.99  5049.8     387
  5092.2  387.92  5120.5  390.85  5134.7  391.66  5181.1  395.65  5219.5  398.02
#Mann= 5 ,-1 , 0
  4646.8     .05       0  4965.3     .16       0  4996.9     .07       0
  5002.9     .16       0  5181.1     .16       0
Bank Sta=4978.9,5021.5
XS Rating Curve= 0 ,0
Exp/Cntr=0.3,0.1

Type RM Length L Ch R = 1 ,30381   ,628,628,628
BEGIN DESCRIPTION:
CANE BRANCH 58.0
END DESCRIPTION:
XS GIS Cut Line= 2
      3616707.52     10509318.09      3617348.87     10508564.06
#Sta/Elev= 30
  4573.2  404.47  4615.7  403.46  4644.3  404.03  4771.6   400.6  4800.2  398.25
  4835.3  396.86  4843.1   395.5  4863.9   394.6  4913.3  390.75    4921  389.28
  4941.9  388.08  4949.6  385.41  4956.1  382.96  4984.7  379.03    4996  376.27
  4998.7  375.77    5002  376.27  5013.3  379.86  5027.6  381.04  5062.7  385.74
  5105.5  384.78  5112.1  384.31  5119.8  382.55  5140.7  384.96  5232.9  388.18
  5304.3  392.09  5354.2   396.1  5486.5  405.15  5502.5  406.32  5563.1  405.13
#Mann= 5 ,-1 , 0
  4573.2     .05       0    4996     .03       0    5002     .05       0
  5354.2     .16       0  5486.5     .05       0
Bank Sta=4949.6,5062.7
XS Rating Curve= 0 ,0
Exp/Cntr=0.3,0.1

Type RM Length L Ch R = 1 ,29753   ,216,216,216
BEGIN DESCRIPTION:
CANE BRANCH 57.0
END DESCRIPTION:
XS GIS Cut Line= 2
      3617436.69     10509786.84      3617436.69     10508684.84
#Sta/Elev= 30
  4533.7  414.58  4550.4  414.97  4610.4  413.37  4650.3  409.71  4680.3  405.56
  4732.3  400.32  4830.3   391.8  4840.3  391.83  4850.3  390.44  4890.3  387.67
  4900.3   387.6  4950.3  383.49  4970.3  381.74  4980.3   379.3  4990.3  375.03
  4997.3  369.09  5000.1  368.59  5003.3  369.09  5020.3  378.11  5040.3  377.58
  5070.3  378.69  5100.3  382.18  5150.3  383.64  5202.6  385.75  5400.3   395.6
  5430.3  396.13  5480.3  399.64  5560.3   403.3  5600.3  404.47  5635.7  403.82
#Mann= 5 ,-1 , 0
  4533.7     .05       0  4732.3     .16       0  4997.3     .07       0
  5003.3     .16       0  5202.6     .05       0
Bank Sta=4950.3,5150.3
XS Rating Curve= 0 ,0
Exp/Cntr=0.3,0.1

Type RM Length L Ch R = 1 ,29537   ,521,521,521
BEGIN DESCRIPTION:
CANE BRANCH 56.0
END DESCRIPTION:
XS GIS Cut Line= 3
      3617637.21       10509786.      3617642.42     10509171.37
      3617491.37     10508739.05
#Sta/Elev= 30
  4475.5  418.12  4481.3  416.86  4551.3  412.66  4653.3  404.03  4681.3  402.41
  4731.3  397.21  4801.3  391.66  4911.3  385.16  4941.3  382.23  4971.3  380.66
  4981.3  378.34  4991.3  372.11  4998.3  370.05  5001.1  369.55  5004.3  370.05
  5011.3  373.91  5021.3  376.03  5031.3  381.53  5041.3  380.53  5061.3  381.32
  5110.6  380.73  5179.1  384.51  5234.8  389.97  5265.8  390.73  5291.6  392.71
  5366.8  394.36    5390  396.69  5446.8  398.39  5483.3  401.74  5548.1  402.46
#Mann= 5 ,-1 , 0
  4475.5     .05       0  4653.3     .16       0  4998.3     .07       0
  5004.3     .16       0  5179.1     .05       0
Bank Sta=4941.3,5031.3
XS Rating Curve= 0 ,0
Exp/Cntr=0.3,0.1

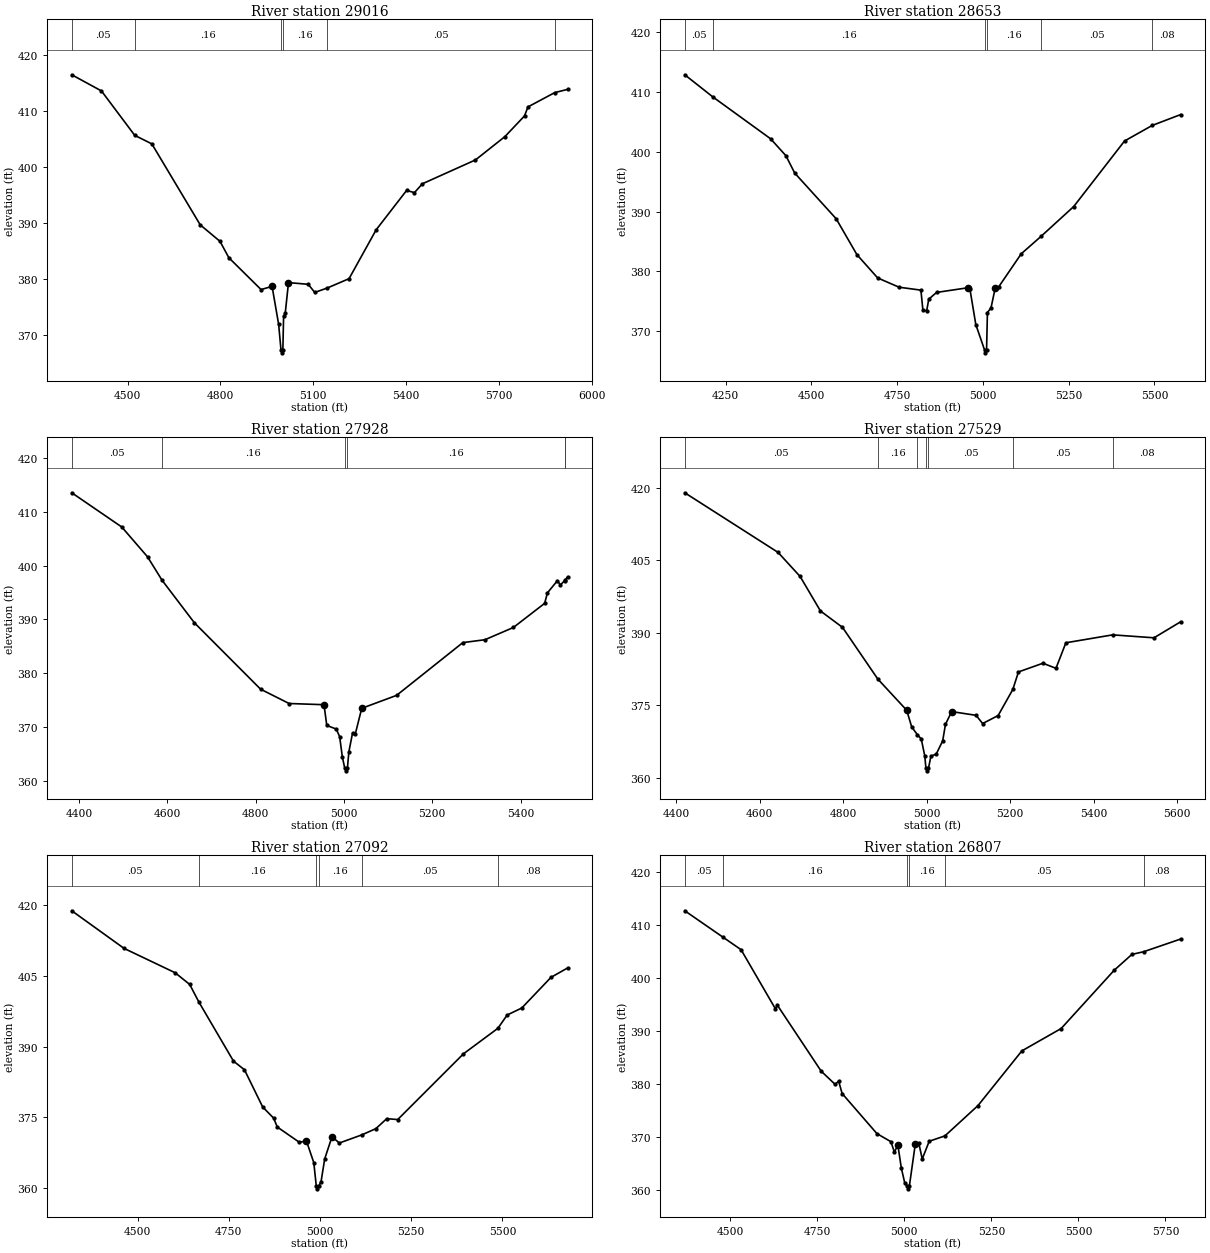
Type RM Length L Ch R = 1 ,29016   ,363,363,363
BEGIN DESCRIPTION:
CANE BRANCH 55.0
END DESCRIPTION:
XS GIS Cut Line= 3
      3617720.57     10509775.52      3618111.17     10509301.58
       3618439.3     10508369.29
#Sta/Elev= 30
  4319.5  416.44  4415.4  413.56    4523  405.64  4578.3  404.12  4734.6  389.69
  4798.5  386.75  4827.2  383.82  4931.3  378.15  4966.9  378.72  4988.1  371.94
  4995.7  367.37  4998.5  366.87  5001.7  367.37  5004.1  373.36  5009.4  373.92
  5019.9  379.39  5083.6  379.09  5104.8  377.64  5144.4  378.41  5215.6  380.09
  5303.2   388.8  5401.6  395.82    5427  395.43  5452.7  397.01  5624.2  401.26
  5719.6  405.43  5782.7  409.11  5793.8  410.71  5880.3  413.26    5922  413.84
#Mann= 6 ,-1 , 0
  4319.5     .05       0    4523     .16       0  4995.7     .07       0
  5001.7     .16       0  5144.4     .05       0  5880.3     .08       0
Bank Sta=4966.9,5019.9
XS Rating Curve= 0 ,0
Exp/Cntr=0.3,0.1

Type RM Length L Ch R = 1 ,28653   ,725,725,725
BEGIN DESCRIPTION:
CANE BRANCH 54.0
END DESCRIPTION:
XS GIS Cut Line= 3
      3618298.68     10510098.41      3618382.01     10509421.37
      3618704.75     10508729.04
#Sta/Elev= 30
  4130.5  412.81    4212  409.13  4380.6  402.14  4425.3  399.32  4451.1  396.41
    4572  388.79  4632.5   382.8  4692.9  378.92  4755.3  377.37  4819.1  376.88
    4825  373.49    4836  373.46    4842  375.38  4864.9   376.5  4956.3  377.28
  4961.9  377.12  4979.2  371.14  5004.6  366.92  5007.3  366.42  5010.6  366.92
  5013.1  373.15  5023.6  373.93    5036   377.3  5045.6   377.4  5111.8  382.95
  5169.8  385.87  5264.6  390.82  5412.9  401.76  5493.7  404.36  5576.5  406.17
#Mann= 6 ,-1 , 0
  4130.5     .05       0    4212     .16       0  5004.6     .07       0
  5010.6     .16       0  5169.8     .05       0  5493.7     .08       0
Bank Sta=4956.3,5036
XS Rating Curve= 0 ,0
Exp/Cntr=0.3,0.1

Type RM Length L Ch R = 1 ,27928   ,399,399,399
BEGIN DESCRIPTION:
CANE BRANCH 53.0
END DESCRIPTION:
XS GIS Cut Line= 2
      3618408.06     10510207.81      3619084.89     10509312.31
#Sta/Elev= 30
  4383.8  413.47    4497  407.13  4555.3  401.61  4588.2  397.27  4661.4  389.39
  4811.3  377.09  4875.8  374.44  4954.8  374.22  4961.1  370.38  4982.5  369.71
  4990.2  368.31  4996.5  364.45  5001.8  362.47  5004.5  361.97  5007.8  362.47
  5011.1  365.49  5019.4  368.97  5025.6  368.77  5040.2  373.55  5119.2  375.95
  5269.1  385.72    5319  386.25  5383.5  388.52  5454.3  392.99  5460.6  394.93
  5483.4  397.21  5489.7  396.38  5499.5  397.19    5501  397.37  5506.3  397.89
#Mann= 6 ,-1 , 0
  4383.8     .05       0  4588.2     .16       0  5001.8     .07       0
  5007.8     .16       0  5499.5     .08       0    5501      .1       0
Bank Sta=4954.8,5040.2
XS Rating Curve= 0 ,0
Exp/Cntr=0.3,0.1

Type RM Length L Ch R = 1 ,27529   ,437,437,437
BEGIN DESCRIPTION:
CANE BRANCH 52.0
END DESCRIPTION:
XS GIS Cut Line= 3
      3618371.61     10510348.44      3619158.05     10509884.91
      3619324.66     10509666.23
#Sta/Elev= 30
  4420.3  418.93  4643.8   406.6  4696.6  401.62  4745.3  394.49  4798.1   391.1
  4882.8   380.4  4951.9  373.96  4963.9   370.5  4977.5  368.91  4986.8  368.02
  4995.2  364.51    4998  361.93  5000.8  361.43    5004  361.93    5010  364.49
  5022.5  364.87  5038.1  367.63  5044.8  371.05  5059.6  373.68  5118.1  372.91
  5133.8  371.21  5170.9  372.86  5206.2  378.27  5219.6  381.88  5278.2  383.68
  5309.5  382.63  5333.2  387.91  5445.3  389.55  5544.3  388.94  5608.1  392.25
#Mann= 7 ,-1 , 0
  4420.3     .05       0  4882.8     .16       0  4977.5     .05       0
    4998     .07       0    5004     .05       0  5206.2     .05       0
  5445.3     .08       0
Bank Sta=4951.9,5059.6
XS Rating Curve= 0 ,0
Exp/Cntr=0.3,0.1

Type RM Length L Ch R = 1 ,27092   ,285,285,285
BEGIN DESCRIPTION:
CANE BRANCH 51.0
END DESCRIPTION:
XS GIS Cut Line= 2
      3618366.38     10510421.37      3619725.17     10510416.17
#Sta/Elev= 30
  4319.8  418.75    4463  410.79    4603  405.63    4643  403.15  4667.6   399.5
    4763  386.91    4793  385.09    4843   377.2    4873  374.84    4883  372.96
    4943  369.75    4963  369.98    4983  365.43    4990  360.37  4992.8  359.87
    4996  360.37    5003  361.42    5013  366.23    5033  370.91    5053  369.57
  5114.8   371.3    5153  372.61    5183  374.73    5213  374.54    5393  388.45
  5487.5  393.86    5513  396.68    5553  398.16    5633  404.65  5678.6  406.64
#Mann= 6 ,-1 , 0
  4319.8     .05       0  4667.6     .16       0    4990     .07       0
    4996     .16       0  5114.8     .05       0  5487.5     .08       0
Bank Sta=4963,5033
XS Rating Curve= 0 ,0
Exp/Cntr=0.3,0.1

Type RM Length L Ch R = 1 ,26807   ,267,267,267
BEGIN DESCRIPTION:
CANE BRANCH 50.0
END DESCRIPTION:
XS GIS Cut Line= 3
      3618408.07     10510676.58      3619366.38     10510707.83
      3619814.34     10510582.82
#Sta/Elev= 30
  4369.6  412.68  4479.3  407.69  4531.2  405.33    4630  394.14    4635  394.89
  4761.3  382.38  4801.4  379.88  4811.4   380.5  4821.4  378.16  4921.4  370.58
  4961.5  369.06  4971.5  367.08  4981.5  368.42  4991.5  364.06  5001.5   361.2
  5008.5  360.65  5011.2  360.15  5014.5  360.65  5031.5  368.59  5041.5  368.82
  5051.5  365.79  5071.5  369.14  5116.6  370.15  5211.6  375.88  5337.6  386.21
  5450.5  390.44  5602.8  401.45  5653.6  404.44  5687.1  404.94  5793.5  407.34
#Mann= 6 ,-1 , 0
  4369.6     .05       0  4479.3     .16       0  5008.5     .07       0
  5014.5     .16       0  5116.6     .05       0  5687.1     .08       0
Bank Sta=4981.5,5031.5
XS Rating Curve= 0 ,0
Exp/Cntr=0.3,0.1

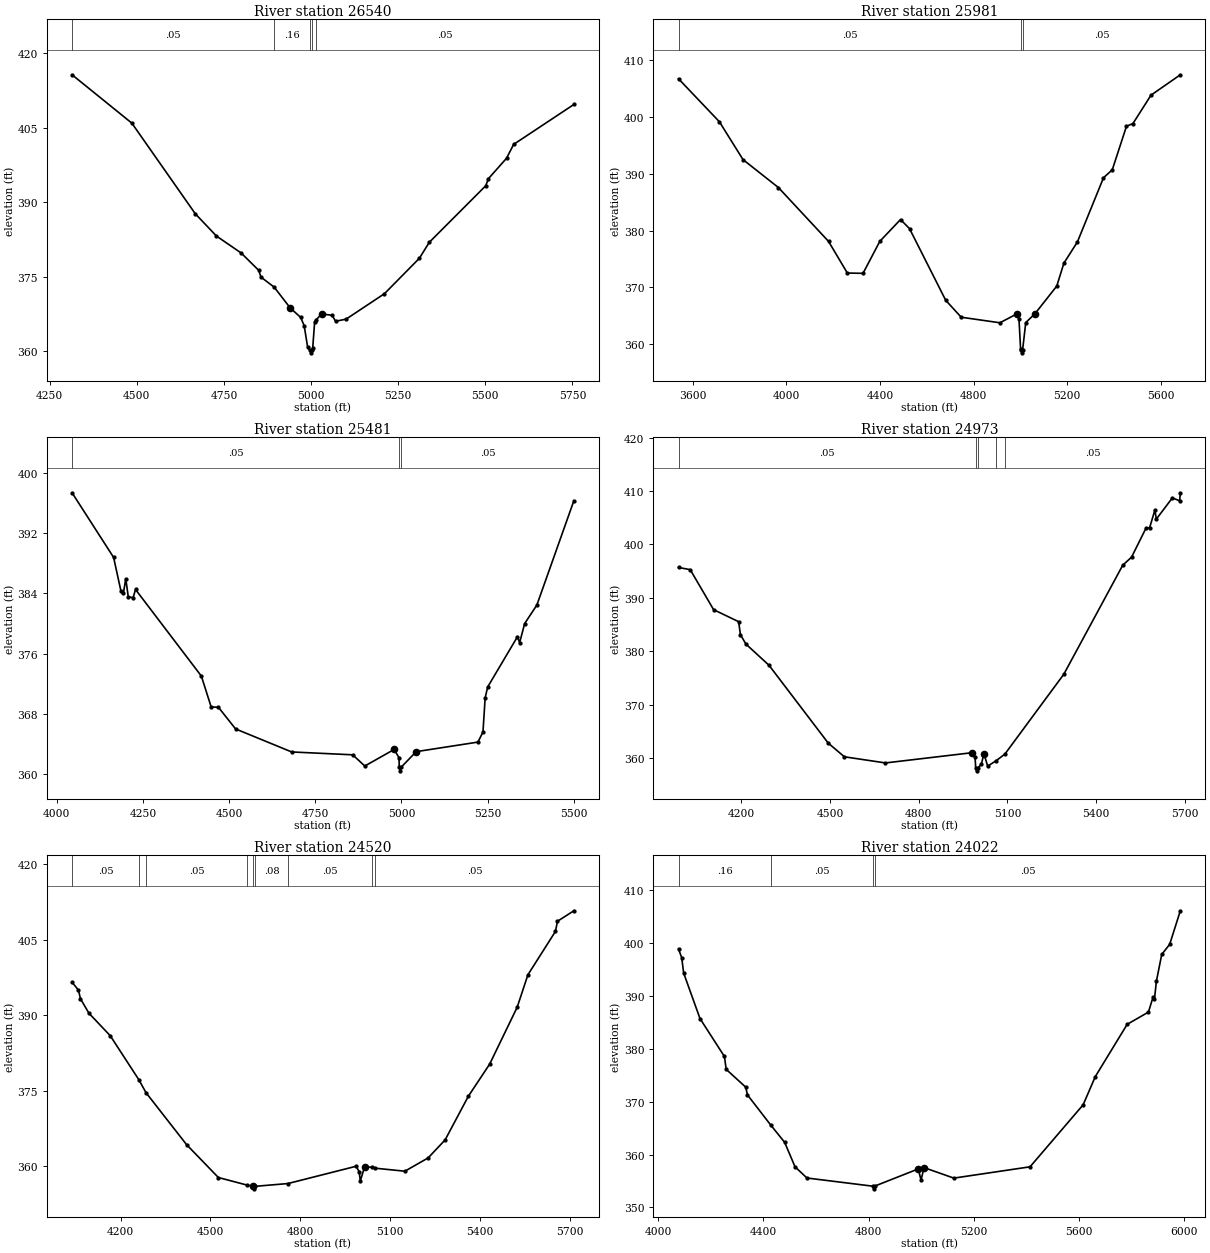
Type RM Length L Ch R = 1 ,26540   ,559,559,559
BEGIN DESCRIPTION:
CANE BRANCH 49.0
END DESCRIPTION:
XS GIS Cut Line= 3
      3618329.97     10510864.09      3618882.01     10510947.41
      3619762.17     10510999.49
#Sta/Elev= 30
  4314.2  415.63  4485.8  405.89  4667.8  387.65  4728.6  383.16  4799.3  379.76
  4849.8  376.26  4856.2   374.9  4894.3  372.87  4940.2  368.69  4970.3  366.78
  4980.3  365.11  4990.3  360.77  4996.7  360.15  4999.5  359.65  5002.7  360.15
  5004.7  360.56  5010.3  365.86  5013.7  366.24  5030.4  367.46  5060.4  367.22
  5070.4  366.01  5100.5  366.43  5210.7  371.56  5310.9  378.69  5339.3   381.9
  5501.2  393.28  5509.1  394.72  5561.3  398.85  5581.3  401.61  5754.2  409.65
#Mann= 5 ,-1 , 0
  4314.2     .05       0  4894.3     .16       0  4996.7     .07       0
  5002.7     .16       0  5013.7     .05       0
Bank Sta=4940.2,5030.4
XS Rating Curve= 0 ,0
Exp/Cntr=0.3,0.1

Type RM Length L Ch R = 1 ,25981   ,500,500,500
BEGIN DESCRIPTION:
CANE BRANCH 48.0
END DESCRIPTION:
XS GIS Cut Line= 3
       3617746.6     10511890.12      3618444.51     10511796.37
      3619720.58     10511129.69
#Sta/Elev= 30
    3539  406.72  3713.6  399.16  3814.5   392.5  3965.8  387.58  4179.8  378.11
  4260.2  372.54  4327.2  372.48  4399.1  378.12  4487.4  381.95  4525.9  380.35
  4680.5  367.74  4746.7  364.76  4912.1  363.78    4984  365.33  4993.6  364.39
  5000.4  359.18    5003  358.99  5005.8  358.49    5009  358.99  5022.5  363.82
    5061  365.33    5155  370.24  5185.4  374.27  5243.3  378.02  5354.6   389.3
  5392.2  390.71  5452.8  398.37  5480.5  398.85  5557.6  403.84  5682.9  407.43
#Mann= 3 ,-1 , 0
    3539     .05       0    5003     .03       0    5009     .05       0
Bank Sta=4984,5061
XS Rating Curve= 0 ,0
Exp/Cntr=0.3,0.1

Type RM Length L Ch R = 1 ,25481   ,508,508,508
BEGIN DESCRIPTION:
CANE BRANCH 47.0
END DESCRIPTION:
XS GIS Cut Line= 3
      3618549.59     10512510.21      3619249.61     10511860.19
      3619549.62     10511460.17
#Sta/Elev= 30
  4044.8  397.36  4165.3  388.77  4186.3  384.35  4193.6  383.98  4200.5  385.94
  4207.8  383.53    4222  383.43  4228.8  384.51  4419.8     373  4448.2   368.9
  4469.2  368.86    4519  365.98  4681.7  362.92  4858.6  362.54  4893.8  361.05
  4978.8  363.25    4993  362.16  4993.7  360.91  4996.4  360.41  4999.7  360.91
  5042.8  362.96    5222  364.23  5236.5  365.58  5242.8  370.09  5250.1  371.55
  5336.5  378.23  5342.8  377.44  5357.4  379.98  5392.8  382.44  5500.1   396.3
#Mann= 3 ,-1 , 0
  4044.8     .05       0  4993.7     .03       0  4999.7     .05       0
Bank Sta=4978.8,5042.8
XS Rating Curve= 0 ,0
Exp/Cntr=0.3,0.1

Type RM Length L Ch R = 1 ,24973   ,453,453,453
BEGIN DESCRIPTION:
CANE BRANCH 46.0
END DESCRIPTION:
XS GIS Cut Line= 3
       3618564.3     10512588.04      3619658.05     10512166.16
      3620146.11     10511974.05
#Sta/Elev= 30
  3987.9   395.7  4027.4  395.29  4106.5   387.8  4191.1  385.55  4197.2  383.13
  4215.7  381.36  4293.7   377.4    4494  362.83  4548.6  360.26  4687.7  359.11
  4979.7  361.02  4990.4  360.26  4992.9  358.13  4995.7  357.63  4998.9  358.13
  5011.8  358.83  5020.6  360.86  5033.2  358.51  5062.6  359.55  5091.5  360.77
  5290.8  375.72  5490.1  396.13  5519.8  397.63  5568.6  403.06    5581  403.15
  5598.4  406.41  5603.8  404.77  5657.9  408.73  5682.3  408.17  5684.7  409.68
#Mann= 5 ,-1 , 0
  3987.9     .05       0  4992.9     .03       0  4998.9     .05       0
  5062.6     .16       0  5091.5     .05       0
Bank Sta=4979.7,5020.6
XS Rating Curve= 0 ,0
Exp/Cntr=0.3,0.1

Type RM Length L Ch R = 1 ,24520   ,498,498,498
BEGIN DESCRIPTION:
CANE BRANCH 45.0
END DESCRIPTION:
XS GIS Cut Line= 3
      3618999.62     10513260.18      3619699.61     10512610.19
      3620184.09     10512077.62
#Sta/Elev= 30
  4038.1  396.54  4059.3     395  4066.2  393.26  4094.5  390.39  4165.4  385.94
    4261  377.19  4284.9  374.62  4420.2  364.31  4526.5  357.77  4622.6  356.26
  4643.7  356.02  4646.4  355.52  4649.7  356.02  4758.5  356.57  4986.2     360
  4996.7  358.92  5000.4  357.07  5014.6  359.88  5038.7  359.81  5050.4  359.62
  5149.1  359.02  5226.8  361.66  5283.5  365.24  5361.3  373.93  5432.2  380.29
  5524.1  391.59  5559.9  398.03  5651.8  406.64  5658.6  408.66  5713.3  410.74
#Mann= 9 ,-1 , 0
  4038.1     .05       0    4261     .16       0  4284.9     .05       0
  4622.6     .08       0  4643.7     .03       0  4649.7     .08       0
  4758.5     .05       0  5038.7     .16       0  5050.4     .05       0
Bank Sta=4643.7,5014.6
XS Rating Curve= 0 ,0
Exp/Cntr=0.3,0.1

Type RM Length L Ch R = 1 ,24022   ,472,472,472
BEGIN DESCRIPTION:
CANE BRANCH 44.0
END DESCRIPTION:
XS GIS Cut Line= 3
      3619038.29      10513322.4      3620079.92     10512957.83
      3620199.61     10512160.15
#Sta/Elev= 30
  4076.7   398.9  4088.7  397.31  4096.3  394.36  4158.3  385.77  4251.4  378.58
  4258.2  376.14  4332.4  372.78  4339.2   371.3  4427.3  365.63  4480.7  362.33
  4520.1  357.71  4565.5  355.58  4816.7  354.03  4819.5  353.53  4822.7  354.03
  4989.3   357.3  4999.9  355.17  5011.2  357.55  5124.7  355.56  5414.8   357.7
    5617  369.44  5663.3  374.78  5784.6  384.67  5865.5  386.98  5883.2  389.85
  5888.3  389.39  5895.9  392.85  5916.1  397.89  5946.4  399.81  5986.9  406.16
#Mann= 4 ,-1 , 0
  4076.7     .16       0  4427.3     .05       0  4816.7     .03       0
  4822.7     .05       0
#XS Ineff= 1 ,-1
 5026.14 5465.91  357.06
Permanent Ineff=
       F
Bank Sta=4989.3,5011.2
XS Rating Curve= 0 ,0
Exp/Cntr=0.3,0.1

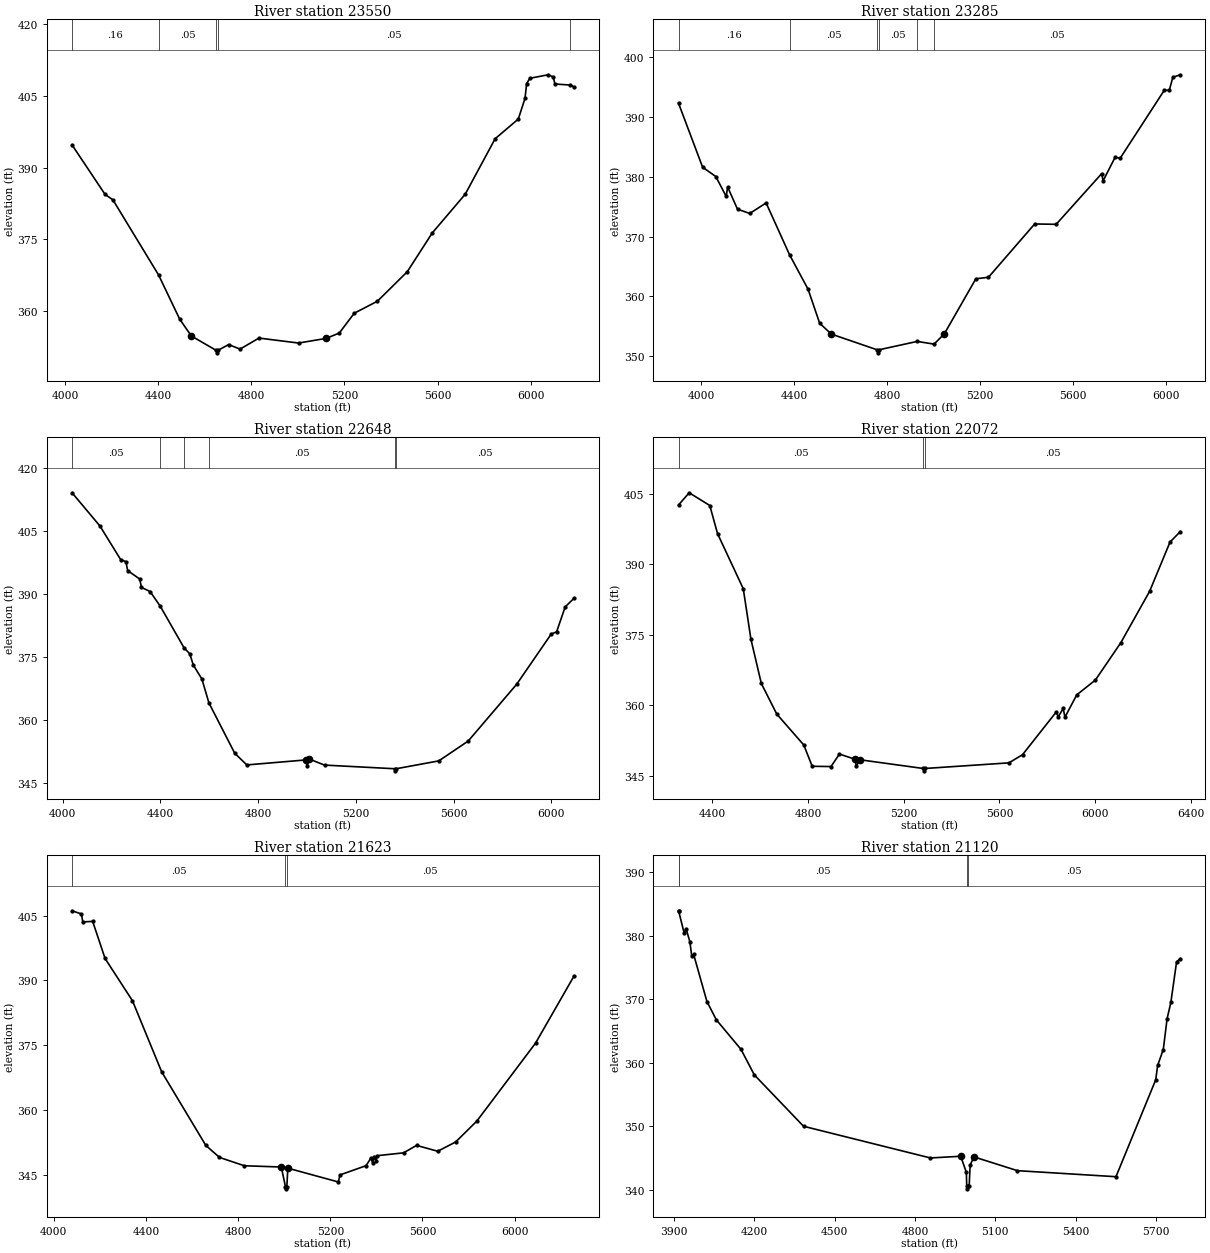
Type RM Length L Ch R = 1 ,23550   ,265,265,265
BEGIN DESCRIPTION:
CANE BRANCH 43.0
END DESCRIPTION:
XS GIS Cut Line= 3
      3619027.84     10513405.75      3620079.92     10513463.04
      3620949.71     10512785.96
#Sta/Elev= 30
  4029.8  394.76  4171.8   384.4  4205.1  383.29  4401.2  367.58  4492.3   358.3
  4542.3  354.79  4649.5  351.76  4652.2  351.26  4655.5  351.76  4702.6  352.99
  4751.4  352.04  4832.8  354.35    5003  353.31  5121.1  354.28  5177.9   355.4
  5242.1  359.55  5341.6  362.06  5470.1  368.24  5577.3  376.35  5718.9  384.45
  5847.4  396.06  5946.9  400.18  5975.9  404.53  5982.8  407.61  5996.7  408.72
  6075.4  409.45  6096.9  409.01  6104.4  407.52  6170.3   407.3  6185.7  406.93
#Mann= 5 ,-1 , 0
  4029.8     .16       0  4401.2     .05       0  4649.5     .03       0
  4655.5     .05       0  6170.3     .08       0
Bank Sta=4542.3,5121.1
XS Rating Curve= 0 ,0
Exp/Cntr=0.3,0.1

Type RM Length L Ch R = 1 ,23285   ,637,637,637
BEGIN DESCRIPTION:
CANE BRANCH 42.0
END DESCRIPTION:
XS GIS Cut Line= 5
      3619004.74     10513431.28      3619152.31     10513643.95
      3620198.32     10513704.71      3620419.67     10513444.29
      3620853.69     10513179.54
#Sta/Elev= 30
  3903.2  392.33  4006.8  381.62  4063.5  380.06  4108.1  376.72  4114.2  378.31
  4156.7  374.59  4209.4  373.88  4279.6  375.64    4381  366.91  4459.9   361.2
  4509.9  355.49    4560  353.68  4757.4  351.04  4760.1  350.54  4763.4  351.04
  4928.9  352.45  5001.7     352  5045.7  353.73  5181.1  362.94  5235.2  363.19
    5434  372.12  5526.3  372.06    5722  380.55  5727.9  379.34  5780.1  383.31
  5801.4  383.12  5991.2  394.52  6012.5   394.5  6027.9  396.69    6060   397.1
#Mann= 6 ,-1 , 0
  3903.2     .16       0    4381     .05       0  4757.4     .07       0
  4763.4     .05       0  4928.9     .08       0  5001.7     .05       0
Bank Sta=4560,5045.7
XS Rating Curve= 0 ,0
Exp/Cntr=0.3,0.1

Type RM Length L Ch R = 1 ,22648   ,576,576,576
BEGIN DESCRIPTION:
CANE BRANCH 41.0
END DESCRIPTION:
XS GIS Cut Line= 3
      3619350.76     10514963.03      3620049.61     10514260.19
      3620749.63     10513460.16
#Sta/Elev= 30
    4038  414.16  4152.3  406.23  4237.2  398.22  4258.4  397.76  4265.5  395.63
    4315  393.61  4322.1  391.62  4357.4  390.64  4398.6  387.18  4496.5  377.22
    4520   375.8  4534.2  373.14  4569.5  369.79  4598.4  364.09  4703.9  352.12
  4753.4  349.34  4993.8  350.52  5000.9  348.99  5007.9  350.76  5071.4   349.3
  5358.8  348.43  5361.6  347.93  5364.8  348.43  5539.3   350.3  5659.8  355.03
  5858.2  368.56  5999.6  380.52  6021.5  381.03  6056.6  386.97  6092.2     389
#Mann= 6 ,-1 , 0
    4038     .05       0  4398.6      .1       0  4496.5     .16       0
  4598.4     .05       0  5358.8     .03       0  5364.8     .05       0
Bank Sta=4993.8,5007.9
XS Rating Curve= 0 ,0
Exp/Cntr=0.3,0.1

Type RM Length L Ch R = 1 ,22072   ,449,449,449
BEGIN DESCRIPTION:
CANE BRANCH 40.0
END DESCRIPTION:
XS GIS Cut Line= 3
      3619538.24     10515108.88      3620022.63     10514916.16
      3621199.72     10513869.28
#Sta/Elev= 30
  4259.2  402.66  4303.7  405.26  4389.8  402.55  4422.1  396.57  4529.7  384.82
  4561.7  374.07  4605.1  364.65  4669.6  358.14  4782.6  351.55  4817.7  347.02
  4896.3  346.96  4931.4  349.62    4995  348.55  5002.5  347.07  5016.7  348.41
  5282.1  346.55  5284.9  346.05  5288.1  346.55  5639.7  347.75  5696.5  349.49
  5837.9  358.62  5845.4  357.51  5866.3  359.35  5873.8  357.48  5923.1  362.23
  6000.9  365.38  6107.1  373.33  6227.5  384.28  6312.8  394.77  6355.8     397
#Mann= 3 ,-1 , 0
  4259.2     .05       0  5282.1     .03       0  5288.1     .05       0
Bank Sta=4995,5016.7
XS Rating Curve= 0 ,0
Exp/Cntr=0.3,0.1

Type RM Length L Ch R = 1 ,21623   ,503,503,503
BEGIN DESCRIPTION:
CANE BRANCH 39.0
END DESCRIPTION:
XS GIS Cut Line= 3
      3619616.39     10515390.12      3620428.88      10515067.2
      3621318.97     10514114.65
#Sta/Elev= 30
  4079.1  406.13  4119.9  405.38  4125.6  403.55  4168.5  403.67  4222.4  395.07
  4341.2  385.28    4468   368.8  4659.6  351.75    4719  348.96    4827  347.03
  4987.3  346.74  5005.3  342.18  5008.1  341.68  5011.3  342.18  5015.6  346.47
    5235  343.27  5241.8   344.9  5355.2  347.05  5376.2  348.82  5383.5  347.69
  5390.3  349.17  5397.7  348.19  5404.5  349.37  5517.8  350.02  5574.5  351.75
  5666.3  350.39    5744  352.54  5836.3  357.41  6090.9  375.46  6257.1  390.94
#Mann= 3 ,-1 , 0
  4079.1     .05       0  5005.3     .03       0  5011.3     .05       0
Bank Sta=4987.3,5015.6
XS Rating Curve= 0 ,0
Exp/Cntr=0.3,0.1

Type RM Length L Ch R = 1 ,21120   ,346,346,346
BEGIN DESCRIPTION:
CANE BRANCH 38.0
END DESCRIPTION:
XS GIS Cut Line= 3
      3620049.63     10515960.17       3620829.5       10515209.
      3621399.58     10514660.22
#Sta/Elev= 30
  3917.2   383.9  3917.4   383.9  3938.4  380.35  3945.3  381.08  3959.5  379.03
  3966.7  376.73  3973.6  377.03  4023.3  369.61  4058.5  366.73  4150.6  362.08
    4200  358.08    4384  349.98  4857.9  344.99  4971.1  345.26  4992.1  342.72
  4993.6  340.63  4996.4  340.13  4999.6  340.63  5002.7  340.63  5006.3  343.87
  5020.4  345.16    5183  342.99  5550.9  342.04  5699.4  357.29  5706.6  359.56
  5727.7  362.06  5741.8  366.89    5756  369.49  5777.3  375.86  5791.3  376.36
#Mann= 4 ,-1 , 0
  3917.2     .16       0  3917.4     .05       0  4993.6     .03       0
  4999.6     .05       0
Bank Sta=4971.1,5020.4
XS Rating Curve= 0 ,0
Exp/Cntr=0.3,0.1

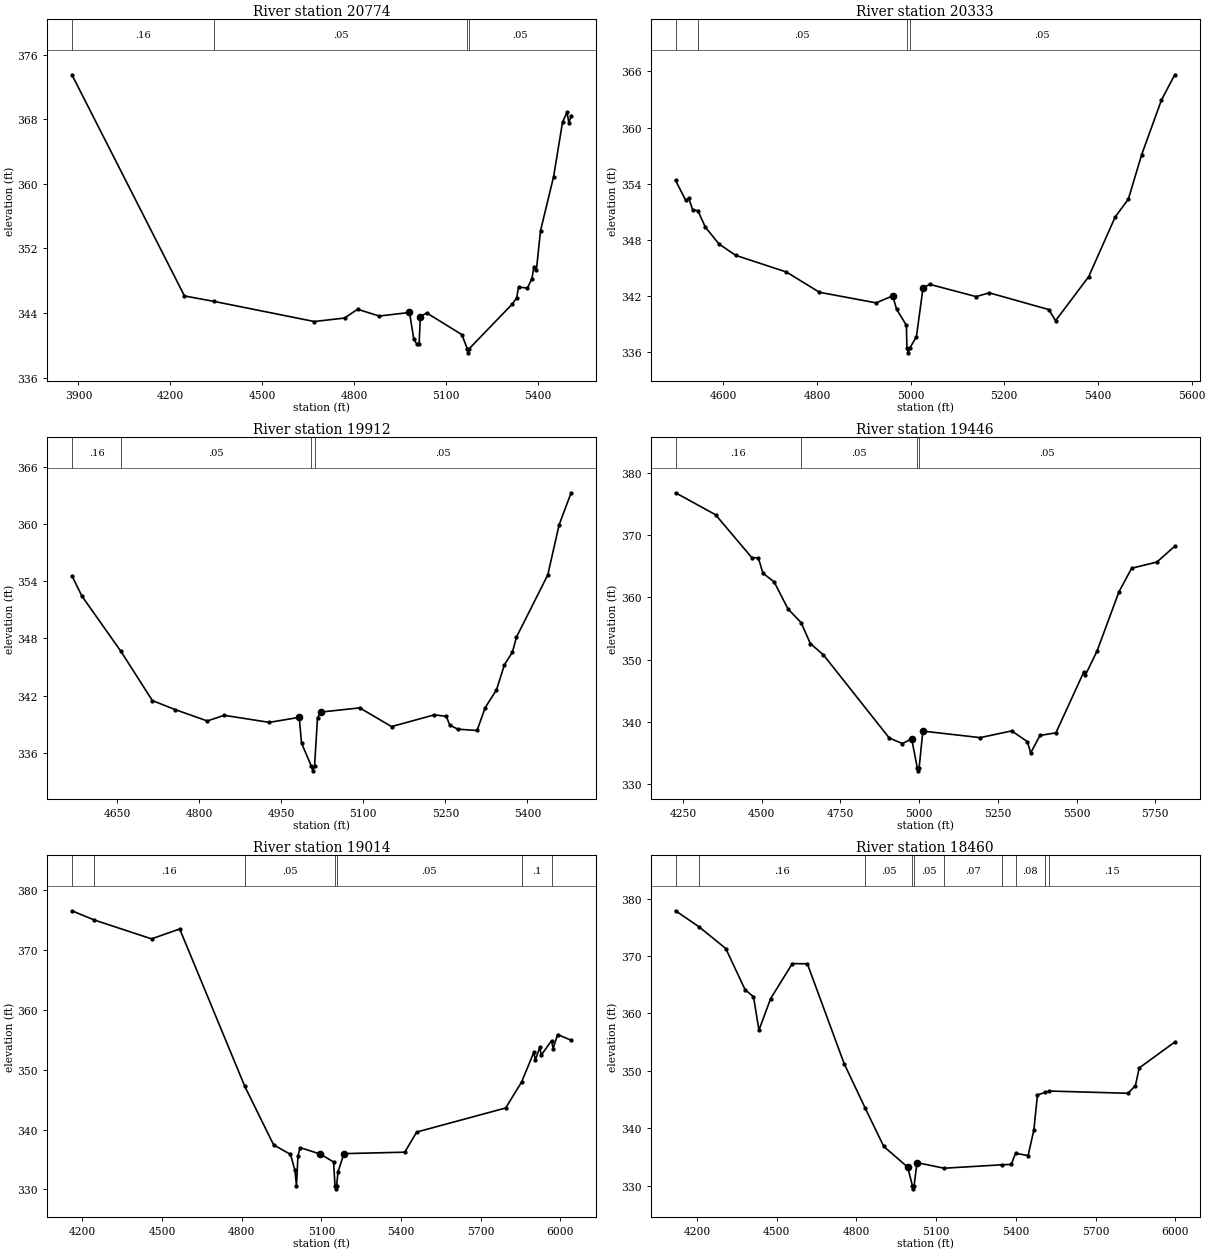
Type RM Length L Ch R = 1 ,20774   ,441,441,441
BEGIN DESCRIPTION:
CANE BRANCH 37.0
END DESCRIPTION:
XS GIS Cut Line= 3
      3620349.63     10516060.17      3621149.61     10515260.19
      3621449.58     10514860.22
#Sta/Elev= 30
  3878.6  373.51  4246.3  346.11  4343.4  345.43  4670.5  342.94  4769.5  343.37
    4812  344.46  4882.7  343.62  4981.7  344.06  4995.8  340.73  5006.4  340.13
  5013.1  340.13  5017.2  343.56  5038.1     344  5152.7  341.32  5170.5  339.56
  5173.2  339.06  5176.5  339.56  5317.2  345.09  5331.8  345.86  5338.1  347.21
  5367.2  347.08  5381.8  348.27  5388.1  349.65  5396.4  349.34  5409.9   354.2
  5452.7   360.9  5481.8  367.65  5496.4  368.85  5502.7  367.53  5509.9  368.45
#Mann= 4 ,-1 , 0
  3878.6     .16       0  4343.4     .05       0  5170.5     .03       0
  5176.5     .05       0
Bank Sta=4981.7,5017.2
XS Rating Curve= 0 ,0
Exp/Cntr=0.3,0.1

Type RM Length L Ch R = 1 ,20333   ,421,421,421
BEGIN DESCRIPTION:
CANE BRANCH 36.0
END DESCRIPTION:
XS GIS Cut Line= 3
      3620999.58     10516060.23      3621299.61     10515660.19
      3621699.59     10515260.21
#Sta/Elev= 30
  4498.2  354.35  4520.1  352.21  4526.4  352.45  4534.7  351.21  4545.8  351.12
  4561.8  349.36    4591  347.56  4626.4  346.35  4734.7  344.57  4805.5   342.4
  4926.4  341.27  4961.8  342.02  4970.1  340.59    4991  338.87  4992.1  336.43
  4994.9  335.93  4998.1  336.43  5012.4  337.64  5026.5  342.86  5040.7  343.25
  5139.7  341.94    5168  342.34  5295.2  340.55  5309.4  339.36  5380.1  344.06
  5436.7  350.44  5464.9  352.36  5493.2  357.09  5535.6  362.95  5563.9  365.64
#Mann= 4 ,-1 , 0
  4498.2     .16       0  4545.8     .05       0  4992.1     .03       0
  4998.1     .05       0
Bank Sta=4961.8,5026.5
XS Rating Curve= 0 ,0
Exp/Cntr=0.3,0.1

Type RM Length L Ch R = 1 ,19912   ,466,466,466
BEGIN DESCRIPTION:
CANE BRANCH 35.0
END DESCRIPTION:
XS GIS Cut Line= 3
      3621449.61      10516360.2      3621549.61     10515960.19
      3621849.59     10515560.21
#Sta/Elev= 30
  4567.6  354.56  4585.7  352.44  4657.2  346.63  4714.5  341.48  4755.7  340.54
    4815  339.34  4845.9  339.93  4928.4  339.19    4983  339.72  4987.2  337.02
    5005  334.61  5007.8  334.11    5011  334.61  5016.4  339.69  5022.6  340.27
  5093.5  340.71  5151.8  338.75  5229.9  339.98  5251.8  339.82    5258  338.91
  5272.6  338.48    5308  338.34  5322.6  340.71  5343.5   342.6    5358  345.23
  5372.6  346.55  5379.9  348.12  5437.2  354.65    5458  359.91  5479.9  363.26
#Mann= 4 ,-1 , 0
  4567.6     .16       0  4657.2     .05       0    5005     .03       0
    5011     .05       0
Bank Sta=4983,5022.6
XS Rating Curve= 0 ,0
Exp/Cntr=0.3,0.1

Type RM Length L Ch R = 1 ,19446   ,432,432,432
BEGIN DESCRIPTION:
CANE BRANCH 34.0
END DESCRIPTION:
XS GIS Cut Line= 3
      3621460.14     10516858.86      3621975.76     10516155.75
      3621923.78     10515443.65
#Sta/Elev= 30
    4226  376.78  4353.2  373.25  4468.2  366.38  4489.1  366.32  4503.7  363.87
  4539.2  362.48  4583.2  358.14  4624.8  355.95  4654.2  352.58  4695.9  350.76
  4905.1  337.41  4946.8  336.53  4976.1  337.29  4993.9  332.65  4996.7  332.15
  4999.9  332.65  5011.6  338.53  5193.7  337.48    5294  338.56  5344.1  336.83
  5354.1  335.01  5383.8  337.83  5434.4  338.25  5522.7  347.99  5527.7  347.49
  5564.7  351.33  5634.9  360.91    5675  364.67  5755.2  365.66  5811.9   368.2
#Mann= 4 ,-1 , 0
    4226     .16       0  4624.8     .05       0  4993.9     .03       0
  4999.9     .05       0
Bank Sta=4976.1,5011.6
XS Rating Curve= 0 ,0
Exp/Cntr=0.3,0.1

Type RM Length L Ch R = 1 ,19014   ,554,554,554
BEGIN DESCRIPTION:
CANE BRANCH 33.0
END DESCRIPTION:
XS GIS Cut Line= 3
      3621611.19     10517155.73      3622199.61     10516560.19
      3623132.01     10516093.24
#Sta/Elev= 30
  4160.6  376.53  4243.5  375.01  4460.4  371.84  4566.4  373.49  4811.8  347.19
    4920  337.45  4983.7  335.85  5000.6  333.17  5006.2  330.63  5011.8  335.62
  5020.2  336.98  5095.6  335.91  5145.9  334.59  5151.4   330.6  5154.1   330.1
  5157.4   330.6  5162.6  332.93    5185  335.98  5414.1  336.22  5458.8  339.58
    5794   343.6  5853.9  347.92  5900.2  352.91  5905.8  351.61  5922.5  353.74
  5928.1  352.42  5966.7  354.84  5972.8  353.53  5989.6  355.87  6040.6  354.91
#Mann= 7 ,-1 , 0
  4160.6     .05       0  4243.5     .16       0  4811.8     .05       0
  5151.4     .03       0  5157.4     .05       0  5853.9      .1       0
  5966.7     .15       0
Bank Sta=5095.6,5185
XS Rating Curve= 0 ,0
Exp/Cntr=0.3,0.1

Type RM Length L Ch R = 1 ,18460   ,495,495,495
BEGIN DESCRIPTION:
CANE BRANCH 32.0
END DESCRIPTION:
XS GIS Cut Line= 3
      3621668.45     10517275.54      3622496.59     10517030.75
       3623173.7      10516275.5
#Sta/Elev= 30
    4120  377.87    4208  375.09  4308.9   371.3  4381.9   364.1  4413.2  362.91
  4433.8  357.09  4477.5  362.56  4559.2  368.67  4615.8  368.64  4754.2  351.26
    4834  343.45  4903.3  336.83  4993.3  333.23  5011.2  329.95    5014  329.45
  5017.2  329.95  5028.4  334.01  5130.7  333.04  5347.4  333.64  5382.8   333.7
  5399.1  335.64  5446.3  335.24  5467.8  339.68  5481.5  345.81  5510.2  346.23
  5526.4  346.48  5821.6  346.09    5850  347.42  5864.2   350.5  5997.9  355.01
#Mann= 10 ,-1 , 0
    4120     .05       0    4208     .16       0    4834     .05       0
  5011.2     .03       0  5017.2     .05       0  5130.7     .07       0
  5347.4     .05       0  5399.1     .08       0  5510.2      .1       0
  5526.4     .15       0
Bank Sta=4993.3,5028.4
XS Rating Curve= 0 ,0
Exp/Cntr=0.3,0.1