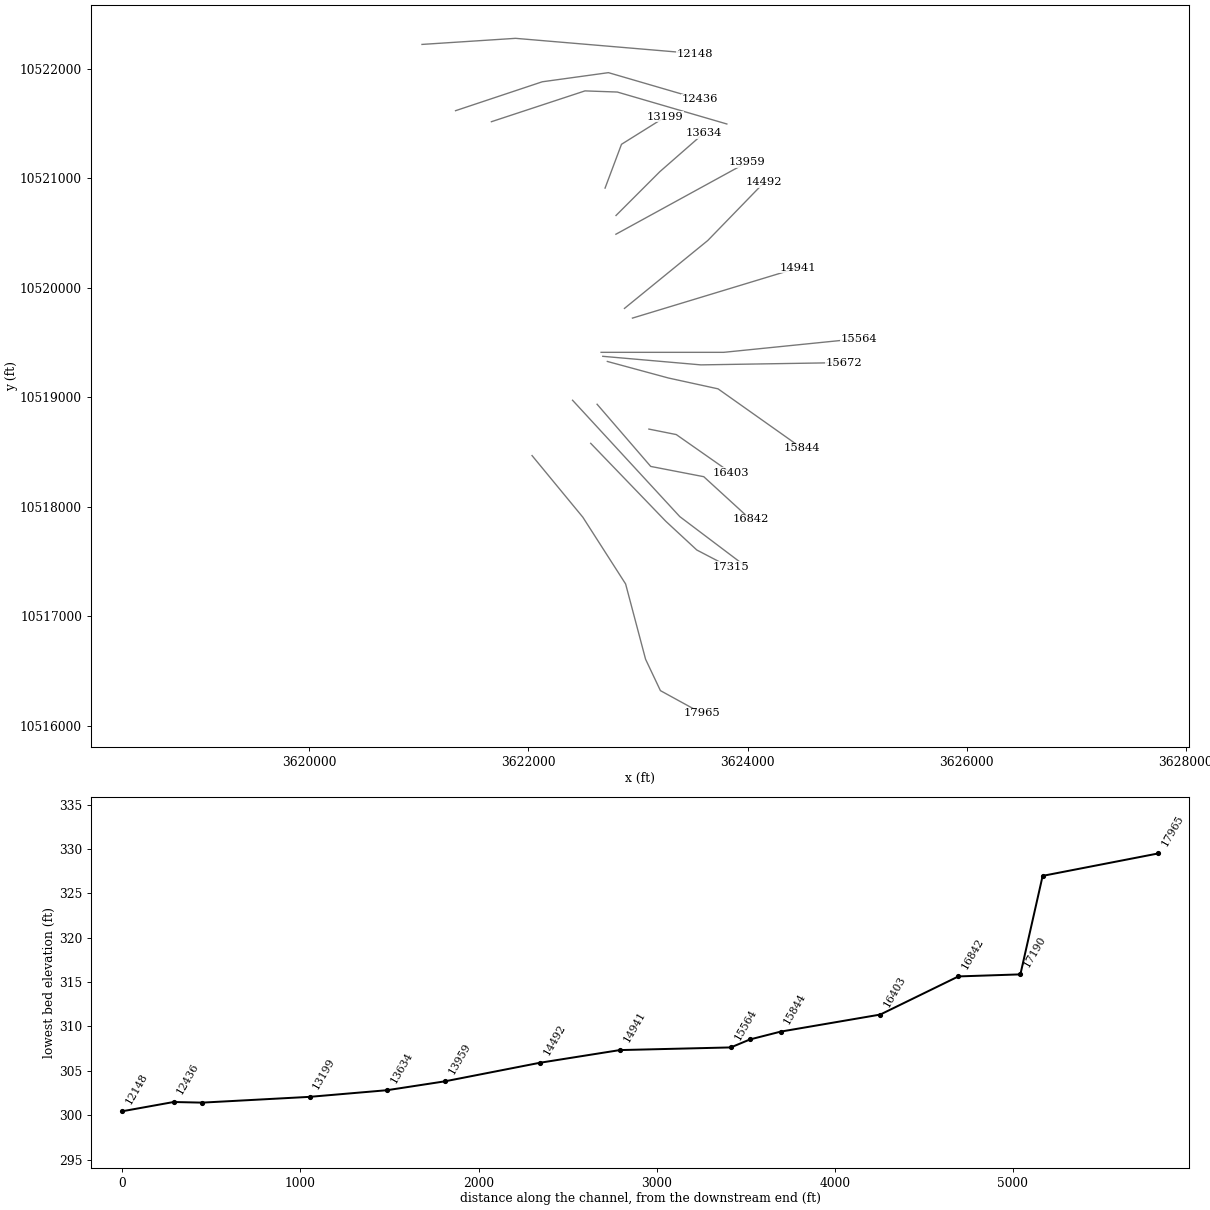
HEC-RAS study CANE BRANCH.prj: CANE BRANCH Base Level Engineering

--- CANE BRANCH.g01 (geometry) --- (continued)

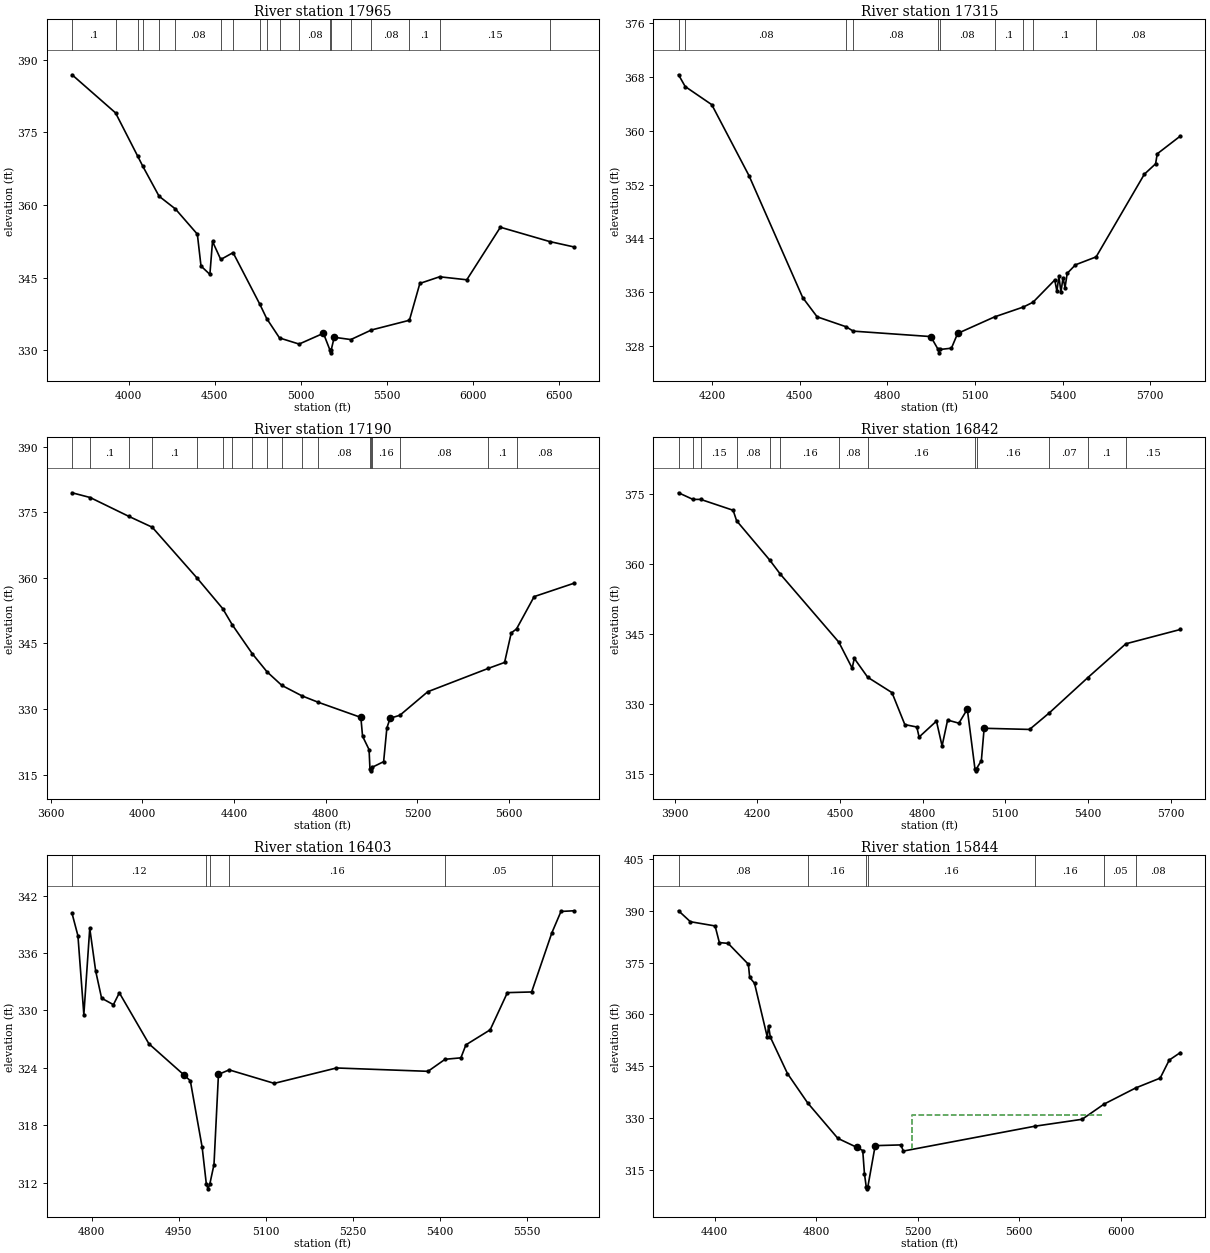
Type RM Length L Ch R = 1 ,17965   ,650,650,650
BEGIN DESCRIPTION:
CANE BRANCH 30.0
END DESCRIPTION:
XS GIS Cut Line= 6
      3622033.05     10518468.25      3622496.59     10517905.75
      3622887.21     10517296.37      3623069.51     10516608.87
      3623204.92     10516322.41      3623583.84     10516114.79
#Sta/Elev= 30
  3671.4  386.86  3923.8     379  4053.3  370.01  4082.8  367.94  4176.5  361.81
  4271.4  359.18  4398.7  353.98  4419.9  347.41  4471.5  345.68  4486.7  352.47
  4534.7  348.76  4606.1  350.17  4762.1  339.48  4801.2  336.58  4875.8  332.57
  4989.5  331.31  5130.6  333.53  5169.3     330    5172   329.5  5175.3     330
  5193.2  332.71  5289.9  332.24    5409  334.21  5629.9  336.22  5690.5  343.82
  5805.2  345.19    5963  344.57    6158  355.41    6444  352.46  6584.6  351.35
#Mann= 19 ,-1 , 0
  3671.4      .1       0  3923.8     .08       0  4053.3     .05       0
  4082.8     .08       0  4176.5     .16       0  4271.4     .08       0
  4534.7     .05       0  4606.1     .08       0  4762.1     .16       0
  4801.2     .08       0  4875.8     .05       0  4989.5     .08       0
  5169.3     .07       0  5175.3     .08       0  5289.9     .05       0
    5409     .08       0  5629.9      .1       0  5805.2     .15       0
    6444      .1       0
Bank Sta=5130.6,5193.2
XS Rating Curve= 0 ,0
Exp/Cntr=0.3,0.1

Type RM Length L Ch R = 1 ,17315   ,125,125,125
BEGIN DESCRIPTION:
Mapping XS 0323b22a
END DESCRIPTION:
XS GIS Cut Line= 5
      3622568.53     10518580.16      3623253.44     10517869.21
      3623537.29     10517606.19      3623782.08     10517478.58
      3623844.55     10517452.55
#Sta/Elev= 30
  4085.4  368.35  4108.2   366.6  4199.2   363.9  4326.6  353.34  4510.5  335.19
  4559.9  332.33  4658.5  330.86  4683.6   330.2  4948.9  329.39  4974.2  327.47
  4976.9  326.97  4980.2  327.47  5019.6  327.66    5041  329.86  5167.3  332.32
    5266  333.79    5299   334.5  5373.4  337.81  5380.8  336.15  5387.6  338.37
  5394.6  336.01  5401.8  338.15  5408.6  336.68    5416   338.8  5444.3  340.07
  5515.1  341.25  5680.1  353.55  5718.6   355.1  5724.3  356.59  5803.3  359.23
#Mann= 10 ,-1 , 0
  4085.4      .1       0  4108.2     .08       0  4658.5      .1       0
  4683.6     .08       0  4974.2     .07       0  4980.2     .08       0
  5167.3      .1       0    5266     .08       0    5299      .1       0
  5515.1     .08       0
Bank Sta=4948.9,5041
XS Rating Curve= 0 ,0
Exp/Cntr=0.3,0.1

Type RM Length L Ch R = 1 ,17190   ,348,348,348
BEGIN DESCRIPTION:
CANE BRANCH 29.0
END DESCRIPTION:
XS GIS Cut Line= 3
      3622402.83     10518973.46      3623382.01     10517910.95
      3623975.72     10517463.06
#Sta/Elev= 30
  3693.8  379.47  3772.5  378.39  3941.6  374.07  4043.5  371.59  4239.4  359.94
  4350.9  352.97  4391.7  349.34  4479.7  342.67  4544.1  338.52  4608.5  335.42
  4696.5  333.02  4767.2  331.56  4953.4  328.09  4960.8  323.79  4989.2  320.72
    4993  316.37  4995.7  315.87    4999  316.37  5001.2  316.64  5052.7  317.97
  5066.8  325.67    5081   327.9  5123.6  328.58    5245  333.96  5509.4  339.31
  5580.2  340.66  5609.3  347.42  5632.3  348.32  5709.2  355.72  5882.4  358.77
#Mann= 18 ,-1 , 0
  3693.8     .08       0  3772.5      .1       0  3941.6     .15       0
  4043.5      .1       0  4239.4     .05       0  4350.9     .08       0
  4391.7     .05       0  4479.7     .08       0  4544.1     .05       0
  4608.5     .08       0  4696.5     .05       0  4767.2     .08       0
    4993     .07       0    4999     .08       0  5001.2     .16       0
  5123.6     .08       0  5509.4      .1       0  5632.3     .08       0
Bank Sta=4953.4,5081
XS Rating Curve= 0 ,0
Exp/Cntr=0.3,0.1

Type RM Length L Ch R = 1 ,16842   ,439,439,439
BEGIN DESCRIPTION:
CANE BRANCH 28.0
END DESCRIPTION:
XS GIS Cut Line= 4
       3622626.8     10518936.99      3623116.38     10518369.29
      3623600.76     10518275.54      3624027.69     10517885.05
#Sta/Elev= 30
  3913.9  375.28  3966.2  373.86  3994.3  373.86    4112  371.53  4124.8  369.27
    4245  360.84  4283.4  357.83  4495.7  343.25  4544.2  337.66  4551.9  339.76
  4600.6  335.71  4688.7  332.42  4735.4  325.56  4778.9  325.04  4787.2  322.89
  4850.2  326.31  4870.6  320.97  4890.7  326.53  4931.7  325.86  4962.2  328.87
  4989.8  316.14  4992.5  315.64  4995.8  316.14  5013.2  317.82  5023.3  324.77
  5188.2  324.52  5259.9  328.07  5398.8  335.59  5537.8  342.89  5735.5  345.96
#Mann= 13 ,-1 , 0
  3913.9      .1       0  3966.2     .08       0  3994.3     .15       0
  4124.8     .08       0    4245     .05       0  4283.4     .16       0
  4495.7     .08       0  4600.6     .16       0  4989.8     .07       0
  4995.8     .16       0  5259.9     .07       0  5398.8      .1       0
  5537.8     .15       0
Bank Sta=4962.2,5023.3
XS Rating Curve= 0 ,0
Exp/Cntr=0.3,0.1

Type RM Length L Ch R = 1 ,16403   ,559,559,559
BEGIN DESCRIPTION:
CANE BRANCH 27.0
END DESCRIPTION:
XS GIS Cut Line= 3
      3623099.66     10518710.18      3623349.61     10518660.19
      3623849.59     10518310.21
#Sta/Elev= 30
    4766  340.14  4776.1  337.81  4786.3  329.56  4796.5  338.59  4806.7  334.12
  4816.9  331.28  4837.3   330.6  4847.5  331.84  4898.5  326.51  4959.7  323.21
  4969.9  322.64  4990.3  315.69  4997.5  311.84  5000.3  311.34  5003.5  311.84
  5010.7  313.88  5018.4  323.31  5036.9  323.78  5114.6  322.37  5221.9  323.98
  5379.7  323.63  5409.2  324.89  5436.4  325.04  5445.1   326.4  5486.9  327.97
  5516.6  331.86  5558.4  331.93  5593.3  338.12    5609  340.35  5631.2  340.42
#Mann= 6 ,-1 , 0
    4766     .12       0  4997.5     .07       0  5003.5     .12       0
  5036.9     .16       0  5409.2     .05       0  5593.3      .1       0
Bank Sta=4959.7,5018.4
XS Rating Curve= 0 ,0
Exp/Cntr=0.3,0.1

Type RM Length L Ch R = 1 ,15844   ,172,172,172
BEGIN DESCRIPTION:
CANE BRANCH 26.0
END DESCRIPTION:
XS GIS Cut Line= 4
      3622720.53     10519327.63      3623277.84     10519176.58
      3623730.96     10519077.62      3624495.62     10518536.64
#Sta/Elev= 30
  4257.5  390.07  4304.1   386.9  4401.6  385.67  4418.4  380.85  4453.1  380.61
  4532.8  374.56  4537.9  370.76    4557  369.04  4607.3  353.45  4612.4  356.72
  4619.2  353.45  4686.9  342.85  4766.6  334.33  4885.5  324.06  4959.6  321.48
  4983.6  320.53  4990.3  313.81  4997.5  309.92  5000.2  309.42  5003.5  309.92
  5032.6  321.95  5133.6  322.16  5143.8  320.38  5662.5  327.59  5848.3  329.59
  5934.8     334  6059.4  338.68    6156  341.54  6191.7  346.77  6235.4  348.94
#Mann= 7 ,-1 , 0
  4257.5     .08       0  4766.6     .16       0  4997.5     .07       0
  5003.5     .16       0  5662.5     .16       0  5934.8     .05       0
  6059.4     .08       0
#XS Ineff= 1 ,-1
 5178.98 5924.72   330.8
Permanent Ineff=
       F
Bank Sta=4959.6,5032.6
XS Rating Curve= 0 ,0
Exp/Cntr=0.3,0.1

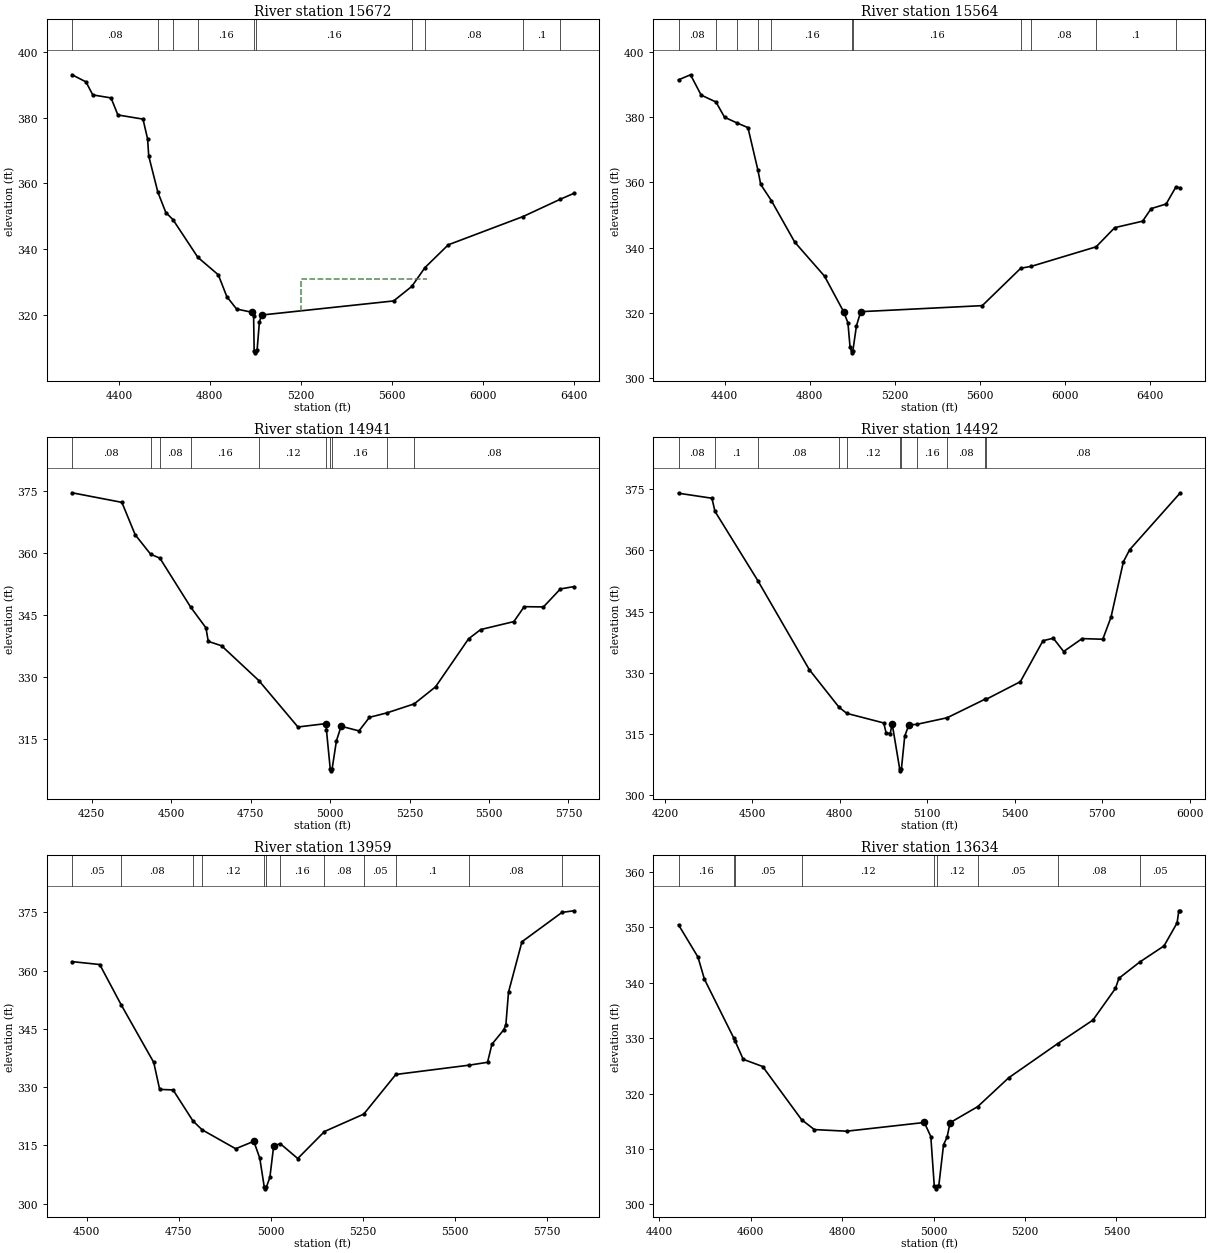
Type RM Length L Ch R = 1 ,15672   ,108,108,108
BEGIN DESCRIPTION:
Mapping XS 8cd49d51
END DESCRIPTION:
XS GIS Cut Line= 3
      3622678.85      10519374.5      3623574.71     10519296.37
      3624881.98      10519317.2
#Sta/Elev= 30
  4194.1  393.03  4255.1  390.88  4285.2  386.91  4365.5     386  4395.6  380.82
    4506  379.56  4526.1  373.57  4531.3  368.32  4571.4  357.35  4606.4  351.18
  4637.8  349.02    4747  337.58  4837.3  332.24  4874.6  325.63  4917.6  321.85
  4987.4  320.84  4992.4  319.75  4994.9  309.04  4997.7  308.54  5000.9  309.04
  5007.9  309.45    5018  317.98    5028  320.03  5608.3  324.31  5688.3  328.74
  5745.7  334.42  5848.4  341.36  6177.2  349.95  6341.1  355.21  6400.8     357
#Mann= 10 ,-1 , 0
  4194.1     .08       0  4571.4      .1       0  4637.8     .08       0
    4747     .16       0  4994.9     .07       0  5000.9     .16       0
  5688.3     .05       0  5745.7     .08       0  6177.2      .1       0
  6341.1     .08       0
#XS Ineff= 1 ,-1
  5201.7  5757.1  331.05
Permanent Ineff=
       F
Bank Sta=4987.4,5028
XS Rating Curve= 0 ,0
Exp/Cntr=0.3,0.1

Type RM Length L Ch R = 1 ,15564   ,623,623,623
BEGIN DESCRIPTION:
CANE BRANCH 25.0
END DESCRIPTION:
XS GIS Cut Line= 3
      3622663.28     10519410.95      3623783.05     10519410.95
      3625015.97     10519535.81
#Sta/Elev= 30
  4182.6  391.56  4238.9  393.11  4288.9  386.87  4358.6  384.74  4398.9  380.06
  4456.8  378.32  4508.9  376.87  4555.7  363.82  4568.9  359.41  4618.9  354.44
  4728.9  341.67  4868.9  331.21  4958.9  320.26  4978.9  316.86  4988.9  309.44
  4995.9  308.14  4998.7  307.64  5001.9  308.14  5018.9   315.9  5038.9  320.29
  5610.5  322.15  5791.4  333.64  5841.7  334.24  6145.8  340.23  6233.2  346.12
  6364.3  348.11  6404.5  351.97  6474.9  353.39  6520.1  358.55  6541.6  358.38
#Mann= 11 ,-1 , 0
  4182.6     .08       0  4358.6      .1       0  4456.8     .15       0
  4555.7      .1       0  4618.9     .16       0  4995.9     .07       0
  5001.9     .16       0  5791.4     .16       0  5841.7     .08       0
  6145.8      .1       0  6520.1     .08       0
Bank Sta=4958.9,5038.9
XS Rating Curve= 0 ,0
Exp/Cntr=0.3,0.1

Type RM Length L Ch R = 1 ,14941   ,449,449,449
BEGIN DESCRIPTION:
CANE BRANCH 24.0
END DESCRIPTION:
XS GIS Cut Line= 2
      3622949.67     10519723.44      3624460.16      10520181.8
#Sta/Elev= 30
  4188.5  374.67  4345.2  372.35    4387  364.51  4435.7  359.79  4464.7  358.84
  4561.5  346.99  4609.7  341.96  4616.9  338.69  4658.7  337.63    4776   329.2
    4899  317.96  4987.2  318.78  4988.7  317.22  5000.6  307.84  5003.3  307.34
  5006.6  307.84  5020.1   314.6  5034.9  318.14  5091.1  317.01    5124   320.3
  5178.7  321.37  5264.7  323.55  5331.9  327.68  5435.8  339.31  5473.9  341.55
  5578.3  343.48  5610.7  347.09  5671.3  347.03  5724.6  351.38    5767  351.95
#Mann= 10 ,-1 , 0
  4188.5     .08       0  4435.7      .1       0  4464.7     .08       0
  4561.5     .16       0    4776     .12       0  4988.7     .16       0
  5000.6     .07       0  5006.6     .16       0  5178.7     .05       0
  5264.7     .08       0
Bank Sta=4987.2,5034.9
XS Rating Curve= 0 ,0
Exp/Cntr=0.3,0.1

Type RM Length L Ch R = 1 ,14492   ,533,533,533
BEGIN DESCRIPTION:
CANE BRANCH 23.0
END DESCRIPTION:
XS GIS Cut Line= 3
      3622876.77     10519811.97      3623637.21     10520431.79
      3624152.86     10520963.05
#Sta/Elev= 30
  4246.8  374.05  4361.4  372.82  4371.7  369.61  4518.9  352.58  4695.3  330.76
  4797.6   321.5  4824.2  320.01  4950.9  317.66  4958.9  315.21  4972.9  315.07
  4979.7  317.44  5005.4  306.41  5008.1  305.91  5011.4  306.41  5022.8  314.44
  5037.1   317.2  5063.2  317.31  5168.4  318.94  5298.7  323.51  5301.4  323.44
  5419.4  327.79  5497.1  337.85  5532.4  338.46  5567.9   335.2  5631.4  338.37
  5702.2  338.21  5730.4  343.62  5772.9  357.23  5794.2  360.16  5968.2  374.16
#Mann= 11 ,-1 , 0
  4246.8     .08       0  4371.7      .1       0  4518.9     .08       0
  4797.6     .05       0  4824.2     .12       0  5005.4     .07       0
  5011.4     .12       0  5063.2     .16       0  5168.4     .08       0
  5298.7     .05       0  5301.4     .08       0
Bank Sta=4979.7,5037.1
XS Rating Curve= 0 ,0
Exp/Cntr=0.3,0.1

Type RM Length L Ch R = 1 ,13959   ,325,325,325
BEGIN DESCRIPTION:
CANE BRANCH 22.0
END DESCRIPTION:
XS GIS Cut Line= 2
      3622798.67     10520489.08      3623995.45     10521144.71
#Sta/Elev= 30
  4459.8  362.29    4535  361.54  4593.3  351.18  4681.9  336.35    4698  329.41
  4734.5  329.27  4788.5   321.3  4813.2  319.03  4904.7  314.14    4954  316.05
  4970.2  311.74  4982.4  304.32  4985.1  303.82  4988.4  304.32  4997.7  306.77
  5008.1  314.87    5026  315.44  5073.5  311.62  5146.2  318.57    5253  323.05
  5340.3  333.25    5540  335.65  5589.7  336.38  5601.6  341.03  5633.8  344.75
  5639.5  346.06  5646.7  354.44  5683.2   367.4  5792.3  374.96  5824.4  375.37
#Mann= 12 ,-1 , 0
  4459.8     .05       0  4593.3     .08       0  4788.5     .05       0
  4813.2     .12       0  4982.4     .07       0  4988.4     .12       0
    5026     .16       0  5146.2     .08       0    5253     .05       0
  5340.3      .1       0    5540     .08       0  5792.3     .05       0
Bank Sta=4954,5008.1
XS Rating Curve= 0 ,0
Exp/Cntr=0.3,0.1

Type RM Length L Ch R = 1 ,13634   ,435,435,435
BEGIN DESCRIPTION:
CANE BRANCH 21.0
END DESCRIPTION:
XS GIS Cut Line= 3
       3622799.6     10520660.18      3623199.61     10521060.19
      3623599.61     10521410.19
#Sta/Elev= 30
  4442.5   350.4  4484.9  344.61  4499.1  340.61  4563.7  329.93    4566  329.49
  4583.9  326.17  4626.4  324.87  4711.6  315.28  4739.5   313.5  4810.2  313.21
  4979.9  314.78  4994.1  312.25  5001.7  303.32  5004.4  302.82  5007.7  303.32
  5011.5  303.32    5022  310.79  5029.6   312.1  5036.2  314.74  5096.7  317.64
  5164.3  322.83  5271.5  328.99  5348.5  333.23  5397.8  338.94  5405.4  340.77
  5450.8  343.69  5504.1  346.61  5532.6  350.75  5536.4  352.94  5539.7  352.94
#Mann= 9 ,-1 , 0
  4442.5     .16       0  4563.7     .08       0    4566     .05       0
  4711.6     .12       0  5001.7     .07       0  5007.7     .12       0
  5096.7     .05       0  5271.5     .08       0  5450.8     .05       0
Bank Sta=4979.9,5036.2
XS Rating Curve= 0 ,0
Exp/Cntr=0.3,0.1

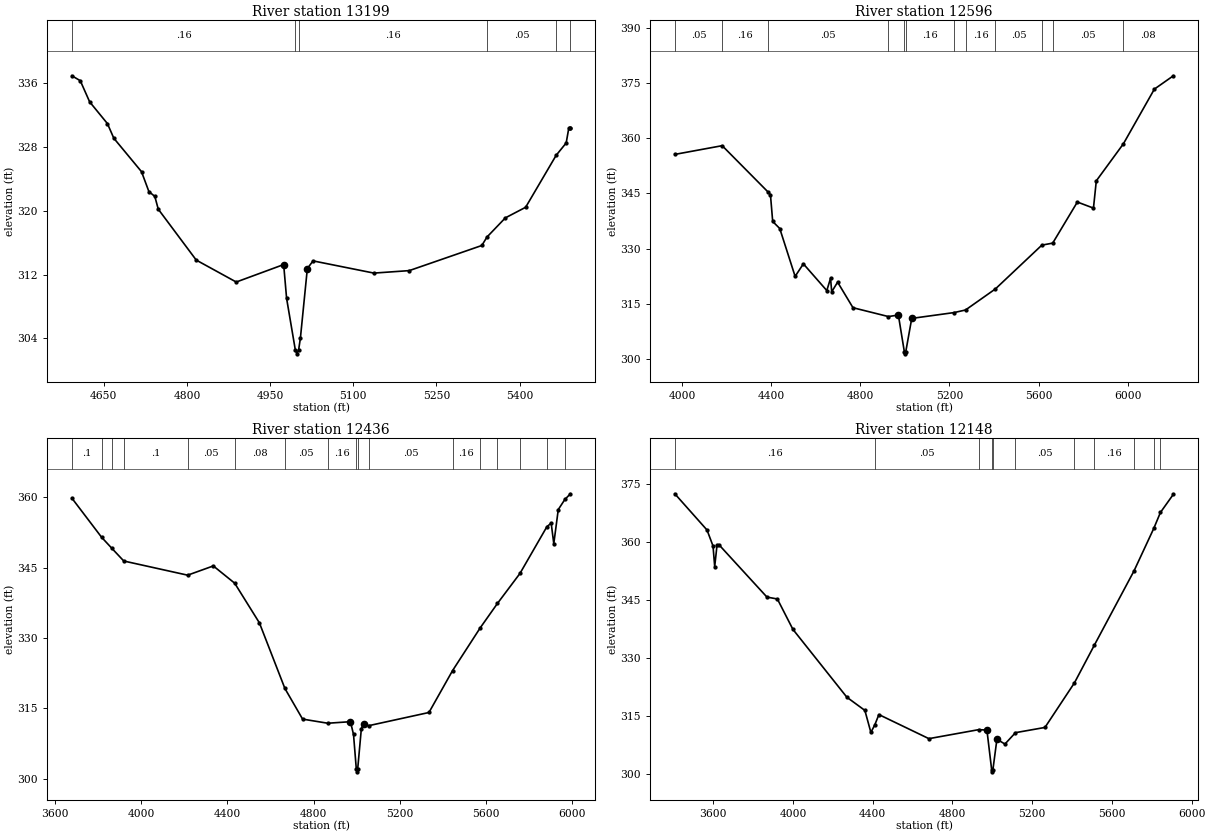
Type RM Length L Ch R = 1 ,13199   ,603,603,603
BEGIN DESCRIPTION:
CANE BRANCH 20.0
END DESCRIPTION:
XS GIS Cut Line= 3
      3622699.62     10520910.22      3622849.61     10521310.19
      3623249.64     10521560.21
#Sta/Elev= 30
  4592.7  336.92  4607.8   336.3  4624.7  333.65  4656.7  330.93  4668.3  329.09
  4718.2   324.9  4731.5  322.41  4742.2   321.8  4748.4   320.2  4816.9  313.82
    4889  311.07  4974.5  313.26  4979.8  309.02  4995.5  302.57  4998.3  302.07
  5001.5  302.57  5004.7  304.05  5017.2  312.76  5027.5  313.72  5137.2  312.19
  5200.9   312.5  5331.8  315.65  5341.1  316.71  5374.2  319.11  5410.8  320.44
  5465.8  326.95  5483.9   328.5  5488.6  330.36  5490.8  330.36  5491.6  330.36
#Mann= 6 ,-1 , 0
  4592.7     .16       0  4995.5     .07       0  5001.5     .16       0
  5341.1     .05       0  5465.8     .16       0  5490.8     .05       0
Bank Sta=4974.5,5017.2
XS Rating Curve= 0 ,0
Exp/Cntr=0.3,0.1

Type RM Length L Ch R = 1 ,12596   ,160,160,160
BEGIN DESCRIPTION:
CANE BRANCH 19.0
END DESCRIPTION:
XS GIS Cut Line= 4
      3621662.01     10521516.41      3622516.21     10521797.67
      3622811.35     10521787.26      3623811.35     10521495.59
#Sta/Elev= 30
    3968   355.6  4180.5  357.97    4386   345.4  4397.1   344.6  4407.1  337.38
  4438.8  335.46  4507.7  322.46  4544.7  325.87  4649.8  318.61  4666.6  321.95
  4671.8  318.28  4698.3  320.89  4767.2  313.95    4926  311.55  4970.8  311.96
  4997.8  301.92  5000.5  301.42  5003.8  301.92  5030.8  311.05  5220.8  312.63
    5272  313.33    5406  319.05  5614.4  330.95  5663.1   331.5  5773.7  342.66
  5845.9  341.01  5858.7  348.42  5980.1  358.47  6119.2  373.34  6204.3  376.96
#Mann= 12 ,-1 , 0
    3968     .05       0  4180.5     .16       0    4386     .05       0
    4926     .16       0  4997.8     .07       0  5003.8     .16       0
  5220.8     .05       0    5272     .16       0    5406     .05       0
  5614.4     .08       0  5663.1     .05       0  5980.1     .08       0
Bank Sta=4970.8,5030.8
XS Rating Curve= 0 ,0
Exp/Cntr=0.3,0.1

Type RM Length L Ch R = 1 ,12436   ,288,288,288
BEGIN DESCRIPTION:
Mapping XS 08a8d1f1
END DESCRIPTION:
XS GIS Cut Line= 4
      3621334.69     10521616.99      3622126.37     10521880.88
      3622730.53     10521964.21      3623563.82     10521721.17
#Sta/Elev= 30
    3679  359.82  3816.7  351.49  3864.4  349.13  3919.6  346.43  4215.8  343.41
  4334.9  345.38    4434   341.7  4548.6  333.25  4666.9  319.26    4749  312.73
  4865.8  311.85    4971  312.18  4985.2  309.45  4998.3  301.99  5001.1  301.49
  5004.3  301.99  5021.5  310.69  5031.6  311.72  5055.6  311.33  5335.1  314.14
  5444.6  323.07  5573.1   332.2    5653   337.4  5757.2  343.78  5882.1  353.74
    5902   354.5  5914.1  350.12  5934.9   357.4  5965.6  359.56  5991.4  360.76
#Mann= 17 ,-1 , 0
    3679      .1       0  3816.7     .05       0  3864.4     .16       0
  3919.6      .1       0  4215.8     .05       0    4434     .08       0
  4666.9     .05       0  4865.8     .16       0  4998.3     .07       0
  5004.3     .16       0  5055.6     .05       0  5444.6     .16       0
  5573.1     .05       0    5653     .16       0  5757.2     .05       0
  5882.1     .08       0  5965.6     .05       0
Bank Sta=4971,5031.6
XS Rating Curve= 0 ,0
Exp/Cntr=0.3,0.1

Type RM Length L Ch R = 1 ,12148   ,834,834,834
BEGIN DESCRIPTION:
CANE BRANCH 18.0
END DESCRIPTION:
XS GIS Cut Line= 3
      3621028.34     10522221.98      3621882.53     10522277.53
      3623521.46     10522138.64
#Sta/Elev= 30
  3407.4  372.42    3569  363.04  3599.1  358.91  3607.5  353.59  3619.1  359.09
  3629.1  359.22  3869.6  345.68  3921.9  345.19  3999.9  337.32  4270.5  319.76
  4360.8  316.35  4390.9  310.66  4410.2  312.56  4431.1  315.27    4682  309.04
  4931.9  311.37    4973  311.26  4996.9  300.95  4999.7  300.45  5002.9  300.95
  5023.2  308.89  5063.3  307.64  5116.3  310.59  5264.1  311.94  5411.9  323.47
  5511.5   333.2  5710.6  352.43  5810.2  363.48  5843.3  367.58  5908.2  372.28
#Mann= 11 ,-1 , 0
  3407.4     .16       0  4410.2     .05       0  4931.9     .16       0
  4996.9     .07       0  5002.9     .16       0  5116.3     .05       0
  5411.9     .08       0  5511.5     .16       0  5710.6     .05       0
  5810.2     .08       0  5843.3     .05       0
Bank Sta=4973,5023.2
XS Rating Curve= 0 ,0
Exp/Cntr=0.3,0.1