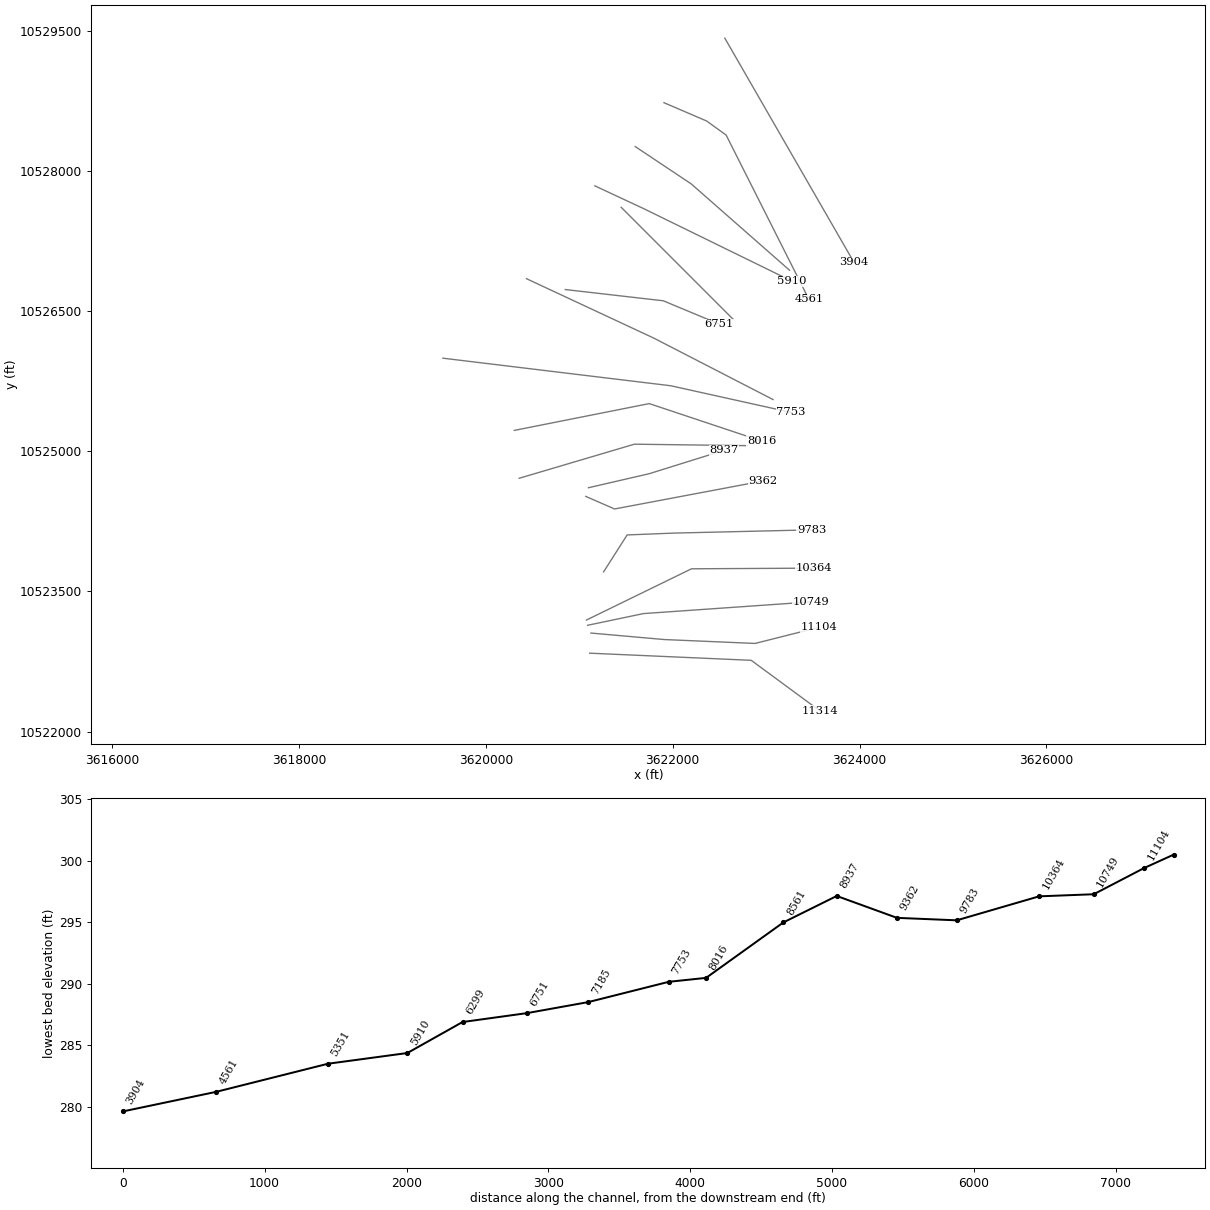
HEC-RAS study CANE BRANCH.prj: CANE BRANCH Base Level Engineering

--- CANE BRANCH.g01 (geometry) --- (continued)

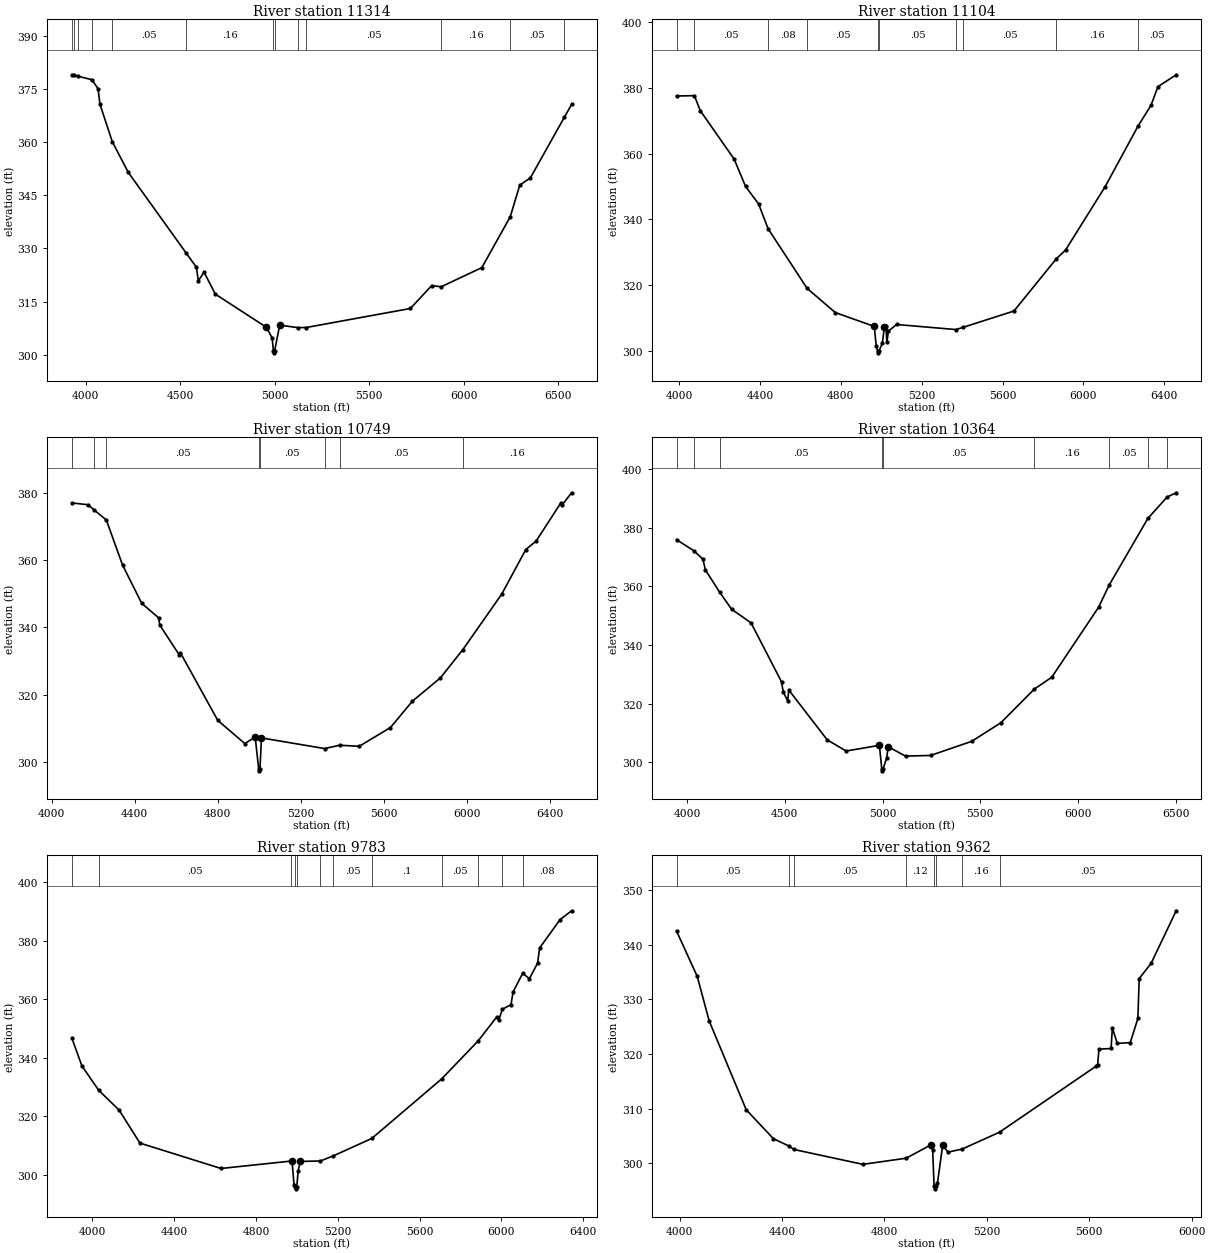
Type RM Length L Ch R = 1 ,11314   ,210,210,210
BEGIN DESCRIPTION:
CANE BRANCH 17.0
END DESCRIPTION:
XS GIS Cut Line= 3
      3621111.66     10522840.04      3622840.86     10522763.65
      3623575.83     10522222.82
#Sta/Elev= 30
  3928.2   379.1  3939.1  378.97  3960.7  378.68  4034.1  377.71  4066.3  375.15
  4076.3  370.78  4141.3  360.21  4226.4  351.48    4534  328.59  4586.8  324.68
  4596.8   320.8  4626.8   323.3  4686.9  317.08  4957.2  307.71  4987.2  304.69
  4994.2  300.99  4996.9  300.49  5000.2  300.99  5027.2  308.32    5123  307.62
  5167.1  307.65  5718.7  313.03  5831.4  319.49  5881.5  319.17  6096.7  324.58
    6247  338.96  6297.3  347.89  6353.6  349.96    6533  367.07  6571.6  370.73
#Mann= 13 ,-1 , 0
  3928.2      .1       0  3939.1     .08       0  3960.7     .05       0
  4034.1     .16       0  4141.3     .05       0    4534     .16       0
  4994.2     .07       0  5000.2     .16       0    5123     .08       0
  5167.1     .05       0  5881.5     .16       0    6247     .05       0
    6533     .08       0
Bank Sta=4957.2,5027.2
XS Rating Curve= 0 ,0
Exp/Cntr=0.3,0.1

Type RM Length L Ch R = 1 ,11104   ,355,355,355
BEGIN DESCRIPTION:
CANE BRANCH 16.0
END DESCRIPTION:
XS GIS Cut Line= 4
      3621125.54     10523055.32      3621910.31     10522985.87
      3622882.53      10522944.2        3623570.     10523117.81
#Sta/Elev= 30
  3988.3  377.54  4076.4  377.65  4105.5   373.1  4273.5  358.29  4329.4  350.03
  4393.9   344.7  4440.8  337.17  4633.8     319  4773.3  311.64  4965.6  307.43
  4975.6  301.47  4982.6  299.89  4985.4  299.39  4988.6  299.89  5005.6  302.29
  5015.7  307.26  5023.1   307.7  5028.1  302.65  5035.7  305.99  5075.7  308.02
  5369.8  306.47  5404.8  307.15  5656.2  312.11  5866.3  328.05  5911.3  330.67
  6107.2  349.96  6270.2  368.44  6334.1  374.74  6368.1  380.39  6458.3     384
#Mann= 10 ,-1 , 0
  3988.3      .1       0  4076.4     .05       0  4440.8     .08       0
  4633.8     .05       0  4982.6     .03       0  4988.6     .05       0
  5369.8     .08       0  5404.8     .05       0  5866.3     .16       0
  6270.2     .05       0
Bank Sta=4965.6,5015.7
XS Rating Curve= 0 ,0
Exp/Cntr=0.3,0.1

Type RM Length L Ch R = 1 ,10749   ,385,385,385
BEGIN DESCRIPTION:
CANE BRANCH 15.0
END DESCRIPTION:
XS GIS Cut Line= 3
      3621090.82     10523138.64      3621688.08     10523263.65
      3623479.73     10523388.64
#Sta/Elev= 30
  4097.7  377.07  4175.8  376.53  4204.9  374.97  4263.3  371.99  4341.7  358.52
  4433.6  347.17  4515.2  342.83  4520.3  340.73  4615.1  331.74  4620.2  332.41
  4799.6  312.32    4930  305.39  4980.1  307.31  4997.1  297.76  4999.9  297.26
  5003.1  297.76  5010.2  307.07  5314.3   303.9  5387.4  304.89  5481.3  304.58
  5631.7  310.17  5736.4  317.96  5872.2  324.96  5979.3   333.3  6167.4   349.9
  6283.2  363.18  6333.4  365.74  6451.4  377.01  6456.5  376.34  6503.9   380.1
#Mann= 8 ,-1 , 0
  4097.7      .1       0  4204.9     .16       0  4263.3     .05       0
  4997.1     .03       0  5003.1     .05       0  5314.3     .08       0
  5387.4     .05       0  5979.3     .16       0
Bank Sta=4980.1,5010.2
XS Rating Curve= 0 ,0
Exp/Cntr=0.3,0.1

Type RM Length L Ch R = 1 ,10364   ,581,581,581
BEGIN DESCRIPTION:
CANE BRANCH 14.0
END DESCRIPTION:
XS GIS Cut Line= 3
      3621076.99     10523194.21      3622201.97     10523742.81
      3623506.03     10523749.75
#Sta/Elev= 30
  3946.5  375.97  4033.9  372.22  4081.5  369.31    4094  365.63  4166.4   358.1
  4227.8  352.26  4327.7  347.56  4483.4  327.47  4492.6  323.88  4515.2  320.99
  4520.7  324.66  4717.1  307.67  4813.7  303.85  4984.1  305.79  4996.5  297.59
  4999.3  297.09  5002.5  297.59    5022  301.64  5028.6  305.33  5117.7  302.12
  5245.8  302.34  5455.8  307.14  5605.8  313.51  5776.1  324.95  5865.8  329.03
  6105.8  352.96  6159.6   360.5  6357.3  383.21  6456.2  390.53  6502.2  391.96
#Mann= 9 ,-1 , 0
  3946.5      .1       0  4033.9     .16       0  4166.4     .05       0
  4996.5     .03       0  5002.5     .05       0  5776.1     .16       0
  6159.6     .05       0  6357.3     .08       0  6456.2     .15       0
Bank Sta=4984.1,5028.6
XS Rating Curve= 0 ,0
Exp/Cntr=0.3,0.1

Type RM Length L Ch R = 1 ,9783    ,421,421,421
BEGIN DESCRIPTION:
CANE BRANCH 13.0
END DESCRIPTION:
XS GIS Cut Line= 4
       3621261.3      10523710.1      3621513.03     10524105.05
      3622014.47     10524124.76      3623485.68     10524159.45
#Sta/Elev= 30
  3900.9  346.64  3949.3  337.23  4031.1   328.9  4131.3  322.09    4233   310.8
  4629.2  302.11  4970.2  304.63  4976.3  304.81  4986.3  296.38  4993.3  295.64
    4996  295.14  4999.3  295.64  5006.3  301.17  5016.3  304.51  5115.3  304.68
  5178.3  306.42  5366.3  312.39  5708.1  332.79  5885.9  345.76  5976.5  353.93
  5986.5  352.84  6004.6   356.6  6046.5  358.16  6056.6  362.48  6103.4  368.88
  6136.6  367.06  6176.6   372.4  6186.6  377.58  6286.6  387.28  6342.7  390.29
#Mann= 12 ,-1 , 0
  3900.9     .16       0  4031.1     .05       0  4970.2     .12       0
  4993.3     .07       0  4999.3     .12       0  5115.3      .1       0
  5178.3     .05       0  5366.3      .1       0  5708.1     .05       0
  5885.9     .16       0  6004.6      .1       0  6103.4     .08       0
Bank Sta=4976.3,5016.3
XS Rating Curve= 0 ,0
Exp/Cntr=0.3,0.1

Type RM Length L Ch R = 1 ,9362    ,425,425,425
BEGIN DESCRIPTION:
CANE BRANCH 12.0
END DESCRIPTION:
XS GIS Cut Line= 3
      3621070.31     10524517.38      3621378.48     10524382.83
      3622965.85     10524682.09
#Sta/Elev= 30
  3988.1  342.48  4068.9  334.18  4115.7  326.02  4260.1  309.81  4366.2  304.52
  4428.6  303.13  4446.1  302.54  4716.1  299.82  4884.9  300.94  4983.3  303.42
  4988.4  302.52  4994.1  295.84  4996.9  295.34  5000.1  295.84  5007.3   296.4
  5027.7  303.36    5048  302.05  5103.6  302.61  5249.8   305.7  5627.8   317.8
  5632.9  318.05  5638.2  320.88  5685.3     321  5690.4  324.77  5709.5  321.93
  5760.3  322.07  5790.1  326.49  5795.2  333.79  5841.8  336.57  5939.7  346.18
#Mann= 8 ,-1 , 0
  3988.1     .05       0  4428.6     .12       0  4446.1     .05       0
  4884.9     .12       0  4994.1     .07       0  5000.1     .12       0
  5103.6     .16       0  5249.8     .05       0
Bank Sta=4983.3,5027.7
XS Rating Curve= 0 ,0
Exp/Cntr=0.3,0.1

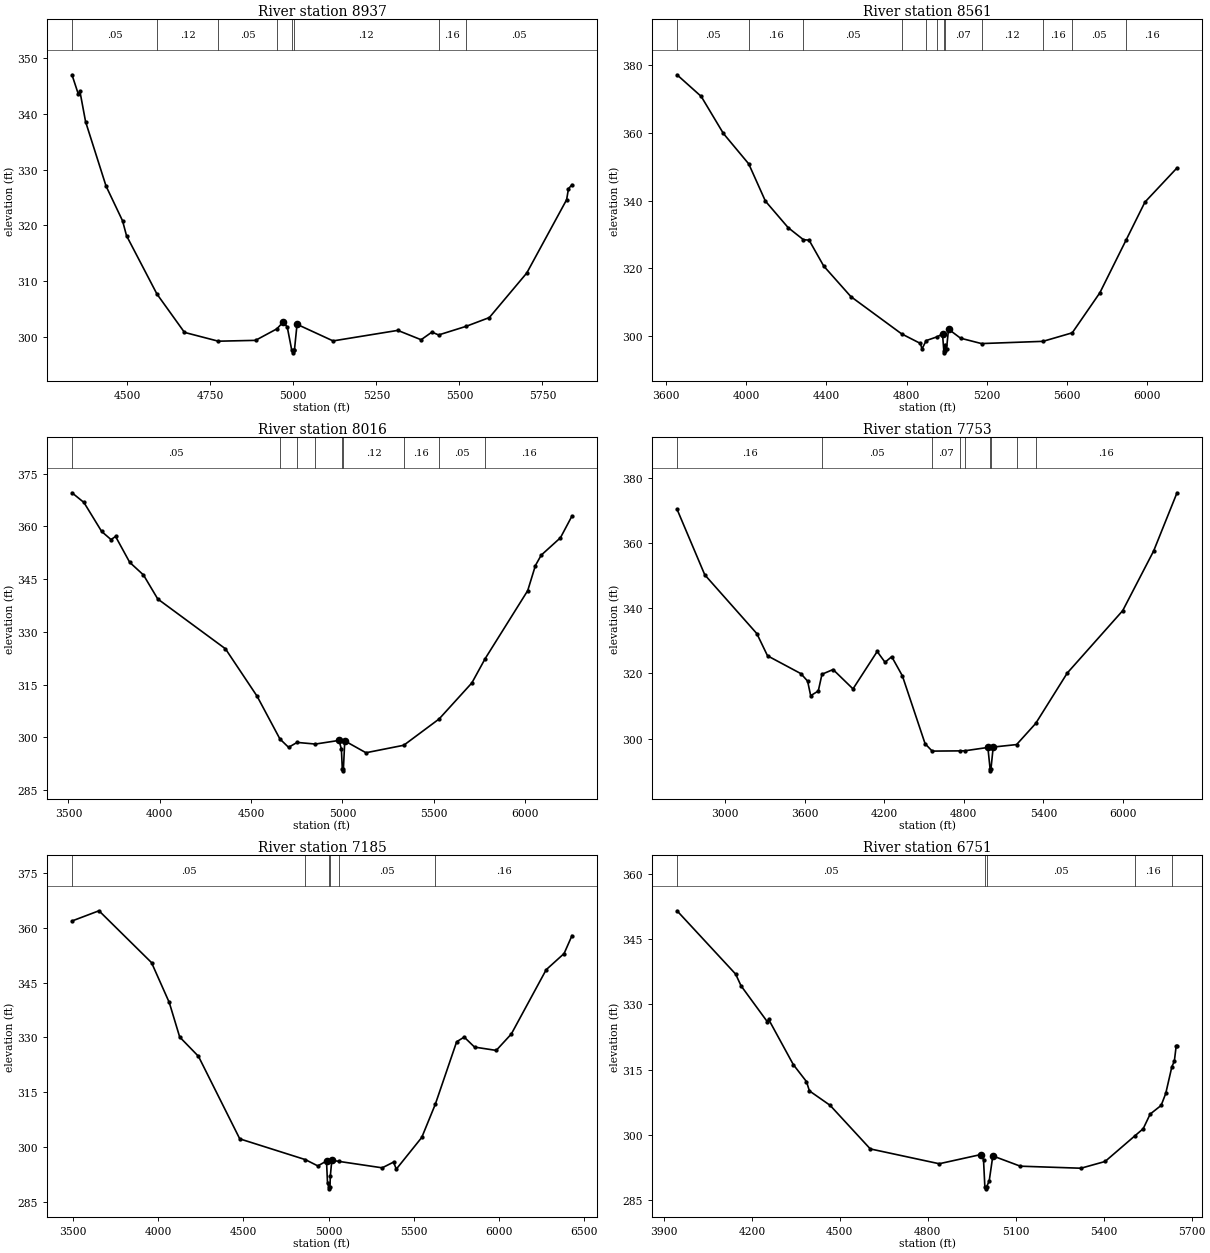
Type RM Length L Ch R = 1 ,8937    ,376,376,376
BEGIN DESCRIPTION:
CANE BRANCH 11.0
END DESCRIPTION:
XS GIS Cut Line= 3
      3621099.64     10524610.19      3621749.61     10524760.19
       3622549.6     10525010.19
#Sta/Elev= 30
  4333.6  347.02  4352.4   343.6  4357.5  344.05  4374.6  338.59  4436.2  327.04
  4485.8  320.82  4497.8  318.14  4589.4  307.67  4672.2  300.79  4774.1  299.21
  4886.1  299.36  4950.3  301.42  4969.9  302.68  4981.8  301.72  4995.1  297.62
  4997.8  297.12  5001.1  297.62  5003.3  297.62  5011.1  302.24  5119.6  299.26
  5314.4  301.15  5384.6  299.47  5417.1  300.84  5437.3  300.33  5520.3  301.88
    5590  303.45  5702.6  311.44  5822.6  324.59  5828.3  326.58  5838.8  327.29
#Mann= 8 ,-1 , 0
  4333.6     .05       0  4589.4     .12       0  4774.1     .05       0
  4950.3     .12       0  4995.1     .07       0  5001.1     .12       0
  5437.3     .16       0  5520.3     .05       0
Bank Sta=4969.9,5011.1
XS Rating Curve= 0 ,0
Exp/Cntr=0.3,0.1

Type RM Length L Ch R = 1 ,8561    ,545,545,545
BEGIN DESCRIPTION:
CANE BRANCH 10.0
END DESCRIPTION:
XS GIS Cut Line= 3
      3620357.71     10524711.31      3621590.34     10525075.89
      3622799.63     10525060.19
#Sta/Elev= 30
  3654.8  377.21  3775.5  370.81  3886.2  359.85  4012.7  350.85  4095.8  339.85
  4209.5  331.99  4285.6  328.43  4313.8   328.3  4386.8  320.64  4522.3   311.6
  4775.5  300.58  4869.5  297.74  4876.9  296.09  4898.2   298.6  4954.4  299.75
  4979.5  300.59  4986.2  295.47  4988.9  294.97  4992.2  295.47  4994.2  297.42
  4999.5   296.1  5009.5  301.97  5069.5   299.3  5174.1  297.71  5480.8  298.37
  5626.8  300.89  5764.5  312.72  5895.3  328.31  5989.6  339.56  6149.6  349.67
#Mann= 12 ,-1 , 0
  3654.8     .05       0  4012.7     .16       0  4285.6     .05       0
  4775.5     .07       0  4898.2     .05       0  4954.4     .07       0
  4986.2     .07       0  4992.2     .07       0  5174.1     .12       0
  5480.8     .16       0  5626.8     .05       0  5895.3     .16       0
Bank Sta=4979.5,5009.5
XS Rating Curve= 0 ,0
Exp/Cntr=0.3,0.1

Type RM Length L Ch R = 1 ,8016    ,263,263,263
BEGIN DESCRIPTION:
CANE BRANCH 9.0
END DESCRIPTION:
XS GIS Cut Line= 3
      3620305.58     10525223.45      3621749.61     10525510.19
      3622949.58      10525110.2
#Sta/Elev= 30
  3519.4  369.59  3584.7  366.84  3681.9  358.58  3733.1  356.27    3758  357.16
  3835.4   349.8  3910.9  346.19  3988.9  339.37  4359.5  325.19  4532.8  311.69
  4657.8  299.52  4705.1  297.15  4751.7  298.55  4851.8  298.08  4981.4  299.12
  4994.3  296.62  4999.2  290.96  5001.9  290.46  5005.2  290.96  5012.7  298.98
  5128.7  295.61  5335.6  297.74  5529.1  305.22  5708.4  315.48  5781.1  322.38
  6014.1  341.74  6056.3  348.89  6087.9  351.83  6193.3  356.79  6256.5  362.98
#Mann= 9 ,-1 , 0
  3519.4     .05       0  4657.8     .07       0  4751.7     .05       0
  4851.8     .12       0  4999.2     .07       0  5005.2     .12       0
  5335.6     .16       0  5529.1     .05       0  5781.1     .16       0
Bank Sta=4981.4,5012.7
XS Rating Curve= 0 ,0
Exp/Cntr=0.3,0.1

Type RM Length L Ch R = 1 ,7753    ,568,568,568
BEGIN DESCRIPTION:
CANE BRANCH 8.0
END DESCRIPTION:
XS GIS Cut Line= 3
      3619541.72     10525996.02      3621979.75     10525701.15
      3623264.48     10525416.42
#Sta/Elev= 30
  2636.2  370.34  2845.6  350.22  3238.4   332.2    3319   325.4  3570.8  319.93
  3621.2  317.65  3644.5  313.18  3701.8  314.61  3729.7  319.75  3813.4  321.19
  3963.7  315.26  4146.1  326.72  4205.4  323.42  4255.8  325.13  4336.4  319.24
  4507.6  298.45    4561  296.19  4770.9  296.26  4807.9  296.29  4981.1  297.31
  4998.2  290.64  5000.9  290.14  5004.2  290.64  5021.3  297.43  5197.8  298.19
  5341.7  304.66    5580  320.12    5998  339.23  6231.3  357.51  6407.9  375.37
#Mann= 9 ,-1 , 0
  2636.2     .16       0  3729.7     .05       0    4561     .07       0
  4770.9     .05       0  4807.9     .12       0  4998.2     .07       0
  5004.2     .12       0  5197.8     .05       0  5341.7     .16       0
Bank Sta=4981.1,5021.3
XS Rating Curve= 0 ,0
Exp/Cntr=0.3,0.1

Type RM Length L Ch R = 1 ,7185    ,434,434,434
BEGIN DESCRIPTION:
CANE BRANCH 7.0
END DESCRIPTION:
XS GIS Cut Line= 3
      3620435.84     10526846.71      3621799.61     10526210.19
      3623074.66     10525553.34
#Sta/Elev= 30
  3491.8   361.9  3650.5   364.7  3959.5  350.49  4063.6  339.57    4125   330.1
  4235.3  324.81  4478.1  302.19  4863.5   296.5  4936.9  294.78  4988.1  296.11
    4994  290.02  5002.1  288.99  5004.8  288.49  5008.1  288.99  5010.7   292.1
  5019.3  296.32  5059.8  296.02  5315.4  294.25  5381.9  295.81  5398.5   293.9
    5548  302.58  5627.7  311.68  5753.1   328.8  5797.5  330.08  5858.3  327.34
  5985.7  326.43  6074.4  330.92  6279.5  348.55  6384.7  352.98  6431.1  357.89
#Mann= 6 ,-1 , 0
  3491.8     .05       0  4863.5     .12       0  5002.1     .07       0
  5008.1     .12       0  5059.8     .05       0  5627.7     .16       0
Bank Sta=4988.1,5019.3
XS Rating Curve= 0 ,0
Exp/Cntr=0.3,0.1

Type RM Length L Ch R = 1 ,6751    ,452,452,452
BEGIN DESCRIPTION:
CANE BRANCH 6.0
END DESCRIPTION:
XS GIS Cut Line= 3
      3620850.89     10526730.45      3621899.61     10526610.19
      3622499.62     10526360.18
#Sta/Elev= 30
  3944.6  351.53  4144.6  336.97    4163  334.28  4252.2  326.06  4257.2  326.55
  4341.4  316.15  4386.2  312.25  4396.3  310.11  4466.7   306.8  4603.9  296.77
  4839.1  293.36  4980.1  295.46  4990.1  294.32  4994.7  288.09  4997.4  287.59
  5000.7  288.09  5009.4  289.35  5021.9  295.16  5115.6   292.8  5322.5  292.33
  5404.8  293.88  5505.8  299.74  5534.8  301.41  5558.6  304.78    5596  306.77
  5611.7  309.52  5632.7  315.69    5641  316.92  5647.5   320.5  5650.2   320.5
#Mann= 5 ,-1 , 0
  3944.6     .05       0  4994.7     .03       0  5000.7     .05       0
  5505.8     .16       0  5632.7     .05       0
Bank Sta=4980.1,5021.9
XS Rating Curve= 0 ,0
Exp/Cntr=0.3,0.1

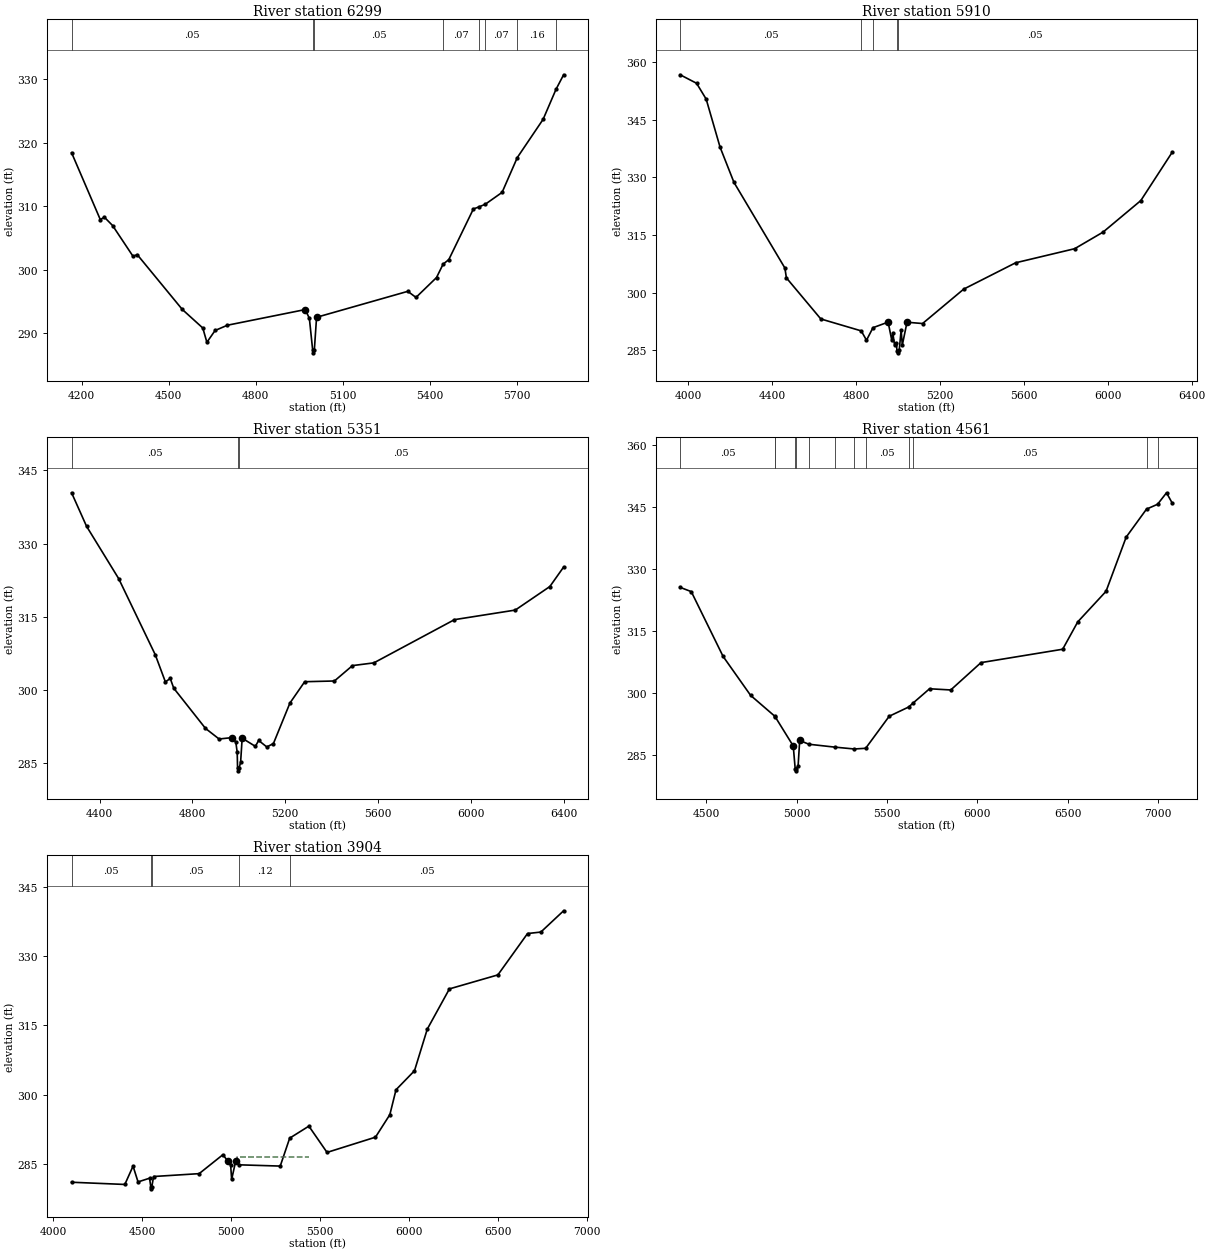
Type RM Length L Ch R = 1 ,6299    ,389,389,389
BEGIN DESCRIPTION:
CANE BRANCH 5.0
END DESCRIPTION:
XS GIS Cut Line= 3
      3621449.61     10527610.19      3622049.61     10527010.19
      3622649.64     10526410.16
#Sta/Elev= 30
  4164.8   318.4  4263.8  307.87  4277.9  308.24  4306.2  306.93  4376.9  302.07
  4391.1  302.35  4546.6  293.71  4617.4  290.78  4631.5  288.53  4659.8  290.39
  4702.2  291.22  4970.9  293.69    4985  292.29  4996.2  287.37  4998.9  286.87
  5002.2  287.37  5009.8  292.47  5324.5  296.56  5352.7   295.6  5423.5  298.73
  5446.2  300.84  5465.9  301.56  5550.7  309.54  5568.7  309.84  5591.7  310.28
  5649.7  312.15  5702.2  317.64  5791.2  323.66  5835.8   328.4  5861.9  330.68
#Mann= 8 ,-1 , 0
  4164.8     .05       0  4996.2     .03       0  5002.2     .05       0
  5446.2     .07       0  5568.7     .16       0  5591.7     .07       0
  5702.2     .16       0  5835.8     .05       0
Bank Sta=4970.9,5009.8
XS Rating Curve= 0 ,0
Exp/Cntr=0.3,0.1

Type RM Length L Ch R = 1 ,5910    ,559,559,559
BEGIN DESCRIPTION:
CANE BRANCH 4.0
END DESCRIPTION:
XS GIS Cut Line= 3
      3621167.28     10527840.02      3621688.08     10527596.98
      3623278.35     10526819.21
#Sta/Elev= 30
  3961.9  356.66  4040.2  354.45  4085.9  350.33  4152.1  337.84  4218.3  328.68
  4461.1   306.4  4468.2  303.85  4632.3  293.16  4824.9  290.06    4850  287.63
  4880.9  290.89  4953.1  292.34    4970  287.74  4975.6  289.44  4983.6  286.38
  4992.5  286.97  4995.1  284.85  4997.9  284.35  5001.1  284.85  5005.9     285
  5015.1  290.29  5020.6  286.36  5043.1  292.31  5117.2  291.97  5313.3  300.92
  5560.9  307.77  5842.2  311.43  5977.3  315.74  6157.4  323.95  6306.9  336.51
#Mann= 5 ,-1 , 0
  3961.9     .05       0  4824.9     .12       0  4880.9     .05       0
  4995.1     .03       0  5001.1     .05       0
Bank Sta=4953.1,5043.1
XS Rating Curve= 0 ,0
Exp/Cntr=0.3,0.1

Type RM Length L Ch R = 1 ,5351    ,790,790,790
BEGIN DESCRIPTION:
CANE BRANCH 3.0
END DESCRIPTION:
XS GIS Cut Line= 3
      3621599.62     10528260.18      3622199.61     10527860.19
      3623250.59     10526937.25
#Sta/Elev= 30
  4279.2  340.42  4343.8  333.55    4482  322.85  4639.7  307.26  4683.3   301.7
  4704.3  302.39  4719.4   300.4  4856.1  292.17  4914.7     290  4971.8  290.29
  4986.8  289.34  4992.8  287.26  4994.3  283.98    4997  283.48  5000.3  283.98
  5007.4   285.2  5014.1  290.17    5071  288.49  5085.2   289.7  5120.3  288.37
  5148.8  289.07    5220  297.37  5283.5  301.73  5411.6  301.88  5489.4  305.03
  5581.5  305.59  5928.8  314.44  6190.7   316.4  6339.7  321.22    6399  325.21
#Mann= 3 ,-1 , 0
  4279.2     .05       0  4994.3     .03       0  5000.3     .05       0
Bank Sta=4971.8,5014.1
XS Rating Curve= 0 ,0
Exp/Cntr=0.3,0.1

Type RM Length L Ch R = 1 ,4561    ,657,657,657
BEGIN DESCRIPTION:
CANE BRANCH 2.0
END DESCRIPTION:
XS GIS Cut Line= 4
      3621907.66     10528729.23      3622363.43      10528533.9
      3622572.63     10528382.86      3623458.03     10526625.95
#Sta/Elev= 30
  4356.4  325.61  4417.9  324.58  4593.8   308.9  4746.1  299.46  4880.4  294.39
  4882.5  294.24  4981.9  287.21  4992.6  281.69  4995.3  281.19  4998.6  281.69
  5008.9  282.45  5017.5  288.54  5068.5  287.63  5211.8  286.93  5319.6  286.48
  5382.4  286.65  5512.7  294.41  5620.6  296.65  5642.8  297.53  5735.8  301.06
    5853  300.77  6020.2  307.39    6472  310.63  6555.6  317.27  6711.8  324.65
  6823.3  337.78  6935.7  344.55  6996.9  345.73  7046.4  348.51  7077.7  346.03
#Mann= 13 ,-1 , 0
  4356.4     .05       0  4880.4     .08       0  4882.5     .05       0
  4992.6     .03       0  4998.6     .05       0  5068.5     .08       0
  5211.8     .05       0  5319.6     .16       0  5382.4     .05       0
  5620.6     .08       0  5642.8     .05       0  6935.7     .08       0
  6996.9     .05       0
Bank Sta=4981.9,5017.5
XS Rating Curve= 0 ,0
Exp/Cntr=0.3,0.1

Type RM Length L Ch R = 1 ,3904    ,0,0,0
BEGIN DESCRIPTION:
CANE BRANCH 1.0
END DESCRIPTION:
XS GIS Cut Line= 2
      3622558.72     10529419.36      3623938.45     10527024.36
#Sta/Elev= 30
  4102.9  281.03    4402  280.55  4448.2  284.52  4476.2   281.1  4540.8   281.9
  4547.8   280.1  4550.6   279.6  4553.8   280.1  4563.6  282.27  4819.5  282.89
  4953.1     287  4980.5   285.6  4996.2  284.87  5002.1  281.64  5025.2  285.68
  5045.5   284.8    5275  284.53  5328.1  290.58  5435.9  293.18  5537.9  287.49
    5810  290.79  5890.8  295.67  5925.4  301.06  6029.2  305.18  6101.1   314.2
  6225.4  322.91  6497.6  325.94  6664.3   334.9    6739  335.22  6866.9  339.83
#Mann= 5 ,-1 , 0
  4102.9     .05       0  4547.8     .03       0  4553.8     .05       0
  5045.5     .12       0  5328.1     .05       0
#XS Ineff= 1 ,-1
 5031.25 5438.64  286.56
Permanent Ineff=
       F
Bank Sta=4980.5,5025.2
XS Rating Curve= 0 ,0
Exp/Cntr=0.3,0.1

Chan Stop Cuts=-1
Use User Specified Reach Order=0
Composite Channel Slope=5