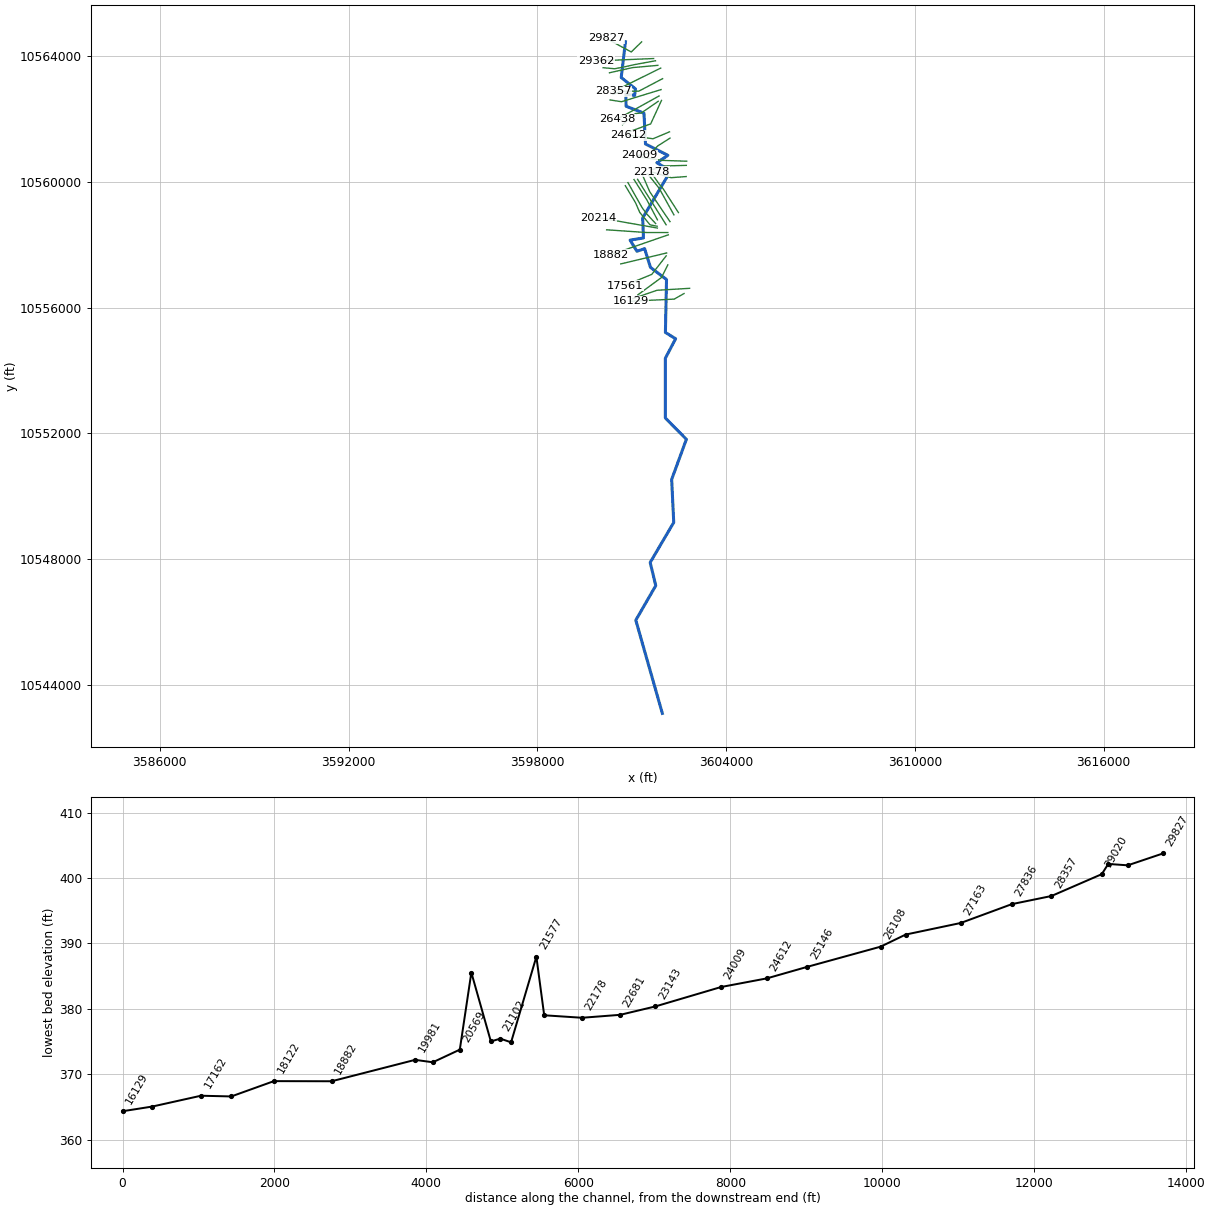
--- CAROLINE CREEK.prj (project) ---

Proj Title=CAROLINE CREEK Base Level Engineering
Current Plan=p01
Default Exp/Contr=0.3,0.1
English Units
Geom File=g01
Flow File=f01
Plan File=p01
BEGIN DESCRIPTION:
CAROLINE CREEK
END DESCRIPTION:

--- CAROLINE CREEK.p01 (plan) ---

Plan Title=Multiple Run
Short Identifier=Multiple
Geom File=g01
Flow File=f01
Subcritical Flow
K Sum by GR= 0
Std Step Tol= 0.01
Critical Tol= 0.01
Num of Std Step Trials= 20
Max Error Tol= 0.3
Flow Tol Ratio= 0.001
Split Flow NTrial= 30
Split Flow Tol= 0.02
Split Flow Ratio= 0.02
Log Output Level= 0
Friction Slope Method= 1
Unsteady Friction Slope Method= 2
Unsteady Bridges Friction Slope Method= 1
Parabolic Critical Depth
Global Vel Dist=  1 , 1 , 1
Global Log Level= 0
CheckData=True
Encroach Param= -1, 0, 0, 0
BEGIN DESCRIPTION:
Multiple Run
END DESCRIPTION:

--- CAROLINE CREEK.f01 (steady flow) ---

Flow Title=Multiple
Number of Profiles=7
Profile Names=10-year,25-year,50-year,1pct_min,100-year,1pct_plu,500-year
River Rch & RM= CAROLINE CREEK,Reach-1,29827
    1377    1905    2343    2099    2839    3840    4157
River Rch & RM= CAROLINE CREEK,Reach-1,20721
    2042    2894    3617    3292    4452    6021    6726
River Rch & RM= CAROLINE CREEK,Reach-1,18882
    2331    3320    4163    3799    5138    6948    7803
River Rch & RM= CAROLINE CREEK,Reach-1,16129
    2746    3932    4947    4526    6121    8278    9347
River Rch & RM= CAROLINE CREEK,Reach-1,9876
    3111    4471    5642    5173    6996    9461   10732
River Rch & RM= CAROLINE CREEK,Reach-1,5848
    3218    4631    5848    5366    7257    9814   11148
Boundary for River Rch & Prof#=CAROLINE CREEK,Reach-1,1
Up Type=0
Dn Type=3
Dn Slope=0.005
Boundary for River Rch & Prof#=CAROLINE CREEK,Reach-1,2
Up Type=0
Dn Type=3
Dn Slope=0.005
Boundary for River Rch & Prof#=CAROLINE CREEK,Reach-1,3
Up Type=0
Dn Type=3
Dn Slope=0.005
Boundary for River Rch & Prof#=CAROLINE CREEK,Reach-1,4
Up Type=0
Dn Type=3
Dn Slope=0.005
Boundary for River Rch & Prof#=CAROLINE CREEK,Reach-1,5
Up Type=0
Dn Type=3
Dn Slope=0.005
Boundary for River Rch & Prof#=CAROLINE CREEK,Reach-1,6
Up Type=0
Dn Type=3
Dn Slope=0.005
Boundary for River Rch & Prof#=CAROLINE CREEK,Reach-1,7
Up Type=0
Dn Type=3
Dn Slope=0.005

--- CAROLINE CREEK.g01 (geometry) ---

Geom Title=Existing Conditions

River Reach=CAROLINE CREEK,Reach-1
Reach XY= 30
      3600802.62     10564463.75      3600667.75     10563324.00
      3601120.25     10562962.00      3601094.25     10562754.00
      3600813.00     10562799.00      3600823.25     10562410.00
      3601391.75     10562188.00      3601439.50     10561209.00
      3602151.50     10560848.00      3601800.75     10560612.00
      3602133.50     10560416.00      3602123.75     10560159.00
      3601349.50     10558855.00      3601374.75     10558218.00
      3600950.50     10558149.00      3601167.00     10557795.00
      3601411.75     10557877.00      3601597.25     10557283.00
      3602108.00     10556895.00      3602072.50     10555211.00
      3602397.25     10555011.00      3602070.50     10554390.00
      3602070.75     10552490.00      3602739.50     10551811.00
      3602271.50     10550534.00      3602337.50     10549166.00
      3601589.00     10547892.00      3601766.00     10547155.00
      3601131.75     10546055.00      3601975.50     10543090.00

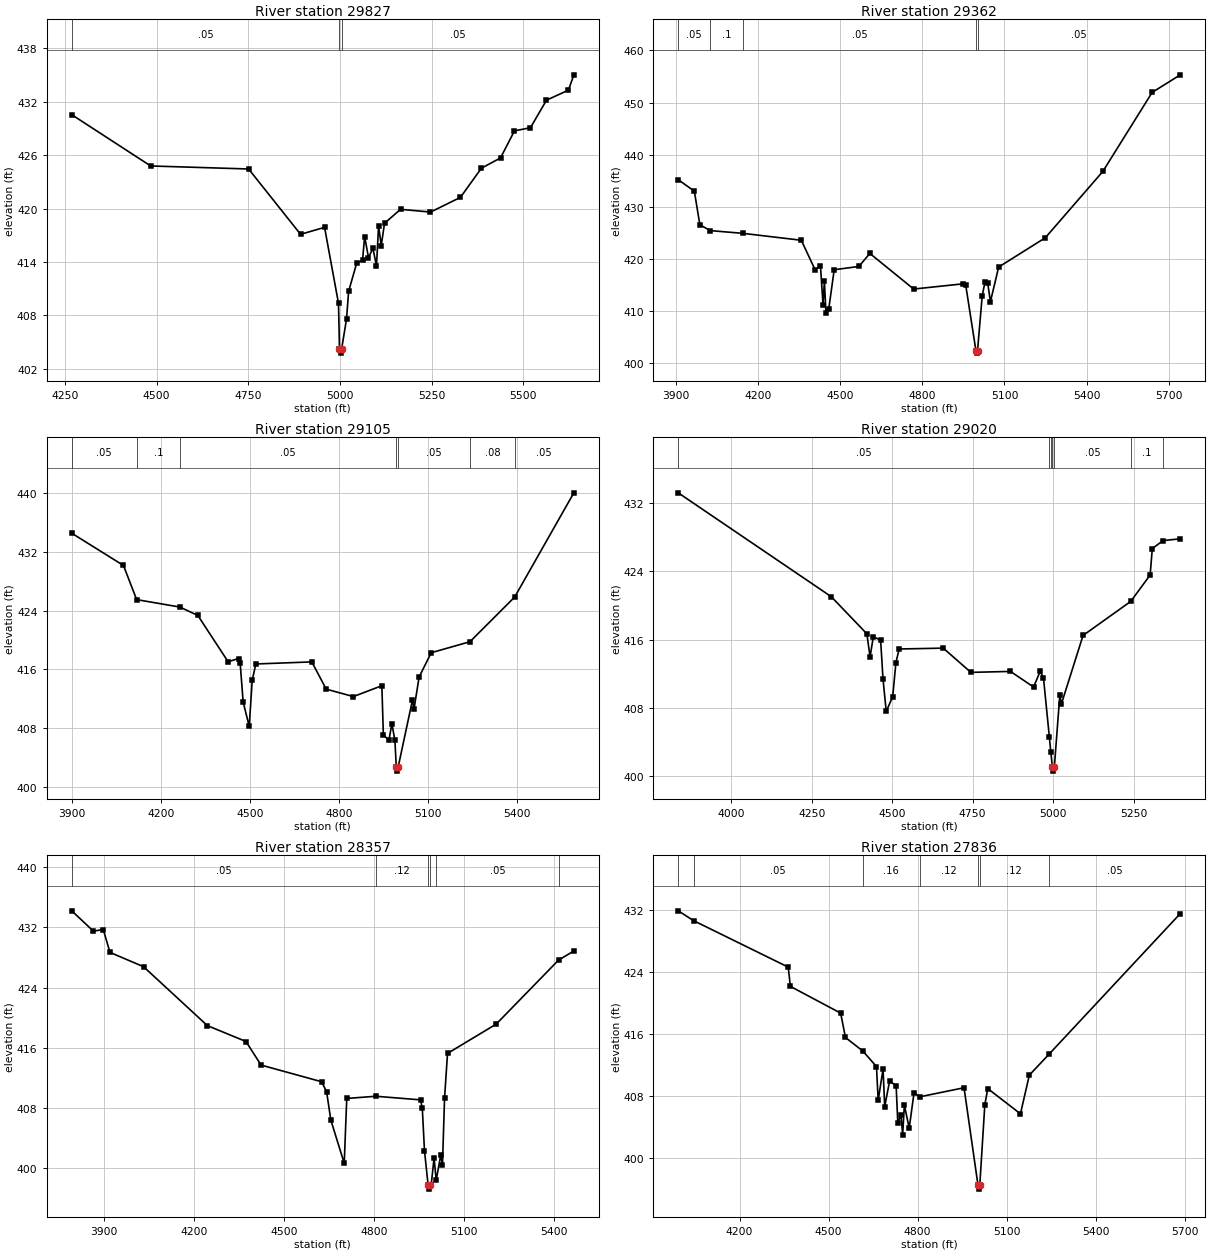
Type RM Length L Ch R = 1,29827,465,465,465
BEGIN DESCRIPTION:
CAROLINE CREEK 46.0
END DESCRIPTION:
XS GIS Cut Line= 3
      3601316.61     10564457.43      3600986.73     10564136.23
      3600188.08     10564570.28
#Sta/Elev= 30
  4268.8  430.55  4484.0  424.79  4751.2  424.45  4892.8  417.11  4958.3  417.89
  4996.3  409.35  4999.0  404.26  5001.8  403.76  5005.0  404.26  5018.2  407.60
  5023.9  410.70  5045.7  413.84  5061.9  414.21  5067.6  416.86  5078.1  414.49
  5090.2  415.54  5099.9  413.56  5105.6  418.04  5112.9  415.85  5121.8  418.35
  5165.5  419.92  5247.2  419.61  5328.9  421.26  5386.1  424.54  5438.2  425.69
  5476.2  428.73  5519.9  429.09  5563.6  432.18  5623.5  433.31  5638.2  435.03
#Mann=3,-1,0
  4268.8    0.05       0  4999.0    0.03       0  5005.0    0.05       0
Bank Sta=4999,5005
Exp/Cntr=0.3,0.1

Type RM Length L Ch R = 1,29362,257,257,257
BEGIN DESCRIPTION:
CAROLINE CREEK 45.0
END DESCRIPTION:
XS GIS Cut Line= 2
      3601698.56     10563927.90      3599866.92     10563849.77
#Sta/Elev= 30
  3908.7  435.21  3967.5  433.00  3987.7  426.55  4025.7  425.44  4145.6  424.91
  4358.1  423.59  4408.1  417.97  4428.1  418.60  4437.4  411.22  4442.4  415.80
  4448.1  409.57  4458.1  410.33  4478.2  417.94  4568.2  418.56  4608.3  421.06
  4768.4  414.23  4948.6  415.23  4958.6  414.94  4995.6  402.44  4998.4  401.94
  5001.6  402.44  5018.7  412.98  5028.7  415.54  5038.7  415.35  5048.7  411.82
  5078.7  418.45  5248.9  424.06  5459.1  436.79  5639.2  451.95  5742.0  455.32
#Mann=5,-1,0
  3908.7    0.05       0  4025.7     0.1       0  4145.6    0.05       0
  4995.6    0.03       0  5001.6    0.05       0
Bank Sta=4995.6,5001.6
Exp/Cntr=0.3,0.1

Type RM Length L Ch R = 1,29105,85,85,85
BEGIN DESCRIPTION:
Mapping XS 44affee1
END DESCRIPTION:
XS GIS Cut Line= 5
      3601757.42     10563856.25      3601093.33     10563734.72
      3600793.85     10563667.44      3600459.65     10563602.34
      3600092.72     10563634.72
#Sta/Elev= 30
  3899.6  434.54  4073.7  430.15  4118.1  425.50  4263.6  424.49  4324.3  423.34
  4426.0  417.05  4461.3  417.48  4466.7  416.85  4476.8  411.56  4497.2  408.24
  4507.3  414.54  4519.6  416.74  4708.0  417.02  4756.5  413.31  4848.2  412.30
  4943.9  413.78  4949.0  407.12  4967.5  406.33  4977.7  408.59  4987.9  406.34
  4992.5  402.65  4995.2  402.15  4998.5  402.65  5047.1  411.84  5052.2  410.61
  5069.4  414.96  5110.1  418.27  5240.7  419.77  5391.2  425.85  5590.5  440.04
#Mann=7,-1,0
  3899.6    0.05       0  4118.1     0.1       0  4263.6    0.05       0
  4992.5    0.03       0  4998.5    0.05       0  5240.7    0.08       0
  5391.2    0.05       0
Bank Sta=4992.5,4998.5
Exp/Cntr=0.3,0.1

Type RM Length L Ch R = 1,29020,663,663,663
BEGIN DESCRIPTION:
CAROLINE CREEK 44.0
END DESCRIPTION:
XS GIS Cut Line= 3
      3601833.37     10563710.85      3601030.40     10563639.23
      3600294.72     10563474.30
#Sta/Elev= 30
  3835.2  433.22  4310.8  421.04  4421.3  416.69  4431.3  413.98  4441.4  416.36
  4464.1  415.93  4471.5  411.39  4481.5  407.59  4501.6  409.32  4511.6  413.32
  4521.7  414.91  4658.7  415.01  4744.6  412.17  4867.6  412.28  4939.4  410.45
  4959.9  412.30  4970.1  411.51  4988.3  404.62  4992.7  402.89  4997.9  401.09
  5000.6  400.59  5003.9  401.09  5020.9  409.50  5026.0  408.49  5093.1  416.50
  5241.3  420.49  5301.5  423.58  5308.3  426.69  5341.8  427.62  5395.3  427.83
#Mann=7,-1,0
  3835.2    0.05       0  4988.3    0.12       0  4992.7    0.05       0
  4997.9    0.03       0  5003.9    0.05       0  5241.3     0.1       0
  5341.8    0.15       0
Bank Sta=4997.9,5003.9
Exp/Cntr=0.3,0.1

Type RM Length L Ch R = 1,28357,521,521,521
BEGIN DESCRIPTION:
CAROLINE CREEK 43.0
END DESCRIPTION:
XS GIS Cut Line= 2
      3601924.25     10563624.09      3600423.03     10562879.80
#Sta/Elev= 30
  3792.2  434.20  3864.4  431.50  3897.3  431.72  3919.7  428.68  4031.8  426.78
  4244.7  418.96  4373.6  416.85  4424.0  413.72  4625.8  411.51  4642.6  410.20
  4656.8  406.42  4701.5  400.68  4709.9  409.29  4807.4  409.58  4956.5  409.10
  4962.1  407.96  4969.3  402.37  4981.5  397.75  4984.2  397.25  4987.5  397.75
  4991.7  397.81  5001.3  401.38  5008.4  398.43  5023.8  401.82  5029.3  400.39
  5036.3  409.33  5046.2  415.27  5208.7  419.16  5416.8  427.66  5467.8  428.87
#Mann=6,-1,0
  3792.2    0.05       0  4807.4    0.12       0  4981.5    0.07       0
  4987.5    0.12       0  5008.4    0.05       0  5416.8    0.08       0
Bank Sta=4981.5,4987.5
Exp/Cntr=0.3,0.1

Type RM Length L Ch R = 1,27836,673,673,673
BEGIN DESCRIPTION:
CAROLINE CREEK 42.0
END DESCRIPTION:
XS GIS Cut Line= 4
      3601983.93     10563286.99      3601224.36     10562887.68
      3600686.17     10562887.68      3600408.39     10562787.85
#Sta/Elev= 30
  3993.5  431.89  4045.4  430.62  4364.1  424.63  4371.2  422.15  4540.7  418.70
  4556.9  415.56  4615.8  413.80  4661.4  411.81  4667.1  407.45  4683.5  411.48
  4689.1  406.65  4705.5  409.93  4727.6  409.34  4733.2  404.58  4744.0  405.55
  4749.6  403.03  4755.3  406.85  4771.6  403.87  4788.0  408.45  4806.8  407.91
  4956.4  409.08  5003.4  396.51  5006.1  396.01  5009.4  396.51  5026.4  406.91
  5036.4  408.97  5146.4  405.72  5176.4  410.71  5242.4  413.39  5685.0  431.54
#Mann=7,-1,0
  3993.5     0.1       0  4045.4    0.05       0  4615.8    0.16       0
  4806.8    0.12       0  5003.4    0.07       0  5009.4    0.12       0
  5242.4    0.05       0
Bank Sta=5003.4,5009.4
Exp/Cntr=0.3,0.1

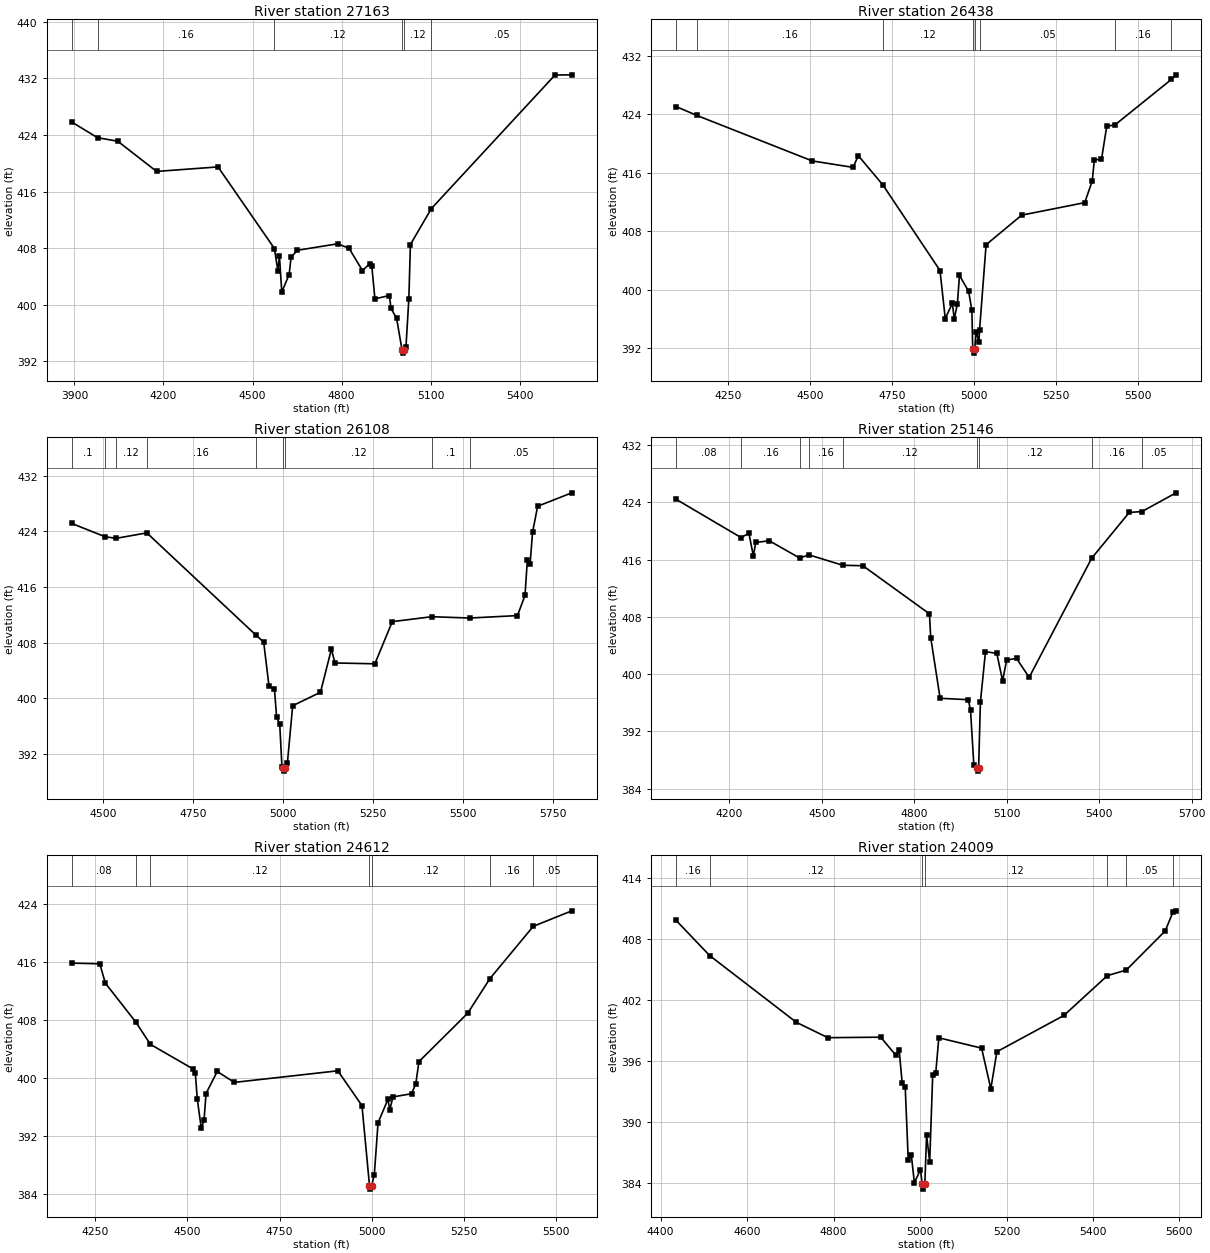
Type RM Length L Ch R = 1,27163,725,725,725
BEGIN DESCRIPTION:
CAROLINE CREEK 41.0
END DESCRIPTION:
XS GIS Cut Line= 3
      3601936.12     10562939.75      3600677.49     10562553.48
      3600313.79     10562609.76
#Sta/Elev= 30
  3890.7  425.84  3977.9  423.61  4045.9  423.12  4176.8  418.84  4383.7  419.48
  4573.7  407.93  4585.3  404.76  4590.5  406.92  4598.4  401.79  4623.3  404.25
  4629.7  406.69  4650.7  407.68  4786.6  408.60  4824.9  407.97  4870.3  404.82
  4895.6  405.81  4901.7  405.45  4912.2  400.81  4961.0  401.28  4966.3  399.48
  4985.4  398.03  5003.3  393.63  5006.1  393.13  5009.3  393.63  5016.8  394.02
  5026.5  400.81  5031.7  408.49  5102.3  413.58  5518.8  432.48  5575.3  432.51
#Mann=6,-1,0
  3890.7     0.1       0  3977.9    0.16       0  4573.7    0.12       0
  5003.3    0.07       0  5009.3    0.12       0  5102.3    0.05       0
Bank Sta=5003.3,5009.3
Exp/Cntr=0.3,0.1

Type RM Length L Ch R = 1,26438,330,330,330
BEGIN DESCRIPTION:
CAROLINE CREEK 40.0
END DESCRIPTION:
XS GIS Cut Line= 2
      3601871.06     10562735.77      3600535.84     10561994.46
#Sta/Elev= 30
  4090.0  425.07  4153.2  423.86  4506.2  417.63  4630.9  416.75  4646.9  418.35
  4722.2  414.33  4896.3  402.65  4912.4  396.08  4934.1  398.18  4939.8  396.01
  4949.5  398.12  4955.8  401.99  4983.8  399.80  4993.6  397.25  4996.3  391.86
  4999.1  391.36  5002.3  391.86  5006.7  394.29  5015.3  392.92  5017.0  394.46
  5037.1  406.18  5145.8  410.22  5338.4  411.93  5361.3  414.91  5367.7  417.79
  5389.5  417.84  5405.5  422.36  5431.1  422.57  5602.8  428.77  5617.2  429.40
#Mann=8,-1,0
  4090.0    0.08       0  4153.2    0.16       0  4722.2    0.12       0
  4996.3    0.07       0  5002.3    0.12       0  5017.0    0.05       0
  5431.1    0.16       0  5602.8    0.08       0
Bank Sta=4996.3,5002.3
Exp/Cntr=0.3,0.1

Type RM Length L Ch R = 1,26108,962,962,962
BEGIN DESCRIPTION:
CAROLINE CREEK 39.0
END DESCRIPTION:
XS GIS Cut Line= 4
      3601844.99     10562566.48      3601309.90     10562197.58
      3601114.59     10562175.87      3600706.64     10561820.00
#Sta/Elev= 30
  4413.3  425.12  4504.9  423.23  4535.7  422.97  4621.9  423.76  4923.9  409.10
  4946.1  408.07  4961.0  401.69  4975.9  401.37  4982.0  397.33  4990.7  396.25
  4996.9  390.06  4999.9  390.01  5002.7  389.51  5005.9  390.01  5011.8  390.61
  5026.6  398.91  5103.8  400.85  5134.0  407.03  5144.0  405.06  5254.7  404.94
  5303.0  411.00  5412.5  411.71  5517.7  411.52  5650.4  411.87  5671.3  414.77
  5677.9  419.88  5685.5  419.29  5692.2  423.83  5706.4  427.59  5801.1  429.52
#Mann=9,-1,0
  4413.3     0.1       0  4504.9    0.16       0  4535.7    0.12       0
  4621.9    0.16       0  4923.9    0.12       0  4999.9    0.07       0
  5005.9    0.12       0  5412.5     0.1       0  5517.7    0.05       0
Bank Sta=4999.9,5005.9
Exp/Cntr=0.3,0.1

Type RM Length L Ch R = 1,25146,534,534,534
BEGIN DESCRIPTION:
CAROLINE CREEK 38.0
END DESCRIPTION:
XS GIS Cut Line= 3
      3601948.58     10562595.37      3601604.82     10561847.97
      3600853.44     10561572.37
#Sta/Elev= 30
  4026.4  424.44  4237.6  419.08  4263.3  419.67  4277.5  416.51  4285.3  418.40
  4329.3  418.63  4428.2  416.21  4457.5  416.67  4567.5  415.21  4633.1  415.14
  4849.1  408.42  4853.2  405.09  4883.7  396.62  4975.2  396.42  4982.4  394.92
  4993.1  387.31  5002.7  386.94  5005.5  386.44  5008.7  386.94  5014.4  396.06
  5030.9  403.14  5067.7  402.89  5086.5  399.05  5099.6  401.97  5131.6  402.19
  5172.7  399.55  5375.6  416.19  5497.5  422.59  5538.6  422.71  5649.4  425.33
#Mann=9,-1,0
  4026.4    0.08       0  4237.6    0.16       0  4428.2    0.05       0
  4457.5    0.16       0  4567.5    0.12       0  5002.7    0.07       0
  5008.7    0.12       0  5375.6    0.16       0  5538.6    0.05       0
Bank Sta=5002.7,5008.7
Exp/Cntr=0.3,0.1

Type RM Length L Ch R = 1,24612,603,603,603
BEGIN DESCRIPTION:
CAROLINE CREEK 37.0
END DESCRIPTION:
XS GIS Cut Line= 3
      3602203.74     10561595.35      3601677.74     10561374.01
      3600899.13     10561485.98
#Sta/Elev= 30
  4185.9  415.82  4262.3  415.73  4277.2  413.07  4360.0  407.69  4399.7  404.62
  4515.9  401.22  4521.4  400.71  4526.8  397.09  4537.6  393.08  4545.1  394.15
  4550.6  397.85  4581.0  400.89  4627.2  399.38  4908.3  400.98  4973.8  396.18
  4994.2  385.17  4996.9  384.67  5000.2  385.17  5007.3  386.66  5017.4  393.81
  5044.2  397.04  5049.3  395.59  5057.8  397.38  5108.3  397.82  5119.8  399.17
  5128.5  402.25  5260.8  408.92  5321.2  413.70  5438.7  420.89  5543.2  423.03
#Mann=7,-1,0
  4185.9    0.08       0  4360.0    0.05       0  4399.7    0.12       0
  4994.2    0.07       0  5000.2    0.12       0  5321.2    0.16       0
  5438.7    0.05       0
Bank Sta=4994.2,5000.2
Exp/Cntr=0.3,0.1

Type RM Length L Ch R = 1,24009,866,866,866
BEGIN DESCRIPTION:
CAROLINE CREEK 36.0
END DESCRIPTION:
XS GIS Cut Line= 4
      3602219.37     10561394.82      3601833.99     10561150.05
      3601597.01     10560918.28      3601235.00     10560847.96
#Sta/Elev= 30
  4435.4  409.82  4513.8  406.33  4714.0  399.77  4786.8  398.26  4909.1  398.31
  4944.4  396.51  4951.6  397.08  4958.6  393.84  4965.7  393.42  4972.7  386.20
  4979.9  386.67  4986.9  383.98  5001.0  385.28  5005.1  383.85  5007.9  383.35
  5011.1  383.85  5015.1  388.68  5022.3  386.03  5029.3  394.58  5036.4  394.81
  5043.4  398.25  5142.4  397.23  5163.7  393.23  5177.8  396.88  5332.8  400.45
  5433.3  404.37  5477.0  404.92  5567.1  408.77  5585.6  410.68  5592.2  410.75
#Mann=7,-1,0
  4435.4    0.16       0  4513.8    0.12       0  5005.1    0.07       0
  5011.1    0.12       0  5433.3    0.16       0  5477.0    0.05       0
  5585.6    0.08       0
Bank Sta=5005.1,5011.1
Exp/Cntr=0.3,0.1

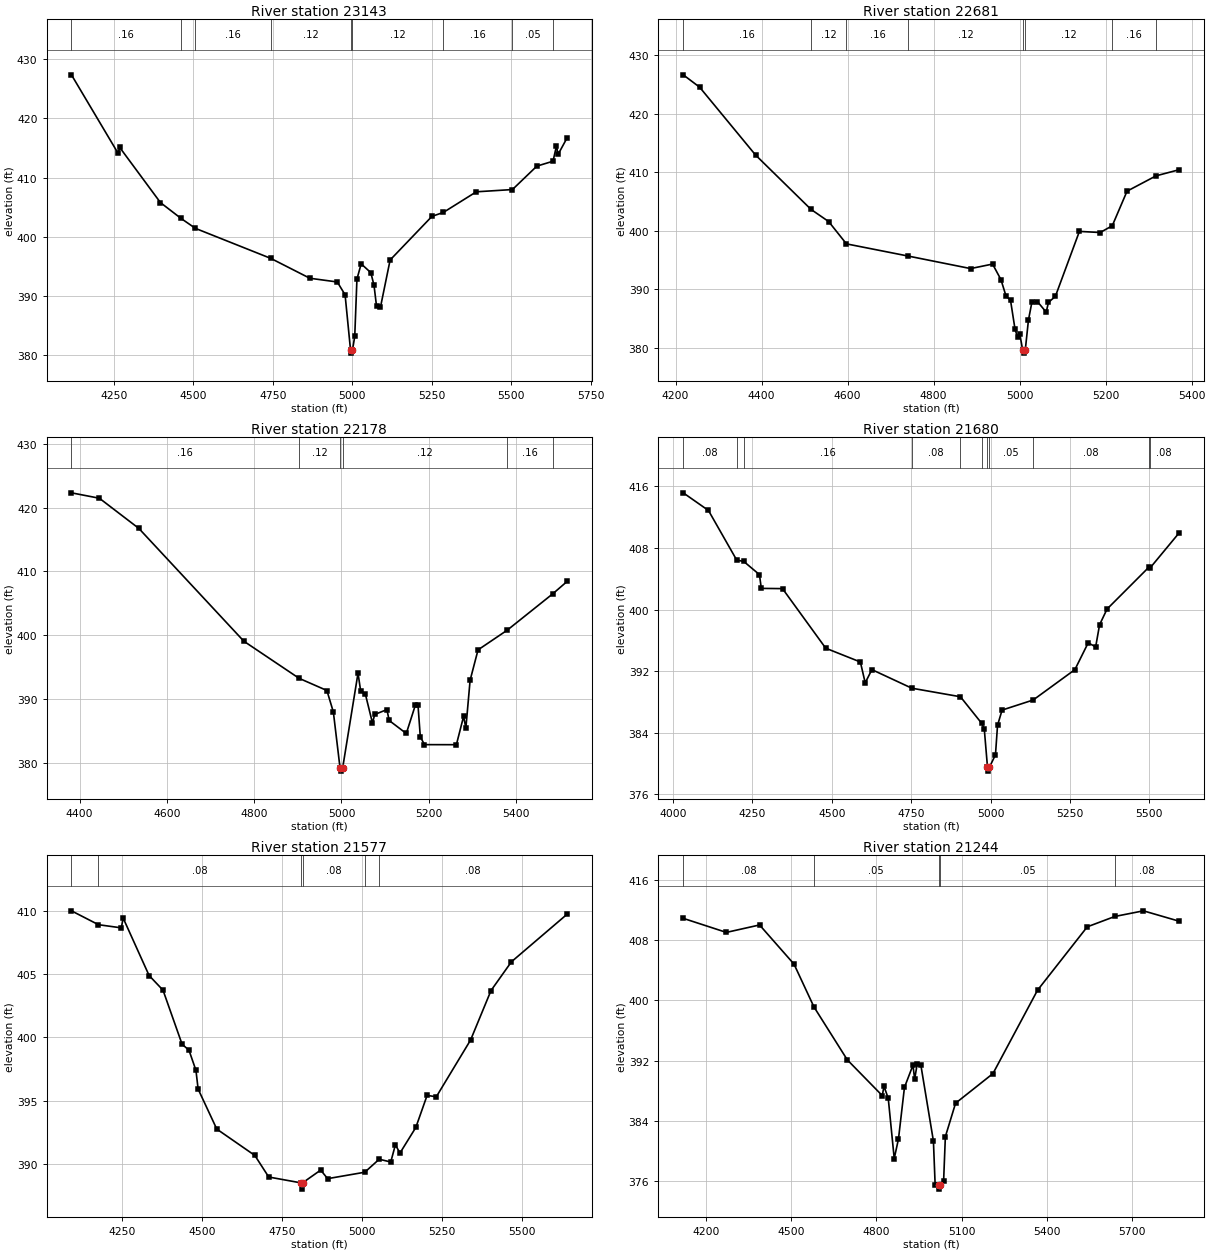
Type RM Length L Ch R = 1,23143,462,462,462
BEGIN DESCRIPTION:
CAROLINE CREEK 35.0
END DESCRIPTION:
XS GIS Cut Line= 3
      3602749.66     10560660.19      3601966.80     10560686.51
      3601199.61     10560810.19
#Sta/Elev= 30
  4115.8  427.32  4262.8  414.07  4267.8  415.07  4396.0  405.77  4461.1  403.09
  4506.2  401.42  4743.8  396.35  4866.3  393.01  4952.8  392.38  4977.3  390.22
  4994.5  380.88  4997.3  380.38  5000.5  380.88  5007.7  383.19  5014.6  392.85
  5027.9  395.44  5058.3  393.96  5068.4  391.81  5076.4  388.25  5088.7  388.13
  5119.1  396.09  5250.8  403.45  5286.6  404.11  5390.5  407.59  5504.2  407.97
  5581.0  411.92  5632.0  412.75  5642.8  415.33  5647.8  413.89  5676.2  416.68
#Mann=9,-1,0
  4115.8    0.16       0  4461.1    0.12       0  4506.2    0.16       0
  4743.8    0.12       0  4994.5    0.07       0  5000.5    0.12       0
  5286.6    0.16       0  5504.2    0.05       0  5632.0    0.08       0
Bank Sta=4994.5,5000.5
Exp/Cntr=0.3,0.1

Type RM Length L Ch R = 1,22681,503,503,503
BEGIN DESCRIPTION:
CAROLINE CREEK 34.0
END DESCRIPTION:
XS GIS Cut Line= 3
      3602737.68     10560527.66      3602046.23     10560509.55
      3601604.05     10560379.50
#Sta/Elev= 30
  4217.7  426.63  4255.8  424.52  4385.8  412.94  4514.8  403.65  4555.9  401.57
  4597.2  397.76  4741.3  395.67  4886.0  393.54  4937.1  394.31  4956.5  391.66
  4968.4  388.84  4978.8  388.13  4989.3  383.18  4995.1  381.84  5000.3  382.41
  5007.1  379.60  5009.9  379.10  5013.1  379.60  5020.5  384.75  5028.5  387.79
  5041.4  387.90  5061.8  386.10  5067.0  387.76  5083.1  388.79  5139.0  399.89
  5187.3  399.70  5215.4  400.85  5249.8  406.76  5317.3  409.38  5370.3  410.41
#Mann=8,-1,0
  4217.7    0.16       0  4514.8    0.12       0  4597.2    0.16       0
  4741.3    0.12       0  5007.1    0.07       0  5013.1    0.12       0
  5215.4    0.16       0  5317.3    0.08       0
Bank Sta=5007.1,5013.1
Exp/Cntr=0.3,0.1

Type RM Length L Ch R = 1,22178,498,498,498
BEGIN DESCRIPTION:
CAROLINE CREEK 33.0
END DESCRIPTION:
XS GIS Cut Line= 3
      3602733.44     10560172.05      3602251.70     10560135.60
      3601626.73     10560323.09
#Sta/Elev= 30
  4381.3  422.35  4445.3  421.50  4535.6  416.77  4776.3  399.05  4903.0  393.22
  4966.6  391.31  4981.4  387.93  4996.7  379.15  4999.4  378.65  5002.7  379.15
  5037.9  394.04  5044.1  391.17  5054.5  390.81  5071.0  386.21  5076.2  387.55
  5104.1  388.31  5109.3  386.60  5148.5  384.56  5169.4  389.04  5175.4  388.96
  5180.6  384.04  5190.2  382.81  5263.3  382.80  5279.8  387.25  5285.0  385.40
  5294.7  392.91  5312.9  397.69  5379.7  400.78  5484.2  406.50  5516.9  408.43
#Mann=6,-1,0
  4381.3    0.16       0  4903.0    0.12       0  4996.7    0.07       0
  5002.7    0.12       0  5379.7    0.16       0  5484.2    0.08       0
Bank Sta=4996.7,5002.7
Exp/Cntr=0.3,0.1

Type RM Length L Ch R = 1,21680,103,103,103
BEGIN DESCRIPTION:
CAROLINE CREEK 32.0
END DESCRIPTION:
XS GIS Cut Line= 4
      3602486.07     10559026.23      3602001.70     10559781.43
      3601876.70     10559929.87      3601608.53     10560315.20
#Sta/Elev= 30
  4032.4  415.14  4111.8  412.85  4200.7  406.42  4223.2  406.23  4272.3  404.53
  4278.3  402.74  4345.0  402.71  4481.1  394.98  4590.2  393.19  4605.4  390.49
  4626.5  392.20  4752.2  389.79  4905.3  388.68  4972.1  385.24  4980.3  384.54
  4990.5  379.53  4993.3  379.03  4996.5  379.53  5015.6  381.15  5022.1  384.97
  5036.4  386.95  5134.4  388.26  5265.7  392.20  5307.6  395.68  5331.1  395.15
  5343.4  398.02  5367.0  400.06  5498.7  405.49  5501.4  405.34  5593.1  409.90
#Mann=11,-1,0
  4032.4    0.08       0  4200.7     0.1       0  4223.2    0.16       0
  4752.2    0.08       0  4905.3    0.12       0  4972.1    0.05       0
  4990.5    0.04       0  4996.5    0.05       0  5134.4    0.08       0
  5498.7    0.16       0  5501.4    0.08       0
Bank Sta=4990.5,4996.5
Exp/Cntr=0.3,0.1

Type RM Length L Ch R = 1,21577,333,333,333
BEGIN DESCRIPTION:
Mapping XS 7eb59c60
END DESCRIPTION:
XS GIS Cut Line= 3
      3602342.84     10558953.31      3601874.09     10559799.66
      3601510.66     10560256.55
#Sta/Elev= 30
  4090.8  410.04  4175.4  408.94  4246.9  408.69  4252.6  409.47  4333.9  404.91
  4377.4  403.75  4437.0  399.47  4458.7  398.99  4480.5  397.39  4487.3  395.91
  4545.7  392.74  4664.8  390.65  4708.3  388.94  4808.3  388.48  4811.1  387.98
  4814.3  388.48  4870.9  389.49  4892.6  388.81  5008.9  389.32  5054.1  390.35
  5090.2  390.13  5104.7  391.49  5119.1  390.84  5168.7  392.87  5204.0  395.41
  5232.8  395.30  5340.1  399.80  5404.0  403.72  5467.9  406.00  5642.1  409.77
#Mann=6,-1,0
  4090.8     0.1       0  4175.4    0.08       0  4808.3    0.07       0
  4814.3    0.08       0  5008.9    0.05       0  5054.1    0.08       0
Bank Sta=4808.3,4814.3
Exp/Cntr=0.3,0.1

Type RM Length L Ch R = 1,21244,142,142,142
BEGIN DESCRIPTION:
CAROLINE CREEK 31.0
END DESCRIPTION:
XS GIS Cut Line= 3
      3602217.86     10558737.13      3601574.62     10559690.28
      3601337.65     10560234.53
#Sta/Elev= 30
  4120.8  410.92  4272.5  409.05  4389.3  410.04  4510.5  404.83  4580.6  399.14
  4698.1  392.09  4821.0  387.34  4827.0  388.59  4842.0  386.97  4863.0  378.97
  4878.0  381.58  4899.0  388.43  4928.9  391.39  4934.9  389.53  4943.9  391.56
  4956.9  391.35  5000.9  381.29  5006.9  375.51  5018.9  375.40  5021.6  374.90
  5024.9  375.40  5036.8  376.04  5042.9  381.88  5078.8  386.33  5210.3  390.27
  5367.1  401.36  5542.0  409.79  5639.0  411.17  5739.6  411.92  5864.3  410.55
#Mann=5,-1,0
  4120.8    0.08       0  4580.6    0.05       0  5018.9    0.04       0
  5024.9    0.05       0  5639.0    0.08       0
Bank Sta=5018.9,5024.9
Exp/Cntr=0.3,0.1

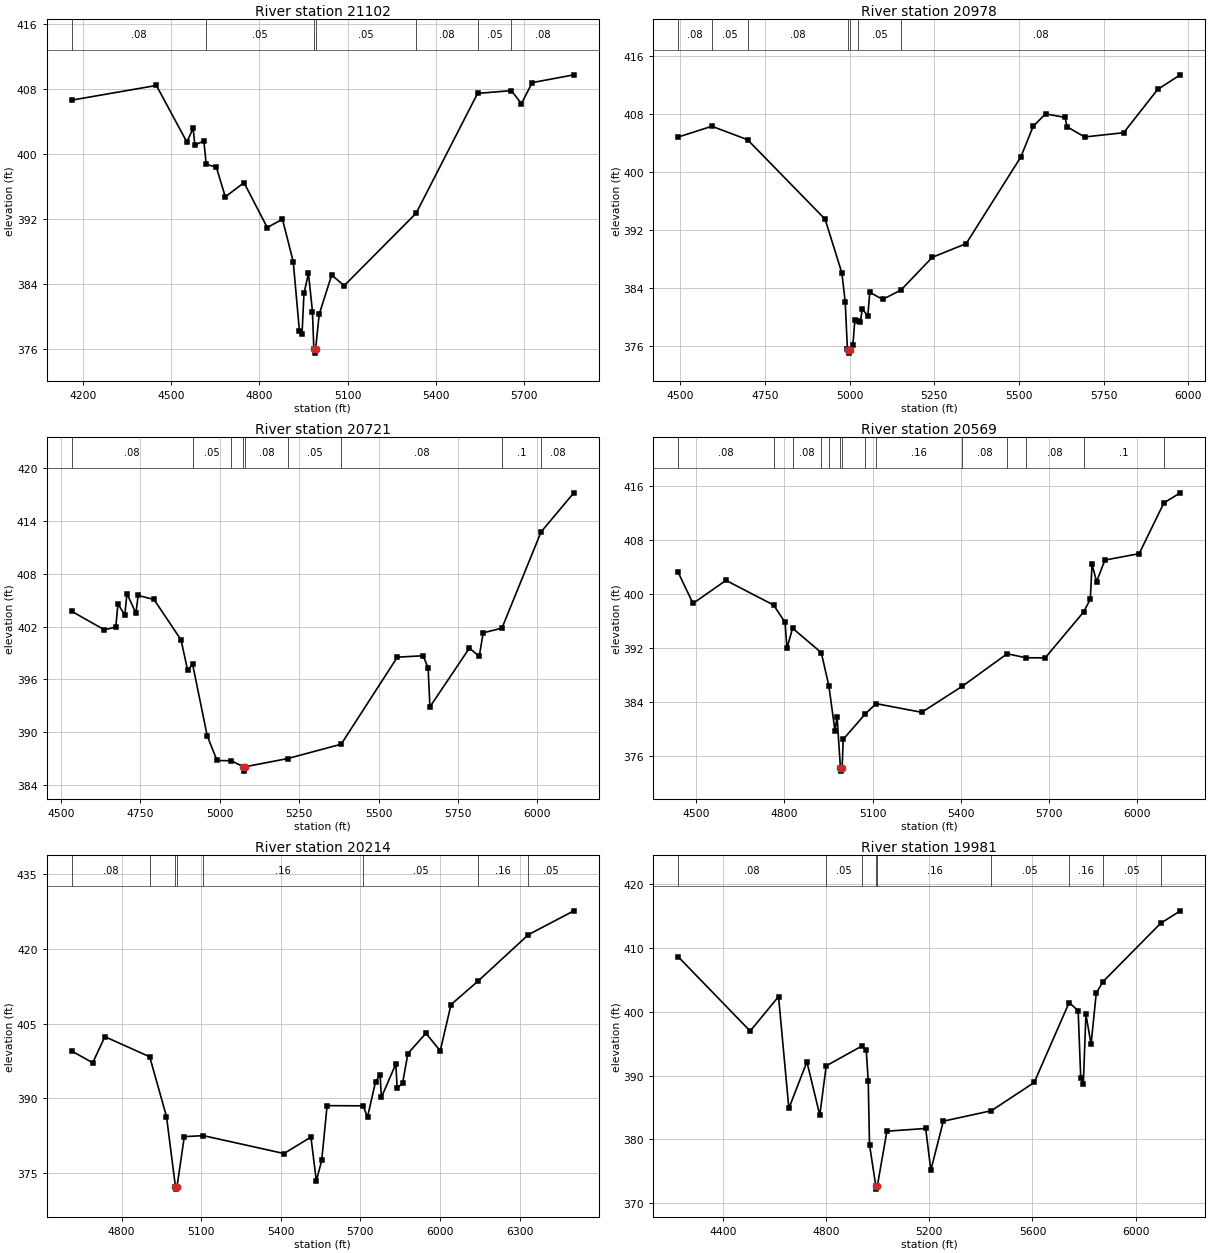
Type RM Length L Ch R = 1,21102,124,124,124
BEGIN DESCRIPTION:
Mapping XS deeea1bf
END DESCRIPTION:
XS GIS Cut Line= 3
      3602095.47     10558638.17      3601368.89     10559791.85
      3601189.19     10560083.53
#Sta/Elev= 30
  4162.9  406.64  4450.4  408.45  4554.0  401.48  4575.2  403.17  4581.1  401.12
  4611.7  401.60  4619.8  398.73  4654.1  398.38  4684.6  394.72  4748.2  396.47
  4827.1  390.94  4878.9  391.96  4915.4  386.73  4936.6  378.13  4945.3  377.83
  4951.9  382.81  4967.2  385.29  4980.7  380.59  4985.4  375.96  4988.1  375.46
  4991.4  375.96  5003.7  380.26  5046.1  385.09  5088.5  383.77  5333.1  392.71
  5541.8  407.47  5656.6  407.81  5690.8  406.22  5727.5  408.80  5868.9  409.76
#Mann=7,-1,0
  4162.9    0.08       0  4619.8    0.05       0  4985.4    0.04       0
  4991.4    0.05       0  5333.1    0.08       0  5541.8    0.05       0
  5656.6    0.08       0
Bank Sta=4985.4,4991.4
Exp/Cntr=0.3,0.1

Type RM Length L Ch R = 1,20978,257,257,257
BEGIN DESCRIPTION:
CAROLINE CREEK 30.0
END DESCRIPTION:
XS GIS Cut Line= 3
      3601819.40     10558794.47      3601483.47     10559427.26
      3601075.58     10560076.77
#Sta/Elev= 30
  4493.5  404.86  4593.0  406.35  4698.3  404.49  4927.4  393.52  4977.0  386.09
  4986.8  382.12  4993.4  375.56  4996.0  375.53  4998.8  375.03  5002.0  375.53
  5009.5  376.14  5015.3  379.62  5024.2  379.48  5031.7  379.26  5037.3  381.19
  5053.6  380.13  5059.3  383.42  5097.6  382.45  5151.8  383.75  5244.2  388.26
  5344.3  390.15  5505.7  402.11  5542.2  406.34  5578.7  408.06  5636.4  407.57
  5642.3  406.28  5694.2  404.87  5809.6  405.46  5910.1  411.44  5976.9  413.45
#Mann=7,-1,0
  4493.5    0.08       0  4593.0    0.05       0  4698.3    0.08       0
  4996.0    0.07       0  5002.0    0.08       0  5024.2    0.05       0
  5151.8    0.08       0
Bank Sta=4996,5002
Exp/Cntr=0.3,0.1

Type RM Length L Ch R = 1,20721,152,152,152
BEGIN DESCRIPTION:
Mapping XS c86cc570
END DESCRIPTION:
XS GIS Cut Line= 4
      3601762.11     10558677.26      3601470.45     10558992.37
      3601327.22     10559190.28      3600881.92     10559979.32
#Sta/Elev= 30
  4534.7  403.73  4637.5  401.63  4673.2  401.95  4680.0  404.57  4701.5  403.31
  4708.3  405.75  4736.7  403.52  4743.5  405.54  4793.4  405.08  4878.4  400.49
  4899.4  397.01  4914.8  397.73  4961.0  389.56  4991.7  386.77  5036.9  386.74
  5074.5  386.06  5077.3  385.56  5080.5  386.06  5214.1  386.99  5382.3  388.62
  5559.0  398.52  5639.9  398.68  5655.8  397.33  5661.6  392.87  5785.8  399.55
  5816.8  398.61  5829.1  401.29  5888.1  401.82  6011.4  412.77  6114.4  417.21
#Mann=9,-1,0
  4534.7    0.08       0  4914.8    0.05       0  5036.9    0.08       0
  5074.5    0.04       0  5080.5    0.08       0  5214.1    0.05       0
  5382.3    0.08       0  5888.1     0.1       0  6011.4    0.08       0
Bank Sta=5074.5,5080.5
Exp/Cntr=0.3,0.1

Type RM Length L Ch R = 1,20569,355,355,355
BEGIN DESCRIPTION:
Mapping XS d6d84530
END DESCRIPTION:
XS GIS Cut Line= 5
      3601808.94     10558591.33      3601585.03     10558635.60
      3601259.51     10559026.22      3601121.49     10559341.33
      3600798.58     10559880.38
#Sta/Elev= 30
  4438.3  403.23  4488.6  398.64  4600.7  402.06  4763.2  398.40  4802.0  395.82
  4808.5  391.98  4827.4  394.97  4925.3  391.35  4951.1  386.40  4971.9  379.76
  4979.0  381.87  4990.3  374.28  4993.1  373.78  4996.3  374.28  4999.8  378.49
  5074.7  382.24  5111.6  383.79  5267.1  382.50  5405.5  386.37  5558.0  391.18
  5622.0  390.59  5687.4  390.57  5817.9  397.36  5841.0  399.26  5846.9  404.45
  5862.4  401.87  5890.7  405.07  6007.3  406.02  6091.6  413.55  6147.4  415.04
#Mann=14,-1,0
  4438.3    0.08       0  4763.2    0.05       0  4827.4    0.08       0
  4925.3    0.12       0  4951.1    0.05       0  4990.3    0.04       0
  4996.3    0.05       0  5074.7    0.08       0  5111.6    0.16       0
  5405.5    0.08       0  5558.0    0.16       0  5622.0    0.08       0
  5817.9     0.1       0  6091.6    0.08       0
Bank Sta=4990.3,4996.3
Exp/Cntr=0.3,0.1

Type RM Length L Ch R = 1,20214,233,233,233
BEGIN DESCRIPTION:
CAROLINE CREEK 29.0
END DESCRIPTION:
XS GIS Cut Line= 2
      3601817.33     10558533.51      3599953.67     10558861.48
#Sta/Elev= 30
  4612.4  399.50  4691.3  397.15  4737.2  402.38  4906.1  398.35  4969.4  386.39
  5003.1  372.35  5005.8  371.85  5009.1  372.35  5036.5  382.36  5108.3  382.56
  5412.2  378.98  5513.8  382.27  5534.1  373.51  5554.4  377.59  5574.7  388.57
  5710.6  388.53  5727.0  386.28  5757.4  393.36  5774.4  394.78  5779.4  390.23
  5833.7  396.90  5838.7  392.11  5859.0  393.02  5879.3  399.00  5947.2  403.07
  6001.1  399.54  6041.8  408.81  6143.4  413.50  6333.6  422.81  6504.7  427.58
#Mann=8,-1,0
  4612.4    0.08       0  4906.1    0.16       0  5003.1    0.07       0
  5009.1    0.16       0  5108.3    0.16       0  5710.6    0.05       0
  6143.4    0.16       0  6333.6    0.05       0
Bank Sta=5003.1,5009.1
Exp/Cntr=0.3,0.1

Type RM Length L Ch R = 1,19981,1099,1099,1099
BEGIN DESCRIPTION:
CAROLINE CREEK 28.0
END DESCRIPTION:
XS GIS Cut Line= 3
      3602148.58     10558391.15      3601468.02     10558391.15
      3600204.36     10558477.94
#Sta/Elev= 30
  4226.1  408.60  4505.1  396.97  4615.1  402.37  4655.1  384.85  4725.1  392.16
  4775.1  383.80  4800.0  391.53  4938.1  394.62  4955.2  394.04  4962.9  389.21
  4967.9  379.18  4992.3  372.72  4995.0  372.22  4998.3  372.72  5035.4  381.29
  5185.7  381.72  5205.8  375.19  5254.2  382.86  5440.7  384.50  5606.7  388.92
  5742.2  401.44  5777.1  400.15  5787.1  389.69  5797.2  388.72  5807.2  399.59
  5827.2  394.91  5847.3  402.91  5872.8  404.68  6096.6  413.83  6173.3  415.80
#Mann=9,-1,0
  4226.1    0.08       0  4800.0    0.05       0  4938.1    0.16       0
  4992.3    0.07       0  4998.3    0.16       0  5440.7    0.05       0
  5742.2    0.16       0  5872.8    0.05       0  6096.6    0.16       0
Bank Sta=4992.3,4998.3
Exp/Cntr=0.3,0.1

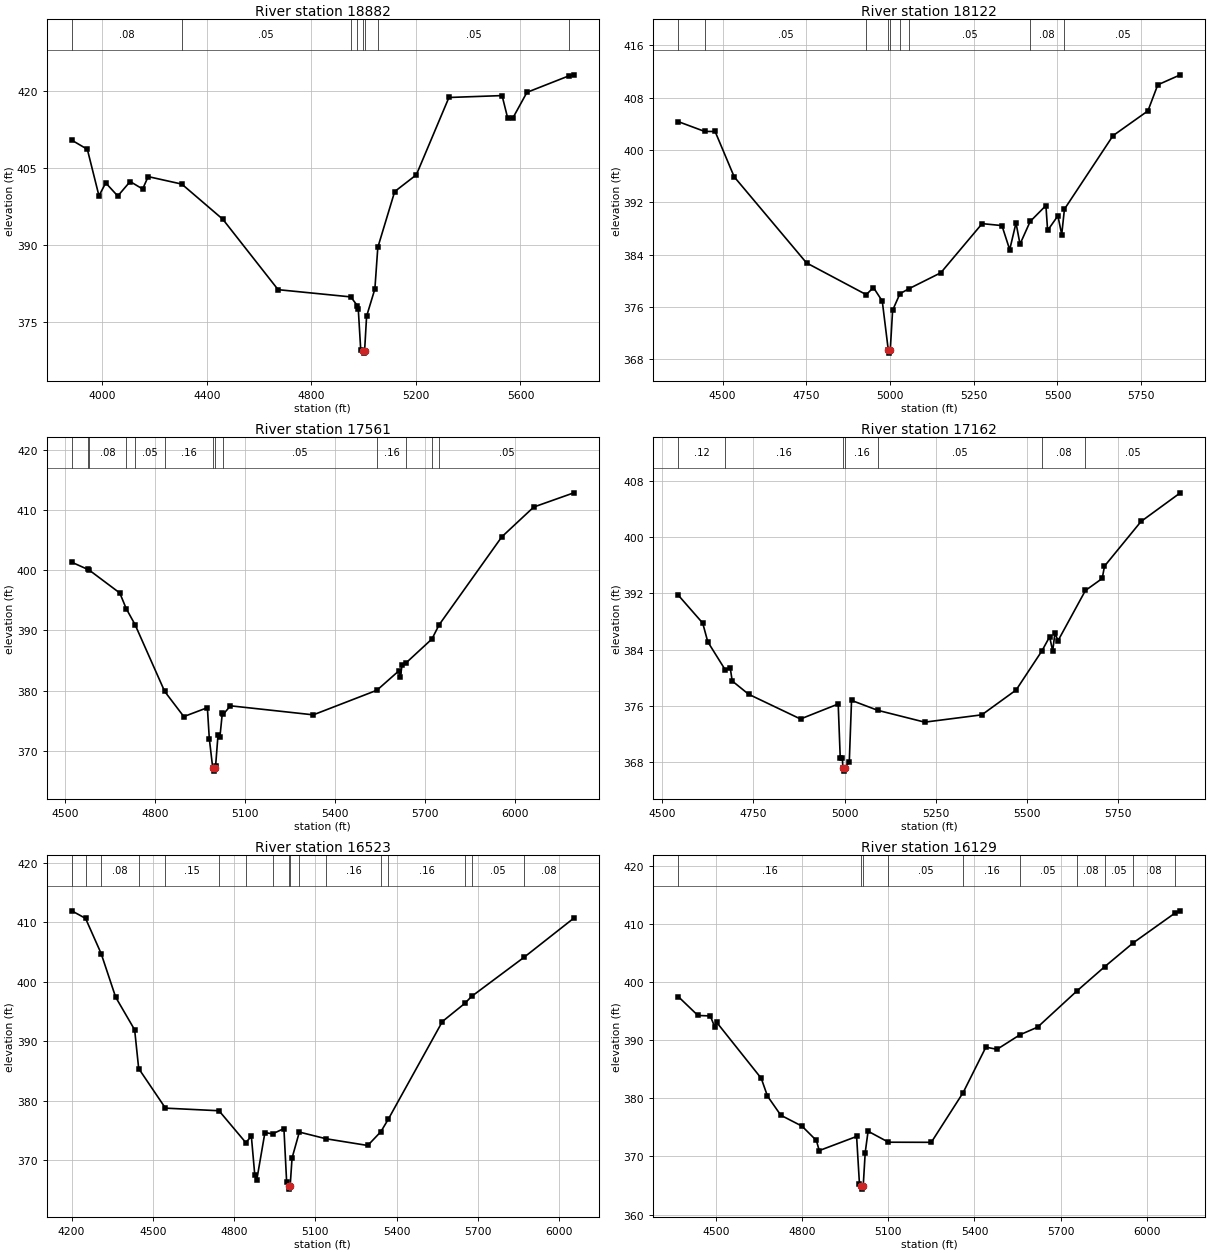
Type RM Length L Ch R = 1,18882,760,760,760
BEGIN DESCRIPTION:
CAROLINE CREEK 27.0
END DESCRIPTION:
XS GIS Cut Line= 2
      3602165.91     10558318.23      3600349.99     10557689.77
#Sta/Elev= 30
  3882.6  410.50  3942.2  408.72  3986.7  399.64  4012.6  402.16  4058.6  399.60
  4106.1  402.43  4153.8  400.97  4175.0  403.39  4303.7  401.93  4460.7  395.07
  4672.3  381.33  4950.6  379.92  4975.6  378.20  4979.2  377.51  4988.6  369.51
  4997.4  369.45  5000.1  368.95  5003.4  369.45  5011.0  376.15  5042.7  381.47
  5053.9  389.57  5118.5  400.47  5201.4  403.74  5326.1  418.83  5529.5  419.20
  5550.6  414.88  5570.1  414.76  5624.7  419.83  5786.7  423.08  5804.2  423.25
#Mann=8,-1,0
  3882.6    0.08       0  4303.7    0.05       0  4950.6    0.08       0
  4975.6    0.16       0  4997.4    0.07       0  5003.4    0.16       0
  5053.9    0.05       0  5786.7    0.08       0
Bank Sta=4997.4,5003.4
Exp/Cntr=0.3,0.1

Type RM Length L Ch R = 1,18122,561,561,561
BEGIN DESCRIPTION:
CAROLINE CREEK 26.0
END DESCRIPTION:
XS GIS Cut Line= 2
      3602112.11     10557740.69      3600654.17     10557391.82
#Sta/Elev= 30
  4367.7  404.35  4446.5  402.85  4477.8  402.84  4534.8  395.91  4750.7  382.76
  4929.0  377.91  4950.6  378.99  4976.9  376.92  4994.8  369.47  4997.5  368.97
  5000.8  369.47  5007.8  375.52  5029.7  378.05  5056.0  378.80  5151.7  381.25
  5275.1  388.76  5334.2  388.46  5357.4  384.78  5376.2  388.86  5388.2  385.63
  5418.5  389.09  5465.5  391.52  5470.6  387.72  5501.3  389.95  5512.7  387.09
  5520.8  390.97  5665.8  402.20  5770.1  405.99  5799.5  409.97  5866.8  411.50
#Mann=9,-1,0
  4367.7    0.08       0  4446.5    0.05       0  4929.0    0.16       0
  4994.8    0.07       0  5000.8    0.16       0  5029.7     0.1       0
  5056.0    0.05       0  5418.5    0.08       0  5520.8    0.05       0
Bank Sta=4994.8,5000.8
Exp/Cntr=0.3,0.1

Type RM Length L Ch R = 1,17561,399,399,399
BEGIN DESCRIPTION:
CAROLINE CREEK 25.0
END DESCRIPTION:
XS GIS Cut Line= 3
      3602096.50     10557646.95      3601638.16     10557058.40
      3600779.95     10556704.71
#Sta/Elev= 30
  4523.5  401.33  4576.9  400.14  4581.2  400.04  4683.6  396.22  4705.1  393.62
  4734.4  390.98  4833.3  379.87  4897.1  375.69  4975.7  377.17  4982.1  372.04
  4993.6  367.13  4996.4  366.63  4999.6  367.13  5003.0  367.40  5011.1  372.60
  5017.4  372.26  5025.6  376.30  5028.3  376.06  5052.7  377.48  5328.9  375.98
  5541.1  380.07  5613.8  383.27  5619.2  382.22  5624.8  384.26  5638.8  384.64
  5724.5  388.58  5748.5  390.94  5957.5  405.55  6064.0  410.50  6197.7  412.86
#Mann=13,-1,0
  4523.5    0.08       0  4576.9    0.16       0  4581.2    0.08       0
  4705.1    0.16       0  4734.4    0.05       0  4833.3    0.16       0
  4993.6    0.07       0  4999.6    0.16       0  5028.3    0.05       0
  5541.1    0.16       0  5638.8    0.08       0  5724.5    0.16       0
  5748.5    0.05       0
Bank Sta=4993.6,4999.6
Exp/Cntr=0.3,0.1

Type RM Length L Ch R = 1,17162,639,639,639
BEGIN DESCRIPTION:
CAROLINE CREEK 24.0
END DESCRIPTION:
XS GIS Cut Line= 3
      3602149.61     10557360.19      3601949.61     10556960.19
      3601199.58     10556410.17
#Sta/Elev= 30
  4543.9  391.75  4611.0  387.78  4625.0  385.11  4673.4  381.09  4686.4  381.44
  4692.0  379.55  4736.8  377.67  4879.3  374.15  4982.7  376.28  4988.3  368.64
  4994.2  368.64  4995.4  367.24  4998.2  366.74  5001.4  367.24  5013.1  368.04
  5019.3  376.79  5091.3  375.38  5220.0  373.70  5376.7  374.74  5470.8  378.27
  5541.7  383.84  5562.7  385.83  5571.1  383.81  5577.3  386.36  5585.8  385.28
  5660.9  392.41  5707.0  394.12  5713.2  395.87  5813.5  402.22  5921.2  406.29
#Mann=7,-1,0
  4543.9    0.12       0  4673.4    0.16       0  4995.4    0.07       0
  5001.4    0.16       0  5091.3    0.05       0  5541.7    0.08       0
  5660.9    0.05       0
Bank Sta=4995.4,5001.4
Exp/Cntr=0.3,0.1

Type RM Length L Ch R = 1,16523,394,394,394
BEGIN DESCRIPTION:
CAROLINE CREEK 23.0
END DESCRIPTION:
XS GIS Cut Line= 3
      3602841.27     10556615.69      3601804.82     10556553.19
      3601034.31     10556287.68
#Sta/Elev= 30
  4200.8  411.96  4251.6  410.69  4309.2  404.77  4362.8  397.42  4432.9  391.92
  4447.8  385.40  4546.6  378.73  4744.3  378.29  4843.1  372.93  4863.7  373.99
  4876.2  367.54  4883.7  366.65  4913.8  374.62  4942.0  374.40  4983.9  375.29
  4993.9  366.32  5000.9  365.59  5003.7  365.09  5006.9  365.59  5013.9  370.32
  5040.8  374.70  5139.6  373.57  5293.3  372.44  5341.7  374.76  5369.1  376.86
  5568.9  393.32  5651.3  396.36  5676.5  397.54  5871.1  404.16  6054.1  410.73
#Mann=17,-1,0
  4200.8    0.08       0  4251.6    0.16       0  4309.2    0.08       0
  4447.8     0.1       0  4546.6    0.15       0  4744.3    0.08       0
  4843.1    0.12       0  4942.0    0.16       0  5000.9    0.07       0
  5006.9    0.16       0  5040.8    0.12       0  5139.6    0.16       0
  5341.7    0.05       0  5369.1    0.16       0  5651.3    0.08       0
  5676.5    0.05       0  5871.1    0.08       0
Bank Sta=5000.9,5006.9
Exp/Cntr=0.3,0.1

Type RM Length L Ch R = 1,16129,270,270,270
BEGIN DESCRIPTION:
CAROLINE CREEK 22.0
END DESCRIPTION:
XS GIS Cut Line= 3
      3602664.21     10556449.03      3602351.70     10556271.94
      3600962.84     10556204.32
#Sta/Elev= 30
  4367.6  397.49  4436.2  394.24  4479.4  394.16  4495.3  392.18  4501.1  393.09
  4656.9  383.43  4678.6  380.37  4725.1  377.08  4799.0  375.20  4849.0  372.74
  4859.0  371.00  4989.2  373.43  4999.2  365.21  5006.2  364.87  5009.0  364.37
  5012.2  364.87  5019.2  370.67  5029.2  374.33  5100.3  372.44  5249.5  372.42
  5360.4  380.97  5439.7  388.79  5478.6  388.42  5558.1  390.91  5619.9  392.23
  5755.7  398.40  5854.5  402.66  5953.4  406.74  6097.5  411.81  6117.3  412.24
#Mann=10,-1,0
  4367.6    0.16       0  5006.2    0.07       0  5012.2    0.16       0
  5100.3    0.05       0  5360.4    0.16       0  5558.1    0.05       0
  5755.7    0.08       0  5854.5    0.05       0  5953.4    0.08       0
  6097.5    0.05       0
Bank Sta=5006.2,5012.2
Exp/Cntr=0.3,0.1