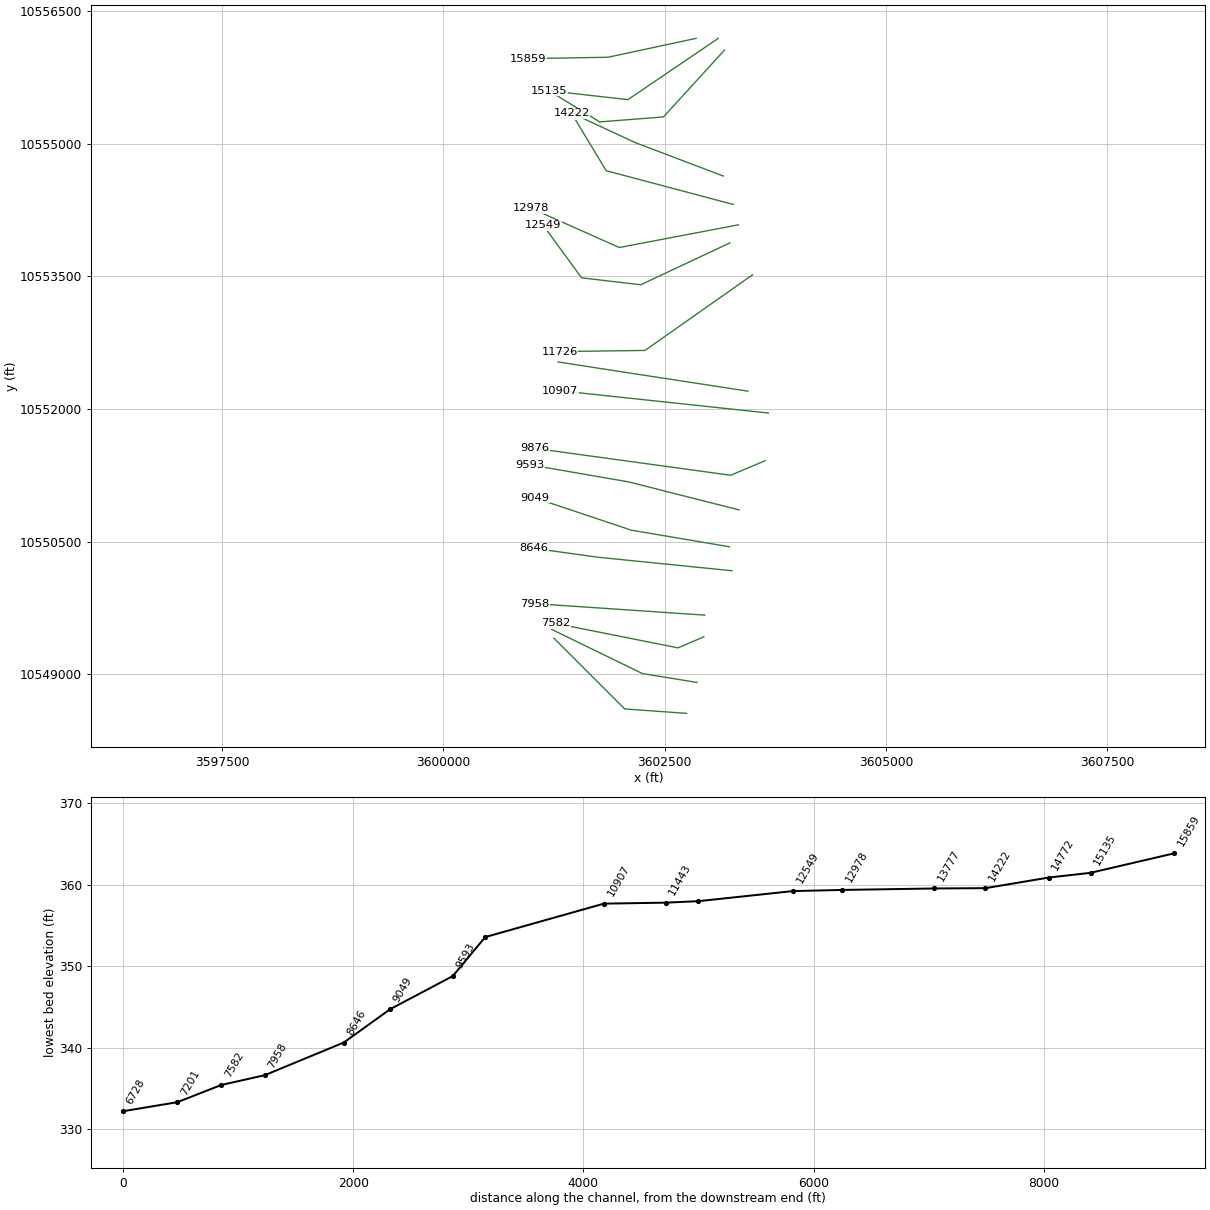
HEC-RAS study CAROLINE CREEK.prj: CAROLINE CREEK Base Level Engineering

--- CAROLINE CREEK.g01 (geometry) --- (continued)

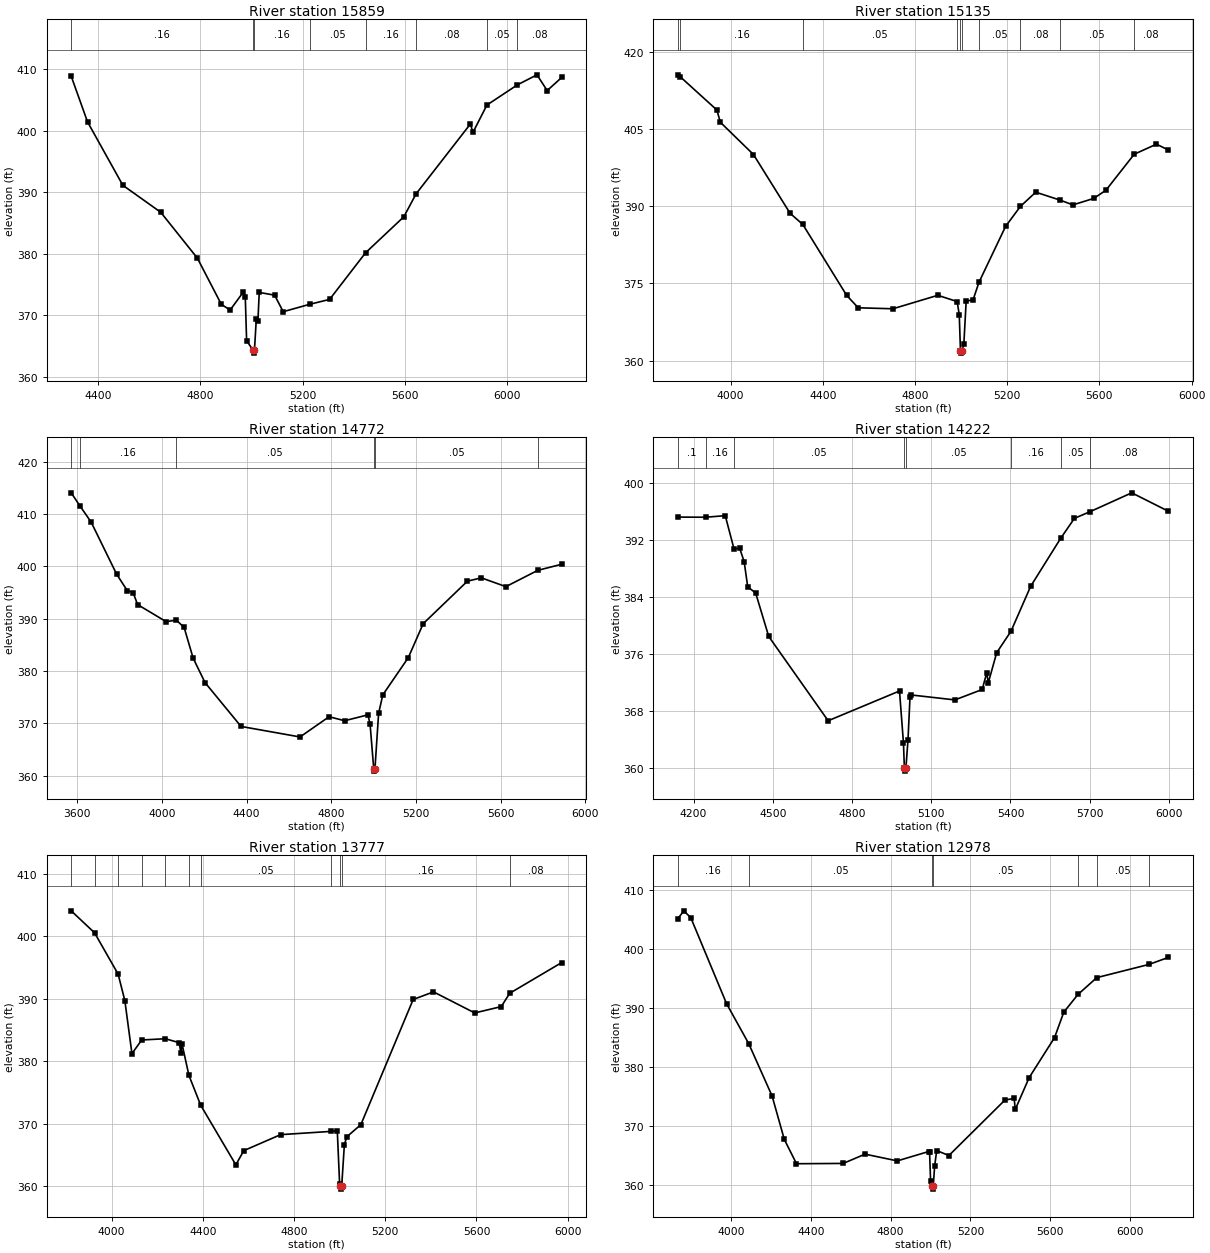
Type RM Length L Ch R = 1,15859,724,724,724
BEGIN DESCRIPTION:
CAROLINE CREEK 21.0
END DESCRIPTION:
XS GIS Cut Line= 3
      3602856.89     10556188.60      3601862.12     10555975.06
      3600962.89     10555959.47
#Sta/Elev= 30
  4295.8  408.89  4359.6  401.46  4497.6  391.14  4645.7  386.75  4788.8  379.29
  4882.5  371.77  4916.9  370.84  4968.1  373.75  4976.1  372.97  4981.3  365.86
  5006.0  364.33  5008.7  363.83  5012.0  364.33  5019.2  369.37  5025.5  369.11
  5030.7  373.71  5090.8  373.26  5124.3  370.57  5227.4  371.77  5305.6  372.57
  5446.0  380.15  5595.8  386.02  5643.7  389.75  5855.8  401.11  5865.8  399.74
  5920.3  404.19  6039.1  407.47  6115.9  409.11  6155.9  406.55  6212.6  408.68
#Mann=8,-1,0
  4295.8    0.16       0  5006.0    0.07       0  5012.0    0.16       0
  5227.4    0.05       0  5446.0    0.16       0  5643.7    0.08       0
  5920.3    0.05       0  6039.1    0.08       0
Bank Sta=5006,5012
Exp/Cntr=0.3,0.1

Type RM Length L Ch R = 1,15135,363,363,363
BEGIN DESCRIPTION:
CAROLINE CREEK 20.0
END DESCRIPTION:
XS GIS Cut Line= 3
      3603106.95     10556188.63      3602086.07     10555495.90
      3601198.09     10555595.72
#Sta/Elev= 30
  3771.7  415.54  3782.8  415.13  3940.9  408.70  3955.9  406.32  4099.6  400.05
  4258.3  388.63  4313.7  386.45  4503.8  372.67  4554.0  370.26  4704.5  370.07
  4899.1  372.69  4982.9  371.47  4992.0  368.93  4997.3  361.95  5000.0  361.45
  5003.3  361.95  5011.9  363.18  5022.0  371.53  5052.2  371.84  5077.7  375.23
  5193.1  386.09  5257.5  389.98  5323.9  392.73  5429.9  391.18  5484.9  390.26
  5575.5  391.52  5628.2  393.11  5750.9  400.11  5847.2  402.06  5899.0  400.93
#Mann=10,-1,0
  3771.7    0.08       0  3782.8    0.16       0  4313.7    0.05       0
  4982.9    0.16       0  4997.3    0.07       0  5003.3    0.16       0
  5077.7    0.05       0  5257.5    0.08       0  5429.9    0.05       0
  5750.9    0.08       0
Bank Sta=4997.3,5003.3
Exp/Cntr=0.3,0.1

Type RM Length L Ch R = 1,14772,550,550,550
BEGIN DESCRIPTION:
CAROLINE CREEK 19.0
END DESCRIPTION:
XS GIS Cut Line= 4
      3603177.25     10556055.83      3602487.12     10555300.58
      3601766.63     10555244.16      3601280.54     10555543.63
#Sta/Elev= 30
  3571.3  414.06  3614.0  411.48  3665.6  408.46  3785.8  398.52  3835.8  395.39
  3863.5  395.00  3885.1  392.70  4019.6  389.44  4067.9  389.72  4104.7  388.34
  4147.2  382.47  4203.3  377.80  4373.6  369.41  4652.1  367.40  4789.5  371.27
  4862.7  370.50  4973.0  371.63  4983.1  369.79  5000.1  361.37  5002.9  360.87
  5006.1  361.37  5023.2  371.89  5043.0  375.44  5163.6  382.57  5233.8  389.05
  5442.8  397.18  5508.5  397.81  5624.4  396.13  5774.7  399.24  5888.0  400.41
#Mann=6,-1,0
  3571.3    0.08       0  3614.0    0.16       0  4067.9    0.05       0
  5000.1    0.03       0  5006.1    0.05       0  5774.7    0.08       0
Bank Sta=5000.1,5006.1
Exp/Cntr=0.3,0.1

Type RM Length L Ch R = 1,14222,445,445,445
BEGIN DESCRIPTION:
CAROLINE CREEK 18.0
END DESCRIPTION:
XS GIS Cut Line= 3
      3603164.21     10554632.18      3602170.27     10555009.79
      3601449.76     10555344.00
#Sta/Elev= 30
  4140.5  395.17  4245.5  395.15  4319.9  395.37  4352.9  390.74  4374.8  390.77
  4391.5  388.93  4405.0  385.40  4435.1  384.53  4484.6  378.44  4709.6  366.63
  4979.8  370.80  4994.8  363.52  4998.2  360.07  5001.0  359.57  5004.2  360.07
  5011.9  363.91  5019.6  369.97  5024.9  370.24  5189.6  369.55  5293.0  371.01
  5310.4  373.38  5315.9  371.93  5347.8  376.16  5402.1  379.18  5476.3  385.46
  5589.7  392.17  5642.1  394.99  5702.7  395.95  5859.3  398.57  5998.0  395.99
#Mann=8,-1,0
  4140.5     0.1       0  4245.5    0.16       0  4352.9    0.05       0
  4998.2    0.03       0  5004.2    0.05       0  5402.1    0.16       0
  5589.7    0.05       0  5702.7    0.08       0
Bank Sta=4998.2,5004.2
Exp/Cntr=0.3,0.1

Type RM Length L Ch R = 1,13777,799,799,799
BEGIN DESCRIPTION:
CAROLINE CREEK 17.0
END DESCRIPTION:
XS GIS Cut Line= 3
      3603277.00     10554311.01      3601840.41     10554692.95
      3601497.51     10555261.56
#Sta/Elev= 30
  3823.2  404.07  3925.7  400.55  4029.1  393.93  4058.5  389.68  4089.5  381.22
  4132.5  383.40  4235.9  383.60  4296.5  382.97  4304.1  381.35  4309.2  382.75
  4339.3  377.74  4390.8  372.97  4545.0  363.42  4580.0  365.69  4741.4  368.25
  4962.6  368.77  4989.8  368.89  5000.1  360.30  5003.2  360.03  5005.9  359.53
  5009.2  360.03  5020.8  366.60  5031.1  367.89  5093.2  369.85  5322.5  389.88
  5411.6  391.10  5592.3  387.73  5708.8  388.74  5745.6  390.87  5973.7  395.79
#Mann=11,-1,0
  3823.2    0.16       0  3925.7    0.05       0  4029.1     0.1       0
  4132.5    0.15       0  4235.9     0.1       0  4339.3    0.08       0
  4390.8    0.05       0  4962.6    0.16       0  5003.2    0.07       0
  5009.2    0.16       0  5745.6    0.08       0
Bank Sta=5003.2,5009.2
Exp/Cntr=0.3,0.1

Type RM Length L Ch R = 1,12978,429,429,429
BEGIN DESCRIPTION:
CAROLINE CREEK 16.0
END DESCRIPTION:
XS GIS Cut Line= 3
      3603333.43     10554080.96      3601987.98     10553824.89
      3600994.29     10554267.50
#Sta/Elev= 30
  3734.0  405.15  3764.1  406.46  3799.0  405.28  3978.0  390.74  4089.1  383.97
  4206.1  375.11  4267.2  367.77  4328.3  363.65  4562.2  363.70  4671.7  365.27
  4833.4  364.13  4989.9  365.71  4995.0  365.61  5000.1  360.73  5007.3  359.85
  5010.1  359.35  5013.3  359.85  5020.5  363.26  5030.7  365.88  5091.8  365.04
  5372.3  374.42  5418.8  374.72  5424.3  372.84  5494.0  378.23  5621.1  385.00
  5667.6  389.32  5738.7  392.31  5832.6  395.15  6093.4  397.38  6191.4  398.57
#Mann=7,-1,0
  3734.0    0.16       0  4089.1    0.05       0  5007.3    0.03       0
  5013.3    0.05       0  5738.7    0.08       0  5832.6    0.05       0
  6093.4    0.08       0
Bank Sta=5007.3,5013.3
Exp/Cntr=0.3,0.1

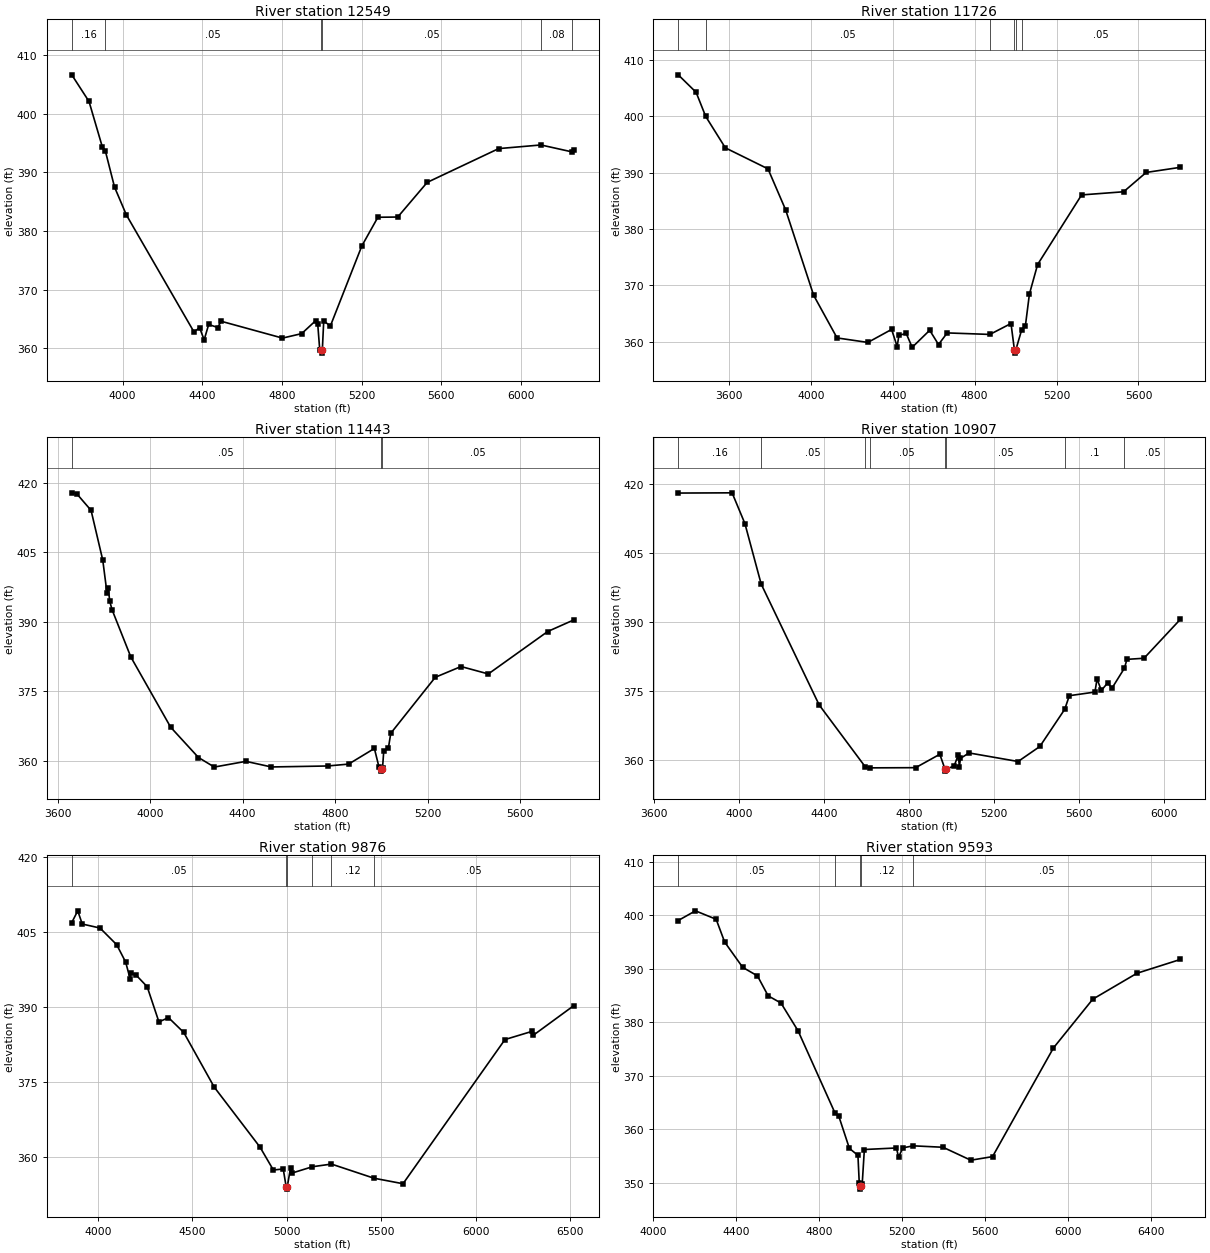
Type RM Length L Ch R = 1,12549,823,823,823
BEGIN DESCRIPTION:
CAROLINE CREEK 15.0
END DESCRIPTION:
XS GIS Cut Line= 4
      3603237.95     10553876.96      3602231.04     10553403.88
      3601562.64     10553482.01      3601129.16     10554075.87
#Sta/Elev= 30
  3745.1  406.59  3831.7  402.05  3898.0  394.38  3913.6  393.64  3959.8  387.48
  4019.5  382.72  4358.6  362.82  4386.9  363.54  4409.7  361.47  4432.5  364.09
  4478.1  363.57  4494.6  364.64  4803.0  361.77  4899.3  362.53  4969.8  364.74
  4979.9  364.18  4989.9  359.82  4997.0  359.71  4999.8  359.21  5003.0  359.71
  5010.1  364.71  5043.2  363.81  5201.4  377.46  5281.9  382.34  5381.6  382.38
  5529.6  388.28  5888.5  394.03  6100.7  394.65  6255.3  393.48  6265.8  393.72
#Mann=6,-1,0
  3745.1    0.16       0  3913.6    0.05       0  4997.0    0.03       0
  5003.0    0.05       0  6100.7    0.08       0  6255.3    0.05       0
Bank Sta=4997,5003
Exp/Cntr=0.3,0.1

Type RM Length L Ch R = 1,11726,283,283,283
BEGIN DESCRIPTION:
CAROLINE CREEK 14.0
END DESCRIPTION:
XS GIS Cut Line= 3
      3603494.04     10553516.72      3602278.78     10552661.70
      3601312.78     10552648.70
#Sta/Elev= 30
  3352.4  407.40  3439.6  404.30  3486.4  400.02  3582.5  394.43  3790.7  390.70
  3876.9  383.42  4013.7  368.24  4128.1  360.67  4278.5  359.87  4394.4  362.18
  4421.6  359.14  4430.1  361.14  4465.8  361.46  4494.9  359.00  4580.5  362.03
  4623.5  359.50  4666.1  361.56  4874.3  361.29  4977.5  363.23  4994.5  358.47
  4997.2  357.97  5000.5  358.47  5029.9  362.14  5047.5  362.73  5067.5  368.47
  5107.5  373.71  5322.3  386.07  5527.5  386.63  5637.6  390.06  5804.4  390.97
#Mann=6,-1,0
  3352.4    0.16       0  3486.4    0.05       0  4874.3    0.16       0
  4994.5    0.07       0  5000.5    0.16       0  5029.9    0.05       0
Bank Sta=4994.5,5000.5
Exp/Cntr=0.3,0.1

Type RM Length L Ch R = 1,11443,536,536,536
BEGIN DESCRIPTION:
CAROLINE CREEK 13.0
END DESCRIPTION:
XS GIS Cut Line= 3
      3603442.00     10552201.62      3601970.62     10552427.32
      3601297.93     10552531.48
#Sta/Elev= 30
  3661.6  417.87  3682.2  417.72  3745.0  414.08  3795.5  403.34  3813.9  396.20
  3818.9  397.32  3825.9  394.41  3836.0  392.59  3916.9  382.42  4088.9  367.27
  4209.0  360.73  4277.4  358.67  4414.2  359.90  4524.0  358.69  4766.8  358.90
  4857.8  359.31  4969.1  362.68  4989.3  358.60  4996.3  358.29  4999.1  357.79
  5002.3  358.29  5004.4  358.51  5009.6  362.18  5029.8  362.83  5039.9  365.96
  5232.2  378.05  5343.5  380.37  5461.4  378.77  5717.9  387.93  5830.9  390.44
#Mann=3,-1,0
  3661.6    0.05       0  4996.3    0.03       0  5002.3    0.05       0
Bank Sta=4996.3,5002.3
Exp/Cntr=0.3,0.1

Type RM Length L Ch R = 1,10907,1031,1031,1031
BEGIN DESCRIPTION:
CAROLINE CREEK 12.0
END DESCRIPTION:
XS GIS Cut Line= 2
      3603672.00     10551954.23      3601319.53     10552205.97
#Sta/Elev= 30
  3713.0  418.05  3966.8  418.10  4027.2  411.42  4103.8  398.29  4377.0  372.05
  4595.0  358.56  4614.5  358.38  4831.7  358.42  4945.6  361.33  4969.5  358.17
  4972.3  357.67  4975.5  358.17  5012.8  358.74  5032.8  361.23  5037.8  358.59
  5042.9  360.43  5083.2  361.62  5314.5  359.76  5416.9  363.02  5534.4  371.11
  5555.9  374.05  5676.5  374.84  5686.6  377.68  5706.7  375.19  5736.9  376.84
  5757.0  375.69  5815.5  380.02  5827.4  381.94  5907.9  382.18  6078.9  390.62
#Mann=8,-1,0
  3713.0    0.16       0  4103.8    0.05       0  4595.0    0.16       0
  4614.5    0.05       0  4969.5    0.03       0  4975.5    0.05       0
  5534.4     0.1       0  5815.5    0.05       0
Bank Sta=4969.5,4975.5
Exp/Cntr=0.3,0.1

Type RM Length L Ch R = 1,9876,283,283,283
BEGIN DESCRIPTION:
CAROLINE CREEK 11.0
END DESCRIPTION:
XS GIS Cut Line= 3
      3603637.31     10551416.05      3603246.66     10551251.11
      3601033.85     10551554.83
#Sta/Elev= 30
  3861.2  406.88  3892.9  409.22  3916.6  406.58  4010.7  405.78  4098.9  402.45
  4146.3  398.98  4170.0  395.66  4175.4  396.73  4199.1  396.47  4260.3  394.05
  4322.6  387.00  4373.1  387.87  4453.9  384.90  4615.4  373.96  4857.6  361.97
  4928.3  357.39  4980.5  357.60  4995.9  354.07  4998.7  353.57  5001.9  354.07
  5019.1  357.77  5029.2  356.81  5135.4  358.05  5235.8  358.58  5461.1  355.75
  5614.6  354.65  6154.2  383.48  6298.4  385.13  6303.5  384.32  6518.8  390.27
#Mann=6,-1,0
  3861.2    0.05       0  4995.9    0.03       0  5001.9    0.05       0
  5135.4    0.07       0  5235.8    0.12       0  5461.1    0.05       0
Bank Sta=4995.9,5001.9
Exp/Cntr=0.3,0.1

Type RM Length L Ch R = 1,9593,544,544,544
BEGIN DESCRIPTION:
CAROLINE CREEK 10.0
END DESCRIPTION:
XS GIS Cut Line= 3
      3603340.13     10550859.61      3602097.07     10551175.58
      3600973.32     10551369.81
#Sta/Elev= 30
  4120.1  399.03  4203.2  400.84  4303.1  399.26  4344.1  395.00  4431.1  390.27
  4502.4  388.67  4554.0  384.94  4615.9  383.59  4698.4  378.39  4876.6  363.02
  4894.5  362.48  4946.1  356.40  4987.3  355.10  4993.8  349.85  4996.0  349.28
  4998.7  348.78  5002.0  349.28  5008.0  349.77  5018.3  356.19  5173.1  356.48
  5183.4  354.77  5204.0  356.50  5254.4  356.88  5398.0  356.61  5532.0  354.19
  5636.9  354.86  5930.8  375.19  6120.6  384.31  6333.8  389.16  6543.1  391.74
#Mann=5,-1,0
  4120.1    0.05       0  4876.6    0.12       0  4996.0    0.07       0
  5002.0    0.12       0  5254.4    0.05       0
Bank Sta=4996,5002
Exp/Cntr=0.3,0.1

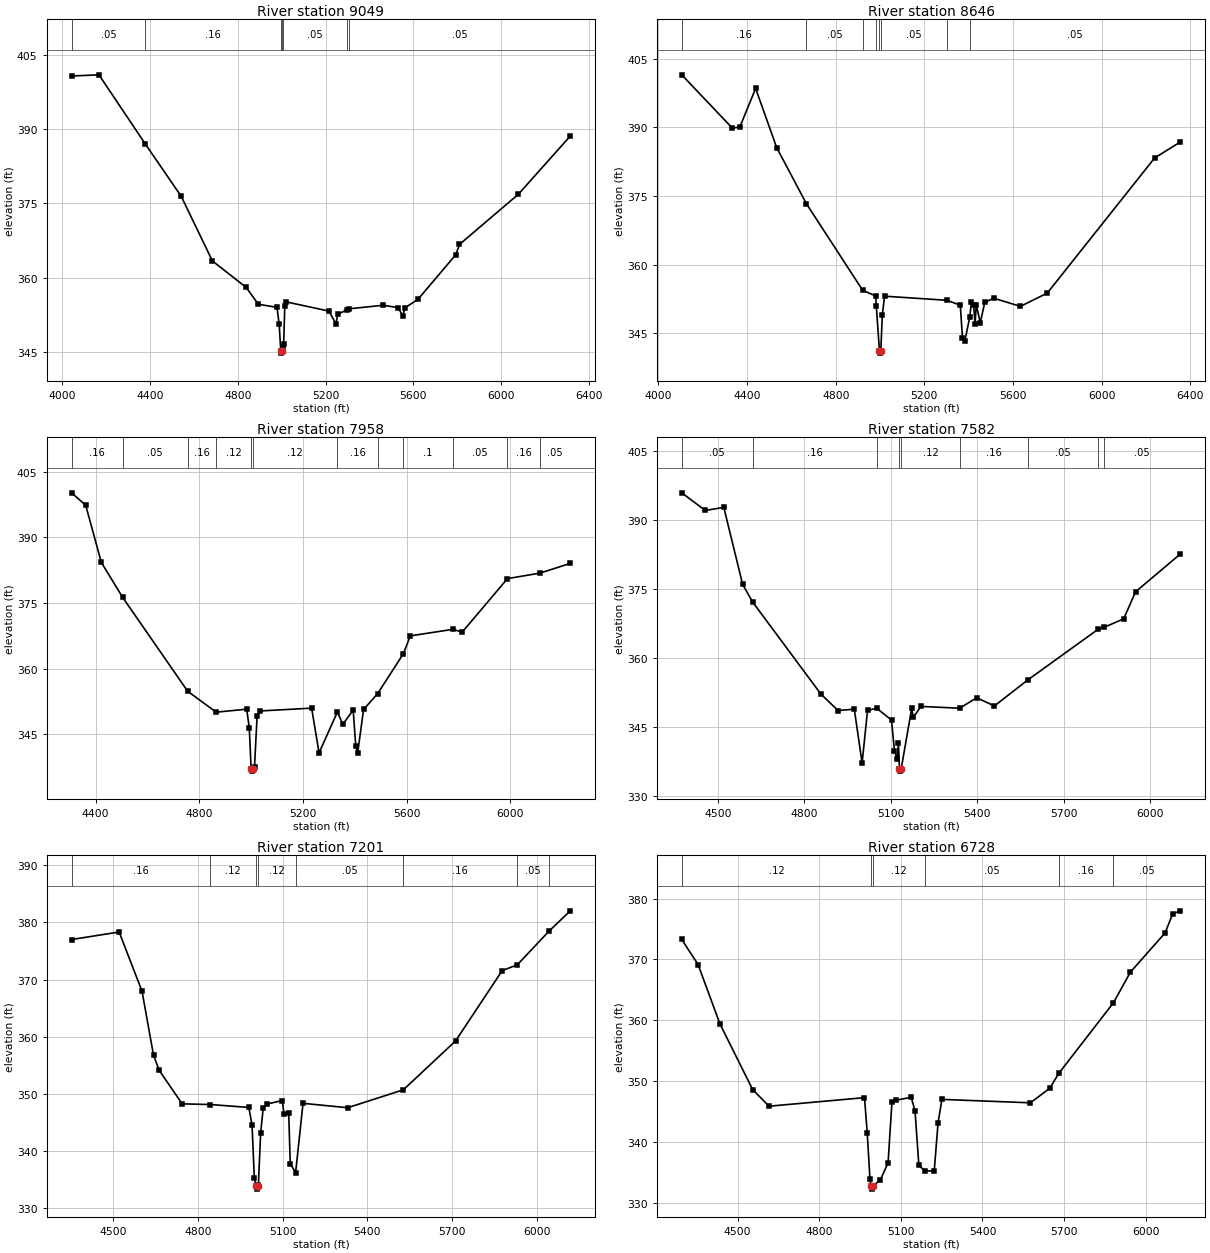
Type RM Length L Ch R = 1,9049,403,403,403
BEGIN DESCRIPTION:
CAROLINE CREEK 9.0
END DESCRIPTION:
XS GIS Cut Line= 3
      3603232.45     10550442.95      3602124.85     10550630.45
      3601034.55     10550995.04
#Sta/Elev= 30
  4042.4  400.75  4167.0  400.99  4379.1  386.96  4542.2  376.41  4684.2  363.35
  4838.1  358.01  4893.4  354.60  4978.4  353.98  4988.5  350.55  4995.7  345.22
  4998.4  344.72  5001.7  345.22  5006.0  345.98  5008.8  346.48  5014.1  354.28
  5019.2  355.09  5215.5  353.22  5247.1  350.64  5255.6  352.58  5297.3  353.48
  5308.9  353.69  5462.9  354.40  5531.3  353.91  5550.9  352.26  5562.9  353.91
  5620.8  355.58  5793.4  364.62  5810.3  366.70  6078.1  376.82  6315.4  388.62
#Mann=7,-1,0
  4042.4    0.05       0  4379.1    0.16       0  4995.7    0.07       0
  5001.7    0.16       0  5006.0    0.05       0  5297.3    0.16       0
  5308.9    0.05       0
Bank Sta=4995.7,5001.7
Exp/Cntr=0.3,0.1

Type RM Length L Ch R = 1,8646,688,688,688
BEGIN DESCRIPTION:
CAROLINE CREEK 8.0
END DESCRIPTION:
XS GIS Cut Line= 3
      3603260.24     10550172.11      3601746.37     10550324.89
      3601024.05     10550425.12
#Sta/Elev= 30
  4105.1  401.48  4333.4  389.83  4367.1  390.06  4438.5  398.51  4533.5  385.56
  4667.6  373.30  4921.5  354.37  4980.2  353.13  4983.1  350.93  4997.3  341.13
  5000.0  340.63  5003.3  341.13  5010.3  349.02  5020.4  353.08  5302.5  352.18
  5362.1  351.10  5372.1  343.96  5382.2  343.19  5404.8  348.50  5412.3  351.78
  5422.4  351.20  5428.9  346.93  5434.0  351.17  5452.5  347.30  5472.6  351.72
  5512.8  352.64  5633.7  350.86  5754.6  353.75  6239.2  383.30  6355.9  386.82
#Mann=8,-1,0
  4105.1    0.16       0  4667.6    0.05       0  4921.5    0.16       0
  4983.1    0.05       0  4997.3    0.03       0  5003.3    0.05       0
  5302.5    0.16       0  5404.8    0.05       0
Bank Sta=4997.3,5003.3
Exp/Cntr=0.3,0.1

Type RM Length L Ch R = 1,7958,376,376,376
BEGIN DESCRIPTION:
CAROLINE CREEK 7.0
END DESCRIPTION:
XS GIS Cut Line= 2
      3602954.02     10549670.38      3601033.42     10549800.50
#Sta/Elev= 30
  4307.2  400.20  4361.7  397.35  4421.9  384.30  4504.1  376.33  4755.2  354.87
  4865.1  350.09  4983.2  350.77  4993.2  346.38  5000.2  337.12  5002.9  336.62
  5006.2  337.12  5013.2  337.58  5023.2  349.16  5033.3  350.36  5233.7  351.01
  5262.4  340.79  5333.2  350.14  5354.0  347.32  5394.1  350.56  5404.1  342.26
  5411.5  340.80  5434.2  350.71  5488.4  354.32  5587.8  363.44  5614.6  367.52
  5778.5  369.01  5815.1  368.39  5989.6  380.60  6115.5  381.86  6232.2  384.09
#Mann=12,-1,0
  4307.2    0.16       0  4504.1    0.05       0  4755.2    0.16       0
  4865.1    0.12       0  5000.2    0.07       0  5006.2    0.12       0
  5333.2    0.16       0  5488.4    0.08       0  5587.8     0.1       0
  5778.5    0.05       0  5989.6    0.16       0  6115.5    0.05       0
Bank Sta=5000.2,5006.2
Exp/Cntr=0.3,0.1

Type RM Length L Ch R = 1,7582,381,381,381
BEGIN DESCRIPTION:
CAROLINE CREEK 6.0
END DESCRIPTION:
XS GIS Cut Line= 3
      3602943.63     10549425.60      3602651.93     10549300.58
      3601266.52     10549576.63
#Sta/Elev= 30
  4374.4  395.98  4456.0  392.14  4520.2  392.82  4585.5  376.07  4620.3  372.22
  4857.3  352.17  4916.7  348.61  4972.9  348.91  5000.0  337.19  5018.8  348.63
  5050.6  349.12  5102.0  346.54  5112.2  339.83  5121.0  338.13  5126.1  341.45
  5129.6  335.93  5132.3  335.43  5135.6  335.93  5172.1  349.12  5177.2  347.10
  5204.0  349.51  5338.1  349.12  5397.7  351.39  5458.9  349.61  5574.3  355.25
  5819.7  366.34  5838.8  366.70  5907.5  368.57  5948.5  374.44  6104.4  382.70
#Mann=9,-1,0
  4374.4    0.05       0  4620.3    0.16       0  5050.6    0.12       0
  5129.6    0.07       0  5135.6    0.12       0  5338.1    0.16       0
  5574.3    0.05       0  5819.7     0.1       0  5838.8    0.05       0
Bank Sta=5129.6,5135.6
Exp/Cntr=0.3,0.1

Type RM Length L Ch R = 1,7201,473,473,473
BEGIN DESCRIPTION:
CAROLINE CREEK 5.0
END DESCRIPTION:
XS GIS Cut Line= 3
      3602865.51     10548909.95      3602249.61     10549010.19
      3601224.83     10549508.93
#Sta/Elev= 30
  4353.9  377.02  4522.0  378.33  4603.0  367.96  4643.6  356.77  4663.8  354.10
  4744.9  348.25  4844.5  348.13  4980.7  347.62  4992.0  344.54  5000.1  335.31
  5005.9  333.82  5008.7  333.32  5011.9  333.82  5014.5  334.09  5022.4  343.15
  5031.5  347.50  5044.6  348.21  5099.1  348.83  5104.7  346.52  5121.7  346.61
  5127.2  337.76  5146.2  336.23  5172.3  348.34  5330.2  347.57  5527.2  350.71
  5711.9  359.27  5876.9  371.59  5929.7  372.57  6043.1  378.53  6117.6  382.04
#Mann=8,-1,0
  4353.9    0.16       0  4844.5    0.12       0  5005.9    0.07       0
  5011.9    0.12       0  5146.2    0.05       0  5527.2    0.16       0
  5929.7    0.05       0  6043.1    0.16       0
Bank Sta=5005.9,5011.9
Exp/Cntr=0.3,0.1

Type RM Length L Ch R = 1,6728,547,547,547
BEGIN DESCRIPTION:
CAROLINE CREEK 4.0
END DESCRIPTION:
XS GIS Cut Line= 3
      3602749.62     10548560.19      3602049.61     10548610.19
      3601249.59     10549410.21
#Sta/Elev= 30
  4294.7  373.28  4354.9  369.13  4435.1  359.38  4555.4  348.58  4615.5  345.85
  4966.4  347.26  4976.4  341.51  4986.5  333.85  4991.0  332.71  4993.7  332.21
  4997.0  332.71  5024.8  333.74  5053.1  336.54  5067.2  346.49  5081.3  346.83
  5137.9  347.32  5152.1  345.10  5166.2  336.14  5188.6  335.19  5222.8  335.22
  5236.9  343.16  5251.1  346.97  5576.3  346.41  5647.0  348.79  5681.2  351.29
  5881.5  362.87  5944.0  367.92  6071.3  374.35  6099.6  377.53  6127.9  377.99
#Mann=6,-1,0
  4294.7    0.12       0  4991.0    0.07       0  4997.0    0.12       0
  5188.6    0.05       0  5681.2    0.16       0  5881.5    0.05       0
Bank Sta=4991,4997
Exp/Cntr=0.3,0.1