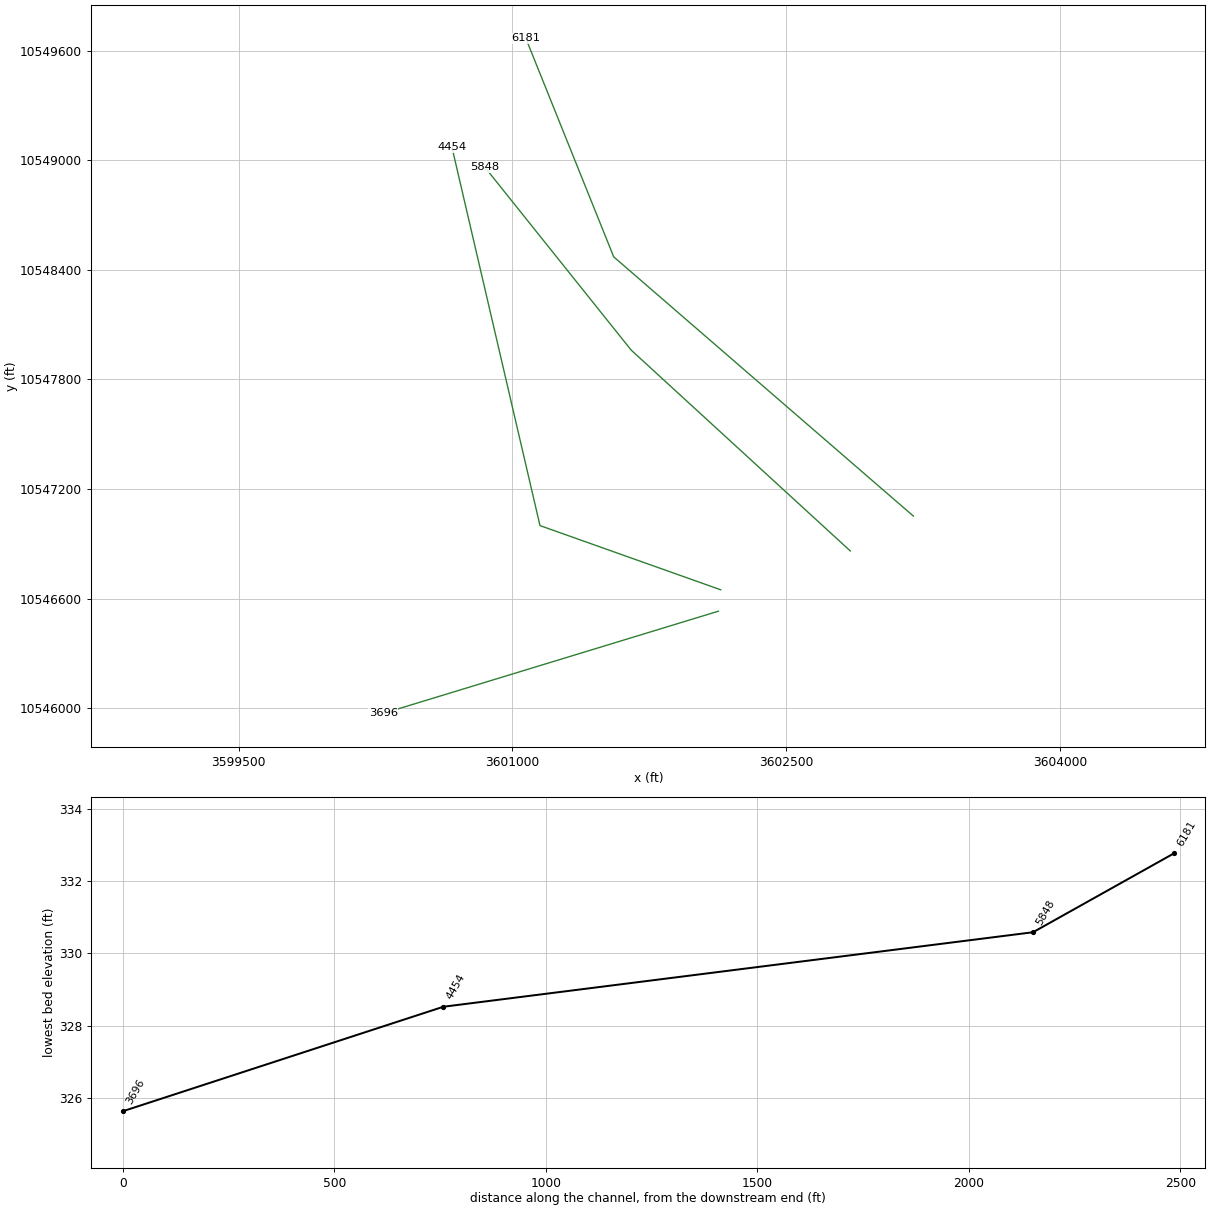
HEC-RAS study CAROLINE CREEK.prj: CAROLINE CREEK Base Level Engineering

--- CAROLINE CREEK.g01 (geometry) --- (continued)

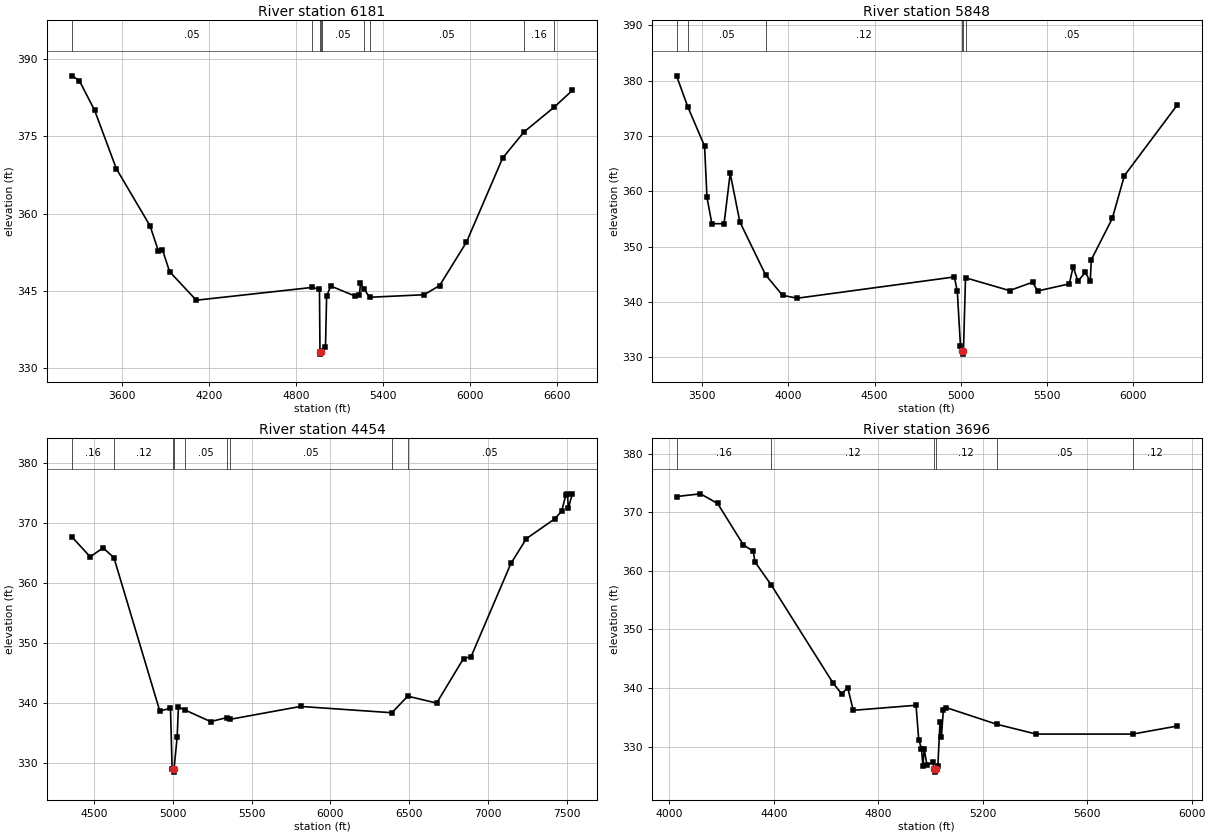
Type RM Length L Ch R = 1,6181,333,333,333
BEGIN DESCRIPTION:
CAROLINE CREEK 3.0
END DESCRIPTION:
XS GIS Cut Line= 3
      3603194.72     10547051.36      3601554.12     10548470.61
      3601073.01     10549666.90
#Sta/Elev= 30
  3250.4  386.70  3302.8  385.79  3409.2  379.99  3558.3  368.73  3791.9  357.61
  3849.0  352.79  3877.5  352.99  3926.8  348.75  4111.1  343.21  4912.7  345.69
  4962.2  345.33  4965.8  333.26  4968.6  332.76  4971.8  333.26  4976.6  333.39
  5003.9  334.23  5011.6  343.98  5040.1  345.96  5210.1  343.99  5238.6  344.18
  5245.2  346.46  5273.2  345.29  5308.0  343.78  5684.8  344.27  5792.3  346.05
  5977.8  354.46  6227.7  370.76  6375.3  375.82  6581.4  380.57  6709.1  383.86
#Mann=9,-1,0
  3250.4    0.05       0  4912.7    0.16       0  4965.8    0.03       0
  4971.8    0.16       0  4976.6    0.05       0  5273.2     0.1       0
  5308.0    0.05       0  6375.3    0.16       0  6581.4    0.05       0
Bank Sta=4965.8,4971.8
Exp/Cntr=0.3,0.1

Type RM Length L Ch R = 1,5848,1394,1394,1394
BEGIN DESCRIPTION:
CAROLINE CREEK 2.0
END DESCRIPTION:
XS GIS Cut Line= 3
      3602849.63     10546860.17      3601649.61     10547960.19
      3600849.63     10548960.16
#Sta/Elev= 30
  3349.9  380.85  3415.3  375.24  3512.7  368.16  3526.6  358.92  3555.0  354.15
  3625.9  354.13  3661.6  363.23  3717.7  354.46  3867.0  344.91  3965.6  341.21
  4050.7  340.68  4963.9  344.52  4981.0  341.96  4999.4  332.12  5010.8  331.08
  5013.6  330.58  5016.8  331.08  5028.7  344.37  5284.4  342.06  5418.8  343.57
  5447.6  341.99  5631.7  343.27  5654.1  346.34  5682.2  343.77  5724.6  345.34
  5753.4  343.73  5759.8  347.64  5881.5  355.09  5951.9  362.82  6258.4  375.56
#Mann=6,-1,0
  3349.9    0.16       0  3415.3    0.05       0  3867.0    0.12       0
  5010.8    0.07       0  5016.8    0.12       0  5028.7    0.05       0
Bank Sta=5010.8,5016.8
Exp/Cntr=0.3,0.1

Type RM Length L Ch R = 1,4454,758,758,758
BEGIN DESCRIPTION:
Mapping XS bd7b4492
END DESCRIPTION:
XS GIS Cut Line= 3
      3602140.08     10546647.68      3601150.48     10546999.25
      3600668.71     10549069.54
#Sta/Elev= 30
  4358.3  367.77  4475.6  364.41  4557.5  365.90  4626.1  364.28  4917.2  338.70
  4984.9  339.17  4995.5  329.04  5001.4  329.02  5004.2  328.52  5007.4  329.02
  5027.4  334.41  5035.3  339.37  5076.1  338.89  5239.6  336.94  5342.1  337.61
  5364.7  337.33  5809.9  339.47  6389.4  338.42  6490.2  341.18  6673.6  340.03
  6844.0  347.46  6891.7  347.75  7144.6  363.30  7242.8  367.44  7423.4  370.75
  7466.0  372.01  7493.7  374.76  7503.5  374.88  7508.6  372.49  7534.1  374.91
#Mann=9,-1,0
  4358.3    0.16       0  4626.1    0.12       0  5001.4    0.07       0
  5007.4    0.12       0  5076.1    0.05       0  5342.1     0.1       0
  5364.7    0.05       0  6389.4    0.08       0  6490.2    0.05       0
Bank Sta=5001.4,5007.4
Exp/Cntr=0.3,0.1

Type RM Length L Ch R = 1,3696,0,0,0
BEGIN DESCRIPTION:
CAROLINE CREEK 1.0
END DESCRIPTION:
XS GIS Cut Line= 2
      3602127.01     10546530.49      3600292.90     10545971.16
#Sta/Elev= 30
  4027.0  372.71  4118.7  373.17  4184.3  371.52  4282.8  364.46  4320.8  363.35
  4327.5  361.53  4390.5  357.55  4626.7  340.83  4659.5  339.01  4682.9  340.03
  4703.8  336.19  4944.3  337.05  4954.7  331.15  4965.2  329.66  4970.6  326.68
  4975.8  329.64  4986.1  326.82  5008.7  327.34  5014.5  326.13  5017.2  325.63
  5020.5  326.13  5027.9  326.69  5036.3  334.26  5041.5  331.69  5048.8  336.19
  5059.3  336.66  5253.2  333.81  5404.3  332.13  5774.3  332.13  5944.5  333.50
#Mann=6,-1,0
  4027.0    0.16       0  4390.5    0.12       0  5014.5    0.07       0
  5020.5    0.12       0  5253.2    0.05       0  5774.3    0.12       0
Bank Sta=5014.5,5020.5
Exp/Cntr=0.3,0.1

Chan Stop Cuts=-1