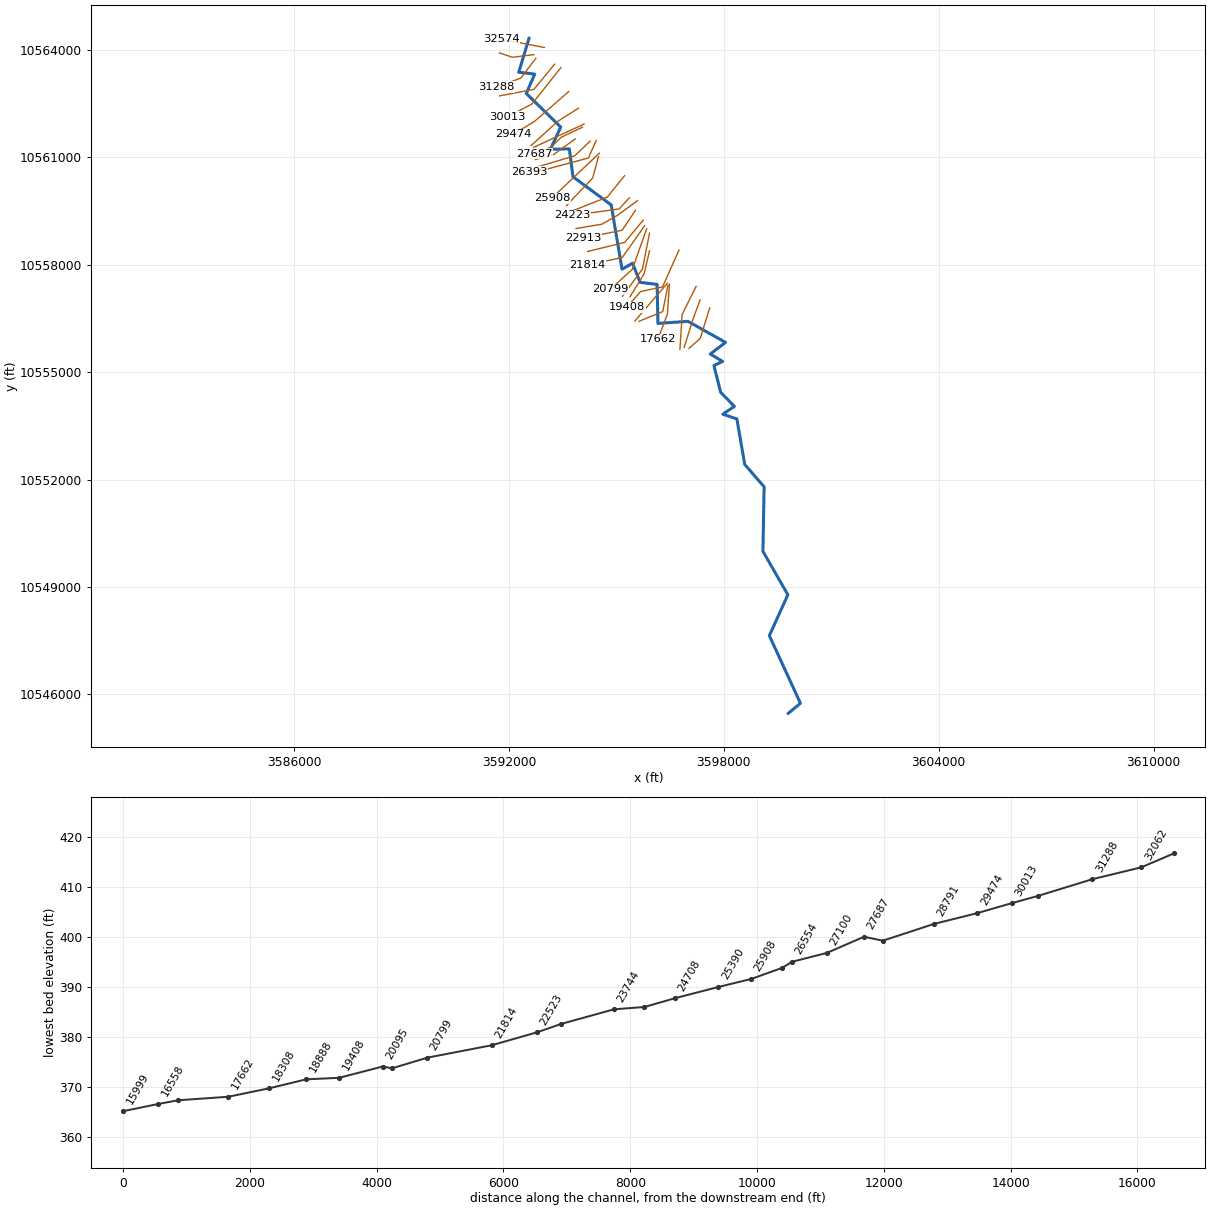
--- CEDAR CREEK 1.prj (project) ---

Proj Title=CEDAR CREEK 1 Base Level Engineering
Current Plan=p01
Default Exp/Contr=0.3,0.1
English Units
Geom File=g01
Flow File=f01
Plan File=p01
BEGIN DESCRIPTION:
CEDAR CREEK 1
END DESCRIPTION:

--- CEDAR CREEK 1.p01 (plan) ---

Plan Title=Multiple Run
Short Identifier=Multiple
Geom File=g01
Flow File=f01
Subcritical Flow
K Sum by GR= 0
Std Step Tol= 0.01
Critical Tol= 0.01
Num of Std Step Trials= 20
Max Error Tol= 0.3
Flow Tol Ratio= 0.001
Split Flow NTrial= 30
Split Flow Tol= 0.02
Split Flow Ratio= 0.02
Log Output Level= 0
Friction Slope Method= 1
Unsteady Friction Slope Method= 2
Unsteady Bridges Friction Slope Method= 1
Parabolic Critical Depth
Global Vel Dist=  1 , 1 , 1
Global Log Level= 0
CheckData=True
Encroach Param= -1, 0, 0, 0
BEGIN DESCRIPTION:
Multiple Run
END DESCRIPTION:

--- CEDAR CREEK 1.f01 (steady flow) ---

Flow Title=Multiple
Number of Profiles=7
Profile Names=10-year,25-year,50-year,1pct_min,100-year,1pct_plu,500-year
River Rch & RM= CEDAR CREEK 1,Reach-1,32574
    1587    2218    2747    2479    3353    4534    4978
River Rch & RM= CEDAR CREEK 1,Reach-1,22523
    1941    2728    3390    3066    4146    5607    6184
River Rch & RM= CEDAR CREEK 1,Reach-1,12054
    2232    3147    3918    3548    4798    6488    7175
Boundary for River Rch & Prof#=CEDAR CREEK 1,Reach-1,1
Up Type=0
Dn Type=3
Dn Slope=0.005
Boundary for River Rch & Prof#=CEDAR CREEK 1,Reach-1,2
Up Type=0
Dn Type=3
Dn Slope=0.005
Boundary for River Rch & Prof#=CEDAR CREEK 1,Reach-1,3
Up Type=0
Dn Type=3
Dn Slope=0.005
Boundary for River Rch & Prof#=CEDAR CREEK 1,Reach-1,4
Up Type=0
Dn Type=3
Dn Slope=0.005
Boundary for River Rch & Prof#=CEDAR CREEK 1,Reach-1,5
Up Type=0
Dn Type=3
Dn Slope=0.005
Boundary for River Rch & Prof#=CEDAR CREEK 1,Reach-1,6
Up Type=0
Dn Type=3
Dn Slope=0.005
Boundary for River Rch & Prof#=CEDAR CREEK 1,Reach-1,7
Up Type=0
Dn Type=3
Dn Slope=0.005

--- CEDAR CREEK 1.g01 (geometry) ---

Geom Title=Existing Conditions

River Reach=CEDAR CREEK 1,Reach-1
Reach XY= 30
      3592559.75     10564321.00      3592273.75     10563375.00
      3592720.25     10563321.00      3592482.75     10562782.00
      3593445.50     10561843.00      3593157.50     10561224.00
      3593686.00     10561233.00      3593787.50     10560454.00
      3594856.00     10559668.00      3595156.75     10557874.00
      3595450.25     10558042.00      3595662.75     10557507.00
      3596137.00     10557450.00      3596159.50     10556361.00
      3596998.50     10556418.00      3598046.75     10555830.00
      3597621.50     10555505.00      3597966.50     10555299.00
      3597723.50     10555184.00      3597911.75     10554436.00
      3598293.75     10554044.00      3597972.00     10553826.00
      3598364.25     10553693.00      3598583.00     10552422.00
      3599125.00     10551797.00      3599091.50     10549996.00
      3599788.10     10548783.00      3599271.00     10547642.00
      3600138.25     10545754.00      3599799.50     10545471.00

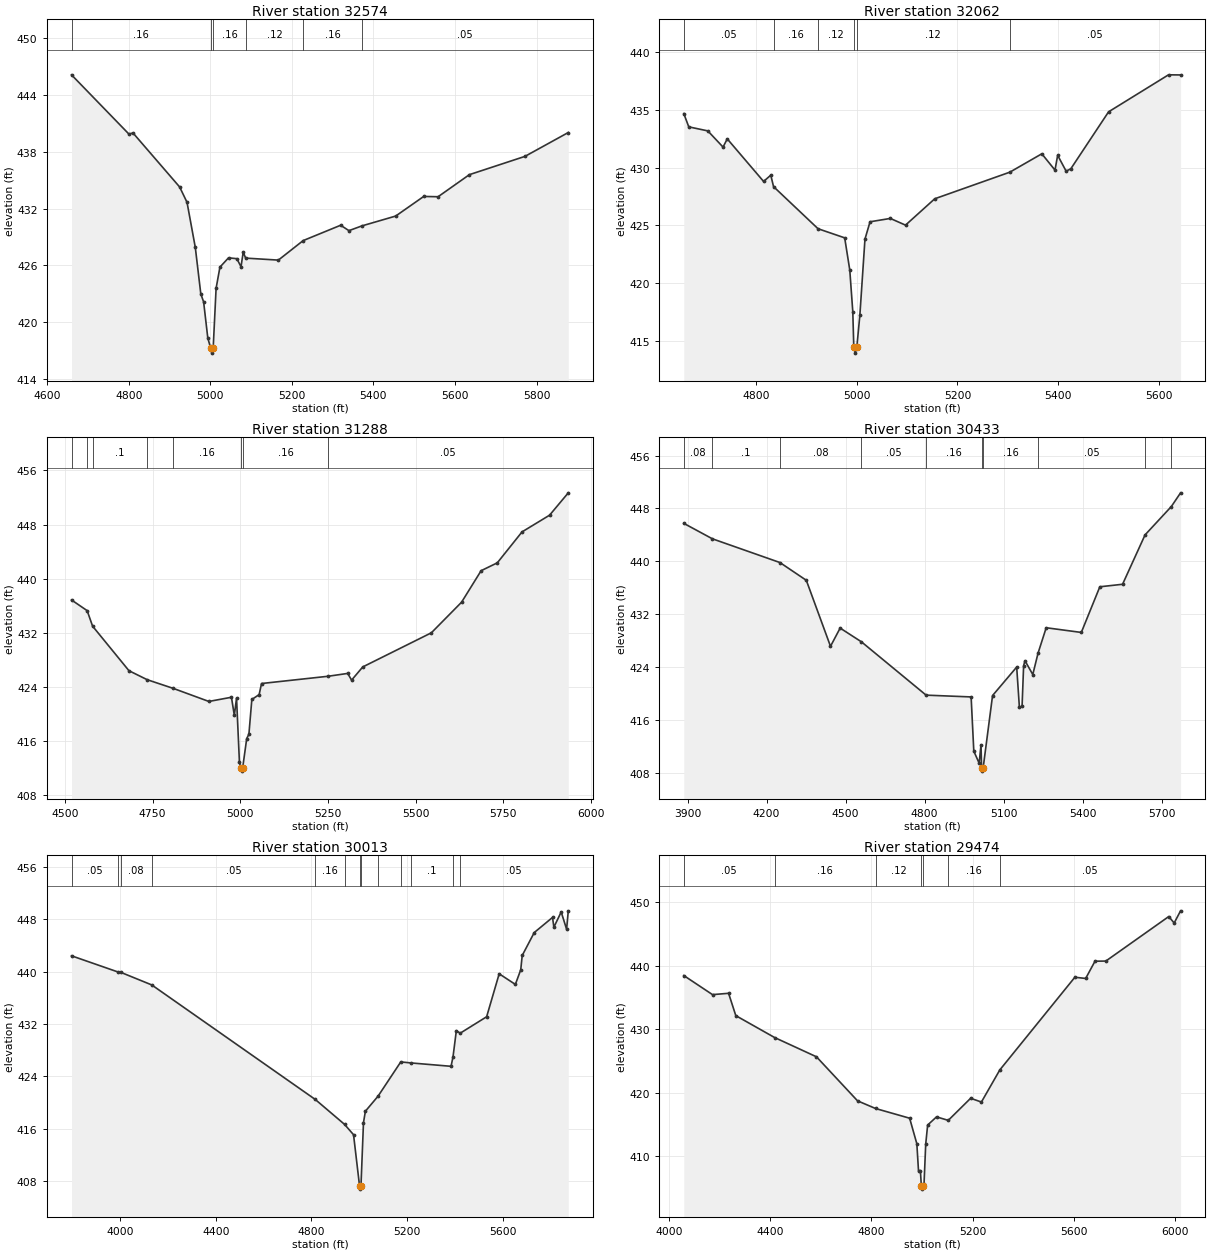
Type RM Length L Ch R = 1,32574,512,512,512
BEGIN DESCRIPTION:
CEDAR CREEK 1 51.0
END DESCRIPTION:
XS GIS Cut Line= 2
      3592987.81     10564065.72      3591791.37     10564295.47
#Sta/Elev= 30
  4659.6  446.12  4800.3  439.87  4810.5  439.98  4924.8  434.28  4942.9  432.66
  4963.2  427.90  4976.7  422.99  4983.6  422.15  4993.8  418.35  5001.0  417.24
  5003.7  416.74  5007.0  417.24  5014.2  423.58  5023.6  425.82  5044.7  426.80
  5065.1  426.71  5075.3  425.86  5080.7  427.40  5086.7  426.77  5166.9  426.56
  5227.7  428.62  5319.6  430.24  5340.0  429.67  5371.6  430.17  5454.6  431.21
  5523.3  433.28  5558.6  433.25  5635.3  435.58  5771.6  437.51  5877.9  440.03
#Mann=6,-1,0
  4659.6    0.16       0  5001.0    0.07       0  5007.0    0.16       0
  5086.7    0.12       0  5227.7    0.16       0  5371.6    0.05       0
Bank Sta=5001,5007
Exp/Cntr=0.3,0.1

Type RM Length L Ch R = 1,32062,774,774,774
BEGIN DESCRIPTION:
CEDAR CREEK 1 50.0
END DESCRIPTION:
XS GIS Cut Line= 3
      3592697.03     10563866.08      3592093.68     10563792.29
      3591734.03     10563913.62
#Sta/Elev= 30
  4656.1  434.68  4666.0  433.53  4703.9  433.18  4734.1  431.78  4742.5  432.49
  4814.7  428.81  4829.0  429.35  4834.5  428.36  4922.9  424.72  4975.9  423.93
  4986.0  421.15  4992.0  417.55  4994.0  414.46  4996.8  413.96  5000.0  414.46
  5006.1  417.26  5016.2  423.82  5026.3  425.32  5066.6  425.61  5096.8  425.03
  5154.9  427.31  5304.1  429.61  5367.7  431.20  5393.9  429.79  5399.2  431.07
  5416.0  429.70  5425.3  429.90  5500.4  434.83  5619.5  438.03  5643.5  438.02
#Mann=6,-1,0
  4656.1    0.05       0  4834.5    0.16       0  4922.9    0.12       0
  4994.0    0.07       0  5000.0    0.12       0  5304.1    0.05       0
Bank Sta=4994,5000
Exp/Cntr=0.3,0.1

Type RM Length L Ch R = 1,31288,855,855,855
BEGIN DESCRIPTION:
CEDAR CREEK 1 49.0
END DESCRIPTION:
XS GIS Cut Line= 3
      3592749.61     10563760.19      3592327.01     10563208.80
      3591649.60     10562960.19
#Sta/Elev= 30
  4518.9  436.86  4563.5  435.28  4579.0  432.99  4682.7  426.41  4734.8  425.08
  4809.5  423.79  4910.5  421.87  4974.9  422.49  4983.1  419.82  4989.4  422.36
  4997.6  412.96  5000.9  412.08  5003.7  411.58  5006.9  412.08  5018.4  416.38
  5024.7  417.04  5033.0  422.16  5053.8  422.88  5060.7  424.52  5250.5  425.59
  5306.3  426.01  5317.4  425.02  5349.3  426.97  5544.9  432.01  5631.0  436.53
  5686.7  441.18  5732.8  442.34  5803.3  446.91  5881.9  449.38  5935.2  452.68
#Mann=8,-1,0
  4518.9     0.1       0  4563.5    0.08       0  4579.0     0.1       0
  4734.8    0.08       0  4809.5    0.16       0  5000.9    0.07       0
  5006.9    0.16       0  5250.5    0.05       0
Bank Sta=5000.9,5006.9
Exp/Cntr=0.3,0.1

Type RM Length L Ch R = 1,30433,420,420,420
BEGIN DESCRIPTION:
CEDAR CREEK 1 48.0
END DESCRIPTION:
XS GIS Cut Line= 3
      3593274.95     10563599.45      3592696.80     10562896.30
      3591738.50     10562714.02
#Sta/Elev= 30
  3885.6  445.74  3994.2  443.40  4250.5  439.81  4350.7  437.12  4442.5  427.13
  4479.1  429.89  4559.9  427.81  4805.4  419.74  4976.3  419.47  4986.5  411.26
  5006.8  409.44  5013.9  412.24  5016.0  408.74  5018.8  408.24  5022.0  408.74
  5057.7  419.68  5149.3  423.99  5159.5  417.93  5169.7  418.05  5175.6  424.19
  5180.7  424.95  5210.4  422.86  5230.4  426.10  5261.3  429.94  5394.6  429.23
  5464.9  436.14  5551.2  436.52  5636.5  443.99  5736.4  448.29  5771.4  450.36
#Mann=10,-1,0
  3885.6    0.08       0  3994.2     0.1       0  4250.5    0.08       0
  4559.9    0.05       0  4805.4    0.16       0  5016.0    0.07       0
  5022.0    0.16       0  5230.4    0.05       0  5636.5    0.08       0
  5736.4     0.1       0
Bank Sta=5016,5022
Exp/Cntr=0.3,0.1

Type RM Length L Ch R = 1,30013,539,539,539
BEGIN DESCRIPTION:
CEDAR CREEK 1 47.0
END DESCRIPTION:
XS GIS Cut Line= 3
      3593451.99     10563505.65      3592639.51     10562484.84
      3591953.28     10562126.14
#Sta/Elev= 30
  3795.8  442.41  3991.0  439.93  4002.3  439.88  4131.7  437.96  4815.8  420.47
  4938.5  416.66  4976.1  415.08  5001.2  407.27  5003.9  406.77  5007.2  407.27
  5017.7  416.93  5025.7  418.67  5078.7  420.97  5173.7  426.20  5218.2  426.04
  5384.2  425.53  5392.4  426.98  5406.3  430.98  5422.5  430.59  5533.1  433.10
  5585.6  439.66  5653.3  438.04  5675.8  440.27  5682.0  442.46  5732.3  445.96
  5808.8  448.27  5814.5  446.78  5845.1  449.11  5867.7  446.47  5874.8  449.28
#Mann=13,-1,0
  3795.8    0.05       0  3991.0     0.1       0  4002.3    0.08       0
  4131.7    0.05       0  4815.8    0.16       0  4938.5    0.12       0
  5001.2    0.07       0  5007.2    0.12       0  5078.7    0.16       0
  5173.7    0.05       0  5218.2     0.1       0  5392.4    0.08       0
  5422.5    0.05       0
Bank Sta=5001.2,5007.2
Exp/Cntr=0.3,0.1

Type RM Length L Ch R = 1,29474,683,683,683
BEGIN DESCRIPTION:
CEDAR CREEK 1 46.0
END DESCRIPTION:
XS GIS Cut Line= 3
      3593665.58     10562833.83      3592712.43     10562000.47
      3592114.06     10561641.45
#Sta/Elev= 30
  4058.2  438.46  4171.7  435.45  4235.3  435.66  4263.8  432.14  4417.1  428.69
  4582.7  425.65  4745.0  418.71  4816.2  417.50  4951.0  415.97  4979.5  411.94
  4986.1  407.65  4993.7  407.61  4997.3  405.29  5000.1  404.79  5003.3  405.29
  5007.9  405.59  5014.6  411.89  5022.2  414.89  5057.3  416.18  5103.7  415.63
  5192.1  419.11  5234.8  418.52  5307.5  423.58  5604.2  438.19  5646.9  438.00
  5683.8  440.72  5726.6  440.74  5975.4  447.76  5996.8  446.74  6022.1  448.66
#Mann=7,-1,0
  4058.2    0.05       0  4417.1    0.16       0  4816.2    0.12       0
  4997.3    0.07       0  5003.3    0.12       0  5103.7    0.16       0
  5307.5    0.05       0
Bank Sta=4997.3,5003.3
Exp/Cntr=0.3,0.1

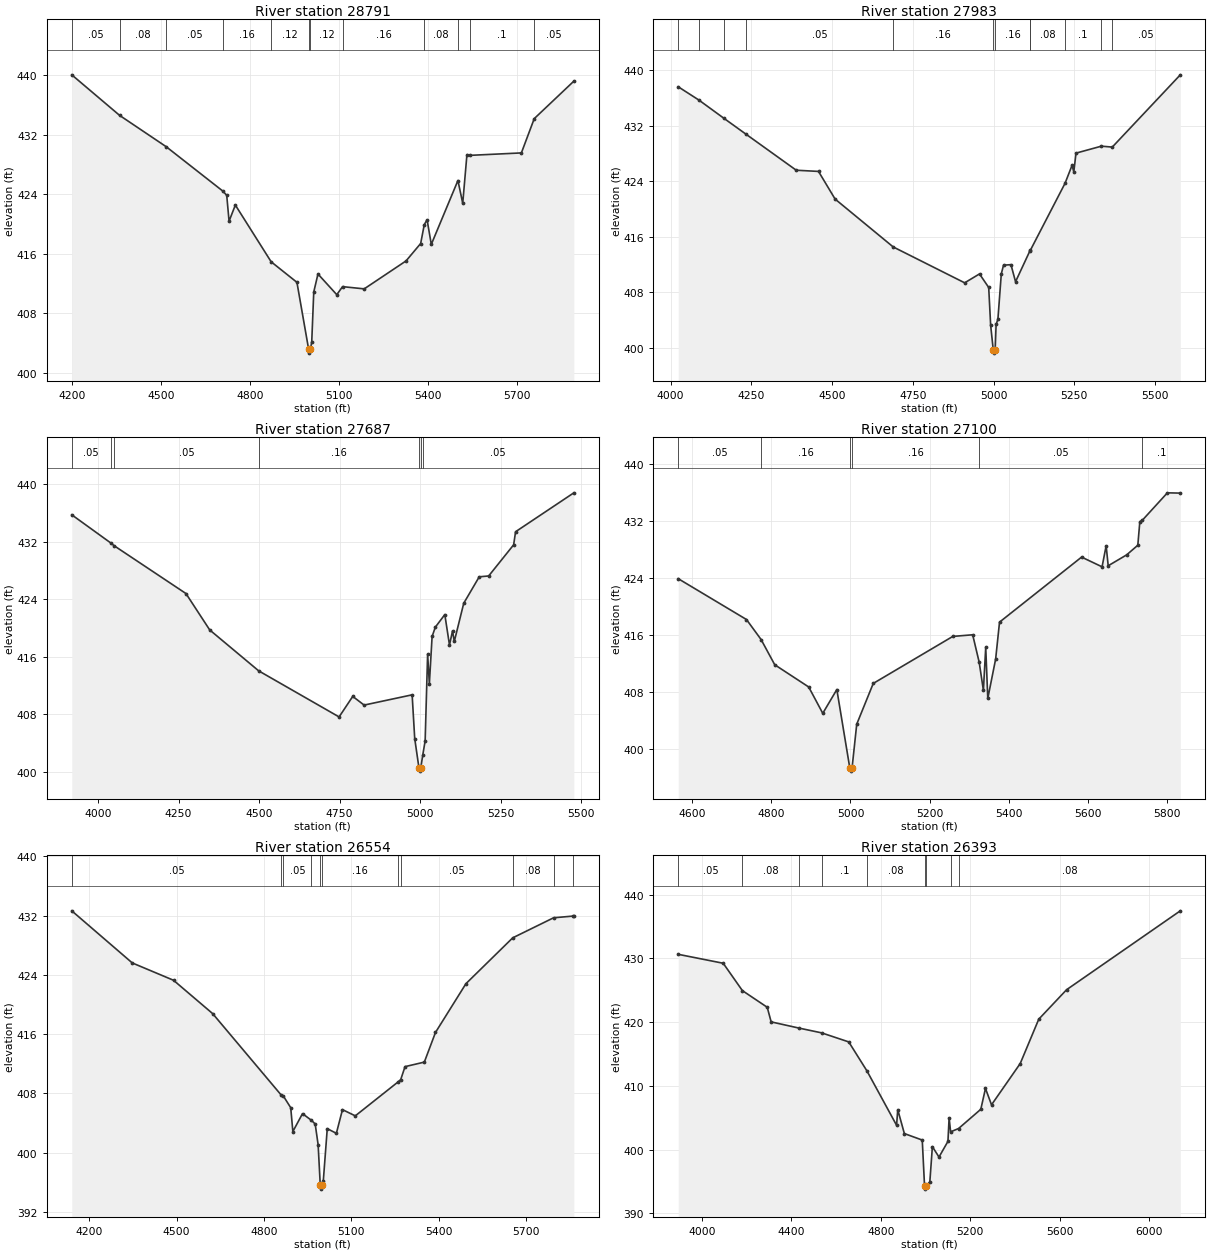
Type RM Length L Ch R = 1,28791,808,808,808
BEGIN DESCRIPTION:
CEDAR CREEK 1 45.0
END DESCRIPTION:
XS GIS Cut Line= 3
      3593941.57     10562370.25      3593373.88     10562010.89
      3592615.03     10561324.79
#Sta/Elev= 30
  4197.7  440.05  4359.1  434.60  4516.3  430.39  4707.3  424.43  4720.8  423.85
  4728.7  420.37  4749.9  422.54  4870.8  414.91  4957.8  412.15  4997.4  403.13
  5000.1  402.63  5003.4  403.13  5007.8  404.17  5014.6  410.85  5028.8  413.27
  5092.3  410.49  5111.9  411.57  5184.9  411.27  5326.2  415.03  5375.5  417.37
  5387.7  419.91  5397.2  420.56  5411.4  417.25  5501.3  425.84  5517.5  422.77
  5531.7  429.32  5540.6  429.22  5715.5  429.55  5758.9  434.16  5892.6  439.20
#Mann=12,-1,0
  4197.7    0.05       0  4359.1    0.08       0  4516.3    0.05       0
  4707.3    0.16       0  4870.8    0.12       0  4997.4    0.07       0
  5003.4    0.12       0  5111.9    0.16       0  5387.7    0.08       0
  5501.3    0.16       0  5540.6     0.1       0  5758.9    0.05       0
Bank Sta=4997.4,5003.4
Exp/Cntr=0.3,0.1

Type RM Length L Ch R = 1,27983,296,296,296
BEGIN DESCRIPTION:
CEDAR CREEK 1 44.0
END DESCRIPTION:
XS GIS Cut Line= 2
      3594097.89     10561927.57      3592686.40     10561276.52
#Sta/Elev= 30
  4023.6  437.57  4087.6  435.66  4163.8  433.08  4234.4  430.72  4389.0  425.57
  4457.9  425.40  4509.3  421.42  4689.1  414.54  4910.4  409.38  4956.3  410.66
  4984.8  408.71  4990.8  403.29  4998.8  399.77  5001.6  399.27  5004.8  399.77
  5007.7  403.39  5013.3  404.15  5023.8  410.67  5030.7  411.92  5053.7  411.99
  5067.9  409.54  5112.8  414.02  5114.1  414.09  5221.1  423.69  5242.8  426.27
  5248.3  425.35  5255.1  428.03  5333.6  429.03  5367.4  428.90  5578.0  439.29
#Mann=12,-1,0
  4023.6    0.08       0  4087.6    0.05       0  4163.8    0.08       0
  4234.4    0.05       0  4689.1    0.16       0  4998.8    0.07       0
  5004.8    0.16       0  5112.8    0.05       0  5114.1    0.08       0
  5221.1     0.1       0  5333.6    0.15       0  5367.4    0.05       0
Bank Sta=4998.8,5004.8
Exp/Cntr=0.3,0.1

Type RM Length L Ch R = 1,27687,587,587,587
BEGIN DESCRIPTION:
CEDAR CREEK 1 43.0
END DESCRIPTION:
XS GIS Cut Line= 4
      3594050.99     10561839.02      3593457.22     10561557.76
      3593186.38     10561292.14      3592702.02     10561094.23
#Sta/Elev= 30
  3918.2  435.77  4038.6  431.87  4050.5  431.44  4272.9  424.80  4346.7  419.73
  4498.8  414.03  4748.6  407.61  4791.0  410.47  4826.3  409.26  4975.5  410.69
  4983.5  404.60  4996.5  400.56  4999.3  400.06  5002.5  400.56  5008.5  402.31
  5015.9  404.27  5023.6  416.36  5029.0  412.22  5037.5  418.82  5047.6  420.12
  5077.0  421.87  5091.5  417.63  5101.0  419.60  5106.4  418.12  5135.8  423.45
  5183.9  427.13  5213.3  427.25  5290.8  431.59  5296.8  433.41  5477.8  438.83
#Mann=7,-1,0
  3918.2    0.05       0  4038.6    0.08       0  4050.5    0.05       0
  4498.8    0.16       0  4996.5    0.07       0  5002.5    0.16       0
  5008.5    0.05       0
Bank Sta=4996.5,5002.5
Exp/Cntr=0.3,0.1

Type RM Length L Ch R = 1,27100,546,546,546
BEGIN DESCRIPTION:
CEDAR CREEK 1 42.0
END DESCRIPTION:
XS GIS Cut Line= 3
      3593849.59     10561510.17      3593243.68     10561073.39
      3592738.45     10560937.96
#Sta/Elev= 30
  4564.4  423.92  4737.0  418.17  4774.0  415.35  4808.5  411.80  4894.4  408.67
  4930.0  404.96  4965.6  408.31  4998.2  397.32  5001.0  396.82  5004.2  397.32
  5015.9  403.43  5057.7  409.17  5258.9  415.79  5309.2  416.02  5325.7  412.14
  5336.3  408.20  5342.2  414.25  5347.4  407.05  5367.3  412.61  5377.1  417.80
  5584.7  426.96  5636.5  425.59  5646.8  428.56  5652.0  425.74  5698.6  427.27
  5726.9  428.63  5732.0  431.95  5738.7  432.17  5801.7  436.01  5834.4  435.97
#Mann=6,-1,0
  4564.4    0.05       0  4774.0    0.16       0  4998.2    0.07       0
  5004.2    0.16       0  5325.7    0.05       0  5738.7     0.1       0
Bank Sta=4998.2,5004.2
Exp/Cntr=0.3,0.1

Type RM Length L Ch R = 1,26554,161,161,161
BEGIN DESCRIPTION:
CEDAR CREEK 1 41.0
END DESCRIPTION:
XS GIS Cut Line= 3
      3594269.73     10561453.61      3593837.43     10561042.14
      3592759.27     10560719.21
#Sta/Elev= 30
  4140.7  432.66  4348.2  425.62  4489.7  423.28  4624.1  418.77  4859.8  407.74
  4866.5  407.64  4891.8  406.06  4899.1  402.84  4932.2  405.26  4963.0  404.35
  4975.7  403.86  4985.8  401.06  4993.2  395.56  4996.0  395.06  4999.2  395.56
  5003.6  396.20  5017.1  403.23  5048.4  402.60  5069.3  405.80  5113.3  404.96
  5259.9  409.54  5269.1  409.86  5283.9  411.61  5350.1  412.22  5388.4  416.23
  5492.9  422.82  5653.3  429.01  5793.5  431.72  5860.3  431.95  5863.0  431.95
#Mann=11,-1,0
  4140.7    0.05       0  4859.8    0.16       0  4866.5    0.05       0
  4963.0    0.16       0  4993.2    0.07       0  4999.2    0.16       0
  5259.9    0.08       0  5269.1    0.05       0  5653.3    0.08       0
  5793.5     0.1       0  5860.3    0.08       0
Bank Sta=4993.2,4999.2
Exp/Cntr=0.3,0.1

Type RM Length L Ch R = 1,26393,485,485,485
BEGIN DESCRIPTION:
CEDAR CREEK 1 40.0
END DESCRIPTION:
XS GIS Cut Line= 4
      3594436.40     10561469.25      3594217.63     10560979.64
      3593035.34     10560661.93      3592556.20     10560599.43
#Sta/Elev= 30
  3894.7  430.63  4095.7  429.23  4181.4  424.94  4292.4  422.33  4309.9  420.04
  4433.9  419.07  4535.3  418.32  4656.7  416.90  4737.9  412.36  4870.5  403.83
  4875.7  406.28  4905.2  402.53  4985.2  401.51  4995.4  394.32  4998.2  393.82
  5001.4  394.32  5019.1  394.96  5030.4  400.48  5060.0  398.85  5100.0  401.31
  5105.2  405.00  5111.9  402.80  5147.4  403.32  5246.9  406.34  5267.7  409.61
  5294.7  407.04  5423.0  413.51  5505.8  420.46  5630.1  425.08  6138.4  437.45
#Mann=9,-1,0
  3894.7    0.05       0  4181.4    0.08       0  4433.9    0.05       0
  4535.3     0.1       0  4737.9    0.08       0  4995.4    0.07       0
  5001.4    0.08       0  5111.9    0.16       0  5147.4    0.08       0
Bank Sta=4995.4,5001.4
Exp/Cntr=0.3,0.1

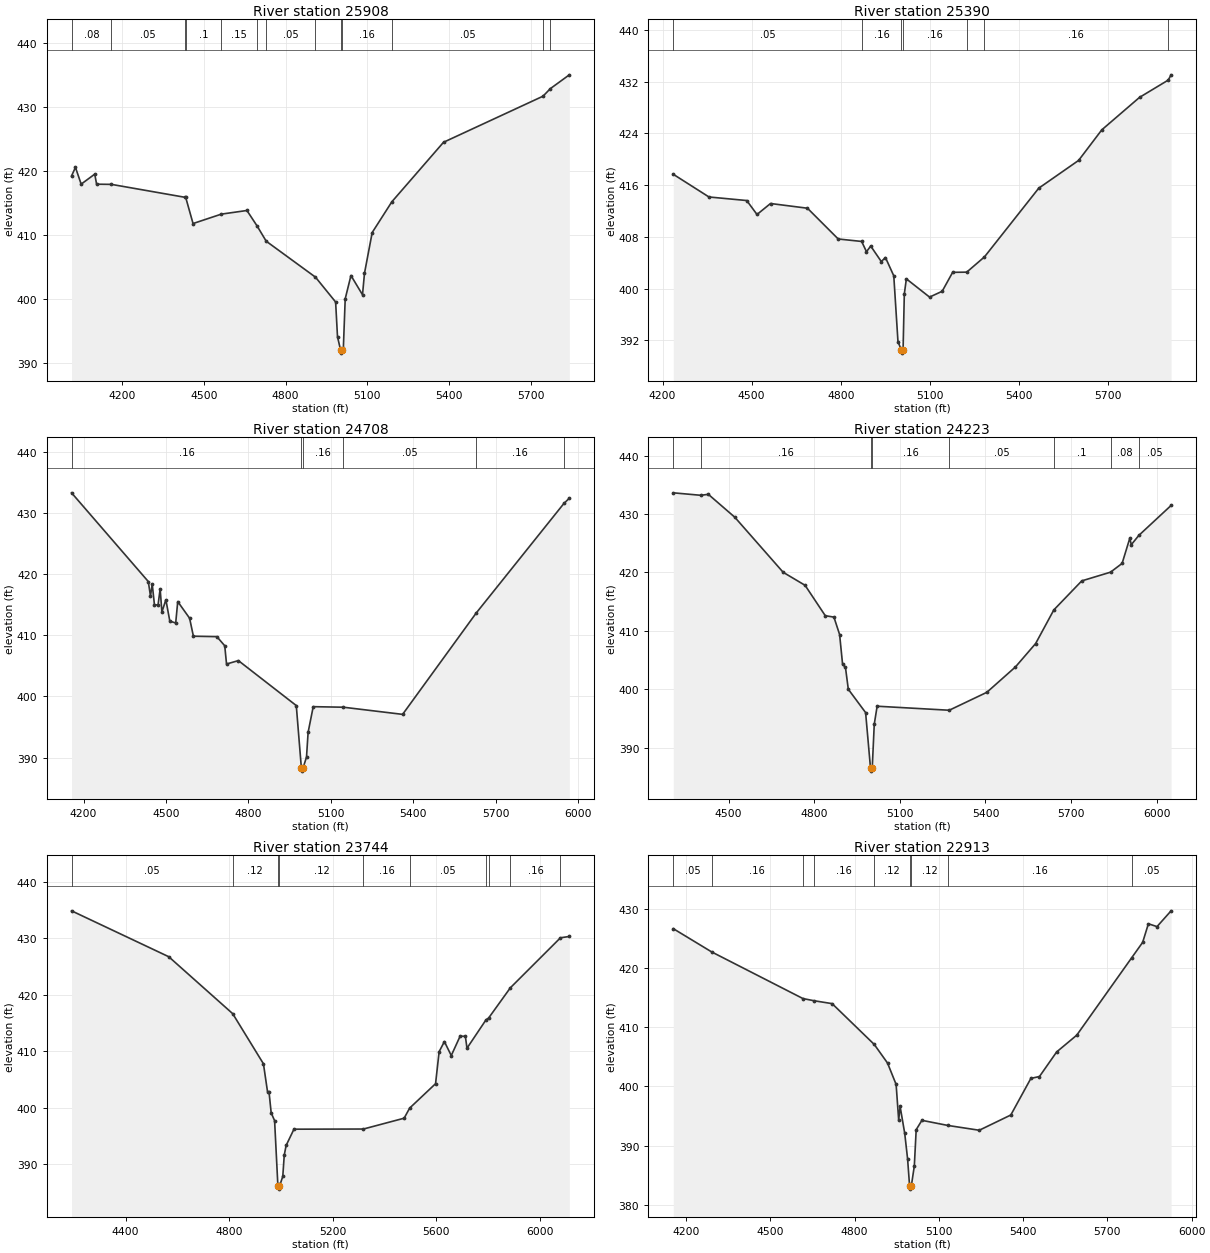
Type RM Length L Ch R = 1,25908,518,518,518
BEGIN DESCRIPTION:
CEDAR CREEK 1 39.0
END DESCRIPTION:
XS GIS Cut Line= 2
      3594524.94     10561115.07      3593196.83     10559859.87
#Sta/Elev= 30
  4014.2  419.30  4028.5  420.64  4049.5  418.02  4099.3  419.58  4106.2  418.01
  4160.7  417.98  4430.8  415.96  4432.8  416.01  4460.2  411.86  4564.0  413.33
  4658.0  413.90  4695.2  411.49  4728.8  409.10  4909.7  403.48  4983.6  399.60
  4990.5  394.17  5001.7  392.11  5004.4  391.61  5007.7  392.11  5012.0  392.41
  5018.8  400.10  5039.9  403.74  5082.3  400.73  5089.6  404.10  5117.9  410.46
  5190.2  415.27  5379.7  424.56  5744.9  431.76  5771.8  432.94  5841.6  435.10
#Mann=13,-1,0
  4014.2    0.08       0  4160.7    0.05       0  4430.8    0.08       0
  4432.8     0.1       0  4564.0    0.15       0  4695.2    0.08       0
  4728.8    0.05       0  4909.7    0.16       0  5001.7    0.07       0
  5007.7    0.16       0  5190.2    0.05       0  5744.9    0.08       0
  5771.8     0.1       0
Bank Sta=5001.7,5007.7
Exp/Cntr=0.3,0.1

Type RM Length L Ch R = 1,25390,682,682,682
BEGIN DESCRIPTION:
CEDAR CREEK 1 38.0
END DESCRIPTION:
XS GIS Cut Line= 3
      3594498.89     10561016.11      3594337.43     10560422.34
      3593608.26     10559651.51
#Sta/Elev= 30
  4236.2  417.68  4356.3  414.17  4483.5  413.62  4518.1  411.46  4563.6  413.16
  4688.0  412.43  4791.6  407.67  4870.5  407.29  4886.8  405.70  4901.0  406.58
  4936.6  404.18  4950.7  404.80  4978.7  401.97  4992.8  391.80  5004.0  390.51
  5006.7  390.01  5010.0  390.51  5014.2  399.17  5021.1  401.50  5099.2  398.68
  5141.7  399.58  5176.9  402.51  5224.4  402.54  5284.1  404.90  5466.9  415.53
  5601.2  419.83  5679.3  424.56  5806.3  429.58  5902.8  432.25  5912.6  433.07
#Mann=7,-1,0
  4236.2    0.05       0  4870.5    0.16       0  5004.0    0.07       0
  5010.0    0.16       0  5224.4    0.05       0  5284.1    0.16       0
  5902.8    0.05       0
Bank Sta=5004,5010
Exp/Cntr=0.3,0.1

Type RM Length L Ch R = 1,24708,485,485,485
BEGIN DESCRIPTION:
CEDAR CREEK 1 37.0
END DESCRIPTION:
XS GIS Cut Line= 3
      3595228.05     10560484.84      3594743.68     10559885.89
      3593774.92     10559505.67
#Sta/Elev= 30
  4156.4  433.32  4435.6  418.80  4443.5  416.44  4449.9  418.36  4457.9  415.02
  4471.0  414.94  4478.7  417.59  4485.1  413.81  4499.5  415.82  4513.9  412.32
  4535.3  412.02  4542.7  415.52  4585.8  412.80  4599.7  409.85  4685.0  409.78
  4713.7  408.29  4720.2  405.30  4763.3  405.86  4974.0  398.50  4992.5  388.27
  4995.3  387.77  4998.5  388.27  5011.2  390.07  5017.0  394.11  5035.6  398.32
  5145.4  398.23  5360.8  397.06  5628.6  413.65  5947.8  431.59  5967.4  432.44
#Mann=6,-1,0
  4156.4    0.16       0  4992.5    0.07       0  4998.5    0.16       0
  5145.4    0.05       0  5628.6    0.16       0  5947.8    0.05       0
Bank Sta=4992.5,4998.5
Exp/Cntr=0.3,0.1

Type RM Length L Ch R = 1,24223,479,479,479
BEGIN DESCRIPTION:
CEDAR CREEK 1 36.0
END DESCRIPTION:
XS GIS Cut Line= 3
      3595363.47     10559870.27      3595077.01     10559557.76
      3593769.69     10559375.47
#Sta/Elev= 30
  4306.5  433.63  4402.2  433.21  4429.3  433.37  4521.8  429.46  4691.4  420.03
  4768.2  417.80  4838.9  412.60  4869.2  412.36  4889.1  409.38  4899.5  404.30
  4909.6  403.76  4919.6  400.01  4980.2  396.02  4997.4  386.50  5000.2  386.00
  5003.4  386.50  5010.5  394.03  5020.6  397.11  5273.1  396.42  5405.0  399.49
  5505.3  403.84  5575.9  407.84  5639.6  413.59  5737.5  418.56  5838.2  420.05
  5878.8  421.55  5905.8  425.87  5910.9  424.75  5937.5  426.35  6050.4  431.47
#Mann=8,-1,0
  4306.5    0.05       0  4402.2    0.16       0  4997.4    0.07       0
  5003.4    0.16       0  5273.1    0.05       0  5639.6     0.1       0
  5838.2    0.08       0  5937.5    0.05       0
Bank Sta=4997.4,5003.4
Exp/Cntr=0.3,0.1

Type RM Length L Ch R = 1,23744,831,831,831
BEGIN DESCRIPTION:
CEDAR CREEK 1 35.0
END DESCRIPTION:
XS GIS Cut Line= 4
      3595587.47     10559786.96      3595031.87     10559381.37
      3594597.84     10559131.37      3593873.39     10559010.05
#Sta/Elev= 30
  4191.3  434.90  4566.8  426.76  4813.9  416.66  4932.7  407.77  4948.5  402.80
  4954.2  402.80  4962.6  399.07  4975.8  397.68  4988.6  386.04  4991.3  385.54
  4994.6  386.04  5007.4  387.79  5013.1  391.57  5020.3  393.28  5050.5  396.17
  5319.1  396.20  5476.3  398.12  5497.6  399.91  5597.7  404.24  5611.5  409.92
  5631.8  411.71  5658.4  409.23  5692.6  412.67  5712.9  412.64  5719.1  410.53
  5792.5  415.56  5802.6  415.88  5886.7  421.25  6080.3  430.12  6114.6  430.35
#Mann=10,-1,0
  4191.3    0.05       0  4813.9    0.12       0  4988.6    0.07       0
  4994.6    0.12       0  5319.1    0.16       0  5497.6    0.05       0
  5792.5     0.1       0  5802.6    0.05       0  5886.7    0.16       0
  6080.3    0.05       0
Bank Sta=4988.6,4994.6
Exp/Cntr=0.3,0.1

Type RM Length L Ch R = 1,22913,390,390,390
BEGIN DESCRIPTION:
CEDAR CREEK 1 34.0
END DESCRIPTION:
XS GIS Cut Line= 3
      3595533.59     10559519.20      3595158.61     10558961.93
      3594080.46     10558743.17
#Sta/Elev= 30
  4155.0  426.68  4291.5  422.75  4616.4  414.86  4655.9  414.49  4720.3  414.00
  4870.4  407.09  4917.5  403.95  4948.1  400.33  4957.2  394.30  4962.3  396.61
  4978.7  392.06  4988.9  387.74  4996.1  383.12  4998.9  382.62  5002.1  383.12
  5012.9  386.55  5019.5  392.68  5039.9  394.26  5132.5  393.39  5244.0  392.58
  5356.3  395.16  5427.7  401.35  5458.3  401.67  5519.5  405.83  5590.9  408.66
  5786.1  421.73  5825.6  424.37  5846.0  427.51  5876.7  427.03  5926.8  429.70
#Mann=9,-1,0
  4155.0    0.05       0  4291.5    0.16       0  4616.4    0.05       0
  4655.9    0.16       0  4870.4    0.12       0  4996.1    0.07       0
  5002.1    0.12       0  5132.5    0.16       0  5786.1    0.05       0
Bank Sta=4996.1,5002.1
Exp/Cntr=0.3,0.1

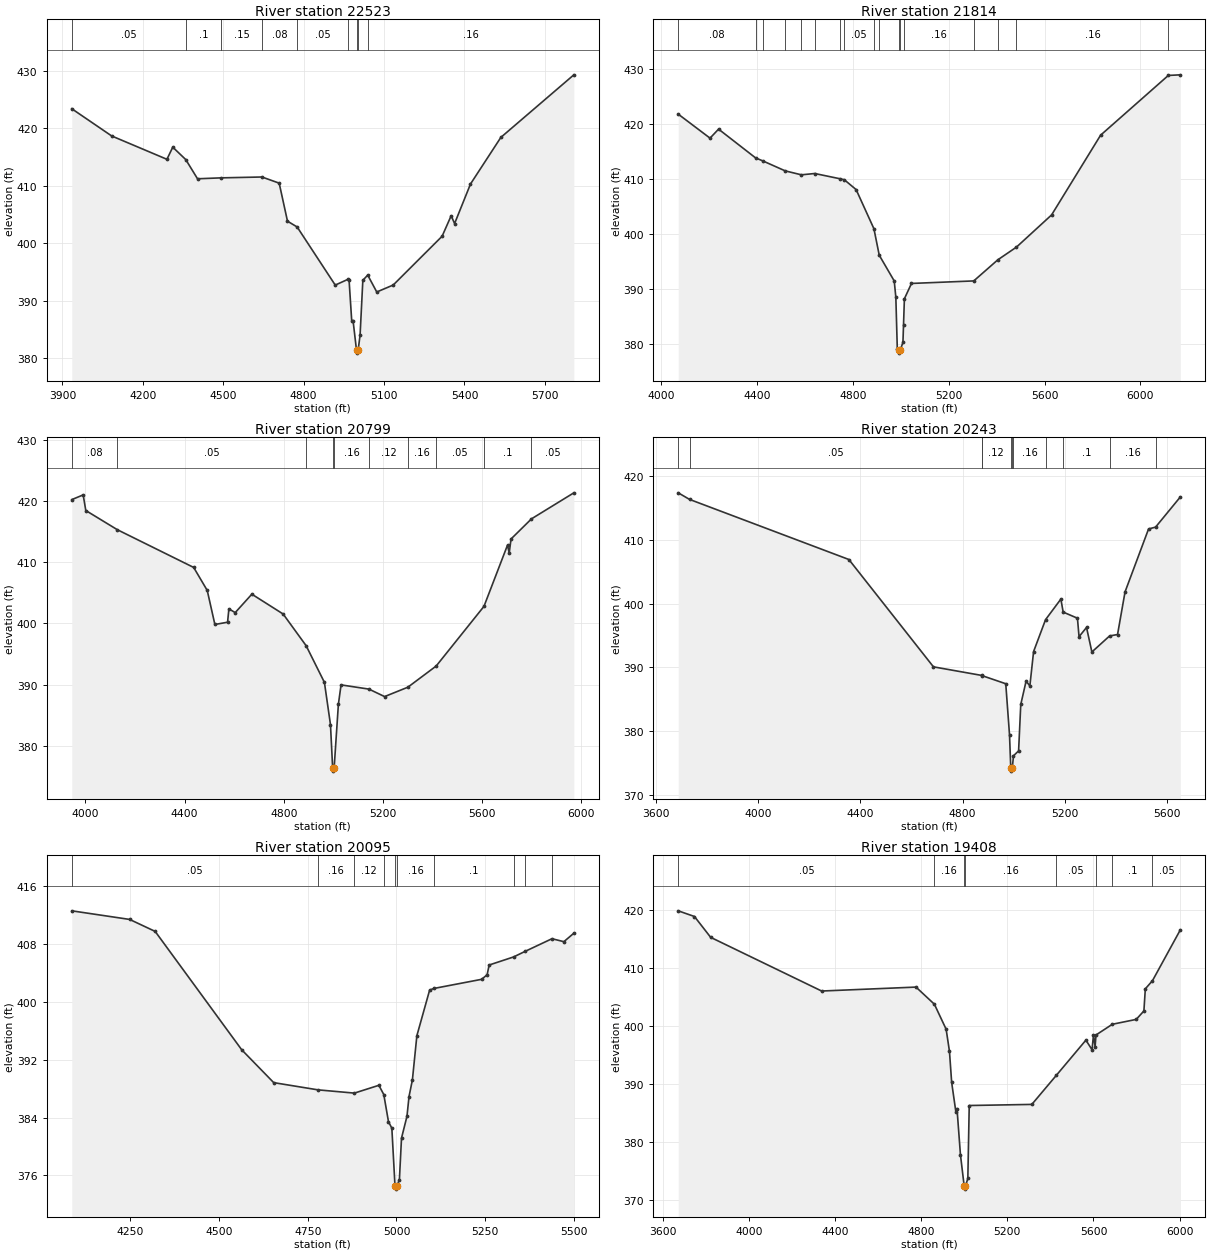
Type RM Length L Ch R = 1,22523,709,709,709
BEGIN DESCRIPTION:
CEDAR CREEK 1 33.0
END DESCRIPTION:
XS GIS Cut Line= 3
      3595747.12     10559243.15      3595231.52     10558623.39
      3594195.07     10558368.18
#Sta/Elev= 30
  3934.6  423.44  4083.6  418.70  4289.7  414.64  4311.5  416.75  4360.0  414.59
  4403.9  411.25  4491.9  411.41  4644.3  411.56  4708.6  410.49  4739.6  403.87
  4775.7  402.86  4917.8  392.75  4964.1  393.73  4969.3  393.69  4979.3  386.52
  4984.5  386.48  4997.2  381.41  5000.0  380.91  5003.2  381.41  5010.5  384.04
  5020.8  393.58  5039.0  394.49  5072.7  391.55  5134.1  392.76  5316.6  401.25
  5350.4  404.82  5363.2  403.46  5422.5  410.34  5535.8  418.45  5808.2  429.34
#Mann=9,-1,0
  3934.6    0.05       0  4360.0     0.1       0  4491.9    0.15       0
  4644.3    0.08       0  4775.7    0.05       0  4964.1    0.12       0
  4997.2    0.07       0  5003.2    0.12       0  5039.0    0.16       0
Bank Sta=4997.2,5003.2
Exp/Cntr=0.3,0.1

Type RM Length L Ch R = 1,21814,1015,1015,1015
BEGIN DESCRIPTION:
CEDAR CREEK 1 32.0
END DESCRIPTION:
XS GIS Cut Line= 3
      3595788.79     10559086.89      3595163.82     10558201.51
      3594174.42     10557988.01
#Sta/Elev= 30
  4070.8  421.86  4203.5  417.49  4239.2  419.13  4393.8  413.89  4422.6  413.37
  4517.3  411.53  4585.0  410.81  4640.7  411.05  4747.5  410.08  4764.2  409.91
  4813.4  408.12  4887.7  400.99  4909.9  396.17  4972.5  391.48  4979.2  388.50
  4985.3  379.10  4991.0  378.84  4993.8  378.34  4997.0  378.84  5008.8  380.28
  5011.2  383.41  5014.9  388.24  5044.5  391.03  5304.5  391.49  5404.8  395.33
  5482.8  397.65  5629.4  403.51  5834.0  418.03  6116.7  428.91  6166.7  429.02
#Mann=17,-1,0
  4070.8    0.08       0  4393.8    0.05       0  4422.6     0.1       0
  4517.3    0.08       0  4585.0     0.1       0  4640.7    0.08       0
  4747.5     0.1       0  4764.2    0.05       0  4887.7    0.08       0
  4909.9    0.05       0  4991.0    0.03       0  4997.0    0.05       0
  5011.2    0.16       0  5304.5     0.1       0  5404.8    0.05       0
  5482.8    0.16       0  6116.7    0.05       0
Bank Sta=4991,4997
Exp/Cntr=0.3,0.1

Type RM Length L Ch R = 1,20799,556,556,556
BEGIN DESCRIPTION:
CEDAR CREEK 1 31.0
END DESCRIPTION:
XS GIS Cut Line= 3
      3595846.10     10559003.56      3595445.07     10557873.39
      3594835.69     10557316.09
#Sta/Elev= 30
  3944.9  420.22  3990.9  420.99  4001.5  418.44  4128.9  415.30  4436.6  409.14
  4491.3  405.38  4522.1  399.82  4573.3  400.19  4578.6  402.37  4604.1  401.76
  4671.2  404.77  4797.4  401.53  4890.2  396.35  4963.9  390.36  4988.3  383.47
  4997.1  376.36  4999.9  375.86  5003.1  376.36  5020.2  386.76  5031.0  389.95
  5143.5  389.26  5206.6  388.04  5300.4  389.57  5414.6  393.03  5607.4  402.78
  5702.4  412.79  5709.2  411.50  5716.6  413.79  5799.1  417.08  5969.9  421.33
#Mann=10,-1,0
  3944.9    0.08       0  4128.9    0.05       0  4890.2    0.16       0
  4997.1    0.07       0  5003.1    0.16       0  5143.5    0.12       0
  5300.4    0.16       0  5414.6    0.05       0  5607.4     0.1       0
  5799.1    0.05       0
Bank Sta=4997.1,5003.1
Exp/Cntr=0.3,0.1

Type RM Length L Ch R = 1,20243,148,148,148
BEGIN DESCRIPTION:
CEDAR CREEK 1 30.0
END DESCRIPTION:
XS GIS Cut Line= 3
      3595924.23     10558878.61      3595726.32     10557878.59
      3595169.01     10557118.16
#Sta/Elev= 30
  3688.5  417.39  3732.6  416.36  4355.4  406.93  4685.9  390.09  4873.8  388.75
  4875.3  388.72  4968.5  387.44  4983.2  379.43  4988.1  374.23  4990.8  373.73
  4994.1  374.23  4998.7  376.13  5018.7  376.91  5027.2  384.19  5048.0  387.85
  5062.7  387.10  5077.3  392.49  5124.0  397.49  5183.9  400.72  5192.9  398.68
  5248.7  397.72  5254.9  394.82  5284.2  396.27  5305.1  392.42  5374.4  394.94
  5405.4  395.16  5434.7  401.85  5526.6  411.72  5554.0  412.01  5650.7  416.74
#Mann=11,-1,0
  3688.5    0.08       0  3732.6    0.05       0  4873.8    0.16       0
  4875.3    0.12       0  4988.1    0.07       0  4994.1    0.12       0
  4998.7    0.16       0  5124.0    0.05       0  5192.9     0.1       0
  5374.4    0.16       0  5554.0    0.05       0
Bank Sta=4988.1,4994.1
Exp/Cntr=0.3,0.1

Type RM Length L Ch R = 1,20095,687,687,687
BEGIN DESCRIPTION:
CEDAR CREEK 1 29.0
END DESCRIPTION:
XS GIS Cut Line= 3
      3595924.23     10558388.99      3595773.19     10557743.18
      3595378.19     10557103.91
#Sta/Elev= 30
  4085.1  412.61  4248.2  411.42  4320.1  409.76  4563.9  393.38  4654.1  388.83
  4778.8  387.83  4881.4  387.38  4950.4  388.46  4964.3  387.18  4977.5  383.42
  4987.0  382.52  4995.8  374.59  4998.5  374.09  5001.8  374.59  5008.3  375.42
  5014.2  381.15  5029.6  384.17  5035.4  386.91  5044.9  389.21  5057.5  395.33
  5093.4  401.63  5104.8  401.86  5240.0  403.13  5255.4  403.76  5261.2  405.11
  5330.2  406.23  5363.0  407.01  5438.2  408.75  5471.7  408.34  5499.8  409.51
#Mann=10,-1,0
  4085.1    0.05       0  4778.8    0.16       0  4881.4    0.12       0
  4964.3    0.16       0  4995.8    0.07       0  5001.8    0.16       0
  5104.8     0.1       0  5330.2    0.05       0  5363.0    0.16       0
  5438.2    0.05       0
Bank Sta=4995.8,5001.8
Exp/Cntr=0.3,0.1

Type RM Length L Ch R = 1,19408,520,520,520
BEGIN DESCRIPTION:
CEDAR CREEK 1 28.0
END DESCRIPTION:
XS GIS Cut Line= 4
      3596747.14     10558409.83      3596288.82     10557378.59
      3595679.44     10557253.59      3595294.30     10556816.41
#Sta/Elev= 30
  3670.5  419.89  3745.9  418.91  3821.2  415.31  4336.9  406.04  4775.4  406.72
  4860.9  403.76  4915.5  399.44  4930.9  395.63  4941.1  390.27  4960.8  385.14
  4965.9  385.75  4981.9  377.80  4999.4  372.33  5002.1  371.83  5005.4  372.33
  5016.3  373.68  5022.8  386.27  5313.7  386.46  5427.1  391.46  5565.0  397.56
  5593.5  395.90  5600.2  398.45  5607.7  396.44  5611.9  398.45  5687.8  400.30
  5798.8  401.14  5834.5  402.60  5841.1  406.42  5874.4  407.83  6003.7  416.60
#Mann=8,-1,0
  3670.5    0.05       0  4860.9    0.16       0  4999.4    0.07       0
  5005.4    0.16       0  5427.1    0.05       0  5611.9    0.08       0
  5687.8     0.1       0  5874.4    0.05       0
Bank Sta=4999.4,5005.4
Exp/Cntr=0.3,0.1

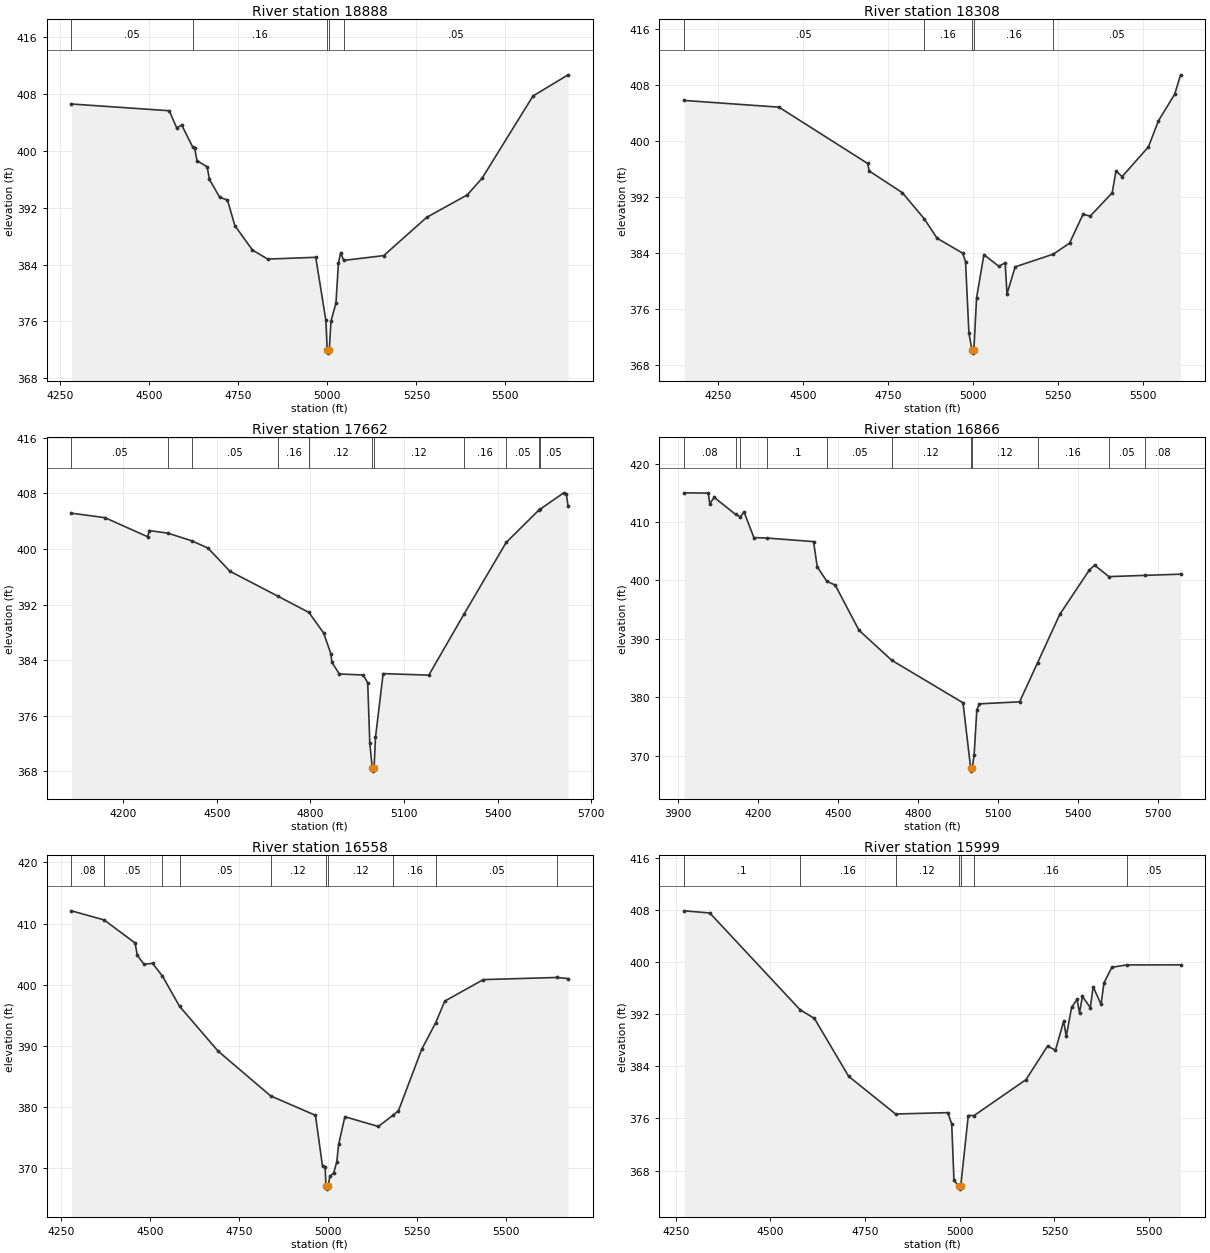
Type RM Length L Ch R = 1,18888,580,580,580
BEGIN DESCRIPTION:
CEDAR CREEK 1 27.0
END DESCRIPTION:
XS GIS Cut Line= 2
      3596424.20     10557482.72      3595513.68     10556426.52
#Sta/Elev= 30
  4281.4  406.62  4555.9  405.67  4576.8  403.27  4591.0  403.64  4621.6  400.58
  4627.2  400.43  4633.8  398.64  4662.3  397.77  4668.9  395.99  4697.5  393.48
  4719.4  393.09  4740.2  389.48  4789.6  386.04  4832.4  384.77  4967.3  385.02
  4995.8  376.12  4999.4  372.02  5002.2  371.52  5005.4  372.02  5010.1  376.02
  5024.1  378.58  5031.0  384.22  5037.6  385.69  5045.6  384.58  5158.2  385.26
  5278.9  390.65  5393.0  393.82  5434.7  396.18  5577.3  407.74  5675.9  410.73
#Mann=5,-1,0
  4281.4    0.05       0  4621.6    0.16       0  4999.4    0.07       0
  5005.4    0.16       0  5045.6    0.05       0
Bank Sta=4999.4,5005.4
Exp/Cntr=0.3,0.1

Type RM Length L Ch R = 1,18308,646,646,646
BEGIN DESCRIPTION:
CEDAR CREEK 1 26.0
END DESCRIPTION:
XS GIS Cut Line= 3
      3596439.86     10557425.48      3596294.02     10556691.09
      3595633.57     10556420.67
#Sta/Elev= 30
  4149.6  405.77  4429.2  404.81  4690.1  396.79  4695.3  395.70  4792.4  392.62
  4857.0  388.90  4894.7  386.13  4970.0  384.00  4978.7  382.80  4988.6  372.63
  4997.3  370.24  5000.1  369.74  5003.3  370.24  5011.2  377.63  5032.8  383.78
  5076.8  382.12  5095.4  382.63  5100.8  378.18  5124.8  382.04  5237.4  383.86
  5285.0  385.42  5324.5  389.52  5346.1  389.29  5410.5  392.59  5421.8  395.70
  5439.9  394.91  5517.3  399.15  5546.7  402.86  5594.7  406.66  5612.0  409.42
#Mann=5,-1,0
  4149.6    0.05       0  4857.0    0.16       0  4997.3    0.07       0
  5003.3    0.16       0  5237.4    0.05       0
Bank Sta=4997.3,5003.3
Exp/Cntr=0.3,0.1

Type RM Length L Ch R = 1,17662,796,796,796
BEGIN DESCRIPTION:
CEDAR CREEK 1 25.0
END DESCRIPTION:
XS GIS Cut Line= 3
      3596481.52     10557456.71      3596424.23     10556623.39
      3596158.64     10555915.14
#Sta/Elev= 30
  4034.0  405.15  4140.8  404.51  4278.3  401.76  4283.4  402.65  4342.7  402.28
  4420.0  401.17  4471.6  400.13  4541.7  396.80  4696.5  393.19  4795.1  390.87
  4842.4  387.90  4865.6  384.89  4868.4  383.71  4892.7  382.02  4968.8  381.87
  4983.5  380.76  4990.2  372.03  4997.9  368.54  5000.6  368.04  5003.9  368.54
  5008.4  372.88  5032.9  382.07  5179.3  381.85  5292.8  390.68  5427.3  400.94
  5533.9  405.68  5535.6  405.71  5611.8  408.08  5620.3  407.86  5625.7  406.15
#Mann=11,-1,0
  4034.0    0.05       0  4342.7    0.16       0  4420.0    0.05       0
  4696.5    0.16       0  4795.1    0.12       0  4997.9    0.07       0
  5003.9    0.12       0  5292.8    0.16       0  5427.3    0.05       0
  5533.9    0.08       0  5535.6    0.05       0
Bank Sta=4997.9,5003.9
Exp/Cntr=0.3,0.1

Type RM Length L Ch R = 1,16866,308,308,308
BEGIN DESCRIPTION:
CEDAR CREEK 1 24.0
END DESCRIPTION:
XS GIS Cut Line= 3
      3597226.33     10557394.25      3596835.69     10556612.97
      3596773.19     10555628.55
#Sta/Elev= 30
  3923.5  415.02  4014.3  414.97  4019.9  413.17  4036.7  414.23  4116.8  411.32
  4134.7  410.92  4148.5  411.73  4185.2  407.35  4235.1  407.27  4408.8  406.66
  4422.4  402.36  4458.9  399.83  4489.5  399.23  4578.9  391.47  4701.4  386.33
  4968.5  379.04  4997.2  367.83  4999.9  367.33  5003.2  367.83  5010.2  370.17
  5020.2  377.84  5030.2  378.86  5180.5  379.21  5247.5  385.88  5330.8  394.18
  5440.7  401.73  5461.1  402.63  5515.0  400.66  5651.9  400.88  5783.4  401.08
#Mann=11,-1,0
  3923.5    0.08       0  4116.8    0.05       0  4134.7    0.08       0
  4235.1     0.1       0  4458.9    0.05       0  4701.4    0.12       0
  4997.2    0.07       0  5003.2    0.12       0  5247.5    0.16       0
  5515.0    0.05       0  5651.9    0.08       0
Bank Sta=4997.2,5003.2
Exp/Cntr=0.3,0.1

Type RM Length L Ch R = 1,16558,559,559,559
BEGIN DESCRIPTION:
CEDAR CREEK 1 23.0
END DESCRIPTION:
XS GIS Cut Line= 3
      3597335.69     10557014.02      3597127.36     10556446.30
      3596892.97     10555691.07
#Sta/Elev= 30
  4279.1  412.08  4370.9  410.59  4457.7  406.83  4464.3  404.78  4482.8  403.35
  4506.9  403.50  4534.5  401.43  4582.9  396.47  4691.0  389.16  4838.6  381.84
  4964.7  378.66  4984.5  370.35  4992.0  370.19  4994.2  367.10  4997.0  366.60
  5000.2  367.10  5005.4  368.70  5015.9  369.24  5024.6  371.04  5029.8  373.90
  5047.3  378.43  5141.5  376.84  5183.2  378.70  5197.9  379.40  5263.1  389.42
  5302.8  393.83  5328.2  397.33  5436.4  400.84  5643.7  401.19  5674.6  401.01
#Mann=10,-1,0
  4279.1    0.08       0  4370.9    0.05       0  4534.5    0.08       0
  4582.9    0.05       0  4838.6    0.12       0  4994.2    0.07       0
  5000.2    0.12       0  5183.2    0.16       0  5302.8    0.05       0
  5643.7    0.08       0
Bank Sta=4994.2,5000.2
Exp/Cntr=0.3,0.1

Type RM Length L Ch R = 1,15999,356,356,356
BEGIN DESCRIPTION:
CEDAR CREEK 1 22.0
END DESCRIPTION:
XS GIS Cut Line= 3
      3597606.52     10556795.26      3597340.90     10555941.09
      3597028.45     10555665.10
#Sta/Elev= 30
  4271.9  407.89  4340.0  407.56  4578.5  392.69  4616.3  391.36  4706.6  382.47
  4830.6  376.68  4968.4  376.89  4978.9  375.15  4984.8  366.51  4996.8  365.64
  4999.6  365.14  5002.8  365.64  5022.6  376.45  5037.9  376.44  5175.1  381.96
  5232.0  387.12  5252.9  386.48  5274.6  390.96  5281.3  388.59  5295.5  393.06
  5309.8  394.29  5316.4  392.22  5324.0  394.74  5344.9  393.02  5352.4  396.23
  5373.3  393.52  5380.9  396.82  5401.8  399.22  5441.2  399.58  5583.3  399.59
#Mann=7,-1,0
  4271.9     0.1       0  4578.5    0.16       0  4830.6    0.12       0
  4996.8    0.07       0  5002.8    0.12       0  5037.9    0.16       0
  5441.2    0.05       0
Bank Sta=4996.8,5002.8
Exp/Cntr=0.3,0.1