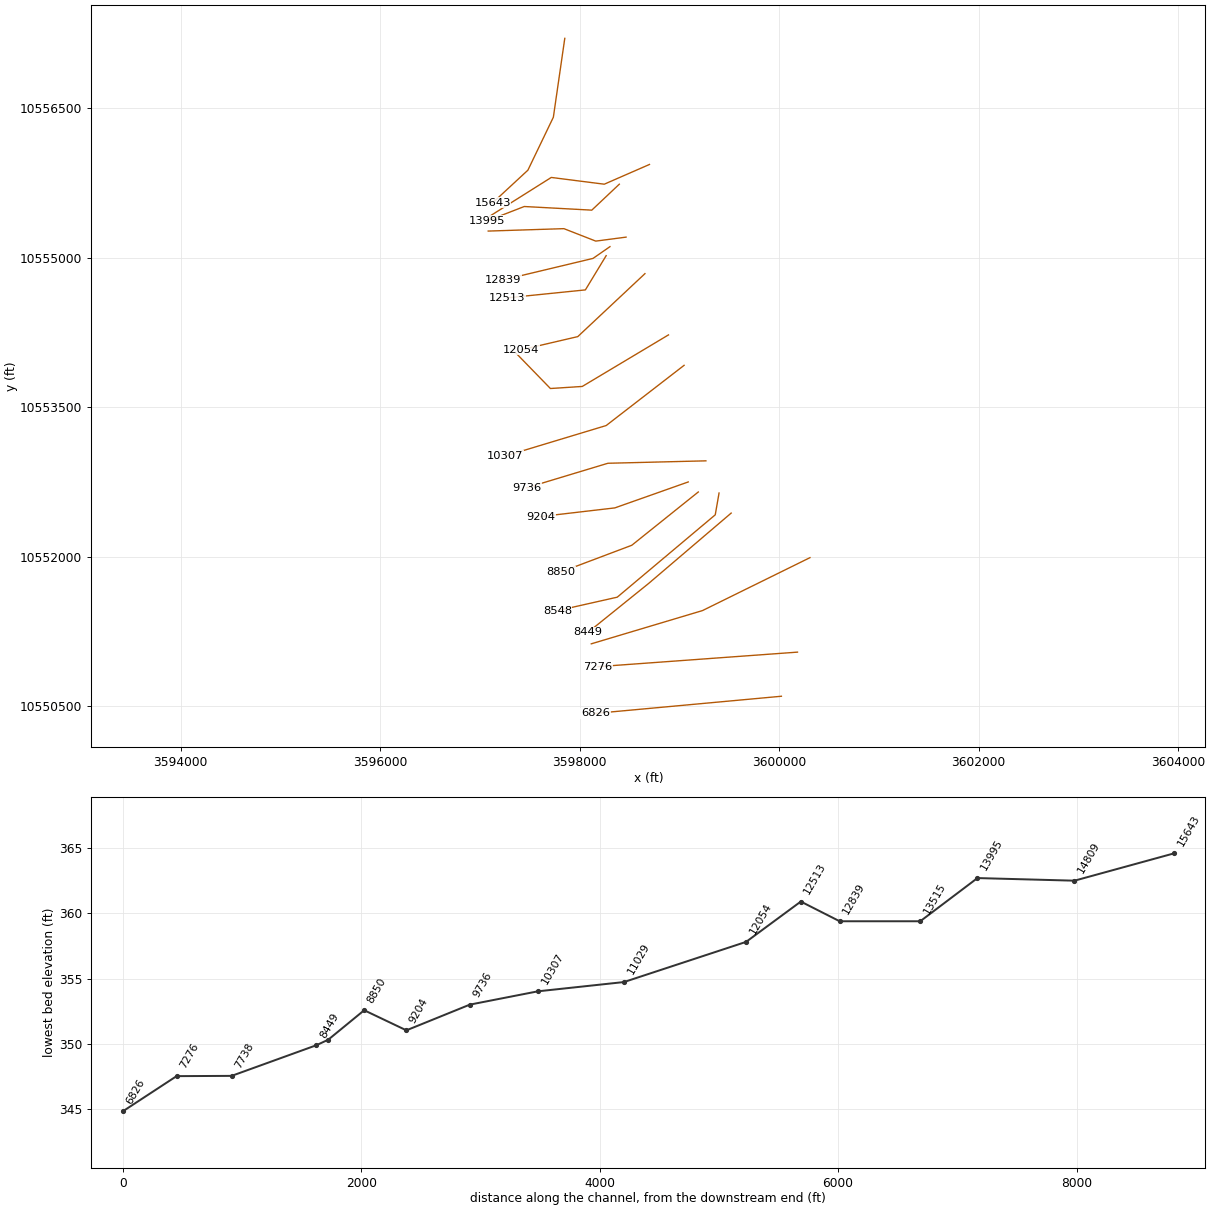
HEC-RAS study CEDAR CREEK 1.prj: CEDAR CREEK 1 Base Level Engineering

--- CEDAR CREEK 1.g01 (geometry) --- (continued)

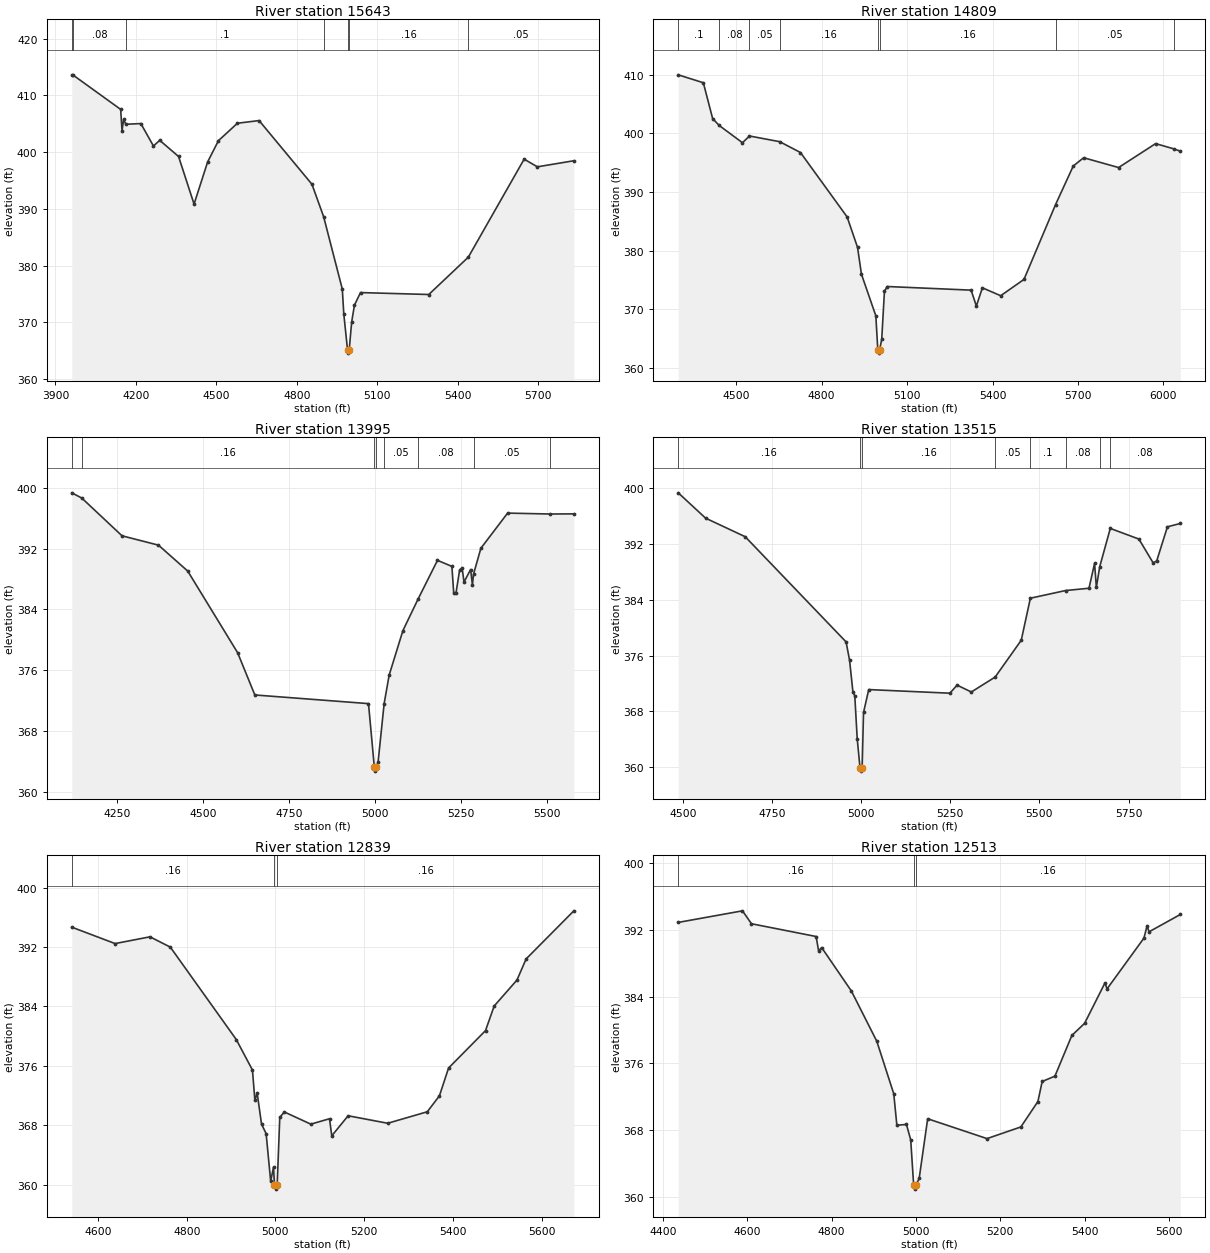
Type RM Length L Ch R = 1,15643,834,834,834
BEGIN DESCRIPTION:
CEDAR CREEK 1 21.0
END DESCRIPTION:
XS GIS Cut Line= 4
      3597851.32     10557201.52      3597736.73     10556409.84
      3597481.52     10555878.59      3597127.36     10555550.47
#Sta/Elev= 30
  3960.7  413.64  3964.6  413.63  4143.0  407.55  4148.1  403.79  4154.0  405.77
  4162.3  404.93  4218.3  405.05  4265.2  401.10  4288.6  402.10  4358.9  399.25
  4416.7  390.86  4467.3  398.29  4507.7  402.04  4578.4  405.11  4659.2  405.58
  4856.2  394.36  4899.9  388.63  4969.4  375.89  4975.0  371.51  4989.1  365.10
  4991.8  364.60  4995.1  365.10  5004.3  370.07  5014.7  373.05  5037.3  375.27
  5291.9  374.93  5439.3  381.51  5647.5  398.78  5696.8  397.43  5832.8  398.50
#Mann=7,-1,0
  3960.7    0.05       0  3964.6    0.08       0  4162.3     0.1       0
  4899.9    0.16       0  4989.1    0.07       0  4995.1    0.16       0
  5439.3    0.05       0
Bank Sta=4989.1,4995.1
Exp/Cntr=0.3,0.1

Type RM Length L Ch R = 1,14809,814,814,814
BEGIN DESCRIPTION:
CEDAR CREEK 1 20.0
END DESCRIPTION:
XS GIS Cut Line= 4
      3598700.30     10555935.90      3598247.15     10555737.97
      3597715.90     10555805.68      3597096.24     10555415.14
#Sta/Elev= 30
  4296.8  409.97  4384.9  408.62  4417.6  402.51  4440.7  401.33  4522.3  398.39
  4546.8  399.54  4652.9  398.57  4725.9  396.72  4889.6  385.74  4926.2  380.55
  4940.0  375.96  4990.4  368.88  4997.5  363.01  5000.3  362.51  5003.5  363.01
  5011.1  364.86  5020.7  373.08  5030.8  373.87  5324.9  373.25  5343.4  370.54
  5364.5  373.65  5428.8  372.30  5510.5  375.08  5621.2  387.82  5683.5  394.42
  5720.0  395.83  5842.6  394.16  5972.6  398.24  6036.1  397.35  6059.3  396.95
#Mann=8,-1,0
  4296.8     0.1       0  4440.7    0.08       0  4546.8    0.05       0
  4652.9    0.16       0  4997.5    0.07       0  5003.5    0.16       0
  5621.2    0.05       0  6036.1    0.08       0
Bank Sta=4997.5,5003.5
Exp/Cntr=0.3,0.1

Type RM Length L Ch R = 1,13995,480,480,480
BEGIN DESCRIPTION:
CEDAR CREEK 1 19.0
END DESCRIPTION:
XS GIS Cut Line= 4
      3598398.21     10555737.99      3598122.15     10555477.55
      3597445.07     10555514.01      3597070.11     10555368.20
#Sta/Elev= 30
  4119.1  399.36  4148.3  398.67  4265.2  393.70  4371.2  392.47  4456.2  389.06
  4601.3  378.31  4651.4  372.74  4981.9  371.60  4998.9  363.21  5001.6  362.71
  5004.9  363.21  5009.8  363.91  5027.4  371.60  5042.0  375.36  5082.0  381.22
  5126.7  385.43  5182.5  390.47  5224.4  389.67  5229.7  386.18  5236.2  386.12
  5246.9  389.21  5254.2  389.46  5259.6  387.61  5278.8  389.26  5284.1  387.23
  5287.4  388.67  5308.7  392.06  5386.4  396.69  5509.0  396.57  5579.0  396.59
#Mann=8,-1,0
  4119.1    0.05       0  4148.3    0.16       0  4998.9    0.07       0
  5004.9    0.16       0  5027.4    0.05       0  5126.7    0.08       0
  5287.4    0.05       0  5509.0    0.08       0
Bank Sta=4998.9,5004.9
Exp/Cntr=0.3,0.1

Type RM Length L Ch R = 1,13515,676,676,676
BEGIN DESCRIPTION:
CEDAR CREEK 1 18.0
END DESCRIPTION:
XS GIS Cut Line= 4
      3598465.87     10555206.72      3598162.08     10555166.79
      3597842.63     10555291.79      3597083.46     10555267.52
#Sta/Elev= 30
  4486.4  399.36  4563.3  395.72  4674.3  393.06  4957.5  377.95  4967.3  375.29
  4976.6  370.79  4981.9  370.19  4988.7  364.03  4996.5  359.90  4999.2  359.40
  5002.5  359.90  5006.4  367.82  5021.0  371.11  5248.9  370.59  5268.9  371.75
  5308.9  370.76  5375.8  372.91  5449.0  378.19  5474.6  384.23  5573.4  385.33
  5639.1  385.66  5654.8  389.22  5659.8  385.79  5669.3  388.76  5698.9  394.25
  5779.2  392.72  5819.2  389.30  5829.2  389.59  5859.2  394.48  5895.4  394.96
#Mann=8,-1,0
  4486.4    0.16       0  4996.5    0.07       0  5002.5    0.16       0
  5375.8    0.05       0  5474.6     0.1       0  5573.4    0.08       0
  5669.3    0.05       0  5698.9    0.08       0
Bank Sta=4996.5,5002.5
Exp/Cntr=0.3,0.1

Type RM Length L Ch R = 1,12839,326,326,326
BEGIN DESCRIPTION:
CEDAR CREEK 1 17.0
END DESCRIPTION:
XS GIS Cut Line= 3
      3598304.42     10555111.22      3598134.30     10554993.18
      3597234.97     10554777.89
#Sta/Elev= 30
  4540.9  394.68  4638.6  392.47  4717.2  393.38  4763.1  391.99  4911.7  379.55
  4948.2  375.44  4953.7  371.35  4958.8  372.35  4968.7  368.15  4979.0  366.88
  4989.3  360.47  4995.7  362.36  4997.9  359.90  5000.6  359.40  5003.9  359.90
  5009.8  369.07  5020.1  369.79  5079.8  368.15  5121.9  368.88  5127.0  366.58
  5163.9  369.28  5253.1  368.27  5342.4  369.82  5369.7  371.97  5390.3  375.71
  5473.6  380.75  5493.1  384.06  5544.5  387.56  5565.1  390.40  5672.7  396.88
#Mann=3,-1,0
  4540.9    0.16       0  4997.9    0.07       0  5003.9    0.16       0
Bank Sta=4997.9,5003.9
Exp/Cntr=0.3,0.1

Type RM Length L Ch R = 1,12513,459,459,459
BEGIN DESCRIPTION:
CEDAR CREEK 1 16.0
END DESCRIPTION:
XS GIS Cut Line= 3
      3598266.23     10555020.93      3598057.91     10554677.21
      3597273.89     10554597.42
#Sta/Elev= 30
  4436.5  392.90  4588.8  394.29  4610.1  392.74  4763.3  391.21  4769.1  389.51
  4776.5  389.88  4846.8  384.68  4907.1  378.65  4947.3  372.35  4954.7  368.57
  4977.4  368.67  4987.5  366.82  4994.5  361.41  4997.3  360.91  5000.5  361.41
  5007.6  362.21  5027.7  369.35  5168.4  366.97  5248.6  368.37  5289.0  371.42
  5299.1  373.82  5329.3  374.46  5369.5  379.35  5399.6  380.79  5447.9  385.64
  5452.9  384.93  5540.3  391.02  5547.5  392.45  5552.6  391.78  5626.5  393.85
#Mann=3,-1,0
  4436.5    0.16       0  4994.5    0.07       0  5000.5    0.16       0
Bank Sta=4994.5,5000.5
Exp/Cntr=0.3,0.1

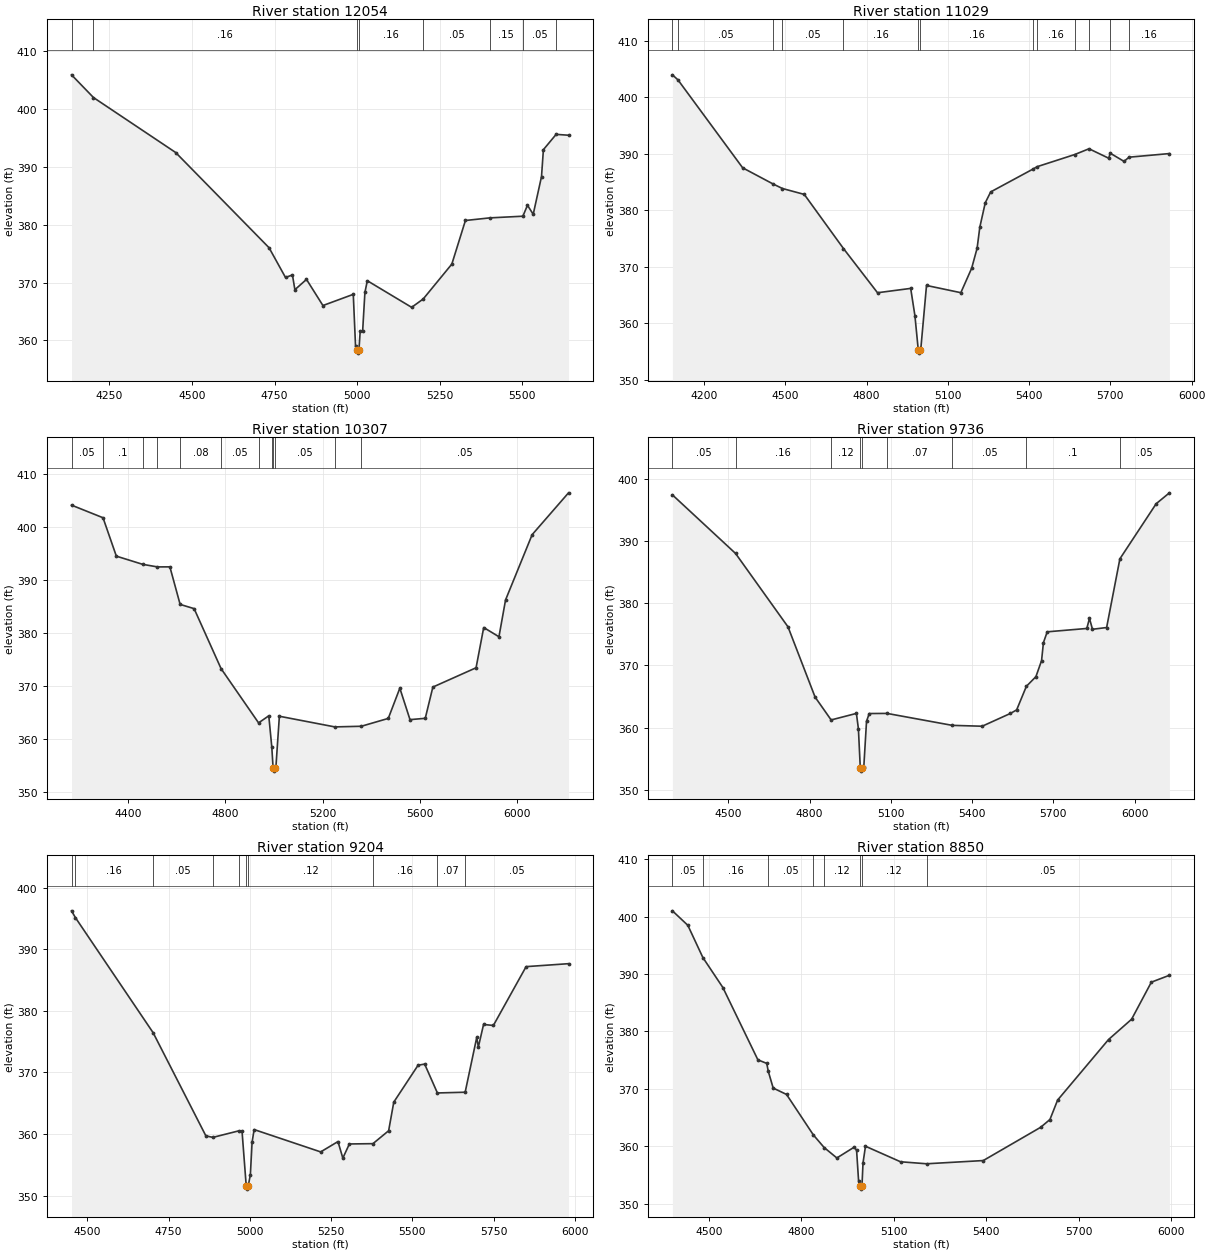
Type RM Length L Ch R = 1,12054,1025,1025,1025
BEGIN DESCRIPTION:
CEDAR CREEK 1 15.0
END DESCRIPTION:
XS GIS Cut Line= 3
      3598655.12     10554840.39      3597981.52     10554208.46
      3597415.52     10554076.50
#Sta/Elev= 30
  4135.2  405.83  4201.7  401.91  4450.5  392.43  4733.3  376.00  4783.1  370.87
  4804.1  371.31  4811.5  368.76  4846.6  370.54  4896.4  366.03  4988.3  367.96
  4995.1  359.07  4999.4  358.32  5002.2  357.82  5005.4  358.32  5009.3  361.67
  5016.6  361.57  5023.5  368.29  5030.8  370.31  5165.0  365.72  5200.0  367.16
  5286.7  373.18  5327.8  380.70  5401.2  381.15  5501.8  381.44  5515.7  383.33
  5533.1  381.77  5558.2  388.28  5563.9  392.92  5602.5  395.56  5640.0  395.41
#Mann=8,-1,0
  4135.2    0.05       0  4201.7    0.16       0  4999.4    0.07       0
  5005.4    0.16       0  5200.0    0.05       0  5401.2    0.15       0
  5501.8    0.05       0  5602.5    0.16       0
Bank Sta=4999.4,5005.4
Exp/Cntr=0.3,0.1

Type RM Length L Ch R = 1,11029,722,722,722
BEGIN DESCRIPTION:
CEDAR CREEK 1 14.0
END DESCRIPTION:
XS GIS Cut Line= 4
      3598891.28     10554225.83      3598026.66     10553708.46
      3597707.22     10553687.62      3597353.82     10554051.42
#Sta/Elev= 30
  4083.0  404.01  4103.4  403.12  4342.3  387.55  4455.3  384.67  4489.4  383.88
  4569.8  382.84  4714.6  373.25  4840.2  365.43  4962.7  366.20  4978.3  361.37
  4990.8  355.24  4993.6  354.74  4996.8  355.24  4999.7  355.31  5021.1  366.72
  5147.8  365.44  5187.8  369.77  5207.9  373.31  5217.9  377.04  5238.0  381.36
  5258.0  383.28  5414.4  387.33  5429.6  387.75  5567.8  389.89  5621.1  390.92
  5693.6  389.25  5699.5  390.13  5750.2  388.69  5769.0  389.43  5917.9  390.07
#Mann=13,-1,0
  4083.0    0.08       0  4103.4    0.05       0  4455.3    0.08       0
  4489.4    0.05       0  4714.6    0.16       0  4990.8    0.07       0
  4996.8    0.16       0  5414.4    0.05       0  5429.6    0.16       0
  5567.8    0.05       0  5621.1    0.16       0  5699.5    0.05       0
  5769.0    0.16       0
Bank Sta=4990.8,4996.8
Exp/Cntr=0.3,0.1

Type RM Length L Ch R = 1,10307,571,571,571
BEGIN DESCRIPTION:
CEDAR CREEK 1 13.0
END DESCRIPTION:
XS GIS Cut Line= 3
      3599047.48     10553920.25      3598266.25     10553316.09
      3597255.83     10553010.54
#Sta/Elev= 30
  4167.5  404.19  4297.0  401.81  4351.8  394.57  4460.5  393.02  4520.9  392.54
  4571.9  392.55  4614.0  385.47  4671.5  384.67  4782.3  373.36  4936.5  363.13
  4978.5  364.46  4990.9  358.53  4996.3  354.53  4999.0  354.03  5002.3  354.53
  5007.5  354.63  5022.0  364.38  5249.8  362.37  5358.8  362.49  5469.7  363.97
  5517.2  369.67  5559.0  363.74  5621.7  363.99  5653.0  369.88  5830.6  373.52
  5862.0  381.11  5924.7  379.37  5951.8  386.31  6061.1  398.62  6210.7  406.51
#Mann=12,-1,0
  4167.5    0.05       0  4297.0     0.1       0  4460.5    0.15       0
  4520.9     0.1       0  4614.0    0.08       0  4782.3    0.05       0
  4936.5    0.07       0  4990.9    0.05       0  4996.3    0.03       0
  5002.3    0.05       0  5249.8    0.07       0  5358.8    0.05       0
Bank Sta=4996.3,5002.3
Exp/Cntr=0.3,0.1

Type RM Length L Ch R = 1,9736,532,532,532
BEGIN DESCRIPTION:
CEDAR CREEK 1 12.0
END DESCRIPTION:
XS GIS Cut Line= 3
      3599266.23     10552961.93      3598283.61     10552937.62
      3597467.66     10552691.10
#Sta/Elev= 30
  4293.2  397.43  4526.4  388.01  4720.0  376.21  4820.0  364.92  4879.3  361.24
  4972.6  362.29  4980.0  359.83  4987.0  353.51  4989.8  353.01  4993.0  353.51
  5000.0  353.74  5010.0  361.02  5020.0  362.27  5085.7  362.29  5326.5  360.37
  5437.0  360.23  5541.5  362.29  5564.4  362.86  5600.3  366.65  5635.5  368.20
  5656.4  370.79  5663.2  373.67  5677.3  375.41  5823.5  375.95  5833.2  377.57
  5844.4  375.82  5896.6  376.10  5945.6  387.15  6079.6  396.01  6128.5  397.76
#Mann=9,-1,0
  4293.2    0.05       0  4526.4    0.16       0  4879.3    0.12       0
  4987.0    0.07       0  4993.0    0.12       0  5085.7    0.07       0
  5326.5    0.05       0  5600.3     0.1       0  5945.6    0.05       0
Bank Sta=4987,4993
Exp/Cntr=0.3,0.1

Type RM Length L Ch R = 1,9204,354,354,354
BEGIN DESCRIPTION:
CEDAR CREEK 1 11.0
END DESCRIPTION:
XS GIS Cut Line= 3
      3599089.20     10552750.14      3598353.05     10552489.71
      3597609.97     10552402.90
#Sta/Elev= 30
  4451.5  396.27  4463.7  395.15  4702.6  376.46  4864.8  359.70  4886.4  359.45
  4966.0  360.51  4976.1  360.44  4989.0  351.54  4991.8  351.04  4995.0  351.54
  5001.7  353.37  5007.0  358.67  5013.3  360.72  5218.0  357.09  5271.2  358.77
  5286.2  356.08  5306.3  358.38  5378.8  358.43  5427.1  360.53  5442.9  365.18
  5517.7  371.18  5537.9  371.36  5577.1  366.67  5662.5  366.79  5698.1  375.69
  5703.1  374.14  5719.1  377.80  5749.3  377.64  5850.0  387.20  5980.5  387.68
#Mann=10,-1,0
  4451.5    0.05       0  4463.7    0.16       0  4702.6    0.05       0
  4886.4    0.16       0  4966.0    0.12       0  4989.0    0.07       0
  4995.0    0.12       0  5378.8    0.16       0  5577.1    0.07       0
  5662.5    0.05       0
Bank Sta=4989,4995
Exp/Cntr=0.3,0.1

Type RM Length L Ch R = 1,8850,302,302,302
BEGIN DESCRIPTION:
CEDAR CREEK 1 10.0
END DESCRIPTION:
XS GIS Cut Line= 3
      3599189.88     10552649.45      3598523.19     10552114.71
      3597814.82     10551847.33
#Sta/Elev= 30
  4381.7  400.99  4431.7  398.47  4480.4  392.87  4545.3  387.65  4658.9  375.07
  4687.7  374.45  4692.5  373.09  4708.5  370.16  4751.8  369.05  4838.9  362.00
  4873.7  359.82  4915.0  358.00  4971.7  359.90  4979.0  359.31  4985.4  354.07
  4990.4  353.08  4993.2  352.58  4996.4  353.08  4999.8  357.13  5007.8  360.04
  5121.4  357.34  5206.1  356.99  5389.8  357.55  5575.8  363.33  5606.0  364.69
  5630.9  368.07  5796.0  378.60  5870.8  382.13  5934.9  388.58  5993.5  389.78
#Mann=8,-1,0
  4381.7    0.05       0  4480.4    0.16       0  4692.5    0.05       0
  4838.9    0.16       0  4873.7    0.12       0  4990.4    0.07       0
  4996.4    0.12       0  5206.1    0.05       0
Bank Sta=4990.4,4996.4
Exp/Cntr=0.3,0.1

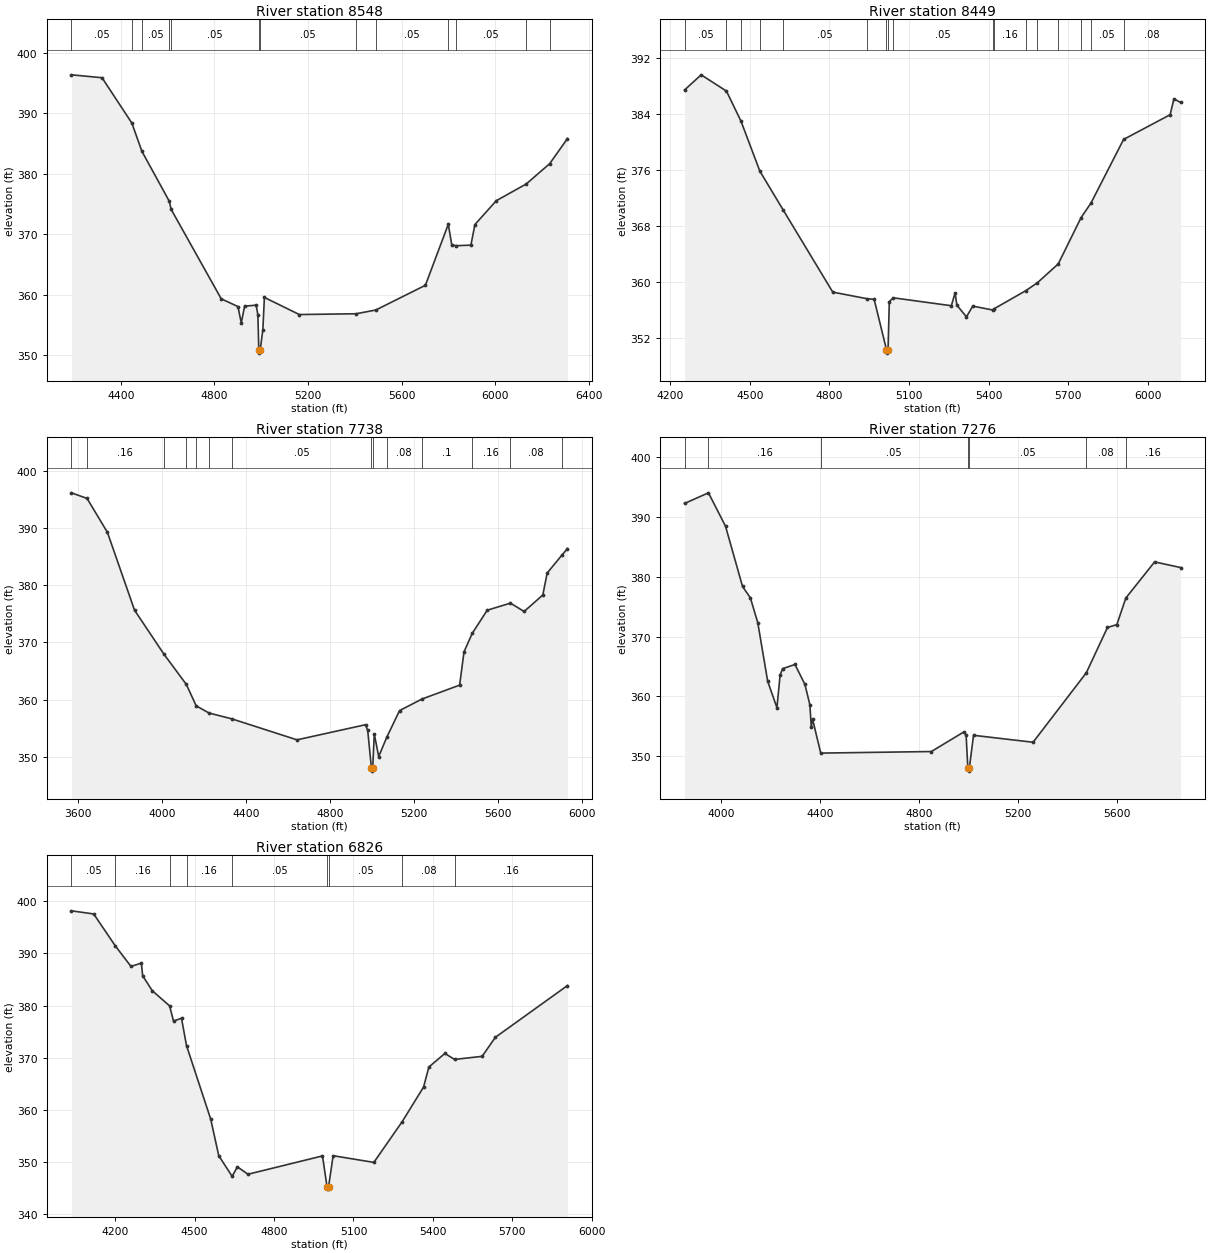
Type RM Length L Ch R = 1,8548,99,99,99
BEGIN DESCRIPTION:
Mapping XS 4e0cc6ac
END DESCRIPTION:
XS GIS Cut Line= 4
      3599398.20     10552639.05      3599360.00     10552420.26
      3598377.36     10551593.87      3597776.67     10551458.46
#Sta/Elev= 30
  4188.2  396.34  4319.0  395.86  4446.7  388.35  4489.4  383.70  4606.6  375.44
  4614.5  374.10  4828.9  359.30  4900.3  358.02  4914.6  355.32  4928.9  358.09
  4978.3  358.25  4985.7  356.60  4989.6  350.82  4992.4  350.32  4995.6  350.82
  5006.9  354.18  5013.5  359.53  5163.0  356.70  5405.9  356.83  5490.1  357.45
  5702.2  361.54  5800.2  371.63  5814.9  368.26  5831.7  368.08  5896.9  368.18
  5914.0  371.58  6005.6  375.53  6133.2  378.28  6233.7  381.64  6310.0  385.80
#Mann=13,-1,0
  4188.2    0.05       0  4446.7    0.08       0  4489.4    0.05       0
  4606.6    0.08       0  4614.5    0.05       0  4989.6    0.04       0
  4995.6    0.05       0  5405.9    0.08       0  5490.1    0.05       0
  5800.2    0.08       0  5831.7    0.05       0  6133.2    0.08       0
  6233.7    0.05       0
Bank Sta=4989.6,4995.6
Exp/Cntr=0.3,0.1

Type RM Length L Ch R = 1,8449,711,711,711
BEGIN DESCRIPTION:
CEDAR CREEK 1 9.0
END DESCRIPTION:
XS GIS Cut Line= 3
      3599519.74     10552437.64      3598693.33     10551732.76
      3598083.39     10551240.65
#Sta/Elev= 30
  4254.3  387.44  4316.7  389.59  4412.1  387.27  4466.8  382.99  4537.9  375.86
  4625.2  370.36  4812.9  358.60  4942.1  357.66  4968.9  357.57  5015.3  350.40
  5018.0  349.90  5021.3  350.40  5026.0  357.25  5041.0  357.79  5259.8  356.66
  5274.1  358.49  5280.7  356.74  5316.9  355.07  5340.5  356.61  5416.7  356.04
  5420.3  356.21  5539.8  358.79  5584.5  359.94  5663.0  362.63  5748.7  369.21
  5786.2  371.30  5909.3  380.38  6084.6  383.90  6099.0  386.16  6124.2  385.65
#Mann=17,-1,0
  4254.3    0.05       0  4412.1    0.08       0  4466.8    0.05       0
  4537.9    0.08       0  4625.2    0.05       0  4942.1    0.12       0
  5015.3    0.07       0  5021.3    0.12       0  5041.0    0.05       0
  5416.7    0.08       0  5420.3    0.16       0  5539.8    0.05       0
  5584.5    0.16       0  5663.0    0.08       0  5748.7    0.16       0
  5786.2    0.05       0  5909.3    0.08       0
Bank Sta=5015.3,5021.3
Exp/Cntr=0.3,0.1

Type RM Length L Ch R = 1,7738,462,462,462
BEGIN DESCRIPTION:
CEDAR CREEK 1 8.0
END DESCRIPTION:
XS GIS Cut Line= 3
      3600309.65     10551990.40      3599231.52     10551459.15
      3598116.91     10551125.81
#Sta/Elev= 30
  3566.9  396.12  3641.3  395.14  3738.4  389.22  3867.6  375.64  4006.6  368.03
  4114.7  362.68  4161.6  358.95  4222.9  357.69  4331.0  356.68  4642.4  353.01
  4969.1  355.65  4979.6  354.65  4997.4  348.05  5000.2  347.55  5003.4  348.05
  5010.9  354.03  5032.0  350.10  5070.0  353.42  5131.3  358.11  5238.1  360.13
  5417.9  362.56  5438.8  368.36  5478.1  371.60  5549.4  375.63  5660.3  376.87
  5725.4  375.41  5814.6  378.29  5835.4  382.12  5904.8  385.21  5932.2  386.39
#Mann=14,-1,0
  3566.9    0.05       0  3641.3    0.16       0  4006.6    0.12       0
  4114.7    0.16       0  4161.6    0.12       0  4222.9    0.16       0
  4331.0    0.05       0  4997.4    0.03       0  5003.4    0.05       0
  5070.0    0.08       0  5238.1     0.1       0  5478.1    0.16       0
  5660.3    0.08       0  5904.8    0.16       0
Bank Sta=4997.4,5003.4
Exp/Cntr=0.3,0.1

Type RM Length L Ch R = 1,7276,450,450,450
BEGIN DESCRIPTION:
CEDAR CREEK 1 7.0
END DESCRIPTION:
XS GIS Cut Line= 2
      3600184.66     10551042.48      3598184.67     10550896.65
#Sta/Elev= 30
  3851.8  392.21  3948.2  393.98  4017.3  388.40  4086.0  378.35  4117.6  376.46
  4147.6  372.31  4187.7  362.52  4225.0  358.13  4237.9  363.56  4247.9  364.63
  4298.0  365.33  4338.1  362.02  4358.2  358.61  4363.9  354.93  4368.9  356.25
  4402.1  350.54  4849.5  350.80  4979.8  354.05  4989.9  353.57  4996.9  348.03
  4999.6  347.53  5002.9  348.03  5019.9  353.51  5260.6  352.35  5475.8  363.94
  5561.4  371.51  5599.3  371.98  5635.6  376.42  5751.9  382.45  5857.1  381.51
#Mann=7,-1,0
  3851.8    0.05       0  3948.2    0.16       0  4402.1    0.05       0
  4996.9    0.03       0  5002.9    0.05       0  5475.8    0.08       0
  5635.6    0.16       0
Bank Sta=4996.9,5002.9
Exp/Cntr=0.3,0.1

Type RM Length L Ch R = 1,6826,361,361,361
BEGIN DESCRIPTION:
CEDAR CREEK 1 6.0
END DESCRIPTION:
XS GIS Cut Line= 2
      3600023.23     10550599.78      3598158.64     10550427.90
#Sta/Elev= 30
  4035.4  398.14  4119.4  397.54  4200.4  391.46  4260.0  387.50  4299.2  388.12
  4304.2  385.70  4340.3  382.85  4405.9  379.93  4420.6  377.03  4450.8  377.56
  4469.7  372.33  4561.2  358.22  4591.4  351.25  4641.9  347.29  4661.7  349.11
  4701.8  347.69  4983.0  351.20  5000.1  345.34  5002.9  344.84  5006.1  345.34
  5023.2  351.24  5176.9  349.96  5283.9  357.76  5364.6  364.39  5384.7  368.23
  5445.0  370.82  5481.8  369.68  5585.6  370.27  5635.8  373.92  5907.9  383.83
#Mann=9,-1,0
  4035.4    0.05       0  4200.4    0.16       0  4405.9    0.05       0
  4469.7    0.16       0  4641.9    0.05       0  5000.1    0.03       0
  5006.1    0.05       0  5283.9    0.08       0  5481.8    0.16       0
Bank Sta=5000.1,5006.1
Exp/Cntr=0.3,0.1