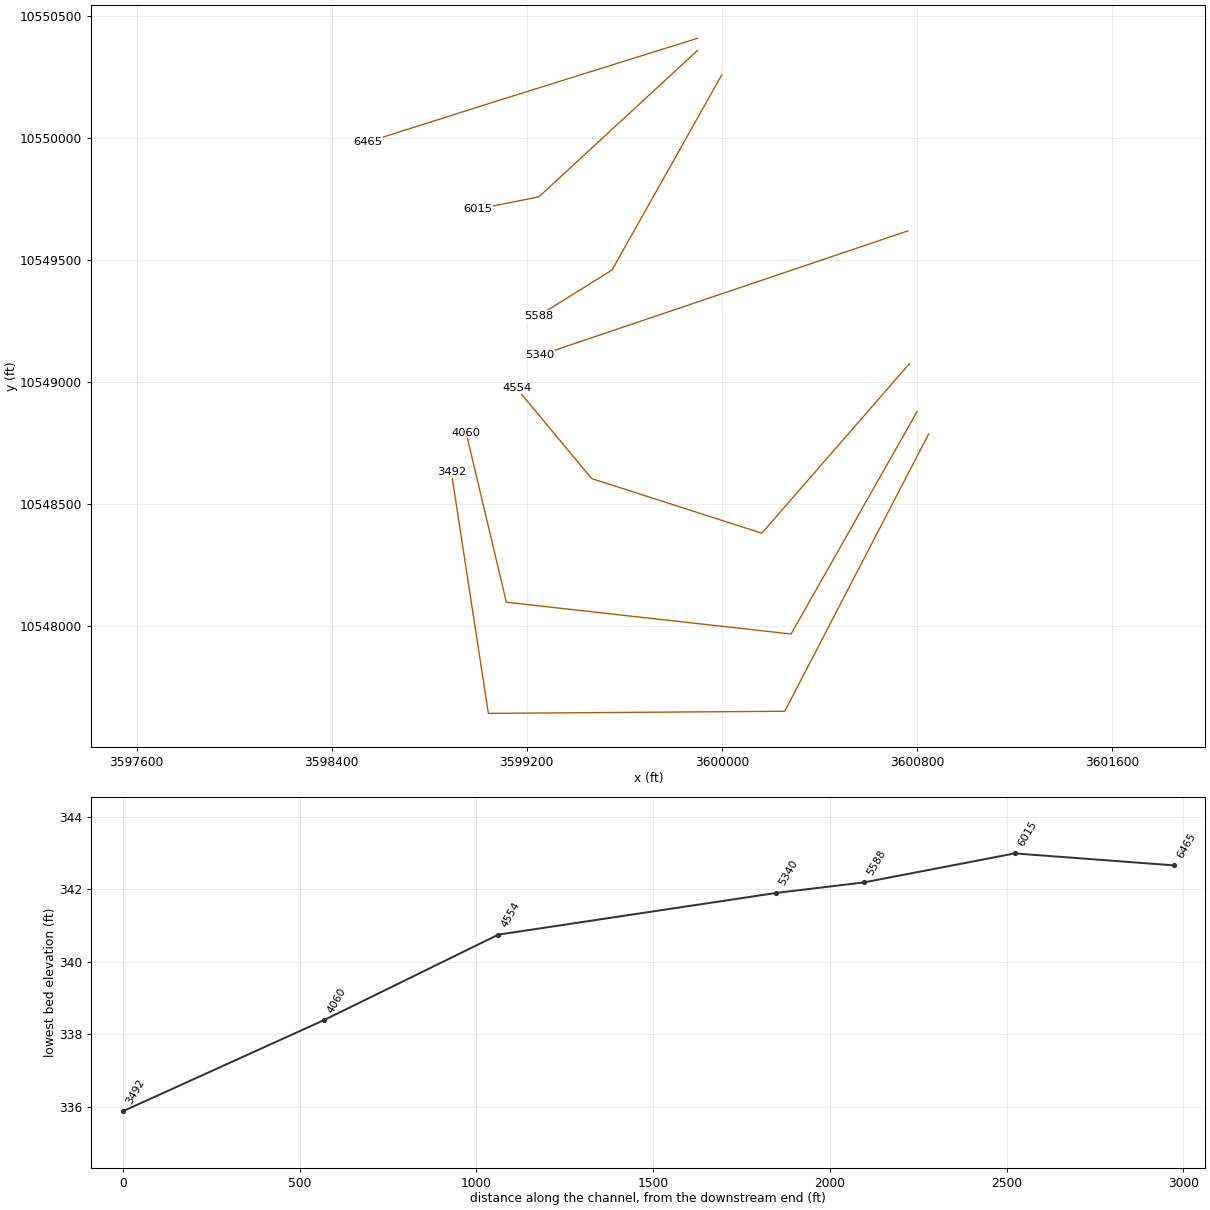
HEC-RAS study CEDAR CREEK 1.prj: CEDAR CREEK 1 Base Level Engineering

--- CEDAR CREEK 1.g01 (geometry) --- (continued)

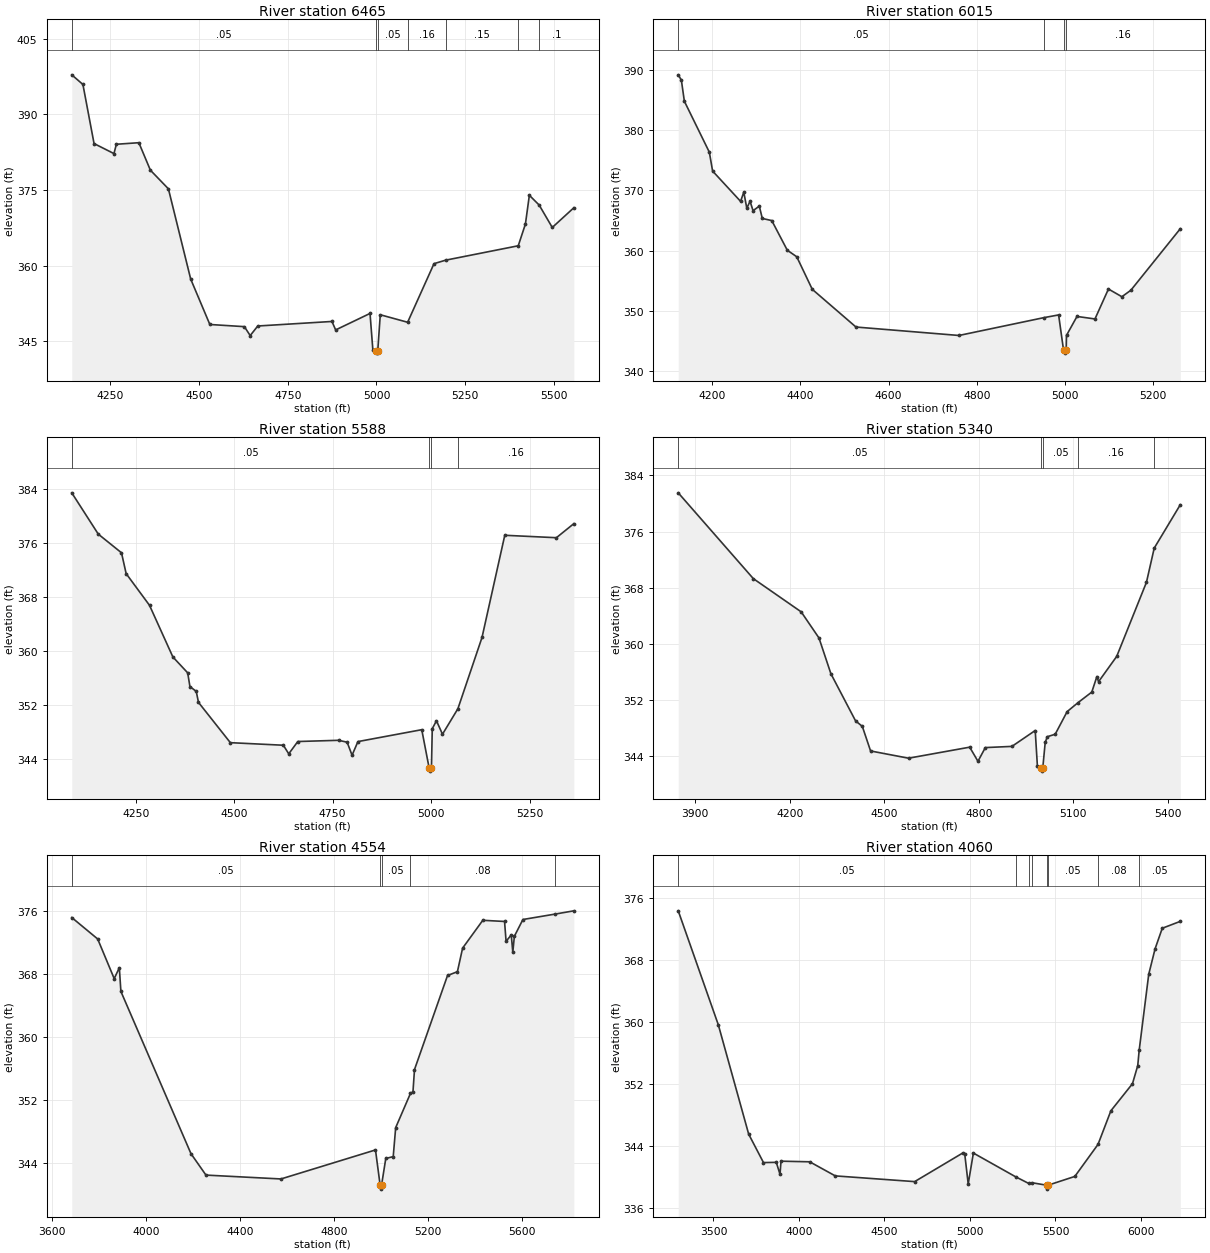
Type RM Length L Ch R = 1,6465,450,450,450
BEGIN DESCRIPTION:
CEDAR CREEK 1 5.0
END DESCRIPTION:
XS GIS Cut Line= 3
      3599899.59     10550410.18      3599099.61     10550160.19
      3598549.47     10549985.95
#Sta/Elev= 30
  4141.2  397.85  4172.6  395.94  4204.0  384.22  4260.1  382.23  4266.9  384.08
  4330.3  384.39  4362.8  378.94  4413.6  375.24  4476.4  357.35  4530.4  348.34
  4627.8  347.91  4644.1  346.14  4665.5  348.04  4874.6  348.94  4885.0  347.26
  4981.9  350.53  4989.8  343.37  4997.7  343.16  5000.5  342.66  5003.7  343.16
  5010.8  350.27  5087.9  348.78  5162.2  360.40  5194.8  361.09  5399.7  363.95
  5419.9  368.26  5431.0  373.96  5458.7  372.02  5495.6  367.58  5556.4  371.49
#Mann=7,-1,0
  4141.2    0.05       0  4997.7    0.03       0  5003.7    0.05       0
  5087.9    0.16       0  5194.8    0.15       0  5399.7    0.08       0
  5458.7     0.1       0
Bank Sta=4997.7,5003.7
Exp/Cntr=0.3,0.1

Type RM Length L Ch R = 1,6015,427,427,427
BEGIN DESCRIPTION:
CEDAR CREEK 1 4.0
END DESCRIPTION:
XS GIS Cut Line= 3
      3599899.60     10550360.18      3599249.61     10549760.19
      3598999.63     10549710.19
#Sta/Elev= 30
  4122.6  389.18  4129.7  388.30  4136.5  384.80  4193.2  376.34  4200.6  373.21
  4264.1  368.18  4271.4  369.71  4278.2  367.04  4285.6  368.20  4292.4  366.63
  4306.6  367.39  4313.4  365.34  4334.9  364.99  4370.1  360.07  4391.6  358.98
  4426.8  353.58  4526.0  347.32  4759.7  345.92  4952.5  348.88  4985.9  349.33
  4997.1  343.49  4999.8  342.99  5003.1  343.49  5003.8  345.94  5027.6  349.08
  5068.4  348.66  5099.0  353.63  5129.5  352.35  5149.9  353.43  5262.1  363.64
#Mann=4,-1,0
  4122.6    0.05       0  4952.5    0.16       0  4997.1    0.07       0
  5003.1    0.16       0
Bank Sta=4997.1,5003.1
Exp/Cntr=0.3,0.1

Type RM Length L Ch R = 1,5588,248,248,248
BEGIN DESCRIPTION:
CEDAR CREEK 1 3.0
END DESCRIPTION:
XS GIS Cut Line= 3
      3599999.62     10550260.20      3599549.61     10549460.19
      3599247.15     10549271.65
#Sta/Elev= 30
  4087.9  383.36  4155.2  377.25  4214.1  374.49  4225.9  371.41  4285.2  366.72
  4344.5  359.08  4382.1  356.73  4387.8  354.70  4403.8  353.99  4409.5  352.36
  4490.4  346.40  4624.9  346.02  4638.6  344.75  4661.6  346.57  4764.9  346.75
  4786.8  346.47  4799.3  344.54  4814.2  346.56  4976.2  348.32  4994.8  342.69
  4997.6  342.19  5000.8  342.69  5002.9  348.47  5013.5  349.64  5028.8  347.65
  5067.9  351.42  5129.1  361.96  5186.9  377.08  5317.9  376.72  5362.2  378.80
#Mann=4,-1,0
  4087.9    0.05       0  4994.8    0.03       0  5000.8    0.05       0
  5067.9    0.16       0
Bank Sta=4994.8,5000.8
Exp/Cntr=0.3,0.1

Type RM Length L Ch R = 1,5340,786,786,786
BEGIN DESCRIPTION:
CEDAR CREEK 1 2.0
END DESCRIPTION:
XS GIS Cut Line= 2
      3600762.73     10549620.59      3599253.48     10549110.57
#Sta/Elev= 30
  3846.3  381.51  4084.5  369.30  4236.4  364.57  4292.9  360.85  4330.8  355.75
  4409.0  349.05  4430.4  348.27  4456.6  344.77  4577.1  343.74  4771.1  345.31
  4797.3  343.30  4820.7  345.25  4905.1  345.42  4979.0  347.68  4986.0  342.57
  4997.1  342.40  4999.9  341.90  5003.1  342.40  5010.7  345.98  5017.4  346.80
  5042.4  347.15  5080.3  350.37  5114.9  351.65  5158.5  353.15  5174.7  355.36
  5180.0  354.63  5237.6  358.23  5332.0  368.78  5356.6  373.64  5439.4  379.82
#Mann=5,-1,0
  3846.3    0.05       0  4997.1    0.03       0  5003.1    0.05       0
  5114.9    0.16       0  5356.6    0.08       0
Bank Sta=4997.1,5003.1
Exp/Cntr=0.3,0.1

Type RM Length L Ch R = 1,4554,494,494,494
BEGIN DESCRIPTION:
Mapping XS 36536dca
END DESCRIPTION:
XS GIS Cut Line= 4
      3600769.01     10549075.99      3600163.82     10548381.02
      3599465.90     10548604.98      3599158.62     10548974.76
#Sta/Elev= 30
  3685.3  375.19  3795.5  372.47  3865.8  367.44  3887.6  368.83  3894.2  365.82
  4192.4  345.24  4256.0  342.53  4575.0  342.04  4977.0  345.72  4996.8  341.25
  4999.6  340.75  5002.8  341.25  5020.8  344.64  5052.4  344.87  5062.9  348.55
  5125.7  352.89  5136.4  353.09  5142.9  355.91  5283.4  367.84  5325.4  368.32
  5347.5  371.31  5433.4  374.84  5525.9  374.69  5532.4  372.17  5554.5  372.99
  5561.0  370.78  5567.6  372.81  5604.0  374.94  5739.5  375.62  5820.6  376.04
#Mann=5,-1,0
  3685.3    0.05       0  4996.8    0.03       0  5002.8    0.05       0
  5125.7    0.08       0  5739.5    0.05       0
Bank Sta=4996.8,5002.8
Exp/Cntr=0.3,0.1

Type RM Length L Ch R = 1,4060,568,568,568
BEGIN DESCRIPTION:
Mapping XS fe9e6990
END DESCRIPTION:
XS GIS Cut Line= 4
      3600800.29     10548879.11      3600283.79     10547967.64
      3599116.25     10548097.85      3598951.32     10548792.31
#Sta/Elev= 30
  3293.9  374.34  3528.4  359.61  3705.9  345.49  3792.4  341.82  3867.4  341.85
  3889.1  340.30  3894.9  342.00  4062.8  341.92  4212.2  340.10  4676.5  339.36
  4959.5  343.08  4969.6  342.89  4989.7  339.06  5019.9  343.05  5266.5  339.99
  5344.1  339.12  5361.8  339.22  5449.6  338.89  5452.3  338.39  5455.6  338.89
  5613.2  340.03  5748.9  344.17  5824.1  348.51  5950.4  352.01  5981.2  354.35
  5989.5  356.32  6045.4  366.14  6082.5  369.43  6124.6  372.09  6230.1  372.98
#Mann=8,-1,0
  3293.9    0.05       0  5266.5    0.08       0  5344.1     0.1       0
  5361.8    0.05       0  5449.6    0.03       0  5455.6    0.05       0
  5748.9    0.08       0  5989.5    0.05       0
Bank Sta=5449.6,5455.6
Exp/Cntr=0.3,0.1

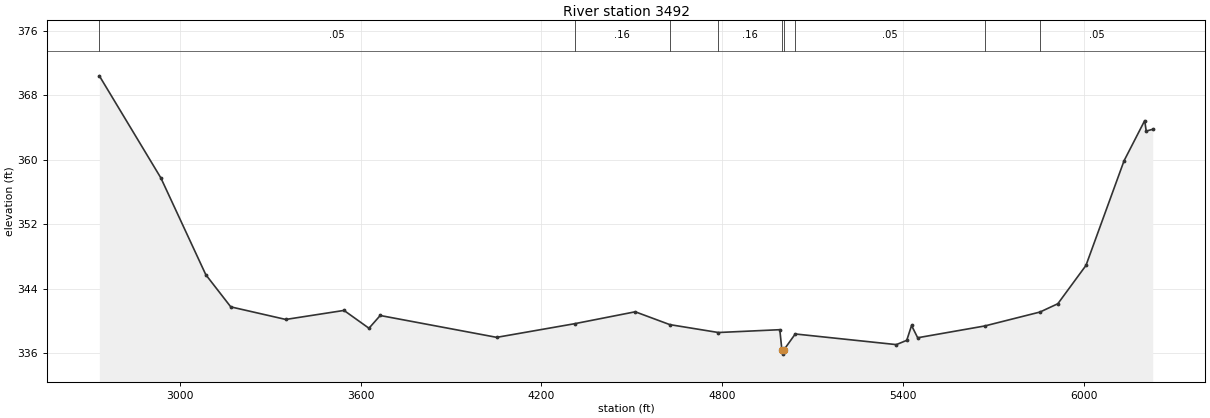
Type RM Length L Ch R = 1,3492,0,0,0
BEGIN DESCRIPTION:
CEDAR CREEK 1 1.0
END DESCRIPTION:
XS GIS Cut Line= 4
      3600848.02     10548787.95      3600257.75     10547650.80
      3599042.47     10547642.12      3598890.56     10548631.69
#Sta/Elev= 30
  2732.0  370.39  2936.3  357.73  3085.5  345.73  3168.4  341.74  3351.0  340.18
  3544.4  341.30  3627.3  339.09  3664.6  340.67  4051.4  337.96  4309.8  339.65
  4511.4  341.13  4626.1  339.54  4787.5  338.56  4991.4  338.91  4998.4  336.38
  5001.1  335.88  5004.4  336.38  5042.7  338.38  5378.3  337.06  5412.9  337.59
  5428.9  339.43  5449.2  337.91  5671.6  339.37  5855.3  341.10  5914.6  342.13
  6008.0  346.88  6134.6  359.87  6203.0  364.84  6208.0  363.54  6229.7  363.76
#Mann=9,-1,0
  2732.0    0.05       0  4309.8    0.16       0  4626.1    0.05       0
  4787.5    0.16       0  4998.4    0.07       0  5004.4    0.16       0
  5042.7    0.05       0  5671.6    0.08       0  5855.3    0.05       0
Bank Sta=4998.4,5004.4
Exp/Cntr=0.3,0.1

Chan Stop Cuts=-1