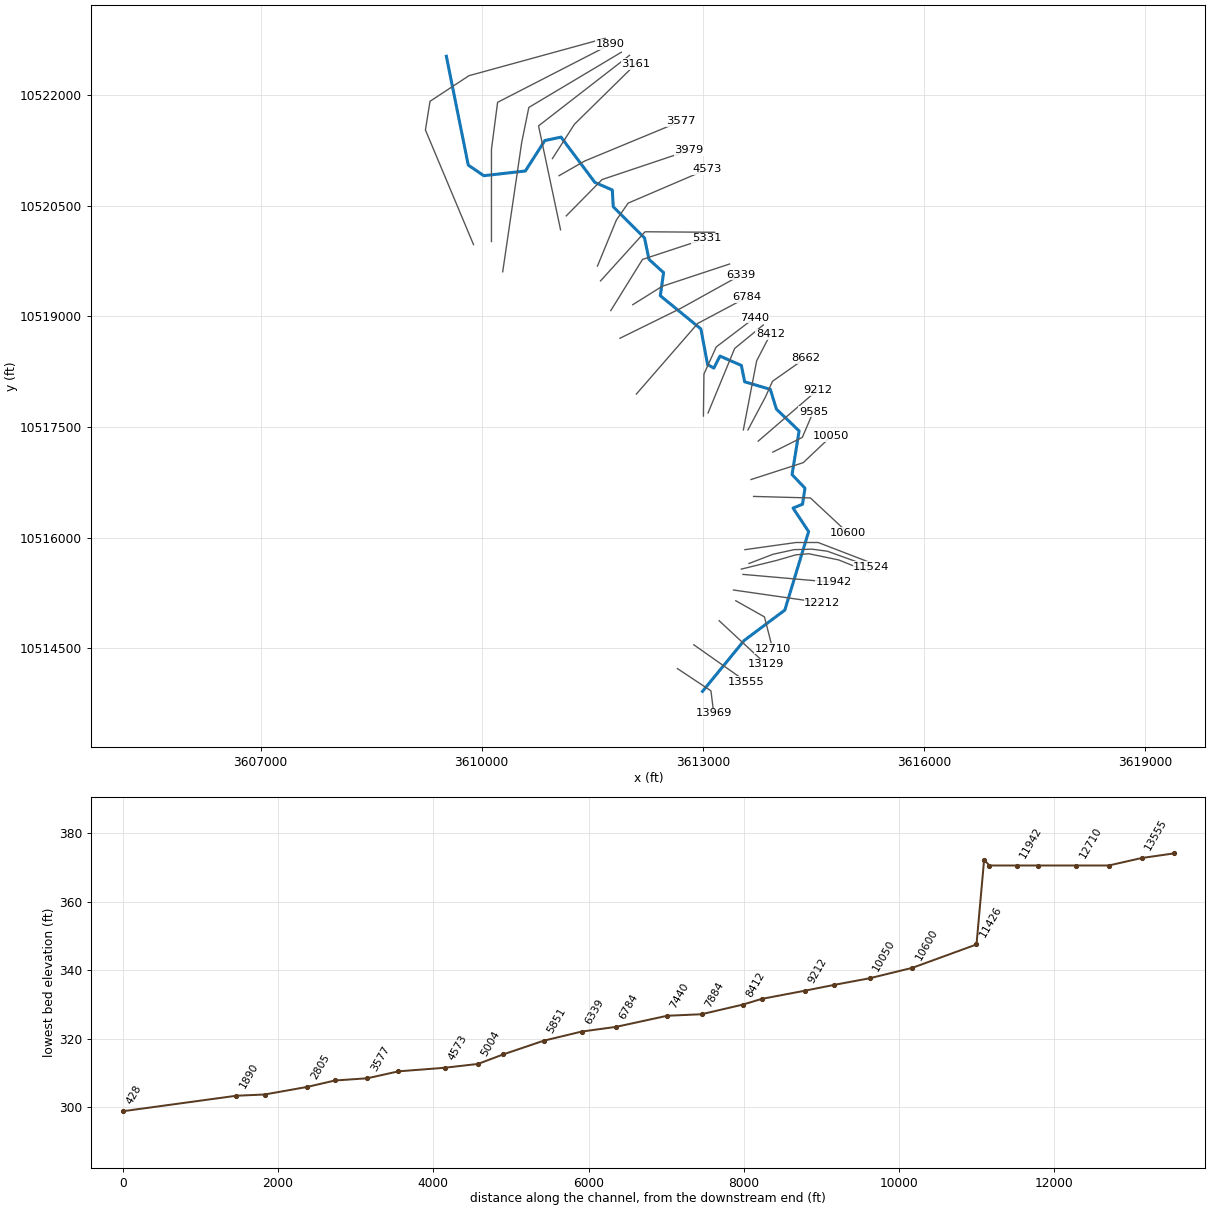
--- CEDAR CREEK 2.prj (project) ---

Proj Title=CEDAR CREEK 2 Base Level Engineering
Current Plan=p01
Default Exp/Contr=0.3,0.1
English Units
Geom File=g01
Flow File=f01
Plan File=p01
BEGIN DESCRIPTION:
CEDAR CREEK 2
END DESCRIPTION:

--- CEDAR CREEK 2.p01 (plan) ---

Plan Title=Multiple Run
Short Identifier=Multiple
Geom File=g01
Flow File=f01
Subcritical Flow
K Sum by GR= 0
Std Step Tol= 0.01
Critical Tol= 0.01
Num of Std Step Trials= 20
Max Error Tol= 0.3
Flow Tol Ratio= 0.001
Split Flow NTrial= 30
Split Flow Tol= 0.02
Split Flow Ratio= 0.02
Log Output Level= 0
Friction Slope Method= 1
Unsteady Friction Slope Method= 2
Unsteady Bridges Friction Slope Method= 1
Parabolic Critical Depth
Global Vel Dist=  1 , 1 , 1
Global Log Level= 0
CheckData=True
Encroach Param= -1, 0, 0, 0
BEGIN DESCRIPTION:
Multiple Run
END DESCRIPTION:

--- CEDAR CREEK 2.f01 (steady flow) ---

Flow Title=Multiple
Number of Profiles=7
Profile Names=10-year,25-year,50-year,1pct_min,100-year,1pct_plu,500-year
River Rch & RM= CEDAR CREEK 2,Reach-1,13969
    1141    1582    1949    1753    2371    3207    3496
River Rch & RM= CEDAR CREEK 2,Reach-1,10600
    1852    2620    3272    2975    4024    5441    6070
Boundary for River Rch & Prof#=CEDAR CREEK 2,Reach-1,1
Up Type=0
Dn Type=3
Dn Slope=0.005
Boundary for River Rch & Prof#=CEDAR CREEK 2,Reach-1,2
Up Type=0
Dn Type=3
Dn Slope=0.005
Boundary for River Rch & Prof#=CEDAR CREEK 2,Reach-1,3
Up Type=0
Dn Type=3
Dn Slope=0.005
Boundary for River Rch & Prof#=CEDAR CREEK 2,Reach-1,4
Up Type=0
Dn Type=3
Dn Slope=0.005
Boundary for River Rch & Prof#=CEDAR CREEK 2,Reach-1,5
Up Type=0
Dn Type=3
Dn Slope=0.005
Boundary for River Rch & Prof#=CEDAR CREEK 2,Reach-1,6
Up Type=0
Dn Type=3
Dn Slope=0.005
Boundary for River Rch & Prof#=CEDAR CREEK 2,Reach-1,7
Up Type=0
Dn Type=3
Dn Slope=0.005

--- CEDAR CREEK 2.g01 (geometry) ---

Geom Title=Existing Conditions

River Reach=CEDAR CREEK 2,Reach-1
Reach XY= 30
      3612995.47     10513914.67      3613561.44     10514605.64
      3614112.00     10515017.00      3614435.25     10516082.00
      3614224.00     10516401.00      3614352.00     10516453.00
      3614385.50     10516671.00      3614210.50     10516855.00
      3614305.75     10517448.00      3613997.50     10517744.00
      3613915.50     10518012.00      3613567.50     10518114.00
      3613522.50     10518336.00      3613232.50     10518463.00
      3613149.50     10518300.00      3613064.50     10518347.00
      3612973.75     10518831.00      3612423.00     10519282.00
      3612467.75     10519595.00      3612269.50     10519775.00
      3612209.25     10520065.00      3611785.00     10520488.00
      3611771.75     10520716.00      3611535.00     10520819.00
      3611076.50     10521433.00      3610856.50     10521387.00
      3610592.75     10520974.00      3610028.75     10520910.00
      3609817.75     10521054.00      3609520.75     10522530.00

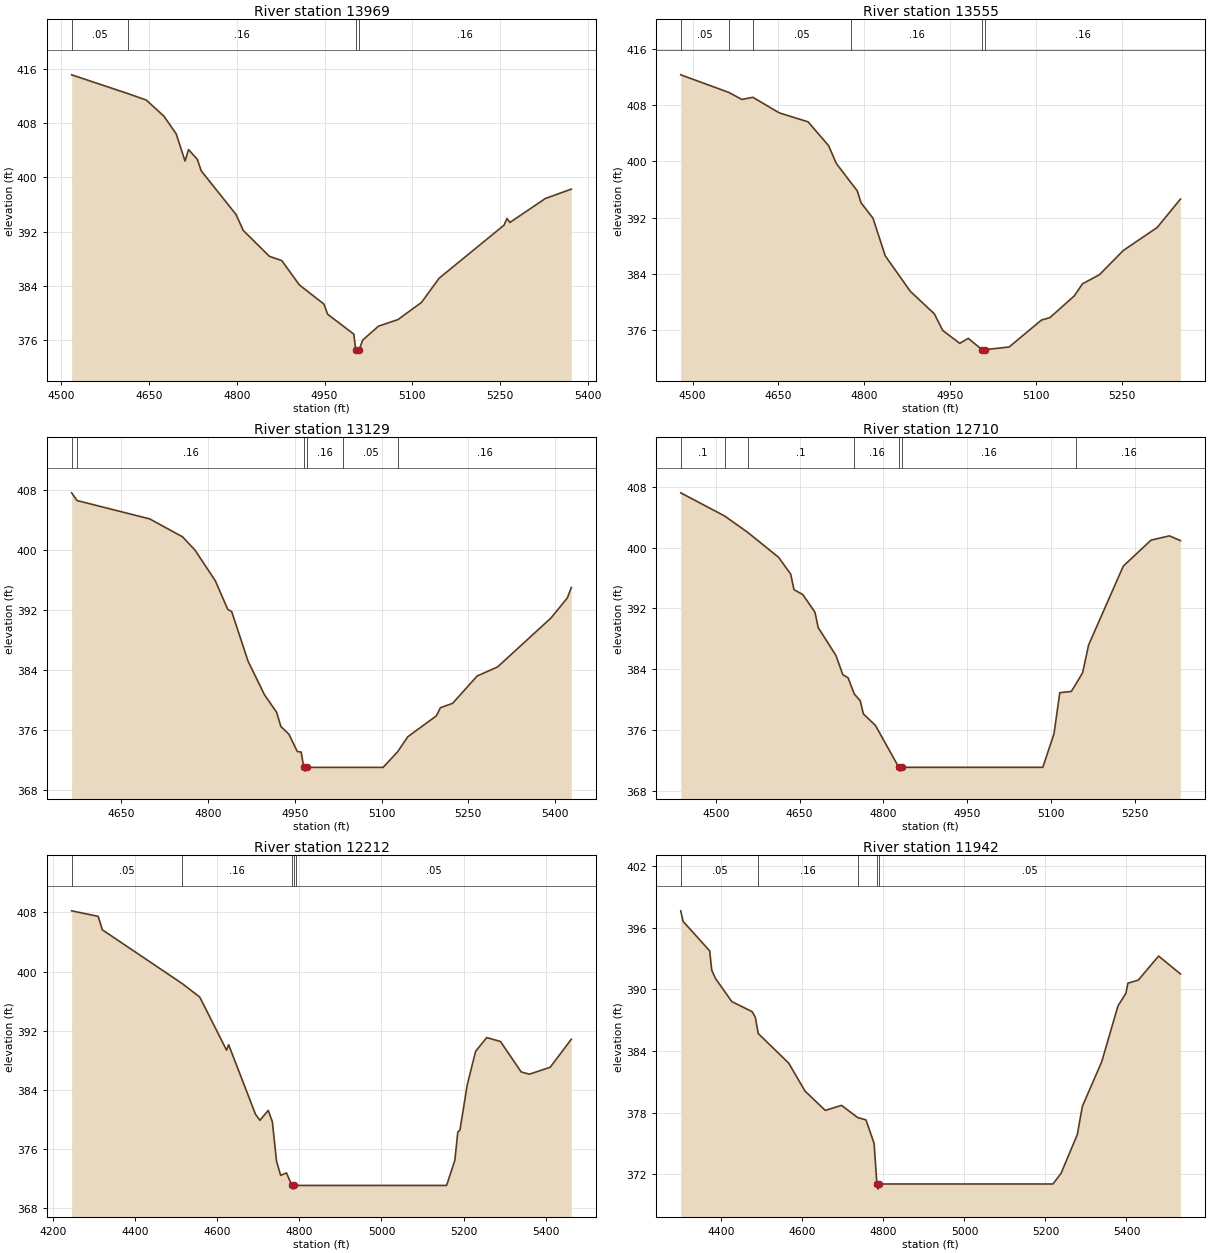
Type RM Length L Ch R = 1,13969,414,414,414
BEGIN DESCRIPTION:
CEDAR CREEK 2 20.0
END DESCRIPTION:
XS GIS Cut Line= 3
      3612655.18     10514223.71      3613110.05     10513921.61
      3613148.25     10513616.04
#Sta/Elev= 30
  4517.8  415.10  4614.5  412.32  4645.4  411.38  4675.5  409.01  4696.5  406.40
  4711.6  402.40  4717.6  404.08  4732.6  402.65  4739.2  400.96  4798.8  394.51
  4811.2  392.16  4855.9  388.35  4876.9  387.73  4907.0  384.14  4949.1  381.31
  4955.3  379.82  5000.2  376.88  5003.2  374.59  5006.0  374.09  5009.2  374.59
  5015.3  376.02  5042.3  378.07  5075.4  379.03  5115.7  381.56  5145.9  385.13
  5256.8  392.95  5261.8  393.94  5266.9  393.35  5327.3  396.87  5371.8  398.26
#Mann=4,-1,0
  4517.8    0.05       0  4614.5    0.16       0  5003.2    0.07       0
  5009.2    0.16       0
Bank Sta=5003.2,5009.2
Exp/Cntr=0.3,0.1

Type RM Length L Ch R = 1,13555,426,426,426
BEGIN DESCRIPTION:
CEDAR CREEK 2 20.1
END DESCRIPTION:
XS GIS Cut Line= 2
      3612877.39     10514546.63      3613591.20     10514044.19
#Sta/Elev= 30
  4479.4  412.28  4563.1  409.79  4586.1  408.78  4605.4  409.09  4651.4  406.88
  4701.9  405.60  4737.7  402.22  4751.1  399.70  4777.1  396.92  4787.8  395.80
  4794.3  394.11  4815.2  391.92  4836.7  386.56  4880.5  381.52  4922.3  378.34
  4937.2  375.96  4966.8  374.14  4981.6  374.85  5005.6  373.25  5008.3  372.75
  5011.6  373.25  5053.0  373.62  5109.6  377.45  5124.4  377.80  5166.9  380.88
  5181.1  382.59  5210.7  383.88  5252.5  387.33  5311.7  390.60  5352.3  394.63
#Mann=6,-1,0
  4479.4    0.05       0  4563.1     0.1       0  4605.4    0.05       0
  4777.1    0.16       0  5005.6    0.07       0  5011.6    0.16       0
Bank Sta=5005.6,5011.6
Exp/Cntr=0.3,0.1

Type RM Length L Ch R = 1,13129,419,419,419
BEGIN DESCRIPTION:
CEDAR CREEK 2 20.2
END DESCRIPTION:
XS GIS Cut Line= 2
      3613221.15     10514873.02      3613854.30     10514284.84
#Sta/Elev= 30
  4564.1  407.67  4573.5  406.64  4699.2  404.19  4755.9  401.80  4777.4  400.04
  4812.6  395.94  4834.1  392.13  4840.9  391.83  4869.3  385.21  4897.6  380.74
  4918.6  378.41  4926.0  376.51  4940.1  375.46  4954.3  373.18  4961.1  373.10
  4965.5  371.06  4968.2  370.56  4971.5  371.06  5033.7  371.06  5102.8  371.06
  5127.9  373.14  5145.4  375.14  5194.7  377.92  5202.0  379.02  5223.0  379.60
  5265.5  383.25  5300.7  384.45  5393.1  390.98  5421.4  393.65  5428.3  395.05
#Mann=6,-1,0
  4564.1     0.1       0  4573.5    0.16       0  4965.5    0.07       0
  4971.5    0.16       0  5033.7    0.05       0  5127.9    0.16       0
Bank Sta=4965.5,4971.5
Exp/Cntr=0.3,0.1

Type RM Length L Ch R = 1,12710,498,498,498
BEGIN DESCRIPTION:
CEDAR CREEK 2 20.3
END DESCRIPTION:
XS GIS Cut Line= 3
      3613446.87     10515143.83      3613835.75     10514925.09
      3613946.86     10514491.06
#Sta/Elev= 30
  4437.3  407.22  4515.8  404.17  4557.0  402.02  4612.5  398.72  4634.1  396.50
  4639.9  394.47  4655.8  393.81  4677.5  391.49  4683.2  389.48  4715.1  385.78
  4727.3  383.27  4736.8  382.85  4747.8  380.72  4758.4  379.84  4764.2  378.09
  4785.8  376.57  4827.5  371.06  4830.3  370.56  4833.5  371.06  5085.2  371.06
  5105.3  375.50  5115.6  380.89  5136.3  381.06  5145.5  382.16  5156.5  383.53
  5167.2  387.18  5229.2  397.56  5278.9  400.99  5311.8  401.55  5331.5  400.93
#Mann=7,-1,0
  4437.3     0.1       0  4515.8    0.16       0  4557.0     0.1       0
  4747.8    0.16       0  4827.5   0.033       0  4833.5    0.16       0
  5145.5    0.16       0
Bank Sta=4827.5,4833.5
Exp/Cntr=0.3,0.1

Type RM Length L Ch R = 1,12212,270,270,270
BEGIN DESCRIPTION:
CEDAR CREEK 2 20.4
END DESCRIPTION:
XS GIS Cut Line= 2
      3613415.59     10515289.67      3614620.44     10515116.06
#Sta/Elev= 30
  4245.2  408.21  4309.9  407.46  4320.0  405.64  4514.3  398.38  4557.3  396.54
  4622.6  389.36  4627.7  390.09  4693.1  380.69  4703.9  379.87  4724.1  381.21
  4734.2  379.67  4744.3  374.34  4754.4  372.42  4768.5  372.76  4781.7  371.06
  4784.5  370.56  4787.7  371.06  4792.8  371.06  5158.6  371.06  5178.8  374.47
  5186.0  378.31  5191.0  378.51  5209.1  384.71  5229.3  389.20  5256.4  391.06
  5289.9  390.53  5340.4  386.41  5360.6  386.11  5411.1  387.05  5462.5  390.84
#Mann=5,-1,0
  4245.2    0.05       0  4514.3    0.16       0  4781.7   0.033       0
  4787.7    0.16       0  4792.8    0.05       0
Bank Sta=4781.7,4787.7
Exp/Cntr=0.3,0.1

Type RM Length L Ch R = 1,11942,349,349,349
BEGIN DESCRIPTION:
CEDAR CREEK 2 20.5
END DESCRIPTION:
XS GIS Cut Line= 2
      3613544.06     10515501.48      3614773.26     10515393.84
#Sta/Elev= 30
  4299.4  397.64  4305.0  396.62  4370.9  393.74  4375.9  391.87  4385.3  391.05
  4425.4  388.81  4475.6  387.83  4483.4  387.30  4490.8  385.70  4566.0  382.82
  4606.1  380.11  4656.3  378.22  4696.5  378.71  4736.4  377.52  4756.7  377.30
  4776.8  375.02  4783.8  371.06  4786.6  370.56  4789.8  371.06  5218.5  371.06
  5238.5  372.10  5278.7  375.87  5291.1  378.61  5338.9  382.95  5379.1  388.39
  5398.6  389.61  5403.7  390.60  5429.3  390.90  5479.4  393.24  5533.3  391.50
#Mann=5,-1,0
  4299.4    0.05       0  4490.8    0.16       0  4736.4    0.05       0
  4783.8   0.033       0  4789.8    0.05       0
Bank Sta=4783.8,4789.8
Exp/Cntr=0.3,0.1

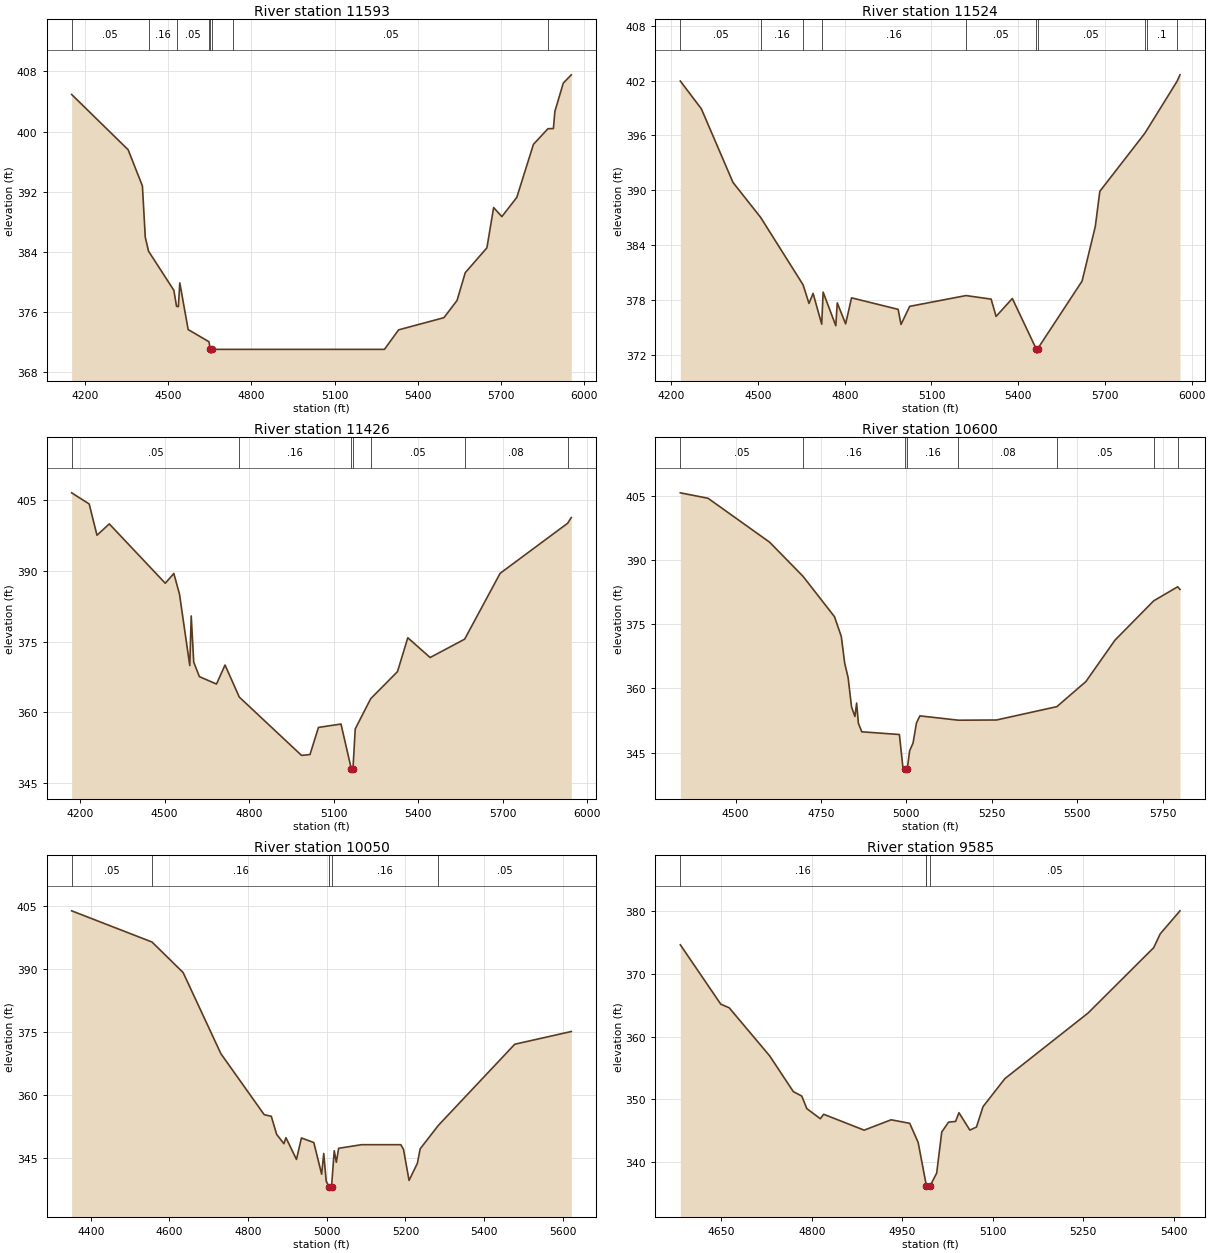
Type RM Length L Ch R = 1,11593,69,69,69
BEGIN DESCRIPTION:
CEDAR CREEK 2 19.0
END DESCRIPTION:
XS GIS Cut Line= 6
      3613521.89     10515573.01      3614001.10     10515691.07
      3614264.99     10515767.46      3614438.60     10515781.35
      3614841.38     10515698.02      3615256.37     10515532.02
#Sta/Elev= 30
  4152.1  404.92  4355.7  397.58  4407.1  392.77  4417.5  385.94  4429.3  384.10
  4520.5  378.90  4530.1  376.78  4536.7  376.74  4541.9  379.89  4572.0  373.69
  4647.1  372.07  4651.5  371.06  4654.2  370.56  4657.5  371.06  4732.6  371.06
  5279.4  371.06  5330.4  373.65  5493.8  375.27  5541.0  377.55  5570.6  381.24
  5648.7  384.55  5672.9  389.90  5702.6  388.69  5756.4  391.25  5816.3  398.29
  5868.6  400.37  5888.3  400.40  5893.7  402.68  5924.0  406.43  5952.8  407.53
#Mann=8,-1,0
  4152.1    0.05       0  4429.3    0.16       0  4530.1    0.05       0
  4647.1    0.16       0  4651.5   0.033       0  4657.5    0.16       0
  4732.6    0.05       0  5868.6     0.1       0
Bank Sta=4651.5,4657.5
Exp/Cntr=0.3,0.1

Type RM Length L Ch R = 1,11524,98,98,98
BEGIN DESCRIPTION:
Mapping XS e05e3d9b
END DESCRIPTION:
XS GIS Cut Line= 6
      3613626.11     10515649.41      3613952.49     10515774.41
      3614237.21     10515836.91      3614480.27     10515843.85
      3614688.60     10515816.07      3615285.20     10515601.02
#Sta/Elev= 30
  4231.3  401.95  4304.0  398.91  4413.5  390.85  4509.2  387.02  4655.9  379.65
  4676.4  377.61  4690.5  378.71  4720.4  375.34  4725.3  378.85  4769.1  375.17
  4774.2  377.67  4803.1  375.37  4823.6  378.22  4984.7  376.96  4994.7  375.31
  5024.8  377.29  5219.6  378.47  5306.5  378.08  5323.6  376.19  5379.8  378.15
  5461.9  372.67  5464.6  372.17  5467.9  372.67  5621.1  380.05  5666.9  386.04
  5682.5  389.88  5837.4  396.20  5846.6  396.66  5949.5  401.91  5959.8  402.63
#Mann=10,-1,0
  4231.3    0.05       0  4509.2    0.16       0  4655.9    0.05       0
  4720.4    0.16       0  5219.6    0.05       0  5461.9    0.07       0
  5467.9    0.05       0  5837.4    0.08       0  5846.6     0.1       0
  5949.5    0.05       0
Bank Sta=5461.9,5467.9
Exp/Cntr=0.3,0.1

Type RM Length L Ch R = 1,11426,826,826,826
BEGIN DESCRIPTION:
CEDAR CREEK 2 18.0
END DESCRIPTION:
XS GIS Cut Line= 4
      3613570.55     10515836.91      3614264.99     10515934.13
      3614563.60     10515934.13      3615285.24     10515656.58
#Sta/Elev= 30
  4169.9  406.62  4232.1  404.26  4259.8  397.62  4303.5  400.02  4502.2  387.42
  4532.5  389.50  4552.7  385.08  4589.1  369.94  4594.2  380.48  4603.1  370.67
  4623.3  367.59  4683.9  366.02  4714.2  370.06  4764.8  363.25  4985.7  350.87
  5015.7  351.05  5045.7  356.81  5125.7  357.53  5162.2  348.03  5165.0  347.53
  5168.2  348.03  5176.2  356.49  5231.1  362.91  5326.2  368.66  5362.7  375.85
  5442.0  371.65  5564.5  375.55  5690.4  389.53  5930.0  400.16  5942.9  401.37
#Mann=7,-1,0
  4169.9    0.05       0  4764.8    0.16       0  5162.2    0.07       0
  5168.2    0.16       0  5231.1    0.05       0  5564.5    0.08       0
  5930.0    0.05       0
Bank Sta=5162.2,5168.2
Exp/Cntr=0.3,0.1

Type RM Length L Ch R = 1,10600,550,550,550
BEGIN DESCRIPTION:
CEDAR CREEK 2 17.0
END DESCRIPTION:
XS GIS Cut Line= 3
      3613688.58     10516559.13      3614459.44     10516538.29
      3614965.47     10516066.92
#Sta/Elev= 30
  4338.4  405.64  4419.5  404.37  4599.5  394.14  4697.5  386.17  4789.6  376.75
  4809.6  372.13  4819.6  365.86  4829.6  362.51  4839.6  355.68  4849.5  353.46
  4854.5  356.59  4859.6  351.88  4869.6  349.89  4979.7  349.25  4989.7  341.77
  4996.7  341.21  4999.4  340.71  5002.7  341.21  5009.7  345.46  5019.7  347.28
  5029.7  351.97  5039.7  353.60  5152.7  352.59  5263.9  352.64  5440.6  355.75
  5525.7  361.61  5610.8  371.27  5724.1  380.44  5794.4  383.72  5801.1  383.10
#Mann=8,-1,0
  4338.4    0.05       0  4697.5    0.16       0  4996.7    0.07       0
  5002.7    0.16       0  5152.7    0.08       0  5440.6    0.05       0
  5724.1     0.1       0  5794.4    0.16       0
Bank Sta=4996.7,5002.7
Exp/Cntr=0.3,0.1

Type RM Length L Ch R = 1,10050,465,465,465
BEGIN DESCRIPTION:
CEDAR CREEK 2 16.0
END DESCRIPTION:
XS GIS Cut Line= 3
      3613653.90     10516788.30      3614362.21     10517017.46
      3614744.17     10517378.58
#Sta/Elev= 30
  4351.6  403.76  4555.9  396.35  4635.0  389.10  4731.0  369.83  4841.1  355.35
  4859.1  354.97  4872.6  350.70  4891.1  348.45  4896.3  349.89  4923.1  344.73
  4935.7  349.82  4967.2  348.73  4987.1  341.21  4992.4  346.13  4998.7  339.55
  5006.2  338.17  5009.0  337.67  5012.2  338.17  5019.1  346.79  5024.4  344.05
  5030.3  347.37  5088.4  348.22  5188.3  348.22  5195.2  347.10  5209.3  339.74
  5230.4  343.79  5237.6  347.24  5283.3  352.76  5478.0  372.08  5621.7  375.10
#Mann=5,-1,0
  4351.6    0.05       0  4555.9    0.16       0  5006.2    0.07       0
  5012.2    0.16       0  5283.3    0.05       0
Bank Sta=5006.2,5012.2
Exp/Cntr=0.3,0.1

Type RM Length L Ch R = 1,9585,373,373,373
BEGIN DESCRIPTION:
CEDAR CREEK 2 15.0
END DESCRIPTION:
XS GIS Cut Line= 3
      3613949.64     10517160.21      3614349.61     10517360.19
      3614499.62     10517710.22
#Sta/Elev= 30
  4582.3  374.60  4649.3  365.15  4663.3  364.57  4730.4  356.91  4769.5  351.23
  4783.5  350.52  4791.9  348.52  4814.3  346.91  4819.8  347.62  4886.9  345.09
  4931.6  346.74  4962.4  346.18  4976.4  343.14  4989.8  336.36  4990.1  336.20
  4992.9  335.70  4996.1  336.20  5007.1  338.25  5015.5  344.79  5026.7  346.36
  5038.5  346.48  5044.0  347.87  5062.1  345.10  5073.0  345.58  5083.9  348.83
  5120.1  353.29  5257.9  363.73  5366.7  374.14  5377.6  376.35  5410.3  380.01
#Mann=4,-1,0
  4582.3    0.16       0  4989.8    0.05       0  4990.1    0.03       0
  4996.1    0.05       0
Bank Sta=4990.1,4996.1
Exp/Cntr=0.3,0.1

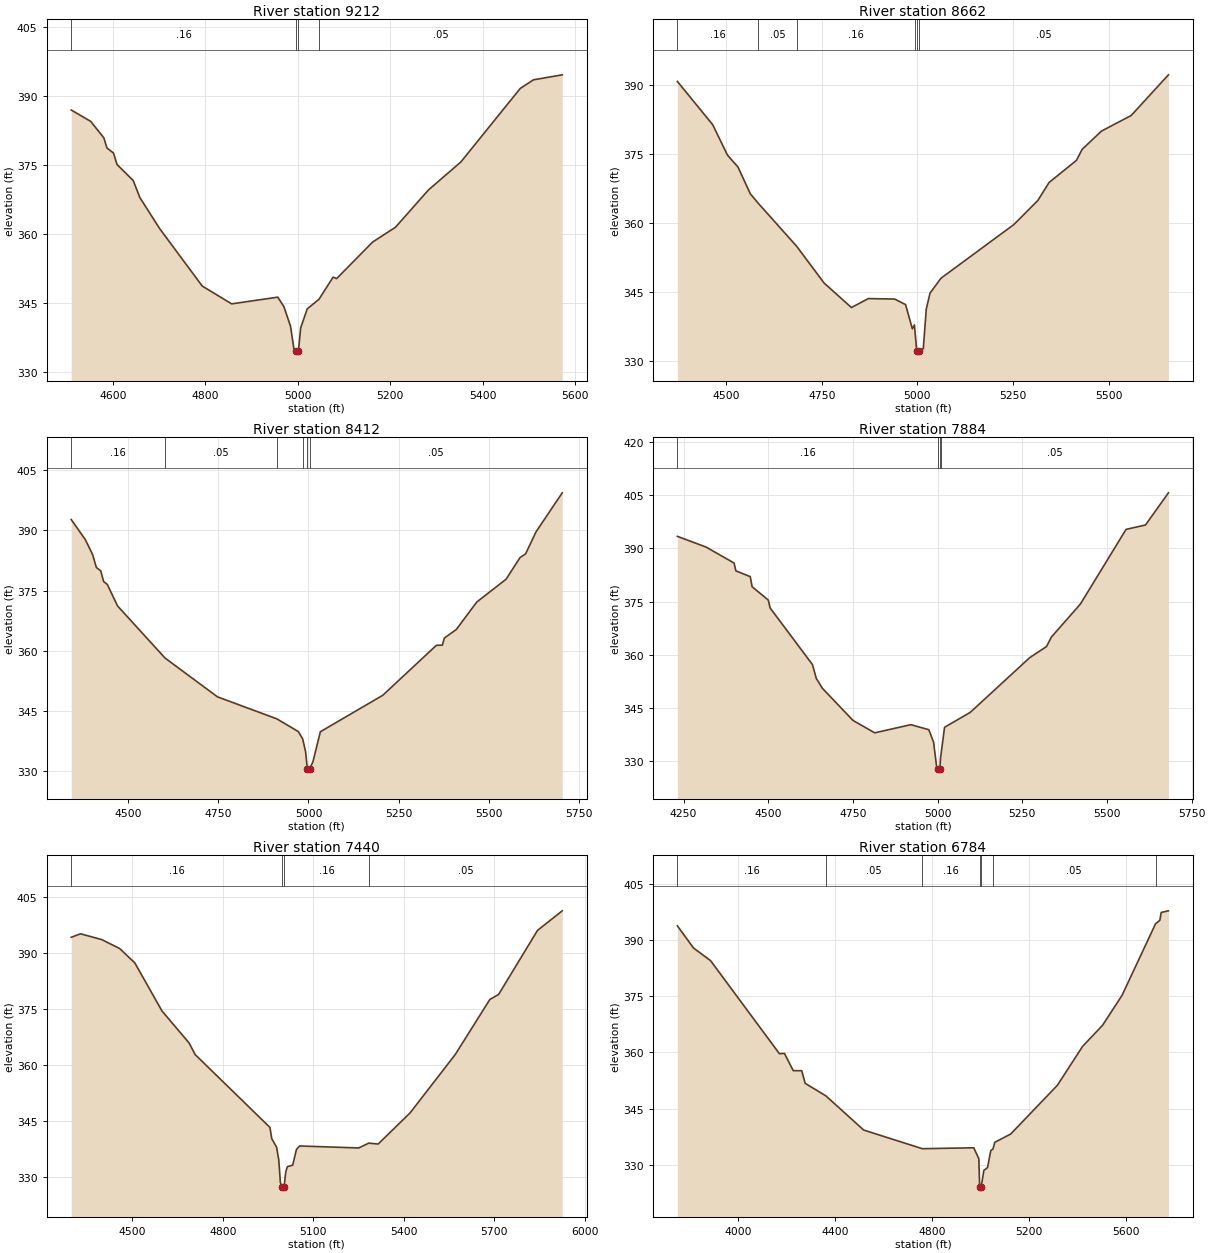
Type RM Length L Ch R = 1,9212,550,550,550
BEGIN DESCRIPTION:
CEDAR CREEK 2 14.0
END DESCRIPTION:
XS GIS Cut Line= 2
      3613751.09     10517309.12      3614555.61     10518002.67
#Sta/Elev= 30
  4510.0  386.93  4552.1  384.46  4580.6  380.87  4587.3  378.66  4601.5  377.56
  4609.1  375.06  4644.2  371.57  4658.5  367.87  4701.3  361.12  4793.4  348.62
  4857.1  344.74  4956.9  346.20  4970.1  344.13  4984.4  339.88  4992.0  334.77
  4995.6  334.52  4998.4  334.02  5001.6  334.52  5006.3  339.49  5020.5  343.64
  5046.0  345.74  5076.5  350.56  5084.2  350.24  5162.1  358.20  5211.4  361.41
  5282.7  369.52  5353.0  375.63  5481.3  391.61  5509.8  393.49  5572.2  394.58
#Mann=4,-1,0
  4510.0    0.16       0  4995.6    0.07       0  5001.6    0.16       0
  5046.0    0.05       0
Bank Sta=4995.6,5001.6
Exp/Cntr=0.3,0.1

Type RM Length L Ch R = 1,8662,250,250,250
BEGIN DESCRIPTION:
CEDAR CREEK 2 13.0
END DESCRIPTION:
XS GIS Cut Line= 4
      3613612.20     10517461.87      3613848.33     10517906.35
      3613945.55     10518121.63      3614389.97     10518434.11
#Sta/Elev= 30
  4372.9  390.79  4465.3  381.36  4503.6  374.77  4531.2  372.16  4563.5  366.33
  4584.2  364.27  4684.7  354.90  4756.0  346.93  4827.6  341.58  4871.6  343.53
  4940.4  343.43  4969.0  342.23  4986.7  336.95  4992.1  337.80  4993.6  336.39
  4998.1  332.16  5000.9  331.66  5004.1  332.16  5015.3  332.62  5023.1  341.25
  5032.9  344.72  5061.5  347.96  5251.7  359.63  5314.5  364.88  5344.1  368.81
  5415.5  373.62  5430.3  376.02  5480.9  379.99  5558.4  383.38  5655.7  392.23
#Mann=6,-1,0
  4372.9    0.16       0  4584.2    0.05       0  4684.7    0.16       0
  4993.6    0.05       0  4998.1    0.03       0  5004.1    0.05       0
Bank Sta=4998.1,5004.1
Exp/Cntr=0.3,0.1

Type RM Length L Ch R = 1,8412,528,528,528
BEGIN DESCRIPTION:
CEDAR CREEK 2 12.0
END DESCRIPTION:
XS GIS Cut Line= 3
      3613549.71     10517461.88      3613730.27     10518399.41
      3613917.75     10518760.48
#Sta/Elev= 30
  4342.1  392.70  4381.1  387.71  4401.5  383.96  4411.7  380.76  4423.9  379.91
  4432.0  377.24  4442.2  376.51  4470.7  371.14  4602.3  358.16  4747.7  348.48
  4912.1  343.00  4971.8  339.83  4983.9  338.00  4992.1  334.77  4996.9  330.46
  4999.6  329.96  5002.9  330.46  5012.5  332.32  5032.9  339.78  5206.0  348.87
  5354.7  361.34  5371.2  361.37  5376.8  363.15  5409.8  365.27  5466.7  372.13
  5548.1  377.83  5586.7  383.22  5602.0  384.13  5631.0  389.63  5703.7  399.36
#Mann=6,-1,0
  4342.1    0.16       0  4602.3    0.05       0  4912.1    0.16       0
  4983.9    0.05       0  4996.9    0.03       0  5002.9    0.05       0
Bank Sta=4996.9,5002.9
Exp/Cntr=0.3,0.1

Type RM Length L Ch R = 1,7884,444,444,444
BEGIN DESCRIPTION:
CEDAR CREEK 2 11.0
END DESCRIPTION:
XS GIS Cut Line= 3
      3613070.56     10517691.10      3613431.66     10518566.07
      3613820.38     10518885.38
#Sta/Elev= 30
  4231.8  393.39  4316.5  390.36  4399.1  385.86  4404.5  383.64  4446.9  382.02
  4452.4  379.18  4500.2  375.40  4505.6  373.18  4630.6  357.21  4641.9  353.30
  4660.0  350.52  4750.1  341.48  4814.3  337.97  4920.9  340.27  4974.1  338.85
  4988.1  335.35  4998.0  327.70  5000.5  327.67  5003.2  327.17  5006.5  327.67
  5008.7  330.91  5020.5  339.53  5096.3  343.74  5272.1  359.19  5321.6  362.31
  5336.0  365.00  5421.6  374.30  5556.3  395.35  5613.7  396.59  5681.4  405.66
#Mann=4,-1,0
  4231.8    0.16       0  5000.5    0.07       0  5006.5    0.16       0
  5008.7    0.05       0
Bank Sta=5000.5,5006.5
Exp/Cntr=0.3,0.1

Type RM Length L Ch R = 1,7440,656,656,656
BEGIN DESCRIPTION:
CEDAR CREEK 2 10.0
END DESCRIPTION:
XS GIS Cut Line= 4
      3613008.05     10517649.45      3613014.99     10518218.85
      3613181.66     10518586.91      3613702.53     10518982.76
#Sta/Elev= 30
  4297.2  394.12  4327.9  395.06  4397.9  393.53  4458.0  391.11  4508.0  387.28
  4598.0  374.42  4688.0  365.84  4708.0  362.74  4955.9  343.24  4962.1  340.20
  4977.9  337.97  4985.2  334.57  4990.6  328.45  4996.8  327.22  4999.6  326.72
  5002.8  327.22  5008.3  331.28  5013.7  332.73  5031.3  333.13  5043.8  337.34
  5054.4  338.27  5250.2  337.74  5283.6  339.03  5314.7  338.79  5420.8  347.15
  5570.6  362.79  5684.9  377.49  5714.0  378.83  5842.9  395.97  5924.9  401.21
#Mann=4,-1,0
  4297.2    0.16       0  4996.8    0.07       0  5002.8    0.16       0
  5283.6    0.05       0
Bank Sta=4996.8,5002.8
Exp/Cntr=0.3,0.1

Type RM Length L Ch R = 1,6784,445,445,445
BEGIN DESCRIPTION:
CEDAR CREEK 2 9.0
END DESCRIPTION:
XS GIS Cut Line= 3
      3612098.32     10517948.01      3612931.66     10518906.35
      3613598.33     10519260.52
#Sta/Elev= 30
  3750.2  393.81  3816.7  387.89  3887.0  384.52  4170.9  359.66  4191.8  359.73
  4227.9  355.14  4263.0  355.11  4277.2  351.74  4362.5  348.40  4518.4  339.27
  4760.1  334.29  4972.3  334.53  4993.2  331.63  4996.8  323.99  4999.6  323.49
  5002.8  323.99  5014.0  328.50  5029.2  329.24  5042.6  333.82  5051.4  334.16
  5058.9  335.98  5124.9  338.22  5317.0  351.21  5421.3  361.63  5503.5  367.25
  5584.0  375.26  5721.9  394.35  5739.7  395.30  5745.3  397.39  5775.1  397.82
#Mann=7,-1,0
  3750.2    0.16       0  4362.5    0.05       0  4760.1    0.16       0
  4996.8    0.07       0  5002.8    0.16       0  5051.4    0.05       0
  5721.9    0.08       0
Bank Sta=4996.8,5002.8
Exp/Cntr=0.3,0.1

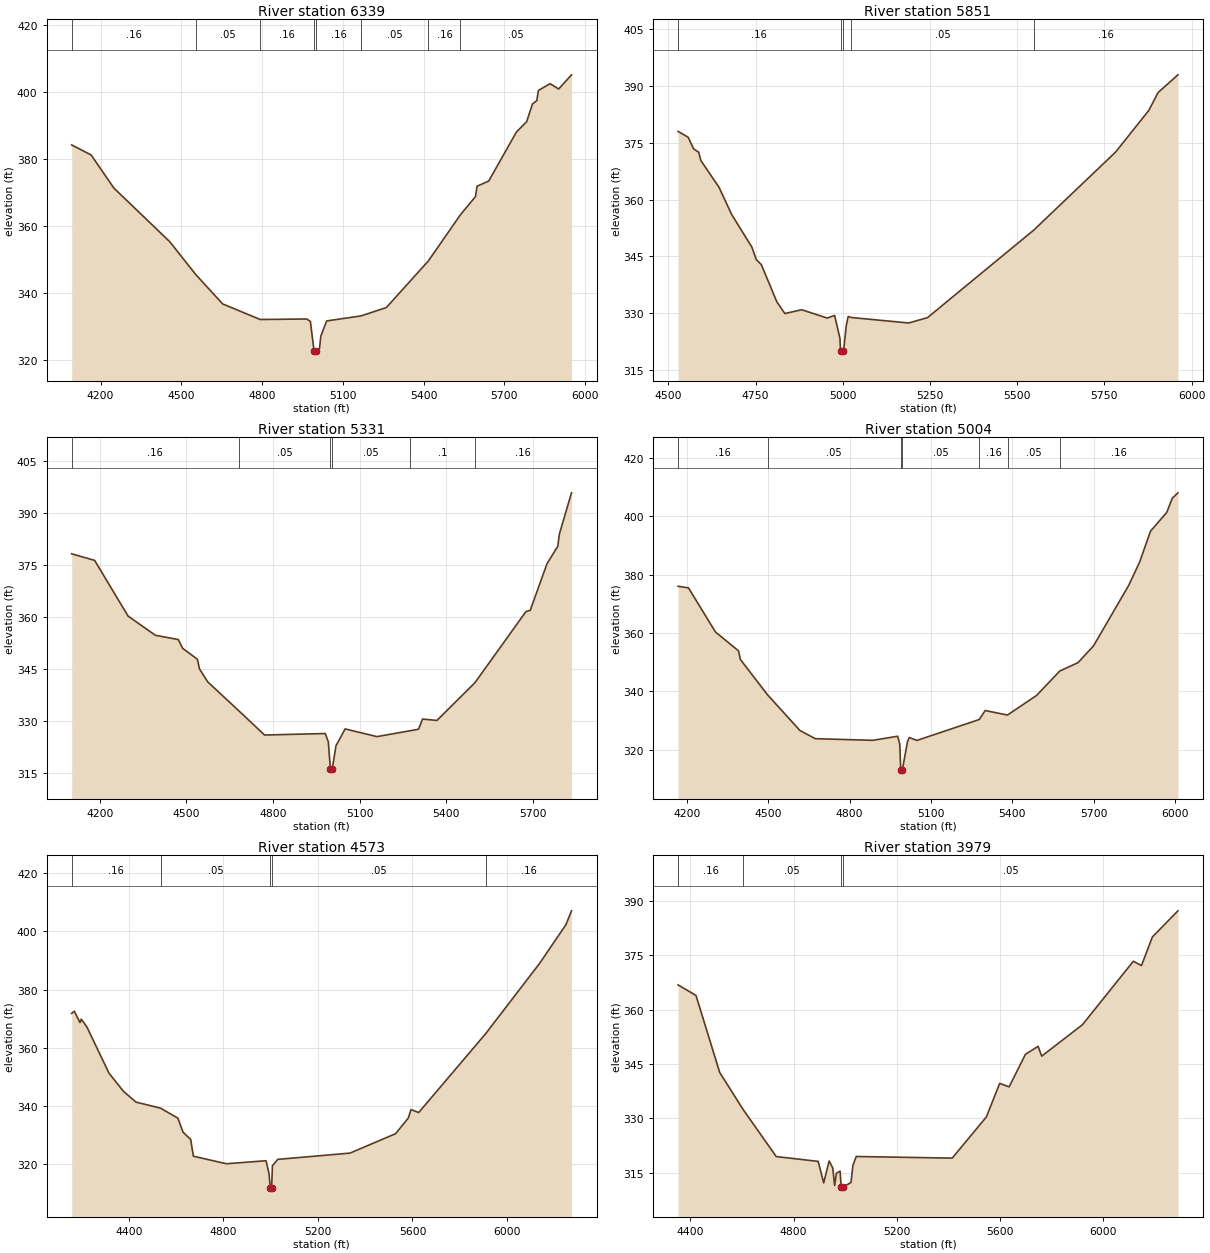
Type RM Length L Ch R = 1,6339,488,488,488
BEGIN DESCRIPTION:
CEDAR CREEK 2 8.0
END DESCRIPTION:
XS GIS Cut Line= 3
      3611876.13     10518704.98      3612699.61     10519110.19
      3613521.14     10519565.63
#Sta/Elev= 30
  4092.4  384.14  4164.8  381.15  4249.1  371.30  4456.9  355.30  4553.7  345.50
  4653.5  336.76  4792.9  332.13  4965.6  332.28  4979.3  331.58  4993.2  322.61
  4995.9  322.11  4999.2  322.61  5013.0  323.40  5018.2  327.21  5039.9  331.70
  5167.7  333.20  5261.7  335.70  5417.8  349.59  5536.8  363.33  5592.8  368.75
  5598.5  371.83  5642.0  373.38  5745.0  388.00  5782.8  391.06  5804.5  396.34
  5820.6  397.34  5826.3  400.35  5869.8  402.39  5901.8  400.81  5949.5  405.02
#Mann=8,-1,0
  4092.4    0.16       0  4553.7    0.05       0  4792.9    0.16       0
  4993.2    0.07       0  4999.2    0.16       0  5167.7    0.05       0
  5417.8    0.16       0  5536.8    0.05       0
Bank Sta=4993.2,4999.2
Exp/Cntr=0.3,0.1

Type RM Length L Ch R = 1,5851,520,520,520
BEGIN DESCRIPTION:
CEDAR CREEK 2 7.0
END DESCRIPTION:
XS GIS Cut Line= 3
      3612049.62     10519160.19      3612449.61     10519410.19
      3613362.24     10519711.91
#Sta/Elev= 30
  4527.9  378.02  4556.8  376.46  4572.1  373.43  4586.9  372.51  4593.3  370.30
  4645.2  363.26  4681.2  356.12  4739.6  347.42  4751.9  344.18  4766.7  342.80
  4810.9  333.03  4833.9  329.90  4882.3  330.91  4955.4  328.71  4976.6  329.41
  4991.9  323.37  4993.6  319.95  4996.4  319.45  4999.6  319.95  5002.2  319.95
  5010.1  326.80  5015.5  329.12  5024.9  328.85  5189.2  327.41  5242.8  328.82
  5547.2  351.92  5782.2  372.56  5877.4  383.57  5903.8  388.26  5960.8  392.95
#Mann=5,-1,0
  4527.9    0.16       0  4993.6    0.07       0  4999.6    0.16       0
  5024.9    0.05       0  5547.2    0.16       0
Bank Sta=4993.6,4999.6
Exp/Cntr=0.3,0.1

Type RM Length L Ch R = 1,5331,327,327,327
BEGIN DESCRIPTION:
CEDAR CREEK 2 6.0
END DESCRIPTION:
XS GIS Cut Line= 3
      3611751.12     10519079.99      3612181.66     10519774.41
      3613049.57     10520060.18
#Sta/Elev= 30
  4102.9  378.31  4182.5  376.41  4298.3  360.30  4392.8  354.75  4471.9  353.52
  4487.3  350.97  4538.5  347.81  4545.2  345.08  4573.8  341.30  4682.2  332.88
  4770.8  325.91  4981.0  326.34  4991.6  323.96  4999.0  315.97  5001.8  315.47
  5005.0  315.97  5018.1  322.79  5049.9  327.68  5159.9  325.45  5273.1  327.12
  5304.1  327.60  5317.9  330.53  5367.7  330.12  5499.5  341.06  5675.8  361.59
  5690.7  361.96  5749.0  375.48  5786.1  380.47  5791.6  383.99  5833.7  395.94
#Mann=6,-1,0
  4102.9    0.16       0  4682.2    0.05       0  4999.0    0.03       0
  5005.0    0.05       0  5273.1     0.1       0  5499.5    0.16       0
Bank Sta=4999,5005
Exp/Cntr=0.3,0.1

Type RM Length L Ch R = 1,5004,431,431,431
BEGIN DESCRIPTION:
CEDAR CREEK 2 5.0
END DESCRIPTION:
XS GIS Cut Line= 3
      3611612.24     10519482.76      3612216.38     10520149.41
      3613160.79     10520142.46
#Sta/Elev= 30
  4167.3  376.08  4205.8  375.50  4305.2  360.39  4390.4  353.90  4397.1  350.96
  4497.3  338.85  4616.8  326.61  4673.5  323.80  4885.7  323.23  4977.6  324.64
  4985.1  321.93  4988.8  313.17  4991.6  312.67  4994.8  313.17  5013.5  322.73
  5020.2  324.20  5048.6  323.20  5278.6  330.38  5300.2  333.45  5382.7  331.91
  5490.2  338.65  5575.3  346.99  5642.9  349.88  5700.2  355.65  5830.2  376.45
  5870.2  384.39  5910.2  394.96  5970.2  401.41  5990.2  406.20  6011.4  408.11
#Mann=7,-1,0
  4167.3    0.16       0  4497.3    0.05       0  4988.8    0.03       0
  4994.8    0.05       0  5278.6    0.16       0  5382.7    0.05       0
  5575.3    0.16       0
Bank Sta=4988.8,4994.8
Exp/Cntr=0.3,0.1

Type RM Length L Ch R = 1,4573,594,594,594
BEGIN DESCRIPTION:
CEDAR CREEK 2 4.0
END DESCRIPTION:
XS GIS Cut Line= 4
      3611570.55     10519684.14      3611827.49     10520309.13
      3611987.21     10520538.29      3613054.00     10520995.49
#Sta/Elev= 30
  4157.6  371.81  4168.9  372.56  4192.9  368.65  4198.3  369.82  4222.2  367.15
  4315.5  351.33  4376.8  345.09  4430.1  341.38  4533.8  339.32  4607.4  335.88
  4629.1  331.08  4661.5  328.56  4672.8  322.84  4812.9  320.25  4980.3  321.29
  4993.1  316.85  4998.2  312.05  5000.9  311.55  5004.2  312.05  5007.3  319.55
  5029.7  321.75  5335.8  323.90  5528.7  330.56  5582.4  335.91  5594.0  338.83
  5626.6  337.82  5910.4  364.90  6138.0  388.93  6249.7  402.24  6273.3  406.98
#Mann=5,-1,0
  4157.6    0.16       0  4533.8    0.05       0  4998.2    0.03       0
  5004.2    0.05       0  5910.4    0.16       0
Bank Sta=4998.2,5004.2
Exp/Cntr=0.3,0.1

Type RM Length L Ch R = 1,3979,402,402,402
BEGIN DESCRIPTION:
CEDAR CREEK 2 3.0
END DESCRIPTION:
XS GIS Cut Line= 3
      3611146.96     10520364.71      3611633.05     10520857.74
      3612813.59     10521253.57
#Sta/Elev= 30
  4352.2  366.83  4421.6  363.93  4513.6  342.68  4604.6  332.44  4732.7  319.49
  4895.3  318.16  4916.6  312.24  4937.8  318.28  4951.9  316.30  4959.0  311.51
  4966.0  314.90  4980.2  315.47  4984.3  311.01  4987.1  310.51  4990.3  311.01
  5022.6  312.36  5029.7  317.00  5042.8  319.51  5414.7  319.06  5547.2  330.42
  5598.7  339.66  5635.5  338.72  5698.6  347.70  5747.6  349.88  5761.7  347.19
  5919.5  355.84  6116.7  373.35  6148.4  372.17  6190.6  380.05  6289.7  387.26
#Mann=4,-1,0
  4352.2    0.16       0  4604.6    0.05       0  4984.3    0.03       0
  4990.3    0.05       0
Bank Sta=4984.3,4990.3
Exp/Cntr=0.3,0.1

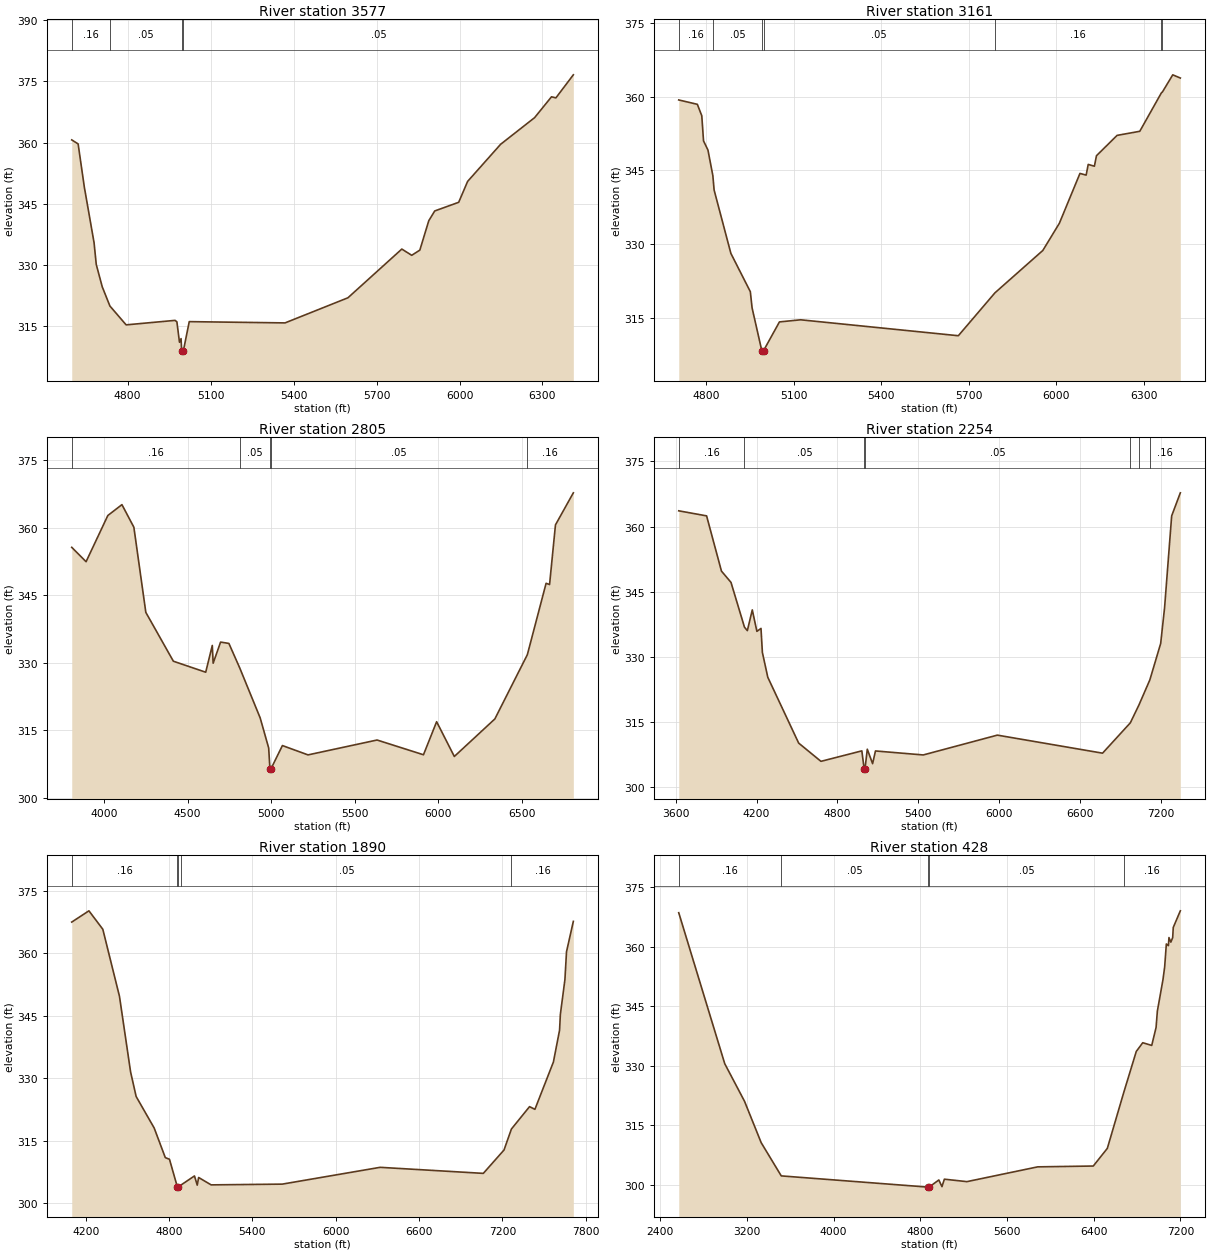
Type RM Length L Ch R = 1,3577,416,416,416
BEGIN DESCRIPTION:
CEDAR CREEK 2 2.0
END DESCRIPTION:
XS GIS Cut Line= 3
      3611049.58     10520910.17      3611399.61     10521110.19
      3612702.49     10521649.40
#Sta/Elev= 30
  4598.3  360.69  4621.4  359.70  4643.7  349.17  4679.0  335.52  4686.9  330.19
  4708.5  324.73  4736.3  320.01  4794.9  315.40  4971.9  316.50  4978.4  316.14
  4987.8  311.14  4993.5  312.03  4995.6  308.98  4998.3  308.48  5001.6  308.98
  5023.1  316.19  5369.4  315.88  5596.7  322.03  5791.5  333.96  5827.3  332.43
  5856.6  333.70  5888.9  340.89  5910.5  343.29  5997.1  345.41  6029.3  350.52
  6148.6  359.61  6271.4  366.13  6332.6  371.24  6348.5  370.98  6411.5  376.62
#Mann=4,-1,0
  4598.3    0.16       0  4736.3    0.05       0  4995.6    0.03       0
  5001.6    0.05       0
Bank Sta=4995.6,5001.6
Exp/Cntr=0.3,0.1

Type RM Length L Ch R = 1,3161,356,356,356
BEGIN DESCRIPTION:
Mapping XS 1c418a78
END DESCRIPTION:
XS GIS Cut Line= 3
      3610959.46     10521142.50      3611258.05     10521607.74
      3612090.35     10522426.17
#Sta/Elev= 30
  4705.1  359.35  4768.9  358.46  4784.1  356.14  4790.1  351.02  4805.3  349.15
  4822.1  343.95  4826.4  341.02  4883.9  328.13  4950.6  320.34  4956.6  317.05
  4989.9  308.34  4992.7  307.84  4995.9  308.34  5050.4  314.19  5123.1  314.62
  5663.9  311.38  5789.5  320.11  5953.7  328.73  6010.3  334.25  6081.0  344.40
  6102.2  344.06  6109.3  346.23  6130.5  345.87  6137.6  348.00  6208.3  352.14
  6286.1  352.97  6360.2  360.79  6364.0  360.99  6399.2  364.46  6425.2  363.81
#Mann=7,-1,0
  4705.1    0.16       0  4822.1    0.05       0  4989.9    0.03       0
  4995.9    0.05       0  5789.5    0.16       0  6360.2    0.05       0
  6364.0    0.16       0
Bank Sta=4989.9,4995.9
Exp/Cntr=0.3,0.1

Type RM Length L Ch R = 1,2805,551,551,551
BEGIN DESCRIPTION:
Mapping XS 7da007fe
END DESCRIPTION:
XS GIS Cut Line= 3
      3611069.93     10520176.24      3610771.32     10521585.94
      3612006.04     10522543.19
#Sta/Elev= 30
  3806.8  355.61  3892.6  352.42  4022.9  362.67  4107.3  365.08  4178.8  360.07
  4250.4  341.18  4415.3  330.35  4608.9  327.91  4648.4  333.85  4653.5  329.91
  4698.0  334.59  4747.7  334.30  4813.2  328.81  4935.2  317.76  4985.9  311.11
  4993.6  306.47  4996.3  305.97  4999.6  306.47  5068.1  311.64  5221.5  309.57
  5634.9  312.87  5912.8  309.60  5991.6  316.93  6097.5  309.22  6340.1  317.54
  6534.8  331.80  6647.0  347.63  6667.8  347.36  6703.1  360.59  6810.1  367.70
#Mann=5,-1,0
  3806.8    0.16       0  4813.2    0.05       0  4993.6    0.03       0
  4999.6    0.05       0  6534.8    0.16       0
Bank Sta=4993.6,4999.6
Exp/Cntr=0.3,0.1

Type RM Length L Ch R = 1,2254,364,364,364
BEGIN DESCRIPTION:
Mapping XS d910f5fb
END DESCRIPTION:
XS GIS Cut Line= 4
      3610285.21     10519606.75      3610542.15     10521356.77
      3610639.38     10521835.94      3611894.85     10522585.06
#Sta/Elev= 30
  3623.1  363.63  3829.6  362.47  3939.9  349.76  4010.6  347.17  4110.5  336.87
  4131.9  336.07  4168.5  340.84  4202.7  335.90  4233.0  336.58  4243.4  331.05
  4283.5  325.34  4512.4  310.20  4677.7  306.00  4980.9  308.41  4998.2  304.25
  5000.9  303.75  5004.2  304.25  5021.4  308.79  5060.7  305.47  5082.0  308.39
  5436.2  307.47  5985.9  312.03  6766.1  307.88  6971.9  314.86  7036.1  318.98
  7116.7  324.74  7197.0  333.11  7226.0  341.34  7278.5  362.46  7342.8  367.77
#Mann=7,-1,0
  3623.1    0.16       0  4110.5    0.05       0  4998.2    0.03       0
  5004.2    0.05       0  6971.9    0.16       0  7036.1    0.05       0
  7116.7    0.16       0
Bank Sta=4998.2,5004.2
Exp/Cntr=0.3,0.1

Type RM Length L Ch R = 1,1890,1462,1462,1462
BEGIN DESCRIPTION:
Mapping XS 8da3d7f4
END DESCRIPTION:
XS GIS Cut Line= 4
      3610132.43     10520016.52      3610132.43     10521266.50
      3610215.76     10521905.38      3611743.54     10522690.10
#Sta/Elev= 30
  4099.2  367.47  4222.9  370.17  4322.9  365.75  4442.9  349.65  4522.9  331.52
  4562.9  325.62  4692.9  318.05  4772.9  310.95  4802.9  310.56  4859.9  303.89
  4862.6  303.39  4865.9  303.89  4887.8  304.42  4982.9  306.55  5002.9  304.35
  5012.9  306.18  5102.9  304.41  5615.1  304.59  6319.8  308.62  7062.8  307.17
  7211.9  312.78  7265.1  317.81  7395.6  323.18  7434.4  322.54  7567.5  333.89
  7611.9  341.53  7617.5  345.29  7650.4  353.67  7661.9  360.36  7711.0  367.64
#Mann=5,-1,0
  4099.2    0.16       0  4859.9    0.03       0  4865.9    0.16       0
  4887.8    0.05       0  7265.1    0.16       0
Bank Sta=4859.9,4865.9
Exp/Cntr=0.3,0.1

Type RM Length L Ch R = 1,428,0,0,0
BEGIN DESCRIPTION:
CEDAR CREEK 2 1.0
END DESCRIPTION:
XS GIS Cut Line= 5
      3609889.37     10519974.84      3609236.60     10521530.38
      3609299.10     10521919.27      3609826.88     10522266.50
      3611674.09     10522773.44
#Sta/Elev= 30
  2570.7  368.63  2995.3  330.52  3177.9  321.03  3331.3  310.60  3516.6  302.21
  4874.1  299.37  4876.9  298.87  4880.1  299.37  4970.5  301.18  4999.3  299.50
  5021.7  301.38  5229.5  300.76  5882.7  304.49  6395.7  304.70  6525.3  309.16
  6678.0  323.38  6792.3  333.62  6852.0  335.82  6934.9  335.14  6975.0  339.68
  6986.8  343.79  7038.6  351.74  7054.2  354.94  7069.7  360.74  7088.7  360.33
  7093.9  362.36  7111.2  361.21  7128.3  362.34  7133.5  364.91  7198.8  369.11
#Mann=5,-1,0
  2570.7    0.16       0  3516.6    0.05       0  4874.1    0.03       0
  4880.1    0.05       0  6678.0    0.16       0
Bank Sta=4874.1,4880.1
Exp/Cntr=0.3,0.1

Chan Stop Cuts=-1