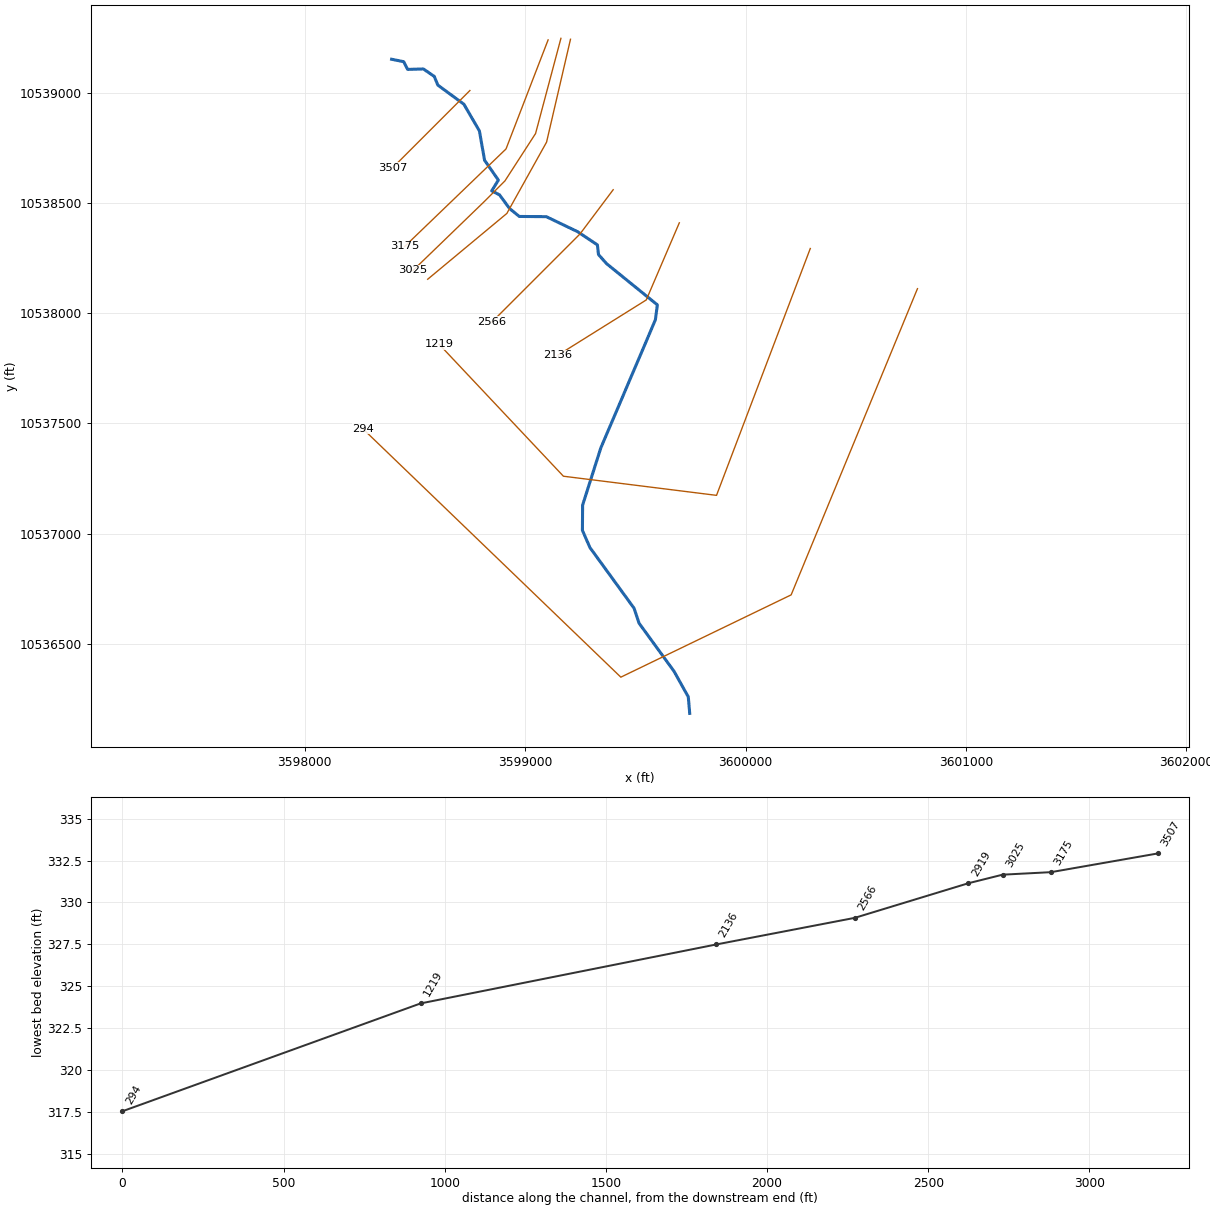
--- CEDAR DUGOUT.prj (project) ---

Proj Title=CEDAR DUGOUT Base Level Engineering
Current Plan=p01
Default Exp/Contr=0.3,0.1
English Units
Geom File=g01
Flow File=f01
Plan File=p01
Y Axis Title=Elevation
X Axis Title(PF)=Main Channel Distance
X Axis Title(XS)=Station
BEGIN DESCRIPTION:
CEDAR DUGOUT
END DESCRIPTION:
DSS Export Rating Curves= 0
DSS Export Rating Curve Sorted= 0
DSS Export Volume Flow Curves= 0
DXF OffsetX= 0
DXF OffsetY= 0
DXF ScaleX= 1
DXF ScaleY= 10

--- CEDAR DUGOUT.p01 (plan) ---

Plan Title=Multiple Run
Short Identifier=Multiple
Geom File=g01
Flow File=f01
Subcritical Flow
K Sum by GR= 0
Std Step Tol= 0.01
Critical Tol= 0.01
Num of Std Step Trials= 20
Max Error Tol= 0.3
Flow Tol Ratio= 0.001
Split Flow NTrial= 30
Split Flow Tol= 0.02
Split Flow Ratio= 0.02
Log Output Level= 0
Friction Slope Method= 1
Unsteady Friction Slope Method= 2
Unsteady Bridges Friction Slope Method= 1
Parabolic Critical Depth
Global Vel Dist=  1 , 1 , 1
Global Log Level= 0
CheckData=True
Encroach Param= -1, 0, 0, 0
BEGIN DESCRIPTION:
Multiple Run
END DESCRIPTION:

--- CEDAR DUGOUT.f01 (steady flow) ---

Flow Title=Multiple
Program Version=4.10
Number of Profiles= 7
Profile Names=10-year,25-year,50-year,1pct_min,100-year,1pct_plu,500-year
River Rch & RM=CEDAR DUGOUT,Reach-1         ,3507
    1211    1689    2089    1886    2551    3450    3791
Boundary for River Rch & Prof#=CEDAR DUGOUT,Reach-1         , 1
Up Type= 0
Dn Type= 3
Dn Slope=0.0015
Boundary for River Rch & Prof#=CEDAR DUGOUT,Reach-1         , 2
Up Type= 0
Dn Type= 3
Dn Slope=0.0015
Boundary for River Rch & Prof#=CEDAR DUGOUT,Reach-1         , 3
Up Type= 0
Dn Type= 3
Dn Slope=0.0015
Boundary for River Rch & Prof#=CEDAR DUGOUT,Reach-1         , 4
Up Type= 0
Dn Type= 3
Dn Slope=0.0015
Boundary for River Rch & Prof#=CEDAR DUGOUT,Reach-1         , 5
Up Type= 0
Dn Type= 3
Dn Slope=0.0015
Boundary for River Rch & Prof#=CEDAR DUGOUT,Reach-1         , 6
Up Type= 0
Dn Type= 3
Dn Slope=0.0015
Boundary for River Rch & Prof#=CEDAR DUGOUT,Reach-1         , 7
Up Type= 0
Dn Type= 3
Dn Slope=0.0015
DSS Import GetInterval= 0
DSS Import GetPeak= 0
DSS Import FillOption= 0

--- CEDAR DUGOUT.g01 (geometry) ---

Geom Title=Existing Conditions
Program Version=4.10

River Reach=CEDAR DUGOUT    ,Reach-1
Reach XY= 30
       3598394.5       10539152.      3598449.25       10539141.
      3598467.25       10539106.      3598538.75       10539108.
      3598588.25       10539074.        3598604.       10539035.
       3598722.5       10538948.      3598792.75       10538827.
      3598816.25       10538694.      3598878.75       10538604.
      3598848.75       10538555.        3598884.       10538537.
       3598929.5       10538475.      3598973.75       10538439.
      3599096.25       10538438.        3599238.       10538370.
        3599328.       10538310.        3599333.       10538266.
       3599369.5       10538225.        3599600.       10538038.
        3599591.       10537970.       3599343.5       10537389.
        3599261.       10537130.        3599260.       10537015.
      3599294.25       10536937.      3599494.25       10536662.
        3599517.       10536594.       3599675.5       10536376.
      3599740.25       10536260.      3599746.75       10536185.

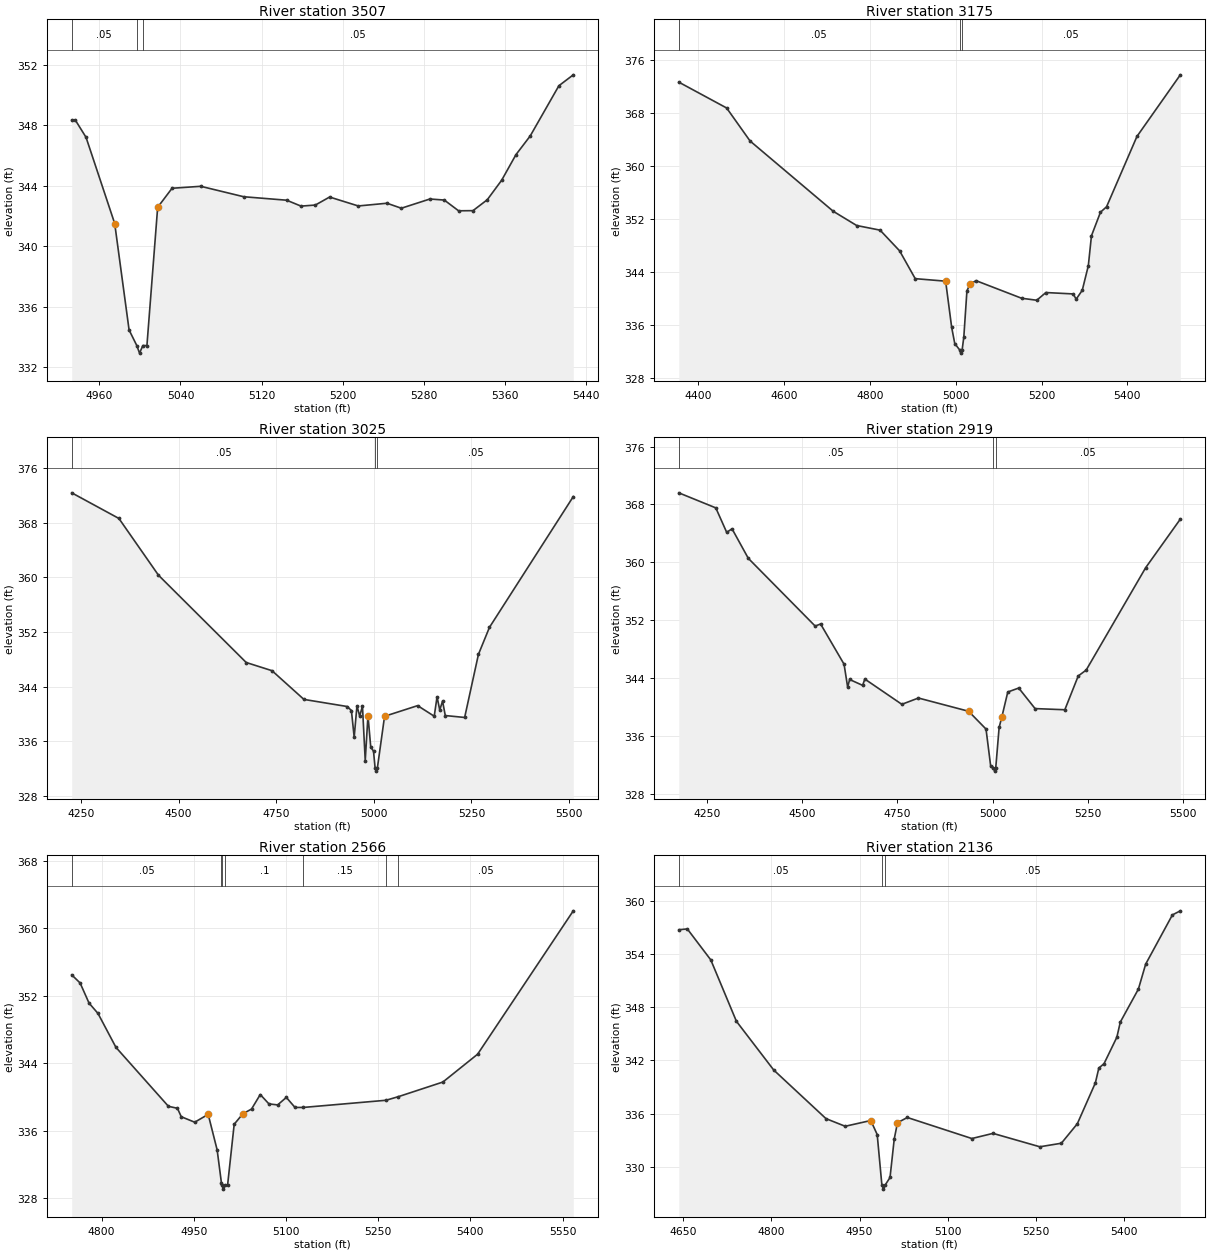
Type RM Length L Ch R = 1 ,3507    ,332,332,332
BEGIN DESCRIPTION:
CEDAR DUGOUT 5.0
END DESCRIPTION:
XS GIS Cut Line= 3
       3598749.6     10539010.18      3598699.61     10538960.19
      3598399.58     10538660.16
#Sta/Elev= 30
  4932.7  348.34  4936.2  348.34  4946.8   347.2  4975.1   341.5  4989.3  334.46
  4996.9  333.43  4999.6  332.93  5002.9  333.43  5006.9  333.43  5017.5  342.57
  5031.7  343.83    5060  343.96  5102.4  343.27  5144.8  343.04    5159  342.65
  5173.1  342.72  5187.2  343.25  5215.5  342.66  5243.8  342.84    5258  342.51
  5286.2  343.12  5300.4  343.05  5314.5  342.34  5328.7  342.35  5342.8  343.07
    5357  344.36  5371.1  346.05  5385.2  347.29  5413.5  350.61  5427.7  351.33
#Mann= 3 ,-1 , 0
  4932.7     .05       0  4996.9     .03       0  5002.9     .05       0
Bank Sta=4975.1,5017.5
XS Rating Curve= 0 ,0
Exp/Cntr=0.3,0.1

Type RM Length L Ch R = 1 ,3175    ,150,150,150
BEGIN DESCRIPTION:
CEDAR DUGOUT 4.0
END DESCRIPTION:
XS GIS Cut Line= 3
      3599104.44      10539239.9      3598913.46     10538745.09
      3598454.01     10538302.98
#Sta/Elev= 30
  4355.3   372.6  4466.7  368.71  4521.3  363.74    4715  353.16  4769.5  351.02
  4824.1  350.32  4869.5  347.21  4905.9  343.02  4976.7  342.64  4990.8  335.68
    4998  333.25  5009.2  332.31  5011.9  331.81  5015.2  332.31  5019.1  334.26
  5026.3  341.18  5033.3  342.17  5047.4  342.72  5153.7  340.07  5188.9  339.77
  5210.2  340.93  5273.8  340.72  5280.7  339.93  5294.9  341.27    5309  344.96
  5316.3  349.47  5337.3  353.02  5351.5  353.84  5422.2  364.42  5523.3   373.7
#Mann= 3 ,-1 , 0
  4355.3     .05       0  5009.2     .03       0  5015.2     .05       0
Bank Sta=4976.7,5033.3
XS Rating Curve= 0 ,0
Exp/Cntr=0.3,0.1

Type RM Length L Ch R = 1 ,3025    ,106,106,106
BEGIN DESCRIPTION:
Mapping XS 93d03428
END DESCRIPTION:
XS GIS Cut Line= 5
      3599162.54     10539246.92      3599047.53     10538815.09
      3598908.64     10538600.25      3598815.33     10538506.93
      3598491.95      10538194.4
#Sta/Elev= 30
  4226.3  372.37  4347.1  368.62  4448.4  360.32  4673.1  347.55  4739.2  346.35
  4820.9  342.15  4931.9  341.11  4942.5  340.52  4949.6  336.62  4956.7  341.22
  4963.7  339.71  4970.8  341.16  4977.9   333.2  4984.9  339.79    4992  335.18
  4999.1  334.58  5003.1  332.16  5005.9  331.66  5009.1  332.16  5027.4  339.68
  5112.1  341.24  5154.6  339.69  5161.8  342.53  5168.7  340.61  5175.9   341.9
  5182.9  339.79  5232.5  339.51  5267.8  348.74  5296.1   352.7  5510.7  371.82
#Mann= 3 ,-1 , 0
  4226.3     .05       0  5003.1     .03       0  5009.1     .05       0
Bank Sta=4984.9,5027.4
XS Rating Curve= 0 ,0
Exp/Cntr=0.3,0.1

Type RM Length L Ch R = 1 ,2919    ,353,353,353
BEGIN DESCRIPTION:
Mapping XS f93af541
END DESCRIPTION:
XS GIS Cut Line= 4
      3599205.96     10539242.63      3599097.44     10538776.03
      3598917.32     10538452.68      3598558.28     10538154.19
#Sta/Elev= 30
  4176.2   369.6  4273.3  367.52  4301.9  364.14  4315.9  364.63  4358.6  360.55
  4534.1  351.19  4548.3  351.48  4609.9  345.92  4619.3  342.75  4624.5  343.81
  4658.6     343  4664.4  343.87  4761.5  340.38    4805  341.25  4936.7  339.42
  4982.4  336.96  4994.7  331.82    5002  331.65  5004.8  331.15    5008  331.65
  5016.8  337.19    5024  338.65  5039.5  342.08  5068.2  342.63  5111.1  339.79
  5189.2  339.63  5224.4   344.3  5245.2  345.11  5401.5  359.27  5492.3  365.97
#Mann= 3 ,-1 , 0
  4176.2     .05       0    5002     .03       0    5008     .05       0
Bank Sta=4936.7,5024
XS Rating Curve= 0 ,0
Exp/Cntr=0.3,0.1

Type RM Length L Ch R = 1 ,2566    ,430,430,430
BEGIN DESCRIPTION:
CEDAR DUGOUT 3.0
END DESCRIPTION:
XS GIS Cut Line= 3
      3599399.61      10538560.2      3599249.61     10538360.19
       3598849.6     10537960.18
#Sta/Elev= 30
  4751.6  354.47  4765.2  353.51  4779.7  351.13  4794.3   349.9  4823.5  345.88
  4908.9  338.89  4923.5  338.66  4929.7  337.66  4951.6  337.01  4973.5  337.94
  4988.1  333.72    4995  329.84  4995.5  329.58  4998.2  329.08  5001.5  329.58
  5005.1  329.58  5015.8  336.77  5029.9  338.01    5044  338.57  5058.2  340.29
  5072.3  339.18  5086.5  339.06  5100.6  339.95  5114.7  338.76  5128.1  338.76
  5262.7  339.61  5282.9  340.04  5355.2  341.77  5411.7  345.07  5567.3  362.06
#Mann= 7 ,-1 , 0
  4751.6     .05       0    4995      .1       0  4995.5     .07       0
  5001.5      .1       0  5128.1     .15       0  5262.7     .08       0
  5282.9     .05       0
Bank Sta=4973.5,5029.9
XS Rating Curve= 0 ,0
Exp/Cntr=0.3,0.1

Type RM Length L Ch R = 1 ,2136    ,917,917,917
BEGIN DESCRIPTION:
CEDAR DUGOUT 2.0
END DESCRIPTION:
XS GIS Cut Line= 3
      3599699.59     10538410.15      3599549.61     10538060.19
      3599149.65     10537810.21
#Sta/Elev= 30
  4642.7  356.71  4657.2   356.8  4697.1  353.31  4740.6   346.4    4804  340.91
  4892.9  335.43  4925.5  334.57    4969  335.22  4979.9  333.64  4987.8  327.99
  4990.6  327.49  4993.8  327.99  5001.7   328.8  5008.9  333.16  5014.4  334.97
  5031.1  335.56  5140.8  333.19  5176.7  333.77  5256.3  332.26  5292.9  332.66
    5320  334.85  5350.7  339.46  5356.6  341.13  5365.4  341.62  5387.2   344.6
  5393.1  346.31  5423.8  350.02  5436.2  352.84  5481.6  358.38  5495.1  358.84
#Mann= 3 ,-1 , 0
  4642.7     .05       0  4987.8     .03       0  4993.8     .05       0
Bank Sta=4969,5014.4
XS Rating Curve= 0 ,0
Exp/Cntr=0.3,0.1

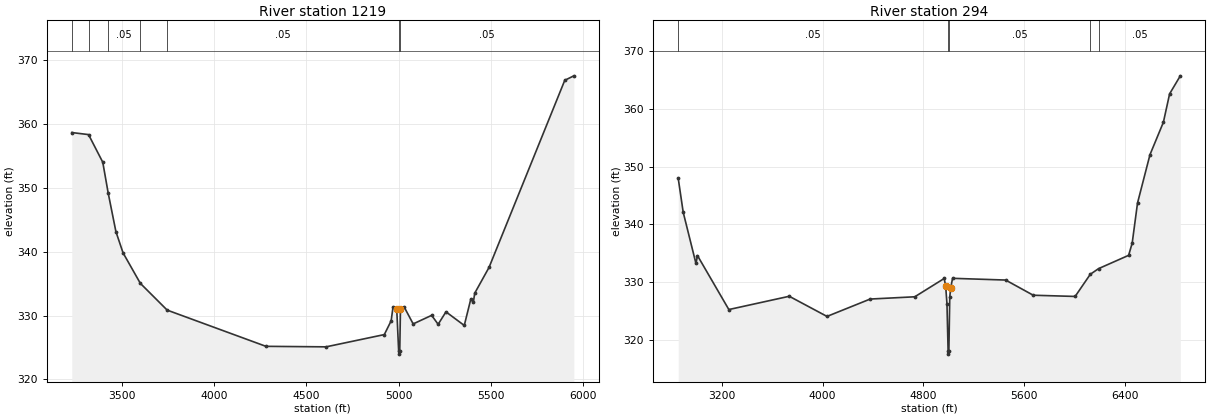
Type RM Length L Ch R = 1 ,1219    ,925,925,925
BEGIN DESCRIPTION:
Mapping XS 1b68b98e
END DESCRIPTION:
XS GIS Cut Line= 4
      3600293.67     10538293.71      3599868.32     10537173.91
      3599173.88     10537260.72      3598609.62     10537859.69
#Sta/Elev= 30
  3228.9  358.66  3319.8  358.34  3396.9  354.01  3426.3  349.18    3468  343.16
  3506.7  339.83  3600.5  335.05  3745.9  330.86    4281  325.19  4606.9  325.11
  4922.5  327.03  4959.6  329.19  4969.7  331.35  4989.8  331.02  5000.2  324.47
  5002.9  323.97  5006.2  324.47    5010  331.06  5030.1  331.35  5078.8   328.7
  5178.9  330.04  5214.1  328.64  5256.6  330.59  5355.7  328.46  5390.9  332.55
  5405.1  332.12  5412.4  333.51    5490  337.55  5900.3  366.84  5949.5  367.54
#Mann= 7 ,-1 , 0
  3228.9     .15       0  3319.8     .08       0  3426.3     .05       0
  3600.5      .1       0  3745.9     .05       0  5000.2     .03       0
  5006.2     .05       0
Bank Sta=4989.8,5010
XS Rating Curve= 0 ,0
Exp/Cntr=0.3,0.1

Type RM Length L Ch R = 1 ,294     ,0,0,0
BEGIN DESCRIPTION:
CEDAR DUGOUT 1.0
END DESCRIPTION:
XS GIS Cut Line= 4
      3600779.79     10538111.44      3600206.86     10536722.53
      3599434.29     10536349.26      3598264.82     10537475.42
#Sta/Elev= 30
  2854.1  347.96  2893.6  342.09  2994.7  333.23  3006.9  334.59  3255.7  325.25
  3735.1  327.55  4034.5  324.06  4377.3  327.07  4731.1  327.46  4964.3  330.63
    4976  329.35  4986.5  326.25  4995.6  318.03  4998.4  317.53  5001.6  318.03
  5008.7  327.41  5015.7  328.96    5031  330.66  5451.9  330.36  5671.1  327.73
  6003.5  327.52  6123.9  331.36  6189.7  332.34    6428  334.64  6456.3  336.76
  6498.5   343.7  6597.5  352.08  6703.8  357.69  6753.2  362.61  6838.1  365.73
#Mann= 5 ,-1 , 0
  2854.1     .05       0  4995.6     .03       0  5001.6     .05       0
  6123.9     .15       0  6189.7     .05       0
Bank Sta=4976,5015.7
XS Rating Curve= 0 ,0
Exp/Cntr=0.3,0.1

Chan Stop Cuts=-1
Use User Specified Reach Order=0
Composite Channel Slope=5