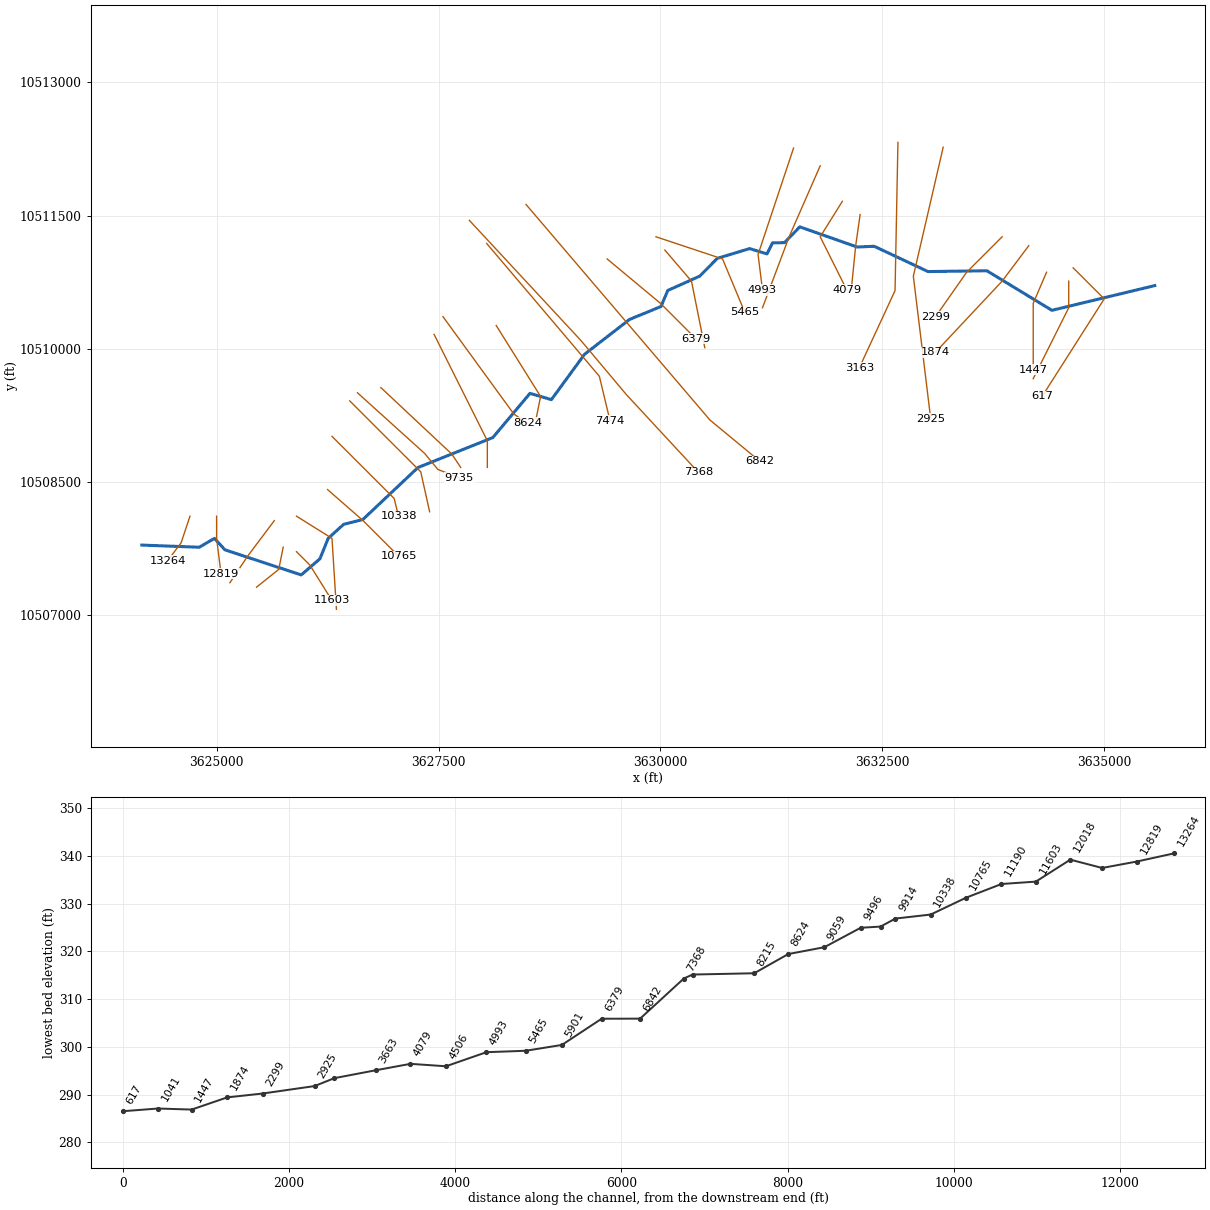
--- COPPER CREEK.prj (project) ---

Proj Title=COPPER CREEK Base Level Engineering
Current Plan=p01
Default Exp/Contr=0.3,0.1
English Units
Geom File=g01
Flow File=f01
Plan File=p01
Y Axis Title=Elevation
X Axis Title(PF)=Main Channel Distance
X Axis Title(XS)=Station
BEGIN DESCRIPTION:
COPPER CREEK
END DESCRIPTION:
DSS Export Rating Curves= 0
DSS Export Rating Curve Sorted= 0
DSS Export Volume Flow Curves= 0
DXF OffsetX= 0
DXF OffsetY= 0
DXF ScaleX= 1
DXF ScaleY= 10

--- COPPER CREEK.p01 (plan) ---

Plan Title=Multiple Run
Short Identifier=Multiple
Geom File=g01
Flow File=f01
Subcritical Flow
K Sum by GR= 0
Std Step Tol= 0.01
Critical Tol= 0.01
Num of Std Step Trials= 20
Max Error Tol= 0.3
Flow Tol Ratio= 0.001
Split Flow NTrial= 30
Split Flow Tol= 0.02
Split Flow Ratio= 0.02
Log Output Level= 0
Friction Slope Method= 1
Unsteady Friction Slope Method= 2
Unsteady Bridges Friction Slope Method= 1
Parabolic Critical Depth
Global Vel Dist=  1 , 1 , 1
Global Log Level= 0
CheckData=True
Encroach Param= -1, 0, 0, 0
BEGIN DESCRIPTION:
Multiple Run
END DESCRIPTION:

--- COPPER CREEK.f01 (steady flow) ---

Flow Title=Multiple
Program Version=4.10
Number of Profiles= 7
Profile Names=10-year,25-year,50-year,1pct_min,100-year,1pct_plu,500-year
River Rch & RM=COPPER CREEK,Reach-1         ,13264
    1144    1586    1954    1757    2376    3213    3502
River Rch & RM=COPPER CREEK,Reach-1         ,11603
    1876    2658    3323    3025    4092    5533    6187
River Rch & RM=COPPER CREEK,Reach-1         ,9059
    3128    4541    5771    5333    7213    9754   11240
River Rch & RM=COPPER CREEK,Reach-1         ,6842
    3128    4541    5771    5333    7213    9754   11240
Boundary for River Rch & Prof#=COPPER CREEK,Reach-1         , 1
Up Type= 0
Dn Type= 3
Dn Slope=0.0054
Boundary for River Rch & Prof#=COPPER CREEK,Reach-1         , 2
Up Type= 0
Dn Type= 3
Dn Slope=0.0054
Boundary for River Rch & Prof#=COPPER CREEK,Reach-1         , 3
Up Type= 0
Dn Type= 3
Dn Slope=0.0054
Boundary for River Rch & Prof#=COPPER CREEK,Reach-1         , 4
Up Type= 0
Dn Type= 3
Dn Slope=0.0054
Boundary for River Rch & Prof#=COPPER CREEK,Reach-1         , 5
Up Type= 0
Dn Type= 3
Dn Slope=0.0054
Boundary for River Rch & Prof#=COPPER CREEK,Reach-1         , 6
Up Type= 0
Dn Type= 3
Dn Slope=0.0054
Boundary for River Rch & Prof#=COPPER CREEK,Reach-1         , 7
Up Type= 0
Dn Type= 3
Dn Slope=0.0054
DSS Import GetInterval= 0
DSS Import GetPeak= 0
DSS Import FillOption= 0

--- COPPER CREEK.g01 (geometry) ---

Geom Title=Existing Conditions
Program Version=4.10

River Reach=COPPER CREEK    ,Reach-1
Reach XY= 30
      3624157.01     10507784.49      3624803.75       10507760.
       3624975.5       10507860.       3625093.5       10507731.
      3625952.75       10507448.        3626163.       10507629.
      3626256.75       10507860.       3626430.5       10508018.
       3626647.5       10508073.      3627267.25       10508658.
      3628111.75       10508997.      3628530.25       10509495.
       3628771.5       10509424.      3629144.25       10509935.
      3629652.75       10510329.       3630006.5       10510474.
       3630082.5       10510655.      3630441.75       10510816.
        3630641.       10511017.      3631004.75       10511127.
        3631200.       10511067.       3631262.5       10511192.
        3631397.       10511194.      3631569.75       10511372.
       3632215.5       10511145.      3632408.25       10511153.
      3633014.25       10510868.        3633678.       10510877.
        3634410.       10510431.        3635569.       10510710.

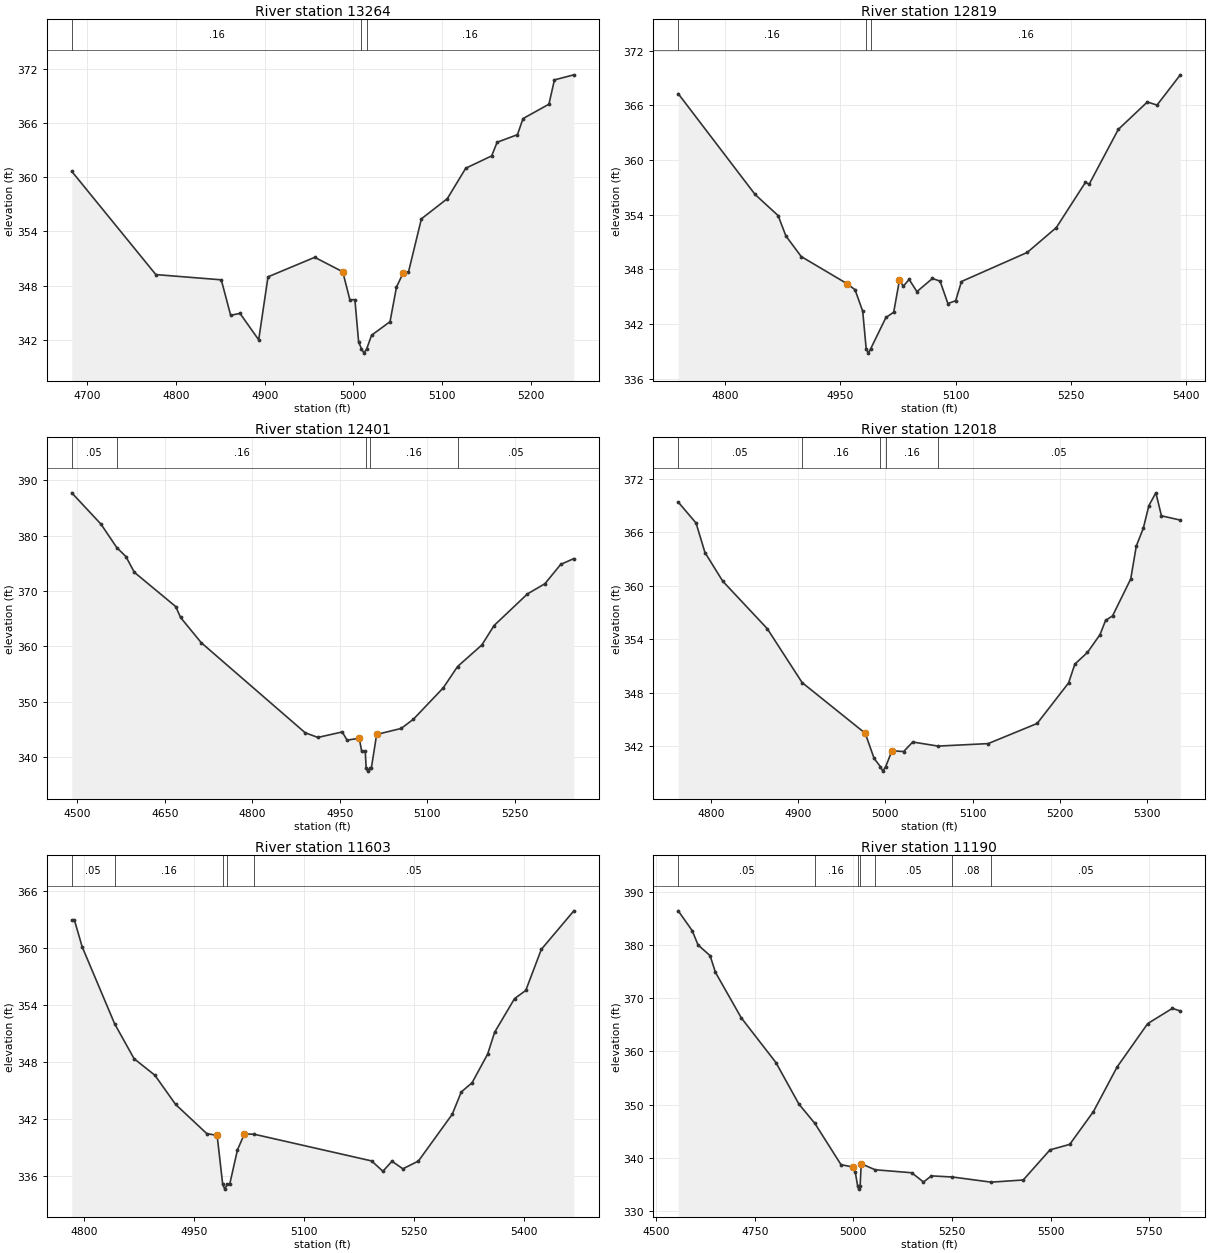
Type RM Length L Ch R = 1 ,13264   ,445,445,445
BEGIN DESCRIPTION:
COPPER CREEK 30.0
END DESCRIPTION:
XS GIS Cut Line= 3
       3624699.6     10508110.15      3624599.61     10507810.19
       3624449.6     10507610.18
#Sta/Elev= 30
  4682.5  360.63  4777.3  349.21  4851.1  348.63  4861.7   344.7  4872.2  344.92
  4893.3  341.99  4903.8  348.96  4956.5  351.12  4988.1  349.52  4996.1  346.43
  5001.8  346.43    5006  341.74  5009.2  341.02    5012  340.52  5015.2  341.02
  5020.6   342.5  5041.4     344  5048.7  347.83    5056  349.34  5062.2  349.49
  5076.8  355.38    5106  357.61  5126.8  360.98    5156  362.34  5162.2  363.85
  5185.1  364.69  5191.4  366.47  5220.6  368.06  5226.8  370.75  5248.7  371.31
#Mann= 3 ,-1 , 0
  4682.5     .16       0  5009.2     .07       0  5015.2     .16       0
Bank Sta=4988.1,5056
XS Rating Curve= 0 ,0
Exp/Cntr=0.3,0.1

Type RM Length L Ch R = 1 ,12819   ,418,418,418
BEGIN DESCRIPTION:
COPPER CREEK 29.0
END DESCRIPTION:
XS GIS Cut Line= 3
      3624999.61     10508110.23      3624999.61     10507860.19
      3625049.61     10507460.14
#Sta/Elev= 30
  4739.1  367.29  4839.1  356.23  4869.1  353.91  4879.1  351.69  4899.1  349.42
  4959.1  346.42  4969.1  345.78  4979.1  343.42  4983.6  339.32  4986.4  338.82
  4989.6  339.32  5009.3  342.73  5019.4  343.31  5026.9  346.82    5032  346.17
  5039.5  346.91  5049.6  345.57  5069.8  347.01  5079.8  346.72  5089.9  344.26
    5100  344.57  5107.6  346.68  5193.2  349.87    5231   352.6  5268.8  357.55
  5273.8  357.37  5311.6  363.37  5349.4  366.38    5362  366.04  5392.3  369.36
#Mann= 3 ,-1 , 0
  4739.1     .16       0  4983.6     .07       0  4989.6     .16       0
Bank Sta=4959.1,5026.9
XS Rating Curve= 0 ,0
Exp/Cntr=0.3,0.1

Type RM Length L Ch R = 1 ,12401   ,383,383,383
BEGIN DESCRIPTION:
COPPER CREEK 28.0
END DESCRIPTION:
XS GIS Cut Line= 3
      3625649.64     10508060.23      3625349.61     10507660.19
      3625149.61     10507360.19
#Sta/Elev= 30
  4490.5  387.75  4540.6  382.09  4567.7  377.85  4583.3  376.24  4597.8  373.39
  4668.7   367.2    4677  365.23  4712.4  360.68  4890.6   344.4  4912.4  343.56
  4954.1  344.55  4962.4  343.06  4983.3  343.42  4987.4  341.06  4993.6  341.06
  4995.1  337.97  4997.8  337.47  5001.1  337.97  5004.1  338.08  5013.1   344.1
  5055.1  345.18  5076.2  346.86  5127.3  352.52  5151.8  356.37  5193.4  360.26
  5214.4  363.78  5271.5  369.48  5301.5  371.33  5328.6  374.82  5351.1  375.87
#Mann= 5 ,-1 , 0
  4490.5     .05       0  4567.7     .16       0  4995.1     .07       0
  5001.1     .16       0  5151.8     .05       0
Bank Sta=4983.3,5013.1
XS Rating Curve= 0 ,0
Exp/Cntr=0.3,0.1

Type RM Length L Ch R = 1 ,12018   ,415,415,415
BEGIN DESCRIPTION:
COPPER CREEK 27.0
END DESCRIPTION:
XS GIS Cut Line= 3
      3625749.61     10507760.22      3625699.61     10507510.19
      3625449.64     10507310.21
#Sta/Elev= 30
  4762.8  369.41  4783.2  367.06  4793.4  363.75  4813.8  360.53  4864.8   355.2
  4904.7  349.15    4977  343.46  4987.2  340.63  4994.4  339.71  4997.1  339.21
  5000.4  339.71  5007.6  341.49    5021  341.41  5031.4  342.48  5060.4  342.02
  5117.8   342.3  5173.9  344.56  5209.9  349.11  5217.1  351.22  5231.5  352.53
  5245.9  354.53  5252.3  356.13  5260.3  356.64  5281.1  360.78  5287.5  364.48
  5295.5  366.47  5301.9  369.02  5309.9  370.45  5316.3  367.87  5337.9  367.39
#Mann= 5 ,-1 , 0
  4762.8     .05       0  4904.7     .16       0  4994.4     .07       0
  5000.4     .16       0  5060.4     .05       0
Bank Sta=4977,5007.6
XS Rating Curve= 0 ,0
Exp/Cntr=0.3,0.1

Type RM Length L Ch R = 1 ,11603   ,413,413,413
BEGIN DESCRIPTION:
COPPER CREEK 26.0
END DESCRIPTION:
XS GIS Cut Line= 3
      3625899.58     10507710.22      3626049.61     10507560.19
      3626299.63     10507160.16
#Sta/Elev= 30
  4783.6  362.96  4787.2  362.96  4797.8  360.13    4842  352.03  4868.5  348.35
  4896.8  346.61  4925.1  343.53  4967.5  340.46  4981.6  340.27  4989.2  335.11
    4992  334.61  4995.2  335.11  4998.7  335.11  5009.3  338.75  5018.8  340.43
  5032.3  340.39  5192.1  337.58  5207.4  336.49  5219.8  337.55  5234.6  336.75
  5255.8  337.57  5301.8  342.49  5314.2  344.85  5328.9  345.82  5350.1  348.84
  5359.6  351.14  5386.7  354.68    5402  355.54  5423.2  359.87  5467.5  363.93
#Mann= 5 ,-1 , 0
  4783.6     .05       0    4842     .16       0  4989.2     .07       0
  4995.2     .16       0  5032.3     .05       0
Bank Sta=4981.6,5018.8
XS Rating Curve= 0 ,0
Exp/Cntr=0.3,0.1

Type RM Length L Ch R = 1 ,11190   ,425,425,425
BEGIN DESCRIPTION:
COPPER CREEK 25.0
END DESCRIPTION:
XS GIS Cut Line= 3
      3625899.57     10508110.21      3626299.61     10507860.19
      3626349.61      10507060.2
#Sta/Elev= 30
  4555.7  386.43  4591.1  382.71  4605.9  380.02  4636.5     378  4650.1  374.86
  4715.5  366.32  4803.4  357.91  4861.8  350.09  4902.2  346.47  4968.5  338.71
  4998.6  338.27  5004.5  337.39  5010.9  334.61  5013.6  334.11  5016.9  334.61
  5019.8  338.88    5055  337.75  5147.7  337.19  5177.7  335.45  5197.8   336.6
  5251.2  336.39  5349.2  335.42  5430.7  335.83  5498.4  341.49  5548.5  342.52
  5608.6  348.68  5668.7  357.07  5746.3  365.23    5809   368.1    5829  367.59
#Mann= 7 ,-1 , 0
  4555.7     .05       0  4902.2     .16       0  5010.9     .07       0
  5016.9     .16       0    5055     .05       0  5251.2     .08       0
  5349.2     .05       0
Bank Sta=4998.6,5019.8
XS Rating Curve= 0 ,0
Exp/Cntr=0.3,0.1

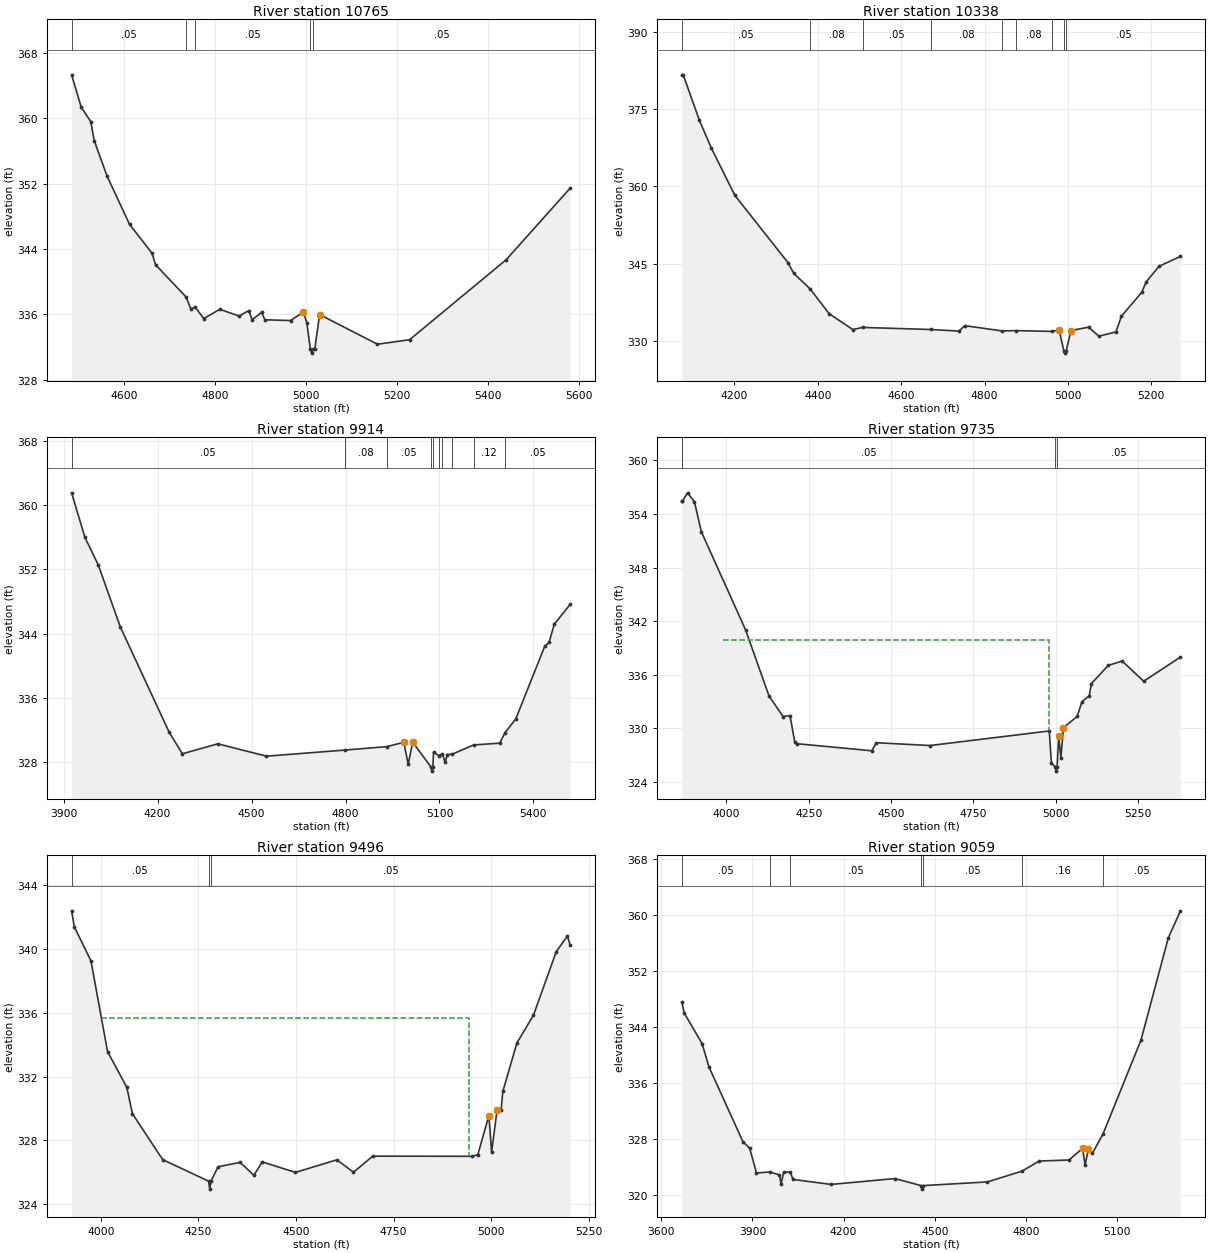
Type RM Length L Ch R = 1 ,10765   ,427,427,427
BEGIN DESCRIPTION:
COPPER CREEK 24.0
END DESCRIPTION:
XS GIS Cut Line= 3
      3626249.63     10508410.17      3626649.61     10508060.19
      3627049.64     10507660.16
#Sta/Elev= 30
  4484.3  365.31  4505.6  361.33  4526.5  359.59  4534.1  357.24  4562.6  352.88
  4611.9     347  4661.3  343.48  4668.9  342.07    4736  338.13  4746.7  336.65
  4756.2  336.87  4775.2  335.48  4810.3  336.61    4853  335.79  4873.9  336.45
  4881.5  335.34  4902.4  336.23  4909.5  335.33  4965.9  335.24  4994.4  336.27
    5002  334.91  5009.5  331.75  5012.2  331.25  5015.5  331.75  5019.3  331.75
  5029.9  335.97  5157.2  332.34  5227.9  332.89    5440  342.66  5581.5  351.46
#Mann= 5 ,-1 , 0
  4484.3     .05       0    4736     .16       0  4756.2     .05       0
  5009.5     .04       0  5015.5     .05       0
Bank Sta=4994.4,5029.9
XS Rating Curve= 0 ,0
Exp/Cntr=0.3,0.1

Type RM Length L Ch R = 1 ,10338   ,424,424,424
BEGIN DESCRIPTION:
COPPER CREEK 23.0
END DESCRIPTION:
XS GIS Cut Line= 3
      3626299.63     10509010.17      3626999.61     10508310.19
      3627049.61     10508110.17
#Sta/Elev= 30
  4073.9  381.64  4077.4  381.64  4116.3   372.8  4144.6  367.49  4201.2  358.28
  4328.4  345.27  4342.6  343.17  4381.8  340.15  4427.4  335.35    4484  332.28
  4507.7  332.69  4671.5  332.29  4738.6  331.98  4752.7  333.03  4842.6  332.01
  4875.4  332.07  4962.6  331.92    4979   332.2  4990.1  328.21  4992.9  327.71
  4996.1  328.21  5007.3  332.09  5049.7  332.74  5074.1  330.99  5115.4  331.83
  5128.2  334.85  5177.2   339.5  5187.5  341.48  5218.4  344.53    5270  346.46
#Mann= 9 ,-1 , 0
  4073.9     .05       0  4381.8     .08       0  4507.7     .05       0
  4671.5     .08       0  4842.6     .05       0  4875.4     .08       0
  4962.6     .05       0  4990.1     .03       0  4996.1     .05       0
Bank Sta=4979,5007.3
XS Rating Curve= 0 ,0
Exp/Cntr=0.3,0.1

Type RM Length L Ch R = 1 ,9914    ,179,179,179
BEGIN DESCRIPTION:
COPPER CREEK 22.0
END DESCRIPTION:
XS GIS Cut Line= 3
       3626499.6      10509410.2      3627299.61     10508610.19
      3627399.62     10508160.15
#Sta/Elev= 30
  3925.4  361.52  3967.8  355.98  4010.3  352.57    4081  344.82  4236.5  331.75
    4279  329.03  4392.1  330.27  4547.7  328.73  4797.3  329.49  4931.8  329.92
  4986.1  330.46  5000.2  327.72  5014.4  330.49    5073  327.37  5075.7  326.87
    5079  327.37  5081.1  329.23  5098.3   328.8  5109.3  328.99  5118.2  327.96
  5124.6  328.93  5140.3  328.97  5208.9  330.13  5292.4  330.35  5309.2  331.65
  5343.6  333.36  5435.8  342.39  5449.9  342.89  5466.5  345.16  5517.8  347.65
#Mann= 10 ,-1 , 0
  3925.4     .05       0  4797.3     .08       0  4931.8     .05       0
    5073     .03       0    5079     .05       0  5098.3     .08       0
  5109.3     .12       0  5140.3     .05       0  5208.9     .12       0
  5309.2     .05       0
Bank Sta=4986.1,5014.4
XS Rating Curve= 0 ,0
Exp/Cntr=0.3,0.1

Type RM Length L Ch R = 1 ,9735    ,239,239,239
BEGIN DESCRIPTION:
Mapping XS b22b26e6
END DESCRIPTION:
XS GIS Cut Line= 5
      3626586.59     10509501.45      3627343.52     10508817.44
      3627492.82     10508636.88       3627669.9     10508567.44
3627733.5588578110508542.4768699
#Sta/Elev= 30
  3865.1  355.41  3866.6  355.41  3882.6  356.37  3903.6  355.37  3924.5  352.01
    4059  340.99    4130  333.59  4172.6   331.3  4193.5  331.42  4207.7  328.49
  4215.2  328.26  4441.6  327.47  4455.8  328.37  4618.7  328.06  4980.1  329.69
  4986.6  326.07  4997.9  325.69  5000.7  325.19  5003.9  325.69  5008.8  329.08
  5015.3   326.7  5023.1  330.06  5064.8  331.32  5079.1  332.96  5101.3  333.63
  5107.8  334.99  5159.1  337.04  5201.6  337.52  5266.5  335.265378.178337.9687
#Mann= 4 ,-1 , 0
  3865.1     .08       0  3866.6     .05       0  4997.9     .03       0
  5003.9     .05       0
#XS Ineff= 1 ,-1
 3990.91    4980  339.85
Permanent Ineff=
       F
Bank Sta=5008.8,5023.1
XS Rating Curve= 0 ,0
Exp/Cntr=0.3,0.1

Type RM Length L Ch R = 1 ,9496    ,437,437,437
BEGIN DESCRIPTION:
COPPER CREEK 21.0
END DESCRIPTION:
XS GIS Cut Line= 3
      3626849.61     10509560.19      3627649.61     10508810.19
      3627749.63     10508660.16
#Sta/Elev= 30
  3925.4  342.41  3932.5   341.4    3975  339.26  4017.5  333.57  4066.8  331.33
    4081  329.68  4158.7  326.79  4276.3  325.44    4279  324.94  4282.3  325.44
  4300.3  326.34  4356.9  326.62  4392.1  325.81  4413.6  326.65  4498.6  325.99
  4604.6  326.78  4647.1     326  4696.4  327.01  4951.4     327  4965.6  327.11
  4993.9  329.56  5000.7  327.25  5014.9  329.93    5025  329.88  5029.5  331.07
  5065.6  334.12  5107.6  335.84  5166.2  339.84  5194.7  340.83  5202.3  340.24
#Mann= 3 ,-1 , 0
  3925.4     .05       0  4276.3     .03       0  4282.3     .05       0
#XS Ineff= 1 ,-1
    4000 4941.82335.6848
Permanent Ineff=
       F
Bank Sta=4993.9,5014.9
XS Rating Curve= 0 ,0
Exp/Cntr=0.3,0.1

Type RM Length L Ch R = 1 ,9059    ,435,435,435
BEGIN DESCRIPTION:
COPPER CREEK 20.0
END DESCRIPTION:
XS GIS Cut Line= 3
      3627449.61     10510160.18      3628049.61     10508960.19
      3628049.61     10508660.22
#Sta/Elev= 30
  3667.4  347.62  3675.8  345.99  3734.5  341.62  3756.8  338.33  3868.6  327.65
    3891   326.7  3913.4  323.18    3957  323.31  3988.8  322.91  3994.4  321.63
  4002.8  323.26  4024.8  323.32  4033.5  322.25  4159.3  321.54    4369  322.38
  4455.4  321.37  4458.1  320.87  4461.4  321.37  4673.6   321.9  4787.6  323.44
  4844.1  324.88  4941.9  325.03  4986.7  326.68  4995.1  324.36  5006.2  326.62
    5019  325.98  5054.1  328.75    5179  342.15    5269  356.75    5309   360.6
#Mann= 7 ,-1 , 0
  3667.4     .05       0    3957     .12       0  4024.8     .05       0
  4455.4     .07       0  4461.4     .05       0  4787.6     .16       0
  5054.1     .05       0
Bank Sta=4986.7,5006.2
XS Rating Curve= 0 ,0
Exp/Cntr=0.3,0.1

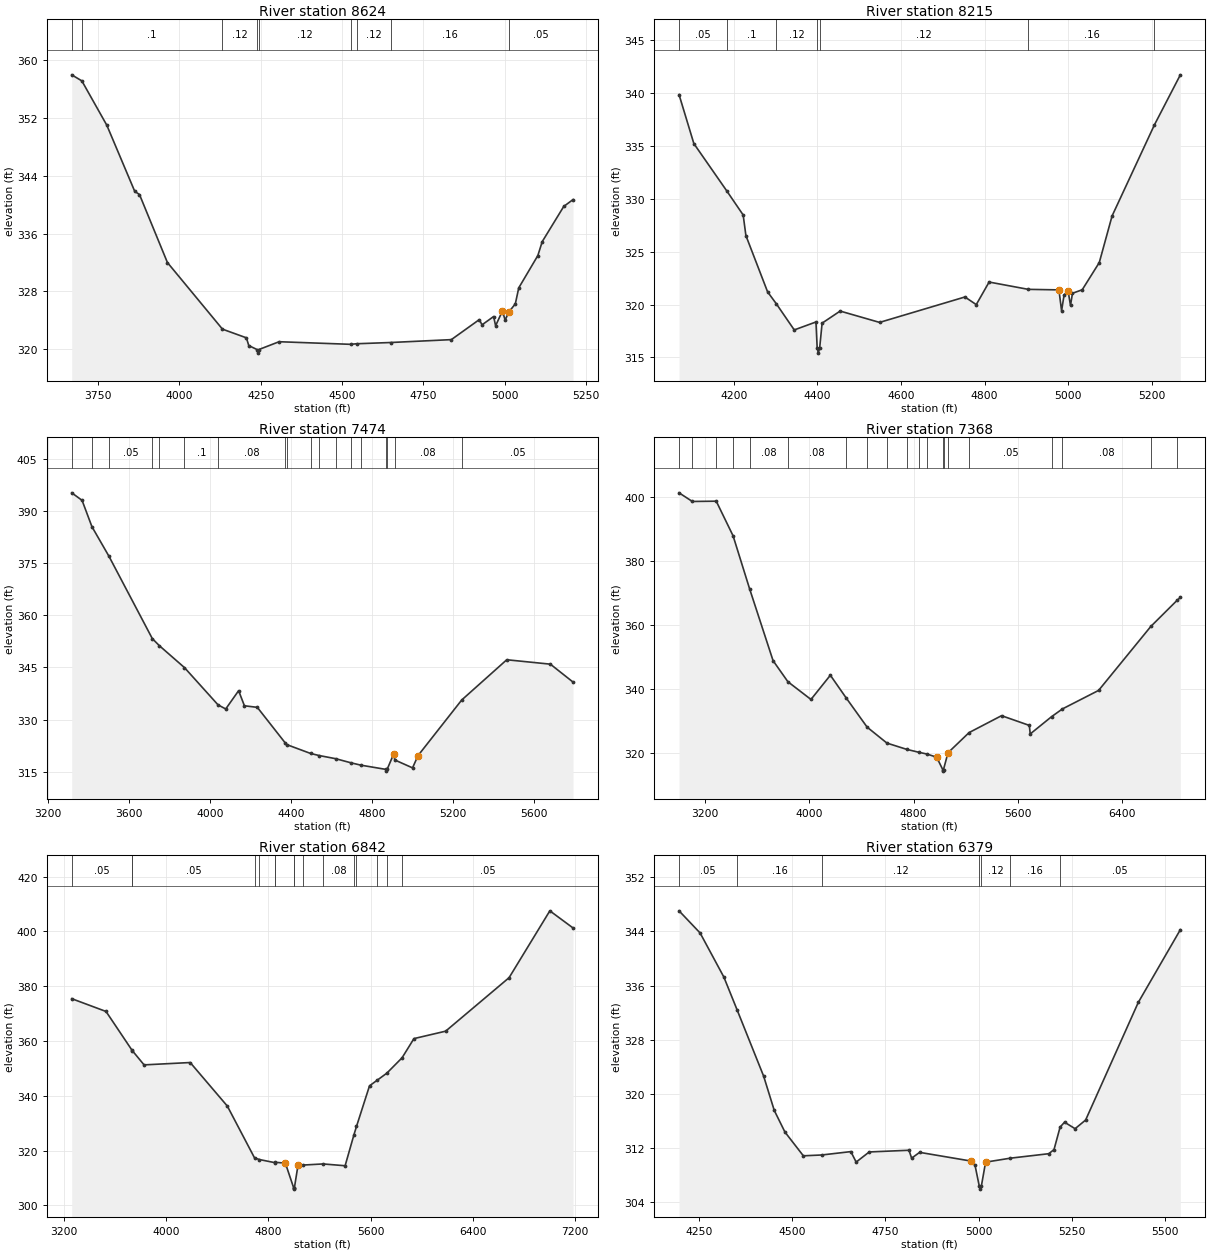
Type RM Length L Ch R = 1 ,8624    ,409,409,409
BEGIN DESCRIPTION:
COPPER CREEK 19.0
END DESCRIPTION:
XS GIS Cut Line= 3
      3627549.62     10510360.17      3628349.61     10509260.19
      3628499.61     10509160.19
#Sta/Elev= 30
  3669.5  357.98  3700.6  357.14  3777.3     351  3863.1  341.84  3877.7   341.4
  3963.5  331.98  4132.7  322.75  4206.2  321.55  4213.5  320.48  4238.7  319.93
  4241.5  319.43  4244.7  319.93  4306.7  321.01  4526.3  320.65  4545.4  320.73
  4649.3   320.9    4836   321.3  4921.8  324.07  4930.3  323.35  4965.9   324.5
    4972  323.22  4992.9  325.27  5001.4  323.99  5011.9  325.08  5032.6  326.26
  5043.1  328.47  5101.7  332.94  5115.3  334.88  5181.4  339.75  5209.9   340.7
#Mann= 9 ,-1 , 0
  3669.5     .16       0  3700.6      .1       0  4132.7     .12       0
  4238.7     .07       0  4244.7     .12       0  4526.3     .05       0
  4545.4     .12       0  4649.3     .16       0  5011.9     .05       0
Bank Sta=4992.9,5011.9
XS Rating Curve= 0 ,0
Exp/Cntr=0.3,0.1

Type RM Length L Ch R = 1 ,8215    ,741,741,741
BEGIN DESCRIPTION:
COPPER CREEK 18.0
END DESCRIPTION:
XS GIS Cut Line= 3
      3628149.59     10510260.22      3628649.61     10509460.19
      3628599.61     10509210.17
#Sta/Elev= 30
  4069.4  339.81  4104.8  335.19    4183  330.75  4222.7  328.45  4229.2  326.51
  4281.1  321.19  4301.9  320.07  4344.8   317.6  4396.7  318.35  4399.6  315.91
  4402.3  315.41  4405.6  315.91  4411.4  318.24  4454.5  319.38  4548.8  318.31
  4752.8  320.71  4779.9  319.99  4810.6  322.12  4904.3  321.43  4977.5  321.38
  4983.9   319.4  4989.8  320.89  4999.3   321.3  5005.2  319.91  5009.9  321.06
  5033.2  321.39    5074  323.96  5104.6  328.36    5206  336.97  5267.8  341.68
#Mann= 7 ,-1 , 0
  4069.4     .05       0    4183      .1       0  4301.9     .12       0
  4399.6     .07       0  4405.6     .12       0  4904.3     .16       0
    5206     .05       0
Bank Sta=4977.5,4999.3
XS Rating Curve= 0 ,0
Exp/Cntr=0.3,0.1

Type RM Length L Ch R = 1 ,7474    ,106,106,106
BEGIN DESCRIPTION:
COPPER CREEK 17.0
END DESCRIPTION:
XS GIS Cut Line= 3
      3628042.27     10511184.93       3629311.8     10509687.53
      3629431.15     10509188.44
#Sta/Elev= 30
  3316.6  395.33  3367.7  393.16  3416.3  385.58    3500   377.1  3714.7  353.32
    3749  351.31  3873.5  344.97  4039.4  334.23  4077.3  333.05    4141  338.32
  4169.6  333.97  4233.3  333.52  4371.6  323.24  4377.9   322.8  4496.1  320.24
  4538.2  319.64  4620.6  318.72  4698.4   317.5  4745.1  316.86  4868.5  315.64
  4871.2  315.14  4874.5  315.64  4907.8   320.2  4912.6  318.35  5000.1  316.08
  5027.5  319.64  5243.1  335.64  5465.5  347.23    5681  345.96  5792.9   340.8
#Mann= 18 ,-1 , 0
  3316.6     .05       0  3416.3     .08       0    3500     .05       0
  3714.7     .08       0    3749     .05       0  3873.5      .1       0
  4039.4     .08       0  4371.6     .16       0  4377.9     .08       0
  4496.1     .12       0  4538.2     .08       0  4620.6     .12       0
  4698.4     .08       0  4745.1     .12       0  4868.5     .07       0
  4874.5     .12       0  4912.6     .08       0  5243.1     .05       0
Bank Sta=4907.8,5027.5
XS Rating Curve= 0 ,0
Exp/Cntr=0.3,0.1

Type RM Length L Ch R = 1 ,7368    ,526,526,526
BEGIN DESCRIPTION:
COPPER CREEK 16.0
END DESCRIPTION:
XS GIS Cut Line= 4
      3627846.95     10511445.35      3629105.64       10510089.
      3629615.62     10509481.36      3630428.13     10508603.86
#Sta/Elev= 30
  3004.1  401.29    3106  398.59    3289  398.68  3418.1  387.84  3544.1  371.34
  3724.2  348.84  3837.8  342.25  4014.5  336.71    4163  344.28  4283.9   337.2
  4444.8  328.05  4596.5  323.07  4748.2  321.11    4839  320.22  4902.8  319.65
  4977.2  318.67  5023.6  314.81  5026.4  314.31  5029.6  314.81  5064.1  320.05
  5225.4  326.35  5474.1  331.64    5687   328.6  5693.8  325.93  5857.7  331.34
  5940.8  333.76  6217.7  339.54  6617.3  359.52  6817.8  367.65  6843.7  368.59
#Mann= 20 ,-1 , 0
  3004.1     .08       0    3106     .05       0    3289     .05       0
  3418.1     .08       0  3544.1     .08       0  3837.8     .08       0
  4283.9     .08       0  4444.8     .05       0  4596.5     .05       0
  4748.2     .05       0    4839     .08       0  4902.8     .05       0
  5023.6     .07       0  5029.6     .08       0  5064.1     .05       0
  5225.4     .05       0  5857.7     .05       0  5940.8     .08       0
  6617.3     .05       0  6817.8     .08       0
Bank Sta=4977.2,5064.1
XS Rating Curve= 0 ,0
Exp/Cntr=0.3,0.1

Type RM Length L Ch R = 1 ,6842    ,463,463,463
BEGIN DESCRIPTION:
COPPER CREEK 15.0
END DESCRIPTION:
XS GIS Cut Line= 3
      3628485.43     10511624.57       3630557.9     10509194.04
      3631122.13     10508727.47
#Sta/Elev= 30
    3259  375.46  3527.6  370.79  3730.4  356.68  3732.6  356.53  3825.6  351.28
  4186.9  352.14  4477.8  336.23  4690.8  317.31  4728.7  316.71  4850.5  315.56
  4853.4   315.7  4932.4  315.39    4997   306.4  4999.8   305.9    5003   306.4
  5031.2  314.61    5067  314.68  5227.8   315.1  5400.2  314.44  5469.6  325.79
  5489.3  328.79  5591.2  343.62    5649   345.6  5726.9  348.25  5846.2  353.87
  5939.3  360.88  6187.4  363.59  6684.6  383.14  7003.7  407.55  7185.3  401.29
#Mann= 16 ,-1 , 0
    3259     .05       0  3730.4      .1       0  3732.6     .05       0
  4690.8     .16       0  4728.7     .05       0  4850.5     .16       0
  4853.4     .05       0    4997     .04       0    5003     .05       0
    5067     .16       0  5227.8     .08       0  5469.6     .05       0
  5489.3     .08       0    5649     .05       0  5726.9     .08       0
  5846.2     .05       0
Bank Sta=4932.4,5031.2
XS Rating Curve= 0 ,0
Exp/Cntr=0.3,0.1

Type RM Length L Ch R = 1 ,6379    ,478,478,478
BEGIN DESCRIPTION:
COPPER CREEK 14.0
END DESCRIPTION:
XS GIS Cut Line= 3
      3629399.59      10511010.2      3629999.61     10510510.19
      3630399.59     10510110.21
#Sta/Elev= 30
  4195.4  347.05    4252  343.77  4315.8  337.25  4351.7  332.35  4422.6   322.6
  4451.2  317.52  4479.8  314.33  4529.3  310.81  4578.6  310.93  4656.9  311.43
  4671.2  309.88  4706.3  311.38  4813.1  311.63  4820.2  310.46  4841.7  311.32
    4980  310.03  4990.6  309.39  5001.7  306.38  5004.5  305.88  5007.7  306.38
  5018.9  309.87  5085.5  310.46  5188.6  311.12  5202.7  311.73  5219.1  315.06
    5231  315.78  5259.3  314.82  5287.6   316.1    5429  333.49  5542.1  344.26
#Mann= 7 ,-1 , 0
  4195.4     .05       0  4351.7     .16       0  4578.6     .12       0
  5001.7     .07       0  5007.7     .12       0  5085.5     .16       0
  5219.1     .05       0
Bank Sta=4980,5018.9
XS Rating Curve= 0 ,0
Exp/Cntr=0.3,0.1

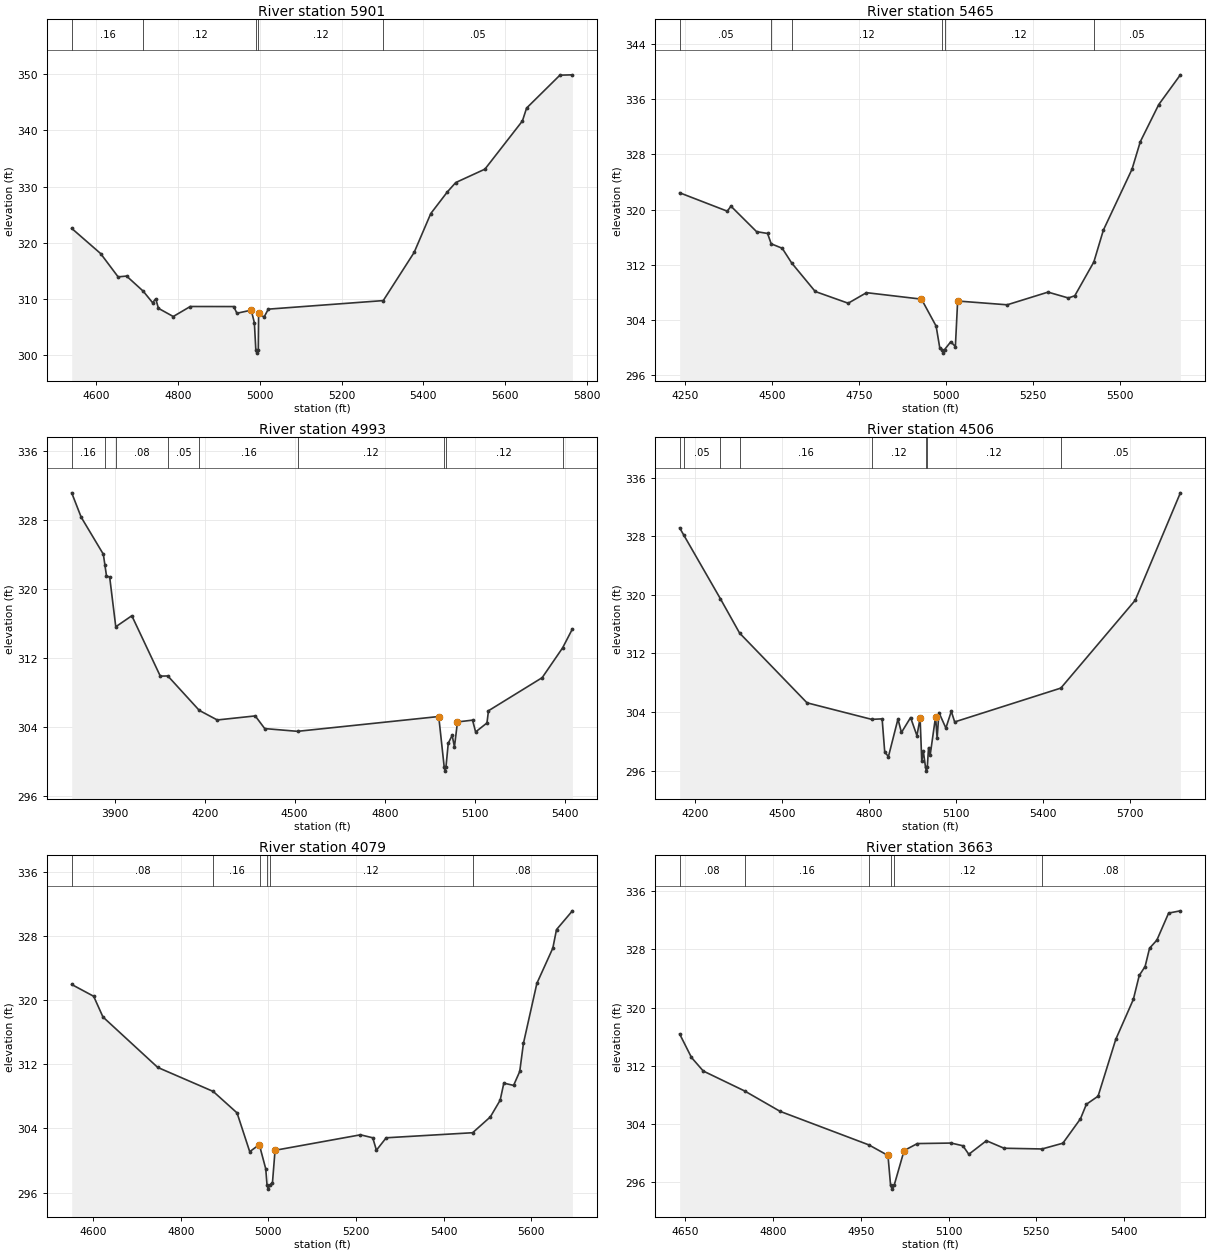
Type RM Length L Ch R = 1 ,5901    ,436,436,436
BEGIN DESCRIPTION:
COPPER CREEK 13.0
END DESCRIPTION:
XS GIS Cut Line= 3
      3630049.64     10511110.15      3630349.61     10510760.19
      3630499.61     10510010.17
#Sta/Elev= 30
  4539.3  322.57    4610   318.1  4652.9  313.95  4673.7  314.09  4714.3  311.41
  4737.4  309.35    4745  310.05  4751.6  308.36  4787.9   306.9  4829.6  308.68
    4936  308.67  4943.7  307.48  4978.8  308.03  4986.5  305.79  4990.1  300.89
  4992.8  300.39  4996.1  300.89  4996.9  307.45  5010.4  306.82  5020.6  308.21
    5302  309.73  5377.6  318.29  5418.4  325.21  5459.1  329.07  5479.5  330.72
  5550.9   333.1  5642.7  341.67  5652.9  343.96  5734.5  349.81  5765.1  349.87
#Mann= 5 ,-1 , 0
  4539.3     .16       0  4714.3     .12       0  4990.1     .07       0
  4996.1     .12       0    5302     .05       0
Bank Sta=4978.8,4996.9
XS Rating Curve= 0 ,0
Exp/Cntr=0.3,0.1

Type RM Length L Ch R = 1 ,5465    ,472,472,472
BEGIN DESCRIPTION:
COPPER CREEK 12.0
END DESCRIPTION:
XS GIS Cut Line= 3
      3629949.65     10511260.18      3630699.61     10511010.19
       3630949.6     10510410.21
#Sta/Elev= 30
    4234  322.43    4371  319.76  4381.5  320.49  4455.3  316.79  4486.9  316.53
  4497.3  315.03  4529.1  314.38  4556.2  312.25    4624  308.11  4718.8  306.41
  4771.5  307.94  4929.7     307  4971.8  303.09  4982.4   299.9  4989.9  299.67
  4992.7  299.17  4995.9  299.67    5014  300.82  5027.2  300.12  5033.7  306.73
  5176.2  306.18  5293.7  308.02  5352.2  307.17  5370.7  307.49  5425.6   312.4
    5453  317.02  5535.3  325.84  5559.2  329.84  5612.2  335.22  5674.5  339.54
#Mann= 6 ,-1 , 0
    4234     .05       0  4497.3     .16       0  4556.2     .12       0
  4989.9     .07       0  4995.9     .12       0  5425.6     .05       0
Bank Sta=4929.7,5033.7
XS Rating Curve= 0 ,0
Exp/Cntr=0.3,0.1

Type RM Length L Ch R = 1 ,4993    ,487,487,487
BEGIN DESCRIPTION:
COPPER CREEK 11.0
END DESCRIPTION:
XS GIS Cut Line= 3
      3631499.61     10512260.18      3631099.61     10511060.19
      3631149.61     10510660.21
#Sta/Elev= 30
  3757.2  331.18  3788.8  328.35  3862.6  324.05  3867.9  322.78  3873.1  321.53
  3883.7   321.4    3904  315.63  3957.5  316.91  4052.3   309.9  4077.4  309.92
  4182.2  305.92  4242.1  304.81  4368.6  305.28  4400.2  303.81  4509.5  303.49
  4979.9  305.21    4998  299.37  5000.8  298.87    5004  299.37  5011.6   302.1
  5024.6  303.03  5032.2  301.68  5042.3  304.58  5092.6  304.79  5102.7  303.42
  5140.5  304.46  5145.6  305.88  5324.4  309.72  5392.5  313.18  5425.2  315.38
#Mann= 9 ,-1 , 0
  3757.2     .16       0  3867.9     .05       0    3904     .08       0
  4077.4     .05       0  4182.2     .16       0  4509.5     .12       0
    4998     .07       0    5004     .12       0  5392.5     .05       0
Bank Sta=4979.9,5042.3
XS Rating Curve= 0 ,0
Exp/Cntr=0.3,0.1

Type RM Length L Ch R = 1 ,4506    ,427,427,427
BEGIN DESCRIPTION:
COPPER CREEK 10.0
END DESCRIPTION:
XS GIS Cut Line= 3
      3631799.62     10512060.22      3631449.61     10511260.19
      3631149.59     10510460.14
#Sta/Elev= 30
  4146.6  329.14  4160.5  328.18  4286.9  319.48  4353.5  314.77    4586  305.25
  4809.1  302.99  4845.2  303.06  4854.2  298.51    4867  297.91  4899.8  303.03
  4911.9   301.2  4943.4  303.24  4965.3  300.76  4976.2  303.16    4982  297.26
  4987.5  298.61    4995  296.42  4997.8  295.92    5001  296.42  5005.4  299.13
  5010.9  298.09  5029.6  303.36    5035   300.4  5041.2  303.92  5065.2   301.8
  5083.9  304.09  5095.5  302.64  5461.8  307.26  5718.5  319.26  5874.3  333.93
#Mann= 8 ,-1 , 0
  4146.6     .08       0  4160.5     .05       0  4286.9     .08       0
  4353.5     .16       0  4809.1     .12       0    4995     .07       0
    5001     .12       0  5461.8     .05       0
Bank Sta=4976.2,5029.6
XS Rating Curve= 0 ,0
Exp/Cntr=0.3,0.1

Type RM Length L Ch R = 1 ,4079    ,416,416,416
BEGIN DESCRIPTION:
COPPER CREEK 9.0
END DESCRIPTION:
XS GIS Cut Line= 3
      3632049.59     10511660.16      3631799.61     10511260.19
      3632099.61     10510660.18
#Sta/Elev= 30
  4551.3  321.94  4601.4  320.47  4622.6  317.89  4747.6   311.6  4874.1  308.61
  4928.6  305.93  4957.5   301.1  4978.7  301.95  4980.9  301.66  4994.1  298.95
    4997  296.93  4999.7  296.43    5003  296.93  5009.4  297.24  5015.3  301.27
  5210.2   303.2  5238.2  302.83  5246.6  301.28  5268.9  302.83  5466.1  303.46
  5506.5  305.43  5528.9  307.51  5537.3  309.64  5559.6  309.36  5573.6   311.1
    5582  314.59  5612.7  322.08  5649.1  326.47  5657.5  328.78  5693.8  331.12
#Mann= 6 ,-1 , 0
  4551.3     .08       0  4874.1     .16       0  4980.9     .12       0
    4997     .07       0    5003     .12       0  5466.1     .08       0
Bank Sta=4978.7,5015.3
XS Rating Curve= 0 ,0
Exp/Cntr=0.3,0.1

Type RM Length L Ch R = 1 ,3663    ,500,500,500
BEGIN DESCRIPTION:
COPPER CREEK 8.0
END DESCRIPTION:
XS GIS Cut Line= 3
      3632249.61     10511510.19      3632199.61     10511160.19
      3632149.61     10510660.24
#Sta/Elev= 30
  4640.4  316.37  4660.6  313.15  4680.8  311.29  4751.4  308.56  4812.1  305.76
  4963.8  301.16  4996.5  299.71    5001  295.59  5003.8  295.09    5007  295.59
  5024.1  300.38  5046.7  301.34  5104.5  301.41  5124.6  301.04  5134.7  299.87
  5164.8  301.73    5195   300.7  5259.9   300.6  5295.5  301.39  5325.6  304.74
  5335.7  306.73  5355.7  307.84  5385.9  315.63    5416  321.12  5426.1  324.41
  5436.1  325.63  5443.7  328.14  5456.2  329.25  5476.3  332.96  5496.4  333.27
#Mann= 6 ,-1 , 0
  4640.4     .08       0  4751.4     .16       0  4963.8     .12       0
    5001     .07       0    5007     .12       0  5259.9     .08       0
Bank Sta=4996.5,5024.1
XS Rating Curve= 0 ,0
Exp/Cntr=0.3,0.1

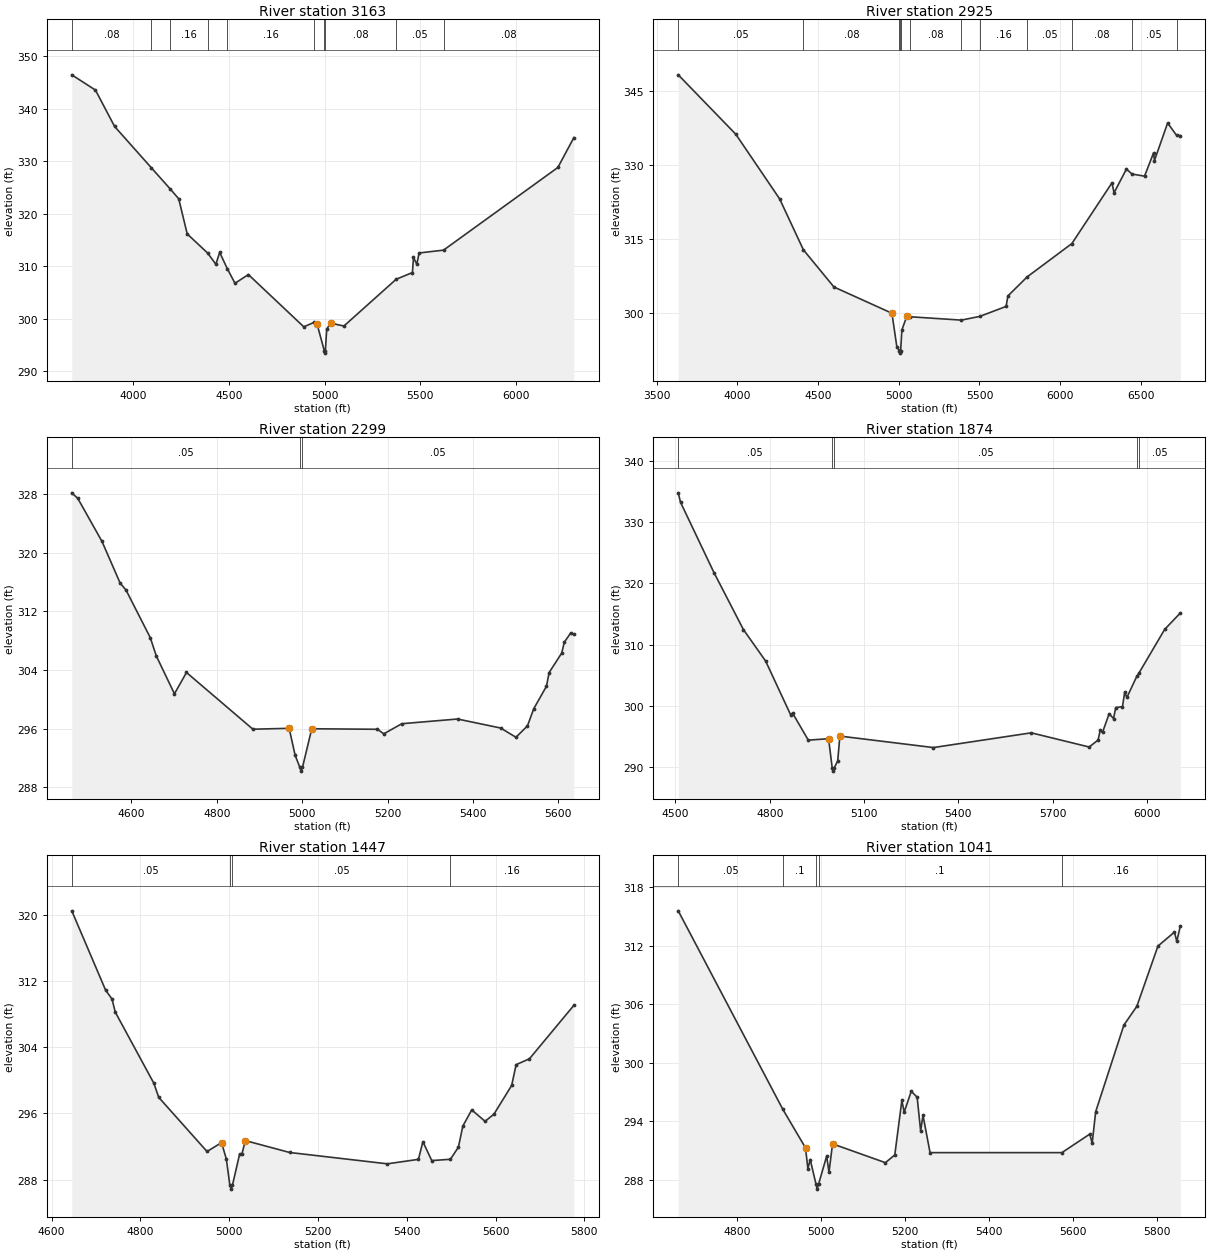
Type RM Length L Ch R = 1 ,3163    ,238,238,238
BEGIN DESCRIPTION:
COPPER CREEK 7.0
END DESCRIPTION:
XS GIS Cut Line= 3
      3632675.52     10512324.29      3632642.97     10510653.24
      3632241.48     10509785.15
#Sta/Elev= 30
  3677.2  346.42  3801.3  343.51  3901.3  336.59  4093.7  328.72    4192  324.71
  4236.9  322.82  4281.4  316.13  4388.4  312.48  4431.4  310.35  4451.4  312.61
  4491.4  309.49  4531.5  306.73  4601.5  308.39  4891.5  298.44  4947.2  299.31
  4961.5   298.9  4998.6  293.93  5001.3  293.43  5004.6  293.93  5011.6  297.99
  5031.6  299.15  5101.6  298.59  5374.9  307.49  5460.2  308.77  5465.7  311.64
  5483.1  310.37  5495.2   312.5    5623  313.04  6221.4  328.78    6305  334.46
#Mann= 10 ,-1 , 0
  3677.2     .08       0  4093.7     .05       0    4192     .16       0
  4388.4     .08       0  4491.4     .16       0  4947.2     .08       0
  4998.6     .07       0  5004.6     .08       0  5374.9     .05       0
    5623     .08       0
Bank Sta=4961.5,5031.6
XS Rating Curve= 0 ,0
Exp/Cntr=0.3,0.1

Type RM Length L Ch R = 1 ,2925    ,626,626,626
BEGIN DESCRIPTION:
COPPER CREEK 6.0
END DESCRIPTION:
XS GIS Cut Line= 3
      3633185.49     10512269.95      3632849.13       10510816.
      3633044.45     10509210.08
#Sta/Elev= 30
  3633.9  348.34  3990.3  336.27  4261.9  323.13  4409.2  312.77  4598.5  305.21
  4957.7  299.88  4988.5  292.96  5004.3  292.29  5005.6  292.27  5008.3  291.77
  5011.6  292.27  5019.3  296.48  5050.1   299.3  5070.3  299.16  5387.9  298.48
  5502.3  299.24  5664.8  301.26  5676.1   303.4  5795.1  307.26  6072.2  314.04
  6320.8  326.39  6333.6  324.35  6410.2  329.19  6444.6  328.18  6522.3  327.74
  6578.7   332.5  6583.7  330.91  6665.4  338.54  6720.8  336.04    6744  335.99
#Mann= 12 ,-1 , 0
  3633.9     .05       0  4409.2     .08       0  5004.3     .05       0
  5005.6     .07       0  5011.6     .05       0  5070.3     .08       0
  5387.9     .05       0  5502.3     .16       0  5795.1     .05       0
  6072.2     .08       0  6444.6     .05       0  6720.8     .08       0
Bank Sta=4957.7,5050.1
XS Rating Curve= 0 ,0
Exp/Cntr=0.3,0.1

Type RM Length L Ch R = 1 ,2299    ,425,425,425
BEGIN DESCRIPTION:
COPPER CREEK 5.0
END DESCRIPTION:
XS GIS Cut Line= 3
      3633849.64     10511260.21      3633449.61     10510860.19
      3633099.58     10510360.15
#Sta/Elev= 30
  4460.3  328.18  4474.5  327.41    4531  321.56  4573.5  315.88  4587.6  314.89
  4644.2  308.42  4658.3  305.93  4700.8  300.76    4729  303.67  4884.6  295.93
  4969.5  296.05  4983.6  292.35  4994.7  290.71  4997.5  290.21  5000.7  290.71
  5022.5  295.99  5176.4  295.92  5191.2   295.3  5233.5  296.68  5363.9  297.32
    5465  296.09  5500.8  294.83  5527.8  296.39  5542.6  298.74  5572.3  301.79
  5578.4  303.65    5608  306.32  5614.1  307.81  5628.9  309.04  5636.4  308.91
#Mann= 3 ,-1 , 0
  4460.3     .05       0  4994.7     .03       0  5000.7     .05       0
Bank Sta=4969.5,5022.5
XS Rating Curve= 0 ,0
Exp/Cntr=0.3,0.1

Type RM Length L Ch R = 1 ,1874    ,427,427,427
BEGIN DESCRIPTION:
COPPER CREEK 4.0
END DESCRIPTION:
XS GIS Cut Line= 3
      3634149.62      10511160.2      3633849.61     10510760.19
      3633099.61     10509960.19
#Sta/Elev= 30
    4509  334.74  4516.3   333.2  4622.6  321.75  4716.3  312.46  4787.1  307.32
  4866.3  298.59  4872.6  298.85  4922.6  294.45  4987.1  294.68  4998.7   289.9
  5001.5   289.4  5004.7   289.9  5016.1  291.07    5023  295.11  5320.4  293.24
  5631.6  295.64  5815.7  293.33    5844  294.46  5850.9  296.02  5858.2  295.72
  5879.2  298.74  5893.4  297.97  5900.2  299.75  5921.7  299.91  5928.6  302.21
  5935.9  301.42    5967  304.82  5973.3  305.31    6056   312.5  6105.6  315.16
#Mann= 5 ,-1 , 0
    4509     .05       0  4998.7     .03       0  5004.7     .05       0
    5967     .12       0  5973.3     .05       0
Bank Sta=4987.1,5023
XS Rating Curve= 0 ,0
Exp/Cntr=0.3,0.1

Type RM Length L Ch R = 1 ,1447    ,406,406,406
BEGIN DESCRIPTION:
COPPER CREEK 3.0
END DESCRIPTION:
XS GIS Cut Line= 3
      3634349.61     10510860.18      3634199.61     10510510.19
      3634199.61     10509760.17
#Sta/Elev= 30
  4645.4   320.5  4721.6  310.91  4736.1  309.83  4743.3  308.26  4830.3  299.65
  4841.2  297.95    4950   291.4  4982.7  292.47  4993.5   290.5  5001.4  287.35
  5004.2  286.85  5007.4  287.35  5023.5   291.1  5028.7   291.1  5036.2  292.72
  5136.2  291.28  5356.2  289.91  5426.2  290.45  5436.2  292.59  5456.2   290.3
  5498.2  290.46  5516.2  291.92  5526.2  294.48  5546.2  296.43  5576.2  295.05
  5596.2  295.91  5636.2  299.39  5646.2   301.9  5676.2  302.61  5776.2  309.07
#Mann= 4 ,-1 , 0
  4645.4     .05       0  5001.4     .03       0  5007.4     .05       0
  5498.2     .16       0
Bank Sta=4982.7,5036.2
XS Rating Curve= 0 ,0
Exp/Cntr=0.3,0.1

Type RM Length L Ch R = 1 ,1041    ,424,424,424
BEGIN DESCRIPTION:
COPPER CREEK 2.0
END DESCRIPTION:
XS GIS Cut Line= 3
      3634599.61     10510760.21      3634599.61     10510460.19
      3634199.59     10509660.15
#Sta/Elev= 30
  4660.3  315.58  4909.3  295.23  4963.1   291.3  4968.7  289.17  4974.3   290.1
  4988.1  287.57  4990.8  287.07  4994.1  287.57  5013.4  290.45    5019   288.8
  5027.4  291.71  5153.2  289.78  5175.5  290.57  5192.3  296.15  5197.9  294.96
  5214.7  297.09  5228.7  296.49    5237  293.04  5242.6  294.63  5259.4  290.81
  5573.1  290.81  5639.5  292.71  5645.1  291.77  5653.5  295.01  5720.6  303.88
  5751.3  305.79  5801.6  311.97  5840.8   313.4  5846.4  312.46  5854.8  314.02
#Mann= 5 ,-1 , 0
  4660.3     .05       0  4909.3      .1       0  4988.1     .03       0
  4994.1      .1       0  5573.1     .16       0
Bank Sta=4963.1,5027.4
XS Rating Curve= 0 ,0
Exp/Cntr=0.3,0.1

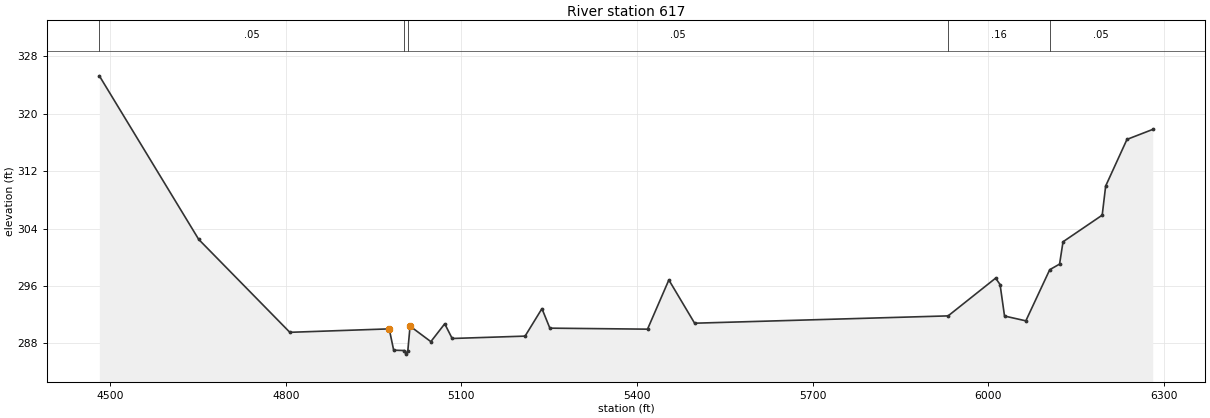
Type RM Length L Ch R = 1 ,617     ,0,0,0
BEGIN DESCRIPTION:
COPPER CREEK 1.0
END DESCRIPTION:
XS GIS Cut Line= 3
      3634649.59     10510910.21      3634999.61     10510560.19
      3634299.63     10509460.23
#Sta/Elev= 30
  4481.7  325.29  4651.4  302.49    4807  289.54  4976.7  290.02  4984.3  287.05
  5002.5     287  5005.2   286.5  5008.5     287  5012.3   290.4  5047.8  288.24
  5071.5  290.73  5084.2  288.68  5208.7  289.01  5237.5  292.84    5251  290.12
  5417.8  289.98  5454.2  296.84  5498.2  290.81  5931.1  291.83  6012.2  297.09
  6019.8   296.2  6027.4  291.81  6063.8  291.14  6104.6  298.27  6121.4  299.05
  6127.3  302.16  6194.2  305.87  6200.1  309.93  6236.5  316.43  6280.5  317.82
#Mann= 5 ,-1 , 0
  4481.7     .05       0  5002.5     .03       0  5008.5     .05       0
  5931.1     .16       0  6104.6     .05       0
Bank Sta=4976.7,5012.3
XS Rating Curve= 0 ,0
Exp/Cntr=0.3,0.1

Chan Stop Cuts=-1
Use User Specified Reach Order=0
Composite Channel Slope=5