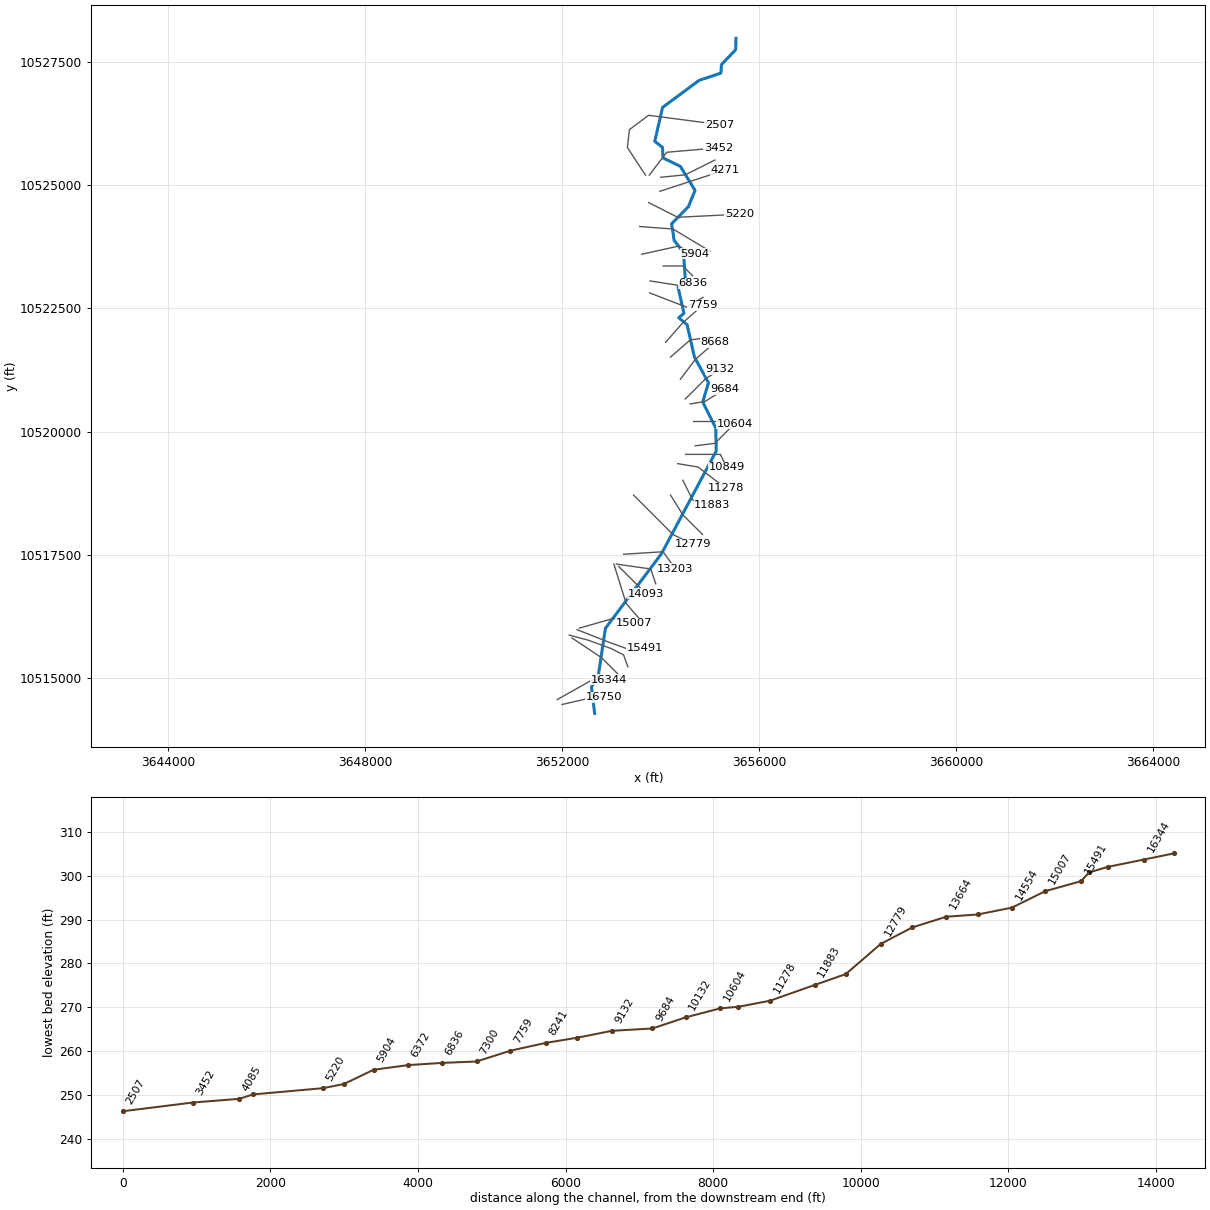
--- COW SLASH CREEK.prj (project) ---

Proj Title=COW SLASH CREEK Base Level Engineering
Current Plan=p01
Default Exp/Contr=0.3,0.1
English Units
Geom File=g01
Flow File=f01
Plan File=p01
Y Axis Title=Elevation
X Axis Title(PF)=Main Channel Distance
X Axis Title(XS)=Station
BEGIN DESCRIPTION:
COW SLASH CREEK
END DESCRIPTION:
DSS Export Rating Curves= 0
DSS Export Rating Curve Sorted= 0
DSS Export Volume Flow Curves= 0
DXF OffsetX= 0
DXF OffsetY= 0
DXF ScaleX= 1
DXF ScaleY= 10

--- COW SLASH CREEK.p01 (plan) ---

Plan Title=Multiple Run
Short Identifier=Multiple
Geom File=g01
Flow File=f01
Subcritical Flow
K Sum by GR= 0
Std Step Tol= 0.01
Critical Tol= 0.01
Num of Std Step Trials= 20
Max Error Tol= 0.3
Flow Tol Ratio= 0.001
Split Flow NTrial= 30
Split Flow Tol= 0.02
Split Flow Ratio= 0.02
Log Output Level= 0
Friction Slope Method= 1
Unsteady Friction Slope Method= 2
Unsteady Bridges Friction Slope Method= 1
Parabolic Critical Depth
Global Vel Dist=  1 , 1 , 1
Global Log Level= 0
CheckData=True
Encroach Param= -1, 0, 0, 0
BEGIN DESCRIPTION:
Multiple Run
END DESCRIPTION:

--- COW SLASH CREEK.f01 (steady flow) ---

Flow Title=Multiple
Program Version=4.10
Number of Profiles= 7
Profile Names=10-year,25-year,50-year,1pct_min,100-year,1pct_plu,500-year
River Rch & RM=COW SLASH CREEK,Reach-1         ,16750
     855    1184    1460    1322    1788    2417    2692
River Rch & RM=COW SLASH CREEK,Reach-1         ,10604
    1333    1887    2362    2165    2929    3961    4529
River Rch & RM=COW SLASH CREEK,Reach-1         ,10132
    1333    1887    2362    2165    2929    3961    4529
River Rch & RM=COW SLASH CREEK,Reach-1         ,8668
    1427    2018    2523    2310    3125    4226    4818
Boundary for River Rch & Prof#=COW SLASH CREEK,Reach-1         , 1
Up Type= 0
Dn Type= 3
Dn Slope=0.007
Boundary for River Rch & Prof#=COW SLASH CREEK,Reach-1         , 2
Up Type= 0
Dn Type= 3
Dn Slope=0.007
Boundary for River Rch & Prof#=COW SLASH CREEK,Reach-1         , 3
Up Type= 0
Dn Type= 3
Dn Slope=0.007
Boundary for River Rch & Prof#=COW SLASH CREEK,Reach-1         , 4
Up Type= 0
Dn Type= 3
Dn Slope=0.007
Boundary for River Rch & Prof#=COW SLASH CREEK,Reach-1         , 5
Up Type= 0
Dn Type= 3
Dn Slope=0.007
Boundary for River Rch & Prof#=COW SLASH CREEK,Reach-1         , 6
Up Type= 0
Dn Type= 3
Dn Slope=0.007
Boundary for River Rch & Prof#=COW SLASH CREEK,Reach-1         , 7
Up Type= 0
Dn Type= 3
Dn Slope=0.007
DSS Import GetInterval= 0
DSS Import GetPeak= 0
DSS Import FillOption= 0

--- COW SLASH CREEK.g01 (geometry) ---

Geom Title=Existing Conditions
Program Version=4.10

River Reach=COW SLASH CREEK ,Reach-1
Reach XY= 30
       3652659.5       10514280.      3652595.25       10514812.
        3652736.       10515062.       3652878.5       10516006.
      3654016.75       10517522.        3655128.       10519606.
       3655117.5       10520074.       3654853.5       10520601.
       3654969.5       10520990.      3654684.75       10521513.
        3654535.       10522170.      3654365.25       10522310.
      3654472.25       10522400.      3654351.75       10522930.
      3654498.25       10523106.      3654462.25       10523640.
        3654274.       10523877.       3654221.5       10524215.
       3654564.5       10524567.        3654697.       10524894.
      3654398.75       10525382.      3654047.25       10525553.
       3654036.5       10525769.      3653879.75       10525890.
       3654037.5       10526577.       3654780.5       10527128.
        3655222.       10527274.      3655233.25       10527448.
       3655521.5       10527749.       3655527.5       10527980.

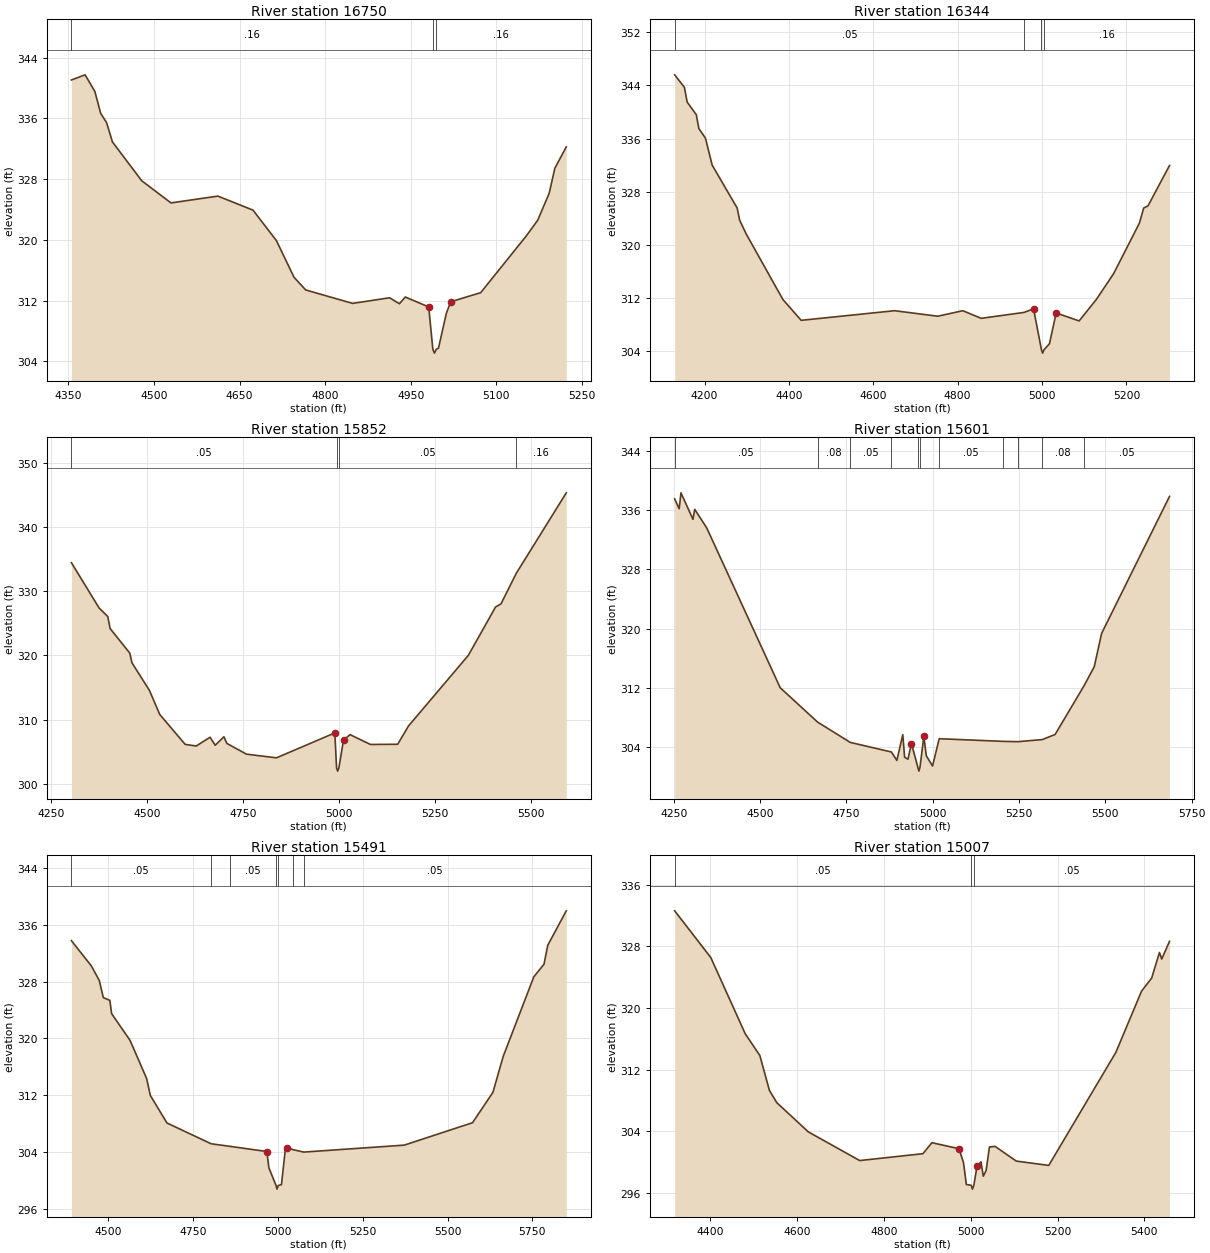
Type RM Length L Ch R = 1 ,16750   ,406,406,406
BEGIN DESCRIPTION:
COW SLASH CREEK 30.0
END DESCRIPTION:
XS GIS Cut Line= 3
      3651999.58     10514460.18      3652649.61     10514610.19
       3652849.6     10514610.19
#Sta/Elev= 30
  4355.3  341.05  4379.3  341.73  4396.4  339.54  4406.6  336.65  4416.9  335.44
  4427.2  332.89  4478.5  327.78  4529.8  324.86  4611.9  325.76  4673.5  323.91
  4714.5   319.9  4745.3  315.08  4765.8   313.4  4847.9  311.63  4912.9  312.37
    4930  311.58  4940.3  312.47  4981.4  311.16  4988.6  305.58  4991.4  305.08
  4994.6  305.58  4998.5  305.74  5012.2   310.3  5019.8  311.84  5072.4  313.04
  5152.4  320.52  5172.4  322.59  5192.4  326.12  5202.4  329.43  5222.4  332.24
#Mann= 3 ,-1 , 0
  4355.3     .16       0  4988.6     .07       0  4994.6     .16       0
Bank Sta=4981.4,5019.8
XS Rating Curve= 0 ,0
Exp/Cntr=0.3,0.1

Type RM Length L Ch R = 1 ,16344   ,492,492,492
BEGIN DESCRIPTION:
COW SLASH CREEK 29.0
END DESCRIPTION:
XS GIS Cut Line= 3
      3651899.58     10514560.17      3652699.61     10515010.19
      3652949.65     10514960.18
#Sta/Elev= 30
  4129.2   345.6  4152.2  343.73  4158.9  341.49  4180.5  339.59  4186.6  337.51
  4202.2  336.06  4218.1     332  4277.4  325.53  4283.2  323.71  4299.1  321.59
  4385.8  311.75  4429.1  308.62  4650.3  310.07  4752.9  309.24  4812.2  310.07
  4855.6  308.92  4957.1  309.81  4979.9  310.35  4998.5  304.18  5001.3  303.68
  5004.5  304.18  5017.5  305.09  5033.4  309.73  5087.9  308.53  5128.7  311.77
  5169.5  315.64  5230.7  323.26  5240.9  325.54  5251.1  325.86  5302.1  331.95
#Mann= 4 ,-1 , 0
  4129.2     .05       0  4957.1     .16       0  4998.5     .07       0
  5004.5     .16       0
Bank Sta=4979.9,5033.4
XS Rating Curve= 0 ,0
Exp/Cntr=0.3,0.1

Type RM Length L Ch R = 1 ,15852   ,251,251,251
BEGIN DESCRIPTION:
COW SLASH CREEK 28.0
END DESCRIPTION:
XS GIS Cut Line= 3
      3652199.64     10515810.17      3652799.61     10515410.19
      3653199.64     10515010.16
#Sta/Elev= 30
  4303.8  334.44  4375.9  327.38  4398.4  326.06  4404.4   324.2  4455.5  320.37
  4461.5  318.83  4506.6  314.58  4533.6  310.81  4599.7  306.16  4628.3  305.91
  4664.3  307.27  4677.8  306.03  4700.4  307.35  4707.9  306.32    4759  304.64
  4837.1  304.07  4988.8  307.95  4993.3   302.5  4996.1     302  4999.3   302.5
  5011.4  306.85  5028.4  307.68  5081.4  306.15  5152.2  306.18  5180.4  309.03
    5336  320.02  5406.7  327.54  5420.9  328.03  5460.8   332.8  5590.6  345.31
#Mann= 4 ,-1 , 0
  4303.8     .05       0  4993.3     .03       0  4999.3     .05       0
  5460.8     .16       0
Bank Sta=4988.8,5011.4
XS Rating Curve= 0 ,0
Exp/Cntr=0.3,0.1

Type RM Length L Ch R = 1 ,15601   ,110,110,110
BEGIN DESCRIPTION:
Mapping XS e858adaa
END DESCRIPTION:
XS GIS Cut Line= 5
      3652144.51      10515869.3      3652537.33     10515762.96
      3652993.06     10515595.86      3653246.97     10515465.65
      3653333.68       10515225.
#Sta/Elev= 30
  4252.4  337.52  4265.5  336.19  4270.7  338.34  4305.4  334.76  4310.5  336.11
  4345.2  333.61  4558.1  312.01  4666.3  307.37  4761.1  304.62    4880  303.33
  4896.1  302.19  4913.2  305.67  4918.5  302.63  4928.1  302.35  4938.4  304.45
    4957  301.24  4959.8  300.74    4963  301.24  4974.2  305.45  4981.3  302.82
  4999.4  301.43  5018.7  305.12  5203.9  304.76  5246.8  304.72  5317.3     305
  5354.4  305.69  5438.6   312.3  5467.8  314.84  5489.1  319.34  5685.9  337.86
#Mann= 11 ,-1 , 0
  4252.4     .05       0  4666.3     .08       0  4761.1     .05       0
    4880     .08       0    4957     .07       0    4963     .08       0
  5018.7     .05       0  5203.9     .08       0  5246.8     .05       0
  5317.3     .08       0  5438.6     .05       0
Bank Sta=4938.4,4974.2
XS Rating Curve= 0 ,0
Exp/Cntr=0.3,0.1

Type RM Length L Ch R = 1 ,15491   ,484,484,484
BEGIN DESCRIPTION:
COW SLASH CREEK 27.0
END DESCRIPTION:
XS GIS Cut Line= 6
      3652302.93     10515977.81      3652676.22      10515832.4
      3652960.51     10515719.55      3653281.69     10515604.54
       3653353.3     10515571.98      3653685.01     10515600.17
#Sta/Elev= 30
  4390.8  333.76  4449.7  330.19  4473.1  328.13  4484.9  325.73  4504.1  325.34
  4509.4  323.47  4563.8   319.7  4612.6  314.33  4623.6  311.93  4672.6  308.06
  4802.9  305.13  4859.8  304.76  4967.2  304.04  4973.1  301.74  4994.4  299.24
  4997.1  298.74  5000.4  299.24  5010.2  299.38    5021  304.09  5027.1   304.6
  5045.1  304.29  5075.9  303.96  5372.2  304.94  5573.6   308.1  5633.8  312.39
  5663.9  317.43  5754.3  328.66  5784.4  330.44  5795.3  333.09    5850  337.96
#Mann= 7 ,-1 , 0
  4390.8     .05       0  4802.9     .08       0  4859.8     .05       0
  4994.4     .03       0  5000.4     .05       0  5045.1     .08       0
  5075.9     .05       0
Bank Sta=4967.2,5027.1
XS Rating Curve= 0 ,0
Exp/Cntr=0.3,0.1

Type RM Length L Ch R = 1 ,15007   ,453,453,453
BEGIN DESCRIPTION:
COW SLASH CREEK 26.0
END DESCRIPTION:
XS GIS Cut Line= 3
      3652349.61     10516010.19      3653049.61     10516210.19
      3653449.59     10516110.19
#Sta/Elev= 30
  4317.6  332.61  4400.8  326.55  4480.1  316.66  4513.9  313.82    4536  309.28
  4552.9   307.7  4625.7   303.9    4744  300.18  4889.6  301.07  4910.4   302.5
  4972.8  301.72  4983.2  299.91  4989.7  297.07    5001  296.97  5003.8  296.47
    5007  296.97  5014.4  299.48  5023.5  300.01  5028.7  298.15  5035.2  298.88
    5043  301.95  5055.9  302.02  5104.9  300.11  5179.6  299.55  5334.2  314.22
  5393.5  322.19  5416.7  323.87  5434.7   327.2  5439.9  326.35  5457.9  328.65
#Mann= 3 ,-1 , 0
  4317.6     .05       0    5001     .03       0    5007     .05       0
Bank Sta=4972.8,5014.4
XS Rating Curve= 0 ,0
Exp/Cntr=0.3,0.1

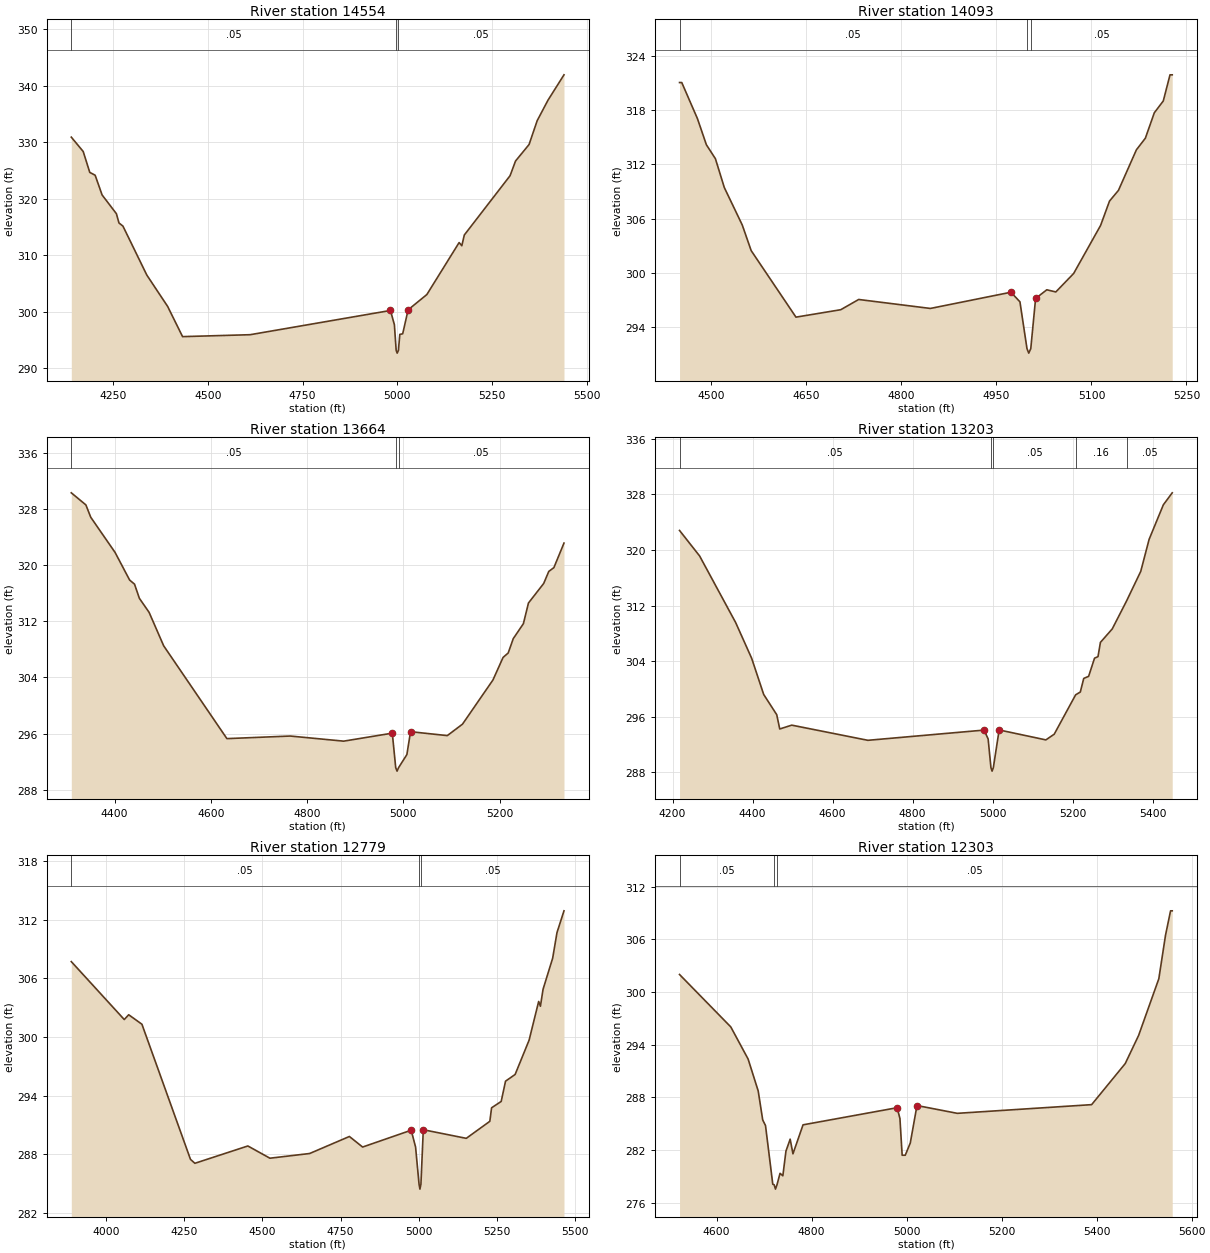
Type RM Length L Ch R = 1 ,14554   ,461,461,461
BEGIN DESCRIPTION:
COW SLASH CREEK 25.0
END DESCRIPTION:
XS GIS Cut Line= 3
       3653049.6      10517310.2      3653299.61     10516510.19
      3653599.58     10516160.22
#Sta/Elev= 30
  4140.3  330.94  4171.7   328.4    4189   324.7  4203.2   324.2  4221.5  320.71
  4259.2  317.39    4266  315.75  4276.5  315.19  4339.4  306.53  4394.4  300.97
  4433.7  295.63  4611.8  295.97  4981.8  300.26  4992.2  297.75  4996.9  293.21
  4999.6  292.71  5002.9  293.21  5006.5  296.03  5014.1  296.13  5028.4  300.37
  5077.8  303.08  5162.9  312.28    5170  311.72  5176.6  313.62  5297.3  324.12
  5311.6  326.71  5347.3  329.63  5368.7  333.85  5397.2  337.48  5439.4  341.97
#Mann= 3 ,-1 , 0
  4140.3     .05       0  4996.9     .03       0  5002.9     .05       0
Bank Sta=4981.8,5028.4
XS Rating Curve= 0 ,0
Exp/Cntr=0.3,0.1

Type RM Length L Ch R = 1 ,14093   ,429,429,429
BEGIN DESCRIPTION:
COW SLASH CREEK 24.0
END DESCRIPTION:
XS GIS Cut Line= 3
      3653149.62     10517260.18      3653549.61     10516860.19
      3653699.61     10516710.19
#Sta/Elev= 30
  4449.7  321.02  4453.2  321.02    4478  317.03  4492.1  314.15  4506.3  312.62
  4520.4  309.43  4548.7   305.3  4562.8  302.47  4633.5  295.13  4704.2  295.95
  4732.5  297.08  4845.7  296.09  4972.9  297.88  4987.1  296.82  4998.2  291.66
    5001  291.16  5004.2  291.66  5011.8  297.19  5029.5  298.15  5043.7  297.91
  5071.9  299.95  5114.4  305.25  5128.5  307.94  5142.6  309.12  5170.9  313.59
  5185.1  314.88  5199.2  317.68  5213.4  318.99    5224  321.87  5227.5  321.87
#Mann= 3 ,-1 , 0
  4449.7     .05       0  4998.2     .03       0  5004.2     .05       0
Bank Sta=4972.9,5011.8
XS Rating Curve= 0 ,0
Exp/Cntr=0.3,0.1

Type RM Length L Ch R = 1 ,13664   ,461,461,461
BEGIN DESCRIPTION:
COW SLASH CREEK 23.0
END DESCRIPTION:
XS GIS Cut Line= 3
      3653099.61     10517310.19      3653799.61     10517210.19
       3653899.6     10516910.22
#Sta/Elev= 30
  4310.2  330.29  4340.5  328.57  4350.6  326.81  4401.1   321.8  4431.4  317.86
  4441.5  317.28  4451.6  315.26  4471.8  313.26  4502.1  308.49  4633.4  295.27
  4764.8  295.64  4875.9  294.91  4976.9  296.05    4984  291.14  4986.8  290.64
    4990  291.14  5007.2     293  5014.8  296.26  5091.1   295.7  5122.7  297.33
    5186  303.63    5207  306.84  5217.6  307.47  5228.1  309.51  5249.2  311.65
  5259.7  314.59  5291.4  317.38  5301.9  319.09  5312.5  319.63  5333.5  323.13
#Mann= 3 ,-1 , 0
  4310.2     .05       0    4984     .03       0    4990     .05       0
Bank Sta=4976.9,5014.8
XS Rating Curve= 0 ,0
Exp/Cntr=0.3,0.1

Type RM Length L Ch R = 1 ,13203   ,424,424,424
BEGIN DESCRIPTION:
COW SLASH CREEK 22.0
END DESCRIPTION:
XS GIS Cut Line= 3
      3653249.63     10517510.19      3654049.61     10517560.19
      3654299.63     10517210.16
#Sta/Elev= 30
  4217.3  322.79  4267.4  319.13  4357.6  309.55  4397.6  304.41  4427.7  299.21
  4460.3   296.3  4467.8  294.25  4497.8   294.8  4688.2  292.62  4978.8  294.09
  4988.8   292.8  4995.8  288.69  4998.6  288.19  5001.8  288.69  5016.3  294.11
  5133.1  292.68    5154   293.5  5207.5  299.16  5219.2  299.56  5227.8  301.52
    5240  301.82  5254.8  304.43  5263.4  304.65  5269.5   306.7    5299  308.63
  5334.8  312.65  5370.3  316.91  5391.2  321.51  5426.8  326.48    5449   328.2
#Mann= 5 ,-1 , 0
  4217.3     .05       0  4995.8     .03       0  5001.8     .05       0
  5207.5     .16       0  5334.8     .05       0
Bank Sta=4978.8,5016.3
XS Rating Curve= 0 ,0
Exp/Cntr=0.3,0.1

Type RM Length L Ch R = 1 ,12779   ,476,476,476
BEGIN DESCRIPTION:
COW SLASH CREEK 21.0
END DESCRIPTION:
XS GIS Cut Line= 3
       3653449.6      10518710.2      3654249.61     10517910.19
      3654649.61     10517710.19
#Sta/Elev= 30
  3887.4  307.71  4057.1  301.79  4071.3  302.28  4113.7  301.31  4269.3   287.5
  4283.4   287.1  4453.1  288.87  4523.8  287.62  4651.1   288.1  4778.4  289.84
  4820.8  288.76  4976.4  290.48  4990.5  288.76  5001.6  284.96  5004.4  284.46
  5007.6  284.96  5015.2  290.53  5152.9  289.65  5228.4  291.39    5234  292.77
  5264.8  293.42  5278.7  295.49  5309.5  296.18  5354.2  299.68  5384.9  303.64
  5390.5  303.15  5398.9  304.88  5429.7  308.06  5443.6  310.68    5466   312.9
#Mann= 3 ,-1 , 0
  3887.4     .05       0  5001.6     .03       0  5007.6     .05       0
Bank Sta=4976.4,5015.2
XS Rating Curve= 0 ,0
Exp/Cntr=0.3,0.1

Type RM Length L Ch R = 1 ,12303   ,420,420,420
BEGIN DESCRIPTION:
COW SLASH CREEK 20.0
END DESCRIPTION:
XS GIS Cut Line= 3
      3654199.63     10518710.16      3654449.61     10518310.19
      3654849.57     10517910.22
#Sta/Elev= 30
  4521.8     302  4629.7  296.03  4666.2  292.37  4687.4  288.74  4696.9  285.44
  4702.8   284.8  4718.1  278.12    4721  278.06  4723.8  277.56    4727  278.06
  4733.4  279.36  4739.3  279.08  4745.8  281.88  4754.7  283.25  4760.6  281.58
  4781.8  284.88  4979.9  286.83  4985.8  285.61  4990.5  281.42    4997  281.42
  5007.6  282.81  5021.7  287.08  5106.6  286.19  5389.4  287.18  5460.2  291.86
  5488.4  295.07  5530.9  301.52    5545  306.48  5555.6  309.25  5559.1  309.25
#Mann= 3 ,-1 , 0
  4521.8     .05       0    4721     .03       0    4727     .05       0
Bank Sta=4979.9,5021.7
XS Rating Curve= 0 ,0
Exp/Cntr=0.3,0.1

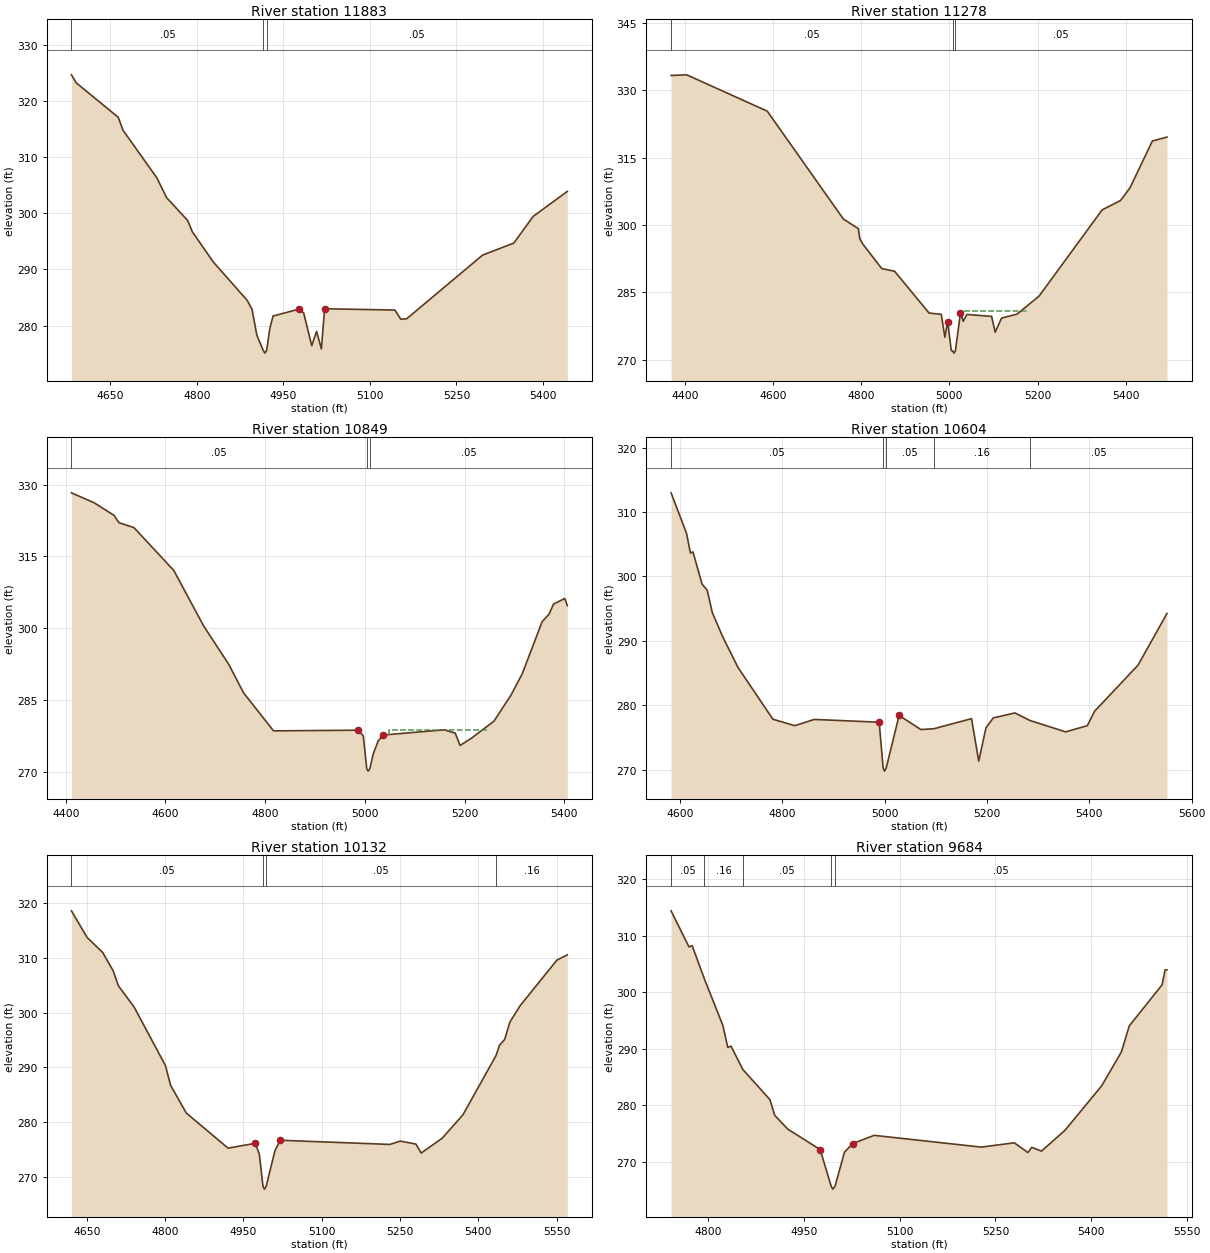
Type RM Length L Ch R = 1 ,11883   ,605,605,605
BEGIN DESCRIPTION:
COW SLASH CREEK 19.0
END DESCRIPTION:
XS GIS Cut Line= 3
      3654449.61     10519010.19      3654649.61     10518610.19
      3655049.58      10518510.2
#Sta/Elev= 30
  4582.7   324.7  4591.1  323.26  4663.8  317.13  4672.1  314.82  4730.8  306.32
  4747.6  302.81    4784  298.75  4792.3  296.71  4828.7  291.32  4887.4  284.49
  4895.8  282.86  4904.1  278.25  4915.1  275.59  4917.9  275.09  4921.1  275.59
  4926.5  279.47  4932.1   281.7  4976.8  282.92  4985.2  282.27  4999.2  276.41
  5007.6  278.97  5015.9  275.84  5021.5     283  5143.3  282.77  5153.6  281.12
  5163.9  281.22  5295.3  292.56  5349.5  294.71    5383  299.46  5442.2  303.92
#Mann= 3 ,-1 , 0
  4582.7     .05       0  4915.1     .03       0  4921.1     .05       0
Bank Sta=4976.8,5021.5
XS Rating Curve= 0 ,0
Exp/Cntr=0.3,0.1

Type RM Length L Ch R = 1 ,11278   ,429,429,429
BEGIN DESCRIPTION:
COW SLASH CREEK 18.0
END DESCRIPTION:
XS GIS Cut Line= 3
      3654344.62     10519348.58      3654761.31     10519279.13
      3655315.75     10518849.44
#Sta/Elev= 30
  4369.1  333.32  4404.6  333.46  4587.1  325.37  4759.6  301.36  4793.6  299.21
  4796.8  296.98  4803.2  295.85  4846.6  290.32  4875.6  289.74  4953.9  280.42
  4981.5  280.14  4989.7  275.03    4996  278.54  5004.2  272.06  5007.5     272
  5010.2   271.5  5013.5     272    5025  280.43  5031.3  278.58  5039.5  280.11
  5095.6  279.68  5103.7  276.16  5118.2   279.3  5153.5  280.19  5203.3  284.21
  5346.1  303.39    5388  305.49  5409.3  308.31  5459.9  318.72    5493  319.61
#Mann= 3 ,-1 , 0
  4369.1     .05       0  5007.5     .03       0  5013.5     .05       0
#XS Ineff= 1 ,-1
 5027.27  5180.8  280.78
Permanent Ineff=
       F
Bank Sta=4996,5025
XS Rating Curve= 0 ,0
Exp/Cntr=0.3,0.1

Type RM Length L Ch R = 1 ,10849   ,245,245,245
BEGIN DESCRIPTION:
COW SLASH CREEK 17.0
END DESCRIPTION:
XS GIS Cut Line= 3
      3654504.32     10519536.07      3655212.33     10519536.07
      3655335.12     10519277.23
#Sta/Elev= 30
  4411.4  328.31  4456.7  326.24  4496.7  323.61  4506.7  322.06  4536.7  321.04
  4616.7  312.07  4676.7  300.44  4726.7  292.47  4756.7  286.47  4816.7  278.53
  4986.7  278.67  4996.7  277.45  5003.7  270.61  5006.4  270.11  5009.7  270.61
  5016.7  273.73  5026.7  276.45  5036.7  277.66  5159.1  278.75  5181.3  278.04
  5190.8  275.47  5213.5  276.99  5258.7  280.55  5292.8  285.98  5315.5  290.47
  5355.4  301.36  5369.4  302.95  5378.2  305.03  5400.9  306.22  5405.9  304.72
#Mann= 3 ,-1 , 0
  4411.4     .05       0  5003.7     .03       0  5009.7     .05       0
#XS Ineff= 1 ,-1
 5048.41 5248.18  278.79
Permanent Ineff=
       F
Bank Sta=4986.7,5036.7
XS Rating Curve= 0 ,0
Exp/Cntr=0.3,0.1

Type RM Length L Ch R = 1 ,10604   ,472,472,472
BEGIN DESCRIPTION:
COW SLASH CREEK 16.0
END DESCRIPTION:
XS GIS Cut Line= 3
      3654699.61     10519710.19      3655099.61     10519760.19
      3655499.61     10520160.19
#Sta/Elev= 30
  4582.9  312.99  4613.1  306.69  4620.7  303.63  4625.7  303.81  4643.4  298.81
  4653.4  297.87  4663.5  294.37  4683.7  290.64  4713.9  285.83  4781.9  277.82
  4824.8  276.82  4862.6  277.79  4989.5  277.36  4997.2  270.26  4999.9  269.76
  5003.2  270.26  5028.4  278.41  5070.9  276.22    5096  276.34  5169.9  277.91
    5184  271.32  5198.1  276.49  5212.3  278.02  5254.7   278.8  5283.9  277.63
  5353.7  275.86  5396.1  276.82  5410.3  279.06  5495.1  286.21  5551.7  294.24
#Mann= 5 ,-1 , 0
  4582.9     .05       0  4997.2     .03       0  5003.2     .05       0
    5096     .16       0  5283.9     .05       0
Bank Sta=4989.5,5028.4
XS Rating Curve= 0 ,0
Exp/Cntr=0.3,0.1

Type RM Length L Ch R = 1 ,10132   ,448,448,448
BEGIN DESCRIPTION:
COW SLASH CREEK 15.0
END DESCRIPTION:
XS GIS Cut Line= 3
      3654649.62     10520210.19      3654999.61     10520210.19
      3655599.62     10520210.19
#Sta/Elev= 30
  4620.5  318.61  4650.5  313.74  4680.5  310.97  4700.5  307.62  4710.5  304.88
  4740.5  301.02  4800.5  290.32  4810.5  286.67  4840.5  281.62  4920.5  275.19
    4973  276.08  4980.5  274.04  4987.5  268.19  4990.2  267.69  4993.5  268.19
  5010.5  274.77  5020.5  276.63  5230.5  275.87  5250.5  276.48  5280.5  275.93
  5290.5  274.29  5330.5  276.98  5370.5  281.28  5433.9  292.13  5440.5  293.99
  5450.5  295.08  5460.5  298.26  5480.5   301.3  5550.5  309.59  5570.5  310.56
#Mann= 4 ,-1 , 0
  4620.5     .05       0  4987.5     .03       0  4993.5     .05       0
  5433.9     .16       0
Bank Sta=4973,5020.5
XS Rating Curve= 0 ,0
Exp/Cntr=0.3,0.1

Type RM Length L Ch R = 1 ,9684    ,552,552,552
BEGIN DESCRIPTION:
COW SLASH CREEK 14.0
END DESCRIPTION:
XS GIS Cut Line= 3
       3654599.6     10520560.19      3654899.61     10520610.19
      3655299.57     10520860.17
#Sta/Elev= 30
  4742.6  314.38  4770.5  308.02  4775.6  308.22  4794.8  302.32  4823.7  294.09
  4831.3  290.22  4836.4  290.45  4854.9  286.32  4897.2     281  4904.8  278.21
  4925.1  275.79  4975.8  272.17  4993.1  265.67  4995.8  265.17  4999.1  265.67
  5013.8  271.68  5026.5  273.21  5060.3  274.68  5227.8   272.6  5279.6  273.36
  5300.9  271.64  5306.8  272.55  5322.1  271.89  5358.7  275.55  5416.4  283.45
  5447.1  289.42  5459.5  294.04  5510.8  301.29  5515.5  303.94  5518.4  303.94
#Mann= 5 ,-1 , 0
  4742.6     .05       0  4794.8     .16       0  4854.9     .05       0
  4993.1     .03       0  4999.1     .05       0
Bank Sta=4975.8,5026.5
XS Rating Curve= 0 ,0
Exp/Cntr=0.3,0.1

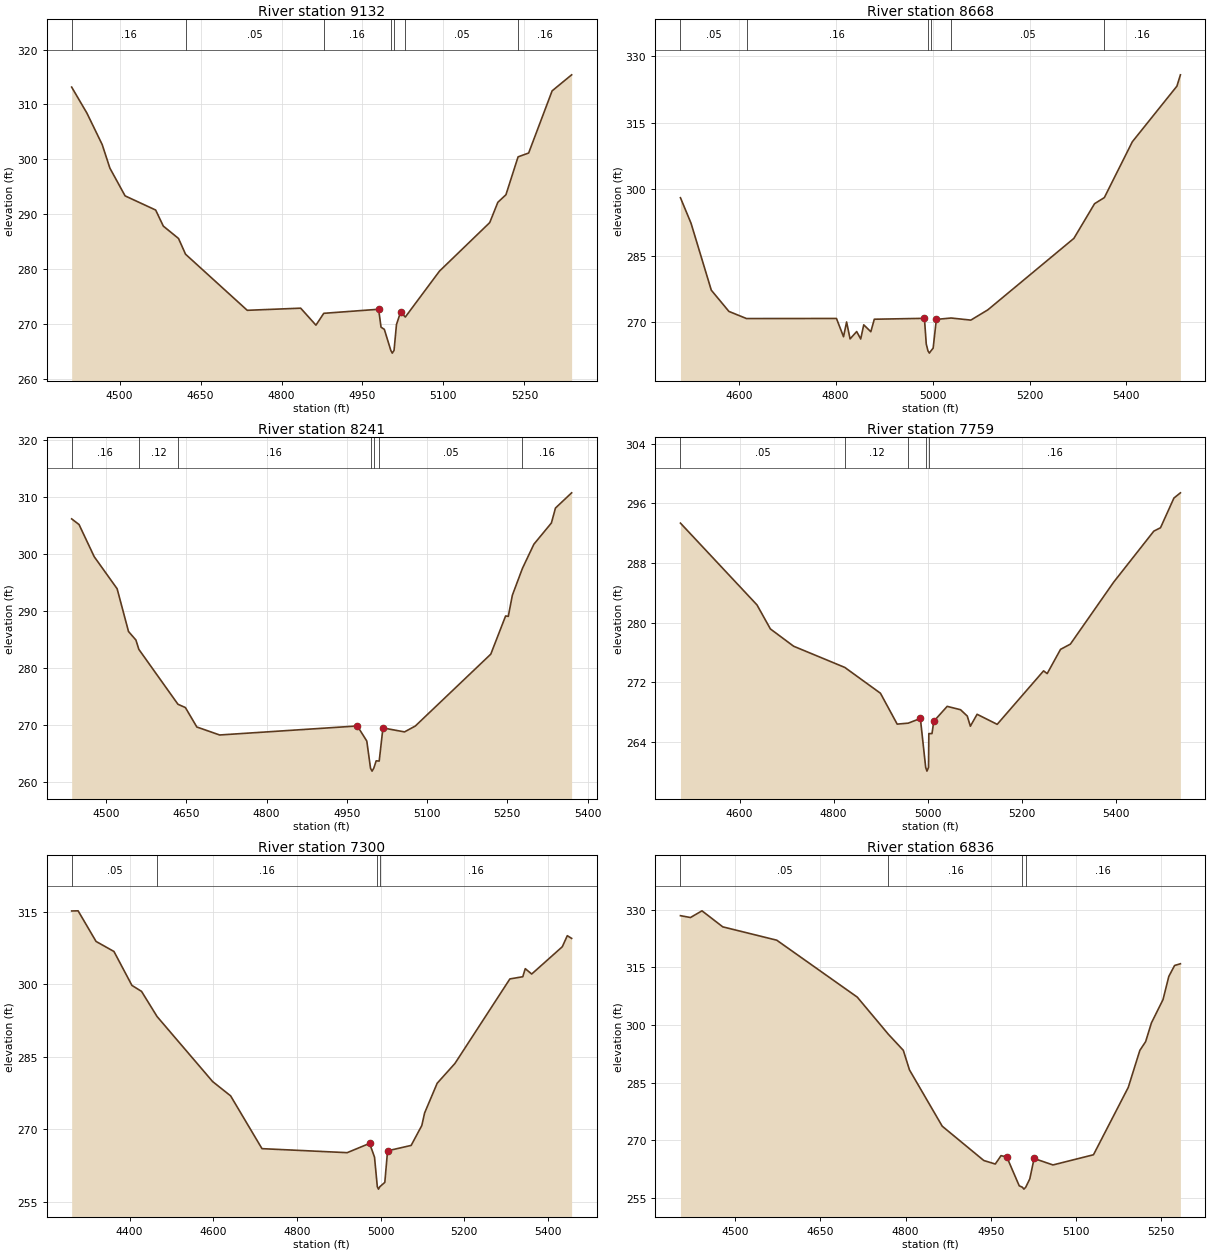
Type RM Length L Ch R = 1 ,9132    ,464,464,464
BEGIN DESCRIPTION:
COW SLASH CREEK 13.0
END DESCRIPTION:
XS GIS Cut Line= 3
      3654499.58     10520660.15      3654899.61     10521060.19
      3655199.62      10521260.2
#Sta/Elev= 30
  4411.2  313.15  4439.5   308.4  4467.8  302.66    4482  298.38  4510.2  293.31
  4566.8  290.73    4581   287.8  4609.2  285.54  4622.2  282.67  4736.5  272.44
  4835.5  272.83  4863.8  269.73  4878.3  271.89  4979.9  272.63  4984.4  269.36
  4990.5  268.97  5002.5  265.13  5005.2  264.63  5008.5  265.13    5013  269.84
  5020.5  272.09  5029.4  271.22  5092.6  279.58  5185.8  288.44  5200.8  292.14
  5215.8  293.52  5238.3  300.43  5257.9  301.13  5301.4  312.47  5337.5  315.39
#Mann= 7 ,-1 , 0
  4411.2     .16       0  4622.2     .05       0  4878.3     .16       0
  5002.5     .07       0  5008.5     .16       0  5029.4     .05       0
  5238.3     .16       0
Bank Sta=4979.9,5020.5
XS Rating Curve= 0 ,0
Exp/Cntr=0.3,0.1

Type RM Length L Ch R = 1 ,8668    ,427,427,427
BEGIN DESCRIPTION:
COW SLASH CREEK 12.0
END DESCRIPTION:
XS GIS Cut Line= 3
      3654399.58     10521060.15      3654699.61     10521460.19
      3655099.65     10521810.22
#Sta/Elev= 30
  4479.8  298.13  4501.7  292.35  4543.4  277.28  4579.8  272.48  4616.1  270.87
  4801.7  270.89  4816.3  266.77  4822.6   270.1  4829.8  266.28  4843.4  267.94
  4851.7  266.26    4858  269.45  4872.6   267.9  4879.8  270.72  4983.2  270.92
    4987   265.1  4990.6  263.57  4993.4  263.07  4996.6  263.57  5001.2  264.19
  5007.8  270.68  5038.3  270.99    5079  270.52  5114.1  272.84  5291.6  288.96
  5334.3  296.79  5354.4  298.16  5412.2  310.76  5504.2  323.31  5511.4  325.86
#Mann= 6 ,-1 , 0
  4479.8     .05       0  4616.1     .16       0  4990.6     .07       0
  4996.6     .16       0  5038.3     .05       0  5354.4     .16       0
Bank Sta=4983.2,5007.8
XS Rating Curve= 0 ,0
Exp/Cntr=0.3,0.1

Type RM Length L Ch R = 1 ,8241    ,482,482,482
BEGIN DESCRIPTION:
COW SLASH CREEK 11.0
END DESCRIPTION:
XS GIS Cut Line= 3
       3654199.6     10521510.18      3654599.61     10521860.19
      3654999.58     10521910.19
#Sta/Elev= 30
  4435.7  306.14  4449.5  305.15  4477.9   299.5  4520.7  293.88    4542  286.38
  4555.8  284.89  4561.3  283.25  4634.4  273.62  4648.3  273.04  4669.7  269.63
  4712.4  268.23  4969.7  269.81  4987.4  267.17  4994.4  262.39  4997.2  261.89
  5000.4  262.39    5005   263.7  5010.6  263.65  5017.6  269.47  5057.9  268.77
  5078.1   269.8  5219.2  282.41  5246.9  289.11  5251.9  289.04  5259.5  292.74
  5278.4  297.47  5299.8   301.7  5332.5  305.42  5340.1  308.04  5370.3  310.71
#Mann= 7 ,-1 , 0
  4435.7     .16       0  4561.3     .12       0  4634.4     .16       0
  4994.4     .07       0  5000.4     .16       0  5010.6     .05       0
  5278.4     .16       0
Bank Sta=4969.7,5017.6
XS Rating Curve= 0 ,0
Exp/Cntr=0.3,0.1

Type RM Length L Ch R = 1 ,7759    ,459,459,459
BEGIN DESCRIPTION:
COW SLASH CREEK 10.0
END DESCRIPTION:
XS GIS Cut Line= 3
      3654099.63     10521810.22      3654449.61     10522210.19
      3654849.63      10522560.2
#Sta/Elev= 30
  4474.3  293.34    4637  282.38  4665.5  279.16  4714.9  276.84  4823.7     274
  4899.5  270.54  4935.1   266.4  4958.6  266.53  4984.4  267.16  4995.7   260.6
  4998.4   260.1  5001.7   260.6  5002.4  265.13  5009.1  265.13  5012.9  266.78
  5041.4  268.78  5069.8  268.33  5084.1  267.48  5090.7  266.12    5105  267.72
  5147.7  266.37  5246.4  273.54    5254  273.17  5282.4  276.42  5303.3  277.12
  5395.4  285.43  5480.8  292.27    5495  292.72  5523.5   296.7  5537.3   297.4
#Mann= 5 ,-1 , 0
  4474.3     .05       0  4823.7     .12       0  4958.6     .16       0
  4995.7     .07       0  5001.7     .16       0
Bank Sta=4984.4,5012.9
XS Rating Curve= 0 ,0
Exp/Cntr=0.3,0.1

Type RM Length L Ch R = 1 ,7300    ,464,464,464
BEGIN DESCRIPTION:
COW SLASH CREEK 9.0
END DESCRIPTION:
XS GIS Cut Line= 3
      3653775.24     10522813.84      3654532.14     10522522.19
      3654858.56     10522723.59
#Sta/Elev= 30
  4261.7  315.16  4277.1  315.19    4320  308.86  4362.8  306.78  4405.7  299.77
  4428.7  298.53  4465.8  293.33  4598.6  279.88  4641.5  276.93  4716.5  266.01
  4920.1  265.18  4973.7   267.1  4985.4  264.25  4992.1  258.14  4994.9  257.64
  4998.1  258.14    5010  259.03  5016.6  265.56  5072.9  266.68  5098.4  270.79
  5105.1  273.39  5135.1  279.53  5177.6  283.63  5308.9  301.11  5339.7  301.56
  5345.6  303.23    5361  302.12  5434.1  307.76  5446.1  310.05  5456.4  309.49
#Mann= 4 ,-1 , 0
  4261.7     .05       0  4465.8     .16       0  4992.1     .07       0
  4998.1     .16       0
Bank Sta=4973.7,5016.6
XS Rating Curve= 0 ,0
Exp/Cntr=0.3,0.1

Type RM Length L Ch R = 1 ,6836    ,464,464,464
BEGIN DESCRIPTION:
COW SLASH CREEK 8.0
END DESCRIPTION:
XS GIS Cut Line= 3
      3653782.17      10523056.9      3654399.61     10522960.19
      3654649.59     10523010.19
#Sta/Elev= 30
  4403.8  328.45  4421.4  327.97  4441.7  329.71  4478.3  325.54  4573.3  322.07
    4715  307.26  4769.9  297.57    4796  293.43  4806.9  288.32  4864.5  273.69
  4937.7  264.76  4957.9  263.85    4968  266.03  4978.2  265.67    5000  258.19
  5005.5  257.82  5008.3  257.32  5011.5  257.82  5018.6  259.99  5026.2  265.29
  5059.4  263.61  5130.7  266.26  5191.9  283.78  5212.3  293.41  5222.5  295.69
  5232.7  300.57  5253.1  306.63  5263.3  312.66  5273.5   315.5  5283.7  315.94
#Mann= 4 ,-1 , 0
  4403.8     .05       0  4769.9     .16       0  5005.5     .07       0
  5011.5     .16       0
Bank Sta=4978.2,5026.2
XS Rating Curve= 0 ,0
Exp/Cntr=0.3,0.1

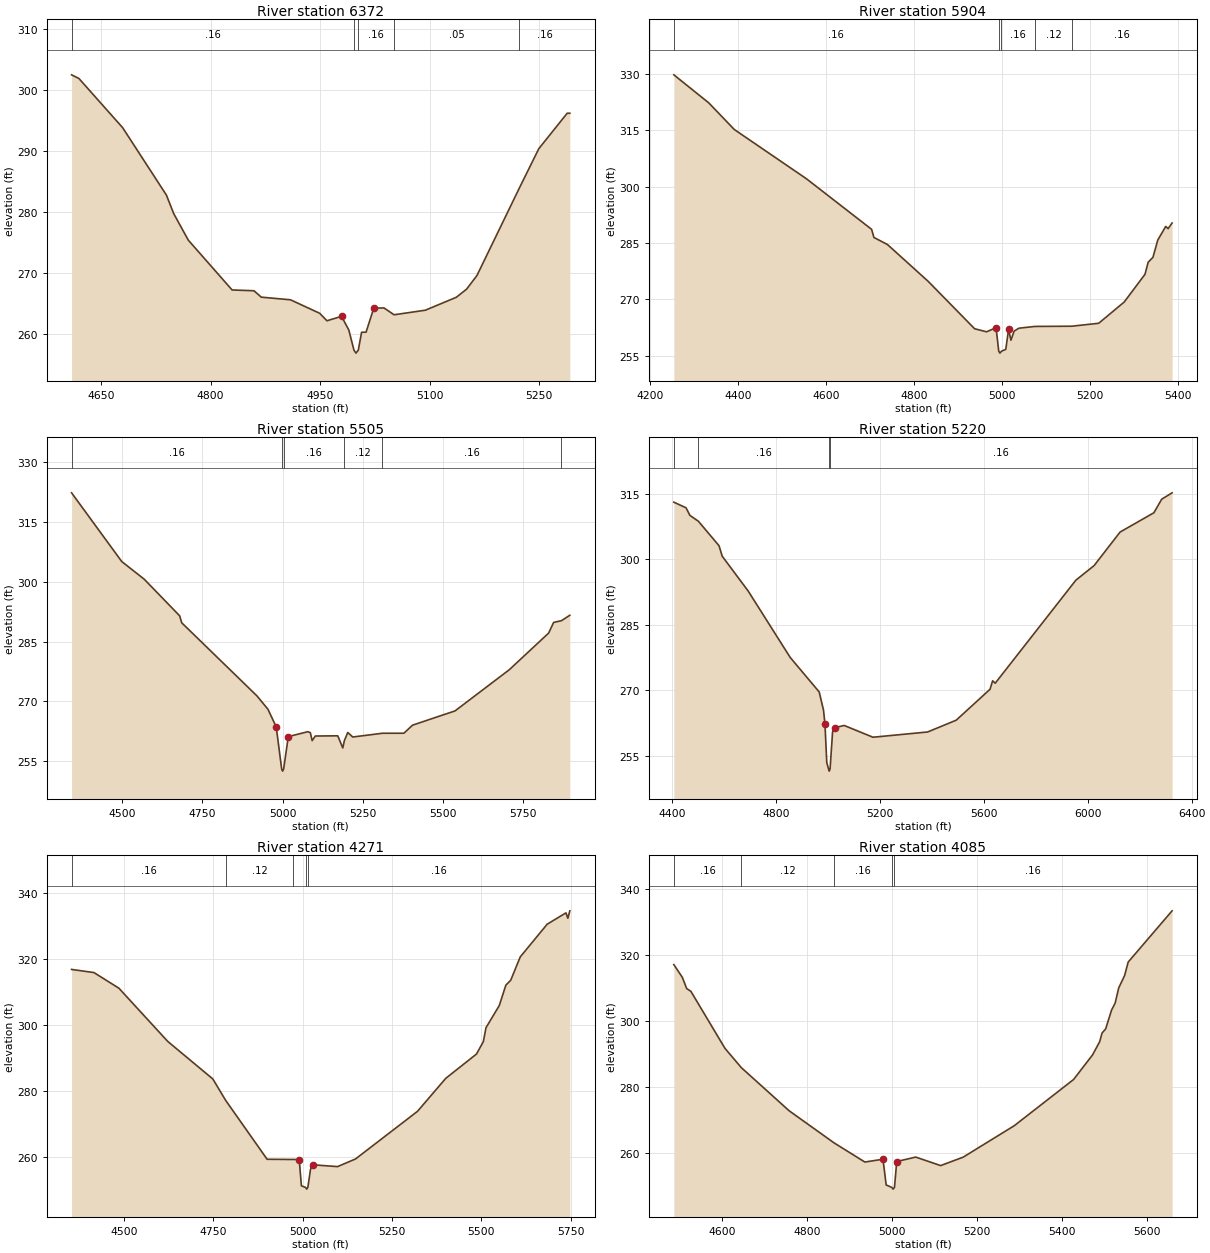
Type RM Length L Ch R = 1 ,6372    ,468,468,468
BEGIN DESCRIPTION:
COW SLASH CREEK 7.0
END DESCRIPTION:
XS GIS Cut Line= 3
      3654049.58     10523360.19      3654449.61     10523360.19
      3654649.63     10523160.17
#Sta/Elev= 30
  4609.4  302.47  4619.4  301.88  4679.4   293.8  4739.4  282.74  4749.4   279.7
  4769.4  275.35  4829.4  267.18  4859.4  267.05  4869.4     266  4909.4  265.57
  4949.4  263.36  4959.4  262.13  4979.4  262.85  4989.4  260.61  4996.4  257.32
  4999.2  256.82  5002.4  257.32  5006.9  260.25    5013  260.25  5023.6   264.2
  5037.7  264.23  5051.4  263.11  5094.3  263.86  5136.7  265.98  5150.8  267.31
    5165  269.55  5223.2  283.92  5249.8  290.36  5288.7  296.17  5292.3  296.17
#Mann= 5 ,-1 , 0
  4609.4     .16       0  4996.4     .07       0  5002.4     .16       0
  5051.4     .05       0  5223.2     .16       0
Bank Sta=4979.4,5023.6
XS Rating Curve= 0 ,0
Exp/Cntr=0.3,0.1

Type RM Length L Ch R = 1 ,5904    ,399,399,399
BEGIN DESCRIPTION:
COW SLASH CREEK 6.0
END DESCRIPTION:
XS GIS Cut Line= 3
      3653615.45     10523598.57      3654349.61     10523760.19
      3654699.58      10523610.2
#Sta/Elev= 30
  4254.8  329.67    4334  322.24  4392.2  315.15    4556  302.08  4704.3  288.63
  4709.6  286.47  4740.3   284.6  4832.5  274.86  4938.4  262.23  4965.6  261.41
  4987.2   262.5  4993.3  256.25  4996.1  255.75  4999.3  256.25  5009.3  256.75
  5015.6  262.05    5021  259.18  5028.3  261.61  5039.2  262.37  5075.5  262.84
  5159.4   262.9  5220.5  263.68  5278.5  269.33  5325.7  276.69  5332.9  279.89
  5343.8   281.2  5354.7  285.77  5372.8   289.4  5378.3  288.82  5387.3  290.31
#Mann= 5 ,-1 , 0
  4254.8     .16       0  4993.3     .07       0  4999.3     .16       0
  5075.5     .12       0  5159.4     .16       0
Bank Sta=4987.2,5015.6
XS Rating Curve= 0 ,0
Exp/Cntr=0.3,0.1

Type RM Length L Ch R = 1 ,5505    ,285,285,285
BEGIN DESCRIPTION:
COW SLASH CREEK 5.0
END DESCRIPTION:
XS GIS Cut Line= 3
      3653573.82     10524161.07      3654249.61     10524110.19
      3654999.57     10523660.21
#Sta/Elev= 30
  4342.3  322.35  4498.5  305.12  4568.7  300.67    4679  291.49  4685.5  289.74
  4919.7  271.41  4954.1  268.05  4979.9  263.61  4996.9  253.02  4999.7  252.52
  5002.9  253.02  5017.5  261.18  5078.3  262.41  5086.1  262.18  5091.9  260.18
  5101.6  261.33  5171.6  261.38  5187.2  258.34  5192.3  260.19  5202.7  262.22
  5218.3  261.08  5310.4  262.02  5377.6  262.03  5404.8  264.06    5537  267.63
  5706.1  277.97  5828.6  287.16  5844.1  289.83  5868.6  290.27  5894.6  291.63
#Mann= 6 ,-1 , 0
  4342.3     .16       0  4996.9     .07       0  5002.9     .16       0
  5192.3     .12       0  5310.4     .16       0  5868.6     .05       0
Bank Sta=4979.9,5017.5
XS Rating Curve= 0 ,0
Exp/Cntr=0.3,0.1

Type RM Length L Ch R = 1 ,5220    ,949,949,949
BEGIN DESCRIPTION:
COW SLASH CREEK 4.0
END DESCRIPTION:
XS GIS Cut Line= 3
      3653754.34      10524647.2      3654344.64     10524348.57
      3655599.59     10524410.19
#Sta/Elev= 30
  4406.7  313.06  4453.6  311.78  4468.6  310.04  4501.1  308.71  4580.7   303.1
  4592.9  300.71  4692.8  292.75  4854.7  277.55  4966.2  269.67  4982.8  265.52
  4988.4  262.38  4995.4  253.52  5002.1  252.06  5004.9  251.56  5008.1  252.06
  5017.8  260.54  5027.4  261.53  5062.6     262  5173.3  259.31  5383.6  260.51
  5493.7  263.21  5623.9  270.28  5633.9  272.22  5643.9  271.67  5954.3  295.23
  6024.4  298.55  6124.5  306.23  6254.6  310.64  6284.7  313.74  6324.7   315.2
#Mann= 4 ,-1 , 0
  4406.7     .05       0  4501.1     .16       0  5002.1     .07       0
  5008.1     .16       0
Bank Sta=4988.4,5027.4
XS Rating Curve= 0 ,0
Exp/Cntr=0.3,0.1

Type RM Length L Ch R = 1 ,4271    ,186,186,186
BEGIN DESCRIPTION:
COW SLASH CREEK 3.0
END DESCRIPTION:
XS GIS Cut Line= 2
      3653983.54     10524876.35      3655309.91      10525306.9
#Sta/Elev= 30
  4353.1  316.81  4415.7  315.86  4485.6  311.11  4622.3  294.96  4748.5  283.56
  4784.3  277.08  4900.4  259.19  4973.4  259.13  4990.3  259.11  4996.3  251.14
  5008.3  250.63  5011.1  250.13  5014.3  250.63  5021.8  256.11  5028.3  257.52
  5097.5  256.96    5148   259.3  5321.2  273.74  5400.3  283.75  5486.3  291.13
  5505.5  294.89    5513  299.14  5550.2  305.86  5568.5  312.03  5582.2  313.54
  5608.9  320.63  5684.2  330.54  5736.8  333.98    5742  332.35  5747.6   334.6
#Mann= 5 ,-1 , 0
  4353.1     .16       0  4784.3     .12       0  4973.4     .16       0
  5008.3     .07       0  5014.3     .16       0
Bank Sta=4990.3,5028.3
XS Rating Curve= 0 ,0
Exp/Cntr=0.3,0.1

Type RM Length L Ch R = 1 ,4085    ,633,633,633
BEGIN DESCRIPTION:
COW SLASH CREEK 2.0
END DESCRIPTION:
XS GIS Cut Line= 3
      3653999.58     10525160.19      3654499.61     10525210.19
      3655099.57     10525510.17
#Sta/Elev= 30
  4486.7  317.15  4506.8  313.27  4516.9   309.9  4526.9  309.04  4607.3  291.74
  4645.6  285.94  4758.1  272.88    4864  263.14  4936.5  257.34  4979.2  258.18
  4986.7   250.4  5000.2  249.63  5002.9  249.13  5006.2  249.63  5011.6  257.49
  5056.3  258.84    5115  256.26  5168.1  258.82  5288.3  268.34  5428.1  282.35
  5472.8  289.81  5489.5  293.81  5495.1  296.42  5503.5  297.66  5517.5  303.38
  5525.9  305.49  5534.3  310.08  5548.2  313.85  5556.6  317.92    5660  333.44
#Mann= 5 ,-1 , 0
  4486.7     .16       0  4645.6     .12       0    4864     .16       0
  5000.2     .07       0  5006.2     .16       0
Bank Sta=4979.2,5011.6
XS Rating Curve= 0 ,0
Exp/Cntr=0.3,0.1

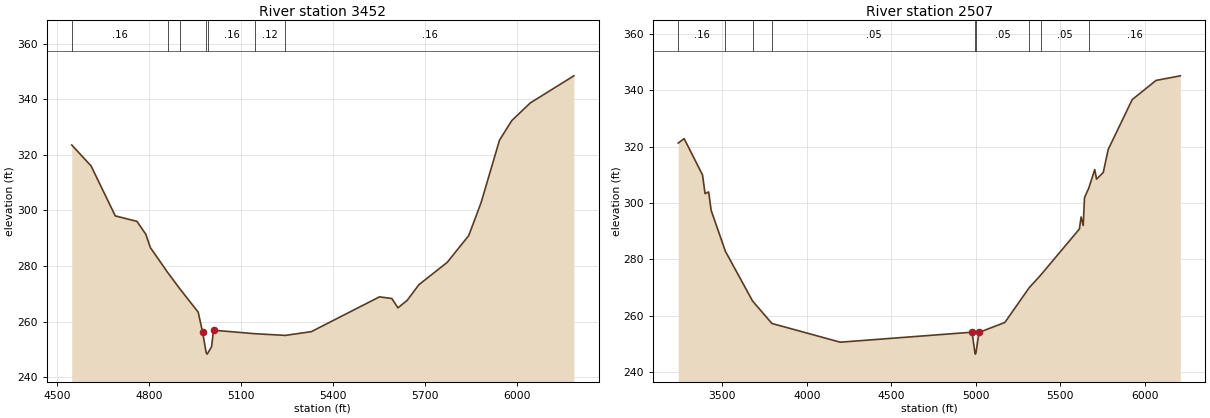
Type RM Length L Ch R = 1 ,3452    ,945,945,945
BEGIN DESCRIPTION:
Mapping XS 87f7c244
END DESCRIPTION:
XS GIS Cut Line= 3
      3653768.27     10525202.76      3654122.42     10525668.02
      3655171.02      10525758.3
#Sta/Elev= 30
  4547.9  323.53  4610.8  316.01  4689.8  298.02  4760.5  296.05  4789.6  291.35
  4804.2  286.61  4860.7  277.66  4900.3  271.79  4960.2  263.38  4974.7   256.1
  4986.2  248.78    4989  248.28  4992.2  248.78  5003.8  250.96  5010.1  256.89
  5145.7  255.62  5244.6  255.02  5329.2  256.37  5551.3  268.89  5591.5  268.29
  5611.6  264.93  5641.7  267.64  5679.7  273.25  5772.2   281.3  5842.4  290.94
  5882.6  302.78  5942.8   325.3  5982.9  332.34  6043.2  338.68  6185.1  348.42
#Mann= 7 ,-1 , 0
  4547.9     .16       0  4860.7     .12       0  4900.3     .16       0
  4986.2     .07       0  4992.2     .16       0  5145.7     .12       0
  5244.6     .16       0
Bank Sta=4974.7,5010.1
XS Rating Curve= 0 ,0
Exp/Cntr=0.3,0.1

Type RM Length L Ch R = 1 ,2507    ,0,0,0
BEGIN DESCRIPTION:
COW SLASH CREEK 1.0
END DESCRIPTION:
XS GIS Cut Line= 5
      3653691.85     10525202.76      3653323.81     10525765.24
      3653365.48     10526126.35      3653754.37     10526418.02
      3655191.88     10526230.52
#Sta/Elev= 30
  3239.1  321.29  3274.2  322.86  3382.8  309.97  3397.9  303.33    3419  303.94
  3434.1  297.35  3518.3  282.83    3679  265.18  3793.3   257.2  4198.1  250.54
    4978  254.09  4995.1   246.8  4997.9   246.3  5001.1   246.8    5019  254.01
    5172  257.54  5315.8  269.86  5383.5  274.33  5613.3  290.75  5623.4  295.04
  5635.9  292.01  5643.6   301.9  5668.7  305.27  5704.1  311.87  5714.9  308.49
  5754.5  310.83  5783.8  319.01  5925.9  336.74  6067.1  343.55  6210.6  345.18
#Mann= 9 ,-1 , 0
  3239.1     .16       0  3518.3     .05       0    3679     .08       0
  3793.3     .05       0  4995.1     .03       0  5001.1     .05       0
  5315.8     .16       0  5383.5     .05       0  5668.7     .16       0
Bank Sta=4978,5019
XS Rating Curve= 0 ,0
Exp/Cntr=0.3,0.1

Chan Stop Cuts=-1
Use User Specified Reach Order=0
Composite Channel Slope=5