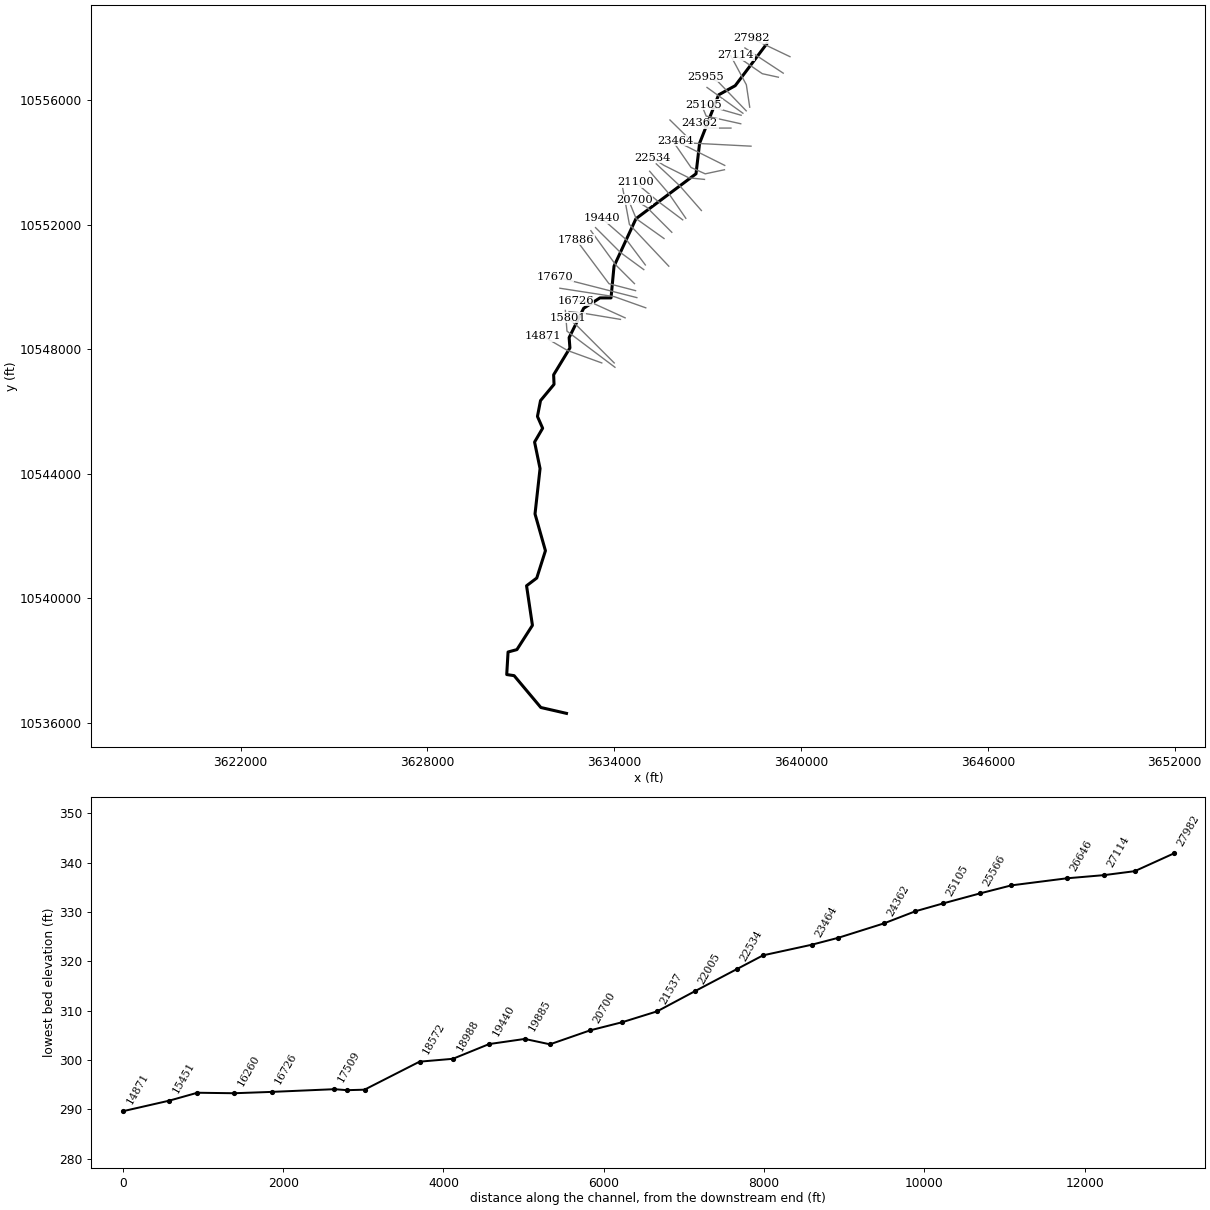
--- DOTTIE BRANCH.prj (project) ---

Proj Title=DOTTIE BRANCH Base Level Engineering
Current Plan=p01
Default Exp/Contr=0.3,0.1
English Units
Geom File=g01
Flow File=f01
Plan File=p01
Y Axis Title=Elevation
X Axis Title(PF)=Main Channel Distance
X Axis Title(XS)=Station
BEGIN DESCRIPTION:
DOTTIE BRANCH
END DESCRIPTION:
DSS Export Rating Curves= 0
DSS Export Rating Curve Sorted= 0
DSS Export Volume Flow Curves= 0
DXF OffsetX= 0
DXF OffsetY= 0
DXF ScaleX= 1
DXF ScaleY= 10

--- DOTTIE BRANCH.p01 (plan) ---

Plan Title=Multiple Run
Short Identifier=Multiple
Geom File=g01
Flow File=f01
Subcritical Flow
K Sum by GR= 0
Std Step Tol= 0.01
Critical Tol= 0.01
Num of Std Step Trials= 20
Max Error Tol= 0.3
Flow Tol Ratio= 0.001
Split Flow NTrial= 30
Split Flow Tol= 0.02
Split Flow Ratio= 0.02
Log Output Level= 0
Friction Slope Method= 1
Unsteady Friction Slope Method= 2
Unsteady Bridges Friction Slope Method= 1
Parabolic Critical Depth
Global Vel Dist=  1 , 1 , 1
Global Log Level= 0
CheckData=True
Encroach Param= -1, 0, 0, 0
BEGIN DESCRIPTION:
Multiple Run
END DESCRIPTION:

--- DOTTIE BRANCH.f01 (steady flow) ---

Flow Title=Multiple
Program Version=4.10
Number of Profiles= 7
Profile Names=10-year,25-year,50-year,1pct_min,100-year,1pct_plu,500-year
River Rch & RM=DOTTIE BRANCH,Reach-1         ,27982
    2112    3018    3796    3477    4702    6359    7196
River Rch & RM=DOTTIE BRANCH,Reach-1         ,22005
    3745    5487    7016    6522    8820   11928   13906
River Rch & RM=DOTTIE BRANCH,Reach-1         ,20199
    3745    5487    7016    6522    8820   11928   13906
River Rch & RM=DOTTIE BRANCH,Reach-1         ,17670
    4405    6466    8277    7697   10409   14077   16422
River Rch & RM=DOTTIE BRANCH,Reach-1         ,16726
    4405    6466    8277    7697   10409   14077   16422
River Rch & RM=DOTTIE BRANCH,Reach-1         ,10323
    4635    6779    8655    8022   10849   14672   17006
River Rch & RM=DOTTIE BRANCH,Reach-1         ,9731
    4635    6779    8655    8022   10849   14672   17006
Boundary for River Rch & Prof#=DOTTIE BRANCH,Reach-1         , 1
Up Type= 0
Dn Type= 3
Dn Slope=0.005
Boundary for River Rch & Prof#=DOTTIE BRANCH,Reach-1         , 2
Up Type= 0
Dn Type= 3
Dn Slope=0.005
Boundary for River Rch & Prof#=DOTTIE BRANCH,Reach-1         , 3
Up Type= 0
Dn Type= 3
Dn Slope=0.005
Boundary for River Rch & Prof#=DOTTIE BRANCH,Reach-1         , 4
Up Type= 0
Dn Type= 3
Dn Slope=0.005
Boundary for River Rch & Prof#=DOTTIE BRANCH,Reach-1         , 5
Up Type= 0
Dn Type= 3
Dn Slope=0.005
Boundary for River Rch & Prof#=DOTTIE BRANCH,Reach-1         , 6
Up Type= 0
Dn Type= 3
Dn Slope=0.005
Boundary for River Rch & Prof#=DOTTIE BRANCH,Reach-1         , 7
Up Type= 0
Dn Type= 3
Dn Slope=0.005
DSS Import GetInterval= 0
DSS Import GetPeak= 0
DSS Import FillOption= 0

--- DOTTIE BRANCH.g01 (geometry) ---

Geom Title=Existing Conditions
Program Version=4.10

River Reach=DOTTIE BRANCH   ,Reach-1
Reach XY= 30
       3638899.5       10557820.       3637886.5       10556473.
       3637353.5       10556178.      3636742.25       10554623.
        3636627.       10553641.      3634697.75       10552197.
        3633993.       10550669.       3633896.5       10549651.
      3633540.25       10549651.       3633017.5       10549317.
        3632551.       10548375.      3632576.25       10548042.
        3632053.       10547179.        3632066.       10546872.
       3631631.5       10546349.        3631533.       10545841.
       3631699.5       10545461.      3631440.75       10545017.
      3631616.75       10544165.        3631455.       10542706.
       3631789.5       10541524.        3631511.       10540646.
      3631183.25       10540397.      3631371.75       10539125.
      3630873.25       10538345.        3630589.       10538268.
        3630546.       10537543.      3630783.25       10537508.
       3631641.5       10536484.       3632465.5       10536295.

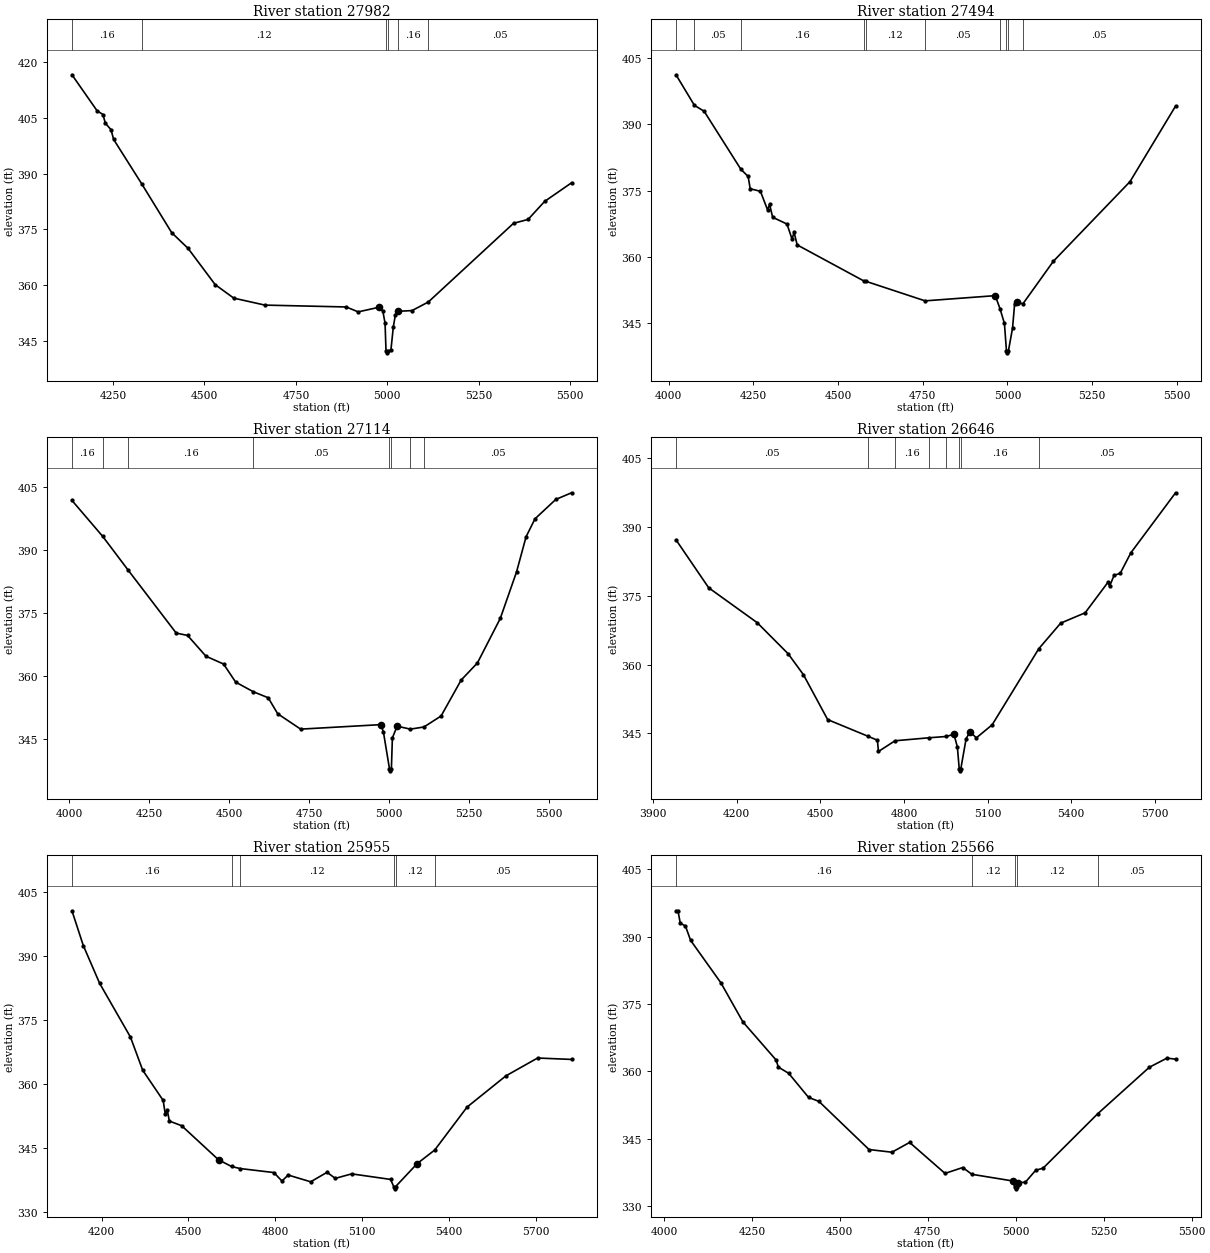
Type RM Length L Ch R = 1 ,27982   ,488,488,488
BEGIN DESCRIPTION:
DOTTIE BRANCH 56.0
END DESCRIPTION:
XS GIS Cut Line= 2
       3639645.9     10557405.26      3638414.33     10557995.03
#Sta/Elev= 30
  4137.9  416.52  4206.5  406.87  4222.5  405.86  4229.2  403.52  4244.7  401.78
  4251.8  399.17  4329.4  387.12  4410.5  374.15  4455.3  369.93  4529.4   360.2
  4580.2  356.58  4665.3  354.71  4887.7  354.21  4920.2  352.89  4976.6  354.12
  4987.5  353.15  4993.7  349.87  4996.3   342.4    4999   341.9  5002.3   342.4
  5009.7  342.64  5016.4  348.95  5021.9  352.08  5029.2  353.05  5067.3  353.24
  5111.8  355.53  5344.8  376.66  5384.6   377.7  5429.9  382.54  5503.4  387.53
#Mann= 6 ,-1 , 0
  4137.9     .16       0  4329.4     .12       0  4996.3     .07       0
  5002.3     .12       0  5029.2     .16       0  5111.8     .05       0
Bank Sta=4976.6,5029.2
XS Rating Curve= 0 ,0
Exp/Cntr=0.3,0.1

Type RM Length L Ch R = 1 ,27494   ,380,380,380
BEGIN DESCRIPTION:
DOTTIE BRANCH 55.0
END DESCRIPTION:
XS GIS Cut Line= 2
      3639428.91     10556875.74       3638197.9     10557686.29
#Sta/Elev= 30
    4022  401.21  4076.4  394.29    4105  392.96  4213.3  379.84  4234.9   378.2
  4240.9  375.42  4271.1  374.85  4292.2  370.64  4298.1   371.9  4307.2  368.97
  4349.4  367.44  4364.4  364.04  4370.4  365.56  4379.5  362.72  4575.8  354.58
  4581.6   354.5  4756.9  350.06  4963.8  351.24  4977.8  348.32    4991  344.95
  4996.9   338.8  4999.7   338.3  5002.9   338.8  5014.9  343.89    5021  349.31
    5027  349.84  5045.5  349.39  5135.4  359.02  5361.4  377.03  5495.9  394.13
#Mann= 10 ,-1 , 0
    4022     .16       0  4076.4     .05       0  4213.3     .16       0
  4575.8      .1       0  4581.6     .12       0  4756.9     .05       0
  4977.8     .12       0  4996.9     .07       0  5002.9     .12       0
  5045.5     .05       0
Bank Sta=4963.8,5027
XS Rating Curve= 0 ,0
Exp/Cntr=0.3,0.1

Type RM Length L Ch R = 1 ,27114   ,468,468,468
BEGIN DESCRIPTION:
DOTTIE BRANCH 54.0
END DESCRIPTION:
XS GIS Cut Line= 3
      3639272.64     10556745.54      3638756.14     10556858.39
      3637905.48      10557444.3
#Sta/Elev= 30
  4008.7  401.81  4104.9  393.25  4183.3  385.34  4334.6  370.26  4370.1   369.7
  4427.5  364.76  4482.7   362.9  4520.4   358.6  4575.4  356.32  4622.1  354.88
  4651.8  351.08  4723.5  347.42  4974.4  348.49  4982.4  346.68  5001.2     338
  5003.9   337.5  5007.2     338  5010.3  345.34  5025.2  348.12  5066.4  347.42
    5109  347.93  5162.5  350.54  5225.3  359.09  5276.1  363.16  5347.7  373.77
  5398.5  384.83  5428.2  393.17    5456  397.43  5520.9  402.04  5570.3  403.63
#Mann= 8 ,-1 , 0
  4008.7     .16       0  4104.9     .05       0  4183.3     .16       0
  4575.4     .05       0  5001.2     .03       0  5007.2     .05       0
  5066.4     .12       0    5109     .05       0
Bank Sta=4974.4,5025.2
XS Rating Curve= 0 ,0
Exp/Cntr=0.3,0.1

Type RM Length L Ch R = 1 ,26646   ,691,691,691
BEGIN DESCRIPTION:
DOTTIE BRANCH 53.0
END DESCRIPTION:
XS GIS Cut Line= 3
       3638352.5       10555782.      3638243.99     10556502.49
      3637740.49     10557440.03
#Sta/Elev= 30
  3981.9  387.26  4099.2  376.79  4273.3  369.18  4384.6  362.38    4439  357.85
  4526.2  348.03  4671.1  344.39  4704.7  343.53  4708.4  341.07    4768  343.41
  4891.2  344.07  4952.5  344.35  4979.3  344.85  4991.7  342.05  4998.2  337.35
    5001  336.85  5004.2  337.35  5023.1  343.88  5037.1  345.36  5059.8  344.05
  5116.5  346.89  5283.9   363.5  5362.5  369.08  5450.2  371.33  5532.2     378
  5537.8  377.12  5554.1  379.51    5576  379.94  5614.2  384.42  5774.7  397.52
#Mann= 8 ,-1 , 0
  3981.9     .05       0  4671.1     .12       0    4768     .16       0
  4891.2     .05       0  4952.5     .16       0  4998.2     .07       0
  5004.2     .16       0  5283.9     .05       0
Bank Sta=4979.3,5037.1
XS Rating Curve= 0 ,0
Exp/Cntr=0.3,0.1

Type RM Length L Ch R = 1 ,25955   ,389,389,389
BEGIN DESCRIPTION:
DOTTIE BRANCH 52.0
END DESCRIPTION:
XS GIS Cut Line= 4
      3638239.66      10555664.8      3637532.18     10556398.32
      3637328.92     10556608.49      3636942.63     10556756.06
#Sta/Elev= 30
  4097.7  400.61  4136.9  392.45  4193.4  383.58  4299.7     371  4341.9  363.24
  4412.6  356.15  4419.8  352.99  4426.8  353.89    4434  351.31  4476.4  350.22
  4603.8  342.23  4648.6  340.66  4678.1  340.18  4794.7  339.24    4823  337.24
    4844  338.66    4922  337.07  4978.6   339.3  5006.9  337.87  5063.5  338.93
  5197.8  337.63  5208.9  335.92  5211.7  335.42  5214.9  335.92  5289.6  341.33
  5350.3  344.52    5462  354.59  5595.9   361.9  5705.5  366.09  5822.7  365.76
#Mann= 6 ,-1 , 0
  4097.7     .16       0  4648.6     .05       0  4678.1     .12       0
  5208.9     .07       0  5214.9     .12       0  5350.3     .05       0
Bank Sta=4603.8,5289.6
XS Rating Curve= 0 ,0
Exp/Cntr=0.3,0.1

Type RM Length L Ch R = 1 ,25566   ,461,461,461
BEGIN DESCRIPTION:
DOTTIE BRANCH 51.0
END DESCRIPTION:
XS GIS Cut Line= 2
      3638133.71     10555587.58      3636980.18     10556415.87
#Sta/Elev= 30
  4034.2  395.77  4039.8  395.77  4046.3  393.03  4061.1  392.36  4075.8  389.17
  4161.7  379.73  4224.4     371  4318.9   362.5  4325.1  360.93  4354.5  359.55
    4411  354.18  4440.5  353.29  4582.9  342.56    4648  341.96  4698.3  344.14
    4799  337.24  4849.3  338.55  4875.2  337.04  4991.8  335.55  4996.5   334.3
  4999.3   333.8  5002.5   334.3  5006.5  335.16  5027.4  335.28  5056.8  337.95
  5077.7   338.4  5233.2  350.55  5379.8   360.9  5430.1  362.94  5454.3  362.69
#Mann= 5 ,-1 , 0
  4034.2     .16       0  4875.2     .12       0  4996.5     .07       0
  5002.5     .12       0  5233.2     .05       0
Bank Sta=4991.8,5006.5
XS Rating Curve= 0 ,0
Exp/Cntr=0.3,0.1

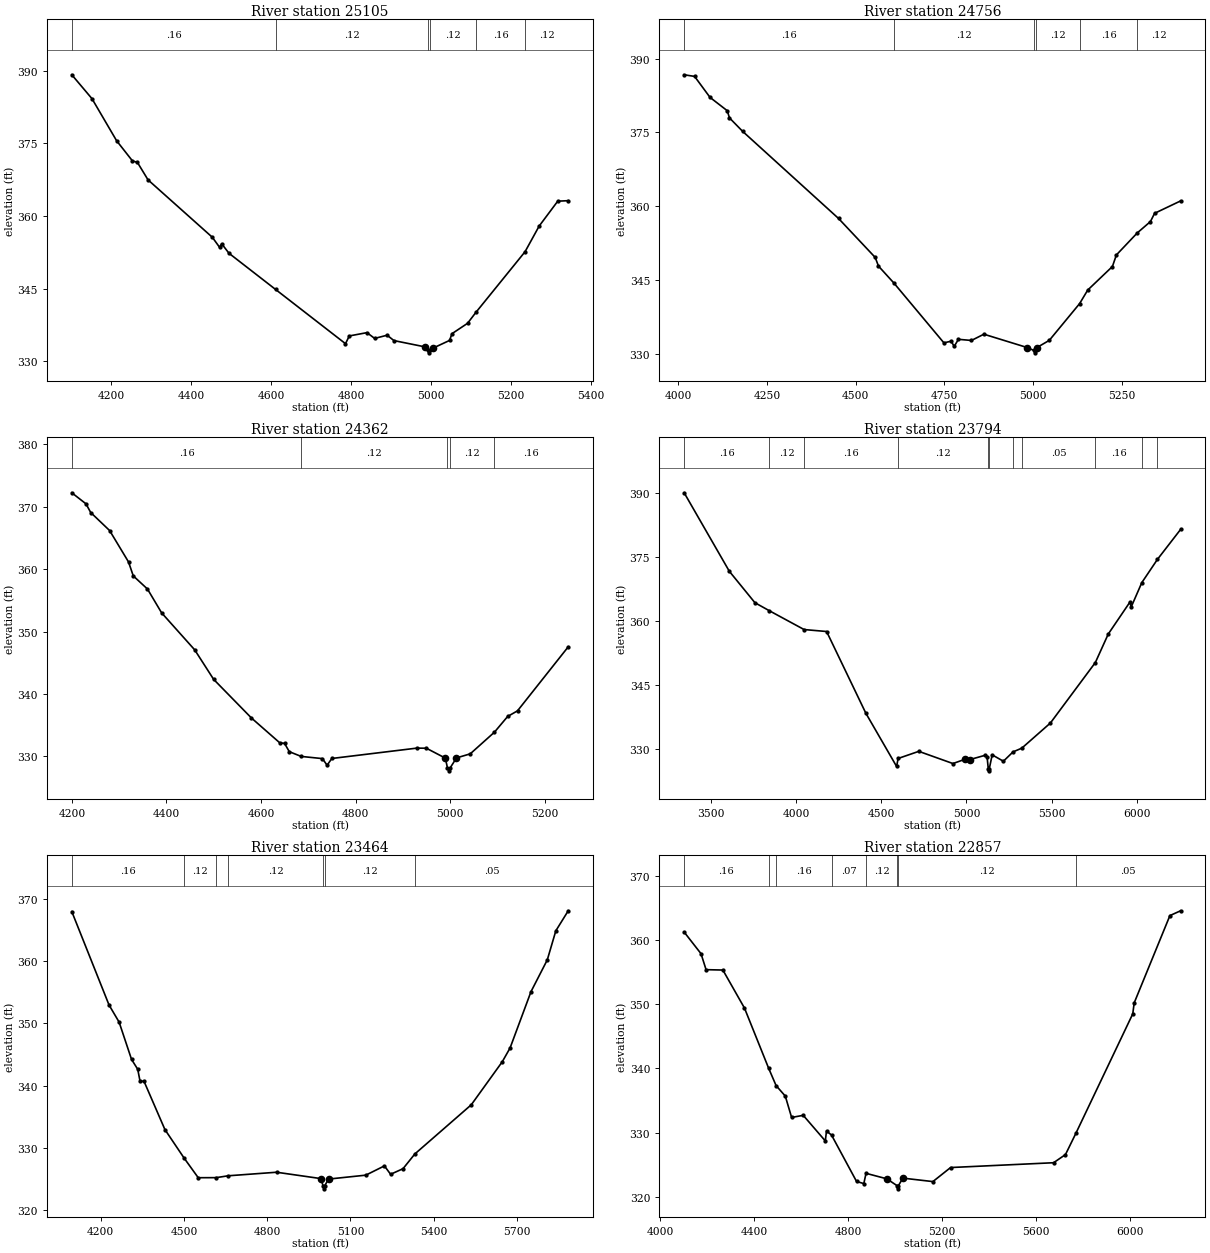
Type RM Length L Ch R = 1 ,25105   ,349,349,349
BEGIN DESCRIPTION:
DOTTIE BRANCH 50.0
END DESCRIPTION:
XS GIS Cut Line= 2
      3638077.34     10555522.45      3636884.39     10555865.15
#Sta/Elev= 30
  4101.5  389.19    4152  384.25  4213.6  375.56  4253.1  371.41  4265.6  371.09
  4292.1  367.49  4452.9  355.63    4471  353.56  4476.3  354.29  4494.5  352.33
    4611  344.86  4785.8  333.66  4795.3  335.26  4839.4  335.94  4858.7  334.75
  4889.9  335.41  4906.9   334.3  4984.7     333  4990.9  332.27  4993.7  331.77
  4996.9  332.27  5004.3  332.73  5045.9  334.33  5052.1  335.73    5091  337.87
  5111.7  340.11  5234.8  352.66    5270  357.95  5316.5  363.09  5342.7  363.19
#Mann= 6 ,-1 , 0
  4101.5     .16       0    4611     .12       0  4990.9     .07       0
  4996.9     .12       0  5111.7     .16       0  5234.8     .12       0
Bank Sta=4984.7,5004.3
XS Rating Curve= 0 ,0
Exp/Cntr=0.3,0.1

Type RM Length L Ch R = 1 ,24756   ,394,394,394
BEGIN DESCRIPTION:
DOTTIE BRANCH 49.0
END DESCRIPTION:
XS GIS Cut Line= 3
      3638064.27     10555249.02      3636953.19     10555496.41
      3636853.99     10555737.95
#Sta/Elev= 30
  4016.8  386.72  4046.2  386.39  4089.7  382.12  4138.3  379.41  4144.5  377.95
  4181.8   375.2  4451.9   357.5  4555.4  349.56  4564.5  347.81    4608  344.36
    4749  332.19  4769.4  332.53    4778  331.47  4789.9  332.91  4826.6  332.68
  4861.7  333.95  4984.6  331.22  5002.1  330.66  5004.8  330.16  5008.1  330.66
  5010.8  331.22  5046.1   332.7  5131.5  340.17  5154.4  342.93    5224  347.72
  5235.3  350.08  5294.2  354.56  5331.2  356.86  5342.9  358.54  5416.2  361.06
#Mann= 6 ,-1 , 0
  4016.8     .16       0    4608     .12       0  5002.1     .07       0
  5008.1     .12       0  5131.5     .16       0  5294.2     .12       0
Bank Sta=4984.6,5010.8
XS Rating Curve= 0 ,0
Exp/Cntr=0.3,0.1

Type RM Length L Ch R = 1 ,24362   ,568,568,568
BEGIN DESCRIPTION:
DOTTIE BRANCH 48.0
END DESCRIPTION:
XS GIS Cut Line= 3
      3637749.62     10555110.19      3636949.61     10555110.19
      3636749.62     10555260.18
#Sta/Elev= 30
  4199.8  372.22  4229.8  370.45  4239.8  369.06  4279.8  366.17  4319.8  361.14
  4329.8  358.91  4359.8  356.81  4389.8  352.99  4459.8  347.06  4499.8  342.34
  4579.8  336.15  4639.8  332.17  4649.8  332.09  4659.8  330.76  4684.9     330
  4729.8  329.65  4739.8  328.59  4749.8  329.67  4929.8  331.33  4949.8  331.31
  4989.8  329.73  4994.3  328.19  4997.1  327.69  5000.3  328.19  5013.4  329.76
  5042.5  330.41  5093.7  333.88  5121.7   336.4  5142.5   337.3  5249.8  347.55
#Mann= 5 ,-1 , 0
  4199.8     .16       0  4684.9     .12       0  4994.3     .07       0
  5000.3     .12       0  5093.7     .16       0
Bank Sta=4989.8,5013.4
XS Rating Curve= 0 ,0
Exp/Cntr=0.3,0.1

Type RM Length L Ch R = 1 ,23794   ,330,330,330
BEGIN DESCRIPTION:
DOTTIE BRANCH 47.0
END DESCRIPTION:
XS GIS Cut Line= 3
      3638394.14     10554528.53      3636549.54     10554624.02
      3635789.97     10555370.57
#Sta/Elev= 30
  3344.4  389.96  3609.3  371.56  3759.5  364.19  3841.8  362.36  4047.9   357.9
    4180  357.44  4410.4  338.27  4590.6  325.81  4599.5  327.68  4720.8  329.35
    4921  326.49  4991.1  327.48  5018.4   327.4  5111.3  328.44  5121.3   328.1
  5128.3  325.28  5131.1  324.78  5134.3  325.28  5151.3  328.53    5217  327.03
  5273.6  329.22  5325.1   330.1  5492.8  335.99  5756.5  350.17  5832.2  356.85
  5959.5  364.35  5966.5  363.17  6029.2  368.91  6120.3  374.33  6256.5  381.37
#Mann= 11 ,-1 , 0
  3344.4     .16       0  3841.8     .12       0  4047.9     .16       0
  4599.5     .12       0  5128.3     .07       0  5134.3     .12       0
  5273.6     .16       0  5325.1     .05       0  5756.5     .16       0
  6029.2     .12       0  6120.3     .16       0
Bank Sta=4991.1,5018.4
XS Rating Curve= 0 ,0
Exp/Cntr=0.3,0.1

Type RM Length L Ch R = 1 ,23464   ,607,607,607
BEGIN DESCRIPTION:
DOTTIE BRANCH 46.0
END DESCRIPTION:
XS GIS Cut Line= 3
      3637549.65     10553910.17      3636749.61     10554310.19
      3635949.61     10554710.19
#Sta/Elev= 30
    4096  367.98  4230.2  352.95  4266.5   350.2  4311.3   344.2  4333.6  342.61
    4342  340.67    4356   340.7  4431.5  332.92  4500.2  328.36  4551.6  325.17
    4616  325.18  4659.7  325.48  4833.9  326.05  4993.3  325.03  5001.4  323.88
  5004.2  323.38  5007.4  323.88  5021.2  324.95  5155.4  325.58  5222.5  327.07
  5244.8  325.72  5289.5  326.62  5332.4     329  5535.5   336.9  5647.3  343.83
  5675.3  346.04  5750.7   355.1  5809.4  360.21  5840.2  364.89  5884.9  368.11
#Mann= 7 ,-1 , 0
    4096     .16       0  4500.2     .12       0    4616     .07       0
  4659.7     .12       0  5001.4     .07       0  5007.4     .12       0
  5332.4     .05       0
Bank Sta=4993.3,5021.2
XS Rating Curve= 0 ,0
Exp/Cntr=0.3,0.1

Type RM Length L Ch R = 1 ,22857   ,323,323,323
BEGIN DESCRIPTION:
DOTTIE BRANCH 45.0
END DESCRIPTION:
XS GIS Cut Line= 4
      3637540.87     10553771.01      3636922.81     10553639.06
      3636467.95     10553843.92      3635908.94     10554652.92
#Sta/Elev= 30
  4101.9  361.26  4173.7  357.89  4195.2   355.4  4266.8  355.34  4358.8  349.41
  4461.7  340.03  4493.5  337.32  4532.6  335.69  4559.5  332.36    4609  332.69
    4703   328.7  4708.1  330.24  4729.4  329.62  4836.1  322.38    4867  322.05
  4876.5  323.65  4965.1  322.79  5008.4  321.73  5011.1  321.23  5014.4  321.73
  5033.5   322.9  5161.2  322.36  5236.5  324.55  5675.1   325.3  5725.8  326.57
  5770.2  329.89  6012.4  348.51  6018.5  350.22  6170.6  363.83  6216.1  364.58
#Mann= 8 ,-1 , 0
  4101.9     .16       0  4461.7     .12       0  4493.5     .16       0
  4729.4     .07       0  4876.5     .12       0  5008.4     .07       0
  5014.4     .12       0  5770.2     .05       0
Bank Sta=4965.1,5033.5
XS Rating Curve= 0 ,0
Exp/Cntr=0.3,0.1

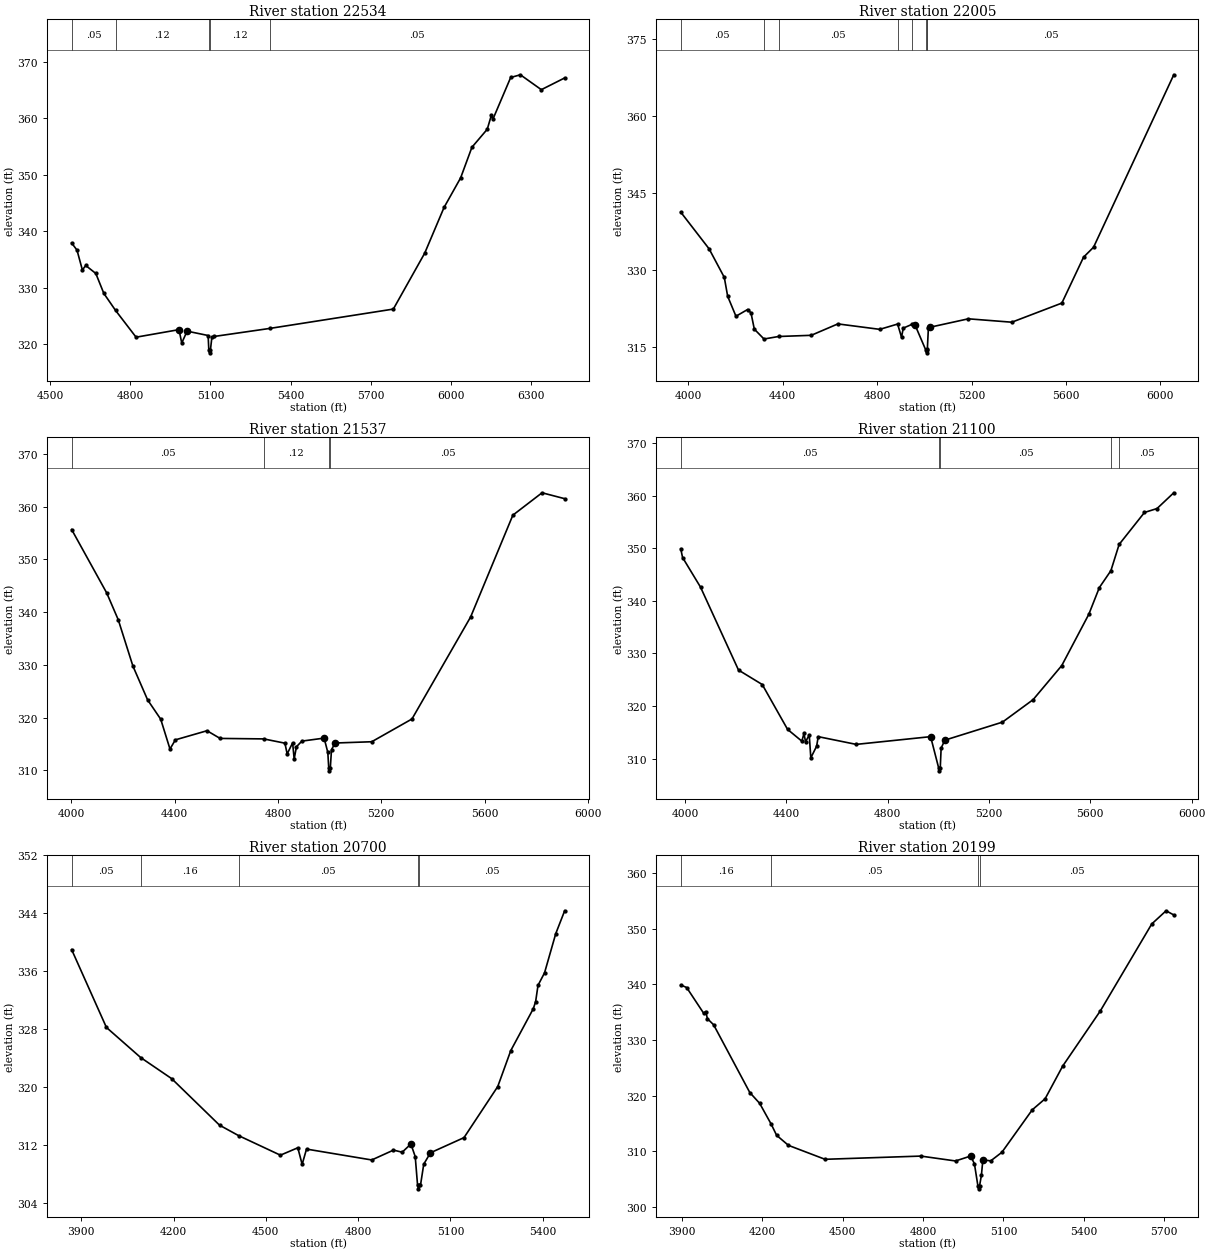
Type RM Length L Ch R = 1 ,22534   ,529,529,529
BEGIN DESCRIPTION:
DOTTIE BRANCH 44.0
END DESCRIPTION:
XS GIS Cut Line= 4
      3636899.63     10553460.19      3636399.61     10553510.19
      3635599.61     10553910.19        3635223.     10554153.67
#Sta/Elev= 30
  4580.6  337.93  4600.7  336.66  4620.8  333.15  4633.4  333.94  4671.1  332.53
  4701.2  328.99  4745.2  325.97  4821.8  321.24  4982.6  322.58  4992.7  320.21
  5012.8  322.31  5091.5  321.54  5094.1  318.97  5096.8  318.47  5100.1  318.97
  5105.5  321.22  5113.9  321.37  5323.1   322.8  5784.7  326.22  5902.1  336.12
  5974.7  344.24  6036.6  349.46  6078.8  354.88  6136.2  358.07  6151.4  360.51
  6157.3  359.84  6223.9  367.24  6260.2  367.72  6338.7  365.08    6426  367.16
#Mann= 5 ,-1 , 0
  4580.6     .05       0  4745.2     .12       0  5094.1     .07       0
  5100.1     .12       0  5323.1     .05       0
Bank Sta=4982.6,5012.8
XS Rating Curve= 0 ,0
Exp/Cntr=0.3,0.1

Type RM Length L Ch R = 1 ,22005   ,468,468,468
BEGIN DESCRIPTION:
DOTTIE BRANCH 43.0
END DESCRIPTION:
XS GIS Cut Line= 3
      3636799.63     10552460.17      3636099.61     10553260.19
      3635349.58     10553960.22
#Sta/Elev= 30
    3968  341.32  4088.1  334.18  4152.6  328.62  4166.9  324.94    4202  321.06
  4251.3  322.37  4265.6  321.73  4279.8  318.55  4320.8  316.63  4382.7  317.12
  4520.9  317.35  4633.8  319.57  4811.3  318.51  4886.9  319.54  4903.4  316.98
    4911  318.75  4949.5  319.52  4960.3  319.41  5006.7  314.44  5009.4  313.94
  5012.7  314.44  5012.9  314.63  5017.3  318.74  5023.9  318.92  5186.6  320.56
  5370.8   319.9  5582.8  323.62  5674.7  332.55  5717.2  334.49    6057  368.04
#Mann= 8 ,-1 , 0
    3968     .05       0  4320.8     .16       0  4382.7     .05       0
  4886.9     .12       0  4949.5     .16       0  5006.7     .07       0
  5012.7     .16       0  5012.9     .05       0
Bank Sta=4960.3,5023.9
XS Rating Curve= 0 ,0
Exp/Cntr=0.3,0.1

Type RM Length L Ch R = 1 ,21537   ,437,437,437
BEGIN DESCRIPTION:
DOTTIE BRANCH 42.0
END DESCRIPTION:
XS GIS Cut Line= 3
       3636299.6      10552210.2      3635749.61     10553010.19
      3635138.11     10553722.37
#Sta/Elev= 30
  4000.8  355.67  4136.8  343.62  4181.4  338.54  4238.2  329.75  4295.1  323.34
  4345.8  319.68  4381.7  314.02  4402.6  315.76  4525.1  317.49  4575.8  316.03
  4744.6  315.94  4826.8  315.13  4835.6  313.08  4856.6   315.2  4862.7  312.13
  4871.5  314.45  4892.5  315.52  4978.7  316.09    4993  313.37  4996.6  310.38
  4999.3  309.88  5002.6  310.38  5007.3  313.91  5021.5  315.16  5163.1   315.4
  5318.9  319.72  5546.1  339.08  5709.6  358.39  5822.7  362.64  5910.3  361.52
#Mann= 4 ,-1 , 0
  4000.8     .05       0  4744.6     .12       0  4996.6     .03       0
  5002.6     .05       0
Bank Sta=4978.7,5021.5
XS Rating Curve= 0 ,0
Exp/Cntr=0.3,0.1

Type RM Length L Ch R = 1 ,21100   ,400,400,400
BEGIN DESCRIPTION:
DOTTIE BRANCH 41.0
END DESCRIPTION:
XS GIS Cut Line= 3
      3636199.58     10552160.21      3635399.61     10552760.19
      3634674.57     10553368.21
#Sta/Elev= 30
  3983.2   349.9  3990.5  348.23  4061.3   342.6  4211.3  326.83    4305  324.08
    4405  315.55  4461.3  313.31  4469.6  314.77  4475.9   313.2  4490.5  314.47
  4496.7  310.14  4519.6  312.35  4525.9  314.17  4675.9   312.7  4969.6  314.17
  5001.6  308.17  5004.4  307.67  5007.6  308.17  5011.1  311.98  5025.5   313.5
  5253.1  316.93  5374.1   321.2  5487.3  327.69    5594  337.43  5635.7  342.52
  5681.2  345.73  5713.7  350.72  5813.8   356.8  5863.3  357.54  5929.4  360.54
#Mann= 5 ,-1 , 0
  3983.2     .05       0  5001.6     .03       0  5007.6     .05       0
  5681.2     .16       0  5713.7     .05       0
Bank Sta=4969.6,5025.5
XS Rating Curve= 0 ,0
Exp/Cntr=0.3,0.1

Type RM Length L Ch R = 1 ,20700   ,501,501,501
BEGIN DESCRIPTION:
DOTTIE BRANCH 40.0
END DESCRIPTION:
XS GIS Cut Line= 3
       3635849.6      10551760.2      3635049.61     10552560.19
      3634649.57     10552810.21
#Sta/Elev= 30
  3868.5     339  3981.6  328.27    4093  324.12  4193.8  321.21  4349.3   314.8
  4411.2  313.36  4547.3  310.66  4603.9  311.68    4618  309.39  4632.2   311.5
  4844.3     310    4915  311.36  4943.3  311.07  4971.6   312.2  4985.7  310.46
  4993.3  306.52  4996.1  306.02  4999.3  306.52  5002.8  306.52  5013.4  309.42
  5035.2  310.99  5144.3  313.08    5254  320.12  5296.4  325.08  5369.6  330.85
  5377.2  331.83  5384.9  334.07  5406.1  335.79  5442.7  341.21  5471.6  344.35
#Mann= 5 ,-1 , 0
  3868.5     .05       0    4093     .16       0  4411.2     .05       0
  4993.3     .03       0  4999.3     .05       0
Bank Sta=4971.6,5035.2
XS Rating Curve= 0 ,0
Exp/Cntr=0.3,0.1

Type RM Length L Ch R = 1 ,20199   ,314,314,314
BEGIN DESCRIPTION:
DOTTIE BRANCH 39.0
END DESCRIPTION:
XS GIS Cut Line= 3
      3635599.57     10551560.21      3634705.79     10552196.35
      3634424.56     10552883.81
#Sta/Elev= 30
  3895.7  339.91  3917.8  339.45  3981.6  334.79  3989.1  335.12  3995.2  333.84
  4018.4  332.74  4153.4  320.54  4190.2  318.59  4233.5  314.82  4253.5  312.83
  4297.7  311.02  4434.2  308.51  4791.7  309.09  4921.2  308.21  4977.7   309.1
  4991.7  307.68  5004.7  303.69  5007.4  303.19  5010.7  303.69  5017.7  305.64
  5023.1   308.4  5052.5  308.23  5094.1  309.77  5207.4  317.42  5255.4  319.41
    5321   325.3  5461.5  335.24  5653.4   350.9  5706.8  353.27  5735.5  352.52
#Mann= 4 ,-1 , 0
  3895.7     .16       0  4233.5     .05       0  5004.7     .03       0
  5010.7     .05       0
Bank Sta=4977.7,5023.1
XS Rating Curve= 0 ,0
Exp/Cntr=0.3,0.1

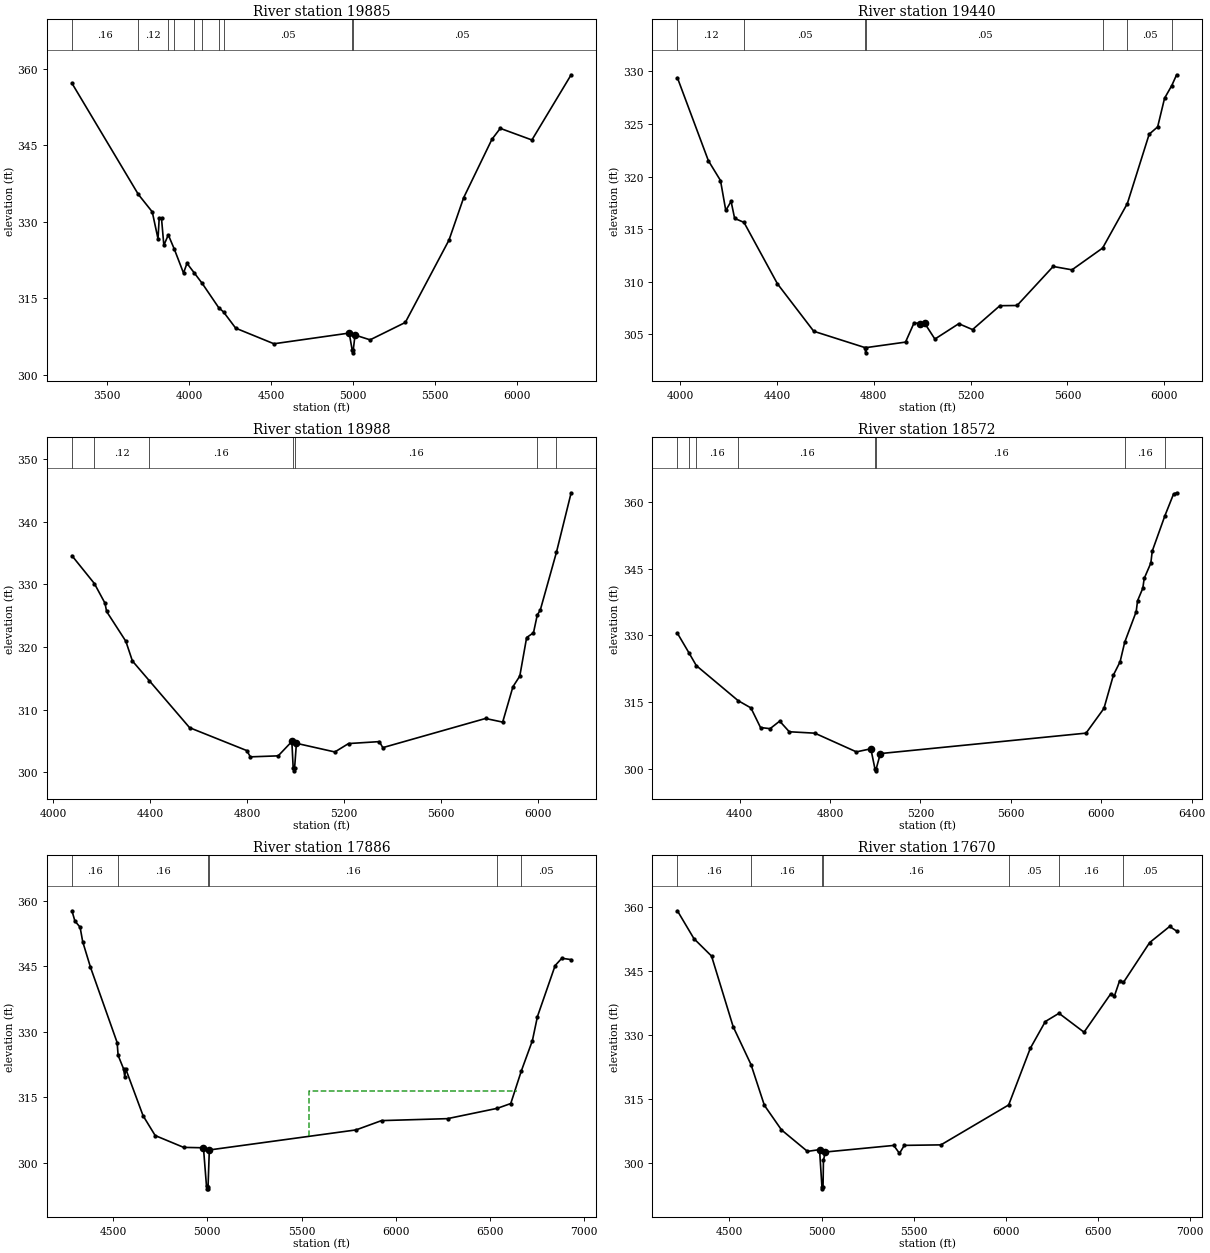
Type RM Length L Ch R = 1 ,19885   ,445,445,445
BEGIN DESCRIPTION:
DOTTIE BRANCH 38.0
END DESCRIPTION:
XS GIS Cut Line= 3
      3635752.67     10550670.31      3634487.04     10552014.06
       3634268.4     10553195.77
#Sta/Elev= 30
  3285.2  357.17  3690.6  335.36  3775.5  331.94  3810.7  326.65    3818  330.75
  3832.1  330.64  3846.3  325.38  3873.5  327.42  3910.1  324.63  3966.4  319.93
  3987.5  321.84  4030.1  320.04  4080.6   317.9  4180.6  313.17  4210.6   312.3
  4284.9  309.12  4518.3  306.06  4977.9  308.16  4996.4  304.78  4999.1  304.28
  5002.4  304.78  5013.5  307.77  5105.4  306.83  5320.4  310.24  5587.1   326.4
  5676.4   334.7  5849.2  346.17  5900.1  348.32  6093.3  346.04  6332.9  358.83
#Mann= 10 ,-1 , 0
  3285.2     .16       0  3690.6     .12       0  3873.5     .16       0
  3910.1     .12       0  4030.1     .16       0  4080.6     .12       0
  4180.6     .16       0  4210.6     .05       0  4996.4     .03       0
  5002.4     .05       0
Bank Sta=4977.9,5013.5
XS Rating Curve= 0 ,0
Exp/Cntr=0.3,0.1

Type RM Length L Ch R = 1 ,19440   ,452,452,452
BEGIN DESCRIPTION:
DOTTIE BRANCH 37.0
END DESCRIPTION:
XS GIS Cut Line= 3
      3634999.61     10550710.19      3634399.61     10551510.19
      3633599.62     10552210.18
#Sta/Elev= 30
  3988.4  329.39  4116.5   321.5  4166.5  319.62  4188.4  316.77  4210.3  317.64
  4224.9  316.02  4263.6  315.64  4401.9   309.8  4551.9  305.29  4763.5  303.74
  4766.3  303.24  4769.5  303.74  4931.1  304.26  4966.5  306.09  4991.7  306.02
  5009.8  306.07  5052.5  304.55  5151.2  306.01  5208.1  305.45  5321.1  307.72
  5392.2  307.74  5541.3  311.45  5619.1  311.13  5745.6   313.2  5847.8  317.43
    5938  324.02  5973.1  324.72  6001.6  327.44  6031.5  328.65  6051.4  329.67
#Mann= 7 ,-1 , 0
  3988.4     .12       0  4263.6     .05       0  4763.5     .03       0
  4769.5     .05       0  5745.6     .16       0  5847.8     .05       0
  6031.5     .16       0
Bank Sta=4991.7,5009.8
XS Rating Curve= 0 ,0
Exp/Cntr=0.3,0.1

Type RM Length L Ch R = 1 ,18988   ,416,416,416
BEGIN DESCRIPTION:
DOTTIE BRANCH 36.0
END DESCRIPTION:
XS GIS Cut Line= 3
       3634949.6      10550560.2      3634199.61     10551110.19
      3633399.62     10551910.18
#Sta/Elev= 30
  4076.5  334.56  4169.1  330.12  4212.9  326.99  4219.7  325.66  4299.1  320.91
  4326.2  317.77  4396.5   314.6  4562.4  307.13  4798.5  303.48  4813.2  302.48
  4928.2  302.64  4984.6  304.93    4990  300.75  4992.8  300.25    4996  300.75
  5003.4  304.64  5162.1  303.26  5218.7   304.6  5345.9  304.91  5360.1  303.95
  5784.4   308.6  5855.1  308.02  5897.5  313.66  5925.8  315.36  5954.1  321.51
  5982.3  322.26  5997.8  325.07  6010.6  325.91    6077  335.08  6137.9  344.59
#Mann= 7 ,-1 , 0
  4076.5     .16       0  4169.1     .12       0  4396.5     .16       0
    4990     .03       0    4996     .16       0  5997.8     .16       0
    6077     .05       0
Bank Sta=4984.6,5003.4
XS Rating Curve= 0 ,0
Exp/Cntr=0.3,0.1

Type RM Length L Ch R = 1 ,18572   ,686,686,686
BEGIN DESCRIPTION:
DOTTIE BRANCH 35.0
END DESCRIPTION:
XS GIS Cut Line= 3
      3634649.62     10550110.17      3634049.61     10550710.19
      3633249.61     10551810.19
#Sta/Elev= 30
  4124.6  330.51  4176.7  326.03  4208.3  323.25  4393.3   315.4  4449.9  313.77
  4492.3  309.38  4534.7  309.12  4577.2  310.81  4619.6  308.43  4732.7  308.11
  4916.6  303.92  4980.5  304.61  4998.4  300.17  5001.1  299.67  5004.4  300.17
  5022.6  303.54  5932.6  308.12  6011.8  313.66  6053.9  321.16  6083.3  324.12
  6103.7   328.5  6154.4  335.33  6160.6   337.8  6183.8   340.6  6189.9  342.78
  6219.3  346.24  6225.5  348.91  6281.7  356.86  6319.8  361.71  6333.3  361.98
#Mann= 8 ,-1 , 0
  4124.6     .16       0  4176.7     .12       0  4208.3     .16       0
  4393.3     .16       0  4998.4     .03       0  5004.4     .16       0
  6103.7     .16       0  6281.7     .05       0
Bank Sta=4980.5,5022.6
XS Rating Curve= 0 ,0
Exp/Cntr=0.3,0.1

Type RM Length L Ch R = 1 ,17886   ,216,216,216
BEGIN DESCRIPTION:
DOTTIE BRANCH 34.0
END DESCRIPTION:
XS GIS Cut Line= 3
      3634684.92     10549883.86      3633830.79     10550107.81
      3632774.05     10551523.75
#Sta/Elev= 30
  4281.3  357.65  4297.1  355.29  4324.5   353.9  4338.5  350.56  4379.8  344.71
  4521.2  327.48  4526.4  324.54  4555.6  321.44  4561.6  319.67  4566.8  321.44
    4659  310.72  4723.2  306.19  4874.4  303.48  4979.4  303.39  4995.6  294.53
  5000.5  293.99    5001  293.99  5003.8  294.49  5010.5  302.89  5789.1  307.48
  5924.6  309.61  6274.8  310.06  6539.6  312.43  6610.5  313.52  6666.6  320.98
  6725.2   327.9  6752.2  333.44  6846.1  345.11  6881.5  346.78  6931.1  346.47
#Mann= 6 ,-1 , 0
  4281.3     .16       0  4526.4     .16       0    5001     .05       0
  5010.5     .16       0  6539.6     .16       0  6666.6     .05       0
#XS Ineff= 1 ,-1
  5539.2 6645.45316.3503
Permanent Ineff=
       F
Bank Sta=4979.4,5010.5
XS Rating Curve= 0 ,0
Exp/Cntr=0.3,0.1

Type RM Length L Ch R = 1 ,17670   ,161,161,161
BEGIN DESCRIPTION:
DOTTIE BRANCH 33.0
END DESCRIPTION:
XS GIS Cut Line= 2
      3634726.66     10549659.89      3632103.13     10550331.38
#Sta/Elev= 30
  4217.6  359.15  4307.5   352.6  4402.9  348.52  4520.2  331.94  4617.1  323.04
  4689.4   313.5  4782.3  307.72  4923.1  302.68  4988.7  303.09  5001.7  294.39
  5004.5  293.89  5007.7  294.39  5009.9  300.56  5019.7  302.53  5391.3  304.08
  5422.3  302.21  5448.5  304.09  5647.4  304.21  6014.6  313.58  6131.9  326.86
  6213.5  333.16  6287.7  335.09  6423.5  330.65  6568.1  339.64  6588.7  339.19
  6616.5  342.73  6637.4  342.34  6779.7   351.7    6888  355.47  6925.7  354.39
#Mann= 7 ,-1 , 0
  4217.6     .16       0  4617.1     .16       0  5001.7     .07       0
  5007.7     .16       0  6014.6     .05       0  6287.7     .16       0
  6637.4     .05       0
Bank Sta=4988.7,5019.7
XS Rating Curve= 0 ,0
Exp/Cntr=0.3,0.1

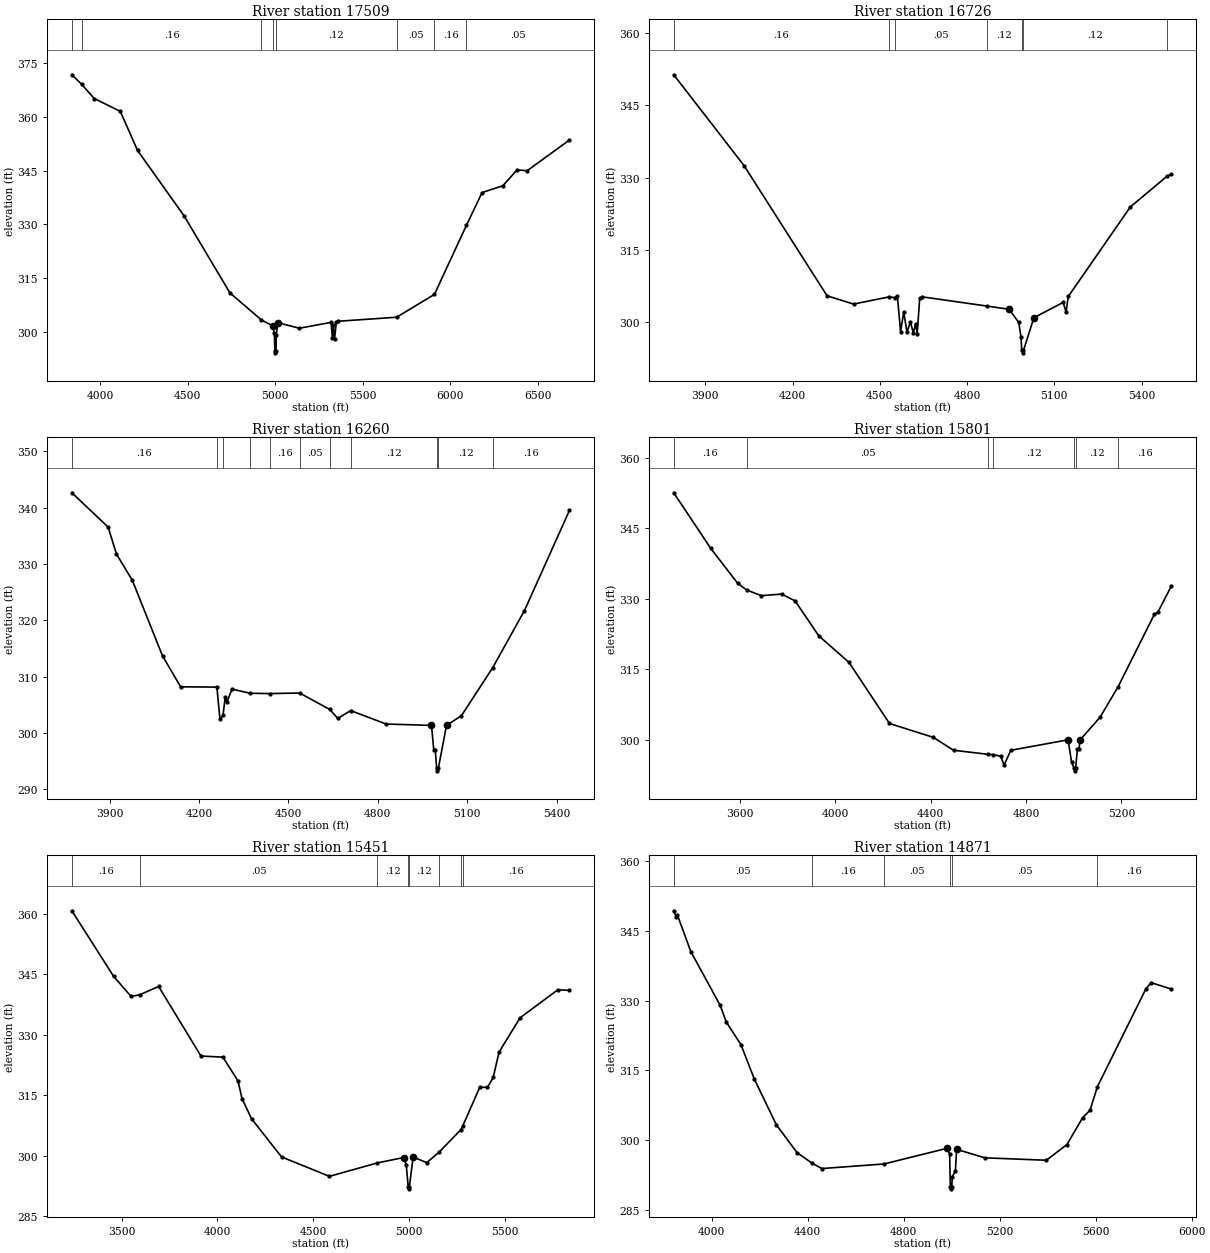
Type RM Length L Ch R = 1 ,17509   ,783,783,783
BEGIN DESCRIPTION:
DOTTIE BRANCH 32.0
END DESCRIPTION:
XS GIS Cut Line= 3
      3635013.09     10549331.77      3634002.67     10549691.14
      3632253.61     10549961.83
#Sta/Elev= 30
  3839.1  371.77  3895.6  369.07  3966.8  365.14  4115.7  361.56  4214.3  350.64
  4480.4  332.33  4742.1  310.83  4921.9  303.27  4985.5  301.65  4995.6  299.61
    4999  294.59  5001.7  294.09    5005  294.59    5007  299.15  5015.8  302.51
  5138.2  300.96  5319.4   302.6  5327.4  298.29  5332.4   301.8  5339.6     298
  5349.7  302.68  5359.9  302.91    5694  304.04    5910  310.41  6093.1  329.73
  6182.4  338.87  6300.9  340.77  6381.9   345.2  6439.7  344.96  6681.4  353.55
#Mann= 8 ,-1 , 0
  3839.1     .12       0  3895.6     .16       0  4921.9     .12       0
  4985.5     .07       0    5005     .12       0    5694     .05       0
    5910     .16       0  6093.1     .05       0
Bank Sta=4985.5,5015.8
XS Rating Curve= 0 ,0
Exp/Cntr=0.3,0.1

Type RM Length L Ch R = 1 ,16726   ,466,466,466
BEGIN DESCRIPTION:
DOTTIE BRANCH 31.0
END DESCRIPTION:
XS GIS Cut Line= 3
      3634349.59      10549010.2      3633249.61     10549510.19
      3632749.59     10549560.19
#Sta/Elev= 30
  3791.3  351.36  4032.9  332.49  4318.5   305.4  4409.7  303.68  4530.5  305.16
  4553.6  305.03  4560.2  305.36  4571.2  297.95  4582.2  302.02  4593.2  297.87
  4605.2  299.93  4615.1  297.65  4622.8   299.6  4628.3  297.51  4637.1  304.94
  4645.9  305.18  4867.9  303.27  4944.7  302.59  4977.6  299.85  4985.3  296.84
  4987.8  294.04  4990.5  293.54  4993.8  294.04  5029.7  300.85  5130.2  304.03
  5140.3  302.04  5147.8  305.26  5361.4  323.89  5486.9  330.24  5502.1   330.7
#Mann= 7 ,-1 , 0
  3791.3     .16       0  4530.5     .12       0  4553.6     .05       0
  4867.9     .12       0  4987.8     .07       0  4993.8     .12       0
  5486.9     .16       0
Bank Sta=4944.7,5029.7
XS Rating Curve= 0 ,0
Exp/Cntr=0.3,0.1

Type RM Length L Ch R = 1 ,16260   ,459,459,459
BEGIN DESCRIPTION:
DOTTIE BRANCH 30.0
END DESCRIPTION:
XS GIS Cut Line= 3
      3634199.64     10548960.18      3632999.61     10549160.19
      3632549.66     10549210.18
#Sta/Elev= 30
  3773.5  342.65  3895.2  336.56  3923.1  331.77  3976.3  327.11  4077.7  313.67
  4138.5  308.19  4260.1  308.14  4270.3  302.43  4280.4   303.1    4288  306.35
  4293.1  305.42  4310.8  307.79  4371.2  307.05  4436.6  306.99  4537.5  307.09
  4638.4  304.18  4665.7  302.58  4708.7  303.97  4827.9  301.58  4979.9  301.34
  4987.5  297.05  4992.6  297.05  4997.1  293.77  4999.9  293.27  5003.1  293.77
  5030.3  301.33  5080.6  303.08  5185.1  311.57  5291.9  321.74  5442.8  339.52
#Mann= 11 ,-1 , 0
  3773.5     .16       0  4260.1     .05       0  4280.4     .16       0
  4371.2     .05       0  4436.6     .16       0  4537.5     .05       0
  4638.4     .16       0  4708.7     .12       0  4997.1     .07       0
  5003.1     .12       0  5185.1     .16       0
Bank Sta=4979.9,5030.3
XS Rating Curve= 0 ,0
Exp/Cntr=0.3,0.1

Type RM Length L Ch R = 1 ,15801   ,350,350,350
BEGIN DESCRIPTION:
DOTTIE BRANCH 29.0
END DESCRIPTION:
XS GIS Cut Line= 3
      3633999.59      10547560.2      3632799.61     10548760.19
      3632499.65     10549010.16
#Sta/Elev= 30
    3322  352.51  3477.5  340.67  3590.7  333.23  3627.8  331.84  3689.7  330.63
  3774.5  330.96  3831.1  329.52  3930.1  322.11  4057.4  316.43  4227.1  303.44
  4410.9  300.49  4495.8  297.75  4641.7  296.88  4660.5  296.82  4693.8  296.48
  4707.9  294.59  4736.2  297.74  4976.6  299.97  4990.8  295.27  5001.9  293.87
  5004.6  293.37  5007.9  293.87  5015.5  297.97  5022.3  297.97  5026.2  299.92
  5110.8  304.79  5186.3  311.26  5338.6  326.68  5352.9   327.1  5409.5  332.66
#Mann= 7 ,-1 , 0
    3322     .16       0  3627.8     .05       0  4641.7     .16       0
  4660.5     .12       0  5001.9     .07       0  5007.9     .12       0
  5186.3     .16       0
Bank Sta=4976.6,5026.2
XS Rating Curve= 0 ,0
Exp/Cntr=0.3,0.1

Type RM Length L Ch R = 1 ,15451   ,580,580,580
BEGIN DESCRIPTION:
DOTTIE BRANCH 28.0
END DESCRIPTION:
XS GIS Cut Line= 3
      3634023.47     10547420.34      3632481.84     10548581.77
      3632429.88     10549246.77
#Sta/Elev= 30
  3240.8  360.72  3458.5  344.47  3550.2  339.47    3596  339.91  3693.8  341.95
  3914.5   324.7  4029.1  324.43  4108.2  318.51    4129  314.12    4179  309.13
  4335.1  299.69  4585.3  294.87  4834.5  298.19  4972.2  299.53    4986  297.78
  4996.3  292.27    4999  291.77  5002.3  292.27  5022.2  299.67    5093  298.26
    5157  300.84  5271.7  306.46  5279.9  307.24    5370  316.97  5410.1  316.92
  5440.2   319.4  5470.3  325.67  5580.6   334.2  5776.8  341.11    5838     341
#Mann= 8 ,-1 , 0
  3240.8     .16       0    3596     .05       0  4834.5     .12       0
  4996.3     .07       0  5002.3     .12       0    5157     .05       0
  5271.7     .12       0  5279.9     .16       0
Bank Sta=4972.2,5022.2
XS Rating Curve= 0 ,0
Exp/Cntr=0.3,0.1

Type RM Length L Ch R = 1 ,14871   ,619,619,619
BEGIN DESCRIPTION:
DOTTIE BRANCH 27.0
END DESCRIPTION:
XS GIS Cut Line= 4
      3633599.64     10547560.18      3632499.61     10547960.19
      3631899.61     10548310.19      3631723.04     10548419.31
#Sta/Elev= 30
  3842.6  349.24  3852.6  347.92  3857.9  348.34  3913.8  340.49  4036.2  328.96
  4061.4   325.4  4122.6  320.54  4178.5  313.14  4270.3  303.34  4356.7  297.36
  4419.9  295.09  4459.8  293.97  4718.2  294.95  4981.2  298.31  4991.8  297.14
  4994.8  290.12  4997.6  289.62  5000.8  290.12  5003.1  292.17    5016  293.53
    5021  298.09  5138.4  296.27  5394.7  295.75  5480.7  299.12  5545.7  304.87
  5576.7  306.48  5607.2   311.5    5810  332.57  5831.3  333.83  5915.3  332.45
#Mann= 6 ,-1 , 0
  3842.6     .05       0  4419.9     .16       0  4718.2     .05       0
  4994.8     .03       0  5000.8     .05       0  5607.2     .16       0
Bank Sta=4981.2,5021
XS Rating Curve= 0 ,0
Exp/Cntr=0.3,0.1