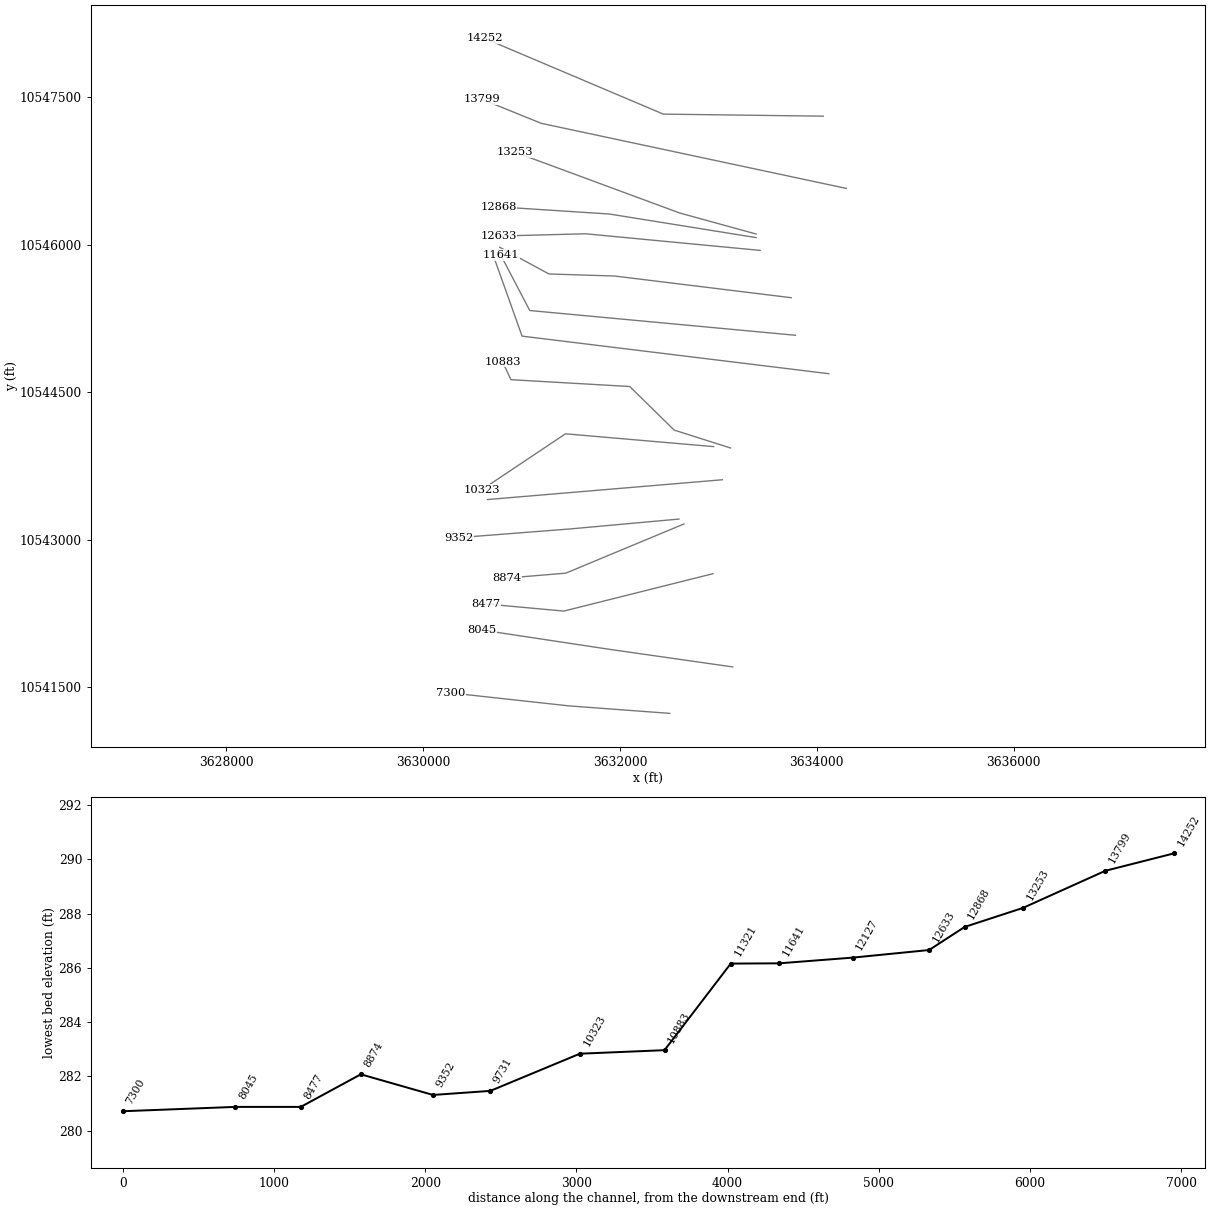
HEC-RAS study DOTTIE BRANCH.prj: DOTTIE BRANCH Base Level Engineering

--- DOTTIE BRANCH.g01 (geometry) --- (continued)

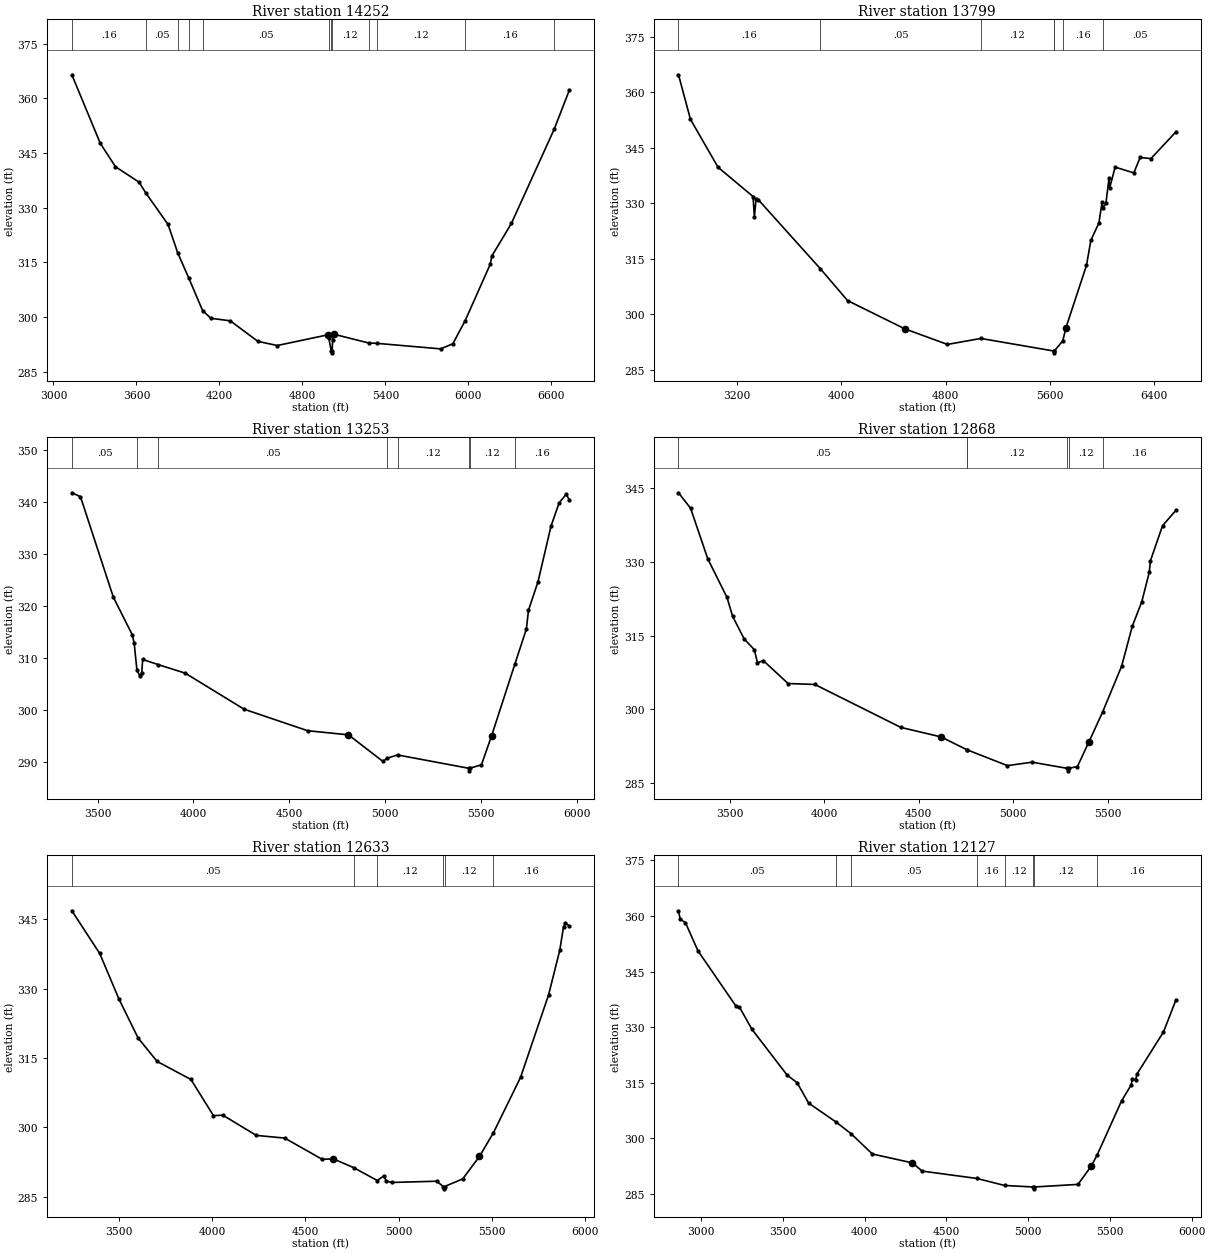
Type RM Length L Ch R = 1 ,14252   ,453,453,453
BEGIN DESCRIPTION:
DOTTIE BRANCH 26.0
END DESCRIPTION:
XS GIS Cut Line= 3
      3634065.15     10547305.73      3632440.17     10547326.56
      3630623.58     10548096.92
#Sta/Elev= 30
  3132.8  366.46  3338.4  347.67  3448.4  341.24  3618.4  337.03  3666.7  334.11
  3828.4  325.43  3899.3  317.56  3979.6  310.63  4078.5   301.8  4138.4  299.69
  4278.4     299  4478.5  293.36  4618.5  292.23  4988.5  295.19  4990.9  294.33
  5009.2  290.72  5011.9  290.22  5015.2  290.72  5019.2  293.83  5030.1   295.3
  5278.6  292.93  5341.9  292.81  5800.2  291.31  5888.2   292.7  5977.2  299.02
  6158.7  314.49  6170.6  316.78  6311.6  325.69  6621.5  351.54  6731.1  362.27
#Mann= 12 ,-1 , 0
  3132.8     .16       0  3666.7     .05       0  3899.3     .16       0
  3979.6     .12       0  4078.5     .05       0  4990.9     .12       0
  5009.2     .07       0  5015.2     .12       0  5278.6     .16       0
  5341.9     .12       0  5977.2     .16       0  6621.5     .05       0
Bank Sta=4988.5,5030.1
XS Rating Curve= 0 ,0
Exp/Cntr=0.3,0.1

Type RM Length L Ch R = 1 ,13799   ,546,546,546
BEGIN DESCRIPTION:
DOTTIE BRANCH 25.0
END DESCRIPTION:
XS GIS Cut Line= 3
      3634299.53     10546571.36      3631200.59     10547232.81
      3630596.44     10547477.59
#Sta/Elev= 30
  2749.4  364.68  2841.3  352.64  3053.1   339.7  3321.9   331.8  3332.2  326.31
  3345.1  331.15  3362.8  330.92  3838.7   312.3  4047.9  303.69  4487.4  296.06
  4814.8  291.85  5071.4  293.47  5629.8  290.08  5632.6  289.58  5635.8  290.08
  5700.7  292.85  5724.9  296.38  5882.5   313.2  5916.1  319.97  5978.1  324.68
  6002.2  330.27  6008.1  328.67  6031.7  330.01  6055.9  336.81  6061.2  334.19
  6102.6  339.74  6246.2  338.18  6294.4  342.35  6377.5  342.04    6570  349.28
#Mann= 7 ,-1 , 0
  2749.4     .16       0  3838.7     .05       0  5071.4     .12       0
  5629.8     .07       0  5635.8     .12       0  5700.7     .16       0
  6008.1     .05       0
Bank Sta=4487.4,5724.9
XS Rating Curve= 0 ,0
Exp/Cntr=0.3,0.1

Type RM Length L Ch R = 1 ,13253   ,385,385,385
BEGIN DESCRIPTION:
DOTTIE BRANCH 24.0
END DESCRIPTION:
XS GIS Cut Line= 3
      3633382.89     10546107.81      3632606.84     10546321.35
       3630929.8     10546941.13
#Sta/Elev= 30
  3366.2  341.75  3411.1     341  3582.4  321.65  3680.8  314.43  3690.8  312.86
  3705.3  307.62  3722.2  306.38  3730.3   307.1  3735.5  309.65  3815.8  308.67
  3957.5  307.01  4263.7  300.08  4594.6  295.94  4807.8  295.14  4986.8  290.04
  5010.4  290.65  5063.7  291.27  5433.8  288.71  5436.6  288.21  5439.8  288.71
  5500.8  289.37  5554.1     295  5675.6  308.82    5735  315.52    5746  319.12
  5795.8  324.65  5863.3  335.32  5905.9  339.83  5942.5  341.46    5959  340.37
#Mann= 8 ,-1 , 0
  3366.2     .05       0  3705.3     .16       0  3815.8     .05       0
  5010.4     .16       0  5063.7     .12       0  5433.8     .07       0
  5439.8     .12       0  5675.6     .16       0
Bank Sta=4807.8,5554.1
XS Rating Curve= 0 ,0
Exp/Cntr=0.3,0.1

Type RM Length L Ch R = 1 ,12868   ,235,235,235
BEGIN DESCRIPTION:
DOTTIE BRANCH 23.0
END DESCRIPTION:
XS GIS Cut Line= 3
      3633382.85     10546071.36      3631893.29     10546310.94
      3630768.26     10546383.86
#Sta/Elev= 30
  3226.7  344.04  3290.8  340.89  3381.9  330.61  3483.2  322.81  3513.6  318.92
  3574.4  314.34  3628.7  312.13  3645.3  309.45  3675.6  309.94  3807.3  305.26
  3949.1  305.07  4404.9  296.34  4617.6  294.41  4755.3  291.79  4755.5  291.79
  4969.6  288.57  5099.9  289.27  5287.2  288.01    5290  287.51  5293.2  288.01
  5340.4  288.39  5400.5  293.32  5474.3   299.5    5575  308.82    5631  316.89
  5681.1  321.85  5721.2  327.87  5727.5  330.23  5791.3  337.33  5862.8   340.5
#Mann= 6 ,-1 , 0
  3226.7     .05       0  4755.3     .16       0  4755.5     .12       0
  5287.2     .07       0  5293.2     .12       0  5474.3     .16       0
Bank Sta=4617.6,5400.5
XS Rating Curve= 0 ,0
Exp/Cntr=0.3,0.1

Type RM Length L Ch R = 1 ,12633   ,506,506,506
BEGIN DESCRIPTION:
DOTTIE BRANCH 22.0
END DESCRIPTION:
XS GIS Cut Line= 3
       3633424.5     10545941.15      3631649.61     10546110.19
      3630768.34     10546086.98
#Sta/Elev= 30
  3249.9  346.87  3399.2  337.62  3502.2  327.75  3605.1   319.3  3706.8  314.24
  3887.7  310.34  4008.2  302.51  4058.4  302.61    4238  298.23  4389.9  297.65
  4590.8  293.05  4651.1  293.14  4761.2  291.21  4885.7  288.46  4922.3  289.52
  4932.4  288.38  4962.5  288.04  5202.9  288.31  5239.9  287.16  5242.6  286.66
  5245.9  287.16  5342.9   288.8    5433  293.68  5507.2  298.76    5653   310.8
  5803.1  328.65  5863.1  338.33  5883.1  343.39  5893.1  344.22  5914.4  343.58
#Mann= 6 ,-1 , 0
  3249.9     .05       0  4761.2     .16       0  4885.7     .12       0
  5239.9     .07       0  5245.9     .12       0  5507.2     .16       0
Bank Sta=4651.1,5433
XS Rating Curve= 0 ,0
Exp/Cntr=0.3,0.1

Type RM Length L Ch R = 1 ,12127   ,486,486,486
BEGIN DESCRIPTION:
DOTTIE BRANCH 21.0
END DESCRIPTION:
XS GIS Cut Line= 4
      3633739.69      10545460.3      3631945.38     10545680.73
      3631278.71     10545701.56      3630778.74     10545972.38
#Sta/Elev= 30
    2861  361.38  2871.2  359.17  2903.8  358.15    2980  350.58  3213.7  335.59
    3234  335.38  3310.3  329.41    3526  317.03  3586.5  315.02    3657  309.51
  3825.5  304.38  3916.6  301.26  4047.1  295.77    4291  293.39  4352.2  291.16
  4685.4  289.19    4856  287.29  5031.7  286.88  5034.5  286.38  5037.7  286.88
  5304.9  287.58  5385.7   292.5  5423.4  295.64  5571.1  310.09  5630.5  314.44
  5636.8  316.09  5658.6  315.83  5664.6  317.28  5827.9  328.71  5904.4  337.38
#Mann= 8 ,-1 , 0
    2861     .05       0  3825.5     .12       0  3916.6     .05       0
  4685.4     .16       0    4856     .12       0  5031.7     .07       0
  5037.7     .12       0  5423.4     .16       0
Bank Sta=4291,5385.7
XS Rating Curve= 0 ,0
Exp/Cntr=0.3,0.1

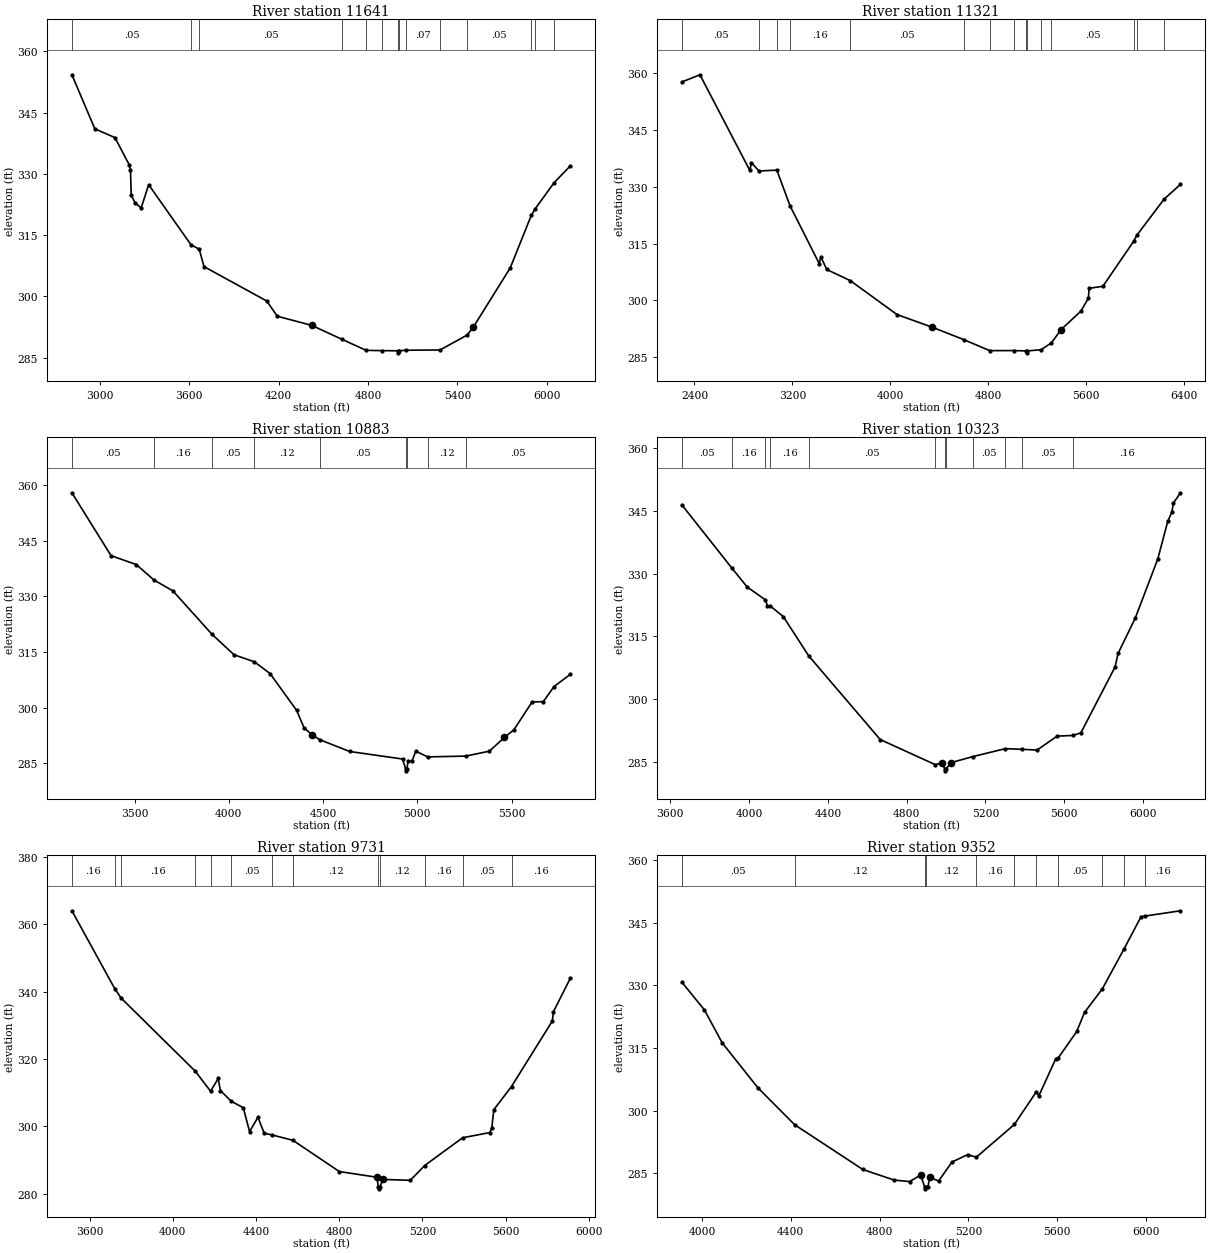
Type RM Length L Ch R = 1 ,11641   ,320,320,320
BEGIN DESCRIPTION:
DOTTIE BRANCH 20.0
END DESCRIPTION:
XS GIS Cut Line= 3
      3633783.17     10545078.34      3631083.48     10545330.08
      3630788.33     10545894.34
#Sta/Elev= 30
  2810.9  354.27  2965.1  341.02  3100.4  338.88  3196.1  332.21  3204.5  330.96
  3209.5  324.77  3236.3  322.84  3276.5  321.68  3326.7  327.34  3611.7   312.6
  3666.1  311.58  3698.3  307.29  4120.1  298.86  4190.4  295.14  4421.4   292.9
  4625.4  289.48  4787.2  286.78  4895.1  286.71  5000.9  286.67  5003.7  286.17
  5006.9  286.67  5056.7  286.81  5284.3  286.87  5465.9  290.52  5506.1  292.38
  5755.5  306.97  5897.1  319.85  5923.6  321.46  6050.6  327.86  6159.1  331.95
#Mann= 14 ,-1 , 0
  2810.9     .05       0  3611.7     .16       0  3666.1     .05       0
  4625.4     .16       0  4787.2      .1       0  4895.1     .12       0
  5000.9     .07       0  5006.9     .12       0  5056.7     .07       0
  5284.3     .12       0  5465.9     .05       0  5897.1     .07       0
  5923.6     .16       0  6050.6     .05       0
Bank Sta=4421.4,5506.1
XS Rating Curve= 0 ,0
Exp/Cntr=0.3,0.1

Type RM Length L Ch R = 1 ,11321   ,438,438,438
BEGIN DESCRIPTION:
DOTTIE BRANCH 19.0
END DESCRIPTION:
XS GIS Cut Line= 3
      3634121.69     10544687.72      3631005.35     10545069.67
      3630693.06     10545945.82
#Sta/Elev= 30
    2299  357.77  2444.9  359.65  2851.9  334.38  2865.3  336.42  2926.9  334.22
  3072.8  334.45  3179.9  325.06  3419.4  309.71  3431.8  311.57  3479.9  308.19
  3673.1  305.23  4054.1  296.27  4337.2  292.98  4598.3  289.66  4811.3  286.74
  5011.5  286.76    5109  286.66  5111.7  286.16    5115  286.66  5230.4  286.98
  5314.7  288.79  5394.1  292.31  5555.3  297.18    5617   300.6  5622.3  303.21
  5734.9  303.74  5985.3   315.6  6011.8  317.22  6234.9  326.78  6368.8  330.69
#Mann= 15 ,-1 , 0
    2299     .05       0  2926.9     .16       0  3072.8     .05       0
  3179.9     .16       0  3673.1     .05       0  4598.3     .16       0
  4811.3     .07       0  5011.5     .12       0    5109     .07       0
    5115     .12       0  5230.4     .12       0  5314.7     .05       0
  5985.3     .07       0  6011.8     .16       0  6234.9     .05       0
Bank Sta=4337.2,5394.1
XS Rating Curve= 0 ,0
Exp/Cntr=0.3,0.1

Type RM Length L Ch R = 1 ,10883   ,560,560,560
BEGIN DESCRIPTION:
DOTTIE BRANCH 18.0
END DESCRIPTION:
XS GIS Cut Line= 5
      3633123.43     10543932.51      3632550.49      10544114.8
       3632099.1     10544557.51      3630892.51     10544626.96
       3630805.7     10544809.26
#Sta/Elev= 30
  3167.5  357.97  3375.2  341.01  3509.4   338.6  3603.4  334.41  3702.7  331.55
    3910  319.83  4027.7  314.27  4134.9   312.4  4218.6  309.22    4360  299.25
  4399.3  294.53  4440.6  292.77  4481.7  291.38  4640.9  288.19  4921.3  286.16
  4938.4  283.47  4941.1  282.97  4944.4  283.47  4951.4  285.69  4971.4  285.53
  4991.5  288.27  5055.3  286.73  5256.7  286.95  5382.1  288.27  5462.2  291.99
  5512.3  294.05  5608.5  301.52  5668.5  301.65  5725.2  305.71  5811.5     309
#Mann= 9 ,-1 , 0
  3167.5     .05       0  3603.4     .16       0    3910     .05       0
  4134.9     .12       0  4481.7     .05       0  4938.4    .035       0
  4944.4     .05       0  5055.3     .12       0  5256.7     .05       0
Bank Sta=4440.6,5462.2
XS Rating Curve= 0 ,0
Exp/Cntr=0.3,0.1

Type RM Length L Ch R = 1 ,10323   ,592,592,592
BEGIN DESCRIPTION:
DOTTIE BRANCH 17.0
END DESCRIPTION:
XS GIS Cut Line= 3
      3632951.47     10543946.53      3631446.25     10544076.74
      3630599.57     10543510.16
#Sta/Elev= 30
  3660.3  346.35  3911.3  331.41  3990.6  326.79  4083.4   323.7  4093.8  322.25
  4108.9  322.21  4174.1  319.71    4303  310.32  4665.9  290.32  4945.7  284.31
  4977.1  284.71  4994.1  283.34  4996.9  282.84  5000.1  283.34  5027.2  284.82
  5134.5  286.23  5300.6  288.14    5383     288  5461.8   287.8  5563.8  291.14
  5645.6   291.3  5684.5  291.94  5858.1   307.7  5873.1   310.9  5960.2  319.34
  6074.3  333.43  6125.3  342.49  6146.3  344.71  6153.8  346.85  6189.9  349.31
#Mann= 12 ,-1 , 0
  3660.3     .05       0  3911.3     .16       0  4083.4     .05       0
  4108.9     .16       0    4303     .05       0  4945.7     .12       0
  4994.1     .07       0  5000.1     .12       0  5134.5     .05       0
  5300.6     .16       0    5383     .05       0  5645.6     .16       0
Bank Sta=4977.1,5027.2
XS Rating Curve= 0 ,0
Exp/Cntr=0.3,0.1

Type RM Length L Ch R = 1 ,9731    ,379,379,379
BEGIN DESCRIPTION:
DOTTIE BRANCH 16.0
END DESCRIPTION:
XS GIS Cut Line= 2
      3633040.72     10543609.72      3630653.19     10543408.45
#Sta/Elev= 30
  3514.6  363.99    3721  340.83  3751.7  338.05  4108.4  316.34  4181.2  310.43
  4218.2  314.23  4228.2  310.65  4280.1   307.5  4338.6  305.52  4368.7  298.44
  4408.9   302.7    4439  297.97  4477.9  297.45  4576.8  295.88  4800.3   286.6
  4980.9  284.91  4987.9  281.97  4990.7  281.47  4993.9  281.97    5011  284.26
  5141.5     284  5210.6  288.39    5393  296.63  5522.8  298.16  5532.8  299.39
  5542.9  304.97  5627.9  311.84  5823.9  331.25  5829.6  334.05  5910.6  343.96
#Mann= 13 ,-1 , 0
  3514.6     .16       0    3721     .05       0  3751.7     .16       0
  4108.4     .12       0  4181.2     .16       0  4280.1     .05       0
  4477.9     .08       0  4576.8     .12       0  4987.9     .07       0
  4993.9     .12       0  5210.6     .16       0    5393     .05       0
  5627.9     .16       0
Bank Sta=4980.9,5011
XS Rating Curve= 0 ,0
Exp/Cntr=0.3,0.1

Type RM Length L Ch R = 1 ,9352    ,478,478,478
BEGIN DESCRIPTION:
DOTTIE BRANCH 15.0
END DESCRIPTION:
XS GIS Cut Line= 3
      3632599.59     10543210.19      3631499.61     10543110.19
      3630363.88     10543021.62
#Sta/Elev= 30
  3910.7  330.68  4011.1  324.13  4091.4  316.23  4252.1  305.48  4417.3  296.66
    4724  285.96  4864.6  283.42  4934.9  283.06  4985.1  284.62  5002.2  281.82
  5004.9  281.32  5008.2  281.82  5017.7  281.83  5025.3  284.06  5065.4  283.19
  5125.6  287.72  5195.8   289.5  5235.2  288.88  5406.5  296.71  5505.4  304.53
  5516.7  303.56    5593  312.44  5604.3  312.65  5687.3  318.95  5722.5  323.53
    5802   329.1  5900.9  338.76  5976.5  346.38  5994.6  346.56  6154.4  347.82
#Mann= 11 ,-1 , 0
  3910.7     .05       0  4417.3     .12       0  5002.2     .07       0
  5008.2     .12       0  5235.2     .16       0  5406.5     .05       0
  5505.4      .1       0  5604.3     .05       0    5802     .16       0
  5900.9     .05       0  5994.6     .16       0
Bank Sta=4985.1,5025.3
XS Rating Curve= 0 ,0
Exp/Cntr=0.3,0.1

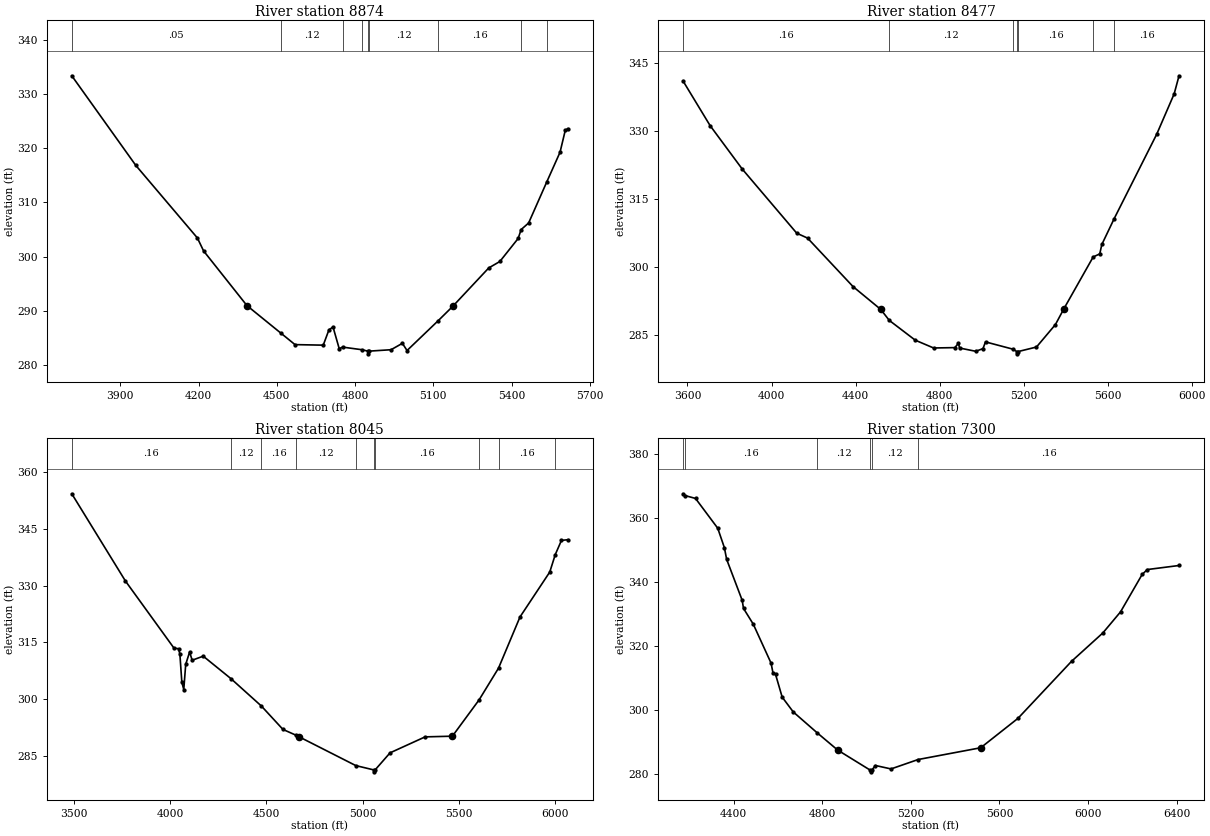
Type RM Length L Ch R = 1 ,8874    ,397,397,397
BEGIN DESCRIPTION:
DOTTIE BRANCH 14.0
END DESCRIPTION:
XS GIS Cut Line= 3
      3632649.57     10543160.17      3631449.61     10542660.19
      3630849.64     10542610.19
#Sta/Elev= 30
  3713.8  333.33  3959.1  316.82  4195.3  303.44  4219.1  301.05  4385.4  290.97
  4515.6  285.89  4569.6  283.78  4677.9  283.68  4699.6  286.49  4715.3  287.04
  4739.1  283.03  4752.1  283.32  4827.6  282.83  4848.3  282.58    4851  282.08
  4854.3  282.58  4937.9  282.84  4981.3  284.02  4999.1  282.69  5118.8   288.2
  5174.3  290.83  5312.3  297.91  5354.9   299.1  5425.2  303.35  5436.4  304.98
  5465.3   306.2  5535.4  313.83  5585.7  319.24  5605.8  323.29  5615.8  323.58
#Mann= 9 ,-1 , 0
  3713.8     .05       0  4515.6     .12       0  4752.1     .05       0
  4827.6     .12       0  4848.3     .07       0  4854.3     .12       0
  5118.8     .16       0  5436.4     .05       0  5535.4     .16       0
Bank Sta=4385.4,5174.3
XS Rating Curve= 0 ,0
Exp/Cntr=0.3,0.1

Type RM Length L Ch R = 1 ,8477    ,432,432,432
BEGIN DESCRIPTION:
DOTTIE BRANCH 13.0
END DESCRIPTION:
XS GIS Cut Line= 3
      3632945.21     10542654.86      3631429.58     10542274.65
       3630633.7     10542347.48
#Sta/Elev= 30
  3578.2  341.02  3707.7  331.14  3860.9  321.56  4120.1  307.45  4171.6  306.37
  4388.1  295.69  4519.6  290.68  4560.8  288.24  4684.2  283.89  4771.7  282.17
  4872.7  282.25  4890.1  283.21  4895.2  282.16  4972.4  281.44  5006.7  282.03
  5018.7  283.51  5149.2  281.91  5167.9  281.38  5170.6  280.88  5173.9  281.38
  5261.4  282.38  5351.6  287.33  5391.8   290.8  5531.3  302.22  5562.5  302.89
  5572.6  304.97    5631  310.63  5833.6  329.23  5916.9  338.14    5940  342.12
#Mann= 7 ,-1 , 0
  3578.2     .16       0  4560.8     .12       0  5149.2     .16       0
  5167.9     .07       0  5173.9     .16       0  5531.3     .05       0
    5631     .16       0
Bank Sta=4519.6,5391.8
XS Rating Curve= 0 ,0
Exp/Cntr=0.3,0.1

Type RM Length L Ch R = 1 ,8045    ,745,745,745
BEGIN DESCRIPTION:
DOTTIE BRANCH 12.0
END DESCRIPTION:
XS GIS Cut Line= 3
      3633145.23     10541707.06      3631881.32     10541887.61
       3630596.6     10542082.06
#Sta/Elev= 30
  3490.4   354.2  3768.8  331.21  4021.4  313.48  4044.7  313.35  4051.7  311.92
  4061.8  304.55  4071.9  302.59    4082  309.22  4102.2  312.47  4115.5  310.31
  4172.9  311.38  4316.7  305.46    4475  298.23    4587  292.06  4656.8  290.49
  4667.9  290.19  4965.1  282.53  5059.2  281.38  5061.9  280.88  5065.2  281.38
  5143.1  285.89  5325.1   290.1  5466.7  290.28  5605.6  299.87  5706.2  308.22
  5817.9  321.73  5972.4  333.57  6000.8  338.15  6033.1  341.91  6066.5  342.09
#Mann= 10 ,-1 , 0
  3490.4     .16       0  4316.7     .12       0    4475     .16       0
  4656.8     .12       0  4965.1     .16       0  5059.2     .07       0
  5065.2     .16       0  5605.6     .05       0  5706.2     .16       0
  6000.8     .05       0
Bank Sta=4667.9,5466.7
XS Rating Curve= 0 ,0
Exp/Cntr=0.3,0.1

Type RM Length L Ch R = 1 ,7300    ,369,369,369
BEGIN DESCRIPTION:
DOTTIE BRANCH 11.0
END DESCRIPTION:
XS GIS Cut Line= 3
      3632506.33     10541234.84      3631478.54     10541311.23
      3630277.19     10541443.17
#Sta/Elev= 30
  4171.2  367.65    4180  367.11  4228.1  366.19  4328.4  356.88  4358.4  350.79
  4368.5  347.17  4438.7  334.35  4444.7  331.81  4488.8  326.88    4569  314.72
  4577.4  311.76  4589.1  311.24  4619.2  304.08  4669.3  299.44    4777  292.93
  4869.8  287.52  5017.3  281.22    5020  280.72  5023.3  281.22  5040.3   282.7
  5110.5  281.63  5232.8  284.57  5515.3  288.25  5683.6  297.45  5925.1  315.26
  6066.7  324.15  6146.4  330.73  6243.9  342.42  6267.1  343.96  6410.4  345.23
#Mann= 6 ,-1 , 0
  4171.2     .05       0    4180     .16       0    4777     .12       0
  5017.3     .07       0  5023.3     .12       0  5232.8     .16       0
Bank Sta=4869.8,5515.3
XS Rating Curve= 0 ,0
Exp/Cntr=0.3,0.1