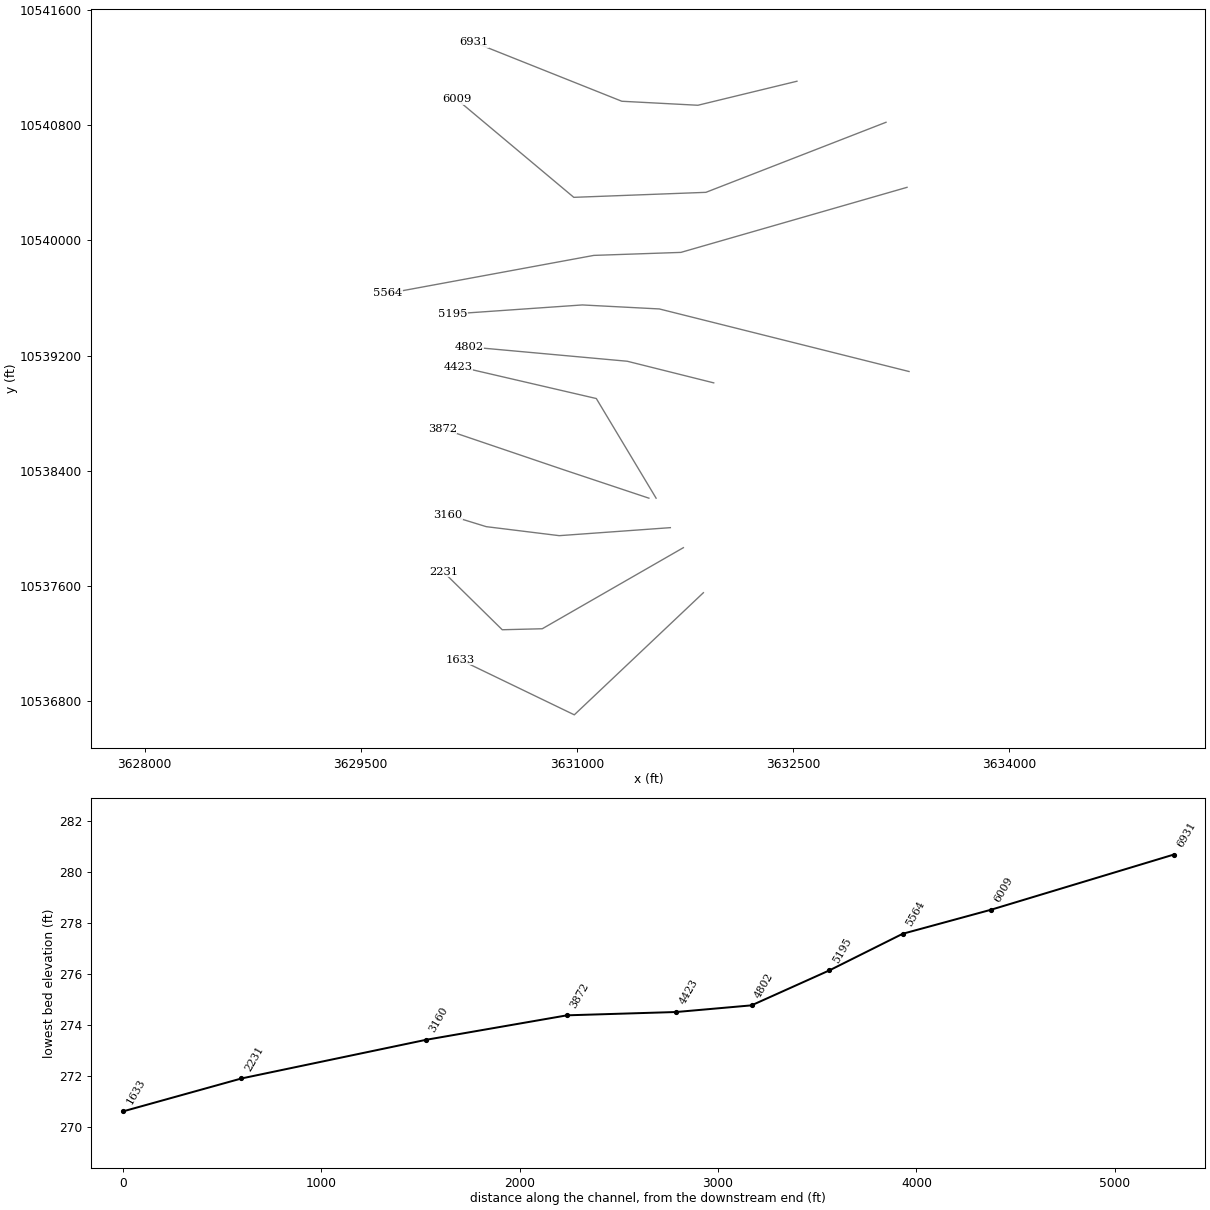
HEC-RAS study DOTTIE BRANCH.prj: DOTTIE BRANCH Base Level Engineering

--- DOTTIE BRANCH.g01 (geometry) --- (continued)

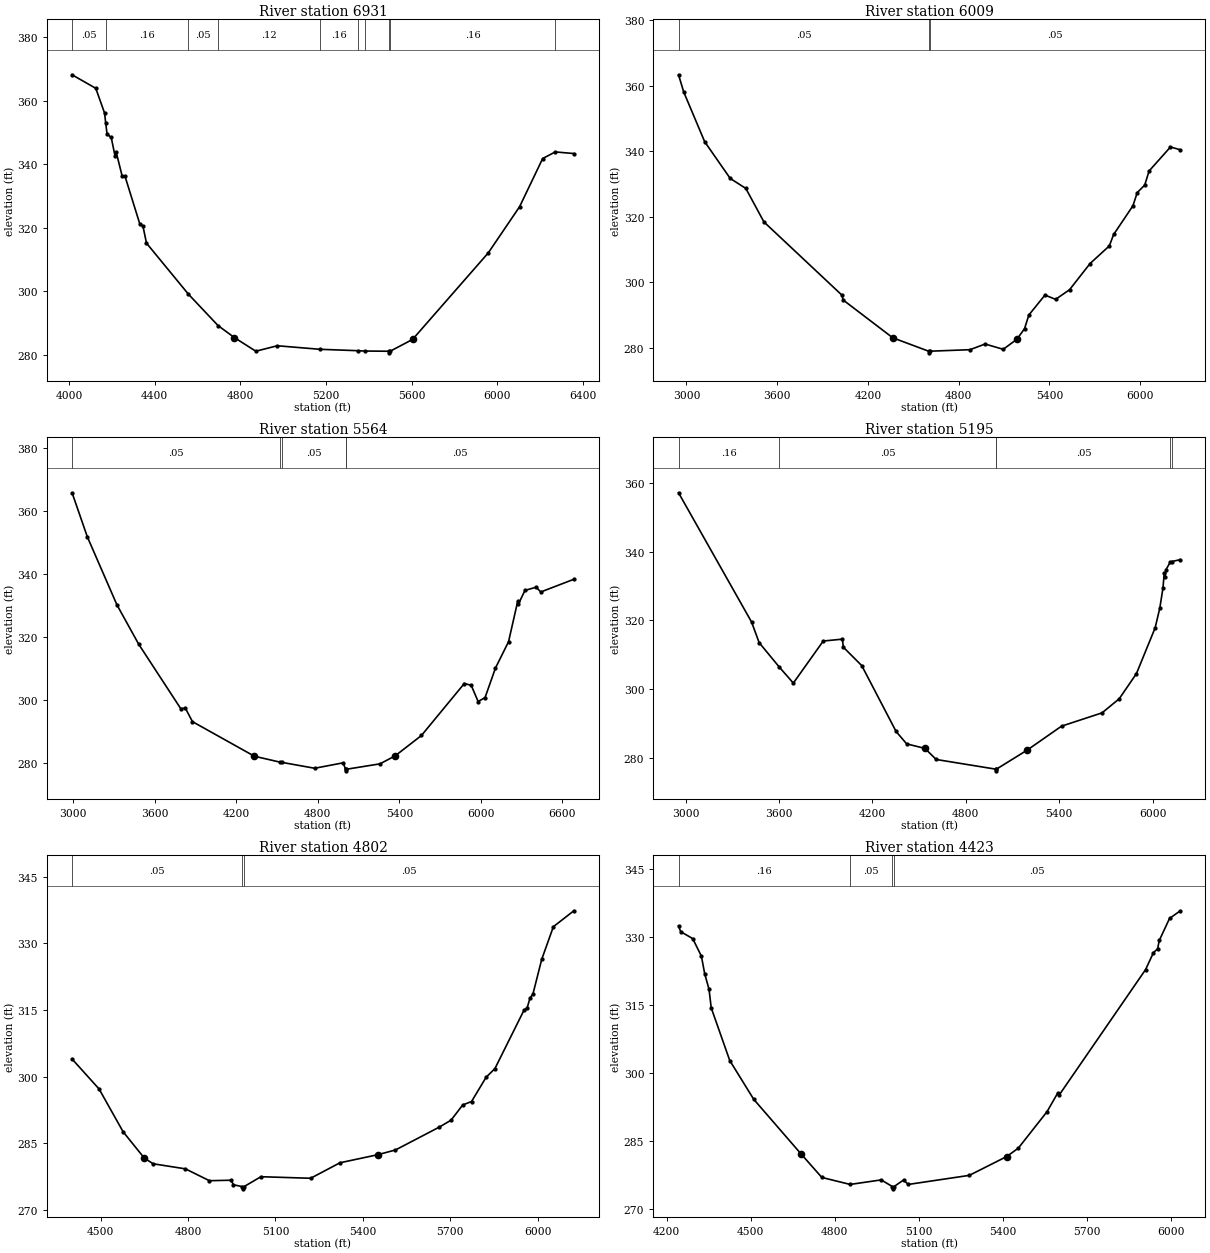
Type RM Length L Ch R = 1 ,6931    ,922,922,922
BEGIN DESCRIPTION:
DOTTIE BRANCH 10.0
END DESCRIPTION:
XS GIS Cut Line= 4
      3632527.12     10541102.89      3631839.65     10540936.23
      3631311.87       10540964.       3630284.4     10541373.61
#Sta/Elev= 30
  4014.9  368.22  4125.5  363.96  4166.7  356.15  4171.7  353.08  4178.5  349.46
  4197.6  348.53  4215.2   342.7  4220.3  344.01    4249  336.24  4262.1  336.23
  4331.3   321.2  4345.7  320.58  4362.2  315.21  4558.2  299.12  4696.3  289.25
  4772.4  285.48  4872.5  281.18  4972.7   282.9  5170.7  281.79  5349.9  281.34
  5381.7  281.24  5493.2  281.17    5496  280.67  5499.2  281.17  5604.1  284.89
  5957.2  312.12  6103.7  326.69  6211.3  341.84  6270.2  343.93  6356.9  343.42
#Mann= 10 ,-1 , 0
  4014.9     .05       0  4171.7     .16       0  4558.2     .05       0
  4696.3     .12       0  5170.7     .16       0  5349.9     .05       0
  5381.7     .16       0  5493.2     .07       0  5499.2     .16       0
  6270.2     .05       0
Bank Sta=4772.4,5604.1
XS Rating Curve= 0 ,0
Exp/Cntr=0.3,0.1

Type RM Length L Ch R = 1 ,6009    ,445,445,445
BEGIN DESCRIPTION:
DOTTIE BRANCH 9.0
END DESCRIPTION:
XS GIS Cut Line= 4
      3633145.18     10540818.16       3631895.2     10540332.06
      3630978.54     10540297.34        3630166.     10540977.92
#Sta/Elev= 30
  2947.5  363.42  2981.8  358.16  3120.5  342.97  3289.1  331.78  3392.6  328.71
  3512.1  318.49  4026.4   296.2  4037.2  294.61  4364.3   283.1  4601.5  279.01
  4604.2  278.51  4607.5  279.01  4874.7  279.47  4974.8   281.2  5094.8  279.59
  5184.9  282.65  5235.5  285.87  5264.1  290.06  5370.8  296.15  5441.1  294.84
  5533.5  297.79  5668.8  305.77  5796.3  311.16  5824.9  314.65  5952.4  323.41
    5981  327.45  6030.5  329.73  6059.1  334.03  6200.9  341.38  6265.9  340.51
#Mann= 3 ,-1 , 0
  2947.5     .05       0  4601.5     .03       0  4607.5     .05       0
Bank Sta=4364.3,5184.9
XS Rating Curve= 0 ,0
Exp/Cntr=0.3,0.1

Type RM Length L Ch R = 1 ,5564    ,369,369,369
BEGIN DESCRIPTION:
DOTTIE BRANCH 8.0
END DESCRIPTION:
XS GIS Cut Line= 4
        3633291.     10540366.77      3631721.59     10539915.39
      3631117.43     10539894.56      3629686.91     10539630.68
#Sta/Elev= 30
  2992.1  365.86  3104.6  351.85  3322.4  330.26  3482.6  317.76  3791.7  297.32
  3825.4  297.48    3878  293.19  4333.5  282.21  4520.4  280.35  4539.4  280.23
  4777.2  278.39  4987.3  280.12  5004.3  278.07  5007.1  277.57  5010.3  278.07
  5257.9  279.79  5369.8  282.34    5563   288.8  5878.2   305.3  5929.1  304.73
  5979.9  299.57  6030.8  300.83  6107.6  310.22  6203.6  318.56  6271.6  331.48
  6276.7  330.56  6324.6  334.87    6407  335.88  6440.8  334.36  6684.3   338.4
#Mann= 5 ,-1 , 0
  2992.1     .05       0  4520.4     .08       0  4539.4     .05       0
  5004.3     .03       0  5010.3     .05       0
Bank Sta=4333.5,5369.8
XS Rating Curve= 0 ,0
Exp/Cntr=0.3,0.1

Type RM Length L Ch R = 1 ,5195    ,393,393,393
BEGIN DESCRIPTION:
DOTTIE BRANCH 7.0
END DESCRIPTION:
XS GIS Cut Line= 4
      3633304.93       10539089.      3631572.29     10539523.03
      3631037.57     10539550.81      3630138.26     10539488.31
#Sta/Elev= 30
    2955  357.13  3424.4  319.46  3472.5   313.5  3602.8  306.33  3692.4   301.7
  3884.5  313.95  4008.1   314.5  4013.2  312.17  4131.7   306.8  4352.2  287.62
    4420     284  4537.8  282.67  4609.9  279.45  4991.2  276.64  4993.9  276.14
  4997.2  276.64  5194.5  282.18  5414.9  289.15  5675.5  293.03  5785.6  297.13
  5896.1  304.45  6016.4   317.8  6046.4  323.58  6066.5  329.35  6075.2  333.88
  6080.2  332.66  6086.5  334.78  6113.6  336.94  6122.5  337.09  6178.1  337.66
#Mann= 6 ,-1 , 0
    2955     .16       0  3602.8     .05       0  4991.2     .03       0
  4997.2     .05       0  6113.6     .08       0  6122.5     .05       0
Bank Sta=4537.8,5194.5
XS Rating Curve= 0 ,0
Exp/Cntr=0.3,0.1

Type RM Length L Ch R = 1 ,4802    ,379,379,379
BEGIN DESCRIPTION:
DOTTIE BRANCH 6.0
END DESCRIPTION:
XS GIS Cut Line= 3
      3631949.61     10539010.19      3631349.61     10539160.19
      3630249.61     10539260.19
#Sta/Elev= 30
  4401.8  303.99  4494.6  297.24    4577  287.62  4649.2  281.74  4680.1  280.41
  4790.9  279.27  4873.4   276.6  4948.1  276.71  4955.8  275.69  4986.3  275.27
  4989.1  274.77  4992.3  275.27  5050.4   277.5  5221.1  277.15  5321.5  280.63
    5452  282.46  5512.3  283.52  5662.9  288.67  5703.1  290.22  5743.2  293.65
  5773.4  294.42  5823.6  299.89  5853.7  301.83  5954.1  315.04  5964.1  315.42
  5974.2  317.72  5984.2  318.59  6014.4  326.41  6054.5  333.77  6124.8  337.35
#Mann= 3 ,-1 , 0
  4401.8     .05       0  4986.3     .03       0  4992.3     .05       0
Bank Sta=4649.2,5452
XS Rating Curve= 0 ,0
Exp/Cntr=0.3,0.1

Type RM Length L Ch R = 1 ,4423    ,551,551,551
BEGIN DESCRIPTION:
DOTTIE BRANCH 5.0
END DESCRIPTION:
XS GIS Cut Line= 3
       3631549.6      10538210.2      3631134.79      10538901.5
      3630176.43     10539123.73
#Sta/Elev= 30
  4242.6  332.42  4250.4  331.14  4293.1  329.63  4324.2  325.75  4335.9  321.89
  4351.4  318.45  4359.2  314.37  4425.3  302.77  4510.8  294.23  4679.9  282.18
  4753.8  277.02  4854.8  275.48  4965.6  276.48  5005.4  275.01  5008.1  274.51
  5011.4  275.01  5045.1  276.45  5062.2  275.48    5280  277.48  5413.4  281.63
  5454.5  283.46  5557.2  291.51  5594.7  295.55  5599.8  295.11  5908.8  322.81
  5936.9  326.55  5951.4  327.35  5957.5  329.21  5994.1  334.06  6032.6  335.75
#Mann= 4 ,-1 , 0
  4242.6     .16       0  4854.8     .05       0  5005.4     .03       0
  5011.4     .05       0
Bank Sta=4679.9,5413.4
XS Rating Curve= 0 ,0
Exp/Cntr=0.3,0.1

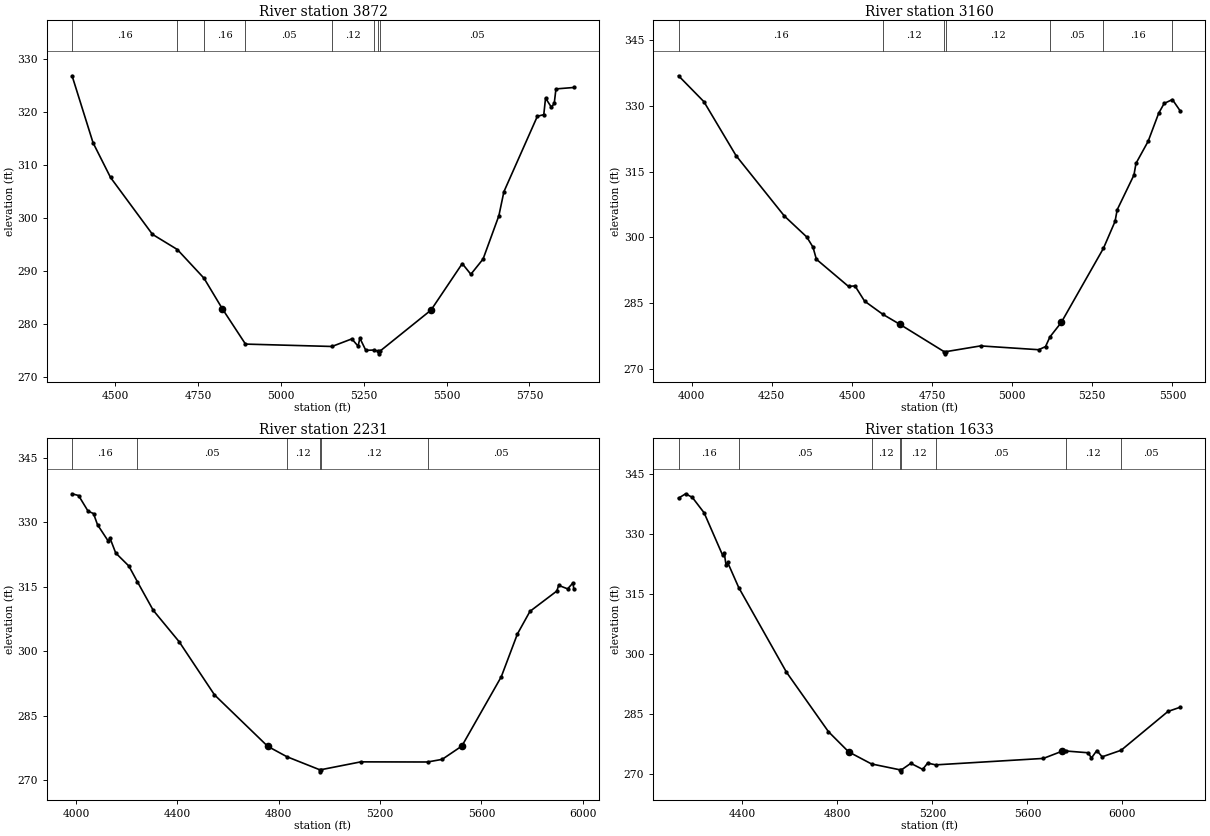
Type RM Length L Ch R = 1 ,3872    ,712,712,712
BEGIN DESCRIPTION:
DOTTIE BRANCH 4.0
END DESCRIPTION:
XS GIS Cut Line= 3
      3631499.63     10538210.18      3630899.61     10538410.19
      3630065.37     10538693.16
#Sta/Elev= 30
  4370.4  326.88  4433.7  314.23  4486.4  307.68  4612.9  296.94  4687.8  294.08
  4768.3  288.66  4823.7  282.88  4893.4  276.22  5154.2  275.77  5214.1   277.2
  5233.1  275.83  5238.4  277.34  5256.3  275.04  5282.2   275.1  5292.9  274.88
  5295.7  274.38  5298.9  274.88    5453  282.64  5547.2  291.42  5573.1   289.4
    5610  292.28  5657.6  300.45  5672.8  304.99  5773.7  319.23  5793.1  319.54
  5798.4  322.67    5816  320.94  5824.6  321.66  5829.8   324.4  5883.8  324.67
#Mann= 8 ,-1 , 0
  4370.4     .16       0  4687.8     .12       0  4768.3     .16       0
  4893.4     .05       0  5154.2     .12       0  5282.2     .05       0
  5292.9     .03       0  5298.9     .05       0
Bank Sta=4823.7,5453
XS Rating Curve= 0 ,0
Exp/Cntr=0.3,0.1

Type RM Length L Ch R = 1 ,3160    ,929,929,929
BEGIN DESCRIPTION:
DOTTIE BRANCH 3.0
END DESCRIPTION:
XS GIS Cut Line= 4
      3631648.64     10538005.67      3630877.84     10537950.11
       3630370.9     10538012.61      3630101.35     10538095.55
#Sta/Elev= 30
  3959.1  336.84  4038.3  330.93  4138.6  318.62    4289  304.88  4359.2  300.07
  4378.6  297.75  4389.2  294.99  4489.5  288.79  4509.6  288.92  4539.6  285.44
  4596.6  282.43  4649.9  280.14  4787.6  273.92  4790.3  273.42  4793.6  273.92
  4901.4  275.23  5082.8  274.36  5104.1  275.07  5117.8  277.27  5153.3  280.58
  5284.9   297.5    5321  303.62  5327.7  306.28    5380   314.2  5386.4  316.87
  5424.3   321.9    5457  328.27  5474.2  330.53  5499.9  331.42  5524.7  328.79
#Mann= 7 ,-1 , 0
  3959.1     .16       0  4596.6     .12       0  4787.6     .07       0
  4793.6     .12       0  5117.8     .05       0  5284.9     .16       0
  5499.9     .05       0
Bank Sta=4649.9,5153.3
XS Rating Curve= 0 ,0
Exp/Cntr=0.3,0.1

Type RM Length L Ch R = 1 ,2231    ,598,598,598
BEGIN DESCRIPTION:
DOTTIE BRANCH 2.0
END DESCRIPTION:
XS GIS Cut Line= 4
      3631738.97     10537866.79      3630759.79     10537304.28
      3630482.01     10537297.34      3630073.47     10537698.95
#Sta/Elev= 30
  3984.6  336.57  4010.3  336.16  4047.7  332.53  4069.2  331.97    4085  329.37
  4128.2  325.49  4133.9  326.31  4156.8   322.8  4208.7  319.77  4241.9  316.16
    4305  309.46  4407.1  302.17  4546.6  289.81  4756.5  277.85  4832.2  275.43
  4961.1  272.41  4963.9  271.91  4967.1  272.41    5124  274.23  5387.1   274.2
  5444.9  274.81  5522.7  277.91  5678.2  294.02    5742  303.99  5791.4  309.23
  5897.5  313.96  5904.5  315.28    5940  314.46  5961.1  315.84  5964.6  314.34
#Mann= 6 ,-1 , 0
  3984.6     .16       0  4241.9     .05       0  4832.2     .12       0
  4961.1     .07       0  4967.1     .12       0  5387.1     .05       0
Bank Sta=4756.5,5522.7
XS Rating Curve= 0 ,0
Exp/Cntr=0.3,0.1

Type RM Length L Ch R = 1 ,1633    ,0,0,0
BEGIN DESCRIPTION:
DOTTIE BRANCH 1.0
END DESCRIPTION:
XS GIS Cut Line= 3
      3631877.85     10537554.28      3630982.01     10536707.06
      3630190.34     10537089.01
#Sta/Elev= 30
  4131.5  338.91  4161.4     340  4189.7  339.09  4239.2  335.25  4317.1  324.66
    4324  325.19  4331.3  322.25  4338.2  322.87    4385  316.58  4585.7  295.49
  4762.5  280.64  4847.5   275.6  4943.7  272.59  5063.7  271.12  5066.5  270.62
  5069.7  271.12  5109.2  272.74    5159  271.24    5180   272.8  5213.9  272.36
    5667  273.97  5744.7  275.74  5761.3  275.82  5855.7  275.38  5869.4  274.06
    5892  275.94  5914.6  274.37  5994.2     276  6191.5  285.69  6243.5  286.75
#Mann= 8 ,-1 , 0
  4131.5     .16       0    4385     .05       0  4943.7     .12       0
  5063.7     .07       0  5069.7     .12       0  5213.9     .05       0
  5761.3     .12       0  5994.2     .05       0
Bank Sta=4847.5,5744.7
XS Rating Curve= 0 ,0
Exp/Cntr=0.3,0.1

Chan Stop Cuts=-1
Use User Specified Reach Order=0
Composite Channel Slope=5