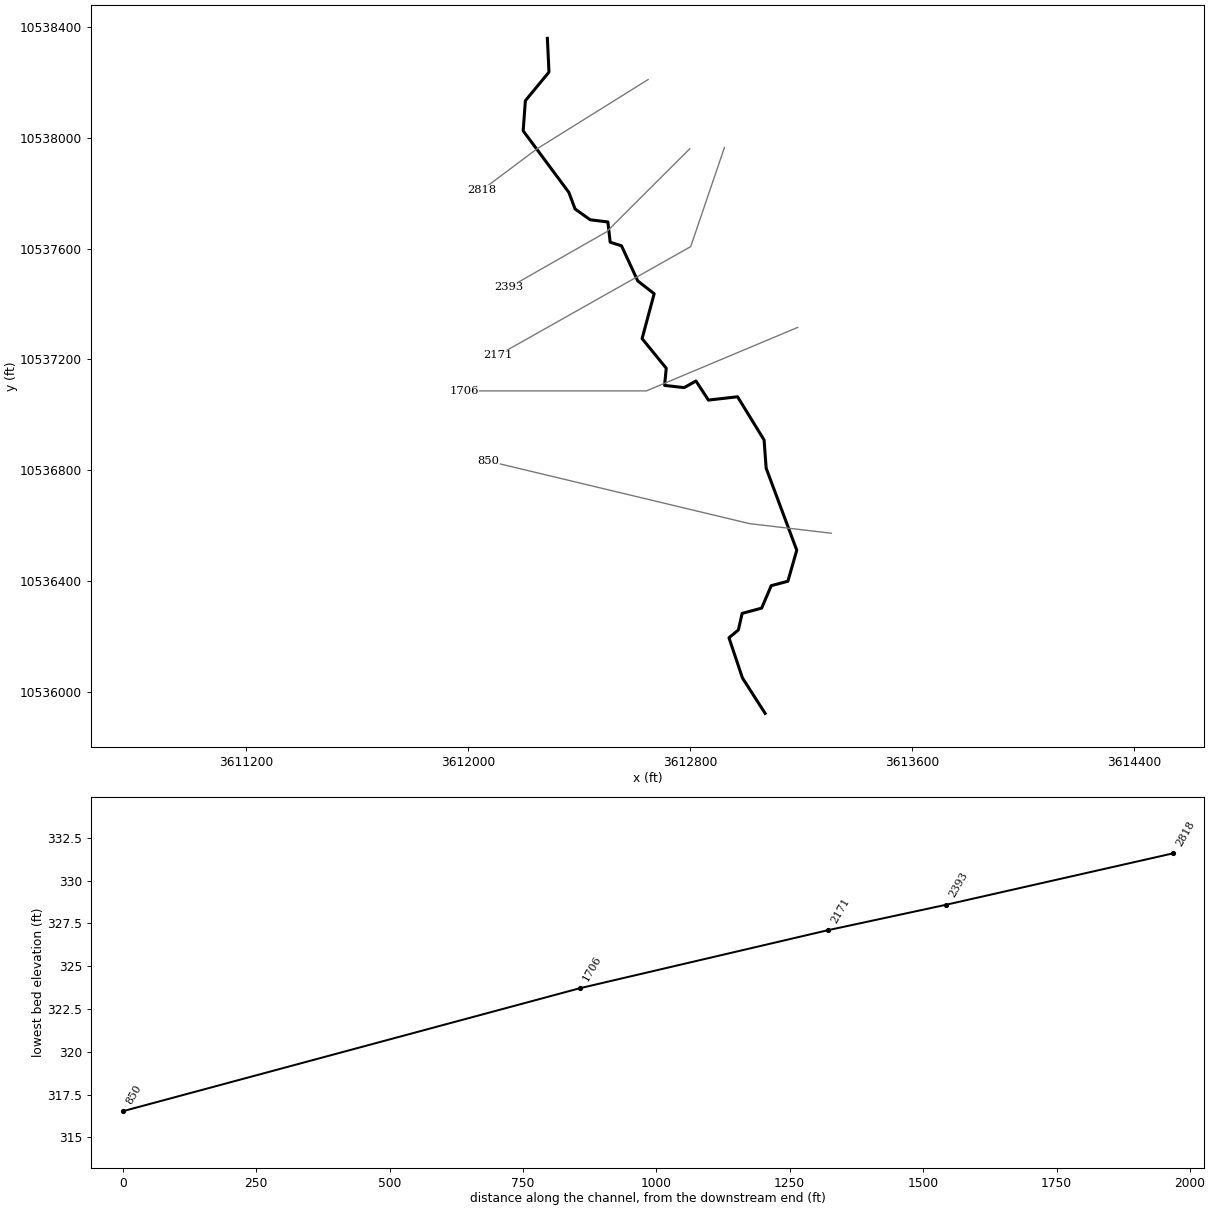
--- FULKS DUGOUT.prj (project) ---

Proj Title=FULKS DUGOUT Base Level Engineering
Current Plan=p01
Default Exp/Contr=0.3,0.1
English Units
Geom File=g01
Flow File=f01
Plan File=p01
Y Axis Title=Elevation
X Axis Title(PF)=Main Channel Distance
X Axis Title(XS)=Station
BEGIN DESCRIPTION:
FULKS DUGOUT
END DESCRIPTION:
DSS Export Rating Curves= 0
DSS Export Rating Curve Sorted= 0
DSS Export Volume Flow Curves= 0
DXF OffsetX= 0
DXF OffsetY= 0
DXF ScaleX= 1
DXF ScaleY= 10

--- FULKS DUGOUT.p01 (plan) ---

Plan Title=Multiple Run
Short Identifier=Multiple
Geom File=g01
Flow File=f01
Subcritical Flow
K Sum by GR= 0
Std Step Tol= 0.01
Critical Tol= 0.01
Num of Std Step Trials= 20
Max Error Tol= 0.3
Flow Tol Ratio= 0.001
Split Flow NTrial= 30
Split Flow Tol= 0.02
Split Flow Ratio= 0.02
Log Output Level= 0
Friction Slope Method= 1
Unsteady Friction Slope Method= 2
Unsteady Bridges Friction Slope Method= 1
Parabolic Critical Depth
Global Vel Dist=  1 , 1 , 1
Global Log Level= 0
CheckData=True
Encroach Param= -1, 0, 0, 0
BEGIN DESCRIPTION:
Multiple Run
END DESCRIPTION:

--- FULKS DUGOUT.f01 (steady flow) ---

Flow Title=Multiple
Program Version=4.10
Number of Profiles= 7
Profile Names=10-year,25-year,50-year,1pct_min,100-year,1pct_plu,500-year
River Rch & RM=FULKS DUGOUT,Reach-1         ,2818
    1332    1873    2331    2119    2865    3875    4312
Boundary for River Rch & Prof#=FULKS DUGOUT,Reach-1         , 1
Up Type= 0
Dn Type= 3
Dn Slope=0.008
Boundary for River Rch & Prof#=FULKS DUGOUT,Reach-1         , 2
Up Type= 0
Dn Type= 3
Dn Slope=0.008
Boundary for River Rch & Prof#=FULKS DUGOUT,Reach-1         , 3
Up Type= 0
Dn Type= 3
Dn Slope=0.008
Boundary for River Rch & Prof#=FULKS DUGOUT,Reach-1         , 4
Up Type= 0
Dn Type= 3
Dn Slope=0.008
Boundary for River Rch & Prof#=FULKS DUGOUT,Reach-1         , 5
Up Type= 0
Dn Type= 3
Dn Slope=0.008
Boundary for River Rch & Prof#=FULKS DUGOUT,Reach-1         , 6
Up Type= 0
Dn Type= 3
Dn Slope=0.008
Boundary for River Rch & Prof#=FULKS DUGOUT,Reach-1         , 7
Up Type= 0
Dn Type= 3
Dn Slope=0.008
DSS Import GetInterval= 0
DSS Import GetPeak= 0
DSS Import FillOption= 0

--- FULKS DUGOUT.g01 (geometry) ---

Geom Title=Existing Conditions
Program Version=4.10

River Reach=FULKS DUGOUT    ,Reach-1
Reach XY= 30
      3612286.75       10538359.       3612292.5       10538237.
       3612207.5       10538134.       3612199.5       10538025.
        3612364.       10537803.       3612386.5       10537743.
        3612441.       10537704.      3612504.75       10537696.
        3612513.       10537623.      3612553.75       10537610.
       3612612.5       10537483.       3612671.5       10537437.
        3612628.       10537275.        3612715.       10537168.
        3612709.       10537106.      3612779.75       10537098.
        3612822.       10537122.        3612867.       10537053.
        3612972.       10537065.       3613067.5       10536909.
        3613075.       10536807.      3613185.25       10536511.
      3613153.25       10536399.      3613093.25       10536383.
      3613058.75       10536302.       3612988.5       10536283.
      3612974.75       10536223.        3612941.       10536195.
       3612989.5       10536050.      3613071.25       10535922.

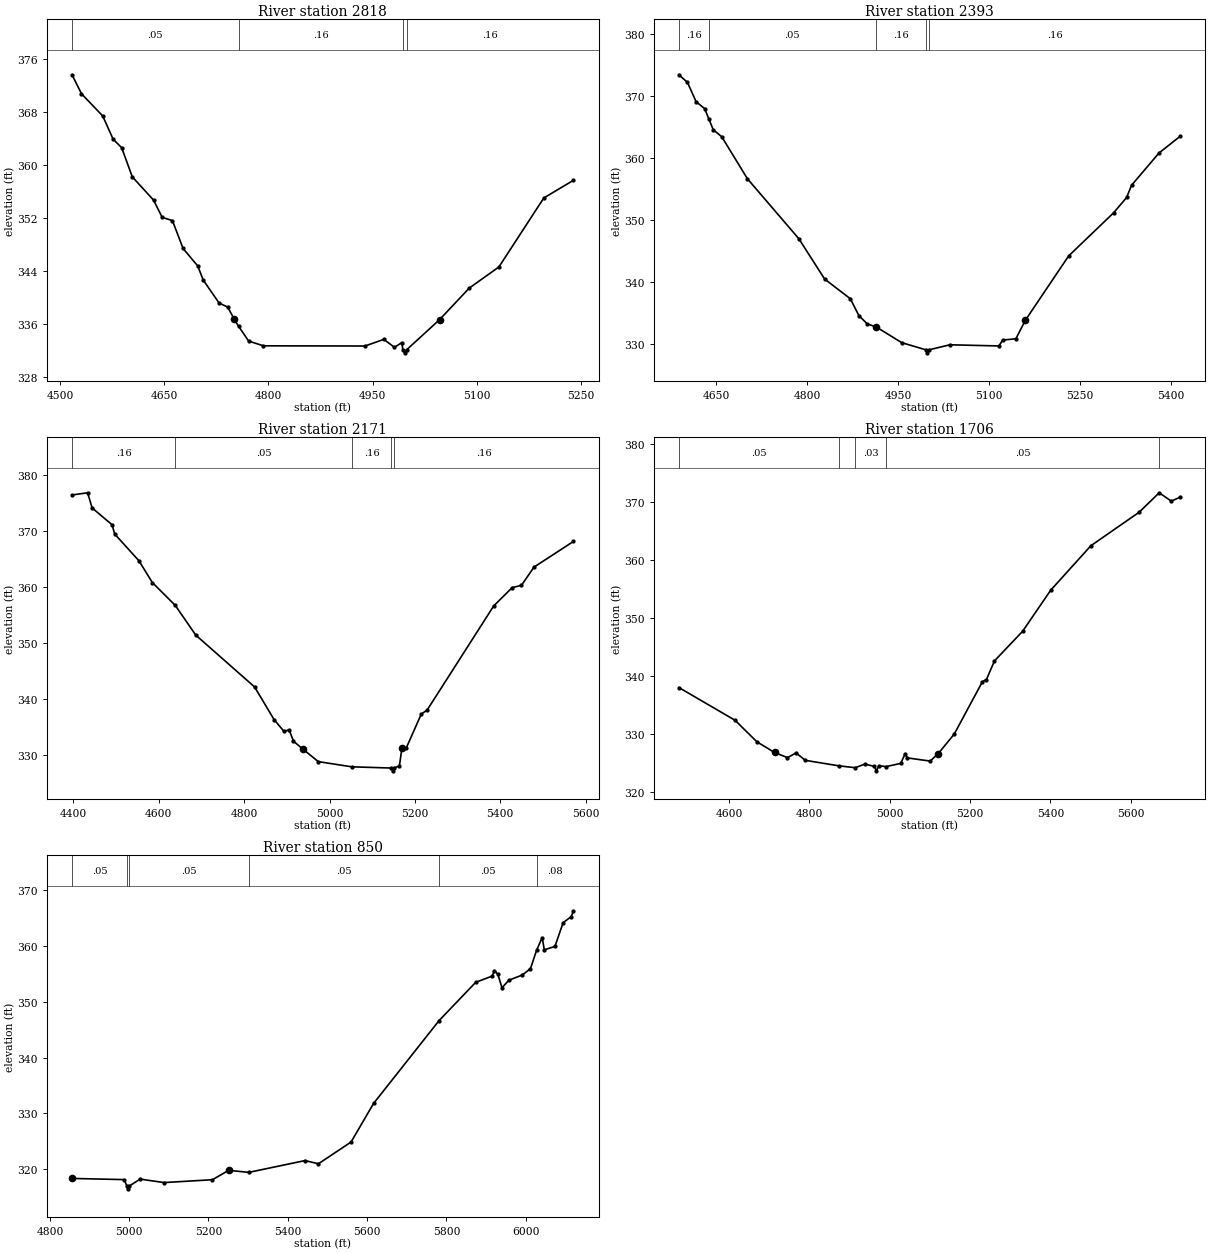
Type RM Length L Ch R = 1 ,2818    ,425,425,425
BEGIN DESCRIPTION:
FULKS DUGOUT 3.0
END DESCRIPTION:
XS GIS Cut Line= 3
      3612649.62     10538210.19      3612249.61     10537960.19
      3612049.61     10537810.19
#Sta/Elev= 30
  4517.5  373.55  4531.1  370.68  4561.7  367.33  4576.5  363.85  4588.9  362.55
  4604.2  358.15  4634.8  354.64  4647.2  352.04    4662  351.54  4677.3  347.34
  4698.5  344.69  4706.2  342.59  4729.2   339.1  4741.6  338.49  4750.4  336.76
  4757.3  335.59  4771.6  333.37  4792.9  332.65  4939.1  332.62  4966.2  333.62
  4981.5  332.43  4992.3  333.14  4993.5  332.09  4996.2  331.59  4999.5  332.09
  5046.5   336.6  5089.2  341.36  5131.9  344.55  5196.5  354.96  5239.2  357.63
#Mann= 4 ,-1 , 0
  4517.5     .05       0  4757.3     .16       0  4993.5     .07       0
  4999.5     .16       0
Bank Sta=4750.4,5046.5
XS Rating Curve= 0 ,0
Exp/Cntr=0.3,0.1

Type RM Length L Ch R = 1 ,2393    ,222,222,222
BEGIN DESCRIPTION:
FULKS DUGOUT 2.0
END DESCRIPTION:
XS GIS Cut Line= 3
      3612799.61     10537960.19      3612499.61     10537660.19
      3612149.59     10537460.18
#Sta/Elev= 30
  4588.4  373.46  4602.5  372.22  4616.7  369.12  4630.8     368  4637.8  366.32
    4645   364.6  4659.1  363.45  4701.5  356.67  4786.4  346.99  4828.8   340.5
  4871.2  337.32  4885.4  334.59  4899.5  333.23  4913.2   332.8  4913.7  332.78
  4956.1  330.23  4995.5  329.09  4998.3  328.59  5001.5  329.09  5035.7  329.89
  5116.3   329.7  5122.8  330.65  5144.4  330.86  5160.2  333.87  5231.5  344.23
  5305.6  351.18  5327.2  353.66  5335.2  355.62  5380.5  360.83  5415.8  363.56
#Mann= 5 ,-1 , 0
  4588.4     .16       0  4637.8     .05       0  4913.2     .16       0
  4995.5     .07       0  5001.5     .16       0
Bank Sta=4913.7,5160.2
XS Rating Curve= 0 ,0
Exp/Cntr=0.3,0.1

Type RM Length L Ch R = 1 ,2171    ,465,465,465
BEGIN DESCRIPTION:
Mapping XS f2a2d8a6
END DESCRIPTION:
XS GIS Cut Line= 3
      3612924.64      10537964.7       3612803.1     10537607.03
      3612109.07     10537214.91
#Sta/Elev= 30
  4396.7  376.45  4433.2  376.84  4443.7  374.13  4490.6  371.11  4496.5  369.47
  4553.4  364.68  4584.8  360.79  4638.6  356.69  4686.6  351.38  4824.5   342.1
  4870.3  336.24  4893.3  334.16  4905.4  334.44  4915.5  332.41  4937.2  331.01
  4973.7  328.75  5051.8  327.82  5144.9   327.6  5147.7   327.1  5150.9   327.6
  5163.8  327.98  5169.6  331.15  5179.8  331.18  5214.9  337.24  5228.8  337.98
  5384.8  356.61  5428.1  359.88  5449.7  360.28  5479.1  363.54  5571.6  368.14
#Mann= 5 ,-1 , 0
  4396.7     .16       0  4638.6     .05       0  5051.8     .16       0
  5144.9     .03       0  5150.9     .16       0
Bank Sta=4937.2,5169.6
XS Rating Curve= 0 ,0
Exp/Cntr=0.3,0.1

Type RM Length L Ch R = 1 ,1706    ,856,856,856
BEGIN DESCRIPTION:
Mapping XS 37da25bf
END DESCRIPTION:
XS GIS Cut Line= 3
      3613188.49     10537315.36      3612643.38      10537086.2
       3611987.1      10537086.2
#Sta/Elev= 30
  4475.5  338.05  4615.3  332.41  4669.5  328.71  4713.3  326.87  4745.5  325.99
  4767.2  326.79  4789.9  325.52  4872.6  324.58  4914.1  324.25  4937.9  324.87
  4961.6  324.48  4966.8  323.71  4973.3   324.6  4990.8  324.44  5027.5  324.99
  5038.3  326.68  5043.7  325.94  5100.6  325.39  5120.6  326.67  5160.6  330.05
  5230.6  339.06  5240.6  339.43  5260.6  342.64  5330.6  347.74  5400.6  354.82
  5500.6  362.48  5620.6  368.24  5670.5  371.59  5700.6  370.15  5723.1  370.85
#Mann= 5 ,-1 , 0
  4475.5     .05       0  4872.6     .05       0  4914.1     .03       0
  4990.8     .05       0  5670.5     .08       0
Bank Sta=4713.3,5120.6
XS Rating Curve= 0 ,0
Exp/Cntr=0.3,0.1

Type RM Length L Ch R = 1 ,850     ,0,0,0
BEGIN DESCRIPTION:
FULKS DUGOUT 1.0
END DESCRIPTION:
XS GIS Cut Line= 3
      3613310.02     10536572.31      3613014.91     10536607.03
      3612074.23     10536832.66
#Sta/Elev= 30
  4855.9  318.39  4987.2  318.18  4994.3  317.03    4997  316.53  5000.3  317.03
  5027.5  318.27  5087.9  317.65  5209.9  318.16    5251  319.84  5301.6  319.47
  5443.3  321.58  5477.3  321.01  5559.6   324.9  5616.4   331.8  5781.3  346.58
  5873.6  353.42  5915.6  354.56  5920.8  355.54  5929.8  354.88  5940.1  352.47
  5957.6  353.81  5991.5  354.75    6012  355.88  6027.3  359.14  6041.6  361.44
  6046.8  359.24  6073.7  359.85  6094.3  364.09  6114.9  365.18  6120.4  366.22
#Mann= 6 ,-1 , 0
  4855.9     .05       0  4994.3     .03       0  5000.3     .05       0
  5301.6     .05       0  5781.3     .05       0  6027.3     .08       0
Bank Sta=4855.9,5251
XS Rating Curve= 0 ,0
Exp/Cntr=0.3,0.1

Chan Stop Cuts=-1
Use User Specified Reach Order=0
Composite Channel Slope=5