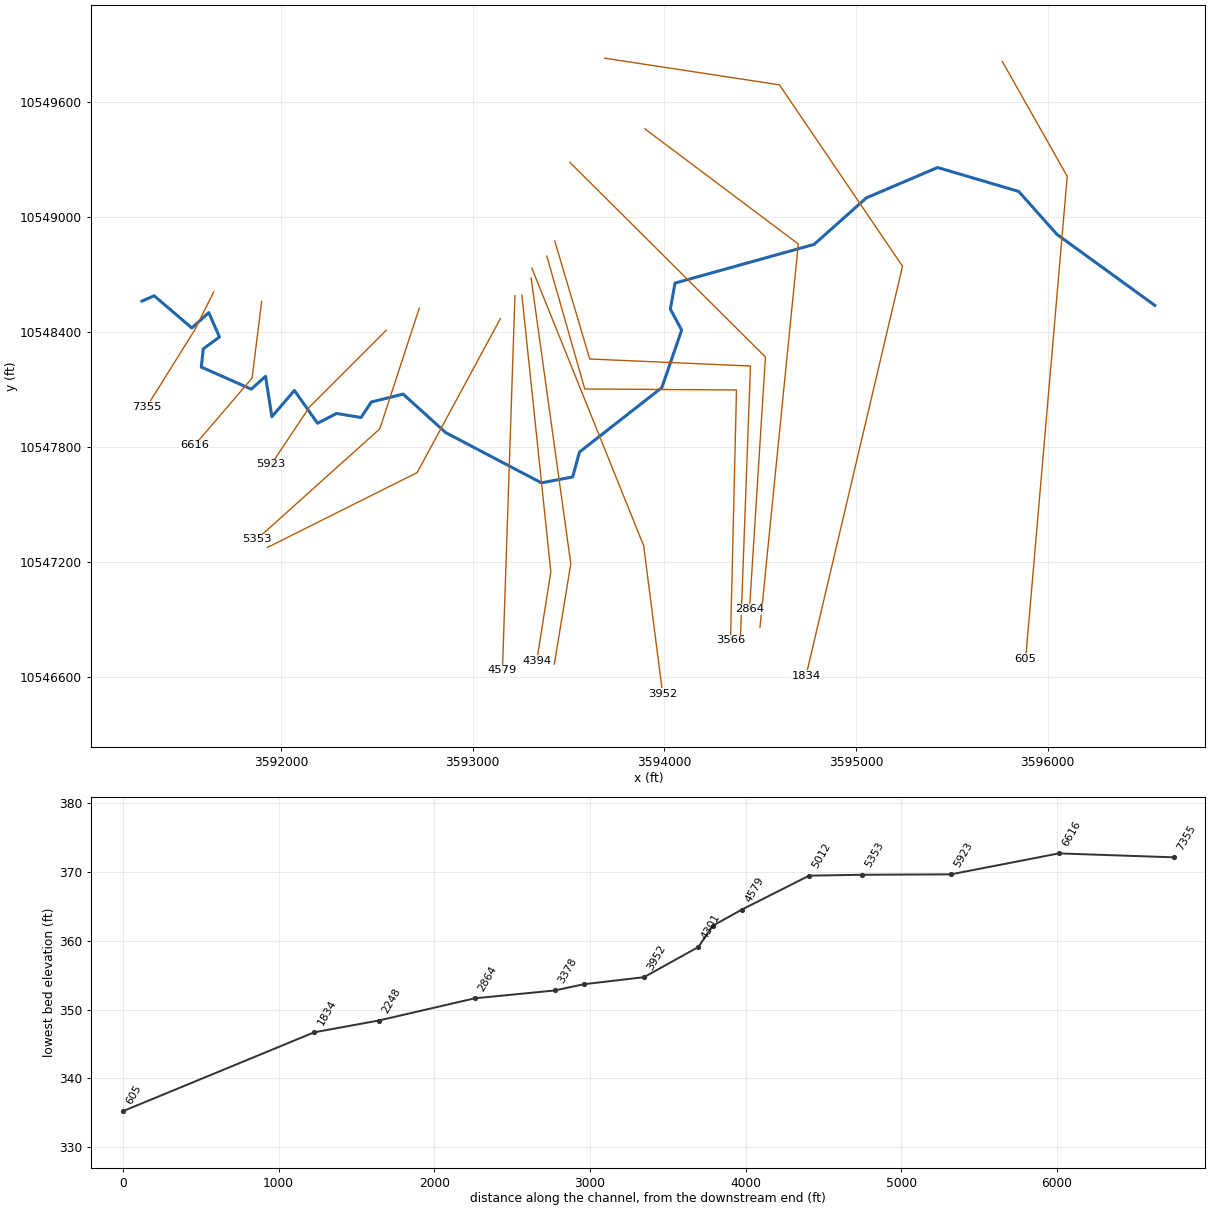
--- GRAVEYARD BRANCH.prj (project) ---

Proj Title=GRAVEYARD BRANCH Base Level Engineering
Current Plan=p01
Default Exp/Contr=0.3,0.1
English Units
Geom File=g01
Flow File=f01
Plan File=p01
Y Axis Title=Elevation
X Axis Title(PF)=Main Channel Distance
X Axis Title(XS)=Station
BEGIN DESCRIPTION:
GRAVEYARD BRANCH
END DESCRIPTION:
DSS Export Rating Curves= 0
DSS Export Rating Curve Sorted= 0
DSS Export Volume Flow Curves= 0
DXF OffsetX= 0
DXF OffsetY= 0
DXF ScaleX= 1
DXF ScaleY= 10

--- GRAVEYARD BRANCH.p01 (plan) ---

Plan Title=Multiple Run
Short Identifier=Multiple
Geom File=g01
Flow File=f01
Subcritical Flow
K Sum by GR= 0
Std Step Tol= 0.01
Critical Tol= 0.01
Num of Std Step Trials= 20
Max Error Tol= 0.3
Flow Tol Ratio= 0.001
Split Flow NTrial= 30
Split Flow Tol= 0.02
Split Flow Ratio= 0.02
Log Output Level= 0
Friction Slope Method= 1
Unsteady Friction Slope Method= 2
Unsteady Bridges Friction Slope Method= 1
Parabolic Critical Depth
Global Vel Dist=  1 , 1 , 1
Global Log Level= 0
CheckData=True
Encroach Param= -1, 0, 0, 0
BEGIN DESCRIPTION:
Multiple Run
END DESCRIPTION:

--- GRAVEYARD BRANCH.f01 (steady flow) ---

Flow Title=Multiple
Program Version=4.10
Number of Profiles= 7
Profile Names=10-year,25-year,50-year,1pct_min,100-year,1pct_plu,500-year
River Rch & RM=GRAVEYARD BRANCH,Reach-1         ,7355
    1770    2520    3161    2890    3909    5286    5961
Boundary for River Rch & Prof#=GRAVEYARD BRANCH,Reach-1         , 1
Up Type= 0
Dn Type= 3
Dn Slope=0.003
Boundary for River Rch & Prof#=GRAVEYARD BRANCH,Reach-1         , 2
Up Type= 0
Dn Type= 3
Dn Slope=0.003
Boundary for River Rch & Prof#=GRAVEYARD BRANCH,Reach-1         , 3
Up Type= 0
Dn Type= 3
Dn Slope=0.003
Boundary for River Rch & Prof#=GRAVEYARD BRANCH,Reach-1         , 4
Up Type= 0
Dn Type= 3
Dn Slope=0.003
Boundary for River Rch & Prof#=GRAVEYARD BRANCH,Reach-1         , 5
Up Type= 0
Dn Type= 3
Dn Slope=0.003
Boundary for River Rch & Prof#=GRAVEYARD BRANCH,Reach-1         , 6
Up Type= 0
Dn Type= 3
Dn Slope=0.003
Boundary for River Rch & Prof#=GRAVEYARD BRANCH,Reach-1         , 7
Up Type= 0
Dn Type= 3
Dn Slope=0.003
DSS Import GetInterval= 0
DSS Import GetPeak= 0
DSS Import FillOption= 0

--- GRAVEYARD BRANCH.g01 (geometry) ---

Geom Title=Existing Conditions
Program Version=4.10

River Reach=GRAVEYARD BRANCH,Reach-1
Reach XY= 30
        3591275.       10548562.      3591338.75       10548590.
      3591535.25       10548422.      3591623.75       10548502.
       3591679.5       10548375.        3591595.       10548313.
      3591584.75       10548218.       3591845.5       10548103.
        3591920.       10548170.        3591953.       10547959.
       3592070.5       10548096.      3592191.25       10547925.
       3592290.5       10547976.        3592418.       10547955.
        3592472.       10548036.      3592637.75       10548077.
      3592860.25       10547876.       3593359.5       10547614.
      3593522.25       10547645.        3593558.       10547775.
      3593987.75       10548111.        3594091.       10548411.
        3594032.       10548520.      3594056.25       10548656.
        3594782.       10548858.       3595055.5       10549101.
       3595426.5       10549259.      3595849.75       10549134.
      3596049.25       10548910.       3596559.5       10548540.

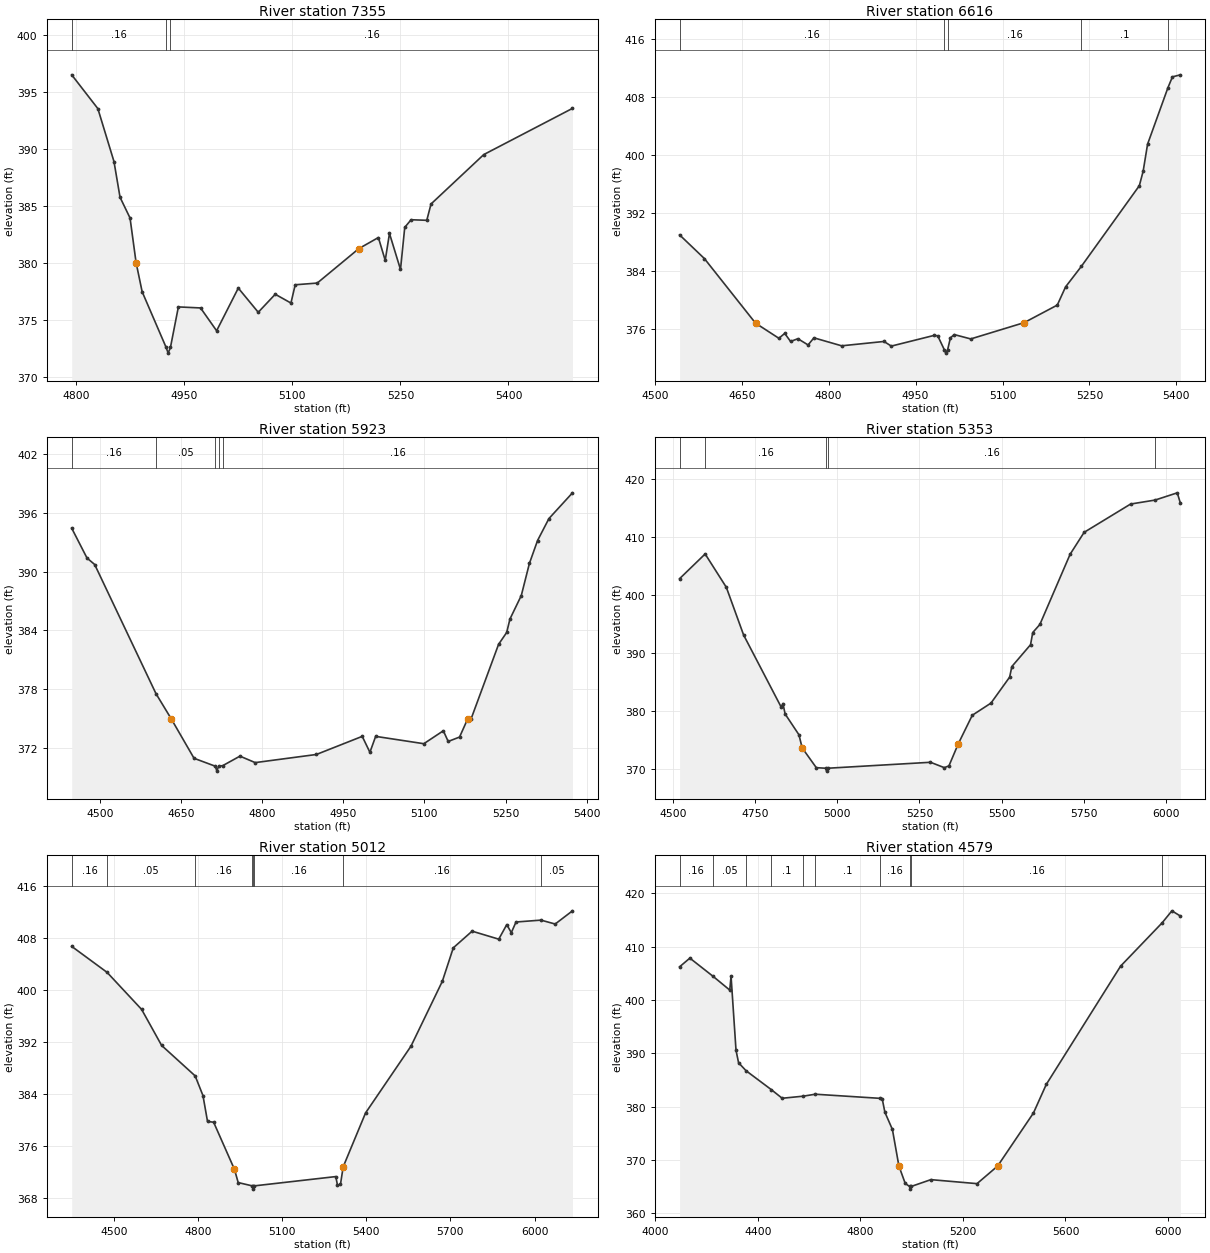
Type RM Length L Ch R = 1 ,7355    ,739,739,739
BEGIN DESCRIPTION:
GRAVEYARD BRANCH 10.0
END DESCRIPTION:
XS GIS Cut Line= 3
       3591649.6     10548610.17      3591549.61     10548410.19
       3591299.6     10548010.18
#Sta/Elev= 30
  4793.6  396.48  4829.9  393.52  4852.3  388.88  4860.7  385.75  4874.6  383.93
    4883  380.02  4891.4  377.47  4924.7  372.59  4927.5  372.09  4930.7  372.59
  4941.7  376.14  4972.5  376.05  4994.8  374.05  5024.9  377.79  5052.6  375.67
  5076.2  377.25    5098  376.48  5103.9  378.08  5134.5  378.23  5192.3  381.25
  5219.4  382.22  5228.9  380.22  5234.8  382.58  5250.1  379.42    5256  383.11
  5264.8  383.78  5286.6  383.73  5292.5  385.16  5365.7  389.49  5488.9  393.54
#Mann= 3 ,-1 , 0
  4793.6     .16       0  4924.7     .07       0  4930.7     .16       0
Bank Sta=4883,5192.3
XS Rating Curve= 0 ,0
Exp/Cntr=0.3,0.1

Type RM Length L Ch R = 1 ,6616    ,693,693,693
BEGIN DESCRIPTION:
GRAVEYARD BRANCH 9.0
END DESCRIPTION:
XS GIS Cut Line= 3
      3591899.61     10548560.17      3591849.61     10548160.19
      3591549.59     10547810.17
#Sta/Elev= 30
  4542.8  388.98  4585.6  385.71  4673.8   376.8  4714.1  374.71  4724.2  375.38
  4734.3  374.27  4746.9  374.65  4764.5  373.79  4774.6  374.77  4822.4  373.67
  4895.5  374.27  4908.1  373.63  4981.6   375.1  4988.2  375.05  4999.4  373.16
  5002.2  372.66  5005.4  373.16  5010.1  374.77  5016.7  375.22  5045.2  374.62
  5137.4  376.87  5194.5  379.29  5208.8   381.8  5235.9  384.62  5336.1  395.77
  5342.7  397.78  5350.3   401.5  5385.5  409.31  5393.2  410.79  5406.9  411.07
#Mann= 5 ,-1 , 0
  4542.8     .16       0  4999.4     .07       0  5005.4     .16       0
  5235.9      .1       0  5385.5     .15       0
Bank Sta=4673.8,5137.4
XS Rating Curve= 0 ,0
Exp/Cntr=0.3,0.1

Type RM Length L Ch R = 1 ,5923    ,570,570,570
BEGIN DESCRIPTION:
GRAVEYARD BRANCH 8.0
END DESCRIPTION:
XS GIS Cut Line= 3
      3592549.63     10548410.21      3592149.61     10548010.19
      3591949.59     10547710.16
#Sta/Elev= 30
  4447.6  394.43  4475.9  391.38  4490.1  390.72  4603.5  377.53  4631.5  374.98
  4673.9  370.93  4713.3  370.12  4716.1  369.62  4719.3  370.12    4727  370.18
  4758.8  371.15    4787  370.49  4900.2  371.32    4985  373.17  4999.2  371.54
  5009.8  373.17  5098.9  372.42    5135  373.74    5144  372.65    5165   373.1
  5180.1  374.96  5186.1  374.92  5237.2  382.57  5252.2  383.78  5258.2  385.15
  5279.2  387.55  5294.2  390.83  5309.3  393.17  5330.3  395.41  5373.9  398.04
#Mann= 5 ,-1 , 0
  4447.6     .16       0  4603.5     .05       0  4713.3     .07       0
  4719.3     .05       0    4727     .16       0
Bank Sta=4631.5,5180.1
XS Rating Curve= 0 ,0
Exp/Cntr=0.3,0.1

Type RM Length L Ch R = 1 ,5353    ,341,341,341
BEGIN DESCRIPTION:
GRAVEYARD BRANCH 7.0
END DESCRIPTION:
XS GIS Cut Line= 3
      3592722.03     10548525.19      3592515.86     10547895.81
      3591875.63     10547320.69
#Sta/Elev= 30
  4520.5  402.83  4598.2   407.1  4662.6  401.34  4715.2  393.09  4829.6  380.61
  4834.8  381.24  4841.4  379.44  4883.5  375.84  4893.2  373.58  4936.2  370.16
  4964.7  370.06  4967.5  369.56  4970.7  370.06  5283.5  371.09  5325.6  370.16
  5339.6  370.47    5368  374.29  5410.6  379.22  5467.4  381.32  5524.2  385.81
  5530.9  387.64  5587.7  391.41  5594.5  393.52  5616.1  394.91  5708.1  407.05
  5750.7  410.84    5892  415.73  5966.6  416.42    6034  417.67  6043.4  415.89
#Mann= 5 ,-1 , 0
  4520.5     .05       0  4598.2     .16       0  4964.7     .07       0
  4970.7     .16       0  5966.6     .05       0
Bank Sta=4893.2,5368
XS Rating Curve= 0 ,0
Exp/Cntr=0.3,0.1

Type RM Length L Ch R = 1 ,5012    ,433,433,433
BEGIN DESCRIPTION:
GRAVEYARD BRANCH 6.0
END DESCRIPTION:
XS GIS Cut Line= 3
       3593145.2      10548470.9      3592711.17     10547667.95
      3591929.94     10547277.33
#Sta/Elev= 30
  4349.2  406.78  4475.4  402.78  4598.6  397.08  4669.9  391.54  4789.6  386.85
  4817.4  383.82  4833.6  379.85  4855.5  379.72  4929.8  372.46    4943  370.44
  4991.3  369.95  4994.3  369.93  4997.1  369.43  5000.3  369.93  5291.1  371.36
  5297.2  370.04  5307.8  370.16  5317.6  372.87  5397.3  381.15  5559.4  391.43
  5671.2  401.41  5710.3  406.56  5777.4  409.12  5872.4  407.89    5901  410.13
  5917.2  408.89  5933.9  410.53  6022.9  410.82  6073.7  410.22  6135.4  412.25
#Mann= 8 ,-1 , 0
  4349.2     .16       0  4475.4     .05       0  4789.6     .16       0
  4991.3     .05       0  4994.3    .033       0  5000.3     .16       0
  5317.6     .16       0  6022.9     .05       0
Bank Sta=4929.8,5317.6
XS Rating Curve= 0 ,0
Exp/Cntr=0.3,0.1

Type RM Length L Ch R = 1 ,4579    ,185,185,185
BEGIN DESCRIPTION:
GRAVEYARD BRANCH 5.0
END DESCRIPTION:
XS GIS Cut Line= 2
      3593221.15     10548590.27      3593156.05     10546637.16
#Sta/Elev= 30
  4094.2  406.23  4134.3  407.86  4224.6  404.45    4290  401.86    4295  404.47
  4314.4  390.54  4324.4  388.22  4353.5  386.72  4451.8  383.18  4494.5  381.55
  4576.3  381.94  4623.5  382.31  4874.7  381.54  4884.7   381.5  4895.3  378.93
  4924.7  375.69 4950.05  368.82  4974.8  365.55  4991.8  364.99  4994.5  364.49
  4997.8  364.99  5074.8  366.27  5254.9  365.52    5335  368.81  5475.1  378.79
  5525.1  384.15  5815.2  406.36  5976.9  414.47  6015.4  416.74  6048.4  415.76
#Mann= 10 ,-1 , 0
  4094.2     .16       0  4224.6     .05       0  4353.5     .15       0
  4451.8      .1       0  4576.3     .08       0  4623.5      .1       0
  4874.7     .16       0  4991.8     .07       0  4997.8     .16       0
  5976.9     .05       0
Bank Sta=4950.05,5335
XS Rating Curve= 0 ,0
Exp/Cntr=0.3,0.1

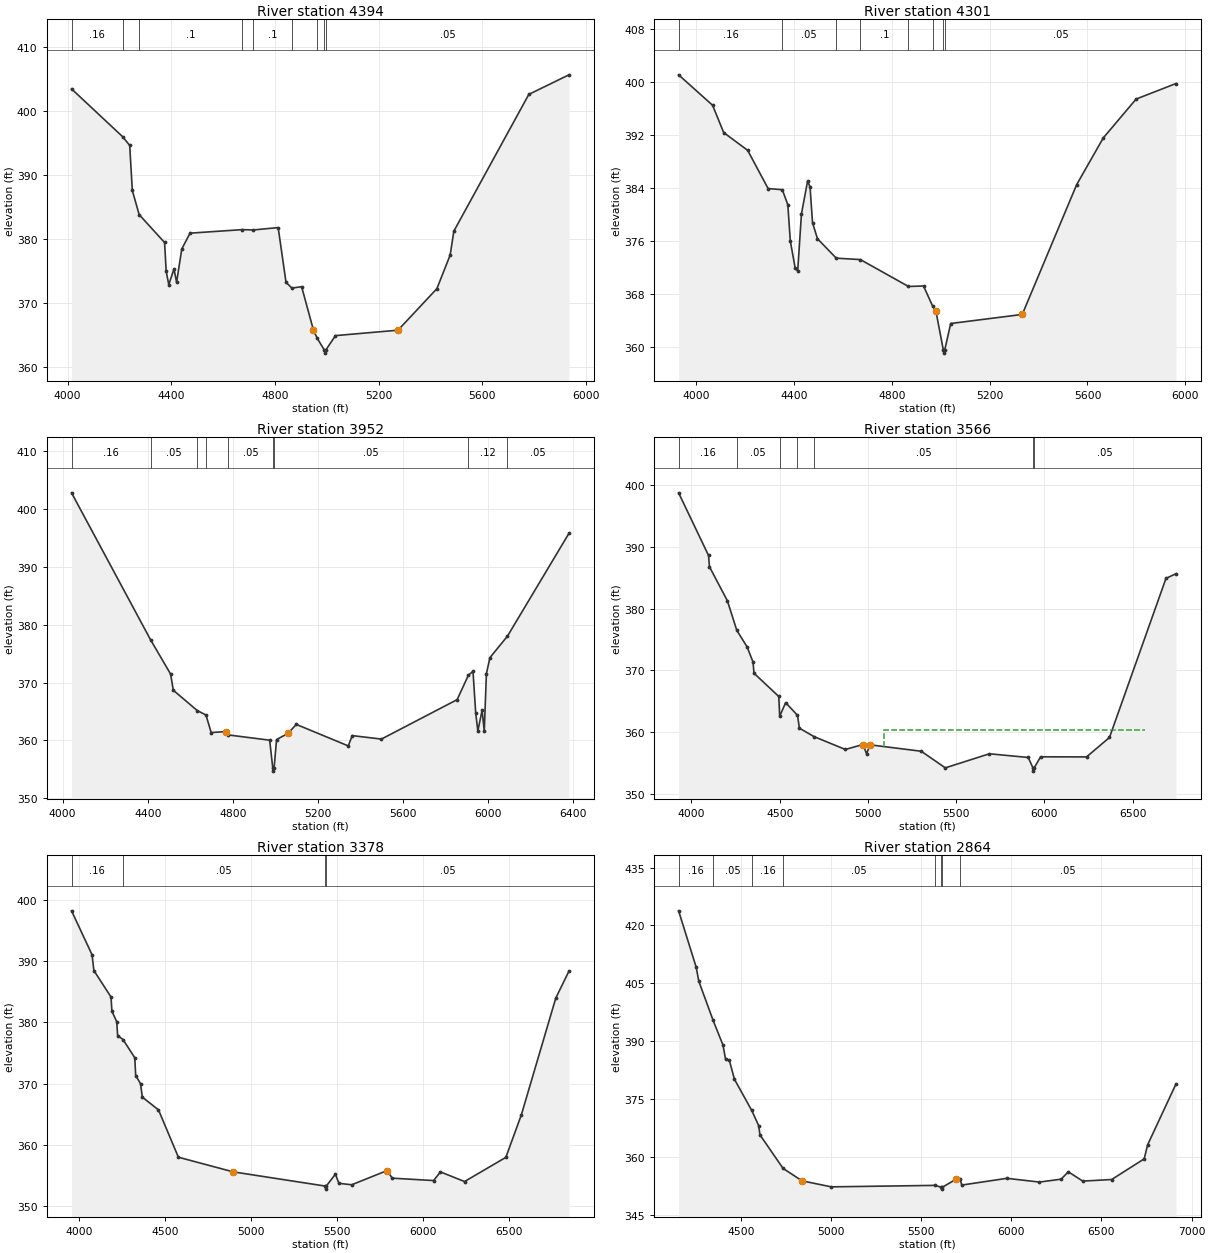
Type RM Length L Ch R = 1 ,4394    ,93,93,93
BEGIN DESCRIPTION:
Mapping XS a5a1567a
END DESCRIPTION:
XS GIS Cut Line= 3
      3593257.33     10548593.47      3593408.37     10547150.72
      3593335.45     10546687.16
#Sta/Elev= 30
  4015.2  403.51  4212.2  396.04  4239.7  394.67  4249.8  387.62  4276.2  383.84
  4374.3  379.48  4380.5  374.97  4390.5  372.89  4410.6  375.33  4420.7  373.26
  4440.8  378.47  4472.6  380.94  4673.6  381.49  4716.5  381.44  4812.8  381.81
    4843  373.25  4865.6  372.35  4903.3  372.56    4949  365.76  4963.8  364.47
  4990.8  362.67  4993.6  362.17  4996.8  362.67    5034  364.91  5275.3  365.76
  5425.4  372.26  5476.5   377.5  5490.9  381.26  5780.2  402.65  5935.1  405.71
#Mann= 9 ,-1 , 0
  4015.2     .16       0  4212.2     .05       0  4276.2      .1       0
  4673.6     .15       0  4716.5      .1       0  4865.6     .08       0
  4963.8     .05       0  4990.8     .03       0  4996.8     .05       0
Bank Sta=4949,5275.3
XS Rating Curve= 0 ,0
Exp/Cntr=0.3,0.1

Type RM Length L Ch R = 1 ,4301    ,349,349,349
BEGIN DESCRIPTION:
GRAVEYARD BRANCH 4.0
END DESCRIPTION:
XS GIS Cut Line= 3
      3593305.42     10548682.86      3593512.54     10547192.38
      3593426.95     10546668.94
#Sta/Elev= 30
  3927.2  401.08  4066.4  396.48  4111.6  392.37  4209.7  389.69  4293.4  383.92
  4351.6  383.74  4374.1  381.47  4384.2     376  4404.4  371.89  4414.5  371.48
  4429.8  380.08  4454.9  385.04    4465  384.17  4475.1  378.77  4495.3  376.35
  4572.3  373.41  4670.8   373.2  4867.8  369.14  4929.4  369.21  4966.3   366.2
  4979.9  365.44  5010.2  359.58  5012.9  359.08  5016.2  359.58  5040.5  363.55
  5333.3  364.92  5555.8   384.5  5664.6  391.55    5799  397.42  5962.4  399.77
#Mann= 8 ,-1 , 0
  3927.2     .16       0  4351.6     .05       0  4572.3     .08       0
  4670.8      .1       0  4867.8     .08       0  4966.3     .05       0
  5010.2     .03       0  5016.2     .05       0
Bank Sta=4979.9,5333.3
XS Rating Curve= 0 ,0
Exp/Cntr=0.3,0.1

Type RM Length L Ch R = 1 ,3952    ,386,386,386
BEGIN DESCRIPTION:
Mapping XS 208a73c2
END DESCRIPTION:
XS GIS Cut Line= 3
      3593309.42     10548734.03      3593892.75     10547286.13
       3593991.7     10546515.34
#Sta/Elev= 30
  4041.8  402.81  4413.2  377.41  4507.4  371.48  4520.3  368.68  4632.4  365.18
  4673.7   364.4  4698.1  361.37  4768.3  361.54  4777.8  360.96  4973.1  360.05
  4987.8   355.2  4990.5   354.7  4993.8   355.2  5005.5  360.16  5059.4  361.22
  5098.2  362.78  5342.6  359.06  5361.2  360.84  5498.4  360.24  5854.4  367.06
  5907.6  371.31  5928.9  371.94  5941.5   364.8  5951.6  361.64  5971.7  365.23
  5981.8  361.58  5991.9  371.56  6008.5  374.32  6090.8  378.03  6379.9  395.81
#Mann= 9 ,-1 , 0
  4041.8     .16       0  4413.2     .05       0  4632.4      .1       0
  4673.7     .08       0  4777.8     .05       0  4987.8     .03       0
  4993.8     .05       0  5907.6     .12       0  6090.8     .05       0
Bank Sta=4768.3,5059.4
XS Rating Curve= 0 ,0
Exp/Cntr=0.3,0.1

Type RM Length L Ch R = 1 ,3566    ,188,188,188
BEGIN DESCRIPTION:
GRAVEYARD BRANCH 3.0
END DESCRIPTION:
XS GIS Cut Line= 4
      3593387.54     10548796.54      3593585.46     10548103.84
      3594377.12     10548098.63      3594345.92      10546793.3
#Sta/Elev= 30
  3927.3  398.76  4096.9  388.61  4102.1  386.78  4203.5  381.28  4257.1  376.48
  4315.3  373.81  4349.1  371.33  4354.3  369.54  4494.7  365.77  4499.9  362.56
  4533.7  364.78  4600.8  362.72  4611.7  360.64  4694.5  359.27  4871.9  357.19
  4971.9  357.99  4991.9   356.5  5011.9  357.94  5301.9   356.9  5438.1  354.21
  5687.9  356.49    5908  355.89    5935  354.18  5937.7  353.68    5941  354.18
    5978     356  6238.1  355.98  6368.1  359.13  6688.2   384.9  6745.1  385.66
#Mann= 7 ,-1 , 0
  3927.3     .16       0  4257.1     .05       0  4499.9      .1       0
  4600.8     .08       0  4694.5     .05       0    5935     .03       0
    5941     .05       0
#XS Ineff= 1 ,-1
 5088.92 6568.47  360.33
Permanent Ineff=
       F
Bank Sta=4971.9,5011.9
XS Rating Curve= 0 ,0
Exp/Cntr=0.3,0.1

Type RM Length L Ch R = 1 ,3378    ,514,514,514
BEGIN DESCRIPTION:
Mapping XS b040c77d
END DESCRIPTION:
XS GIS Cut Line= 4
      3593429.19     10548874.72       3593611.5     10548260.09
      3594450.04     10548223.63      3594398.01     10546813.72
#Sta/Elev= 30
  3954.8  398.21  4074.2  391.03  4084.7  388.46  4184.3  384.14  4189.5  381.81
  4217.5  380.11  4222.8  377.84  4253.9   377.2  4322.4  374.22  4327.7  371.31
  4355.7     370  4366.3  367.79  4460.2  365.71  4575.9  357.98  4894.3  355.59
  5429.5  353.27  5432.3  352.77  5435.5  353.27  5488.7  355.22  5508.7  353.72
  5583.2  353.48  5788.9   355.8  5818.9  354.56  6059.1  354.17  6099.1  355.58
  6239.2  354.01  6479.4  357.96  6569.4   364.9  6769.6  383.97  6846.1  388.37
#Mann= 4 ,-1 , 0
  3954.8     .16       0  4253.9     .05       0  5429.5     .03       0
  5435.5     .05       0
Bank Sta=4894.3,5788.9
XS Rating Curve= 0 ,0
Exp/Cntr=0.3,0.1

Type RM Length L Ch R = 1 ,2864    ,616,616,616
BEGIN DESCRIPTION:
Mapping XS d6b95111
END DESCRIPTION:
XS GIS Cut Line= 3
      3593507.36      10549286.1      3594528.17     10548270.51
      3594444.91     10546953.99
#Sta/Elev= 30
  4154.3  423.77    4252  409.13  4266.1  405.56  4345.9  395.35  4400.5  388.97
  4414.6  385.34  4435.9  384.99  4464.1   380.1  4559.8  372.04  4598.5  368.08
  4605.6   365.7  4733.8     357  4838.9  353.78  5001.5  352.22    5576   352.6
  5611.6  352.13  5614.4  351.63  5617.6  352.13  5694.8  354.24  5716.1  354.29
  5724.8  352.68  5975.3  354.43  6155.7  353.46  6275.9  354.21    6316  356.12
  6396.2  353.71  6556.5  354.12  6736.9  359.48  6755.8  363.11  6913.4  378.91
#Mann= 8 ,-1 , 0
  4154.3     .16       0  4345.9     .05       0  4559.8     .16       0
  4733.8     .05       0    5576      .1       0  5611.6     .03       0
  5617.6      .1       0  5716.1     .05       0
Bank Sta=4838.9,5694.8
XS Rating Curve= 0 ,0
Exp/Cntr=0.3,0.1

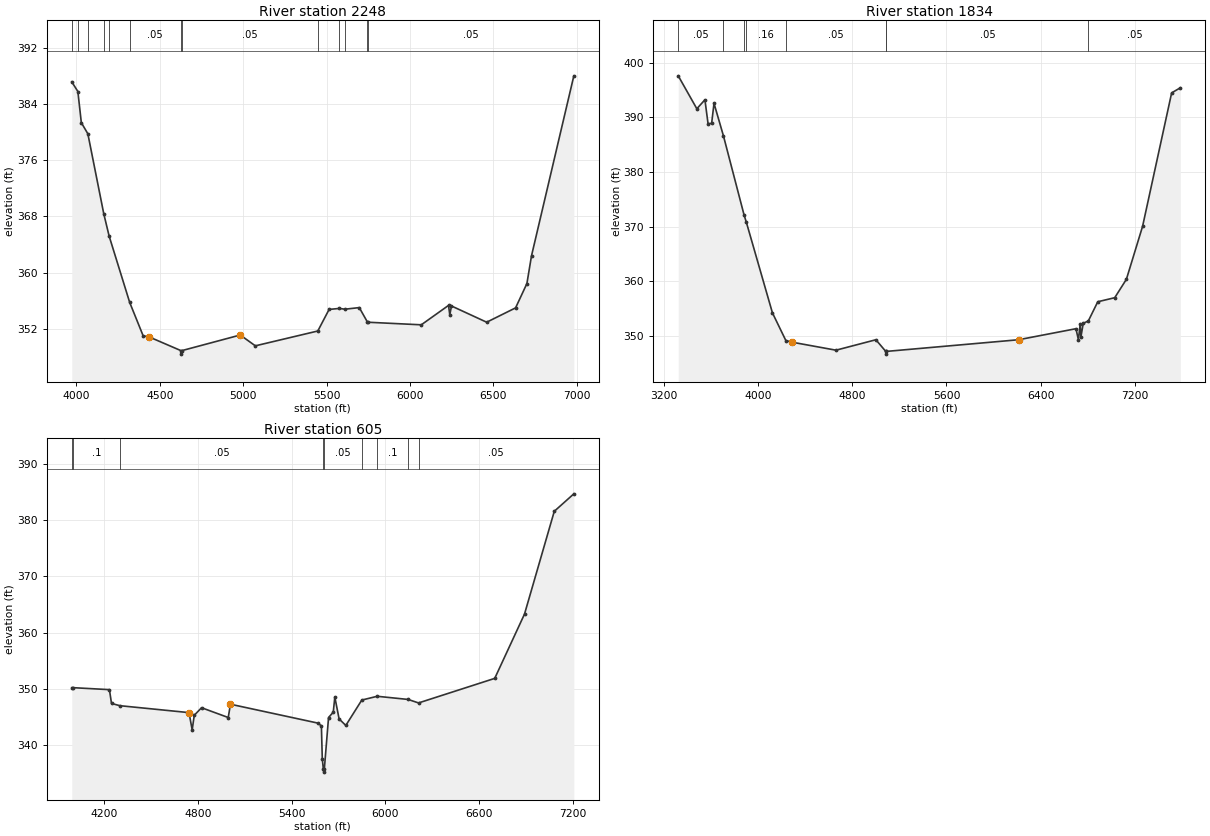
Type RM Length L Ch R = 1 ,2248    ,414,414,414
BEGIN DESCRIPTION:
GRAVEYARD BRANCH 2.0
END DESCRIPTION:
XS GIS Cut Line= 3
      3593899.63     10549460.17      3594699.61     10548860.19
       3594499.6     10546860.14
#Sta/Elev= 30
  3972.7  387.15  4009.2  385.77    4030  381.34  4069.2  379.75  4164.6  368.37
  4196.6  365.21    4320  355.76  4400.8  351.01  4436.2  350.86    4627  348.91
  4629.7  348.41    4633  348.91  4982.7  351.13  5073.2  349.59  5447.7   351.7
  5515.4  354.77  5577.2  354.91  5610.8   354.8  5696.3  355.03  5744.6     353
    5746  352.95  6068.1  352.58  6231.4  355.34    6239  353.99    6249  355.26
  6460.1  352.95  6633.4  354.99  6701.3  358.45  6728.9   362.4  6982.7     388
#Mann= 13 ,-1 , 0
  3972.7     .05       0  4009.2     .08       0  4069.2      .1       0
  4164.6     .16       0  4196.6     .08       0    4320     .05       0
    4627     .03       0    4633     .05       0  5447.7      .1       0
  5577.2     .15       0  5610.8      .1       0  5744.6     .08       0
    5746     .05       0
Bank Sta=4436.2,4982.7
XS Rating Curve= 0 ,0
Exp/Cntr=0.3,0.1

Type RM Length L Ch R = 1 ,1834    ,1229,1229,1229
BEGIN DESCRIPTION:
Mapping XS fc56d79a
END DESCRIPTION:
XS GIS Cut Line= 4
      3593689.59     10549829.11        3594601.     10549690.23
      3595243.36     10548744.05      3594739.89     10546608.65
#Sta/Elev= 30
  3324.5   397.6  3482.3  391.58  3550.9  393.22  3577.4  388.85  3607.8   388.9
    3628  392.57  3708.4  386.59  3883.8  372.09  3901.7  370.87  4123.6  354.25
  4237.3  349.19  4288.6  348.89  4662.9  347.42  5001.3  349.33  5085.1   347.2
  5087.8   346.7  5091.1   347.2  6211.7  349.33  6698.8  351.35  6719.4  349.33
  6735.1  352.27  6740.3  349.79  6760.5  352.33  6803.9  352.78  6883.8  356.28
  7027.6  357.02  7126.4  360.38  7263.9  370.07  7510.5  394.48    7584  395.41
#Mann= 8 ,-1 , 0
  3324.5     .05       0  3708.4     .16       0  3883.8     .08       0
  3901.7     .16       0  4237.3     .05       0  5085.1     .03       0
  5091.1     .05       0  6803.9     .05       0
Bank Sta=4288.6,6211.7
XS Rating Curve= 0 ,0
Exp/Cntr=0.3,0.1

Type RM Length L Ch R = 1 ,605     ,0,0,0
BEGIN DESCRIPTION:
GRAVEYARD BRANCH 1.0
END DESCRIPTION:
XS GIS Cut Line= 3
      3595764.19     10549811.75      3596102.73      10549212.8
      3595885.72     10546695.44
#Sta/Elev= 30
    3992  350.24  4000.1  350.25    4233   349.9  4246.5  347.45  4300.2  347.05
  4742.8  345.82  4762.9  342.75  4776.3  345.35  4823.1  346.69  4993.8  344.95
  5008.1  347.31  5565.9  343.97  5590.3  343.48    5596  337.64    5603  335.75
  5605.8  335.25    5609  335.75  5636.1  344.95  5666.3   345.9  5676.3  348.58
  5703.7   344.7  5746.6  343.54    5849  348.05  5947.8  348.72  6145.4  348.16
  6212.4  347.54  6700.1   351.9  6890.8  363.32  7081.5  381.58  7206.7  384.68
#Mann= 9 ,-1 , 0
    3992     .08       0  4000.1      .1       0  4300.2     .05       0
    5603     .03       0    5609     .05       0    5849     .08       0
  5947.8      .1       0  6145.4     .08       0  6212.4     .05       0
Bank Sta=4742.8,5008.1
XS Rating Curve= 0 ,0
Exp/Cntr=0.3,0.1

Chan Stop Cuts=-1
Use User Specified Reach Order=0
Composite Channel Slope=5