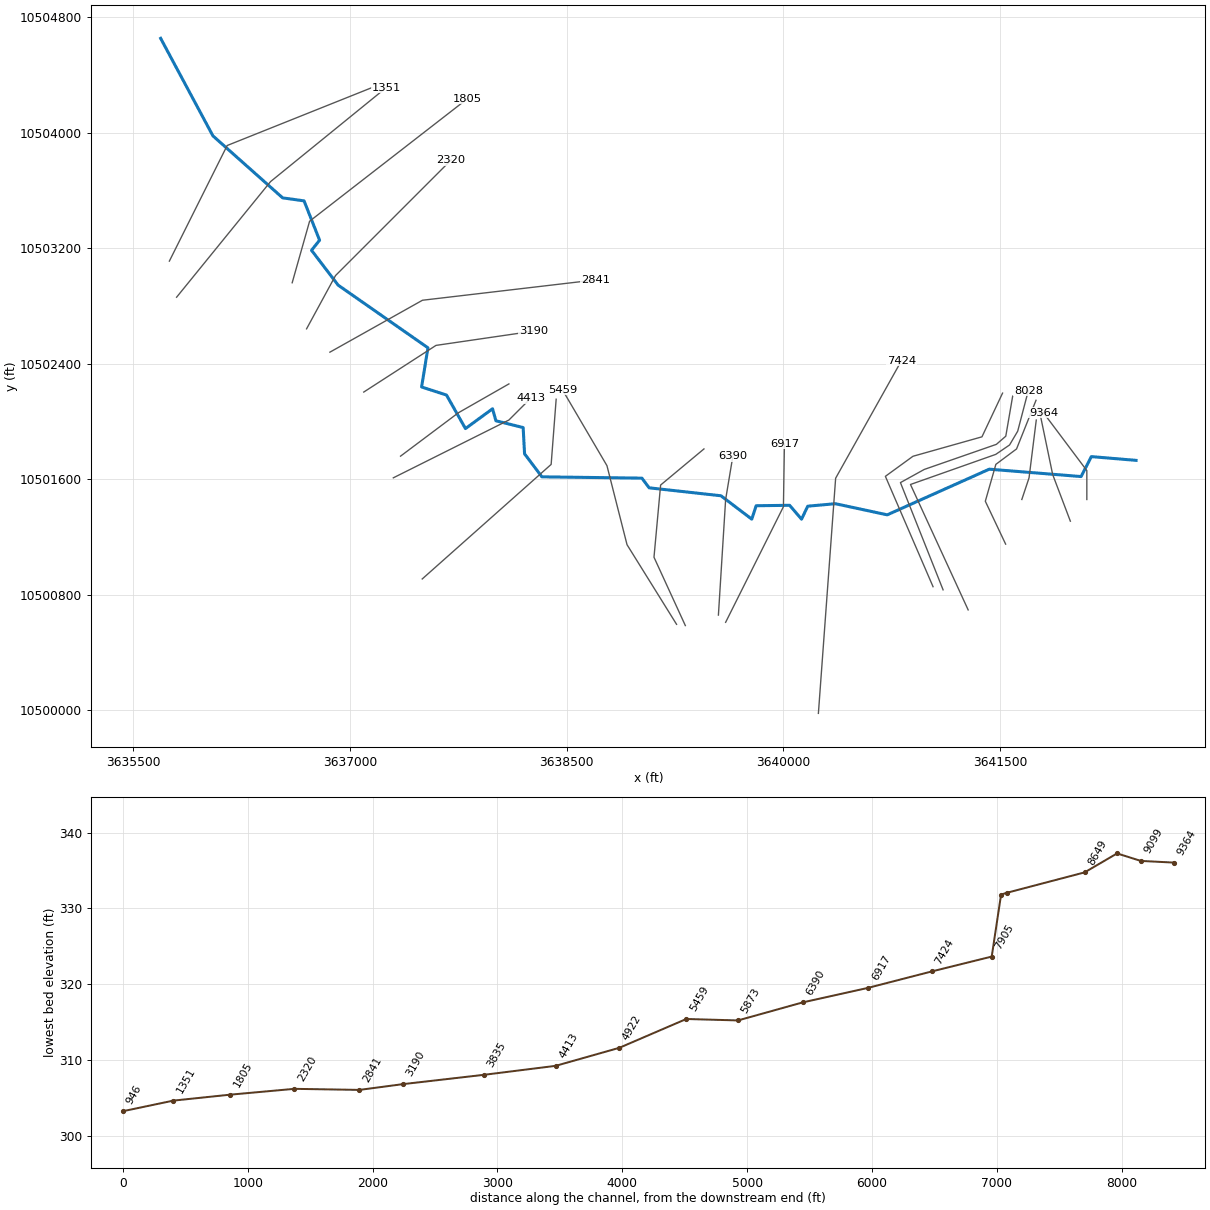
--- HAW BRANCH.prj (project) ---

Proj Title=HAW BRANCH Base Level Engineering
Current Plan=p01
Default Exp/Contr=0.3,0.1
English Units
Geom File=g01
Flow File=f01
Plan File=p01
Y Axis Title=Elevation
X Axis Title(PF)=Main Channel Distance
X Axis Title(XS)=Station
BEGIN DESCRIPTION:
HAW BRANCH
END DESCRIPTION:
DSS Export Rating Curves= 0
DSS Export Rating Curve Sorted= 0
DSS Export Volume Flow Curves= 0
DXF OffsetX= 0
DXF OffsetY= 0
DXF ScaleX= 1
DXF ScaleY= 10

--- HAW BRANCH.p01 (plan) ---

Plan Title=Multiple Run
Short Identifier=Multiple
Geom File=g01
Flow File=f01
Subcritical Flow
K Sum by GR= 0
Std Step Tol= 0.01
Critical Tol= 0.01
Num of Std Step Trials= 20
Max Error Tol= 0.3
Flow Tol Ratio= 0.001
Split Flow NTrial= 30
Split Flow Tol= 0.02
Split Flow Ratio= 0.02
Log Output Level= 0
Friction Slope Method= 1
Unsteady Friction Slope Method= 2
Unsteady Bridges Friction Slope Method= 1
Parabolic Critical Depth
Global Vel Dist=  1 , 1 , 1
Global Log Level= 0
CheckData=True
Encroach Param= -1, 0, 0, 0
BEGIN DESCRIPTION:
Multiple Run
END DESCRIPTION:

--- HAW BRANCH.f01 (steady flow) ---

Flow Title=Multiple
Program Version=4.10
Number of Profiles= 7
Profile Names=10-year,25-year,50-year,1pct_min,100-year,1pct_plu,500-year
River Rch & RM=HAW BRANCH,Reach-1         ,9364
    1217    1697    2100    1898    2567    3472    3823
River Rch & RM=HAW BRANCH,Reach-1         ,9099
    1424    1995    2475    2241    3030    4098    4528
River Rch & RM=HAW BRANCH,Reach-1         ,6917
    1424    1995    2475    2241    3030    4098    4528
River Rch & RM=HAW BRANCH,Reach-1         ,5459
    3762    5543    7116    6644    8986   12152   14295
River Rch & RM=HAW BRANCH,Reach-1         ,3835
    3762    5543    7116    6644    8986   12152   14295
Boundary for River Rch & Prof#=HAW BRANCH,Reach-1         , 1
Up Type= 0
Dn Type= 3
Dn Slope=0.003
Boundary for River Rch & Prof#=HAW BRANCH,Reach-1         , 2
Up Type= 0
Dn Type= 3
Dn Slope=0.003
Boundary for River Rch & Prof#=HAW BRANCH,Reach-1         , 3
Up Type= 0
Dn Type= 3
Dn Slope=0.003
Boundary for River Rch & Prof#=HAW BRANCH,Reach-1         , 4
Up Type= 0
Dn Type= 3
Dn Slope=0.003
Boundary for River Rch & Prof#=HAW BRANCH,Reach-1         , 5
Up Type= 0
Dn Type= 3
Dn Slope=0.003
Boundary for River Rch & Prof#=HAW BRANCH,Reach-1         , 6
Up Type= 0
Dn Type= 3
Dn Slope=0.003
Boundary for River Rch & Prof#=HAW BRANCH,Reach-1         , 7
Up Type= 0
Dn Type= 3
Dn Slope=0.003
DSS Import GetInterval= 0
DSS Import GetPeak= 0
DSS Import FillOption= 0

--- HAW BRANCH.g01 (geometry) ---

Geom Title=Existing Conditions
Program Version=4.10

River Reach=HAW BRANCH      ,Reach-1
Reach XY= 30
      3642440.25       10501731.      3642130.75       10501757.
        3642060.       10501619.      3641424.25       10501670.
        3640718.       10501354.       3640359.5       10501431.
        3640168.       10501414.        3640125.       10501324.
       3640042.5       10501420.      3639810.75       10501417.
       3639780.5       10501324.      3639567.25       10501486.
      3639070.25       10501541.        3639020.       10501608.
      3638328.25       10501617.        3638208.       10501776.
      3638198.25       10501958.      3638009.75       10502005.
      3637986.25       10502088.        3637799.       10501951.
      3637667.75       10502183.      3637495.25       10502239.
      3637539.25       10502510.       3636917.5       10502944.
       3636733.5       10503185.      3636789.25       10503255.
      3636681.75       10503527.      3636533.25       10503548.
        3636051.       10503977.      3635689.25       10504652.

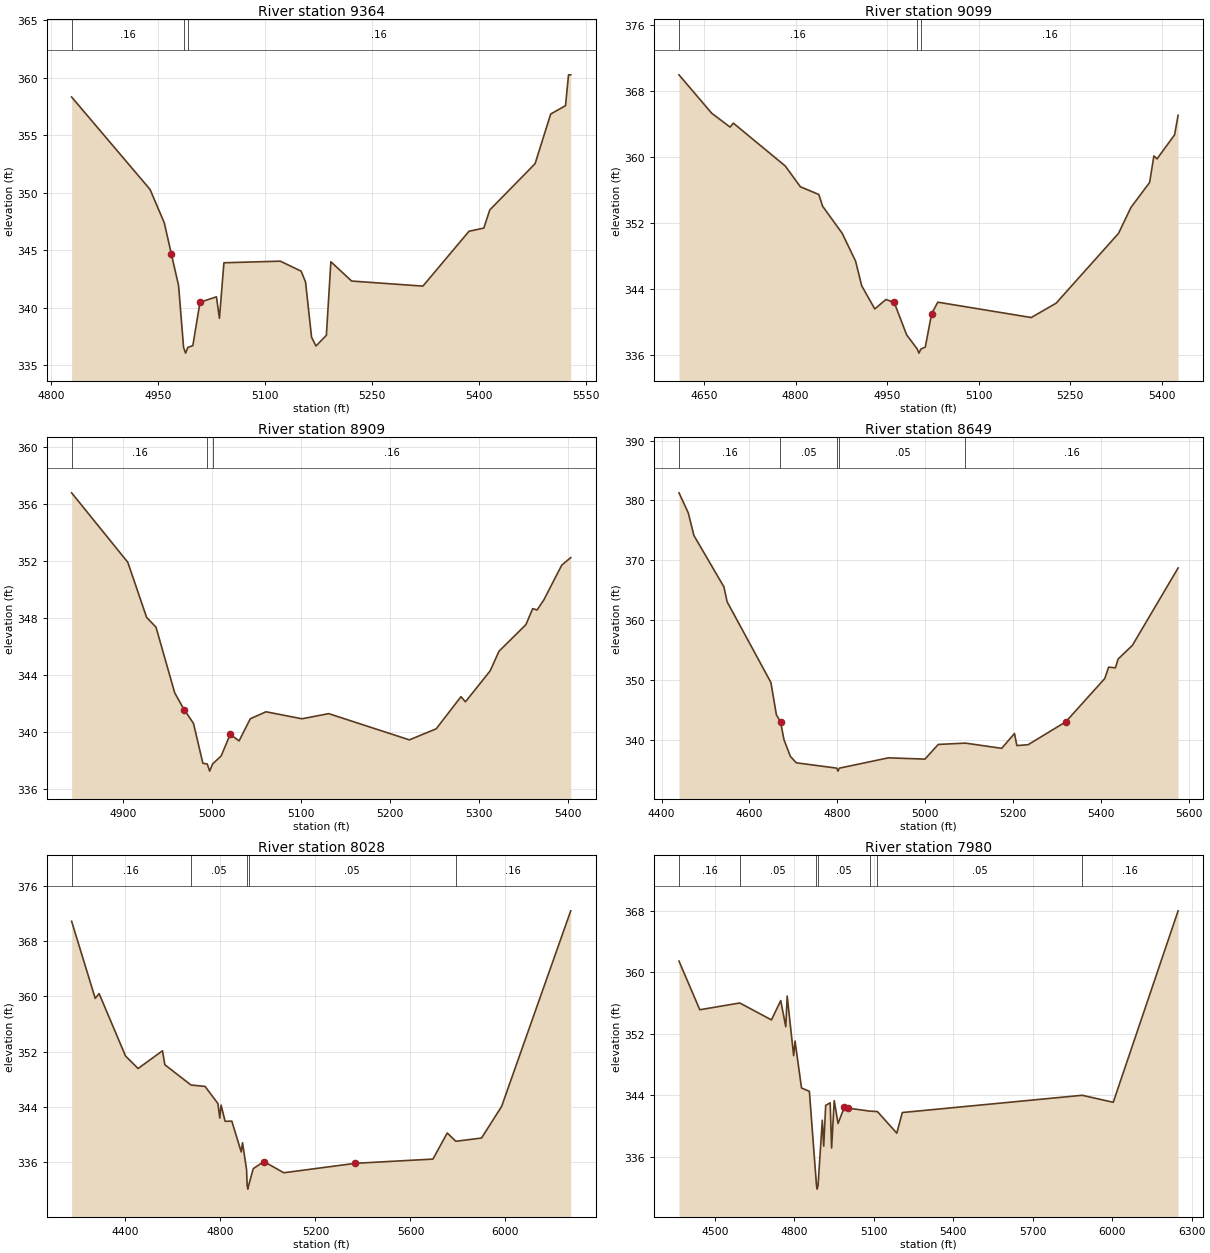
Type RM Length L Ch R = 1 ,9364    ,265,265,265
BEGIN DESCRIPTION:
HAW BRANCH 18.0
END DESCRIPTION:
XS GIS Cut Line= 3
      3642099.61     10501460.16      3642099.61     10501660.19
      3641799.62     10502060.17
#Sta/Elev= 30
  4828.5  358.32  4938.5  350.28  4958.5  347.37  4968.5  344.63  4978.5  341.92
  4985.5  336.54  4988.3  336.04  4991.5  336.54  4998.5  336.69  5008.5  340.46
  5031.6  340.94  5035.8  339.07  5042.1   343.9  5121.2  344.04  5150.4  343.17
  5156.6  342.22    5165  337.43  5171.2  336.66  5185.8  337.59  5192.1  343.99
  5221.2  342.31  5321.2  341.87  5385.8  346.64  5406.6  346.92    5415   348.5
  5478.5  352.52  5500.4  356.84  5521.2  357.57  5525.4  360.25  5528.5  360.25
#Mann= 3 ,-1 , 0
  4828.5     .16       0  4985.5     .07       0  4991.5     .16       0
Bank Sta=4968.5,5008.5
XS Rating Curve= 0 ,0
Exp/Cntr=0.3,0.1

Type RM Length L Ch R = 1 ,9099    ,190,190,190
BEGIN DESCRIPTION:
Mapping XS f8c0b121
END DESCRIPTION:
XS GIS Cut Line= 3
      3641985.53     10501310.09      3641863.12     10501633.04
      3641766.91     10502095.88
#Sta/Elev= 30
  4608.9  369.96  4662.5  365.31  4692.7  363.63    4698  364.11  4783.1  358.92
  4807.9   356.4  4838.1  355.47  4844.3  354.05  4876.4  350.77  4898.4  347.39
  4908.4  344.41  4929.8  341.61    4948  342.75  4961.6  342.41    4982  338.48
  4999.4  336.76  5002.2  336.26  5005.4  336.76  5012.6  336.99  5022.9  341.01
  5033.1  342.43  5186.3  340.57  5227.1  342.31  5329.3  350.76  5349.7   353.9
  5380.3  356.93  5387.3  360.14  5392.4  359.78  5421.2  362.69    5427  365.06
#Mann= 3 ,-1 , 0
  4608.9     .16       0  4999.4     .07       0  5005.4     .16       0
Bank Sta=4961.6,5022.9
XS Rating Curve= 0 ,0
Exp/Cntr=0.3,0.1

Type RM Length L Ch R = 1 ,8909    ,260,260,260
BEGIN DESCRIPTION:
HAW BRANCH 17.0
END DESCRIPTION:
XS GIS Cut Line= 3
      3641649.61      10501460.2      3641699.61     10501610.19
      3641749.61     10502010.18
#Sta/Elev= 30
  4842.1  356.76  4905.3  351.89  4926.4  348.03    4937  347.34    4958  342.74
  4968.6  341.56  4979.1   340.6  4989.7   337.8  4994.6  337.75  4997.3  337.25
  5000.6  337.75  5010.3  338.32  5020.4  339.83  5030.4  339.37    5043  340.92
  5060.7  341.41    5101  340.92  5131.2  341.28  5221.9  339.44  5252.1  340.22
  5279.9  342.47  5284.9  342.11  5312.6  344.27  5322.7  345.66  5352.9  347.52
  5360.5  348.64  5365.5  348.55  5373.1  349.26  5393.2  351.69  5403.3  352.22
#Mann= 3 ,-1 , 0
  4842.1     .16       0  4994.6     .07       0  5000.6     .16       0
Bank Sta=4968.6,5020.4
XS Rating Curve= 0 ,0
Exp/Cntr=0.3,0.1

Type RM Length L Ch R = 1 ,8649    ,621,621,621
BEGIN DESCRIPTION:
Mapping XS 99e114c8
END DESCRIPTION:
XS GIS Cut Line= 5
      3641537.61     10501151.24      3641396.97     10501448.14
      3641469.89     10501703.35      3641613.12     10501810.12
      3641747.83     10502146.89
#Sta/Elev= 30
  4439.7  381.26  4460.7  377.93  4473.7  374.12  4541.9  365.54  4549.2  363.05
  4648.8  349.56  4661.2  344.18  4669.8  343.08  4670.9  342.94  4678.4  340.03
    4693  337.22  4706.6  336.14  4798.6  335.25  4801.3  334.75  4804.6  335.25
    4916  336.97  4999.2  336.76  5029.4  339.21  5091.3  339.43  5173.7  338.56
  5202.9  341.04  5208.2  339.02  5233.9  339.17  5319.3  342.98  5408.2  350.23
    5417  352.13  5432.4  352.02  5438.5  353.48  5470.9  355.76    5575   368.7
#Mann= 5 ,-1 , 0
  4439.7     .16       0  4669.8     .05       0  4798.6    .035       0
  4804.6     .05       0  5091.3     .16       0
Bank Sta=4670.9,5319.3
XS Rating Curve= 0 ,0
Exp/Cntr=0.3,0.1

Type RM Length L Ch R = 1 ,8028    ,48,48,48
BEGIN DESCRIPTION:
Mapping XS 88ca6cbc
END DESCRIPTION:
XS GIS Cut Line= 6
      3641278.21     10500696.06      3640878.92      10501564.1
       3641469.2     10501772.43      3641564.68     10501837.54
      3641621.11     10501933.02      3641694.74     10502214.58
#Sta/Elev= 30
  4173.5  370.87  4272.9   359.7  4289.3  360.39  4400.5  351.35  4453.4  349.54
  4556.1  352.11  4566.2  350.08  4676.1  347.15  4735.2  346.95  4789.6  344.46
  4797.3  342.36  4802.8  344.24  4819.8  341.89    4848  341.92  4887.5  337.46
  4893.1  338.79  4910.1  334.89  4912.6  332.57  4915.4  332.07  4918.6  332.57
  4938.2  335.04  4983.3  336.06  5066.8  334.44  5368.6  335.81  5694.7  336.42
    5755   340.2    5791     339  5899.3  339.47  5983.9  344.05  6274.9  372.38
#Mann= 5 ,-1 , 0
  4173.5     .16       0  4676.1     .05       0  4912.6    .035       0
  4918.6     .05       0    5791     .16       0
Bank Sta=4983.3,5368.6
XS Rating Curve= 0 ,0
Exp/Cntr=0.3,0.1

Type RM Length L Ch R = 1 ,7980    ,75,75,75
BEGIN DESCRIPTION:
HAW BRANCH 16.0
END DESCRIPTION:
XS GIS Cut Line= 6
      3641104.61     10500834.94      3640809.47     10501577.12
       3640974.4     10501668.26      3641473.54     10501841.88
      3641538.64      10501898.3       3641586.3     10502175.59
#Sta/Elev= 30
  4364.1  361.45  4442.7  355.13  4593.7  356.01  4713.2  353.81  4748.3  356.32
  4767.3  352.92  4772.7  356.91  4797.1  349.17  4802.4  351.06  4826.8  344.97
  4856.5  344.53  4883.3  332.33    4886  331.83  4889.3  332.33  4905.3  340.78
  4910.6  337.41  4918.1  342.71    4935  343.04  4940.4  337.17  4950.3  343.33
  4964.8  340.36  4989.1  342.52  5004.1  342.35  5084.5  341.96  5113.3  341.91
  5186.6   339.1  5207.5  341.78  5886.9  344.02    6004  343.11    6249  367.98
#Mann= 7 ,-1 , 0
  4364.1     .16       0  4593.7     .05       0  4883.3    .035       0
  4889.3     .05       0  5084.5     .16       0  5113.3     .05       0
  5886.9     .16       0
Bank Sta=4989.1,5004.1
XS Rating Curve= 0 ,0
Exp/Cntr=0.3,0.1

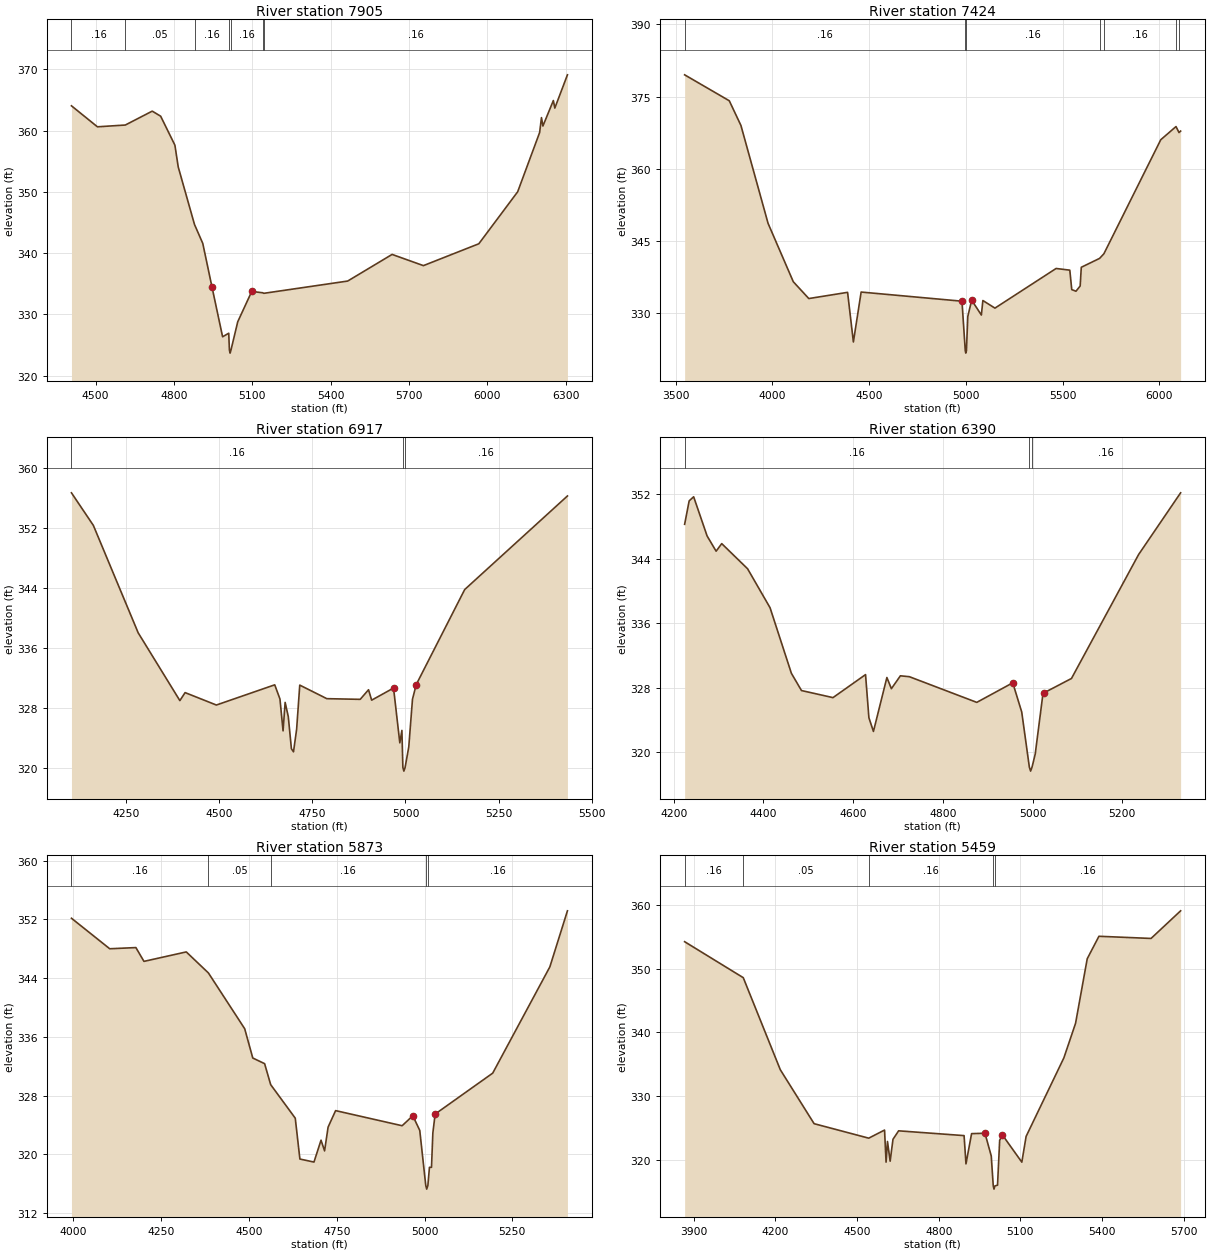
Type RM Length L Ch R = 1 ,7905    ,481,481,481
BEGIN DESCRIPTION:
HAW BRANCH 15.0
END DESCRIPTION:
XS GIS Cut Line= 5
      3641035.16     10500856.65      3640705.31     10501620.52
      3640896.28     10501759.41      3641373.71     10501893.96
      3641516.34     10502196.51
#Sta/Elev= 30
  4407.4  364.05  4506.8  360.62  4613.5  360.91  4716.6  363.18  4748.9  362.35
  4803.4  357.62  4816.1  354.07  4878.4  344.67  4910.1  341.58    4945  334.53
    4986  326.33  5009.5  326.91    5012  324.16  5014.7  323.66    5018  324.16
  5043.9  328.78  5097.5  333.73  5139.1  333.52  5144.2  333.43  5464.8  335.43
  5634.9  339.78  5754.7  337.95  5966.9  341.52  6115.6  350.01  6199.6  359.68
  6206.7  362.12  6212.2  360.75  6252.2  364.91  6257.8  363.68  6306.1  369.11
#Mann= 7 ,-1 , 0
  4407.4     .16       0  4613.5     .05       0  4878.4     .16       0
    5012     .07       0    5018     .16       0  5139.1     .05       0
  5144.2     .16       0
Bank Sta=4945,5097.5
XS Rating Curve= 0 ,0
Exp/Cntr=0.3,0.1

Type RM Length L Ch R = 1 ,7424    ,507,507,507
BEGIN DESCRIPTION:
HAW BRANCH 14.0
END DESCRIPTION:
XS GIS Cut Line= 3
      3640241.62     10499979.89      3640360.98      10501607.5
      3640816.71     10502421.31
#Sta/Elev= 30
    3546  379.53  3776.9  374.14  3837.1  369.01  3977.4  348.67  4107.8  336.54
    4188  333.04  4388.6  334.33  4418.6  324.02  4458.7  334.39  4980.1  332.49
  4997.2   322.2  4999.9   321.7  5003.2   322.2  5010.2  329.32  5030.3   332.7
  5080.4  329.62  5088.2  332.63  5150.6  331.05  5466.9  339.29  5537.7  338.94
  5547.8   334.9  5569.6  334.56  5591.3  335.65  5597.1  339.54  5691.5  341.38
  5713.9  342.34    6008  366.04  6086.9  368.78  6102.4  367.53  6110.7  367.84
#Mann= 7 ,-1 , 0
    3546     .16       0  4997.2     .07       0  5003.2     .16       0
  5691.5     .08       0  5713.9     .16       0  6086.9     .08       0
  6102.4     .05       0
Bank Sta=4980.1,5030.3
XS Rating Curve= 0 ,0
Exp/Cntr=0.3,0.1

Type RM Length L Ch R = 1 ,6917    ,527,527,527
BEGIN DESCRIPTION:
HAW BRANCH 13.0
END DESCRIPTION:
XS GIS Cut Line= 3
      3639599.59     10500610.16      3639999.61     10501410.19
      3640006.51     10501845.67
#Sta/Elev= 30
  4104.4  356.73  4163.1  352.38  4283.3  338.03  4395.1  328.97  4409.1  330.04
    4493  328.38  4649.5  331.08  4663.5  329.18  4671.8  324.93  4677.4  328.73
  4685.8  326.84  4694.2  322.54  4699.8  322.13  4708.2  325.14  4716.6  331.04
  4789.2  329.23  4878.7  329.14    4901  330.42  4909.4  329.03  4968.1  330.65
  4984.9  323.33  4990.5  324.99  4993.1  320.05  4995.8  319.55  4999.1  320.05
  5008.9  322.78  5018.9  329.16  5028.9  331.11  5158.9  343.81  5434.4  356.31
#Mann= 3 ,-1 , 0
  4104.4     .16       0  4993.1     .07       0  4999.1     .16       0
Bank Sta=4968.1,5028.9
XS Rating Curve= 0 ,0
Exp/Cntr=0.3,0.1

Type RM Length L Ch R = 1 ,6390    ,517,517,517
BEGIN DESCRIPTION:
HAW BRANCH 12.0
END DESCRIPTION:
XS GIS Cut Line= 3
      3639549.61     10500660.15      3639599.61     10501460.19
       3639649.6     10501760.15
#Sta/Elev= 30
  4224.3  348.28  4234.4  351.19  4244.4   351.7  4274.4  346.83  4294.5  344.94
    4307  345.88  4364.6  342.76  4414.7  337.92  4462.3  329.77  4484.8  327.63
    4555  326.75  4627.6  329.61  4635.1  324.25  4645.2  322.55  4675.2  329.25
  4685.2  327.86  4705.3  329.46  4725.3  329.35  4875.6  326.16  4955.8  328.59
  4975.8  324.96  4992.8  318.12  4995.6  317.62  4998.8  318.12  5005.9  319.75
  5023.4  327.36  5025.9  327.36  5086.7  329.13  5236.3  344.52    5330  352.19
#Mann= 3 ,-1 , 0
  4224.3     .16       0  4992.8     .07       0  4998.8     .16       0
Bank Sta=4955.8,5025.9
XS Rating Curve= 0 ,0
Exp/Cntr=0.3,0.1

Type RM Length L Ch R = 1 ,5873    ,414,414,414
BEGIN DESCRIPTION:
HAW BRANCH 11.0
END DESCRIPTION:
XS GIS Cut Line= 4
      3639320.74     10500587.57      3639103.74     10501060.63
      3639149.61     10501560.19      3639449.59     10501810.17
#Sta/Elev= 30
  3994.5  352.17  4103.5  348.01    4178  348.17    4201  346.29  4321.5  347.58
  4384.6  344.71  4487.9  337.11  4510.9  333.12  4544.6  332.35  4561.9  329.49
  4631.9  324.92  4645.1  319.35  4685.2  318.94  4705.3  321.92  4715.4  320.46
  4725.4   323.7  4746.8  325.95  4936.3  323.89  4966.7  325.25  4986.5  323.25
  5003.6  315.75  5006.3  315.25  5009.6  315.75  5014.1  318.22  5019.9  318.22
  5023.8  322.91  5030.3  325.48  5194.3  331.06    5357  345.54  5407.1  353.18
#Mann= 5 ,-1 , 0
  3994.5     .16       0  4384.6     .05       0  4561.9     .16       0
  5003.6     .07       0  5009.6     .16       0
Bank Sta=4966.7,5030.3
XS Rating Curve= 0 ,0
Exp/Cntr=0.3,0.1

Type RM Length L Ch R = 1 ,5459    ,537,537,537
BEGIN DESCRIPTION:
HAW BRANCH 10.0
END DESCRIPTION:
XS GIS Cut Line= 4
      3639259.98     10500596.25      3638917.11     10501147.43
      3638778.22     10501694.31      3638470.05     10502219.51
#Sta/Elev= 30
  3866.3  354.23  4081.7  348.59  4217.8  334.16    4342   325.7  4542.7  323.43
  4600.8   324.7  4606.4  319.67  4611.6  322.91  4621.4  319.82  4631.8  323.25
  4652.5  324.58    4893  323.83    4900   319.4  4920.6  324.14  4969.8   324.2
  4992.9  320.63  5000.2  315.94  5002.9  315.44  5006.2  315.94  5015.9  316.06
  5023.8   323.1  5034.1  323.92  5105.2  319.67  5120.9   323.7  5259.6  336.01
  5302.6  341.43  5345.5  351.56  5388.5  355.08    5580  354.74  5688.6  359.07
#Mann= 5 ,-1 , 0
  3866.3     .16       0  4081.7     .05       0  4542.7     .16       0
  5000.2     .07       0  5006.2     .16       0
Bank Sta=4969.8,5034.1
XS Rating Curve= 0 ,0
Exp/Cntr=0.3,0.1

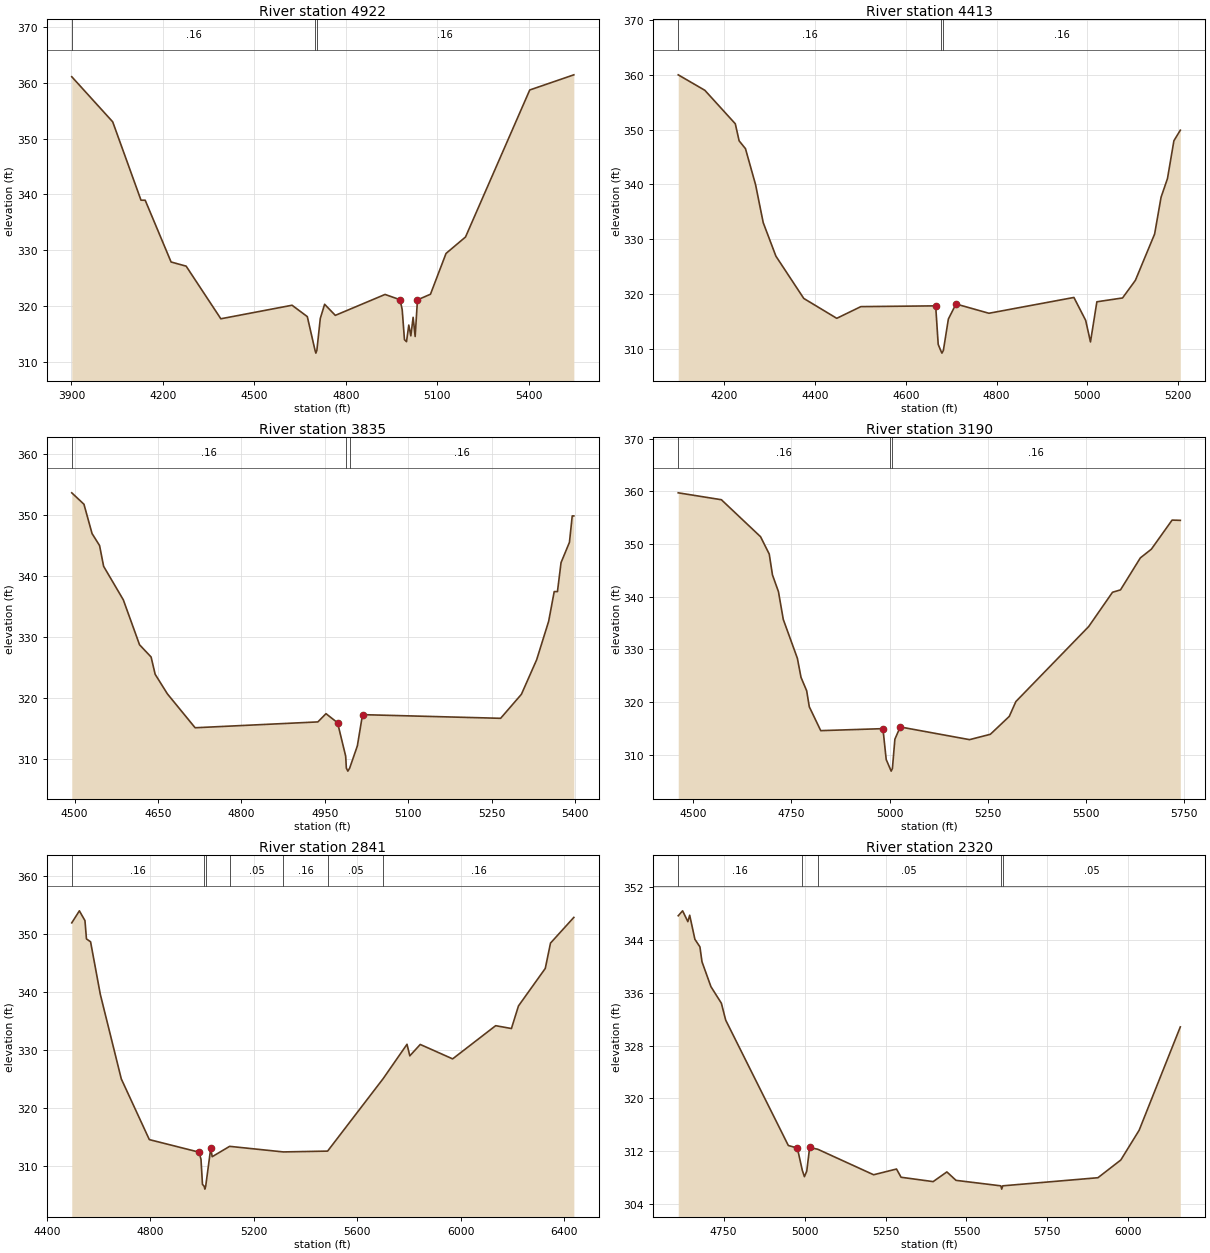
Type RM Length L Ch R = 1 ,4922    ,509,509,509
BEGIN DESCRIPTION:
HAW BRANCH 9.0
END DESCRIPTION:
XS GIS Cut Line= 3
      3637499.62      10500910.2      3638391.94     10501702.99
      3638426.66     10502154.33
#Sta/Elev= 30
  3901.2  361.05  4035.4  352.99  4128.2  338.98    4142  338.97  4226.9  327.93
  4276.2  327.19    4390  317.78  4623.5   320.2  4673.5  318.17  4698.9  312.14
  4701.6  311.64  4704.9  312.14  4716.1  317.84  4730.3  320.37  4765.4  318.39
  4928.5  322.13  4977.8  321.18  4984.7   319.4  4992.1  314.04  4998.8  313.69
  5006.3  316.66    5013  314.73  5020.5  318.04  5027.2  314.61  5034.7  321.16
  5077.4  322.17  5128.4  329.46  5192.3   332.4  5402.9  358.68  5547.5  361.39
#Mann= 3 ,-1 , 0
  3901.2     .16       0  4698.9     .07       0  4704.9     .16       0
Bank Sta=4977.8,5034.7
XS Rating Curve= 0 ,0
Exp/Cntr=0.3,0.1

Type RM Length L Ch R = 1 ,4413    ,578,578,578
BEGIN DESCRIPTION:
HAW BRANCH 8.0
END DESCRIPTION:
XS GIS Cut Line= 3
      3637299.58     10501610.17      3638099.61     10502010.19
      3638249.61     10502160.19
#Sta/Elev= 30
  4098.3  359.96    4157  357.14  4224.1  351.04  4232.5  347.94  4246.5  346.51
  4268.8  339.94  4285.6  333.04  4313.6  326.93    4375  319.23  4447.7  315.61
  4500.8  317.74  4665.7  317.88  4671.3  310.86  4676.7  309.77  4679.5  309.27
  4682.7  309.77  4693.7  315.48  4710.5  318.22  4783.1  316.53  4970.4  319.41
  4996.3  315.24  5006.9  311.31    5021  318.62  5077.6  319.32  5105.9  322.53
  5148.3  330.97  5162.5  337.67  5176.6  341.06  5190.8  347.96  5204.9  349.87
#Mann= 3 ,-1 , 0
  4098.3     .16       0  4676.7     .07       0  4682.7     .16       0
Bank Sta=4665.7,4710.5
XS Rating Curve= 0 ,0
Exp/Cntr=0.3,0.1

Type RM Length L Ch R = 1 ,3835    ,645,645,645
BEGIN DESCRIPTION:
HAW BRANCH 7.0
END DESCRIPTION:
XS GIS Cut Line= 3
       3637349.6     10501760.18      3637749.61     10502060.19
      3638099.59     10502260.18
#Sta/Elev= 30
  4494.8  353.71  4516.7  351.84  4531.3  347.03  4544.8  345.07  4552.1  341.66
  4587.5  336.17  4616.7   328.8  4637.5  326.79  4644.8  323.96  4666.7  320.76
  4716.7  315.19  4937.5  316.15  4952.1   317.5  4972.9  316.01  4987.5  310.53
  4988.7  308.58  4991.4  308.08  4994.7  308.58  5008.5  312.22  5017.8  317.34
  5266.2  316.74  5303.6  320.68    5331  326.34  5352.6  332.65  5362.6  337.52
  5368.4  337.51  5374.9  342.27    5390   345.6    5395  349.92  5397.9  349.92
#Mann= 3 ,-1 , 0
  4494.8     .16       0  4988.7     .07       0  4994.7     .16       0
Bank Sta=4972.9,5017.8
XS Rating Curve= 0 ,0
Exp/Cntr=0.3,0.1

Type RM Length L Ch R = 1 ,3190    ,349,349,349
BEGIN DESCRIPTION:
HAW BRANCH 6.0
END DESCRIPTION:
XS GIS Cut Line= 3
      3637095.04     10502203.84      3637595.06     10502526.77
      3638270.26     10502625.45
#Sta/Elev= 30
    4462  359.73  4571.8  358.42  4671.5  351.39  4693.6  348.09  4701.8  344.13
    4717  340.96  4729.3  335.68  4765.2  328.29  4774.4  324.68  4788.8  322.13
  4795.5  319.09  4824.6  314.55  4982.9  314.93  4991.2  309.07    5001  307.36
  5003.8  306.86    5007  307.36  5013.3  312.93  5026.9  315.25  5203.3  312.84
  5256.3  313.86  5304.4  317.26  5321.2  320.08  5506.5  334.33  5567.1  340.84
  5587.4  341.29  5637.9  347.37  5665.9  349.02  5718.7  354.55  5739.6   354.5
#Mann= 3 ,-1 , 0
    4462     .16       0    5001     .07       0    5007     .16       0
Bank Sta=4982.9,5026.9
XS Rating Curve= 0 ,0
Exp/Cntr=0.3,0.1

Type RM Length L Ch R = 1 ,2841    ,521,521,521
BEGIN DESCRIPTION:
HAW BRANCH 5.0
END DESCRIPTION:
XS GIS Cut Line= 3
      3636860.68     10502479.89      3637501.31     10502839.27
      3638699.24      10502979.9
#Sta/Elev= 30
  4495.8  351.91  4525.2  353.98  4546.8  352.29  4552.6  349.15  4568.5  348.65
  4606.2   339.6  4687.2  325.07  4795.6  314.62  4987.6  312.46  4995.3  311.23
    5001  306.92  5007.5   306.6  5010.3   306.1  5013.5   306.6  5032.9  313.11
  5038.6  311.68    5106  313.46  5313.5   312.5  5484.7  312.64  5699.6  325.12
  5791.6  331.02  5802.5  329.03  5842.8  330.99    5968  328.51  6134.3  334.22
  6195.2  333.73  6222.5  337.62  6326.1  344.07  6346.3  348.43  6436.5  352.85
#Mann= 7 ,-1 , 0
  4495.8     .16       0  5007.5     .07       0  5013.5     .16       0
    5106     .05       0  5313.5     .16       0  5484.7     .05       0
  5699.6     .16       0
Bank Sta=4987.6,5032.9
XS Rating Curve= 0 ,0
Exp/Cntr=0.3,0.1

Type RM Length L Ch R = 1 ,2320    ,515,515,515
BEGIN DESCRIPTION:
HAW BRANCH 4.0
END DESCRIPTION:
XS GIS Cut Line= 3
      3636699.22     10502641.34      3636899.61     10503010.19
      3637699.58     10503810.16
#Sta/Elev= 30
  4609.6  347.71  4623.1  348.46  4639.3  346.82    4645  347.79  4661.1  344.14
  4676.6  342.99    4683  340.73  4710.7  336.95  4742.9  334.44  4756.2  331.88
  4949.7  312.86  4977.6  312.47  4992.9   309.1  4999.4  308.13  5006.6  308.95
  5015.6  312.56  5040.6  312.29  5213.2  308.42  5283.9  309.29  5298.1  308.04
  5397.1  307.38  5439.5  308.85  5467.8  307.57  5606.2  306.74  5608.9  306.24
  5612.2  306.74  5906.2  307.97  5976.9  310.66  6033.5  315.17  6160.7  330.85
#Mann= 5 ,-1 , 0
  4609.6     .16       0  4992.9     .12       0  5040.6     .05       0
  5606.2     .07       0  5612.2     .05       0
Bank Sta=4977.6,5015.6
XS Rating Curve= 0 ,0
Exp/Cntr=0.3,0.1

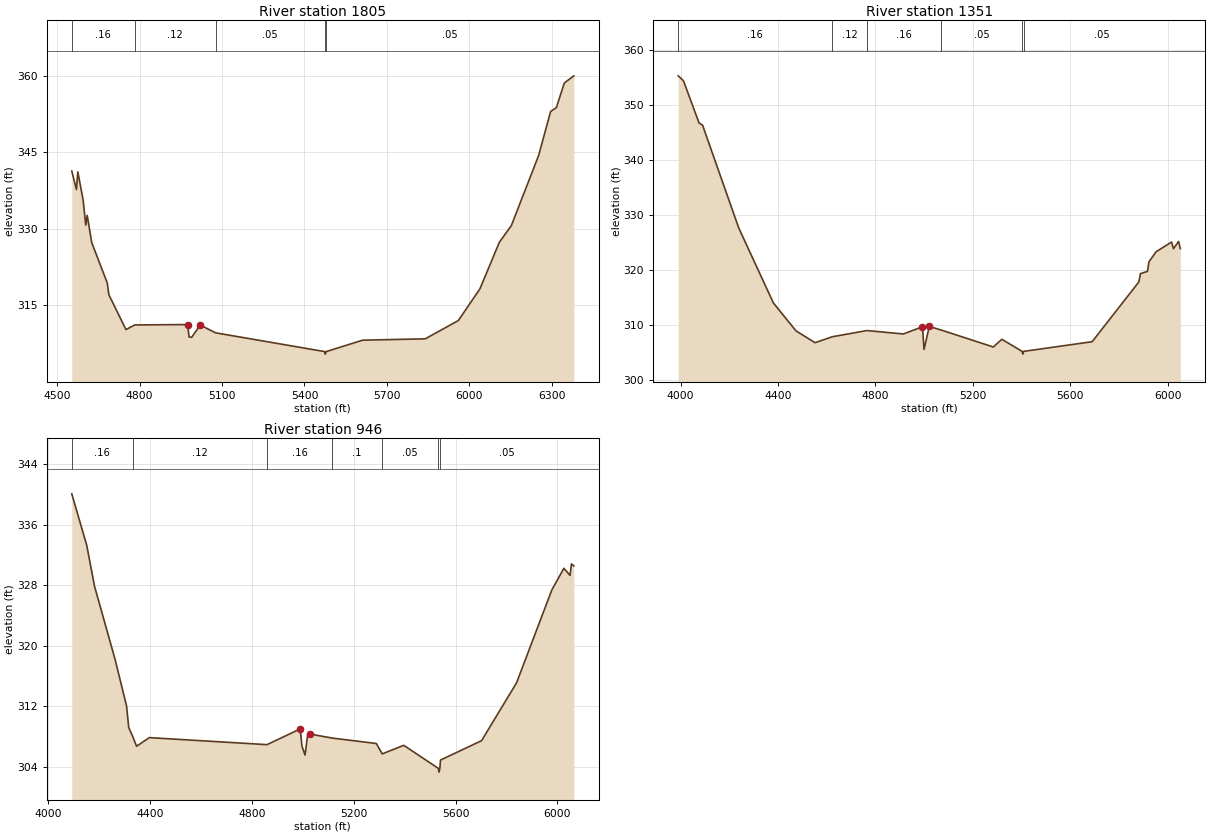
Type RM Length L Ch R = 1 ,1805    ,454,454,454
BEGIN DESCRIPTION:
HAW BRANCH 3.0
END DESCRIPTION:
XS GIS Cut Line= 3
      3636599.62     10502960.22      3636720.06     10503386.15
      3637813.82     10504235.11
#Sta/Elev= 30
  4553.2  341.34  4570.1  337.73  4575.3  341.17  4594.7  335.61  4604.1  330.74
  4609.3  332.66  4625.9  327.32  4682.4  319.41  4688.3  317.09  4750.4  310.28
  4782.6  311.19  4974.9  311.26  4980.1  308.83  4989.6  308.76  5020.6  311.17
  5076.8  309.64  5473.3  305.97    5476  305.47  5479.3  305.97  5611.6   308.2
  5839.7  308.47  5960.1  312.05  6038.8  318.28  6109.4  327.39  6152.9  330.64
  6252.4   344.4  6295.9  353.01  6316.7  353.75  6345.7  358.58  6380.4  359.99
#Mann= 5 ,-1 , 0
  4553.2     .16       0  4782.6     .12       0  5076.8     .05       0
  5473.3     .07       0  5479.3     .05       0
Bank Sta=4974.9,5020.6
XS Rating Curve= 0 ,0
Exp/Cntr=0.3,0.1

Type RM Length L Ch R = 1 ,1351    ,405,405,405
BEGIN DESCRIPTION:
HAW BRANCH 2.0
END DESCRIPTION:
XS GIS Cut Line= 3
      3635799.61     10502860.19      3636449.61     10503660.19
      3637249.57     10504310.16
#Sta/Elev= 30
  3990.5  355.35    4012  354.45    4076  346.77  4090.3  346.38    4239  327.65
  4381.2  314.01  4473.9  308.93  4552.2  306.77    4623  307.85  4765.1  308.98
    4915  308.36  4993.3  309.67  4999.7  305.55  5021.3  309.72  5070.6  309.07
  5284.2  305.99  5319.4  307.39  5402.6  305.19  5405.3  304.69  5408.6  305.19
    5690  306.95  5881.8  317.83  5888.3  319.34    5917  319.75  5923.4  321.49
  5952.2  323.31  6016.1   325.1    6024  323.88  6044.9   325.2    6052  323.89
#Mann= 6 ,-1 , 0
  3990.5     .16       0    4623     .12       0  4765.1     .16       0
  5070.6     .05       0  5402.6     .07       0  5408.6     .05       0
Bank Sta=4993.3,5021.3
XS Rating Curve= 0 ,0
Exp/Cntr=0.3,0.1

Type RM Length L Ch R = 1 ,946     ,0,0,0
BEGIN DESCRIPTION:
HAW BRANCH 1.0
END DESCRIPTION:
XS GIS Cut Line= 3
       3635749.6     10503110.17      3636149.61     10503910.19
      3637149.63      10504310.2
#Sta/Elev= 30
  4092.9  340.06  4151.6  333.27  4182.4  327.83  4263.4  318.13  4308.1  312.02
  4316.5  309.19  4332.6  307.97  4347.3  306.71  4397.6  307.85  4859.6  306.92
    4990     309  4996.8  306.73  5008.9  305.55  5019.7  308.38  5026.4  308.33
  5115.6  307.79  5288.9  307.07  5311.9   305.7  5396.6  306.83  5532.3  303.79
    5535  303.29  5538.3  303.79  5540.7  304.88  5702.2  307.45  5839.5  315.09
  5978.2  327.38  6025.3  330.22  6049.6  329.28    6055   330.8  6064.4  330.53
#Mann= 7 ,-1 , 0
  4092.9     .16       0  4332.6     .12       0  4859.6     .16       0
  5115.6      .1       0  5311.9     .05       0  5532.3     .07       0
  5538.3     .05       0
Bank Sta=4990,5026.4
XS Rating Curve= 0 ,0
Exp/Cntr=0.3,0.1

Chan Stop Cuts=-1
Use User Specified Reach Order=0
Composite Channel Slope=5