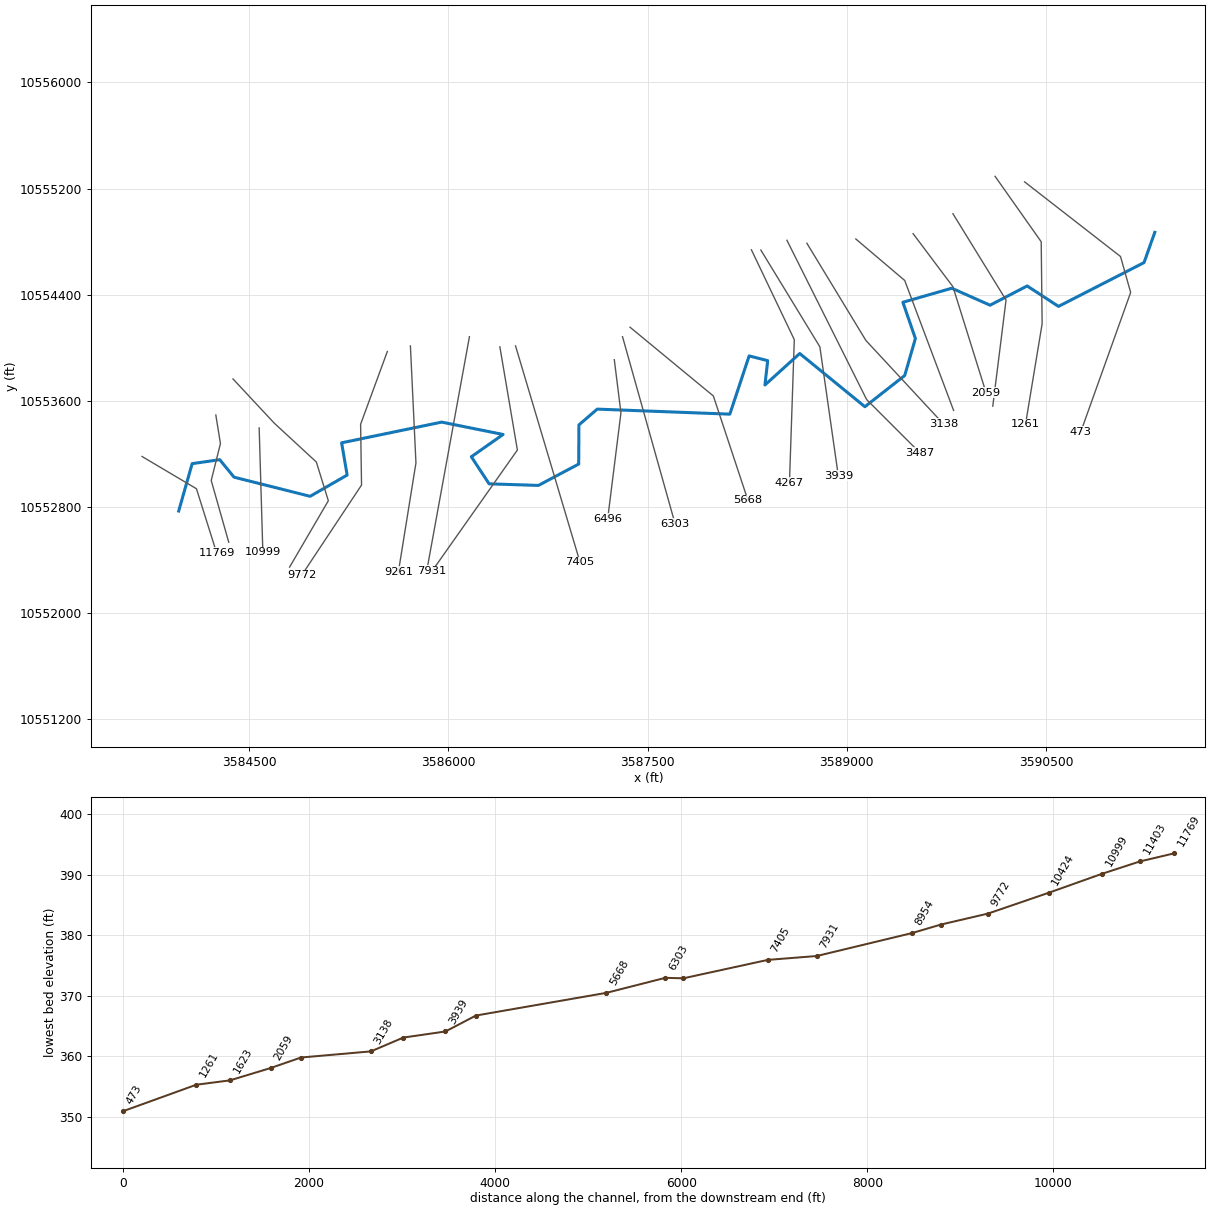
--- HAYES BRANCH.prj (project) ---

Proj Title=HAYES BRANCH Base Level Engineering
Current Plan=p01
Default Exp/Contr=0.3,0.1
English Units
Geom File=g01
Flow File=f01
Plan File=p01
Y Axis Title=Elevation
X Axis Title(PF)=Main Channel Distance
X Axis Title(XS)=Station
BEGIN DESCRIPTION:
HAYES BRANCH
END DESCRIPTION:
DSS Export Rating Curves= 0
DSS Export Rating Curve Sorted= 0
DSS Export Volume Flow Curves= 0
DXF OffsetX= 0
DXF OffsetY= 0
DXF ScaleX= 1
DXF ScaleY= 10

--- HAYES BRANCH.p01 (plan) ---

Plan Title=Multiple Run
Short Identifier=Multiple
Geom File=g01
Flow File=f01
Subcritical Flow
K Sum by GR= 0
Std Step Tol= 0.01
Critical Tol= 0.01
Num of Std Step Trials= 20
Max Error Tol= 0.3
Flow Tol Ratio= 0.001
Split Flow NTrial= 30
Split Flow Tol= 0.02
Split Flow Ratio= 0.02
Log Output Level= 0
Friction Slope Method= 1
Unsteady Friction Slope Method= 2
Unsteady Bridges Friction Slope Method= 1
Parabolic Critical Depth
Global Vel Dist=  1 , 1 , 1
Global Log Level= 0
CheckData=True
Encroach Param= -1, 0, 0, 0
BEGIN DESCRIPTION:
Multiple Run
END DESCRIPTION:

--- HAYES BRANCH.f01 (steady flow) ---

Flow Title=Multiple
Number of Profiles=7
Profile Names=10-year,25-year,50-year,1pct_min,100-year,1pct_plu,500-year
River Rch & RM= HAYES BRANCH,Reach-1,11769
    1172    1631    2015    1817    2457    3323    3643
River Rch & RM= HAYES BRANCH,Reach-1,9772
    2327    3336    4201    3851    5208    7043    7984
Boundary for River Rch & Prof#=HAYES BRANCH,Reach-1,1
Up Type=0
Dn Type=3
Dn Slope=0.005
Boundary for River Rch & Prof#=HAYES BRANCH,Reach-1,2
Up Type=0
Dn Type=3
Dn Slope=0.005
Boundary for River Rch & Prof#=HAYES BRANCH,Reach-1,3
Up Type=0
Dn Type=3
Dn Slope=0.005
Boundary for River Rch & Prof#=HAYES BRANCH,Reach-1,4
Up Type=0
Dn Type=3
Dn Slope=0.005
Boundary for River Rch & Prof#=HAYES BRANCH,Reach-1,5
Up Type=0
Dn Type=3
Dn Slope=0.005
Boundary for River Rch & Prof#=HAYES BRANCH,Reach-1,6
Up Type=0
Dn Type=3
Dn Slope=0.005
Boundary for River Rch & Prof#=HAYES BRANCH,Reach-1,7
Up Type=0
Dn Type=3
Dn Slope=0.005

--- HAYES BRANCH.g01 (geometry) ---

Geom Title=Existing Conditions
Program Version=4.10

River Reach=HAYES BRANCH    ,Reach-1
Reach XY= 30
       3583969.5       10552770.      3584070.75       10553127.
      3584278.25       10553157.      3584386.25       10553025.
      3584959.25       10552881.      3585237.75       10553041.
      3585196.25       10553284.       3585949.5       10553440.
      3586412.25       10553347.        3586173.       10553179.
      3586306.75       10552975.      3586678.25       10552963.
       3586981.5       10553124.      3586983.25       10553419.
      3587120.75       10553538.       3588119.5       10553500.
        3588265.       10553939.      3588404.75       10553903.
        3588384.       10553720.        3588646.       10553957.
       3589136.5       10553556.      3589436.25       10553791.
        3589517.       10554070.      3589422.75       10554343.
      3589790.75       10554449.        3590079.       10554321.
       3590358.5       10554466.       3590594.5       10554312.
       3591238.5       10554642.       3591319.5       10554870.

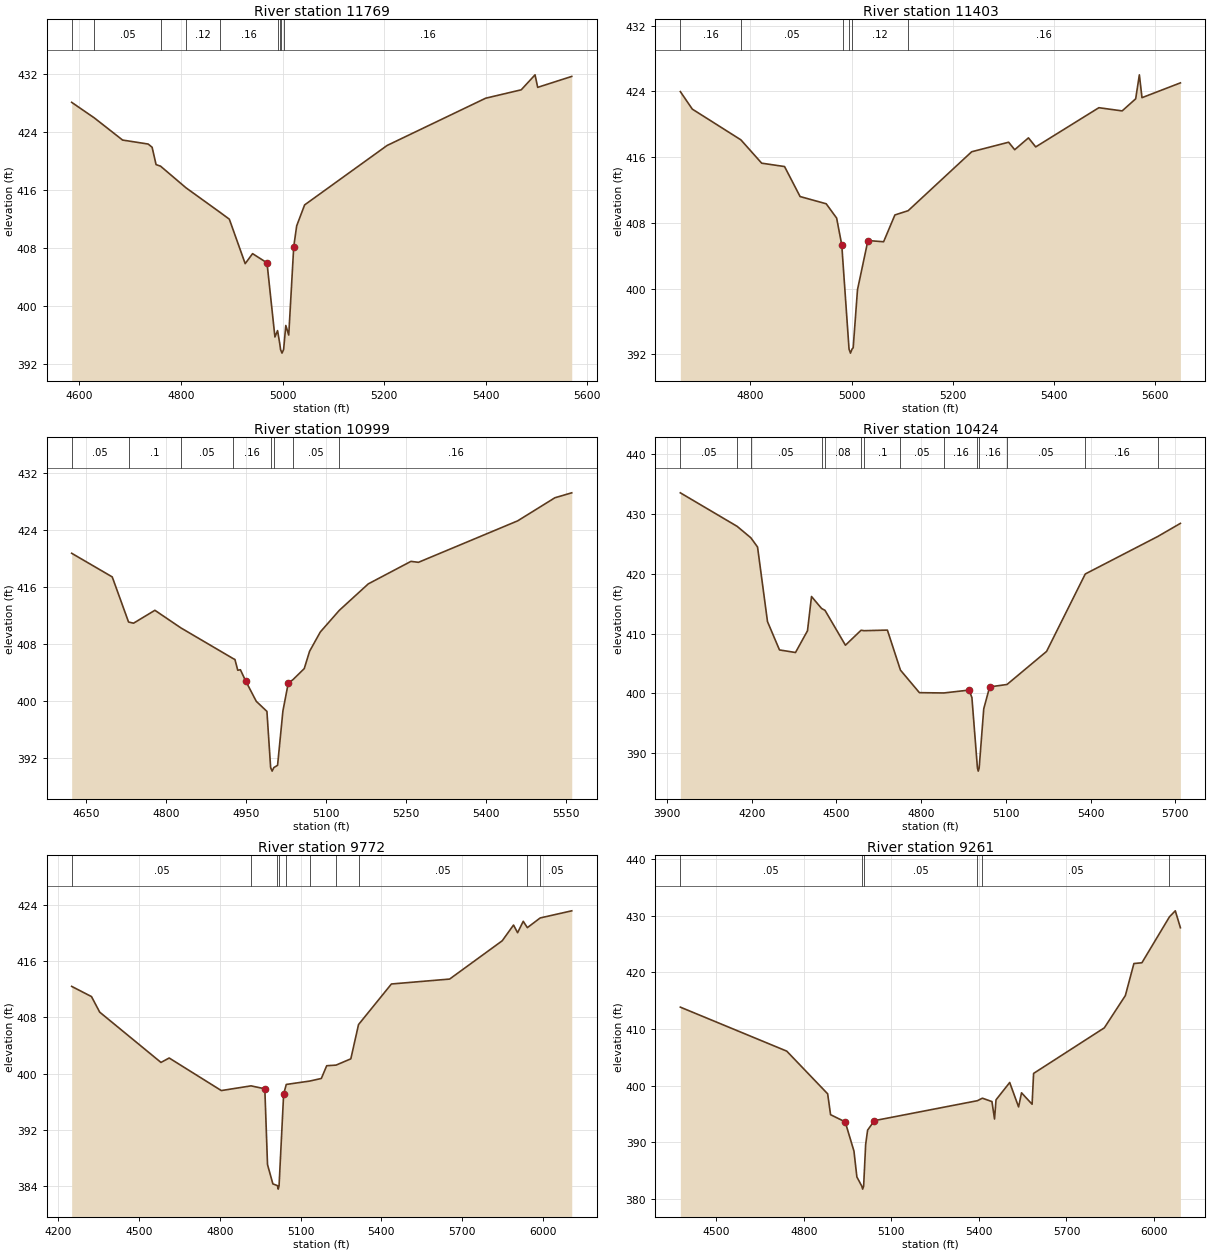
Type RM Length L Ch R = 1 ,11769   ,366,366,366
BEGIN DESCRIPTION:
HAYES BRANCH 19.0
END DESCRIPTION:
XS GIS Cut Line= 3
      3583693.45     10553180.94      3584103.15      10552937.9
      3584255.38     10552453.52
#Sta/Elev= 30
  4585.1  428.13  4629.7  425.98  4685.3  422.92  4735.6  422.37  4743.4  421.93
  4751.2  419.53  4760.1  419.31    4810  416.33  4877.8   412.9  4895.4  411.99
  4926.6  405.85  4941.1  407.23  4969.5  405.96  4985.1  395.72  4990.3   396.6
  4994.5  394.86  4996.2  393.99    4999  393.49  5002.2  393.99  5006.5  397.31
  5012.3  395.99  5022.1  408.17  5027.9  411.07  5043.5  413.96  5205.8  422.17
  5399.8   428.7  5469.8  429.86    5497  431.93  5502.2   430.2  5569.2  431.71
#Mann= 9 ,-1 , 0
  4585.1     .16       0  4629.7     .05       0  4760.1     .07       0
    4810     .12       0  4877.8     .16       0  4990.3     .12       0
  4994.5     .16       0  4996.2     .07       0  5002.2     .16       0
Bank Sta=4969.5,5022.1
XS Rating Curve= 0 ,0
Exp/Cntr=0.3,0.1

Type RM Length L Ch R = 1 ,11403   ,404,404,404
BEGIN DESCRIPTION:
Mapping XS dd41e99f
END DESCRIPTION:
XS GIS Cut Line= 4
      3584248.98      10553493.5      3584283.71     10553278.17
      3584214.26      10553000.4      3584346.19     10552535.17
#Sta/Elev= 30
  4661.5  423.98  4685.1  421.85  4781.1  418.11  4822.2  415.27  4867.4  414.86
  4898.1  411.21  4949.7  410.33  4970.3  408.59  4980.6  405.27  4981.9  404.01
  4994.8  392.66  4997.6  392.16  5000.8  392.66    5003  392.81  5011.5  399.87
  5032.1  405.86  5063.1  405.71  5085.4  408.97  5111.6  409.49  5237.1  416.66
  5310.1  417.82  5322.1  416.91  5349.3  418.35  5363.6  417.25  5488.4  422.02
  5534.4  421.63  5561.1   423.1  5568.4  426.02  5573.6  423.24  5649.5  425.04
#Mann= 6 ,-1 , 0
  4661.5     .16       0  4781.1     .05       0  4981.9     .12       0
  4994.8     .07       0  5000.8     .12       0  5111.6     .16       0
Bank Sta=4980.6,5032.1
XS Rating Curve= 0 ,0
Exp/Cntr=0.3,0.1

Type RM Length L Ch R = 1 ,10999   ,575,575,575
BEGIN DESCRIPTION:
HAYES BRANCH 18.0
END DESCRIPTION:
XS GIS Cut Line= 2
      3584575.37     10553396.24      3584603.15     10552458.75
#Sta/Elev= 30
  4623.6  420.74  4699.7  417.42  4730.3  411.08  4739.7  410.92  4779.7  412.73
  4828.4  410.26  4926.4  405.95  4929.8  405.83  4935.1  404.31  4940.1  404.38
  4949.8  402.83  4969.8  399.95  4989.8  398.53  4996.8  390.64  4999.6  390.14
  5002.8  390.64  5009.8  390.96  5019.8  398.59  5029.8  402.49  5038.8     403
  5059.8  404.54  5069.8  406.97  5089.9  409.68  5125.4  412.71  5179.9  416.44
  5259.9   419.6    5274  419.47    5460  425.29    5530  428.54  5561.5  429.23
#Mann= 8 ,-1 , 0
  4623.6     .05       0  4730.3      .1       0  4828.4     .05       0
  4926.4     .16       0  4996.8     .07       0  5002.8     .16       0
  5038.8     .05       0  5125.4     .16       0
Bank Sta=4949.8,5029.8
XS Rating Curve= 0 ,0
Exp/Cntr=0.3,0.1

Type RM Length L Ch R = 1 ,10424   ,652,652,652
BEGIN DESCRIPTION:
HAYES BRANCH 17.0
END DESCRIPTION:
XS GIS Cut Line= 5
      3584378.26     10553765.45      3584689.17     10553432.05
      3585005.93     10553139.29      3585096.21     10552847.62
      3584804.58     10552347.68
#Sta/Elev= 30
  3947.1  433.57  4148.3  427.96    4197  426.04  4220.6   424.5  4255.8  412.02
  4298.3  407.28    4355  406.85  4397.5  410.49  4411.7  416.22  4447.4  414.22
  4459.6   413.9  4531.9  408.07  4587.1  410.57  4598.2   410.5  4680.5   410.6
  4726.8   403.9  4793.9  400.13  4880.2  400.08  4969.9  400.56  4979.9   399.3
  4999.5   387.5  5002.3     387  5005.5   387.5  5021.8  397.43  5042.7  401.09
  5104.2   401.5  5244.3  407.03  5381.4  419.99    5638  426.26  5718.4  428.46
#Mann= 14 ,-1 , 0
  3947.1     .05       0  4148.3     .16       0    4197     .05       0
  4447.4     .16       0  4459.6     .08       0  4587.1     .05       0
  4598.2      .1       0  4726.8     .05       0  4880.2     .16       0
  4999.5     .07       0  5005.5     .16       0  5104.2     .05       0
  5381.4     .16       0    5638     .05       0
Bank Sta=4969.9,5042.7
XS Rating Curve= 0 ,0
Exp/Cntr=0.3,0.1

Type RM Length L Ch R = 1 ,9772    ,511,511,511
BEGIN DESCRIPTION:
HAYES BRANCH 16.0
END DESCRIPTION:
XS GIS Cut Line= 4
      3585540.65     10553972.62      3585339.26     10553424.01
      3585346.21     10552965.67      3584894.84     10552285.15
#Sta/Elev= 30
  4249.1  412.39  4322.8  410.94  4353.3  408.73  4581.2  401.58  4611.7  402.21
  4805.6  397.58  4916.1  398.25  4967.3  397.83  4977.3  387.06  4997.3  384.31
  5014.3  384.07  5017.1  383.57  5020.3  384.07  5037.3  397.09  5047.1  398.45
  5134.1  398.93  5177.4   399.3  5197.4  401.11  5232.2   401.2  5287.1  402.09
  5315.7  406.96    5438  412.73  5654.5  413.43    5850  418.87  5892.1  421.11
  5907.2  420.02  5928.2  421.64  5943.5  420.74  5991.3  422.12  6108.5  423.13
#Mann= 10 ,-1 , 0
  4249.1     .05       0  4916.1     .16       0  5014.3     .07       0
  5020.3     .16       0  5047.1     .05       0  5134.1     .08       0
  5232.2      .1       0  5315.7     .05       0  5943.5     .16       0
  5991.3     .05       0
Bank Sta=4967.3,5037.3
XS Rating Curve= 0 ,0
Exp/Cntr=0.3,0.1

Type RM Length L Ch R = 1 ,9261    ,307,307,307
BEGIN DESCRIPTION:
HAYES BRANCH 15.0
END DESCRIPTION:
XS GIS Cut Line= 3
      3585714.26     10554014.26      3585755.93     10553132.34
      3585623.99      10552312.9
#Sta/Elev= 30
  4377.4  413.84  4741.9  406.08    4882  398.55    4892  394.87  4942.1   393.6
  4972.1  388.45  4982.1  383.89  4999.2  382.24  5001.9  381.74  5005.2  382.24
  5012.2  389.62  5018.8  392.14  5042.2  393.82  5395.1  397.34    5412  397.78
  5444.8  397.18  5453.6  394.11  5458.7  397.49  5505.6  400.55    5536  396.24
  5546.1  398.73  5582.3  396.71  5587.4  402.15  5829.7  410.19  5901.7  415.88
    5931  421.53  5958.4  421.67  6052.9  429.78  6072.8  430.83  6090.3  427.85
#Mann= 6 ,-1 , 0
  4377.4     .05       0  4999.2     .03       0  5005.2     .05       0
  5395.1     .08       0    5412     .05       0  6052.9     .08       0
Bank Sta=4942.1,5042.2
XS Rating Curve= 0 ,0
Exp/Cntr=0.3,0.1

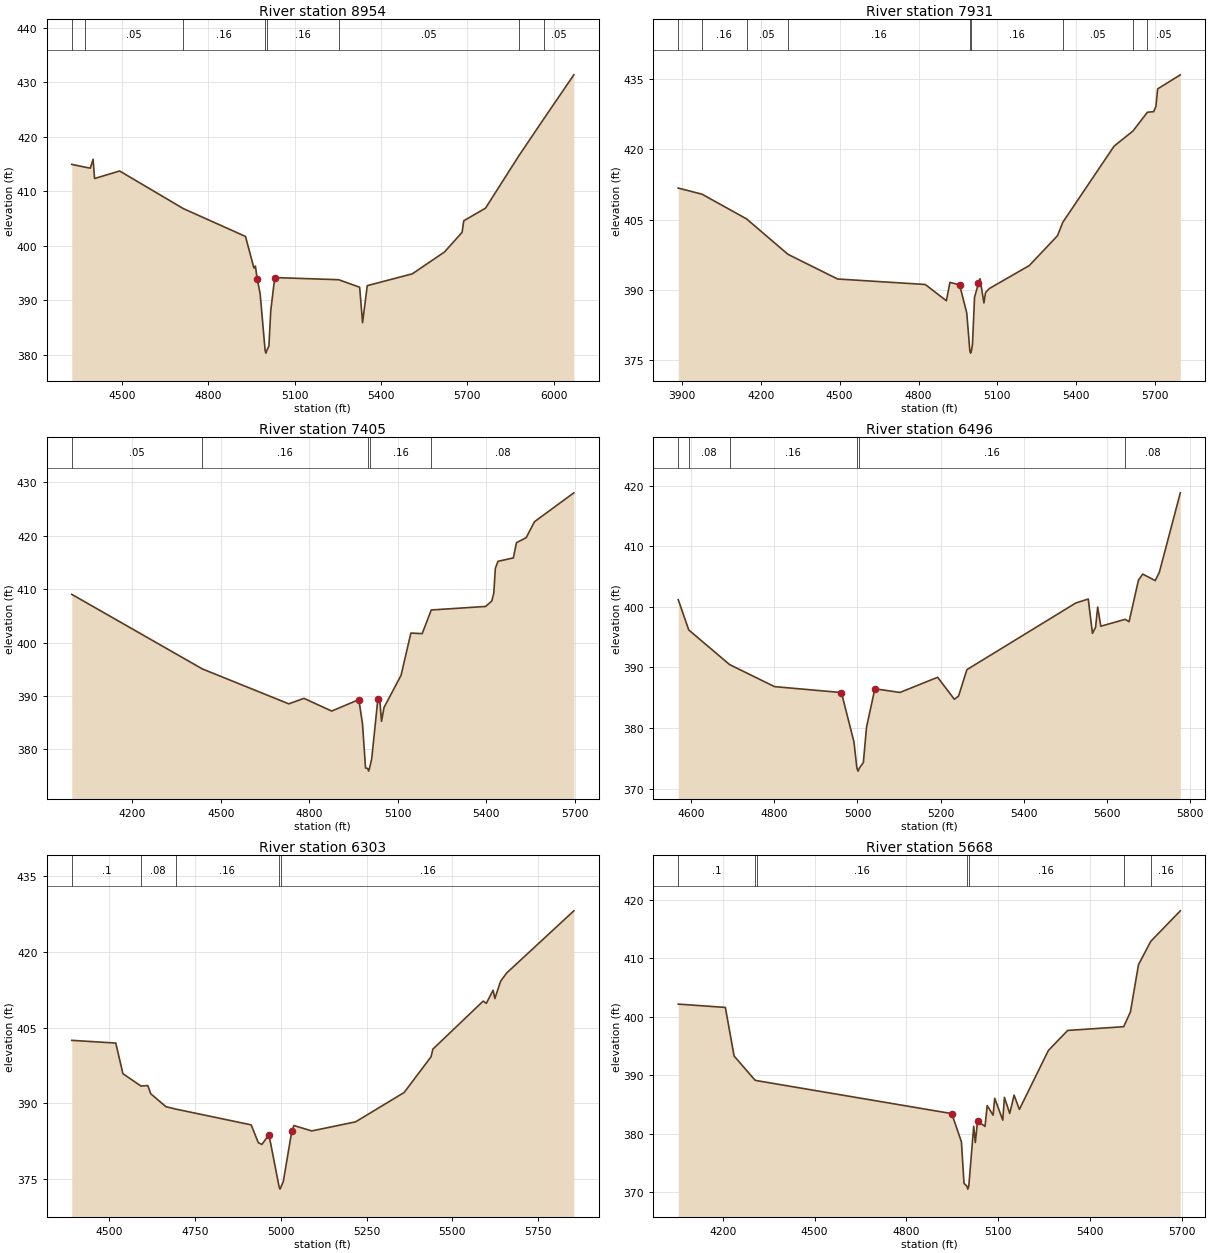
Type RM Length L Ch R = 1 ,8954    ,1023,1023,1023
BEGIN DESCRIPTION:
HAYES BRANCH 14.0
END DESCRIPTION:
XS GIS Cut Line= 2
       3586158.7     10554083.69       3585846.2     10552368.43
#Sta/Elev= 30
  4326.4  414.95  4372.9  414.44  4390.9  414.26  4400.5  415.89  4405.6  412.36
  4492.6  413.74  4714.1  406.84  4929.7  401.74    4959  395.95  4964.1  396.31
  4970.3  393.94  4980.5  391.28  4997.8  380.85  5000.6  380.35  5003.8  380.85
    5011  381.63  5017.4  388.13  5031.3   394.2  5253.3  393.81  5326.1  392.43
  5336.3  385.94  5352.5  392.72  5509.1  394.89  5620.9   398.9  5681.9   402.5
  5687.6  404.61  5763.2  406.93  5879.4  416.56    5965  423.26  6069.9  431.37
#Mann= 8 ,-1 , 0
  4326.4      .1       0  4372.9     .05       0  4714.1     .16       0
  4997.8     .07       0  5003.8     .16       0  5253.3     .05       0
  5879.4     .16       0    5965     .05       0
Bank Sta=4970.3,5031.3
XS Rating Curve= 0 ,0
Exp/Cntr=0.3,0.1

Type RM Length L Ch R = 1 ,7931    ,526,526,526
BEGIN DESCRIPTION:
HAYES BRANCH 13.0
END DESCRIPTION:
XS GIS Cut Line= 3
      3586387.87     10554007.38      3586519.82     10553229.56
      3585875.11     10552314.49
#Sta/Elev= 30
  3886.8  411.73  3977.5  410.42  4146.3  405.17    4304  397.61  4492.5  392.36
  4825.8  391.19  4905.9  387.73  4919.6  391.64  4956.3   391.1  4983.4  385.14
  4995.2  377.07    4998  376.57  5001.2  377.07  5005.2  378.45    5013  388.48
  5027.8  391.42  5033.9  392.41  5048.7  387.26  5054.8  389.47  5069.6  390.34
  5221.2  395.23  5328.3  401.58  5348.5  404.44  5543.5  420.66  5615.1  423.88
    5670  427.88  5694.1  428.01  5702.5  429.16  5708.9  432.85  5795.1  435.85
#Mann= 9 ,-1 , 0
  3886.8     .05       0  3977.5     .16       0  4146.3     .05       0
    4304     .16       0  4995.2     .07       0  5001.2     .16       0
  5348.5     .05       0  5615.1     .08       0    5670     .05       0
Bank Sta=4956.3,5027.8
XS Rating Curve= 0 ,0
Exp/Cntr=0.3,0.1

Type RM Length L Ch R = 1 ,7405    ,909,909,909
BEGIN DESCRIPTION:
HAYES BRANCH 12.0
END DESCRIPTION:
XS GIS Cut Line= 2
      3586505.93     10554014.27      3586991.62     10552383.77
#Sta/Elev= 30
  3994.9  409.04  4437.4  395.07  4730.3  388.53  4781.7  389.56  4875.6  387.18
  4967.7  389.32    4980   384.8  4990.4  376.51  4997.8  376.43  5000.6  375.93
  5003.8  376.43  5011.3  378.24  5032.1  389.44  5039.3  388.73  5044.5  385.26
    5053  387.85  5110.8  393.89    5144  401.79  5182.3  401.68  5213.1  406.11
  5397.3  406.77  5418.2   407.8  5424.9  409.25  5430.2  413.91  5439.1  415.22
  5491.3  415.86  5501.7  418.71  5534.9  419.66  5562.8  422.64  5696.2  428.05
#Mann= 5 ,-1 , 0
  3994.9     .05       0  4437.4     .16       0  4997.8     .07       0
  5003.8     .16       0  5213.1     .08       0
Bank Sta=4967.7,5032.1
XS Rating Curve= 0 ,0
Exp/Cntr=0.3,0.1

Type RM Length L Ch R = 1 ,6496    ,193,193,193
BEGIN DESCRIPTION:
HAYES BRANCH 11.0
END DESCRIPTION:
XS GIS Cut Line= 3
      3587249.61     10553910.17      3587299.61     10553510.19
      3587199.61     10552710.21
#Sta/Elev= 30
  4568.3   401.2  4593.7  396.19    4692  390.48  4800.1  386.84  4961.3  385.86
  4991.5  377.73  4998.6  373.39  5001.4  372.89  5004.6  373.39  5014.2  374.32
  5021.8  380.13  5041.9  386.48  5102.4  385.88  5193.1  388.38  5233.4  384.75
  5243.5  385.28  5263.6  389.64  5525.7  400.64  5555.9   401.3    5566  395.63
  5573.5  396.65  5578.6  399.97  5586.1  396.81  5644.8  397.95  5654.2  397.56
  5676.8  404.41  5686.9  405.42  5717.2  404.34  5727.2  405.73  5777.6  418.83
#Mann= 6 ,-1 , 0
  4568.3      .1       0  4593.7     .08       0    4692     .16       0
  4998.6     .07       0  5004.6     .16       0  5644.8     .08       0
Bank Sta=4961.3,5041.9
XS Rating Curve= 0 ,0
Exp/Cntr=0.3,0.1

Type RM Length L Ch R = 1 ,6303    ,635,635,635
BEGIN DESCRIPTION:
HAYES BRANCH 10.0
END DESCRIPTION:
XS GIS Cut Line= 2
      3587311.49      10554083.7      3587707.15      10552674.6
#Sta/Elev= 30
  4390.6  402.47  4518.9  401.93  4539.7  395.86  4592.4  393.41  4612.4   393.5
  4620.8  391.88  4665.3  389.31  4693.1  388.85  4913.6  385.71  4934.4  382.18
  4944.7  381.83  4965.5  383.74  4994.9  373.47  4997.7  372.97  5000.9  373.47
  5007.1  374.43    5032  384.45  5038.2  385.58  5090.2  384.51    5218  386.31
  5359.5  392.13    5438  399.22  5443.3  400.73  5589.9  410.25  5599.1  409.81
  5618.8  412.41    5624  410.76  5640.7  414.19    5658   415.8  5854.2  428.15
#Mann= 5 ,-1 , 0
  4390.6      .1       0  4592.4     .08       0  4693.1     .16       0
  4994.9     .07       0  5000.9     .16       0
Bank Sta=4965.5,5032
XS Rating Curve= 0 ,0
Exp/Cntr=0.3,0.1

Type RM Length L Ch R = 1 ,5668    ,1401,1401,1401
BEGIN DESCRIPTION:
HAYES BRANCH 9.0
END DESCRIPTION:
XS GIS Cut Line= 3
      3587368.01     10554155.13       3587995.6     10553636.92
        3588256.     10552850.49
#Sta/Elev= 30
  4053.8  402.17  4207.9   401.6  4236.6  393.28  4304.9  389.15  4311.2  389.06
  4948.5  383.42  4980.1  378.59  4988.6  371.48  4998.2  370.99  5000.9  370.49
  5004.2  370.99  5020.3  381.25  5025.6  378.46  5032.8  382.13  5057.3  381.23
  5064.4  384.79  5083.7  383.15    5089  386.05  5115.4   382.3  5120.7   386.2
  5138.1  383.45  5152.4  386.58  5169.7  384.14  5264.5  394.23  5327.7  397.66
  5510.8   398.3  5532.9  400.82  5559.3  408.92  5599.5  412.92  5696.1  418.14
#Mann= 7 ,-1 , 0
  4053.8      .1       0  4304.9     .08       0  4311.2     .16       0
  4998.2     .07       0  5004.2     .16       0  5510.8      .1       0
  5599.5     .16       0
Bank Sta=4948.5,5032.8
XS Rating Curve= 0 ,0
Exp/Cntr=0.3,0.1

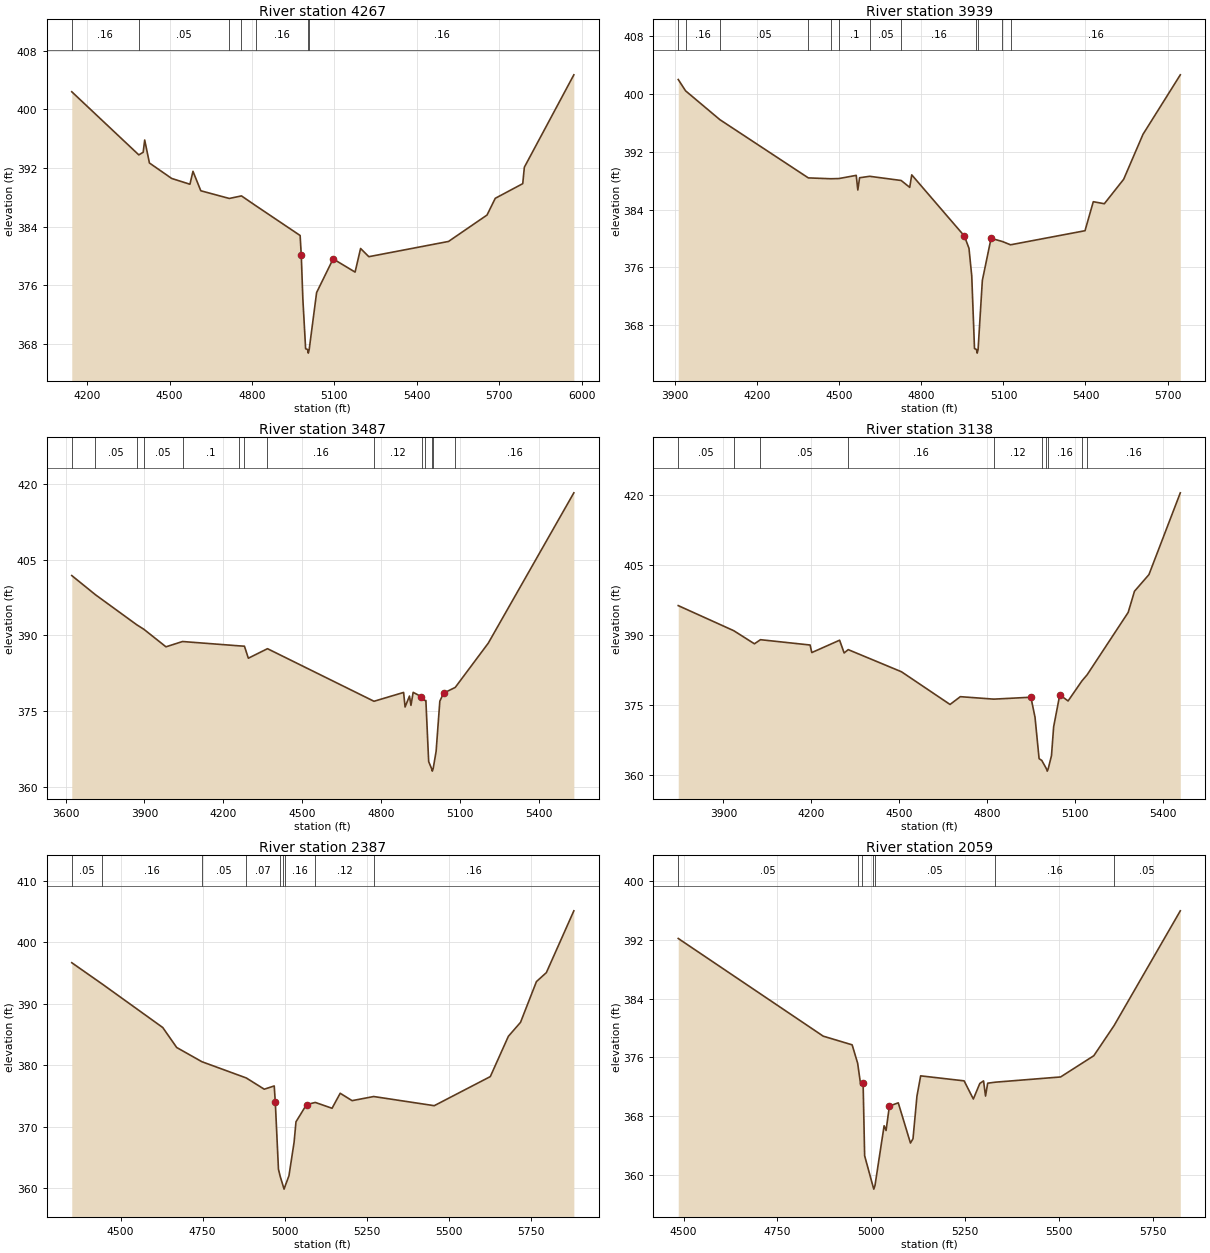
Type RM Length L Ch R = 1 ,4267    ,328,328,328
BEGIN DESCRIPTION:
HAYES BRANCH 8.0
END DESCRIPTION:
XS GIS Cut Line= 3
      3588282.06     10554738.48      3588604.97      10554061.4
      3588568.55     10552984.25
#Sta/Elev= 30
    4144  402.39  4388.2  393.78    4404  394.14  4409.5  395.81  4426.7  392.68
  4507.7  390.57  4574.2  389.78  4585.3  391.54  4613.8  388.89  4717.6  387.84
  4761.8  388.19  4814.9  386.83  4975.4  382.79 4979.55  380.09  4985.4  374.09
  4995.4  367.35  5002.4  367.25  5005.2  366.75  5008.4  367.25  5035.4  375.01
  5095.5   379.6  5175.5   377.8  5195.5  381.02  5225.5   379.9  5515.7  381.98
  5655.8  385.58  5685.8  387.86  5785.9  389.86  5791.7   392.1  5971.9   404.7
#Mann= 7 ,-1 , 0
    4144     .16       0  4388.2     .05       0  4717.6     .16       0
  4761.8     .05       0  4814.9     .16       0  5002.4     .07       0
  5008.4     .16       0
Bank Sta=4979.55,5095.5
XS Rating Curve= 0 ,0
Exp/Cntr=0.3,0.1

Type RM Length L Ch R = 1 ,3939    ,452,452,452
BEGIN DESCRIPTION:
HAYES BRANCH 7.0
END DESCRIPTION:
XS GIS Cut Line= 3
      3588353.16      10554736.5       3588797.6     10554007.34
      3588936.48     10553035.15
#Sta/Elev= 30
  3910.8  402.03  3937.7  400.46    4063  396.47  4386.5   388.4  4469.2  388.28
  4498.7  388.31  4561.7  388.75  4567.5  386.72    4574  388.42  4610.9  388.62
    4726  388.04  4757.3  387.09  4764.7  388.82  4957.3  380.34    4974  378.64
  4984.1  374.84  4994.2  364.76  5001.3  364.62    5004  364.12  5007.3  364.62
  5022.9   374.2  5054.8  380.03  5096.5  379.58    5126  379.13  5398.3  381.08
  5428.6   385.1    5469  384.82  5539.7  388.21  5610.4  394.44  5746.8  402.68
#Mann= 12 ,-1 , 0
  3910.8     .05       0  3937.7     .16       0    4063     .05       0
  4386.5      .1       0  4469.2     .15       0  4498.7      .1       0
  4610.9     .05       0    4726     .16       0  5001.3     .07       0
  5007.3     .16       0  5096.5     .12       0    5126     .16       0
Bank Sta=4957.3,5054.8
XS Rating Curve= 0 ,0
Exp/Cntr=0.3,0.1

Type RM Length L Ch R = 1 ,3487    ,349,349,349
BEGIN DESCRIPTION:
HAYES BRANCH 6.0
END DESCRIPTION:
XS GIS Cut Line= 3
      3588549.62     10554810.18      3589149.61     10553610.19
       3589549.6      10553210.2
#Sta/Elev= 30
  3623.8  401.87  3713.5  398.08  3871.4  392.09  3897.6  391.23  3981.6  387.75
  4044.6   388.8  4259.8  387.94  4279.8  387.87  4294.6  385.49  4367.3  387.38
  4771.9  376.96  4884.4  378.71    4890  375.83  4906.7  377.99  4912.3  376.15
  4920.7  378.73  4951.5  377.88    4955   377.8  4964.6  377.12    4969  377.12
  4979.6  365.01  4990.7  363.62  4993.5  363.12  4996.7  363.62  5007.9  367.04
    5022  376.97  5036.1  378.56  5080.6  379.71  5205.8  388.46  5531.1  418.26
#Mann= 14 ,-1 , 0
  3623.8     .08       0  3713.5     .05       0  3871.4     .16       0
  3897.6     .05       0  4044.6      .1       0  4259.8     .15       0
  4279.8      .1       0  4367.3     .16       0  4771.9     .12       0
    4955     .16       0  4964.6     .12       0  4990.7     .07       0
  4996.7     .12       0  5080.6     .16       0
Bank Sta=4951.5,5036.1
XS Rating Curve= 0 ,0
Exp/Cntr=0.3,0.1

Type RM Length L Ch R = 1 ,3138    ,751,751,751
BEGIN DESCRIPTION:
Mapping XS 301d93c3
END DESCRIPTION:
XS GIS Cut Line= 3
      3588699.74     10554787.86      3589144.18     10554055.23
      3589727.54     10553426.73
#Sta/Elev= 30
  3745.7  396.34  3935.3  390.96  4005.9  388.15  4026.4  389.03  4195.9  387.89
  4201.8  386.27  4296.7  388.92  4312.2  386.18  4326.1   386.9    4508  382.15
  4673.8  375.14    4709  376.81  4823.1  376.28  4949.9  376.69    4964  372.39
  4977.9  363.52  4987.2  363.12    5003  361.34  5005.8  360.84    5009  361.34
  5020.2  364.16  5027.6  370.35  5048.5   377.2  5076.9  375.89  5123.9  380.17
    5142  381.51  5282.1  394.88  5303.6  399.42    5353  402.99  5460.1  420.53
#Mann= 10 ,-1 , 0
  3745.7     .05       0  3935.3     .16       0  4026.4     .05       0
  4326.1     .16       0  4823.1     .12       0  4987.2     .16       0
    5003     .07       0    5009     .16       0  5123.9     .12       0
    5142     .16       0
Bank Sta=4949.9,5048.5
XS Rating Curve= 0 ,0
Exp/Cntr=0.3,0.1

Type RM Length L Ch R = 1 ,2387    ,328,328,328
BEGIN DESCRIPTION:
HAYES BRANCH 4.0
END DESCRIPTION:
XS GIS Cut Line= 3
      3589068.41     10554819.86      3589436.49     10554507.34
      3589804.54     10553528.18
#Sta/Elev= 30
  4351.4  396.65  4444.8  393.16  4628.5  386.11    4671  382.86  4747.7  380.55
  4882.8  377.91  4937.6  376.08  4967.9  376.61 4971.14  374.03  4980.8  363.06
  4986.1  361.91  4995.1  360.33  4997.9  359.83  5001.1  360.33  5012.8  362.01
  5028.4  367.45  5034.2  370.78  5066.2  373.57    5093  373.93    5144  372.98
  5168.8  375.42  5205.1  374.22  5270.8  374.89  5455.2   373.4  5625.9  378.13
    5681  384.69  5717.9  386.95  5766.4  393.58  5796.6  395.04  5880.3  405.09
#Mann= 9 ,-1 , 0
  4351.4     .05       0  4444.8     .16       0  4747.7     .05       0
  4882.8     .07       0  4986.1     .16       0  4995.1     .07       0
  5001.1     .16       0    5093     .12       0  5270.8     .16       0
Bank Sta=4971.14,5066.2
XS Rating Curve= 0 ,0
Exp/Cntr=0.3,0.1

Type RM Length L Ch R = 1 ,2059    ,436,436,436
BEGIN DESCRIPTION:
HAYES BRANCH 3.0
END DESCRIPTION:
XS GIS Cut Line= 3
      3589499.63     10554860.16      3589799.61     10554460.19
       3590049.6      10553660.2
#Sta/Elev= 30
  4485.8  392.19  4872.2   378.9  4949.3  377.72    4964  375.21  4972.2  372.22
  4976.7  372.46  4978.5  372.56  4982.6  362.63  5004.2  358.59    5007  358.09
  5010.2  358.59  5034.5  366.71  5039.7  366.07  5048.6  369.39  5072.2  369.83
  5104.7  364.36  5111.5  364.95    5122  370.73  5131.9   373.5  5247.7  372.82
  5272.3  370.35  5289.6  372.47  5299.5  372.81  5304.8  370.75  5310.5   372.5
    5331  372.64  5504.9  373.35  5593.4  376.24  5647.4  380.34  5823.9  395.95
#Mann= 7 ,-1 , 0
  4485.8     .05       0    4964      .1       0  4976.7     .05       0
  5004.2     .03       0  5010.2     .05       0    5331     .16       0
  5647.4     .05       0
Bank Sta=4978.5,5048.6
XS Rating Curve= 0 ,0
Exp/Cntr=0.3,0.1

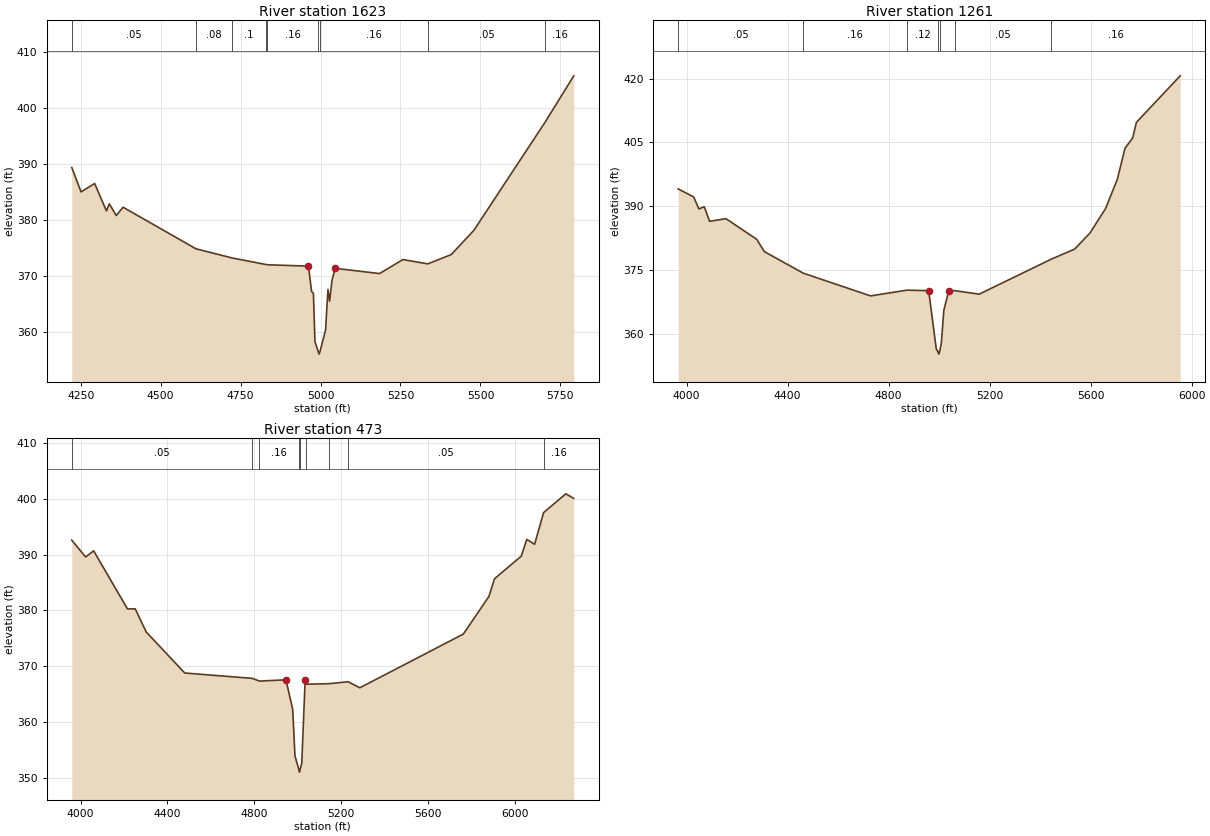
Type RM Length L Ch R = 1 ,1623    ,362,362,362
BEGIN DESCRIPTION:
HAYES BRANCH 2.0
END DESCRIPTION:
XS GIS Cut Line= 3
       3589799.6     10555010.21      3590199.61     10554360.19
      3590099.61     10553560.16
#Sta/Elev= 30
  4222.3  389.37  4251.3  385.02  4293.9  386.51  4330.6  381.62  4339.7  382.88
  4361.4   380.8  4382.7  382.28  4610.5  374.86    4723  373.23  4829.9  372.05
  4833.8  372.01  4962.4  371.76    4972  367.25  4977.8  366.89  4982.6  358.29
  4992.6  356.56  4995.4  356.06  4998.6  356.56  5015.8  360.38  5023.3  367.62
  5028.4  365.52  5035.9  369.25    5046  371.37  5184.6  370.44  5257.6  372.94
  5335.2  372.17  5408.8  373.83  5479.4  378.15  5702.3  397.47  5791.8  405.73
#Mann= 9 ,-1 , 0
  4222.3     .05       0  4610.5     .08       0    4723      .1       0
  4829.9     .05       0  4833.8     .16       0  4992.6     .07       0
  4998.6     .16       0  5335.2     .05       0  5702.3     .16       0
Bank Sta=4962.4,5046
XS Rating Curve= 0 ,0
Exp/Cntr=0.3,0.1

Type RM Length L Ch R = 1 ,1261    ,788,788,788
BEGIN DESCRIPTION:
Mapping XS 8117bbc3
END DESCRIPTION:
XS GIS Cut Line= 4
      3590117.02     10555292.09      3590464.26     10554799.01
      3590471.21     10554180.95       3590346.3     10553424.57
#Sta/Elev= 30
  3966.9  394.11  4028.2  392.23  4049.1   389.4  4070.1  389.93  4091.5  386.51
  4156.3  387.12  4278.2  382.27  4307.8  379.41  4461.6  374.35  4728.8     369
  4872.4  370.35  4958.8  370.23  4988.8   356.6  4995.8  355.84  4998.6  355.34
  5001.8  355.84  5008.8  357.83  5018.8  365.64  5038.8  370.26  5063.5  370.22
  5158.8  369.41  5444.3  377.62    5537  379.99  5598.1   383.8  5659.2   389.5
  5705.8  396.36  5736.2  403.64  5766.6  406.07  5781.4  409.73  5954.7  420.64
#Mann= 7 ,-1 , 0
  3966.9     .05       0  4461.6     .16       0  4872.4     .12       0
  4995.8     .07       0  5001.8     .12       0  5063.5     .05       0
  5444.3     .16       0
Bank Sta=4958.8,5038.8
XS Rating Curve= 0 ,0
Exp/Cntr=0.3,0.1

Type RM Length L Ch R = 1 ,473     ,0,0,0
BEGIN DESCRIPTION:
HAYES BRANCH 1.0
END DESCRIPTION:
XS GIS Cut Line= 4
      3590339.27     10555250.39      3591061.49      10554687.9
      3591137.87     10554417.06      3590762.87     10553368.43
#Sta/Elev= 30
  3959.5   392.6  4023.3  389.59  4060.3  390.69  4215.9  380.26  4251.5  380.28
  4302.2  376.12  4479.6  368.76  4790.3   367.8  4823.4  367.31  4945.3  367.54
  4976.4  362.21  4986.8  353.86  5004.6  351.47  5007.4  350.97  5010.6  351.47
    5018  352.54  5033.7  367.58  5036.7  366.75  5143.2  366.84  5231.1  367.19
  5285.3  366.11  5761.8  375.75  5879.6  382.52  5905.1  385.68  6028.2  389.73
  6053.7  392.74  6089.8  391.87  6130.8  397.53    6233  400.92    6270  400.11
#Mann= 9 ,-1 , 0
  3959.5     .05       0  4790.3     .12       0  4823.4     .16       0
  5004.6     .07       0  5010.6     .16       0  5036.7     .05       0
  5143.2      .1       0  5231.1     .05       0  6130.8     .16       0
Bank Sta=4945.3,5033.7
XS Rating Curve= 0 ,0
Exp/Cntr=0.3,0.1

Chan Stop Cuts=-1
Use User Specified Reach Order=0
Composite Channel Slope=5