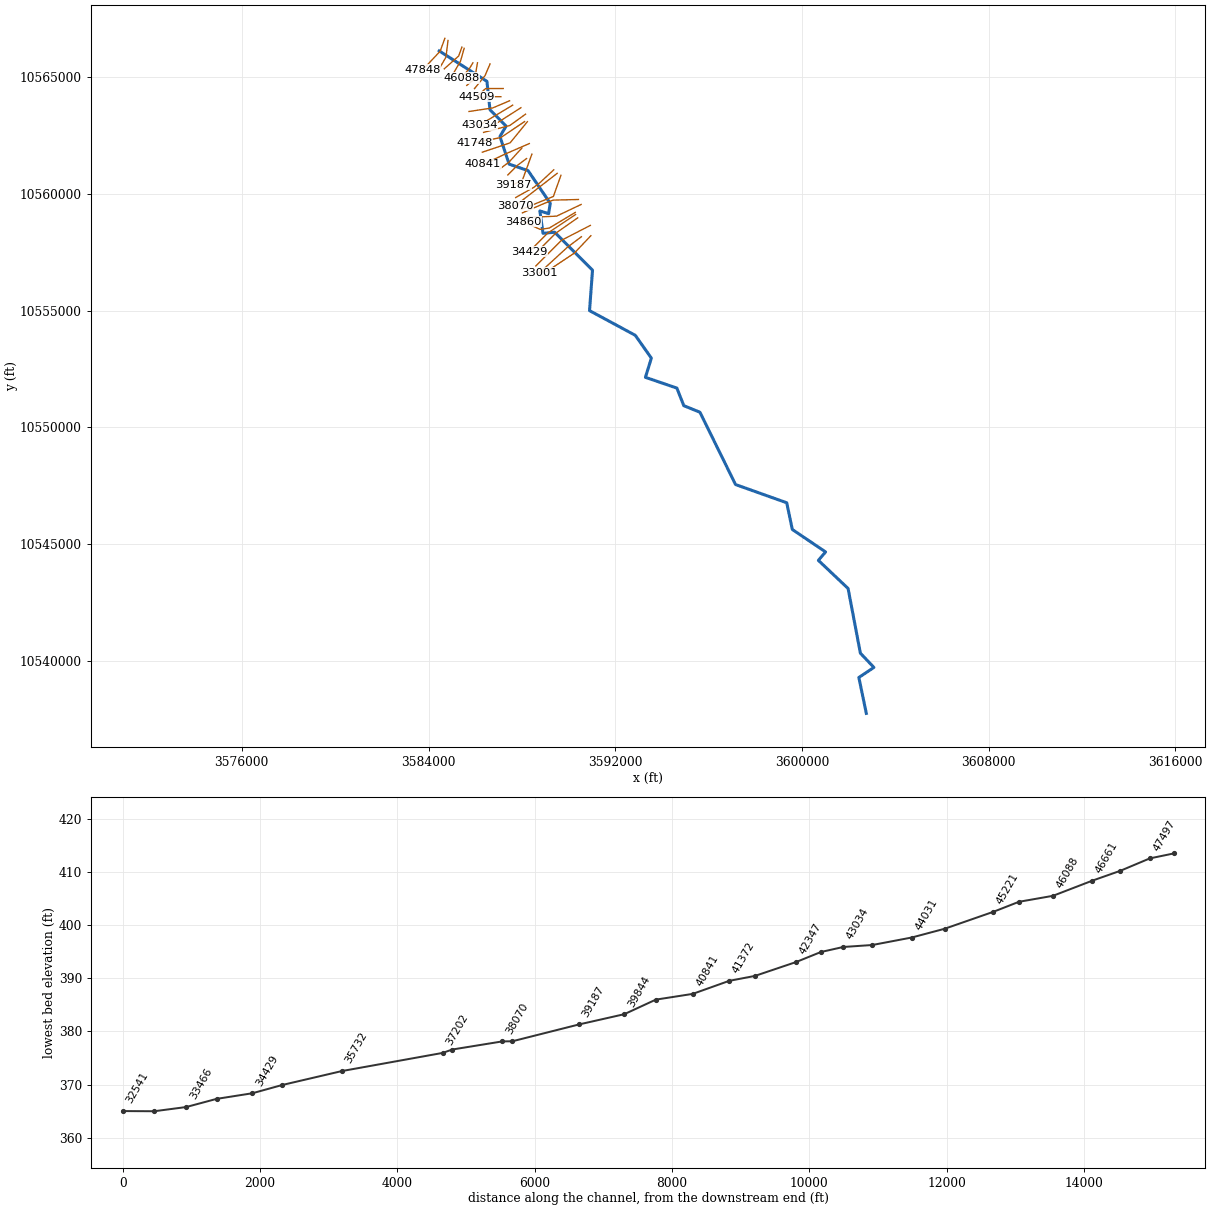
--- LINN CREEK.prj (project) ---

Proj Title=LINN CREEK Base Level Engineering
Current Plan=p01
Default Exp/Contr=0.3,0.1
English Units
Geom File=g01
Flow File=f01
Plan File=p01
Y Axis Title=Elevation
X Axis Title(PF)=Main Channel Distance
X Axis Title(XS)=Station
BEGIN DESCRIPTION:
LINN CREEK
END DESCRIPTION:
DSS Export Rating Curves= 0
DSS Export Rating Curve Sorted= 0
DSS Export Volume Flow Curves= 0
DXF OffsetX= 0
DXF OffsetY= 0
DXF ScaleX= 1
DXF ScaleY= 10

--- LINN CREEK.p01 (plan) ---

Plan Title=Multiple Run
Short Identifier=Multiple
Geom File=g01
Flow File=f01
Subcritical Flow
K Sum by GR= 0
Std Step Tol= 0.01
Critical Tol= 0.01
Num of Std Step Trials= 20
Max Error Tol= 0.3
Flow Tol Ratio= 0.001
Split Flow NTrial= 30
Split Flow Tol= 0.02
Split Flow Ratio= 0.02
Log Output Level= 0
Friction Slope Method= 1
Unsteady Friction Slope Method= 2
Unsteady Bridges Friction Slope Method= 1
Parabolic Critical Depth
Global Vel Dist=  1 , 1 , 1
Global Log Level= 0
CheckData=True
Encroach Param= -1, 0, 0, 0
BEGIN DESCRIPTION:
Multiple Run
END DESCRIPTION:

--- LINN CREEK.f01 (steady flow) ---

Flow Title=Multiple
Program Version=4.10
Number of Profiles= 7
Profile Names=10-year,25-year,50-year,1pct_min,100-year,1pct_plu,500-year
River Rch & RM=LINN CREEK,Reach-1         ,47848
    1258    1743    2147    1928    2607    3526    3835
River Rch & RM=LINN CREEK,Reach-1         ,47497
    2012    2858    3578    3261    4411    5965    6687
River Rch & RM=LINN CREEK,Reach-1         ,42347
    2436    3477    4368    3991    5397    7299    8221
River Rch & RM=LINN CREEK,Reach-1         ,34429
    3016    4338    5477    5025    6796    9190   10440
River Rch & RM=LINN CREEK,Reach-1         ,33466
    3016    4338    5477    5025    6796    9190   10440
River Rch & RM=LINN CREEK,Reach-1         ,28082
    4480    6551    8362    7748   10478   14171   16420
River Rch & RM=LINN CREEK,Reach-1         ,23112
    4498    6561    8360    7731   10455   14139   16318
River Rch & RM=LINN CREEK,Reach-1         ,18116
    5126    7495    9564    8853   11973   16192   18725
River Rch & RM=LINN CREEK,Reach-1         ,17290
    5126    7495    9564    8853   11973   16192   18725
River Rch & RM=LINN CREEK,Reach-1         ,14267
    6173    9072   11618   10789   14591   19732   22959
River Rch & RM=LINN CREEK,Reach-1         ,12126
    7713   11388   14631   13622   18423   24915   29135
River Rch & RM=LINN CREEK,Reach-1         ,6658
    7713   11388   14631   13622   18423   24915   29135
Boundary for River Rch & Prof#=LINN CREEK,Reach-1         , 1
Up Type= 0
Dn Type= 3
Dn Slope=0.003
Boundary for River Rch & Prof#=LINN CREEK,Reach-1         , 2
Up Type= 0
Dn Type= 3
Dn Slope=0.003
Boundary for River Rch & Prof#=LINN CREEK,Reach-1         , 3
Up Type= 0
Dn Type= 3
Dn Slope=0.003
Boundary for River Rch & Prof#=LINN CREEK,Reach-1         , 4
Up Type= 0
Dn Type= 3
Dn Slope=0.003
Boundary for River Rch & Prof#=LINN CREEK,Reach-1         , 5
Up Type= 0
Dn Type= 3
Dn Slope=0.003
Boundary for River Rch & Prof#=LINN CREEK,Reach-1         , 6
Up Type= 0
Dn Type= 3
Dn Slope=0.003
Boundary for River Rch & Prof#=LINN CREEK,Reach-1         , 7
Up Type= 0
Dn Type= 3
Dn Slope=0.003
DSS Import GetInterval= 0
DSS Import GetPeak= 0
DSS Import FillOption= 0

--- LINN CREEK.g01 (geometry) ---

Geom Title=Existing Conditions
Program Version=4.10

River Reach=LINN CREEK      ,Reach-1
Reach XY= 30
       3584459.5       10566120.      3586501.75       10564818.
      3586632.75       10563602.      3587324.25       10562900.
       3587059.5       10562455.      3587452.75       10561271.
        3588266.       10560992.      3589216.25       10559588.
      3589144.75       10559150.      3588771.75       10559265.
      3588904.75       10558307.       3589405.5       10558353.
      3591025.75       10556728.        3590898.       10554995.
        3592858.       10553937.       3593547.5       10552959.
      3593292.25       10552137.        3594640.       10551676.
        3594936.       10550923.       3595628.5       10550641.
        3597153.       10547544.        3599346.       10546763.
      3599585.75       10545619.       3601010.5       10544656.
      3600702.25       10544296.       3601975.5       10543090.
      3602501.75       10540320.      3603081.25       10539708.
       3602436.5       10539278.       3602756.5       10537740.

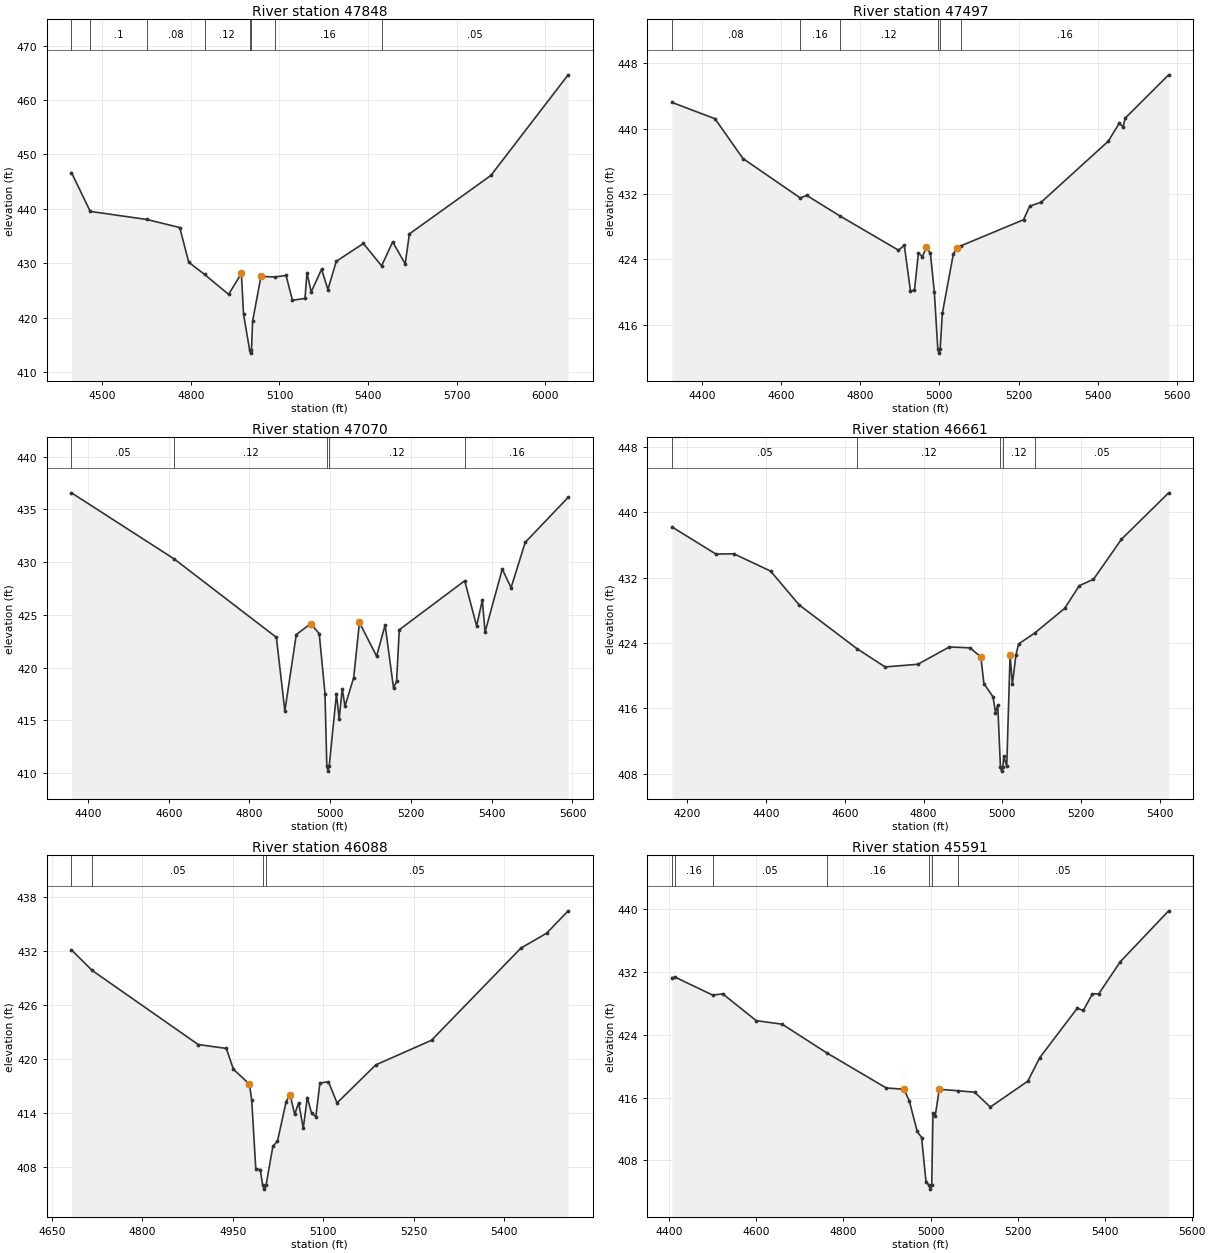
Type RM Length L Ch R = 1 ,47848   ,351,351,351
BEGIN DESCRIPTION:
LINN CREEK 86.0
END DESCRIPTION:
XS GIS Cut Line= 3
      3584699.62     10566660.22      3584499.61     10566110.19
      3583749.58     10565310.16
#Sta/Elev= 30
  4395.7  446.67  4459.1  439.53    4651  438.04  4762.2  436.56  4792.8  430.17
  4846.4  427.93  4927.8  424.27    4971  428.12  4978.3  420.63  4999.2  413.96
    5002  413.46  5005.2  413.96  5009.1  419.38  5037.4  427.57  5084.4  427.47
  5122.4  427.74  5143.9  423.18  5186.4  423.52  5193.2  428.25  5207.4  424.71
  5242.6  428.89    5264  425.16  5292.4  430.35  5384.2  433.63  5445.9  429.51
  5483.3  433.92  5525.8  429.89    5540  435.39    5816  446.14  6077.6  464.65
#Mann= 8 ,-1 , 0
  4395.7     .08       0  4459.1      .1       0    4651     .08       0
  4846.4     .12       0  4999.2     .07       0  5005.2     .12       0
  5084.4     .16       0  5445.9     .05       0
Bank Sta=4971,5037.4
XS Rating Curve= 0 ,0
Exp/Cntr=0.3,0.1

Type RM Length L Ch R = 1 ,47497   ,427,427,427
BEGIN DESCRIPTION:
LINN CREEK 85.0
END DESCRIPTION:
XS GIS Cut Line= 3
      3584834.05     10566568.06      3584749.61     10565860.19
      3584479.87     10565390.99
#Sta/Elev= 30
  4324.7  443.23  4433.3  441.23  4503.8  436.36  4648.6  431.53    4665  431.84
  4747.8  429.35  4896.6  425.13  4911.3  425.72  4926.8  420.16  4936.9  420.21
    4947   424.8    4957  424.33  4967.1  425.51  4977.2  424.73  4987.2  419.98
  4995.9  413.02  4998.6  412.52  5001.9  413.02  5007.4   417.4  5035.1  424.67
  5045.5  425.43    5055  425.68  5212.3  428.86  5228.1  430.53  5256.8     431
  5426.4  438.48  5453.8  440.66  5463.8  440.27  5469.6  441.33  5578.8  446.61
#Mann= 6 ,-1 , 0
  4324.7     .08       0  4648.6     .16       0  4747.8     .12       0
  4995.9     .07       0  5001.9     .12       0    5055     .16       0
Bank Sta=4967.1,5045.5
XS Rating Curve= 0 ,0
Exp/Cntr=0.3,0.1

Type RM Length L Ch R = 1 ,47070   ,409,409,409
BEGIN DESCRIPTION:
LINN CREEK 84.0
END DESCRIPTION:
XS GIS Cut Line= 3
      3585429.71     10566283.54      3585290.81     10565901.57
       3584674.8     10565354.96
#Sta/Elev= 30
  4359.3  436.56  4613.5   430.3  4866.7  422.87  4887.7  415.89    4916  423.14
    4952  424.17  4972.9  423.21  4987.1  417.54  4991.6   410.7  4994.4   410.2
  4997.6   410.7  5015.5  417.52  5022.2  415.13  5029.8  418.01  5036.5  416.34
  5058.2  419.06  5072.4  424.28  5114.9  421.09    5136  424.04  5156.9  418.06
  5164.4  418.72  5171.1  423.59  5333.1  428.23  5362.6  423.95  5376.8   426.4
  5383.5  423.37  5426.2  429.34  5447.9  427.57    5483  431.87  5589.3  436.13
#Mann= 5 ,-1 , 0
  4359.3     .05       0  4613.5     .12       0  4991.6     .07       0
  4997.6     .12       0  5333.1     .16       0
Bank Sta=4952,5072.4
XS Rating Curve= 0 ,0
Exp/Cntr=0.3,0.1

Type RM Length L Ch R = 1 ,46661   ,573,573,573
BEGIN DESCRIPTION:
LINN CREEK 83.0
END DESCRIPTION:
XS GIS Cut Line= 3
      3585525.19     10566231.46      3585368.93     10565675.87
       3585021.7     10565085.57
#Sta/Elev= 30
  4160.8  438.19  4272.5  434.87  4317.9  434.91  4411.4  432.79  4484.2  428.65
  4630.8  423.31  4702.3  421.08  4785.5   421.4  4865.6  423.52  4918.4  423.41
  4945.6  422.29  4953.4  419.04  4976.6  417.42  4982.8   415.5  4988.6  416.41
  4995.4  408.84  4998.2  408.34  5001.4  408.84  5004.2  410.13  5011.4  408.94
  5019.9  422.57  5025.7  418.93  5034.6  422.49  5041.4  423.88    5082   425.2
  5158.5  428.23  5195.7  431.01  5231.8  431.79    5303  436.69  5422.8  442.36
#Mann= 5 ,-1 , 0
  4160.8     .05       0  4630.8     .12       0  4995.4     .07       0
  5001.4     .12       0    5082     .05       0
Bank Sta=4945.6,5019.9
XS Rating Curve= 0 ,0
Exp/Cntr=0.3,0.1

Type RM Length L Ch R = 1 ,46088   ,497,497,497
BEGIN DESCRIPTION:
LINN CREEK 82.0
END DESCRIPTION:
XS GIS Cut Line= 3
      3585899.63     10565610.23      3585749.61     10565360.19
      3585399.61     10564960.19
#Sta/Elev= 30
  4682.5  432.13  4716.8  429.84  4892.5  421.59  4939.1  421.16  4950.8  418.84
  4977.4  417.18  4981.2   415.4  4987.9  407.76  4995.4  407.66  4999.1  405.99
  5001.8  405.49  5005.1  405.99  5016.3  410.27  5023.9  410.83  5038.2  415.23
  5044.8     416  5052.4  413.81    5059  415.11  5066.6  412.26  5073.3  415.69
  5080.4  413.93  5087.5  413.57  5094.2  417.31  5108.4  417.44  5122.6  415.09
  5186.7  419.32  5279.2  422.07  5427.3  432.33    5470  433.99  5505.6  436.48
#Mann= 4 ,-1 , 0
  4682.5     .16       0  4716.8     .05       0  4999.1     .03       0
  5005.1     .05       0
Bank Sta=4977.4,5044.8
XS Rating Curve= 0 ,0
Exp/Cntr=0.3,0.1

Type RM Length L Ch R = 1 ,45591   ,370,370,370
BEGIN DESCRIPTION:
LINN CREEK 81.0
END DESCRIPTION:
XS GIS Cut Line= 3
       3586098.1     10565615.11      3585976.57     10564920.66
      3585639.43     10564644.04
#Sta/Elev= 30
    4406  431.25  4413.8  431.29  4499.4  429.03  4522.7  429.18  4599.5  425.78
    4659  425.33  4761.3  421.69  4898.3  417.22  4938.9  417.06  4951.2  415.58
  4969.4  411.69  4979.5  410.92  4989.7  405.24  4996.8  404.86  4999.6  404.36
  5002.8  404.86  5005.6  414.02  5010.7  413.64  5020.1  417.05  5062.9  416.87
  5101.3  416.68  5137.4   414.8  5223.5  418.08  5250.8  421.06  5336.9  427.34
  5351.2  427.09  5372.1  429.19  5386.4  429.18  5435.9  433.26  5547.1  439.74
#Mann= 7 ,-1 , 0
    4406     .05       0  4413.8     .16       0  4499.4     .05       0
  4761.3     .16       0  4996.8     .07       0  5002.8     .16       0
  5062.9     .05       0
Bank Sta=4938.9,5020.1
XS Rating Curve= 0 ,0
Exp/Cntr=0.3,0.1

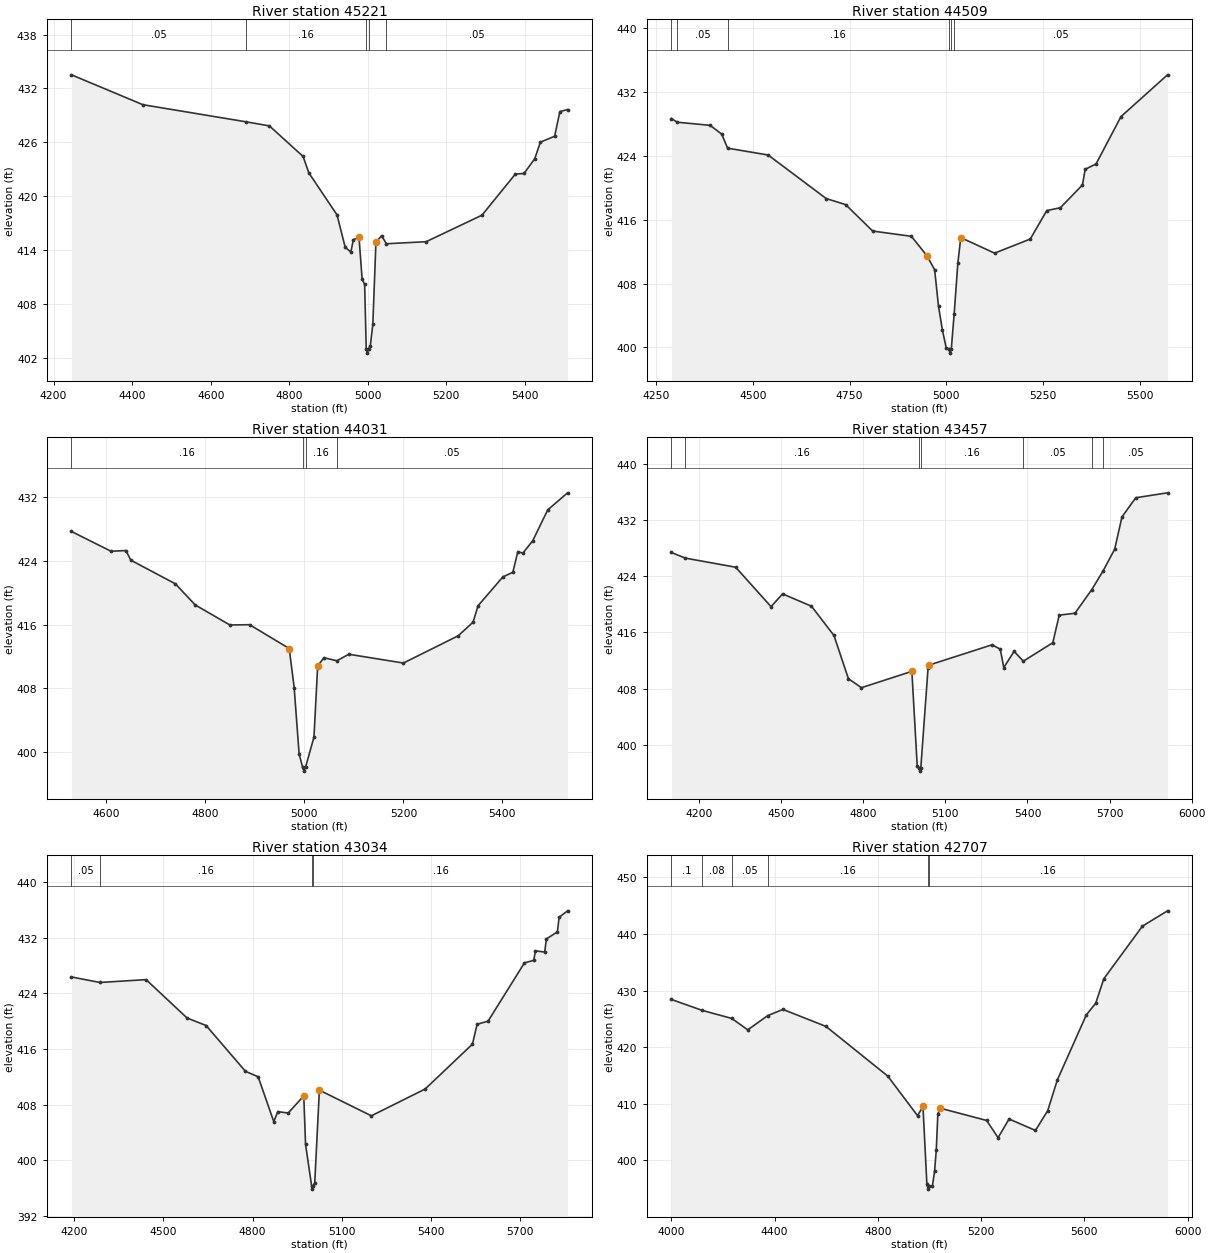
Type RM Length L Ch R = 1 ,45221   ,712,712,712
BEGIN DESCRIPTION:
LINN CREEK 80.0
END DESCRIPTION:
XS GIS Cut Line= 3
      3586636.29     10565563.01      3586419.28     10565059.55
      3585968.37     10564504.58
#Sta/Elev= 30
  4245.5  433.51  4427.4  430.18  4690.5  428.27  4749.5  427.82  4835.4  424.41
  4849.8  422.59  4921.7   417.9  4942.5  414.29  4956.9  413.76  4963.3  415.14
  4977.7  415.39  4985.6  410.75    4992  410.15  4996.1  402.99  4998.8  402.49
  5002.1  402.99  5006.4  403.28  5012.9  405.72  5020.8  414.87  5035.2  415.57
  5047.5  414.68  5148.6  414.91  5290.9  417.87  5375.6  422.44  5397.9  422.52
  5425.2  424.16  5439.5  426.01  5475.8  426.66  5489.1  429.41  5508.8  429.64
#Mann= 5 ,-1 , 0
  4245.5     .05       0  4690.5     .16       0  4996.1     .07       0
  5002.1     .16       0  5047.5     .05       0
Bank Sta=4977.7,5020.8
XS Rating Curve= 0 ,0
Exp/Cntr=0.3,0.1

Type RM Length L Ch R = 1 ,44509   ,478,478,478
BEGIN DESCRIPTION:
LINN CREEK 79.0
END DESCRIPTION:
XS GIS Cut Line= 3
       3587199.6     10564510.19      3586449.61     10564510.19
       3586049.6     10564160.18
#Sta/Elev= 30
  4289.7  428.69    4305  428.23  4389.7  427.84  4419.7  426.74  4434.9  424.98
  4539.7  424.12  4689.7  418.66  4739.7  417.91  4809.7  414.59  4909.7  413.93
  4949.7   411.5  4969.7  409.74  4979.7  405.16  4989.7   402.2  4999.7  399.92
  5006.7  399.79  5009.4  399.29  5012.7  399.79  5020.1  404.17  5029.7  410.59
  5037.2  413.77  5124.6  411.82  5216.7  413.59  5259.4  417.16  5294.5  417.51
  5351.5  420.37  5358.6  422.33  5386.6     423  5451.1  428.94  5571.2  434.17
#Mann= 6 ,-1 , 0
  4289.7     .16       0    4305     .05       0  4434.9     .16       0
  5006.7     .07       0  5012.7     .16       0  5020.1     .05       0
Bank Sta=4949.7,5037.2
XS Rating Curve= 0 ,0
Exp/Cntr=0.3,0.1

Type RM Length L Ch R = 1 ,44031   ,574,574,574
BEGIN DESCRIPTION:
LINN CREEK 78.0
END DESCRIPTION:
XS GIS Cut Line= 3
      3587099.58     10564160.19      3586599.61     10564160.19
      3586099.57     10564110.18
#Sta/Elev= 30
  4529.3  427.67  4609.3  425.19  4639.3  425.28  4649.3  424.07  4739.3  421.11
  4779.3  418.47  4849.3  415.96  4889.3  415.99  4969.3  413.01  4979.3  408.11
  4989.3  399.82  4996.3  398.15    4999  397.65  5002.3  398.15  5019.3  401.91
  5026.8  410.82  5039.3  411.85  5065.8  411.48  5089.6  412.29  5200.1  411.19
  5310.7   414.6  5340.8  416.31  5350.9  418.37  5401.1  421.98  5421.2  422.56
  5431.3  425.15  5441.3  424.95  5461.4  426.51  5491.6  430.37  5531.8  432.51
#Mann= 4 ,-1 , 0
  4529.3     .16       0  4996.3     .07       0  5002.3     .16       0
  5065.8     .05       0
Bank Sta=4969.3,5026.8
XS Rating Curve= 0 ,0
Exp/Cntr=0.3,0.1

Type RM Length L Ch R = 1 ,43457   ,423,423,423
BEGIN DESCRIPTION:
LINN CREEK 77.0
END DESCRIPTION:
XS GIS Cut Line= 3
      3587474.69     10563984.78      3586745.51     10563677.48
      3585735.13     10563526.44
#Sta/Elev= 30
  4098.8   427.4  4149.3   426.6  4333.6   425.3    4463  419.68  4505.1   421.5
  4610.8  419.74  4692.9  415.57  4745.7  409.41  4793.2  408.13  4977.6  410.46
  4997.2  396.94  5004.3  396.74    5007  396.24  5010.3  396.74  5036.7  410.92
  5041.8  411.37  5270.2  414.24  5300.5  413.63  5313.5     411  5351.1  413.31
  5384.9  411.91  5492.6  414.54  5516.1  418.47  5573.5  418.74  5635.1  422.11
    5677  424.82  5718.7  427.87  5745.4  432.48  5795.9   435.2  5911.7   435.9
#Mann= 7 ,-1 , 0
  4098.8     .05       0  4149.3     .16       0  5004.3     .07       0
  5010.3     .16       0  5384.9     .05       0  5635.1     .16       0
    5677     .05       0
Bank Sta=4977.6,5041.8
XS Rating Curve= 0 ,0
Exp/Cntr=0.3,0.1

Type RM Length L Ch R = 1 ,43034   ,327,327,327
BEGIN DESCRIPTION:
LINN CREEK 76.0
END DESCRIPTION:
XS GIS Cut Line= 2
      3587604.91     10563797.29      3586173.59     10562938.49
#Sta/Elev= 30
  4190.4  426.37  4286.2  425.58  4441.4  425.99  4579.4  420.47  4643.5  419.39
  4775.7  412.81  4818.5  412.02    4871  405.58  4884.6  407.01  4919.6  406.81
    4972  409.28  4977.9  402.33  4998.3  396.37    5001  395.87  5004.3  396.37
  5008.9   396.8  5024.5   410.1  5199.4  406.41  5380.2  410.26  5539.6  416.72
  5555.1  419.57    5592  420.02  5714.5   428.4  5745.6  428.76  5751.4  430.12
  5782.5  429.96  5788.4  431.85  5825.3  432.85  5831.1  434.96  5859.6  435.88
#Mann= 4 ,-1 , 0
  4190.4     .05       0  4286.2     .16       0  4998.3     .07       0
  5004.3     .16       0
Bank Sta=4972,5024.5
XS Rating Curve= 0 ,0
Exp/Cntr=0.3,0.1

Type RM Length L Ch R = 1 ,42707   ,360,360,360
BEGIN DESCRIPTION:
LINN CREEK 75.0
END DESCRIPTION:
XS GIS Cut Line= 3
      3587959.04     10563687.89      3586859.61      10562985.9
      3586276.79     10562781.66
#Sta/Elev= 30
  4000.1  428.43  4118.1  426.52    4234  425.08    4296  423.06  4373.3  425.58
  4432.5  426.67  4599.2  423.66  4838.6  414.88  4953.7   407.9  4974.8  409.52
    4990  395.78    4993  395.42  4995.8  394.92    4999  395.42  5011.2  395.47
  5019.8  398.09  5026.4   401.9  5032.4  408.21  5041.6  409.22  5221.5  407.05
  5265.8  404.01  5308.3  407.31  5410.5  405.29    5458  408.78  5495.3  414.21
  5607.8  425.72  5644.1  427.77  5675.4  432.09  5824.9  441.38  5922.1  444.09
#Mann= 6 ,-1 , 0
  4000.1      .1       0  4118.1     .08       0    4234     .05       0
  4373.3     .16       0    4993     .07       0    4999     .16       0
Bank Sta=4974.8,5041.6
XS Rating Curve= 0 ,0
Exp/Cntr=0.3,0.1

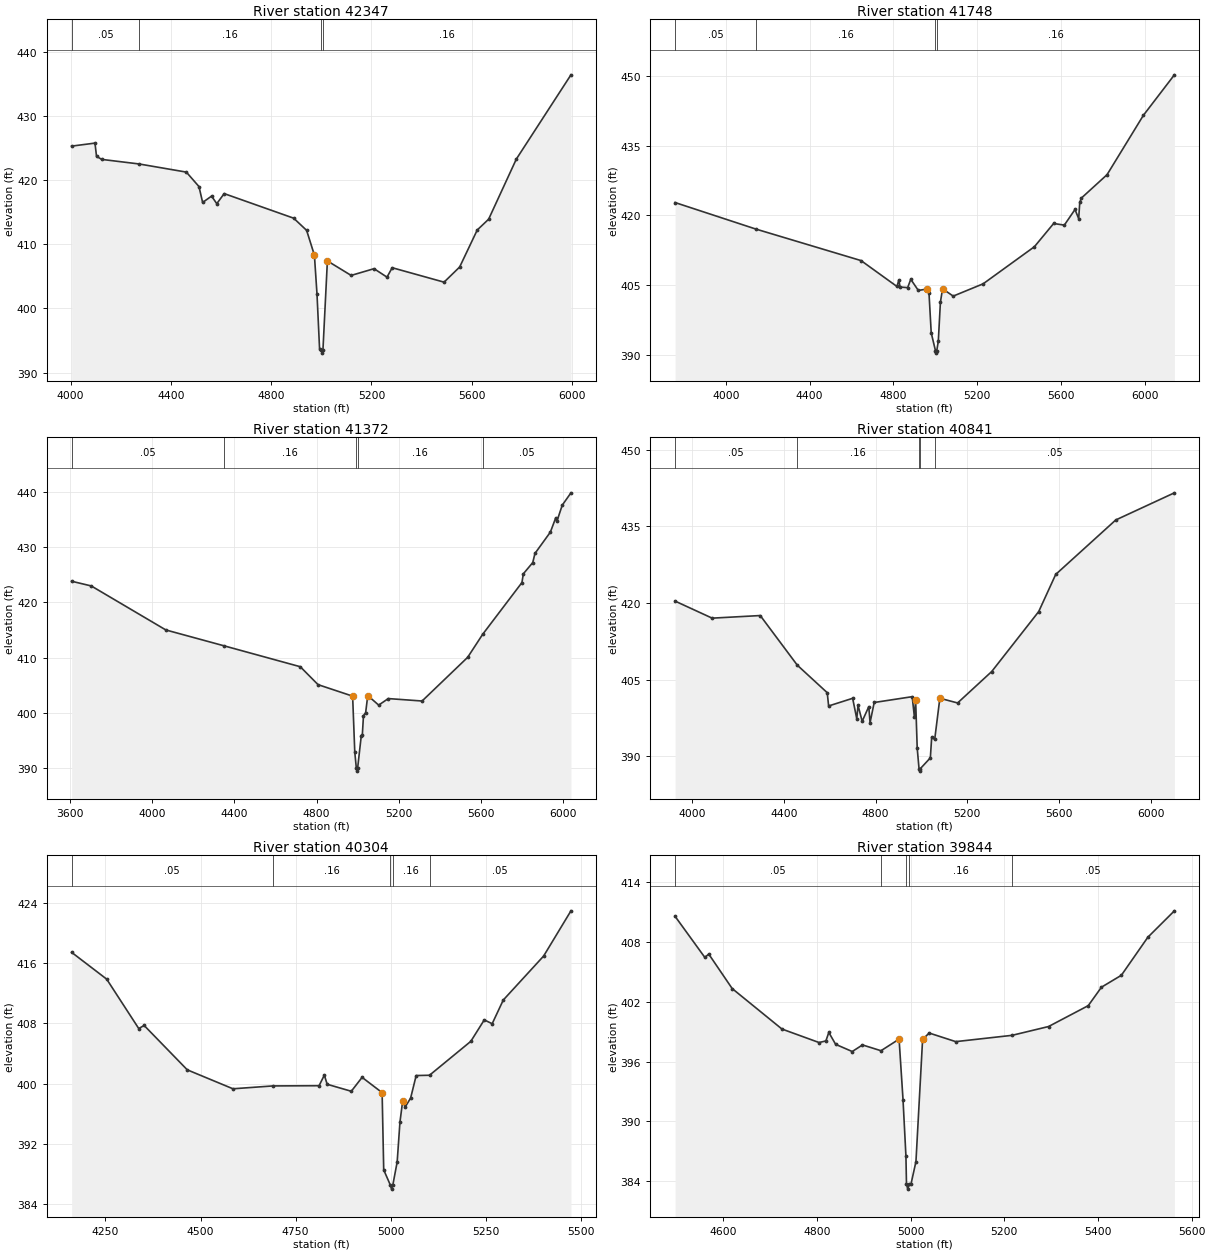
Type RM Length L Ch R = 1 ,42347   ,599,599,599
BEGIN DESCRIPTION:
LINN CREEK 74.0
END DESCRIPTION:
XS GIS Cut Line= 3
      3588157.01     10563411.88       3587485.1     10562927.48
      3586360.12     10562630.61
#Sta/Elev= 30
    4004   425.3  4097.1  425.77  4103.3  423.71  4124.1  423.23  4272.9  422.52
  4461.6  421.25  4511.9     419  4526.6  416.52  4562.2  417.51    4583  416.33
  4612.5   417.9  4889.7  414.07  4941.4  412.17  4972.4  408.31  4982.8  402.21
    4993  393.73  5000.5  393.54  5003.2  393.04  5006.5  393.54  5024.2  407.41
    5119  405.15  5210.3   406.2    5262  404.88  5282.7  406.35  5489.6   404.1
  5551.8  406.46    5622  412.23  5667.4  413.91  5777.9  423.28  5995.8  436.41
#Mann= 4 ,-1 , 0
    4004     .05       0  4272.9     .16       0  5000.5     .07       0
  5006.5     .16       0
Bank Sta=4972.4,5024.2
XS Rating Curve= 0 ,0
Exp/Cntr=0.3,0.1

Type RM Length L Ch R = 1 ,41748   ,376,376,376
BEGIN DESCRIPTION:
LINN CREEK 73.0
END DESCRIPTION:
XS GIS Cut Line= 3
      3588115.29     10563094.14      3587099.61     10562410.19
      3585964.46     10562187.94
#Sta/Elev= 30
  3758.4  422.78  4142.5   417.1  4645.3  410.31  4816.5  404.75  4825.4  406.11
  4831.5  404.63  4867.5   404.5  4882.4  406.29  4918.4   403.9  4960.4   404.2
  4969.4  403.27  4979.9  394.79  5000.3  390.93    5003  390.43  5006.3  390.93
  5013.7  392.99  5023.7  401.34  5033.9  404.25  5084.8  402.68  5227.5  405.32
    5472  413.29  5563.7  418.28  5614.7  417.93  5665.6  421.29  5683.2  419.32
  5688.3  422.82  5696.2  423.75  5818.5  428.77  5991.7  441.52  6139.6  450.22
#Mann= 4 ,-1 , 0
  3758.4     .05       0  4142.5     .16       0  5000.3     .07       0
  5006.3     .16       0
Bank Sta=4960.4,5033.9
XS Rating Curve= 0 ,0
Exp/Cntr=0.3,0.1

Type RM Length L Ch R = 1 ,41372   ,531,531,531
BEGIN DESCRIPTION:
LINN CREEK 72.0
END DESCRIPTION:
XS GIS Cut Line= 3
       3588235.1     10563088.94      3587495.51     10562182.69
      3586303.72     10561781.96
#Sta/Elev= 30
  3609.5  423.84  3704.9  422.99  4067.5  415.03  4348.5  412.18  4720.9  408.38
  4807.3  405.14  4975.4  403.06  4985.8  392.93  4993.5     390  4996.2   389.5
  4999.5     390  5017.4   395.9  5022.6  396.11  5028.1  399.52  5038.7  400.09
  5048.9  403.17    5102  401.44  5148.7  402.62    5313  402.18  5534.5  410.08
  5607.6  414.25  5798.3   423.6  5805.2  425.19    5851  427.22  5861.6  428.87
  5936.5  432.72  5962.8  435.33    5968  434.65  5994.3   437.6  6036.6  439.83
#Mann= 5 ,-1 , 0
  3609.5     .05       0  4348.5     .16       0  4993.5     .07       0
  4999.5     .16       0  5607.6     .05       0
Bank Sta=4975.4,5048.9
XS Rating Curve= 0 ,0
Exp/Cntr=0.3,0.1

Type RM Length L Ch R = 1 ,40841   ,537,537,537
BEGIN DESCRIPTION:
LINN CREEK 71.0
END DESCRIPTION:
XS GIS Cut Line= 3
      3588318.46     10562151.45      3587299.61     10561710.19
      3586334.33     10561255.74
#Sta/Elev= 30
  3925.5  420.37  4087.2  417.03  4296.9  417.54  4458.5  407.81    4589  402.42
    4595  399.82  4699.8  401.32  4717.8   397.3  4723.2  399.96  4741.3  396.82
  4770.2  399.69  4775.7  396.54  4793.7   400.5  4959.5  401.64  4968.9  397.71
  4974.4  400.94  4981.3  391.55  4989.2  387.55    4992  387.05  4995.2  387.55
  5038.6  389.65  5044.4  393.69  5057.6  393.28    5080  401.33  5157.4  400.41
  5306.2  406.57  5511.1  418.32  5585.2   425.6    5847  436.27  6102.7  441.59
#Mann= 5 ,-1 , 0
  3925.5     .05       0  4458.5     .16       0  4989.2     .07       0
  4995.2     .16       0  5057.6     .05       0
Bank Sta=4974.4,5080
XS Rating Curve= 0 ,0
Exp/Cntr=0.3,0.1

Type RM Length L Ch R = 1 ,40304   ,460,460,460
BEGIN DESCRIPTION:
LINN CREEK 70.0
END DESCRIPTION:
XS GIS Cut Line= 3
       3587999.6     10561960.17      3587449.61     10561360.19
      3587049.63      10561060.2
#Sta/Elev= 30
  4160.9  417.45  4253.1  413.89  4337.5  407.32  4351.7  407.73  4465.2  401.83
  4585.4  399.31  4690.2  399.69    4812  399.72  4825.9  401.13  4833.3  399.91
  4896.8  398.98  4925.2  400.83  4977.9   398.8  4982.1  388.53  4999.9  386.47
  5002.7  385.97  5005.9  386.47  5017.5  389.58  5024.8  394.87  5032.1  397.73
  5038.4  396.88  5052.9  398.07  5067.5  401.07  5102.6  401.11  5211.3  405.62
  5246.7  408.47  5267.5  407.96  5296.7  411.11  5402.9  416.96  5474.8  422.97
#Mann= 5 ,-1 , 0
  4160.9     .05       0  4690.2     .16       0  4999.9     .07       0
  5005.9     .16       0  5102.6     .05       0
Bank Sta=4977.9,5032.1
XS Rating Curve= 0 ,0
Exp/Cntr=0.3,0.1

Type RM Length L Ch R = 1 ,39844   ,657,657,657
BEGIN DESCRIPTION:
LINN CREEK 69.0
END DESCRIPTION:
XS GIS Cut Line= 3
       3588199.6     10561510.18      3587799.61     10561210.19
      3587399.59     10560810.17
#Sta/Elev= 30
  4497.5  410.53    4561  406.42  4569.4  406.75  4619.4   403.3  4725.6  399.25
  4804.8   397.9  4819.4  398.06  4825.6  398.91  4840.2  397.72  4875.6     397
  4897.5  397.66    4937  397.08  4975.6  398.24    4984  392.19  4990.2  386.55
  4991.4  383.73  4994.1  383.23  4997.4  383.73    5001  383.73  5011.6  385.99
  5025.8  398.22  5039.9  398.85  5096.5  397.99  5216.7  398.62  5294.5   399.5
  5379.3  401.59  5407.6  403.44    5450  404.63  5506.6  408.44  5563.2  411.08
#Mann= 5 ,-1 , 0
  4497.5     .05       0    4937     .16       0  4991.4     .07       0
  4997.4     .16       0  5216.7     .05       0
Bank Sta=4975.6,5025.8
XS Rating Curve= 0 ,0
Exp/Cntr=0.3,0.1

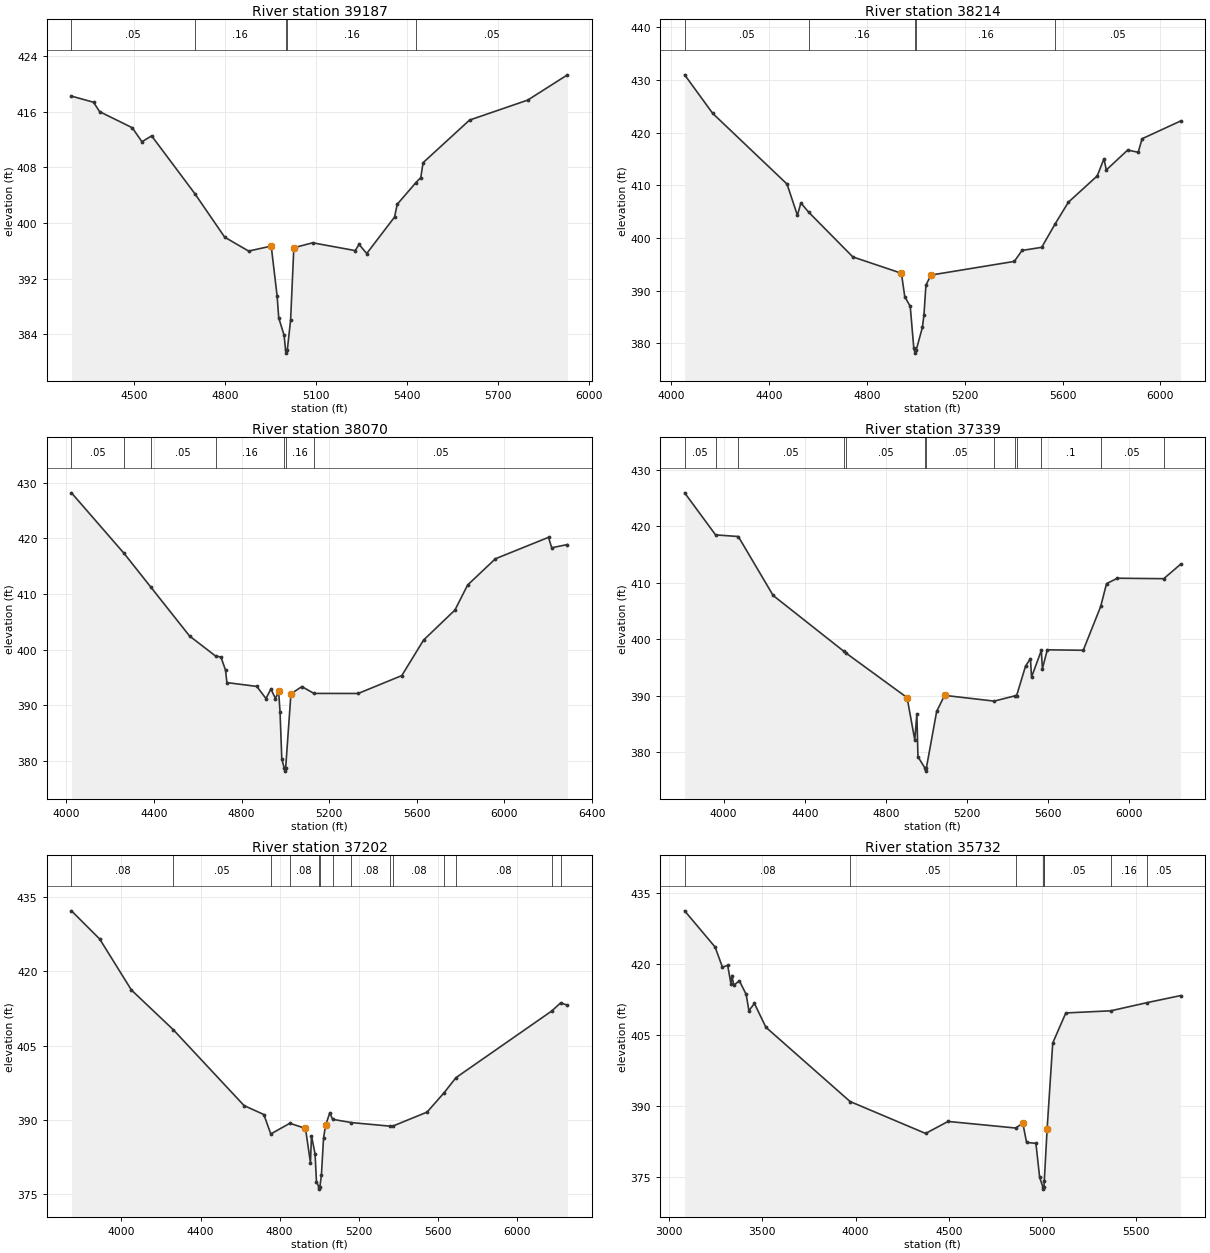
Type RM Length L Ch R = 1 ,39187   ,973,973,973
BEGIN DESCRIPTION:
LINN CREEK 68.0
END DESCRIPTION:
XS GIS Cut Line= 3
      3588427.79     10561698.29      3588021.56     10560583.73
      3587620.51     10560385.81
#Sta/Elev= 30
  4294.5  418.23  4367.3  417.35  4387.2     416  4494.7  413.69  4526.6  411.68
  4558.6  412.52  4700.7  404.23  4799.1  397.97  4877.9  395.97  4952.4  396.69
  4971.9  389.49  4977.2  386.36  4994.9  383.87  4999.5  381.81  5002.2  381.31
  5005.5  381.81  5016.2  386.04  5026.9  396.45  5088.8  397.16  5229.1  396.04
  5241.7  396.93  5266.9  395.62  5358.6  400.86  5367.5   402.7    5429  405.81
    5445  406.54  5452.6  408.67  5605.6  414.79  5797.3  417.66    5928  421.29
#Mann= 5 ,-1 , 0
  4294.5     .05       0  4700.7     .16       0  4999.5     .07       0
  5005.5     .16       0    5429     .05       0
Bank Sta=4952.4,5026.9
XS Rating Curve= 0 ,0
Exp/Cntr=0.3,0.1

Type RM Length L Ch R = 1 ,38214   ,144,144,144
BEGIN DESCRIPTION:
LINN CREEK 67.0
END DESCRIPTION:
XS GIS Cut Line= 4
      3589365.32     10561026.45      3588792.39     10560495.19
      3588526.76     10560286.86      3587735.11     10559838.94
#Sta/Elev= 30
  4054.4  430.96  4169.2  423.64  4473.1  410.23  4515.6   404.3  4529.8  406.64
  4561.9  404.88  4742.4   396.4  4940.9   393.3  4954.6  388.87  4977.1  387.01
  4991.6  379.09    4995  378.64  4997.7  378.14    5001  378.64  5026.9  383.04
  5033.2  385.42  5041.3  391.07  5062.1  392.96  5402.8  395.55  5434.3  397.63
  5514.7  398.22  5568.7  402.59  5623.7  406.78    5742  411.78  5769.4  415.04
    5779   412.9  5866.2  416.68  5909.4  416.26  5925.3  418.83  6082.9   422.2
#Mann= 5 ,-1 , 0
  4054.4     .05       0  4561.9     .16       0    4995     .07       0
    5001     .16       0  5568.7     .05       0
Bank Sta=4940.9,5062.1
XS Rating Curve= 0 ,0
Exp/Cntr=0.3,0.1

Type RM Length L Ch R = 1 ,38070   ,731,731,731
BEGIN DESCRIPTION:
LINN CREEK 66.0
END DESCRIPTION:
XS GIS Cut Line= 2
       3589511.1     10560875.37      3587719.46     10559489.97
#Sta/Elev= 30
  4023.4  428.22  4263.8  417.31  4384.5  411.31  4562.8  402.44  4681.5  398.84
  4705.9  398.66  4726.8  396.32  4733.2  394.06  4869.8  393.37  4911.5  391.19
  4934.1  392.91    4955  391.19  4969.4  392.48  4975.8  388.84  4983.9  380.28
  4995.4  378.62  4998.2  378.12  5001.4  378.62  5025.6  392.03  5075.4  393.34
  5130.7  392.11  5332.6   392.1  5531.8  395.32  5631.4  401.72  5774.5  407.12
  5832.5  411.63  5959.3  416.35  6201.9  420.21  6216.4  418.33  6288.2  418.91
#Mann= 7 ,-1 , 0
  4023.4     .05       0  4263.8     .08       0  4384.5     .05       0
  4681.5     .16       0  4995.4     .07       0  5001.4     .16       0
  5130.7     .05       0
Bank Sta=4969.4,5025.6
XS Rating Curve= 0 ,0
Exp/Cntr=0.3,0.1

Type RM Length L Ch R = 1 ,37339   ,137,137,137
BEGIN DESCRIPTION:
LINN CREEK 64.0
END DESCRIPTION:
XS GIS Cut Line= 3
      3589672.59     10560792.04      3589349.68     10559885.81
      3587974.66     10559328.52
#Sta/Elev= 30
  3807.5  425.96    3960   418.5  4072.1  418.21  4243.9  407.75  4593.6  397.82
  4602.9  397.54  4904.4  389.63  4942.3  382.13  4952.6  386.73    4958  379.14
  4993.2  377.09    4996  376.59  4999.2  377.09  5050.2  387.18  5089.3  390.03
  5333.8  389.01  5438.8  389.97  5444.5  389.99  5488.6  395.23  5512.7  396.55
  5518.1  393.26  5566.3  398.01  5571.7  394.76  5595.8  398.11  5773.1  398.03
    5859   405.8  5887.9  409.85  5941.5  410.81    6170  410.73  6253.2  413.29
#Mann= 13 ,-1 , 0
  3807.5     .05       0    3960      .1       0  4072.1     .05       0
  4593.6     .08       0  4602.9     .05       0  4993.2     .04       0
  4999.2     .05       0  5333.8     .08       0  5438.8      .1       0
  5444.5     .08       0  5566.3      .1       0    5859     .05       0
    6170     .08       0
Bank Sta=4904.4,5089.3
XS Rating Curve= 0 ,0
Exp/Cntr=0.3,0.1

Type RM Length L Ch R = 1 ,37202   ,1470,1470,1470
BEGIN DESCRIPTION:
LINN CREEK 63.0
END DESCRIPTION:
XS GIS Cut Line= 4
      3590422.59      10559755.6      3589339.26     10559729.56
       3588985.1     10559599.36      3588023.07     10559183.34
#Sta/Elev= 30
    3747  432.25    3890  426.54  4050.1  416.24  4261.7  408.22  4620.2  392.86
  4720.3  391.05  4755.3  387.12  4851.9  389.28  4930.9  388.24    4956  381.32
  4961.3  386.73  4979.4   383.1  4986.5  377.47  4997.7  376.46  5000.5  375.96
  5003.7  376.46  5011.4  378.73  5022.3  386.33  5032.7  388.88    5054  391.42
    5068  390.08  5163.5  389.42  5360.2  388.69  5374.5  388.74  5546.1  391.54
    5632  395.45  5692.3  398.51  6175.6  411.96  6222.1  413.64  6256.1  413.15
#Mann= 14 ,-1 , 0
    3747     .08       0  4261.7     .05       0  4755.3     .12       0
  4851.9     .08       0  4997.7     .07       0  5003.7     .08       0
    5068     .16       0  5163.5     .08       0  5360.2     .16       0
  5374.5     .08       0    5632     .05       0  5692.3     .08       0
  6175.6     .16       0  6222.1     .08       0
Bank Sta=4930.9,5032.7
XS Rating Curve= 0 ,0
Exp/Cntr=0.3,0.1

Type RM Length L Ch R = 1 ,35732   ,872,872,872
BEGIN DESCRIPTION:
LINN CREEK 62.0
END DESCRIPTION:
XS GIS Cut Line= 3
      3590537.14     10559542.04       3589485.1     10559042.06
      3587995.54     10558974.36
#Sta/Elev= 30
  3084.1  431.16  3247.4  423.52  3286.3   419.3  3314.6  419.66  3331.8  415.83
  3337.3  417.53  3347.1  415.48  3377.2  416.43  3413.5  413.55  3428.2  410.13
  3457.8  411.65  3519.1  406.64  3970.1  390.99  4374.5  384.27  4494.6   386.8
  4856.6  385.41  4895.1  386.41  4915.1  382.37  4965.1  382.19  4985.2     375
  5002.2  373.04  5004.9  372.54  5008.2  373.04  5010.1  374.32  5025.2  385.25
  5055.2  403.32  5125.3  409.65  5365.6   410.1  5560.3  411.82    5740  413.31
#Mann= 8 ,-1 , 0
  3084.1     .08       0  3970.1     .05       0  4856.6     .16       0
  5002.2     .07       0  5008.2     .16       0  5010.1     .05       0
  5365.6     .16       0  5560.3     .05       0
Bank Sta=4895.1,5025.2
XS Rating Curve= 0 ,0
Exp/Cntr=0.3,0.1

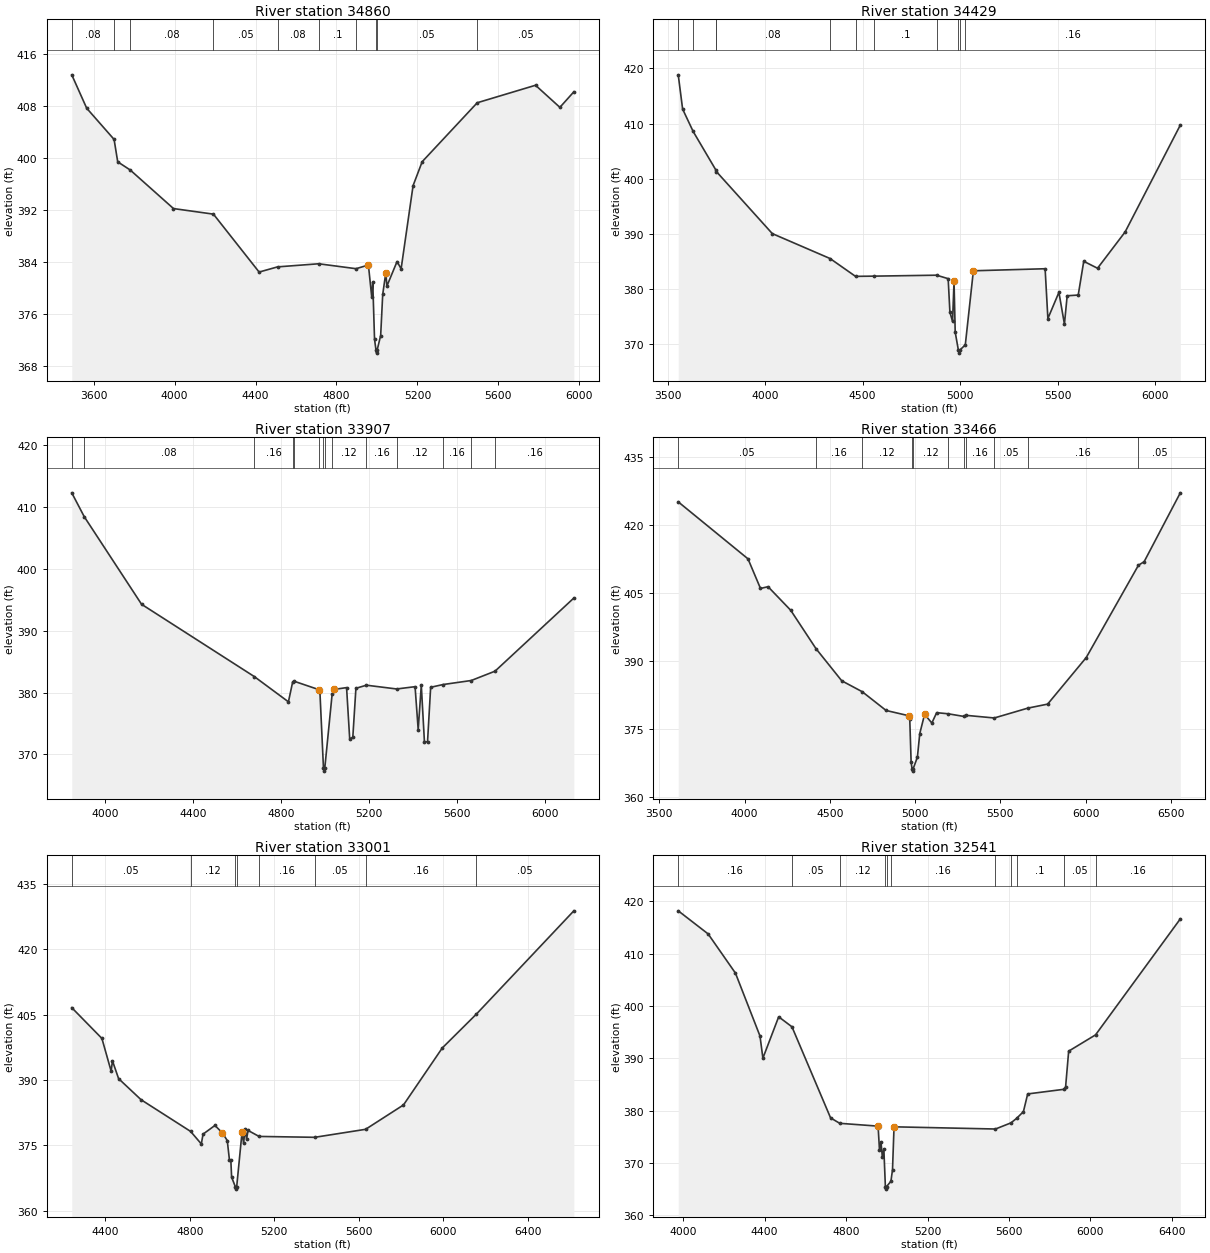
Type RM Length L Ch R = 1 ,34860   ,431,431,431
BEGIN DESCRIPTION:
LINN CREEK 61.0
END DESCRIPTION:
XS GIS Cut Line= 4
      3590287.21     10559203.54       3589172.6     10558531.65
      3588781.97     10558474.36      3588068.46     10558802.47
#Sta/Elev= 30
  3491.6  412.86  3565.3  407.71  3700.8  402.89  3718.7  399.43  3780.2  398.18
  3994.4  392.22  4191.8  391.36  4417.6  382.42  4508.6  383.22  4711.9   383.7
  4896.8  382.94  4957.8  383.51  4974.2  378.57  4979.2  380.88  4988.1  372.03
  4995.2  370.41    4998  369.91  5001.2  370.41  5018.4  372.63  5028.5  378.98
    5044  382.35  5049.1  380.25  5099.3  384.04  5119.5  382.93  5178.6  395.76
  5223.5  399.45  5495.7  408.55  5783.8  411.25  5904.2  407.84  5973.2  410.24
#Mann= 10 ,-1 , 0
  3491.6     .08       0  3700.8     .05       0  3780.2     .08       0
  4191.8     .05       0  4508.6     .08       0  4711.9      .1       0
  4896.8     .05       0  4995.2     .07       0  5001.2     .05       0
  5495.7     .05       0
Bank Sta=4957.8,5044
XS Rating Curve= 0 ,0
Exp/Cntr=0.3,0.1

Type RM Length L Ch R = 1 ,34429   ,522,522,522
BEGIN DESCRIPTION:
LINN CREEK 60.0
END DESCRIPTION:
XS GIS Cut Line= 3
       3590299.6     10559110.18      3589099.61     10558310.19
      3588299.59     10557510.17
#Sta/Elev= 30
  3554.7  418.83  3577.2  412.62  3631.2  408.56  3748.6  401.51  3750.4  401.28
  4036.9  390.04  4333.1  385.52  4463.4  382.29  4558.8  382.33  4878.9   382.5
  4938.3  381.87  4947.3  375.79  4960.8  374.11  4968.4  381.39  4974.4  372.18
  4990.9  368.87  4993.7  368.37  4996.9  368.87  5026.2  369.87  5067.6   383.3
  5435.3  383.67  5449.5  374.64    5506  379.39  5534.3  373.64  5548.4  378.77
    5605   378.9  5633.3  385.02    5704  383.76  5845.4  390.34  6128.3  409.72
#Mann= 11 ,-1 , 0
  3554.7      .1       0  3631.2     .08       0  3748.6     .05       0
  3750.4     .08       0  4333.1     .05       0  4463.4     .08       0
  4558.8      .1       0  4878.9     .05       0  4990.9     .03       0
  4996.9     .05       0  5026.2     .16       0
Bank Sta=4968.4,5067.6
XS Rating Curve= 0 ,0
Exp/Cntr=0.3,0.1

Type RM Length L Ch R = 1 ,33907   ,441,441,441
BEGIN DESCRIPTION:
LINN CREEK 59.0
END DESCRIPTION:
XS GIS Cut Line= 3
      3590391.37     10558969.17      3589449.61     10558310.19
       3588649.6     10557510.18
#Sta/Elev= 30
  3848.5  412.33    3905  408.48  4165.6   394.3  4677.5  382.61  4832.7  378.52
  4851.9  381.72  4858.7  381.85  4969.4  380.51  4975.7  380.19  4991.9  367.81
  4994.6  367.31  4997.9  367.81  5031.4  379.81  5040.3  380.53  5096.9  380.82
  5111.1  372.51  5125.2  372.79  5139.3  380.71  5187.1  381.21  5324.4   380.6
    5408  380.97  5422.2  374.03  5436.3  381.21  5450.5  372.09  5464.6  372.03
  5478.8  380.87  5535.5  381.32  5663.3  381.97  5771.3  383.48  6129.3  395.31
#Mann= 14 ,-1 , 0
  3848.5      .1       0    3905     .08       0  4677.5     .16       0
  4851.9     .05       0  4858.7     .12       0  4969.4     .05       0
  4991.9     .03       0  4997.9     .05       0  5031.4     .12       0
  5187.1     .16       0  5324.4     .12       0  5535.5     .16       0
  5663.3     .05       0  5771.3     .16       0
Bank Sta=4969.4,5040.3
XS Rating Curve= 0 ,0
Exp/Cntr=0.3,0.1

Type RM Length L Ch R = 1 ,33466   ,465,465,465
BEGIN DESCRIPTION:
LINN CREEK 58.0
END DESCRIPTION:
XS GIS Cut Line= 3
      3590933.03     10558646.24      3589699.61     10558010.19
      3588599.61     10556910.19
#Sta/Elev= 30
  3611.5  425.05  4020.4  412.51  4093.7  405.99    4138  406.38  4270.9  401.19
  4418.9  392.75  4569.9  385.67  4690.1  383.26  4830.2  379.13  4963.2  377.97
  4968.8  377.21  4976.8  367.77  4982.4  366.28  4985.1  365.78  4988.4  366.28
  5013.4  368.81  5027.5  374.06  5055.8  378.28  5098.3  376.37  5126.5  378.65
  5194.2   378.4  5286.1  377.82  5298.7  378.06  5464.3  377.48  5661.2  379.65
  5777.1  380.53  6003.4  390.78  6309.5   411.1  6342.8  411.88  6554.9  427.04
#Mann= 11 ,-1 , 0
  3611.5     .05       0  4418.9     .16       0  4690.1     .12       0
  4982.4     .07       0  4988.4     .12       0  5194.2     .16       0
  5286.1     .12       0  5298.7     .16       0  5464.3     .05       0
  5661.2     .16       0  6309.5     .05       0
Bank Sta=4963.2,5055.8
XS Rating Curve= 0 ,0
Exp/Cntr=0.3,0.1

Type RM Length L Ch R = 1 ,33001   ,460,460,460
BEGIN DESCRIPTION:
LINN CREEK 57.0
END DESCRIPTION:
XS GIS Cut Line= 3
      3590549.57     10558160.16      3589949.61     10557710.19
      3588749.63     10556610.21
#Sta/Elev= 30
  4241.4  406.59  4384.1  399.54  4427.8  392.04  4434.1   394.4  4463.2  390.32
  4569.5  385.49  4804.3  378.22  4854.9  375.35  4863.2   377.6  4919.5  379.59
  4954.9  377.87  4977.8  376.13  4988.2  371.65  4994.7  371.65  4998.4  367.75
  5016.4  365.49  5019.2  364.99  5022.4  365.49  5047.8  378.07  5055.2  375.51
    5062   378.7  5069.4  376.45  5076.1  378.45  5128.4  377.07  5392.1  376.87
  5632.8   378.7  5812.4  384.29  5996.1  397.35  6157.2  405.09  6619.2  428.79
#Mann= 8 ,-1 , 0
  4241.4     .05       0  4804.3     .12       0  5016.4     .07       0
  5022.4     .12       0  5128.4     .16       0  5392.1     .05       0
  5632.8     .16       0  6157.2     .05       0
Bank Sta=4954.9,5047.8
XS Rating Curve= 0 ,0
Exp/Cntr=0.3,0.1

Type RM Length L Ch R = 1 ,32541   ,1032,1032,1032
BEGIN DESCRIPTION:
LINN CREEK 56.0
END DESCRIPTION:
XS GIS Cut Line= 3
      3590953.85     10558203.53      3590249.61     10557460.19
       3589049.6     10556660.18
#Sta/Elev= 30
  3975.6  418.17  4122.4  413.76  4256.7  406.27  4377.2  394.26  4391.4  390.03
    4469  397.93  4534.2  396.02  4723.9  378.63  4768.8  377.59  4957.3  377.05
  4964.2  372.45  4971.4  374.04  4978.3  371.13  4985.6  372.67  4993.1  365.52
  4995.9  365.02  4999.1  365.52  5020.3  366.52  5028.1  368.71  5035.6  376.92
  5533.8   376.5  5609.7  377.67  5637.6  378.53  5671.1  379.82  5692.1   383.2
  5869.3  384.08  5878.4  384.57  5893.4  391.37  6025.4  394.48  6441.8  416.63
#Mann= 11 ,-1 , 0
  3975.6     .16       0  4534.2     .05       0  4768.8     .12       0
  4993.1     .07       0  4999.1     .12       0  5020.3     .16       0
  5533.8     .05       0  5609.7     .08       0  5637.6      .1       0
  5869.3     .05       0  6025.4     .16       0
Bank Sta=4957.3,5035.6
XS Rating Curve= 0 ,0
Exp/Cntr=0.3,0.1