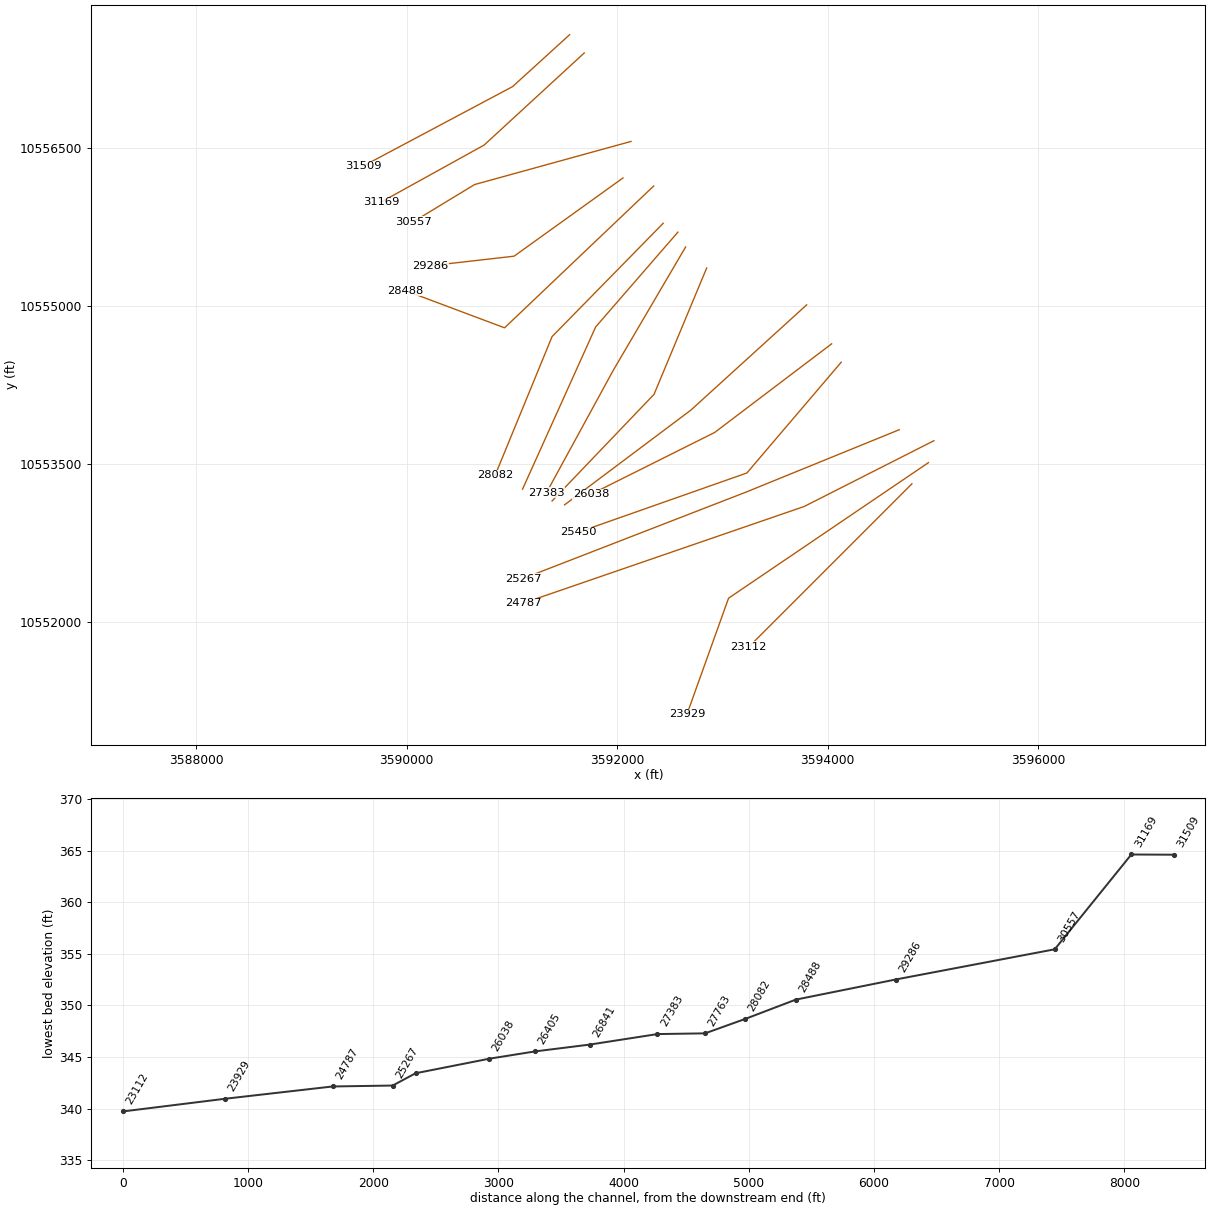
HEC-RAS study LINN CREEK.prj: LINN CREEK Base Level Engineering

--- LINN CREEK.g01 (geometry) --- (continued)

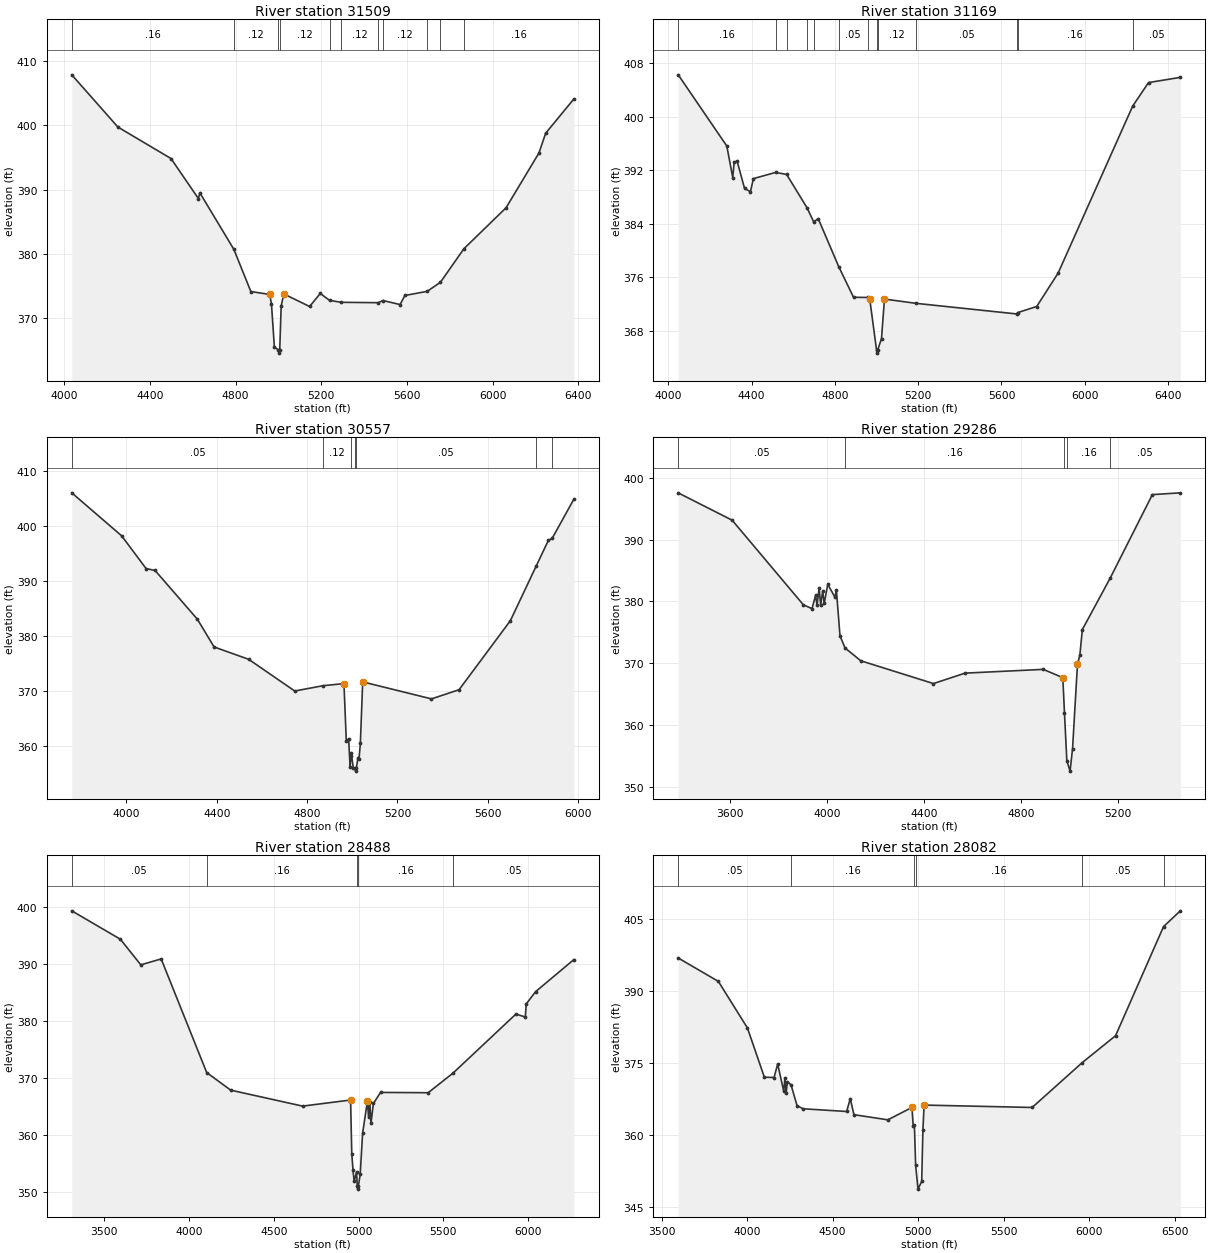
Type RM Length L Ch R = 1 ,31509   ,340,340,340
BEGIN DESCRIPTION:
LINN CREEK 55.0
END DESCRIPTION:
XS GIS Cut Line= 3
      3591547.58     10557576.77      3591005.93     10557083.73
      3589583.45     10556327.39
#Sta/Elev= 30
  4035.6  407.82    4251  399.71  4498.9  394.82  4626.6  388.61  4633.4   389.5
  4792.2  380.72  4871.5  374.17  4959.4  373.72  4967.7  372.24  4981.3  365.55
  5000.3  365.11  5003.1  364.61  5006.3  365.11    5013  371.92  5025.3   373.8
  5145.8  371.85  5195.4  373.87  5239.1   372.8  5293.9   372.5  5466.3  372.44
  5488.1  372.78    5568  372.15  5590.3  373.56  5694.5   374.2  5756.3  375.61
    5866  380.82  6062.5  387.17  6216.3  395.69  6247.5  398.75  6379.1  404.07
#Mann= 11 ,-1 , 0
  4035.6     .16       0  4792.2     .12       0  5000.3     .07       0
  5006.3     .12       0  5239.1     .16       0  5293.9     .12       0
  5466.3     .16       0  5488.1     .12       0  5694.5     .16       0
  5756.3     .12       0    5866     .16       0
Bank Sta=4959.4,5025.3
XS Rating Curve= 0 ,0
Exp/Cntr=0.3,0.1

Type RM Length L Ch R = 1 ,31169   ,612,612,612
BEGIN DESCRIPTION:
LINN CREEK 54.0
END DESCRIPTION:
XS GIS Cut Line= 3
      3591686.46     10557403.15       3590735.1     10556528.17
      3589755.97     10555986.53
#Sta/Elev= 30
  4047.6  406.24    4281  395.59  4309.4  390.88  4316.2  393.17  4330.3  393.35
  4366.1  389.26  4394.4  388.77  4408.6  390.72  4515.5  391.65  4568.3  391.34
  4666.8  386.33    4698  384.26    4720  384.73  4818.2  377.58  4889.5  372.98
  4957.3  372.95  4967.2  372.77    5000  365.13  5002.7  364.63    5006  365.13
  5023.9  366.81  5038.1  372.71  5190.9  372.07  5672.9  370.49  5677.3  370.68
  5769.3   371.6  5872.1  376.59  6230.4  401.57  6306.4  405.08  6459.1  405.86
#Mann= 13 ,-1 , 0
  4047.6     .16       0  4515.5     .05       0  4568.3     .16       0
  4666.8     .05       0    4698     .16       0  4818.2     .05       0
  4957.3     .12       0    5000     .07       0    5006     .12       0
  5190.9     .05       0  5672.9     .12       0  5677.3     .16       0
  6230.4     .05       0
Bank Sta=4967.2,5038.1
XS Rating Curve= 0 ,0
Exp/Cntr=0.3,0.1

Type RM Length L Ch R = 1 ,30557   ,1271,1271,1271
BEGIN DESCRIPTION:
LINN CREEK 53.0
END DESCRIPTION:
XS GIS Cut Line= 3
       3592130.9     10556562.89      3590644.82     10556153.17
      3590063.08     10555799.97
#Sta/Elev= 30
  3758.4  405.99  3979.1  398.18  4087.4  392.23    4127  391.89  4314.4  383.03
  4388.3  377.99  4541.4  375.75  4745.2  369.99  4871.1  370.96    4963  371.34
  4973.4  360.98  4983.8  361.31  4990.2  356.26  4994.1  358.17  4995.3  358.76
  5004.5  355.95  5011.9  355.94  5014.6  355.44  5017.9  355.94  5024.5  357.78
  5029.7  357.66  5035.6  360.46    5046  371.65  5350.4  368.56  5472.6  370.23
  5699.3  382.75  5813.1  392.62  5867.6  397.34  5884.9  397.74  5980.5  404.83
#Mann= 7 ,-1 , 0
  3758.4     .05       0  4871.1     .12       0  4994.1     .05       0
  5011.9     .03       0  5017.9     .05       0  5813.1     .16       0
  5884.9     .05       0
Bank Sta=4963,5046
XS Rating Curve= 0 ,0
Exp/Cntr=0.3,0.1

Type RM Length L Ch R = 1 ,29286   ,798,798,798
BEGIN DESCRIPTION:
LINN CREEK 51.0
END DESCRIPTION:
XS GIS Cut Line= 3
      3592054.53     10556215.66      3591019.82     10555472.62
      3590228.12     10555382.34
#Sta/Elev= 30
  3386.5  397.57  3609.1  393.14  3902.6  379.44  3938.2  378.83  3952.9  380.96
    3959   379.4  3967.6  382.18  3973.8  379.46  3982.3  381.67  3988.5  379.67
  4003.2  382.76  4032.7  380.68  4038.8  381.84  4053.6  374.44  4074.5  372.45
  4139.5  370.38  4439.1  366.69  4569.3  368.38  4892.1  368.99  4972.6  367.65
  4979.4  361.99  4989.2   354.2  5002.5  352.51  5012.8  356.17    5033   369.8
    5043  371.31  5053.1  375.43  5168.1  383.78  5341.9  397.29  5457.2  397.58
#Mann= 5 ,-1 , 0
  3386.5     .05       0  4074.5     .16       0  4979.4     .07       0
  4989.2     .16       0  5168.1     .05       0
Bank Sta=4972.6,5033
XS Rating Curve= 0 ,0
Exp/Cntr=0.3,0.1

Type RM Length L Ch R = 1 ,28488   ,406,406,406
BEGIN DESCRIPTION:
LINN CREEK 50.0
END DESCRIPTION:
XS GIS Cut Line= 3
      3592346.19     10556139.27      3590929.54     10554792.06
      3589986.52     10555145.69
#Sta/Elev= 30
  3308.1  399.34  3594.9  394.36  3715.4  389.87  3835.6  390.91  4104.2  370.99
  4245.7  367.91    4670  365.11  4953.1  366.18    4960  356.79  4967.3  353.89
  4974.2  351.91  4988.3  353.55  4992.6  351.06  4995.3  350.56  4998.6  351.06
  5009.7  353.13  5023.9  360.32  5052.2  365.98  5059.1  363.27  5066.4  365.79
  5073.3  362.07  5087.4  365.57  5129.9  367.51  5410.8  367.46  5556.7  370.88
  5928.7  381.25  5983.9  380.72  5989.3  383.02  6044.4  385.17  6270.2  390.79
#Mann= 5 ,-1 , 0
  3308.1     .05       0  4104.2     .16       0  4992.6     .07       0
  4998.6     .16       0  5556.7     .05       0
Bank Sta=4953.1,5052.2
XS Rating Curve= 0 ,0
Exp/Cntr=0.3,0.1

Type RM Length L Ch R = 1 ,28082   ,319,319,319
BEGIN DESCRIPTION:
LINN CREEK 49.0
END DESCRIPTION:
XS GIS Cut Line= 3
      3592436.48     10555785.11      3591380.93     10554708.73
      3590839.25     10553389.26
#Sta/Elev= 30
  3597.6  396.88  3832.2     392  4001.9  382.29  4100.9  372.02  4157.5  371.96
  4178.7  374.76  4214.1  369.08  4221.1  371.92  4228.2  368.81  4235.2  371.02
  4256.5  370.47  4291.8   366.1  4327.2  365.44  4581.8  364.87    4603  367.56
  4624.3  364.21  4822.3  363.13  4963.6  365.72  4970.7  361.81  4977.7  361.97
  4984.9  353.64  4998.8  348.68  5020.2  350.28  5027.3  360.97  5034.3  366.21
  5665.7  365.71  5957.6  375.04  6153.2  380.68  6433.6  403.44  6531.5  406.72
#Mann= 6 ,-1 , 0
  3597.6     .05       0  4256.5     .16       0  4977.7     .07       0
  4984.9     .16       0  5957.6     .05       0  6433.6     .16       0
Bank Sta=4963.6,5034.3
XS Rating Curve= 0 ,0
Exp/Cntr=0.3,0.1

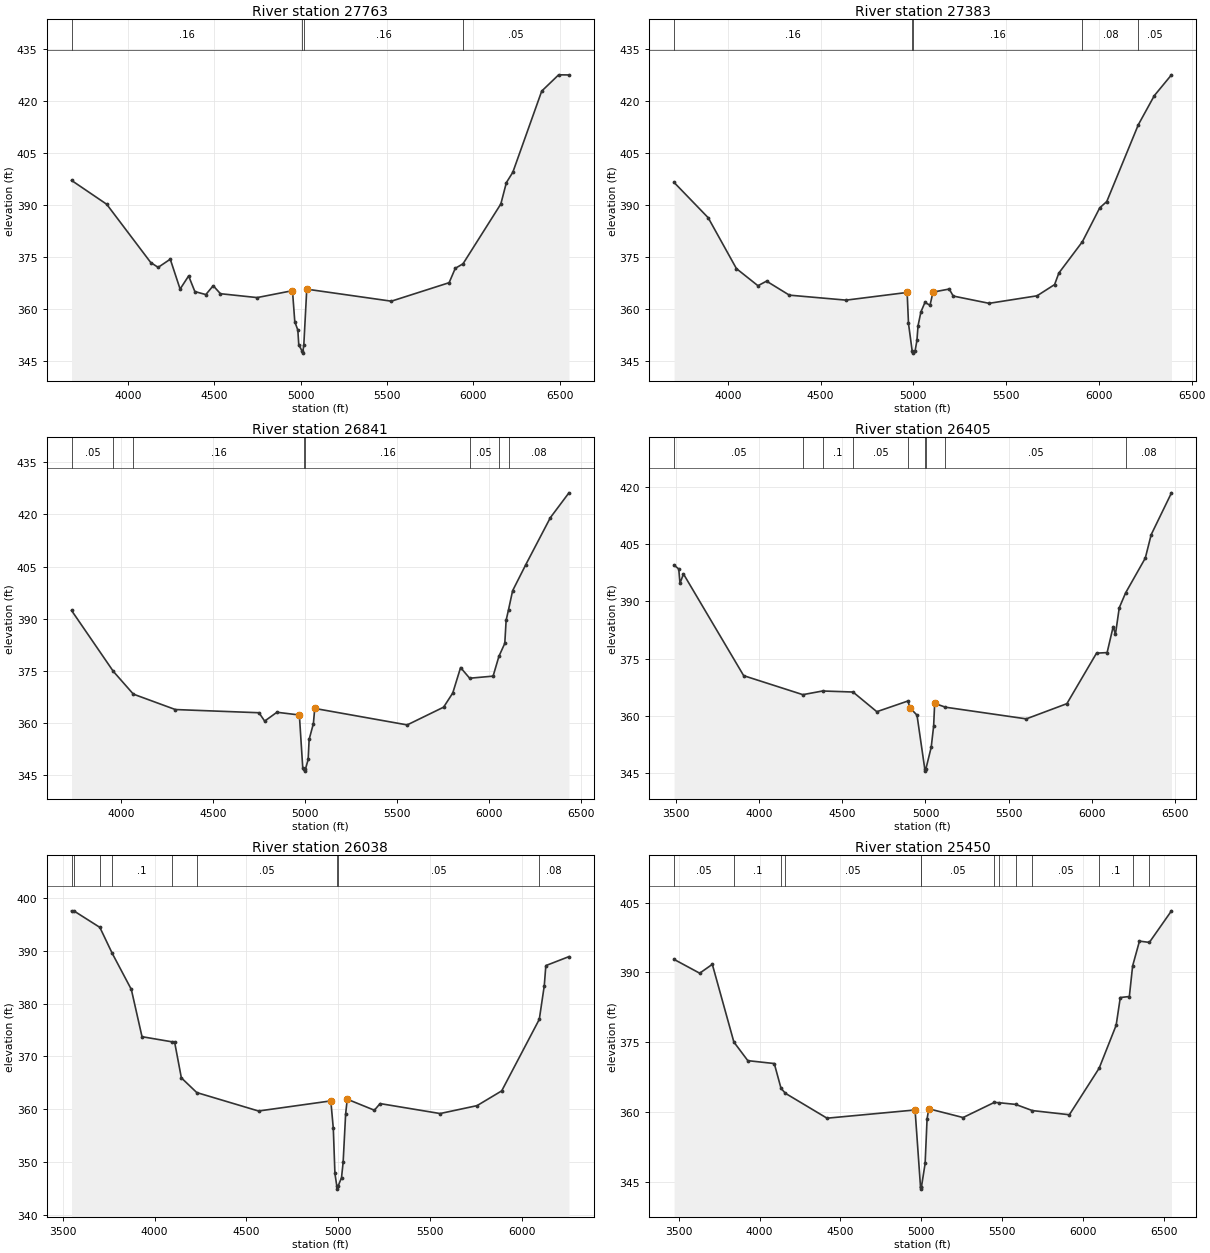
Type RM Length L Ch R = 1 ,27763   ,380,380,380
BEGIN DESCRIPTION:
LINN CREEK 48.0
END DESCRIPTION:
XS GIS Cut Line= 3
      3592576.27     10555701.09      3591795.01     10554800.47
      3591100.57     10553259.69
#Sta/Elev= 30
  3672.1  397.14  3875.8  390.26  4131.2  373.43    4174  372.04  4244.2   374.4
  4301.2  365.78  4350.6  369.57  4386.7  365.06  4450.3  364.19  4493.1  366.75
  4534.8  364.44  4747.5  363.32  4952.4  365.32  4965.8  356.35  4983.4  353.94
  4988.9  349.68    5009  347.79  5011.8  347.29  5018.2  349.78  5035.2  365.75
  5525.3  362.28  5860.2  367.62  5895.7  371.77  5940.6  373.07  6159.8  390.34
  6191.9  396.51  6229.2  399.49  6396.7  422.92  6494.7  427.61  6554.4  427.58
#Mann= 4 ,-1 , 0
  3672.1     .16       0    5009     .07       0  5018.2     .16       0
  5940.6     .05       0
Bank Sta=4952.4,5035.2
XS Rating Curve= 0 ,0
Exp/Cntr=0.3,0.1

Type RM Length L Ch R = 1 ,27383   ,542,542,542
BEGIN DESCRIPTION:
LINN CREEK 47.0
END DESCRIPTION:
XS GIS Cut Line= 3
      3592649.62     10555560.21      3591962.11     10554388.14
      3591328.44     10553227.14
#Sta/Elev= 30
  3709.8  396.47  3893.5   386.3    4046   371.6    4162  366.67  4208.2  367.99
  4331.2  363.95  4637.3  362.51  4966.3  364.73  4973.5  355.78  4993.7  347.72
  4996.4  347.22  5009.2  347.91  5019.1  350.92  5024.9   355.1  5040.6  359.13
  5062.1  361.83  5089.5  361.05  5105.7  364.83    5193  365.71  5214.8  363.69
  5408.1  361.59  5666.6  363.76  5761.2     367    5784  370.32  5910.9  379.36
  6004.4  389.13  6042.4  390.96  6212.5  413.12  6298.7  421.51  6391.3  427.52
#Mann= 5 ,-1 , 0
  3709.8     .16       0  4993.7     .07       0  4996.4     .16       0
  5910.9     .08       0  6212.5     .05       0
Bank Sta=4966.3,5105.7
XS Rating Curve= 0 ,0
Exp/Cntr=0.3,0.1

Type RM Length L Ch R = 1 ,26841   ,436,436,436
BEGIN DESCRIPTION:
LINN CREEK 46.0
END DESCRIPTION:
XS GIS Cut Line= 3
      3592849.61     10555360.18      3592349.61     10554160.19
      3591380.48     10553146.79
#Sta/Elev= 30
    3731  392.38    3958  374.87  4066.8  368.33  4294.9   363.9  4749.3  362.98
  4780.2  360.58  4846.8  363.12  4968.7  362.33  4987.1  347.19  4995.5   346.7
  4998.2   346.2  5001.5   346.7  5016.4  349.56  5021.8  355.31    5045  359.88
  5052.2  364.22  5554.5  359.48  5752.3  364.58    5802  368.65  5844.5  375.96
  5893.8   372.9  6021.2   373.5  6052.7  379.18  6084.7  382.92    6092  389.56
  6105.2  392.64  6127.2  398.05    6198  405.46  6332.3  419.05  6433.2  426.18
#Mann= 8 ,-1 , 0
    3731     .05       0    3958     .08       0  4066.8     .16       0
  4995.5     .07       0  5001.5     .16       0  5893.8     .05       0
  6052.7      .1       0  6105.2     .08       0
Bank Sta=4968.7,5052.2
XS Rating Curve= 0 ,0
Exp/Cntr=0.3,0.1

Type RM Length L Ch R = 1 ,26405   ,367,367,367
BEGIN DESCRIPTION:
LINN CREEK 45.0
END DESCRIPTION:
XS GIS Cut Line= 3
      3593799.61     10555010.19      3592699.61     10554010.19
      3591499.61     10553110.19
#Sta/Elev= 30
  3490.6  399.46  3518.6  398.47  3526.1  394.73    3547  397.16  3908.5  370.53
  4263.8  365.56  4382.5  366.52  4564.9  366.25  4707.9   361.1  4894.8   363.9
  4906.6  362.13  4949.2  360.19  4996.1  346.04  4998.8  345.54  5002.1  346.04
  5034.5   351.8  5049.1  357.35  5055.3  363.28  5119.6  362.28  5605.3  359.22
  5849.1   363.2  6027.2  376.43  6090.7  376.57  6127.2  383.38  6140.7  381.36
  6163.7  388.32  6201.7   392.2  6319.9  401.31  6355.3  407.45  6477.2   418.4
#Mann= 9 ,-1 , 0
  3490.6     .05       0  4263.8     .08       0  4382.5      .1       0
  4564.9     .05       0  4894.8     .12       0  4996.1     .07       0
  5002.1     .12       0  5119.6     .05       0  6201.7     .08       0
Bank Sta=4906.6,5055.3
XS Rating Curve= 0 ,0
Exp/Cntr=0.3,0.1

Type RM Length L Ch R = 1 ,26038   ,588,588,588
BEGIN DESCRIPTION:
LINN CREEK 44.0
END DESCRIPTION:
XS GIS Cut Line= 3
      3594036.74     10554639.86      3592925.65     10553797.87
       3591749.6     10553210.18
#Sta/Elev= 30
  3547.7  397.63  3563.4  397.55  3701.9  394.49  3769.5  389.55  3873.3  382.72
  3931.5  373.75  4092.7  372.79  4108.7  372.79  4145.8  365.94  4229.7  363.15
    4566  359.65  4959.7  361.57  4973.3  356.34  4982.1   347.8  4992.7  345.33
  4995.4  344.83  4998.7  345.33    5018  347.01  5026.8  349.93  5040.4  359.08
  5049.2  361.89    5197   359.8    5228  361.06  5554.8  359.17  5756.1  360.67
  5890.3  363.47  6095.1  377.05  6122.3  383.45  6130.7  387.24  6256.5  388.94
#Mann= 9 ,-1 , 0
  3547.7     .05       0  3563.4     .08       0  3701.9     .05       0
  3769.5      .1       0  4092.7     .08       0  4229.7     .05       0
  4992.7     .03       0  4998.7     .05       0  6095.1     .08       0
Bank Sta=4959.7,5049.2
XS Rating Curve= 0 ,0
Exp/Cntr=0.3,0.1

Type RM Length L Ch R = 1 ,25450   ,183,183,183
BEGIN DESCRIPTION:
LINN CREEK 43.0
END DESCRIPTION:
XS GIS Cut Line= 3
      3594127.81     10554465.22      3593231.97     10553413.12
       3591633.8      10552850.9
#Sta/Elev= 30
  3471.2  392.81  3629.6  389.84  3707.6  391.75    3841  375.04  3927.2  371.04
  4090.8  370.42  4132.6  365.09  4159.7  364.02    4417  358.67  4961.5  360.44
  4995.1  343.92  4997.8  343.42  5001.1  343.92  5023.7  348.95  5035.7   358.5
  5046.3  360.69  5258.4  358.81  5451.3  362.06  5479.6     362    5583  361.64
  5686.4  360.31  5915.6  359.41  6100.1  369.43    6205  378.65  6230.6  384.61
  6286.6  384.83  6306.9  391.41  6349.2  396.74  6410.3  396.46  6547.2  403.25
#Mann= 13 ,-1 , 0
  3471.2     .05       0    3841      .1       0  4132.6     .08       0
  4159.7     .05       0  4995.1     .03       0  5001.1     .05       0
  5451.3      .1       0  5479.6     .15       0    5583      .1       0
  5686.4     .05       0  6100.1      .1       0  6306.9     .08       0
  6410.3     .05       0
Bank Sta=4961.5,5046.3
XS Rating Curve= 0 ,0
Exp/Cntr=0.3,0.1

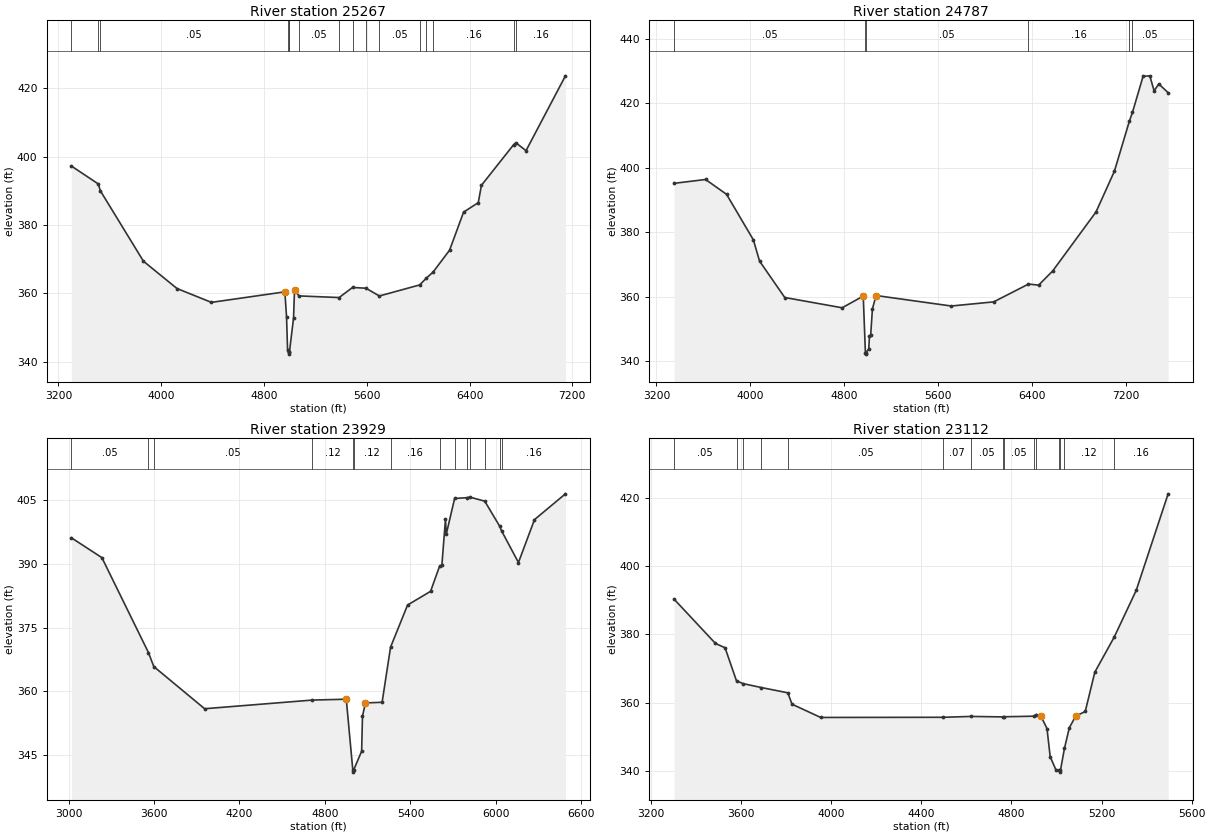
Type RM Length L Ch R = 1 ,25267   ,480,480,480
BEGIN DESCRIPTION:
LINN CREEK 42.0
END DESCRIPTION:
XS GIS Cut Line= 3
      3594679.14     10553823.91      3593229.47     10553233.63
      3591103.63     10552409.32
#Sta/Elev= 30
    3301  397.26  3510.6  392.01  3526.1  390.04  3861.9  369.41  4123.1  361.42
    4391  357.37  4962.6  360.45  4975.6  353.18  4983.9  343.31  4991.8  342.73
  4994.5  342.23  4997.8  342.73  5030.1  352.78  5037.7  360.95  5072.9  359.26
  5384.8  358.78  5489.2  361.73  5593.7  361.51  5698.2  359.24  6011.6  362.47
  6064.5  364.48  6116.1  366.23  6244.6  372.64  6353.6  383.77  6467.9  386.54
  6492.4  391.61  6744.2  403.55  6760.8  404.04  6839.6  401.75  7146.3  423.64
#Mann= 16 ,-1 , 0
    3301     .05       0  3510.6     .16       0  3526.1     .05       0
  4983.9     .12       0  4991.8     .07       0  4997.8     .12       0
  5072.9     .05       0  5384.8      .1       0  5489.2     .15       0
  5593.7      .1       0  5698.2     .05       0  6011.6     .08       0
  6064.5     .05       0  6116.1     .16       0  6744.2     .05       0
  6760.8     .16       0
Bank Sta=4962.6,5037.7
XS Rating Curve= 0 ,0
Exp/Cntr=0.3,0.1

Type RM Length L Ch R = 1 ,24787   ,858,858,858
BEGIN DESCRIPTION:
LINN CREEK 41.0
END DESCRIPTION:
XS GIS Cut Line= 3
      3595008.95     10553719.72      3593776.34     10553094.74
      3591104.54     10552175.22
#Sta/Elev= 30
  3349.9  395.16  3618.2  396.36  3797.1  391.75  4025.4  377.61  4077.9  371.03
  4292.6  359.72  4781.3  356.53  4961.1  360.16  4979.3  342.64    4982  342.14
  4985.3  342.64  5007.9  343.76    5014  347.71  5024.6  348.11  5039.1  356.19
  5070.3  360.33  5710.3  357.08  6071.6  358.36  6368.3  363.89  6454.5  363.56
  6574.1  367.95  6943.5  386.29  7099.7   398.9  7227.4  414.46  7253.7  417.18
  7344.2   428.4  7401.4  428.54  7437.9  423.89  7478.1  426.01  7557.5  423.31
#Mann= 6 ,-1 , 0
  3349.9     .05       0  4979.3     .03       0  4985.3     .05       0
  6368.3     .16       0  7227.4      .1       0  7253.7     .05       0
Bank Sta=4961.1,5070.3
XS Rating Curve= 0 ,0
Exp/Cntr=0.3,0.1

Type RM Length L Ch R = 1 ,23929   ,817,817,817
BEGIN DESCRIPTION:
LINN CREEK 40.0
END DESCRIPTION:
XS GIS Cut Line= 3
       3594956.9     10553511.41      3593057.59     10552223.21
      3592661.77     10551119.07
#Sta/Elev= 30
    3020  396.14  3234.2  391.46    3561  369.11  3598.5  365.81  3955.3  355.88
  4711.6  357.92  4949.6  358.12  4995.4  341.45  4998.1  340.95  5001.4  341.45
  5057.4  345.87  5063.4  354.16  5084.4  357.24  5201.1   357.4  5260.5  370.39
  5379.8   380.3  5541.3  383.53  5604.3  389.43  5620.5  389.63    5646  400.54
  5651.3  396.96    5710   405.4  5796.7  405.58  5815.7  405.72  5921.4  404.77
  6027.1  398.82  6039.2   397.8  6158.1  390.31  6270.5  400.41  6487.9  406.49
#Mann= 14 ,-1 , 0
    3020     .05       0    3561      .1       0  3598.5     .05       0
  4711.6     .12       0  4995.4     .07       0  5001.4     .12       0
  5260.5     .16       0  5604.3      .1       0    5710     .15       0
  5796.7      .1       0  5815.7     .15       0  5921.4      .1       0
  6027.1     .08       0  6039.2     .16       0
Bank Sta=4949.6,5084.4
XS Rating Curve= 0 ,0
Exp/Cntr=0.3,0.1

Type RM Length L Ch R = 1 ,23112   ,546,546,546
BEGIN DESCRIPTION:
LINN CREEK 39.0
END DESCRIPTION:
XS GIS Cut Line= 3
      3594799.58     10553310.16      3593599.61     10552110.19
       3593249.6     10551760.18
#Sta/Elev= 30
  3303.6  390.32  3487.4  377.35  3529.8   376.1  3580.7  366.39    3610  365.61
  3689.9  364.47  3808.4  362.92  3826.8  359.59  3954.1  355.71  4497.3  355.76
  4620.7  356.01  4765.1  355.87  4766.5  355.91    4901  356.08  4909.5  356.56
  4929.9  356.27  4958.2  352.46  4972.3  344.23  4997.1  340.48  5011.8  340.22
  5014.5  339.72  5017.8  340.22  5035.6  346.65  5057.2   352.7  5085.5  356.09
  5127.9  357.46  5170.3  368.95  5256.4  379.22  5354.2  392.91  5495.6  421.12
#Mann= 15 ,-1 , 0
  3303.6     .05       0  3580.7      .1       0    3610     .15       0
  3689.9      .1       0  3808.4     .05       0  4497.3     .07       0
  4620.7     .05       0  4765.1     .07       0  4766.5     .05       0
    4901     .07       0  4909.5     .16       0  5011.8     .07       0
  5017.8     .16       0  5035.6     .12       0  5256.4     .16       0
Bank Sta=4929.9,5085.5
XS Rating Curve= 0 ,0
Exp/Cntr=0.3,0.1