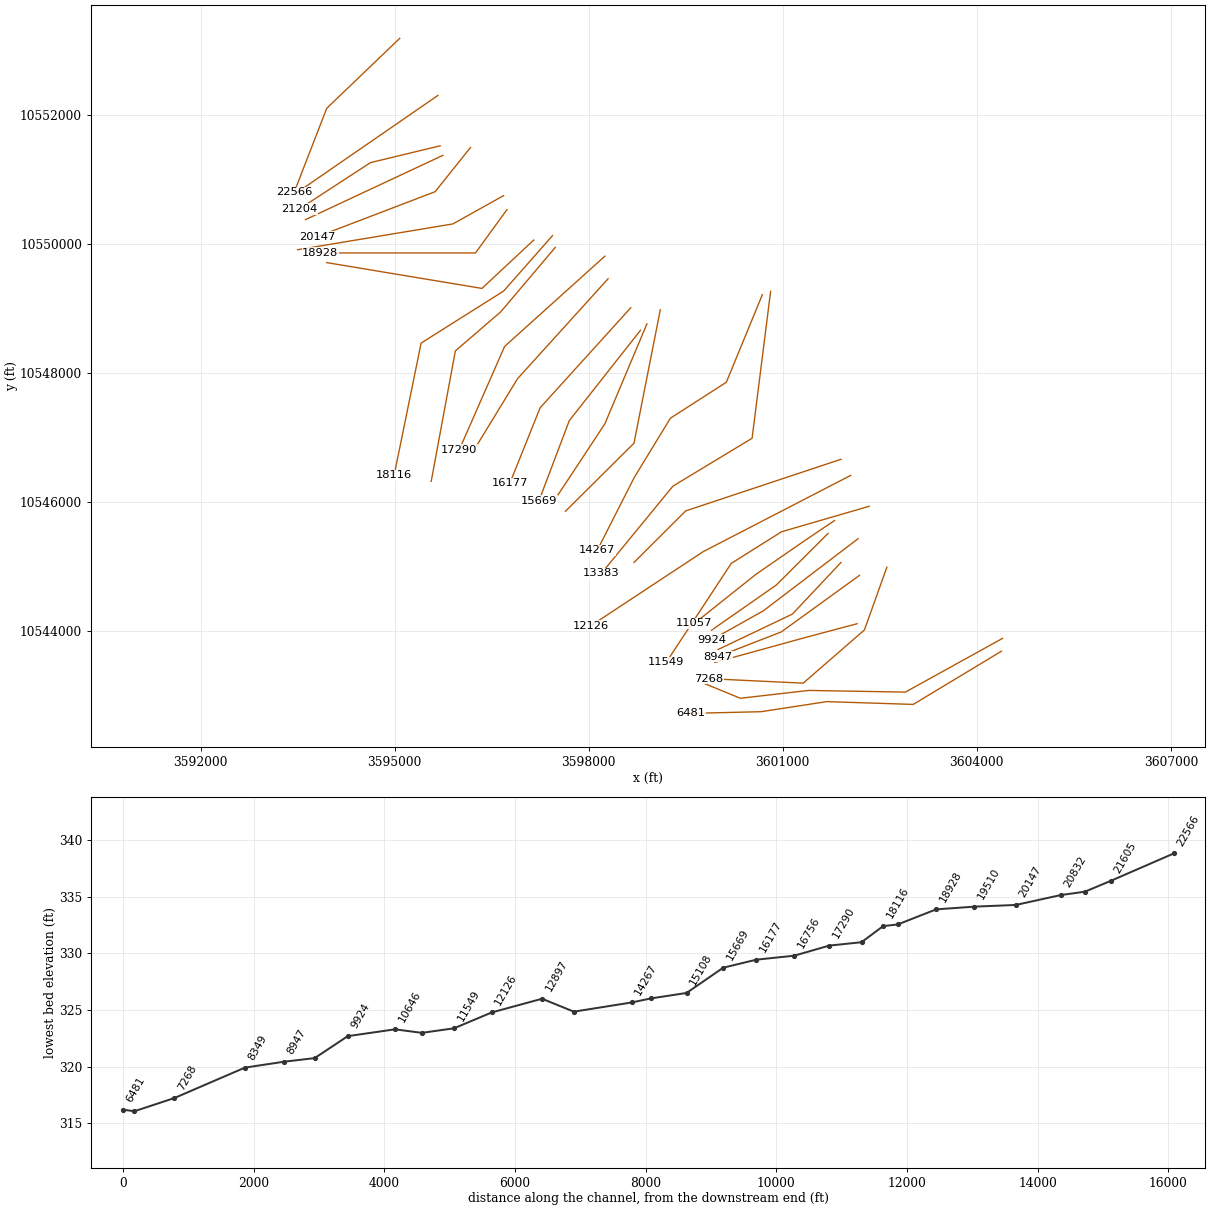
HEC-RAS study LINN CREEK.prj: LINN CREEK Base Level Engineering

--- LINN CREEK.g01 (geometry) --- (continued)

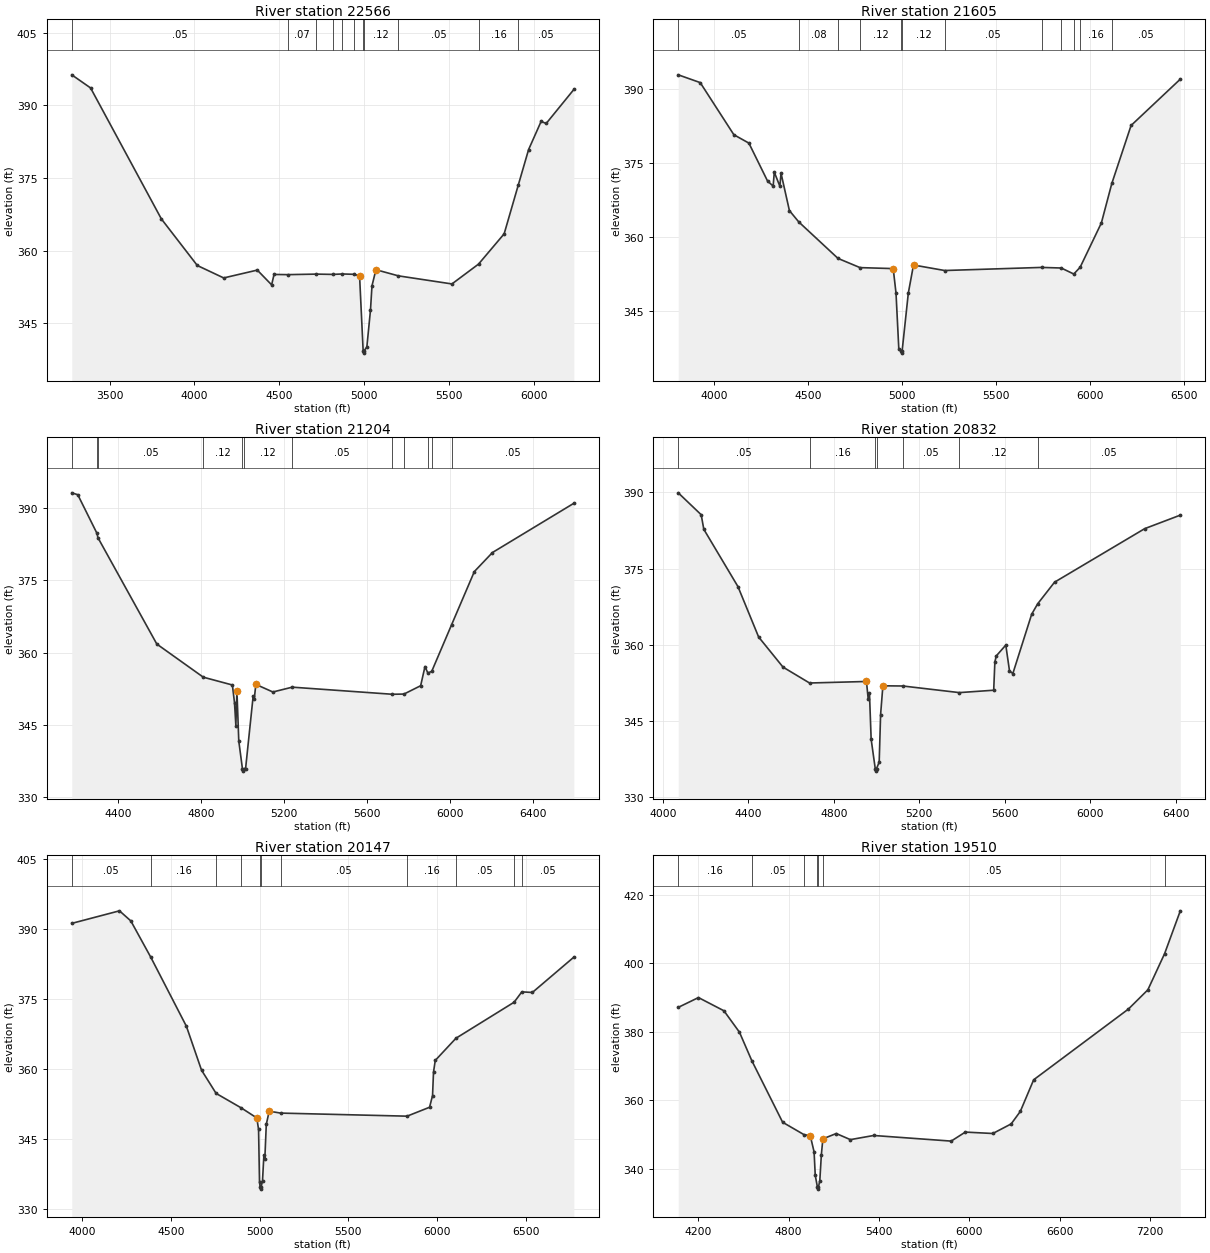
Type RM Length L Ch R = 1 ,22566   ,961,961,961
BEGIN DESCRIPTION:
LINN CREEK 38.0
END DESCRIPTION:
XS GIS Cut Line= 3
       3595078.4     10553188.46      3593949.96     10552103.42
      3593446.48     10550801.34
#Sta/Elev= 30
  3276.3  396.31  3387.3   393.6  3804.6  366.56  4016.8  356.93  4172.5  354.36
  4370.6  355.98  4455.2  352.93  4469.4  355.08  4550.9  355.04  4717.8  355.15
  4815.4  355.09  4872.3  355.18  4940.8  355.11  4973.9  354.79    4995  339.33
  4997.7  338.83    5001  339.33  5016.8  340.08  5038.2   347.7  5047.1  352.73
  5070.4  356.06  5202.8  354.79  5518.7  353.12  5675.7  357.22  5826.7  363.47
  5910.7  373.62    5971  380.88  6044.8  386.69  6074.7  386.26  6237.8  393.28
#Mann= 11 ,-1 , 0
  3276.3     .05       0  4550.9     .07       0  4717.8     .05       0
  4815.4     .12       0  4872.3     .07       0  4940.8     .12       0
    4995     .07       0    5001     .12       0  5202.8     .05       0
  5675.7     .16       0  5910.7     .05       0
Bank Sta=4973.9,5070.4
XS Rating Curve= 0 ,0
Exp/Cntr=0.3,0.1

Type RM Length L Ch R = 1 ,21605   ,401,401,401
BEGIN DESCRIPTION:
LINN CREEK 37.0
END DESCRIPTION:
XS GIS Cut Line= 2
       3595668.7     10552303.07      3593472.49     10550783.95
#Sta/Elev= 30
  3809.1  392.95    3926  391.37    4105  380.78  4184.9  379.08  4284.1  371.38
  4313.9  370.35    4320  373.17  4349.7  370.32  4355.8  372.97  4400.4  365.37
  4450.4  363.06  4658.9  355.66    4776  353.79  4952.5  353.59  4967.4  348.61
  4982.2  337.34  4994.1  336.92  4996.9  336.42  5000.1  336.92  5032.9  348.63
  5060.4  354.32  5226.4   353.2  5741.2  353.83  5846.2  353.71  5912.9  352.49
  5946.7  353.86  6059.5  362.85  6115.2  370.88  6217.6  382.66  6479.5  392.07
#Mann= 12 ,-1 , 0
  3809.1     .05       0  4450.4     .08       0  4658.9     .05       0
    4776     .12       0  4994.1     .07       0  5000.1     .12       0
  5226.4     .05       0  5741.2      .1       0  5846.2     .15       0
  5912.9     .07       0  5946.7     .16       0  6115.2     .05       0
Bank Sta=4952.5,5060.4
XS Rating Curve= 0 ,0
Exp/Cntr=0.3,0.1

Type RM Length L Ch R = 1 ,21204   ,372,372,372
BEGIN DESCRIPTION:
LINN CREEK 36.0
END DESCRIPTION:
XS GIS Cut Line= 3
      3595703.47     10551521.83      3594627.04     10551261.41
      3593524.58     10550540.91
#Sta/Elev= 30
  4174.4  393.16  4203.4  392.77  4296.4  384.73  4300.7  383.86  4585.1   361.8
  4809.5  354.93    4950  353.31  4960.3  349.62  4966.8   344.9  4971.9  352.08
  4980.9  341.68  4998.5  335.95  5001.2  335.45  5004.5  335.95  5013.8  335.99
  5050.5  351.08  5055.6  350.34  5063.2  353.44  5145.5  351.86  5239.1  352.86
  5721.8  351.39  5778.6  351.43  5859.1  353.16  5880.1  357.14  5893.8   355.8
  5912.5  356.13    6009  365.85  6118.4  376.83  6205.9  380.78  6598.9  390.99
#Mann= 12 ,-1 , 0
  4174.4     .05       0  4296.4     .16       0  4300.7     .05       0
  4809.5     .12       0  4998.5     .07       0  5004.5     .12       0
  5239.1     .05       0  5721.8     .16       0  5778.6     .12       0
  5893.8     .07       0  5912.5     .16       0    6009     .05       0
Bank Sta=4971.9,5063.2
XS Rating Curve= 0 ,0
Exp/Cntr=0.3,0.1

Type RM Length L Ch R = 1 ,20832   ,685,685,685
BEGIN DESCRIPTION:
LINN CREEK 35.0
END DESCRIPTION:
XS GIS Cut Line= 2
      3595746.81     10551374.24      3593620.13     10550376.01
#Sta/Elev= 30
  4071.7  389.91  4179.1   385.6  4191.4  382.73  4351.1  371.46  4447.9  361.54
  4561.9  355.62  4686.1  352.49  4952.4  352.79  4960.8  349.26  4966.4  350.57
  4974.4  341.42  4993.5  335.65  4996.3  335.15  4999.5  335.65    5012  336.92
  5018.6  346.28  5029.3  351.94  5122.9   351.9    5387   350.6  5547.8  351.07
  5553.3  356.64  5559.9  357.82  5604.4  359.95  5621.7   354.9  5637.3  354.34
  5725.6  366.03  5753.7  368.08  5832.6  372.33  6254.3  382.86    6421  385.52
#Mann= 7 ,-1 , 0
  4071.7     .05       0  4686.1     .16       0  4993.5     .07       0
  4999.5     .16       0  5122.9     .05       0    5387     .12       0
  5753.7     .05       0
Bank Sta=4952.4,5029.3
XS Rating Curve= 0 ,0
Exp/Cntr=0.3,0.1

Type RM Length L Ch R = 1 ,20147   ,637,637,637
BEGIN DESCRIPTION:
LINN CREEK 34.0
END DESCRIPTION:
XS GIS Cut Line= 3
      3596172.19      10551495.8       3595625.3     10550810.02
      3593799.58     10550110.18
#Sta/Elev= 30
  3940.1  391.25  4209.2  393.94  4273.2  391.78  4386.2  383.97  4586.8  369.19
    4672  359.79  4754.4   354.8  4896.3  351.69    4984  349.54  4993.9  347.07
  4999.2  335.88  5002.4  334.78  5005.1  334.28  5008.4  334.78  5016.1  336.02
  5023.9  341.56  5029.2  340.73  5037.5  348.16  5053.9  350.99  5118.2  350.58
  5831.7  349.92  5958.5  351.83  5975.4  354.34  5980.8  359.37  5990.7  361.87
  6107.6  366.63  6435.6  374.35  6479.1  376.57  6538.6  376.44  6772.5  384.01
#Mann= 11 ,-1 , 0
  3940.1     .05       0  4386.2     .16       0  4754.4     .05       0
  4896.3     .12       0  5002.4     .07       0  5008.4     .12       0
  5118.2     .05       0  5831.7     .16       0  6107.6     .05       0
  6435.6     .08       0  6479.1     .05       0
Bank Sta=4984,5053.9
XS Rating Curve= 0 ,0
Exp/Cntr=0.3,0.1

Type RM Length L Ch R = 1 ,19510   ,582,582,582
BEGIN DESCRIPTION:
LINN CREEK 33.0
END DESCRIPTION:
XS GIS Cut Line= 3
      3596684.31     10550749.24      3595899.61     10550310.19
      3593499.59     10549910.19
#Sta/Elev= 30
  4067.6  387.12  4201.8  389.98  4370.9  386.13    4474  379.88  4556.2  371.55
  4760.5  353.63  4902.1  350.02  4943.9   349.7  4969.3  344.98  4976.9  338.17
  4991.7  334.63  4994.4  334.13  4997.7  334.63  5007.3  336.61  5017.5  344.19
  5027.2  348.61  5027.6  348.79  5116.3  350.34  5210.1  348.56  5364.7  349.77
  5879.2  348.13    5973  350.76  6155.5  350.35  6277.1  353.14  6337.9  356.78
  6426.6  366.01  7055.2  386.62  7184.5  392.24  7295.7  402.79  7399.9  415.27
#Mann= 7 ,-1 , 0
  4067.6     .16       0  4556.2     .05       0  4902.1     .16       0
  4991.7     .07       0  4997.7     .16       0  5027.2     .05       0
  7295.7     .16       0
Bank Sta=4943.9,5027.6
XS Rating Curve= 0 ,0
Exp/Cntr=0.3,0.1

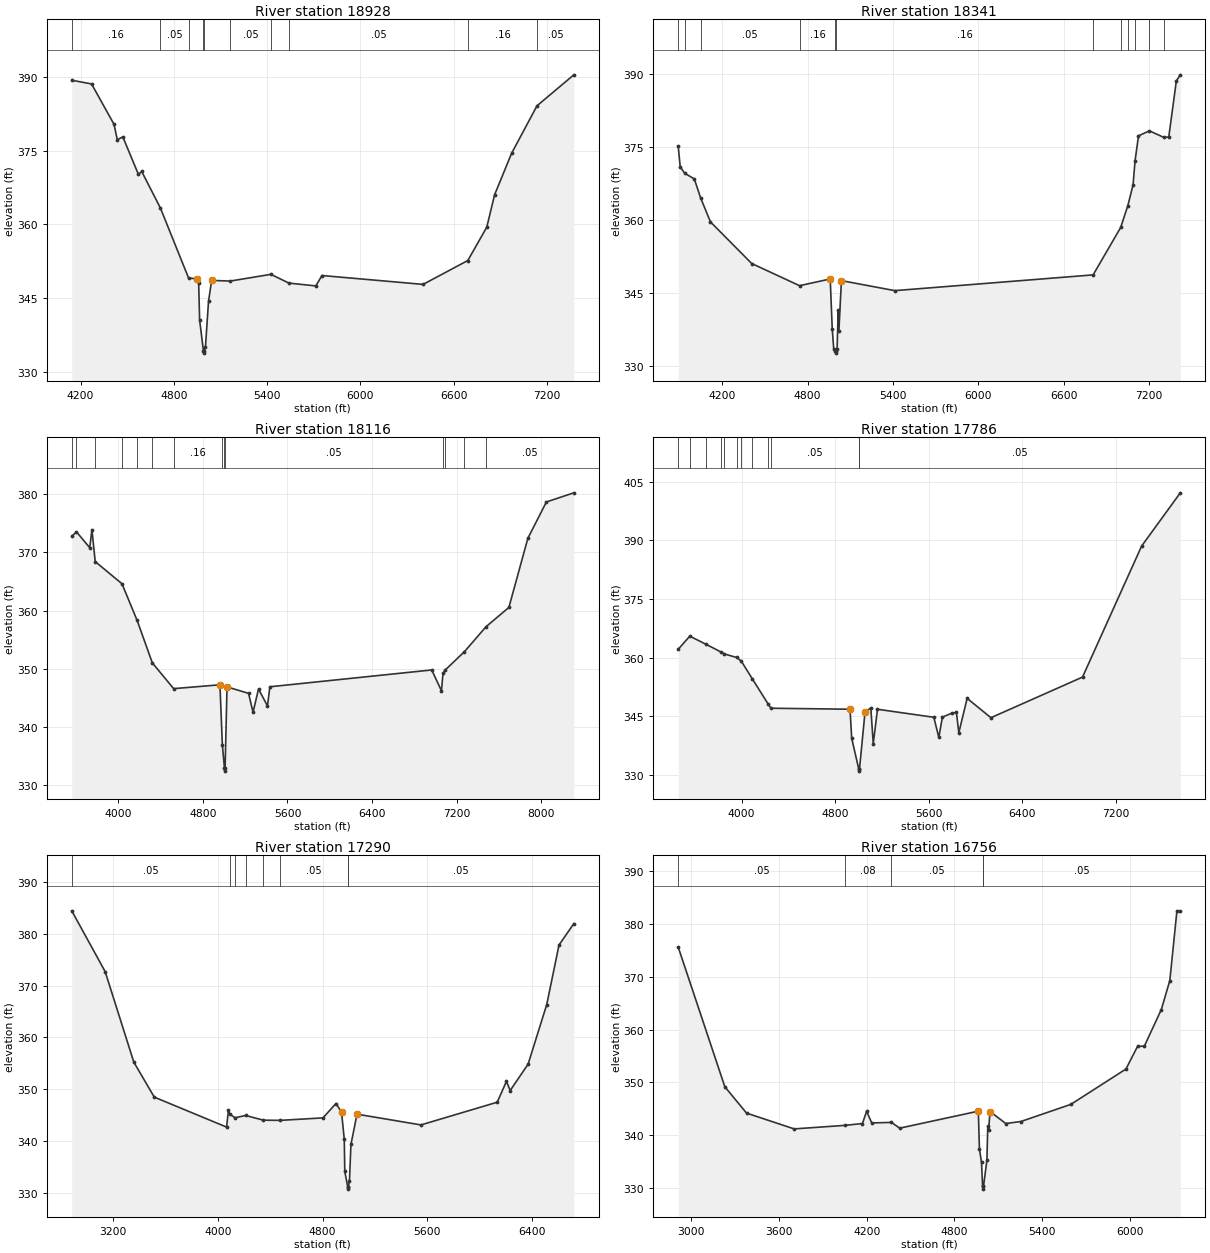
Type RM Length L Ch R = 1 ,18928   ,587,587,587
BEGIN DESCRIPTION:
LINN CREEK 32.0
END DESCRIPTION:
XS GIS Cut Line= 3
      3596736.42     10550532.25      3596249.61     10549860.19
      3593849.66     10549860.19
#Sta/Elev= 30
  4143.4  389.27  4270.7  388.52  4415.3  380.32  4436.2   377.2  4471.8  377.78
  4572.3  370.15  4593.2  370.76  4713.6  363.34  4895.1  349.11  4951.2     349
  4959.7  348.16  4965.9  340.58  4990.2  334.39    4993  333.89  4996.2  334.39
  5003.2  335.05  5023.2  344.42  5043.2  348.64  5163.8  348.52  5424.3  349.88
  5540.3   348.1  5713.2  347.53  5753.2  349.64  6403.2  347.84  6691.1  352.68
  6813.2  359.46  6863.2  366.01  6973.2  374.47  7136.3  384.09  7373.2  390.37
#Mann= 10 ,-1 , 0
  4143.4     .16       0  4713.6     .05       0  4895.1     .16       0
  4990.2     .07       0  4996.2     .16       0  5163.8     .05       0
  5424.3     .08       0  5540.3     .05       0  6691.1     .16       0
  7136.3     .05       0
Bank Sta=4951.2,5043.2
XS Rating Curve= 0 ,0
Exp/Cntr=0.3,0.1

Type RM Length L Ch R = 1 ,18341   ,225,225,225
BEGIN DESCRIPTION:
LINN CREEK 31.0
END DESCRIPTION:
XS GIS Cut Line= 3
      3597149.59     10550060.17      3596349.61     10549310.19
      3593949.57     10549710.19
#Sta/Elev= 30
  3890.2  375.06  3904.1  370.88  3935.3  369.56  4003.3  368.38  4047.7  364.47
  4116.6  359.55  4406.7  350.99  4743.1  346.43  4958.7  347.81  4972.8  337.59
  4983.3  333.41  4993.9  333.06  4996.6  332.56  4999.9  333.06    5007  333.33
  5014.6  341.33  5019.7  337.18  5037.4  347.47  5412.6  345.41  6806.9  348.65
  7000.8  358.41  7050.9  362.88  7087.8  367.16  7101.7  372.08  7125.9  377.24
  7202.6  378.27  7303.5  376.93  7338.8     377    7392  388.54  7419.9  389.79
#Mann= 12 ,-1 , 0
  3890.2      .1       0  3935.3     .08       0  4047.7     .05       0
  4743.1     .16       0  4993.9     .03       0  4999.9     .16       0
  6806.9     .16       0  7000.8     .08       0  7050.9     .16       0
  7101.7     .08       0  7202.6      .1       0  7303.5     .16       0
Bank Sta=4958.7,5037.4
XS Rating Curve= 0 ,0
Exp/Cntr=0.3,0.1

Type RM Length L Ch R = 1 ,18116   ,330,330,330
BEGIN DESCRIPTION:
LINN CREEK 30.0
END DESCRIPTION:
XS GIS Cut Line= 4
      3597439.87     10550128.85      3596684.69     10549269.51
      3595408.65     10548462.22      3594992.15     10546414.43
#Sta/Elev= 30
  3562.3  372.77  3606.4  373.55  3731.9  370.82  3752.8  373.91  3783.7  368.43
  4036.6  364.62    4180  358.31  4323.4  351.02  4524.9  346.59  4962.1  347.25
  4985.2  336.94    5005  332.91  5007.7  332.41    5011  332.91  5029.1  346.89
  5232.6  345.78    5275  342.52  5326.7  346.52  5411.4  343.62  5434.2  346.91
  6963.3   349.8  7055.1  346.22  7069.9  349.25  7092.1  349.82  7271.7  352.93
  7477.3  357.25  7692.3  360.55  7871.5  372.43  8046.5  378.68    8306  380.25
#Mann= 14 ,-1 , 0
  3562.3     .08       0  3606.4      .1       0  3783.7     .08       0
  4036.6     .05       0    4180     .08       0  4323.4     .05       0
  4524.9     .16       0  4985.2     .05       0    5005     .03       0
    5011     .05       0  7069.9     .16       0  7092.1     .05       0
  7271.7     .16       0  7477.3     .05       0
Bank Sta=4962.1,5029.1
XS Rating Curve= 0 ,0
Exp/Cntr=0.3,0.1

Type RM Length L Ch R = 1 ,17786   ,496,496,496
BEGIN DESCRIPTION:
Mapping XS 0761c7bc
END DESCRIPTION:
XS GIS Cut Line= 4
      3597483.31      10549946.6      3596641.29     10548948.33
      3595938.16     10548340.69       3595564.9     10546318.12
#Sta/Elev= 30
  3457.8  362.13  3556.6  365.48  3691.6  363.46  3824.3  361.42  3849.7  360.96
    3957  360.03  3996.3  359.12  4089.7  354.64  4226.7  348.12  4250.2  347.06
  4926.4  346.81  4940.6   339.4  5001.2  331.49    5004  330.99  5007.2  331.49
  5054.6  346.12    5104  347.13  5124.9  338.01    5161   346.8  5642.6  344.75
  5685.4  339.61  5715.8  344.79  5795.3  345.79  5835.9     346  5856.3  340.79
  5927.5  349.59  6130.8  344.64  6913.8  355.02    7419   388.5  7749.8  402.11
#Mann= 12 ,-1 , 0
  3457.8     .05       0  3556.6     .08       0  3691.6     .05       0
  3824.3     .12       0  3849.7     .08       0    3957     .05       0
  3996.3     .08       0  4089.7     .05       0  4226.7     .16       0
  4250.2     .05       0  5001.2     .03       0  5007.2     .05       0
Bank Sta=4926.4,5054.6
XS Rating Curve= 0 ,0
Exp/Cntr=0.3,0.1

Type RM Length L Ch R = 1 ,17290   ,534,534,534
BEGIN DESCRIPTION:
LINN CREEK 29.0
END DESCRIPTION:
XS GIS Cut Line= 3
      3598249.64     10549810.22      3596699.61     10548410.19
      3595999.62     10546810.21
#Sta/Elev= 30
  2884.8  384.48    3140  372.72    3359  355.22  3515.2  348.47  4067.4  342.68
  4081.6  345.99  4090.6   345.2  4132.7  344.48  4212.6  344.93    4348  344.02
  4476.7  343.98  4803.5  344.46  4902.9  347.24  4945.5  345.56  4966.4  340.32
  4970.1  334.11  4992.3  331.19  4995.1  330.69  4998.3  331.19  5005.9  332.25
  5017.2  339.32  5063.6  345.18    5552   343.1  6134.8  347.49    6205  351.52
  6233.8  349.75  6370.6  354.85  6512.9  366.37  6606.5  377.87  6719.9  382.02
#Mann= 8 ,-1 , 0
  2884.8     .05       0  4090.6      .1       0  4132.7     .15       0
  4212.6      .1       0    4348     .08       0  4476.7     .05       0
  4992.3     .03       0  4998.3     .05       0
Bank Sta=4945.5,5063.6
XS Rating Curve= 0 ,0
Exp/Cntr=0.3,0.1

Type RM Length L Ch R = 1 ,16756   ,579,579,579
BEGIN DESCRIPTION:
LINN CREEK 28.0
END DESCRIPTION:
XS GIS Cut Line= 3
      3598299.59     10549460.16      3596899.61     10547910.19
      3596199.62      10546760.2
#Sta/Elev= 30
  2910.8   375.6  3229.5  349.18  3378.2  344.19    3704   341.2  4051.8  341.87
  4171.1  342.22  4199.5  344.53  4234.6  342.33  4369.8  342.43  4425.9  341.34
  4963.9  344.56  4971.4  337.39  4985.6  334.86  4993.1   330.3  4995.8   329.8
  4999.1   330.3  5022.6  335.27  5028.5  341.76  5034.5  341.08    5044  344.49
  5151.6  342.22  5255.1   342.6  5596.5  345.84  5973.8  352.53  6053.3  356.83
  6099.7  356.87  6215.9   363.8    6274  369.29  6322.5  382.48  6345.7   382.4
#Mann= 5 ,-1 , 0
  2910.8     .05       0  4051.8     .08       0  4369.8     .05       0
  4993.1     .03       0  4999.1     .05       0
Bank Sta=4963.9,5044
XS Rating Curve= 0 ,0
Exp/Cntr=0.3,0.1

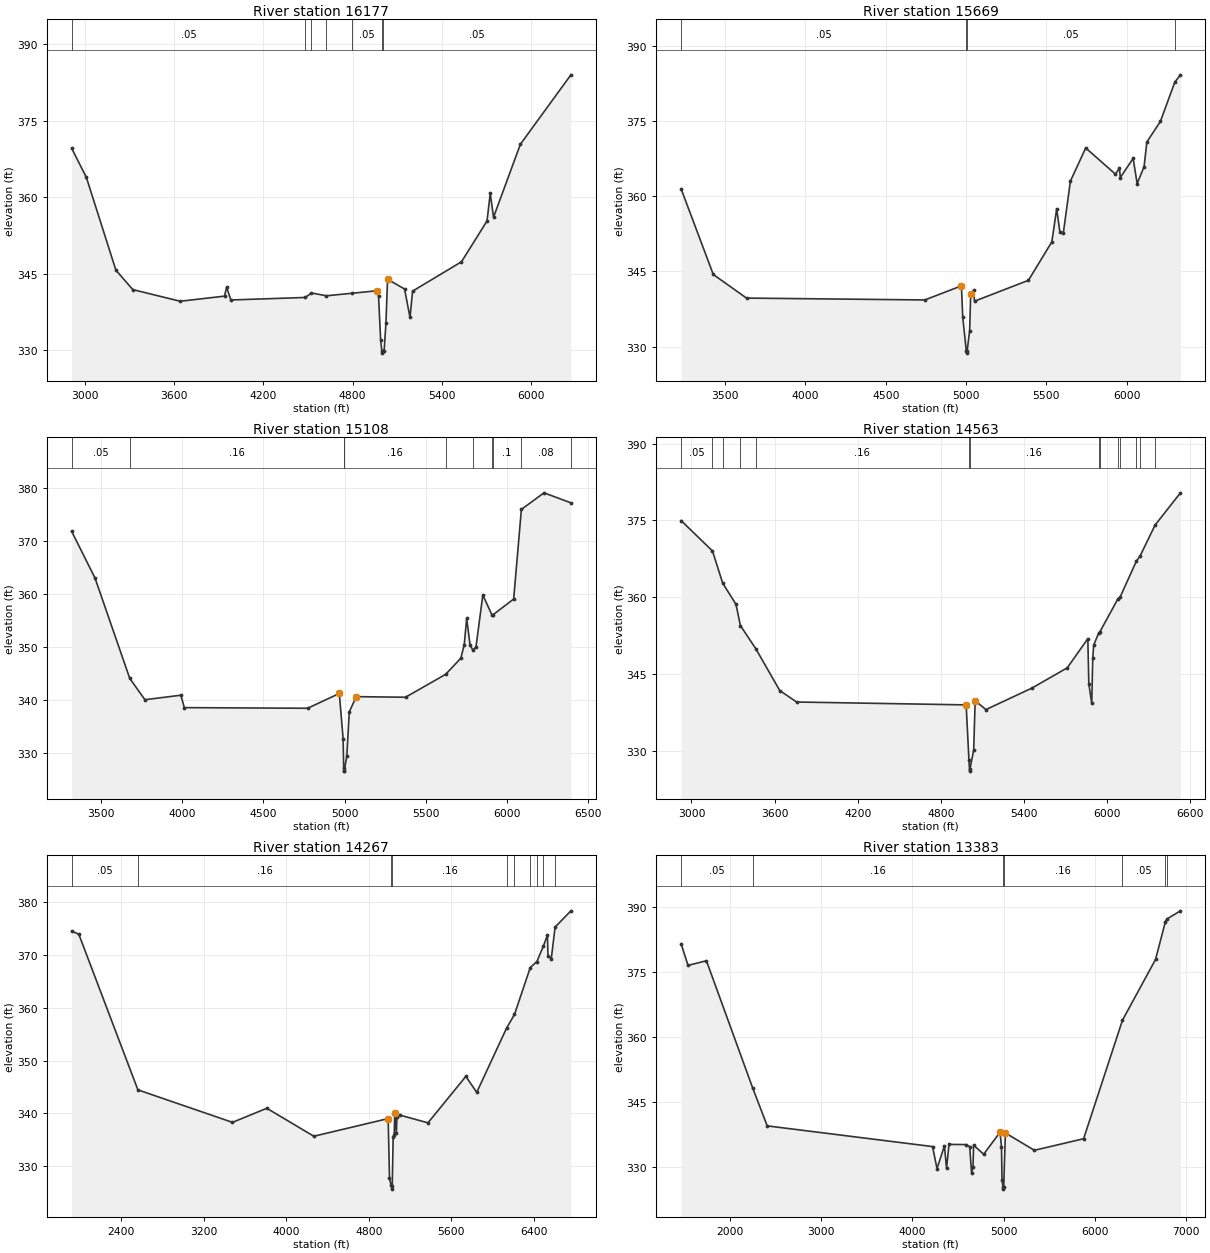
Type RM Length L Ch R = 1 ,16177   ,508,508,508
BEGIN DESCRIPTION:
LINN CREEK 27.0
END DESCRIPTION:
XS GIS Cut Line= 3
       3598649.6     10549010.17      3597249.61     10547460.19
      3596779.81     10546287.43
#Sta/Elev= 30
  2913.4  369.57  3012.4  363.86  3210.4  345.71    3324  341.89  3642.4  339.61
  3939.8  340.61    3954  342.35  3982.4  339.86  4482.4  340.35  4523.6  341.23
  4623.8  340.68  4797.7  341.18  4966.5  341.67    4974  340.61  4988.2  331.98
  4995.7  329.95  4998.4  329.45  5001.7  329.95  5011.5  329.96  5023.6  335.29
  5034.4  343.91  5148.7  342.01  5185.2  336.43  5202.5  341.59  5530.9  347.34
  5702.3  355.33  5723.8  360.72  5746.1  356.08  5926.4  370.36  6265.4  383.95
#Mann= 7 ,-1 , 0
  2913.4     .05       0  4482.4     .08       0  4523.6     .05       0
  4623.8     .08       0  4797.7     .05       0  4995.7     .03       0
  5001.7     .05       0
Bank Sta=4966.5,5034.4
XS Rating Curve= 0 ,0
Exp/Cntr=0.3,0.1

Type RM Length L Ch R = 1 ,15669   ,561,561,561
BEGIN DESCRIPTION:
LINN CREEK 26.0
END DESCRIPTION:
XS GIS Cut Line= 3
      3598799.63     10548660.22      3597699.61     10547260.19
      3597231.22     10546018.38
#Sta/Elev= 30
  3226.5  361.41  3426.3   344.4  3633.2   339.7  4743.1  339.33  4970.9  342.14
    4979  335.96  5000.8  329.24  5003.6  328.74  5006.8  329.24  5022.1  333.24
  5028.4  340.45  5046.9  341.26  5052.3  339.08    5388  343.24  5533.6  350.89
  5563.8  357.49  5583.3  352.95  5605.5  352.73  5649.1  362.98  5744.4   369.6
  5929.7  364.38  5954.5  365.58  5959.9  363.71  6039.8  367.52  6064.6  362.51
  6107.8  365.86    6125  370.77  6209.4  374.88  6299.1  382.71  6334.2  384.16
#Mann= 4 ,-1 , 0
  3226.5     .05       0  5000.8     .03       0  5006.8     .05       0
  6299.1      .1       0
Bank Sta=4970.9,5028.4
XS Rating Curve= 0 ,0
Exp/Cntr=0.3,0.1

Type RM Length L Ch R = 1 ,15108   ,545,545,545
BEGIN DESCRIPTION:
LINN CREEK 25.0
END DESCRIPTION:
XS GIS Cut Line= 3
      3598899.61     10548760.19      3598249.61     10547210.19
      3597484.03     10546046.05
#Sta/Elev= 30
    3319  371.75  3463.3  362.91  3676.8  344.01  3770.3  339.98  3991.3  340.83
    4013  338.49  4772.1  338.37  4967.2  341.16  4990.6  332.66  4994.1  327.01
  4996.8  326.51  4997.3  326.51  5013.3  329.35  5028.4  337.68  5071.6  340.56
  5374.8  340.45  5621.9  344.77  5715.3  347.81  5736.4  350.36  5751.4  355.35
  5772.5  350.23  5790.5  349.32  5808.7  349.94  5850.8  359.72  5906.4  356.02
    5911  355.95  6040.7  358.97  6088.2  375.88  6227.4  379.01  6393.1  377.12
#Mann= 10 ,-1 , 0
    3319     .05       0  3676.8     .16       0  4994.1     .07       0
  4997.3     .16       0  5621.9     .05       0  5790.5      .1       0
  5906.4     .08       0    5911      .1       0  6088.2     .08       0
  6393.1     .05       0
Bank Sta=4967.2,5071.6
XS Rating Curve= 0 ,0
Exp/Cntr=0.3,0.1

Type RM Length L Ch R = 1 ,14563   ,296,296,296
BEGIN DESCRIPTION:
LINN CREEK 24.0
END DESCRIPTION:
XS GIS Cut Line= 3
       3599106.2     10548978.42      3598699.61     10546910.19
      3597640.11     10545854.33
#Sta/Elev= 30
    2926  374.96    3152  369.03  3225.7  362.74  3321.7  358.61  3353.5  354.46
  3464.3  349.95  3637.6  341.77  3759.3  339.53  4982.9  338.97    5003  328.22
  5007.9  326.03  5011.1  326.53  5037.3  330.18  5047.9  339.78  5125.7  338.05
  5458.1  342.26  5712.6  346.21  5861.1   351.9  5868.2   343.1  5889.4  339.24
  5896.5  348.04  5903.6  350.67  5938.9  352.96  5948.5  353.26  6077.7  359.65
  6093.1  359.97    6212  367.08  6237.8  368.03  6346.4  374.09  6529.6  380.39
#Mann= 14 ,-1 , 0
    2926     .05       0    3152     .08       0  3225.7     .05       0
  3353.5     .08       0  3464.3     .16       0    5003     .07       0
  5011.1     .16       0  5938.9     .12       0  5948.5     .12       0
  6077.7     .08       0  6093.1     .05       0    6212      .1       0
  6237.8     .05       0  6346.4      .1       0
Bank Sta=4982.9,5047.9
XS Rating Curve= 0 ,0
Exp/Cntr=0.3,0.1

Type RM Length L Ch R = 1 ,14267   ,884,884,884
BEGIN DESCRIPTION:
LINN CREEK 23.0
END DESCRIPTION:
XS GIS Cut Line= 5
      3600684.64     10549214.33      3600127.36     10547854.98
      3599262.77     10547297.69      3598705.48     10546381.02
      3598132.55      10545250.8
#Sta/Elev= 30
  1920.1  374.56  1989.4  373.98  2562.2  344.48  3478.5  338.32  3811.2  340.99
    4267  335.69  4987.2  339.04  5000.1  327.78  5014.4  326.45  5023.3  325.67
  5026.5  326.17  5035.7  335.53  5045.3   335.9  5051.2     340  5066.7  336.35
  5072.5  339.38  5103.5  339.68  5372.8  338.23  5739.9  347.03  5845.6  344.01
  6135.1   356.2  6211.3  358.77  6364.3  367.66  6428.3  368.79  6492.3  371.77
  6530.4   373.8    6536  369.81  6567.9  369.35  6604.5  375.31  6757.8   378.4
#Mann= 10 ,-1 , 0
  1920.1     .05       0  2562.2     .16       0  5014.4     .07       0
  5026.5     .16       0  6135.1     .05       0  6211.3     .08       0
  6364.3     .05       0  6428.3      .1       0  6492.3     .08       0
  6604.5     .05       0
Bank Sta=4987.2,5051.2
XS Rating Curve= 0 ,0
Exp/Cntr=0.3,0.1

Type RM Length L Ch R = 1 ,13383   ,486,486,486
BEGIN DESCRIPTION:
LINN CREEK 22.0
END DESCRIPTION:
XS GIS Cut Line= 4
      3600811.93     10549264.84      3600525.48     10546986.23
      3599301.52     10546244.05      3598194.72     10544889.85
#Sta/Elev= 30
  1463.7  381.38  1538.9  376.43  1740.5  377.51  2246.7  348.25  2407.5  339.44
  4221.2  334.67    4270  329.59  4351.8  334.84  4374.4  329.63  4401.6  335.17
  4585.7  335.13  4628.4  334.67  4649.7  328.54  4665.2  330.07  4671.1  335.01
  4781.6   332.9  4961.9  337.98  4977.4  334.61  4983.4  326.87  4995.7  325.36
  4998.5  324.86  5001.7  325.36  5020.1  337.81  5338.5  333.81  5878.4  336.48
  6304.8  363.81  6667.3   377.8  6775.9  386.54  6792.5  387.13  6940.6  389.01
#Mann= 7 ,-1 , 0
  1463.7     .05       0  2246.7     .16       0  4995.7     .07       0
  5001.7     .16       0  6304.8     .05       0  6775.9     .08       0
  6792.5     .05       0
Bank Sta=4961.9,5020.1
XS Rating Curve= 0 ,0
Exp/Cntr=0.3,0.1

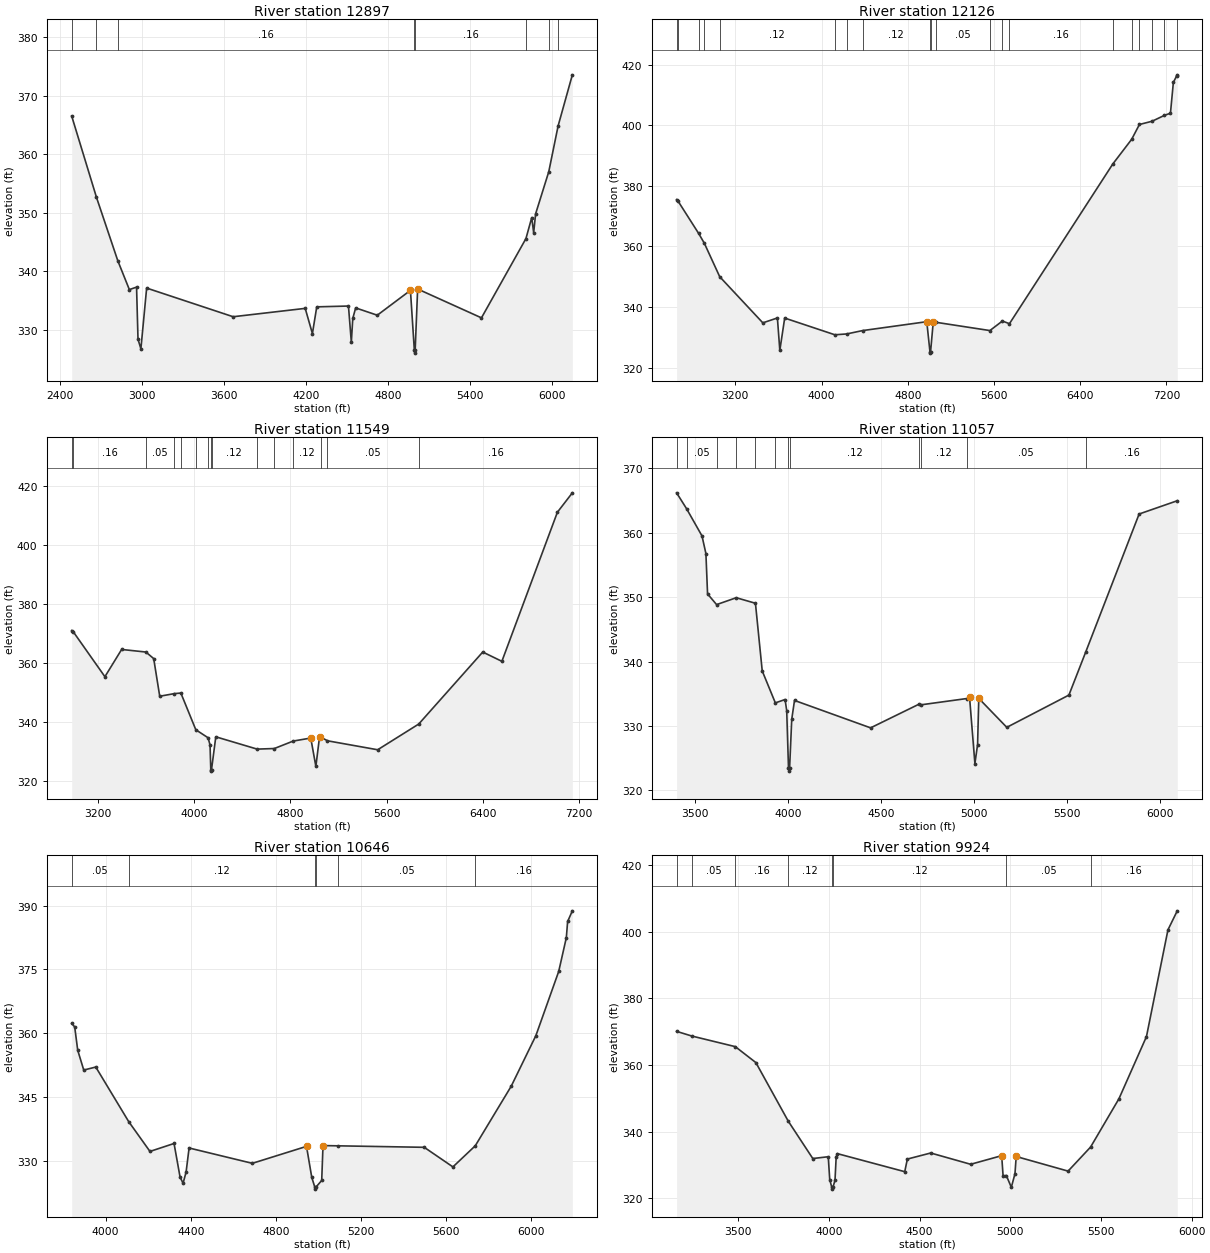
Type RM Length L Ch R = 1 ,12897   ,771,771,771
BEGIN DESCRIPTION:
LINN CREEK 21.0
END DESCRIPTION:
XS GIS Cut Line= 3
      3601899.61     10546660.19      3599499.61     10545860.19
       3598699.6     10545060.18
#Sta/Elev= 30
  2488.2  366.52  2669.5  352.62  2825.5  341.78  2909.8  336.86  2962.5  337.28
  2973.1  328.37  2994.2  326.74  3036.3  337.12  3668.8  332.22  4195.8  333.65
  4248.5  329.34  4280.2  333.91  4512.1  334.05  4533.1  327.85  4543.7  331.93
  4564.8  333.73  4722.9  332.48  4965.3  336.73  4993.9   326.5  4996.7     326
  4999.9   326.5    5018  336.96  5484.7  332.03    5810  345.58  5852.4  349.17
  5866.5  346.58  5880.7  349.81  5976.9  357.01  6045.6  364.87  6149.4  373.57
#Mann= 8 ,-1 , 0
  2488.2     .16       0  2669.5     .12       0  2825.5     .16       0
  4993.9     .07       0  4999.9     .16       0    5810     .05       0
  5976.9     .16       0  6045.6     .05       0
Bank Sta=4965.3,5018
XS Rating Curve= 0 ,0
Exp/Cntr=0.3,0.1

Type RM Length L Ch R = 1 ,12126   ,577,577,577
BEGIN DESCRIPTION:
LINN CREEK 20.0
END DESCRIPTION:
XS GIS Cut Line= 3
      3602049.65     10546410.21      3599770.27     10545228.42
      3598038.46     10544082.56
#Sta/Elev= 30
  2655.8  375.49  2669.4  374.97  2860.5   364.3  2913.3  361.05  3055.7  350.02
  3455.6  334.79  3590.8   336.4  3613.3  325.71  3658.4  336.37  4123.9  330.85
  4233.1  331.12  4380.4  332.23  4976.3  335.17  5005.8  325.29  5008.5  324.79
  5011.8  325.29  5036.5  335.13  5061.8  334.97  5561.9  332.24  5677.5  335.38
  5743.3  334.51  6701.5  387.22  6877.2   395.4  6948.8  400.28  7066.1  401.35
  7179.9  403.28  7236.7  404.01  7263.7  414.17  7295.5  416.43  7299.9  416.68
#Mann= 20 ,-1 , 0
  2655.8     .12       0  2669.4     .16       0  2860.5     .12       0
  2913.3     .16       0  3055.7     .12       0  4123.9     .16       0
  4233.1     .05       0  4380.4     .12       0  5005.8     .07       0
  5011.8     .12       0  5061.8     .05       0  5561.9      .1       0
  5677.5     .05       0  5743.3     .16       0  6701.5     .05       0
  6877.2     .16       0  6948.8      .1       0  7066.1     .05       0
  7179.9     .16       0  7295.5     .16       0
Bank Sta=4976.3,5036.5
XS Rating Curve= 0 ,0
Exp/Cntr=0.3,0.1

Type RM Length L Ch R = 1 ,11549   ,492,492,492
BEGIN DESCRIPTION:
LINN CREEK 19.0
END DESCRIPTION:
XS GIS Cut Line= 4
      3602334.59      10545931.2      3600980.42     10545536.23
      3600203.51     10545045.78      3599197.33     10543509.63
#Sta/Elev= 30
  2979.5  371.03  2993.7  370.55  3255.8  355.39    3395  364.62  3596.6  363.75
  3661.8  361.52  3711.9  348.77  3834.2  349.66  3887.8  349.85  4012.2  337.41
    4114   334.7  4130.5  332.28  4136.8  323.89  4139.5  323.39  4142.8  323.89
  4178.5  335.02  4522.5  330.85  4665.5  331.05  4822.7  333.58  4968.7   334.6
  5011.1  324.99  5041.5  334.96  5057.4  334.79  5107.8  333.67  5525.3  330.63
  5867.1  339.35  6399.6  363.75  6558.8   360.6  7020.7  411.12  7145.2   417.7
#Mann= 15 ,-1 , 0
  2979.5     .05       0  2993.7     .16       0  3596.6     .05       0
  3834.2      .1       0  3887.8     .05       0  4012.2     .07       0
    4114     .12       0  4136.8     .07       0  4142.8     .12       0
  4522.5     .16       0  4665.5     .05       0  4822.7     .12       0
  5057.4     .16       0  5107.8     .05       0  5867.1     .16       0
Bank Sta=4968.7,5041.5
XS Rating Curve= 0 ,0
Exp/Cntr=0.3,0.1

Type RM Length L Ch R = 1 ,11057   ,411,411,411
BEGIN DESCRIPTION:
LINN CREEK 18.0
END DESCRIPTION:
XS GIS Cut Line= 4
      3601799.61     10545710.19      3601362.37     10545414.71
      3600585.46     10544876.51       3599634.9     10544116.93
#Sta/Elev= 30
  3401.4  366.21    3455  363.74  3537.8  359.52  3558.8  356.78  3567.7  350.51
  3616.3  348.85  3721.8  349.92  3824.9  349.06  3861.4  338.55  3931.8  333.59
  3984.1  334.11  3992.9  332.39  4002.5  323.49  4005.2  322.99  4008.5  323.49
  4019.9  331.04  4034.8  333.97  4443.5  329.71  4704.5   333.4  4712.4  333.28
  4959.5  334.26  4975.1  334.49  5003.9  324.17  5018.3  327.11  5024.7  334.29
  5175.2  329.79  5508.9   334.8  5600.2  341.56  5886.1  362.92    6091  364.98
#Mann= 12 ,-1 , 0
  3401.4     .16       0    3455     .05       0  3616.3      .1       0
  3721.8     .05       0  3824.9     .07       0  3931.8     .12       0
  4002.5     .03       0  4008.5     .12       0  4704.5     .05       0
  4712.4     .12       0  4959.5     .05       0  5600.2     .16       0
Bank Sta=4975.1,5024.7
XS Rating Curve= 0 ,0
Exp/Cntr=0.3,0.1

Type RM Length L Ch R = 1 ,10646   ,722,722,722
BEGIN DESCRIPTION:
LINN CREEK 17.0
END DESCRIPTION:
XS GIS Cut Line= 3
       3601699.6     10545510.18      3600899.61     10544710.19
      3599899.62     10544010.19
#Sta/Elev= 30
  3840.4  362.31  3854.5  361.47  3868.7  355.98    3897  351.32  3953.5  352.03
    4108   339.2  4208.1  332.17  4321.2  334.04  4349.5  326.14  4363.6  324.68
  4377.8  327.31  4391.9  332.98  4688.9  329.37  4943.5  333.36  4968.2  326.06
  4982.3   323.8    4985   323.3  4988.3   323.8  5014.9  325.34    5021  333.55
  5091.1  333.49  5496.6  333.14  5631.3  328.53  5736.3   333.5  5905.1  347.51
  6021.1  359.43  6128.3  374.53  6164.1  382.47  6170.2  386.28  6192.4  388.79
#Mann= 6 ,-1 , 0
  3840.4     .05       0    4108     .12       0  4982.3     .07       0
  4988.3     .12       0  5091.1     .05       0  5736.3     .16       0
Bank Sta=4943.5,5021
XS Rating Curve= 0 ,0
Exp/Cntr=0.3,0.1

Type RM Length L Ch R = 1 ,9924    ,507,507,507
BEGIN DESCRIPTION:
LINN CREEK 16.0
END DESCRIPTION:
XS GIS Cut Line= 3
      3602164.04     10545429.03      3600699.61     10544310.19
      3599899.61     10543860.19
#Sta/Elev= 30
  3159.9  370.08  3243.1  368.69  3483.6  365.49  3597.1   360.7  3775.8  343.09
  3910.9  331.89  3996.1  332.43  4004.3  325.59  4015.8   323.2  4018.6   322.7
  4021.8   323.2  4033.4  325.38  4039.7  332.23  4046.4  333.36  4417.9  327.94
  4432.4  331.73  4561.2  333.55  4781.5  330.16  4952.5  332.75  4960.2  326.72
    4978  326.79  5005.7  323.25  5025.8  327.33  5032.5   332.5  5318.7  328.11
  5442.8  335.34  5599.1  349.84  5750.8   368.5  5869.4  400.57  5920.7  406.28
#Mann= 8 ,-1 , 0
  3159.9     .16       0  3243.1     .05       0  3483.6     .16       0
  3775.8     .12       0  4015.8     .03       0  4021.8     .12       0
    4978     .05       0  5442.8     .16       0
Bank Sta=4952.5,5032.5
XS Rating Curve= 0 ,0
Exp/Cntr=0.3,0.1

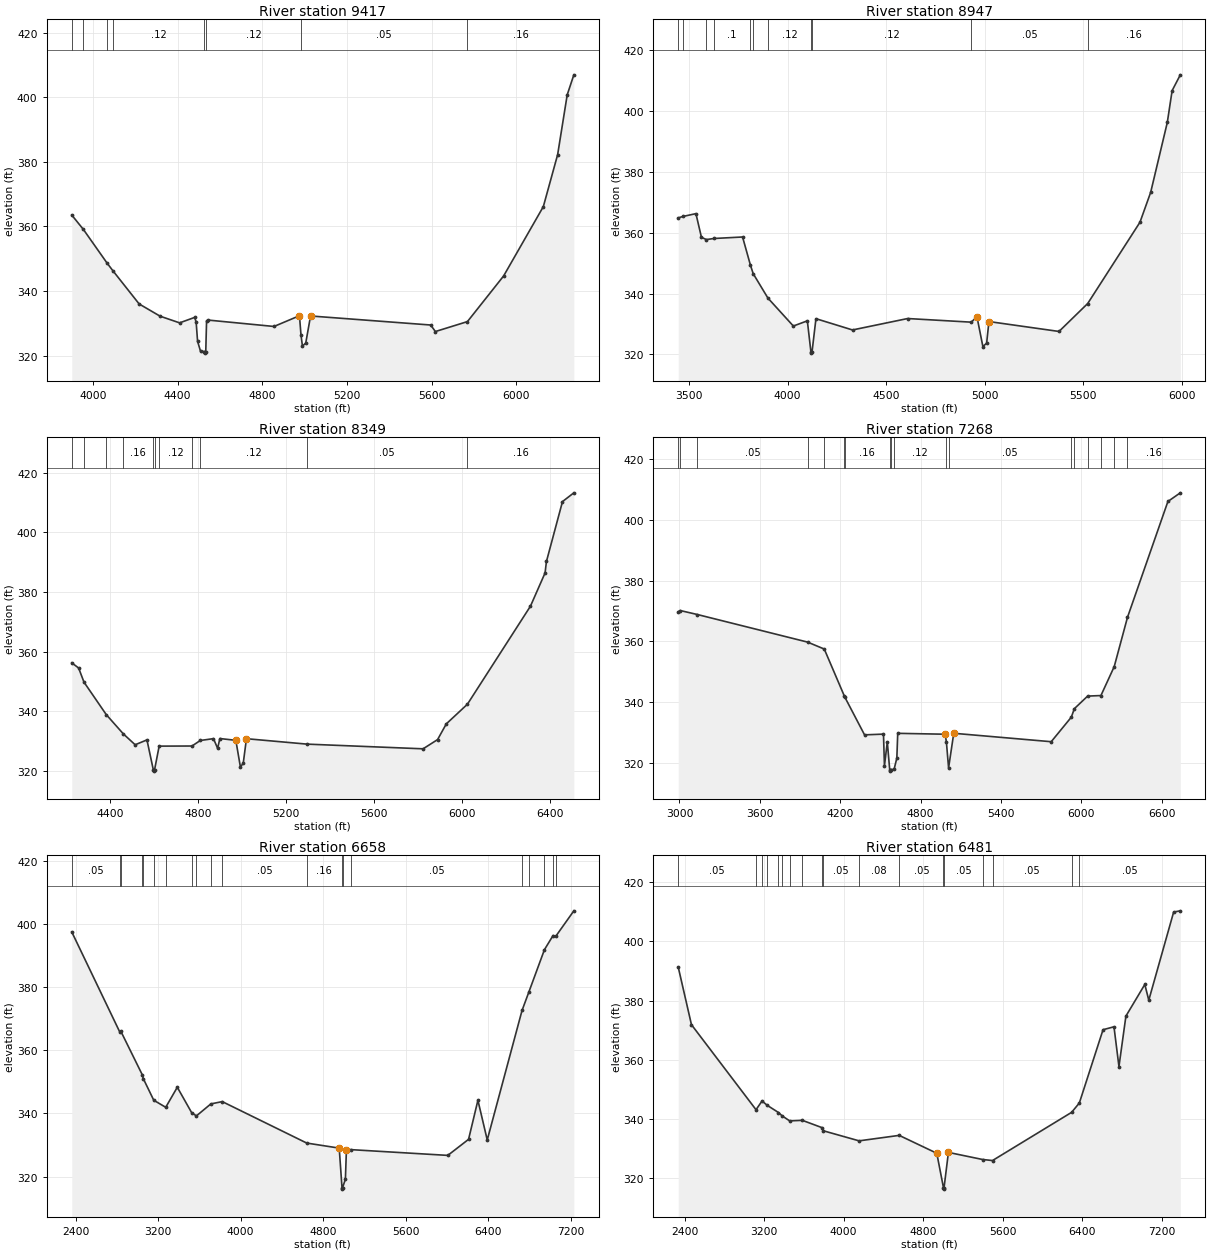
Type RM Length L Ch R = 1 ,9417    ,470,470,470
BEGIN DESCRIPTION:
LINN CREEK 15.0
END DESCRIPTION:
XS GIS Cut Line= 3
      3601899.63     10545060.21      3601149.61     10544260.19
      3599999.58     10543710.17
#Sta/Elev= 30
  3900.4  363.54  3955.3  359.08    4066  348.76  4094.1  346.33  4218.7  335.99
  4317.8   332.2  4409.7  330.14  4480.5  331.82  4487.8  330.45  4494.6  324.43
  4508.8  321.28  4527.3  321.26    4530  320.76  4533.3  321.26  4537.1  330.76
  4544.4     331  4855.6  329.02  4975.8  332.35  4983.1  326.35  4989.9  322.94
  5005.6   323.9  5028.2  332.27  5595.6  329.47  5617.8  327.45  5769.2  330.53
  5940.2  344.68  6127.7  366.16  6195.2  382.24  6240.5   400.8  6271.8  406.99
#Mann= 8 ,-1 , 0
  3900.4     .16       0  3955.3     .12       0    4066     .16       0
  4094.1     .12       0  4527.3     .07       0  4533.3     .12       0
  4983.1     .05       0  5769.2     .16       0
Bank Sta=4975.8,5028.2
XS Rating Curve= 0 ,0
Exp/Cntr=0.3,0.1

Type RM Length L Ch R = 1 ,8947    ,598,598,598
BEGIN DESCRIPTION:
LINN CREEK 14.0
END DESCRIPTION:
XS GIS Cut Line= 3
      3602184.88     10544859.59      3600976.08     10543982.41
      3599995.15     10543600.46
#Sta/Elev= 30
  3445.4  364.81  3469.3  365.28  3535.1   366.2  3563.1  358.43  3588.1   357.7
  3626.8  358.05  3771.7  358.54  3811.5  349.31  3825.7  346.49  3900.3  338.49
  4029.1  329.33  4100.2  331.03  4118.1  320.94  4120.9  320.44  4124.1  320.94
  4143.8  331.74  4329.2  328.04  4608.9  331.79  4931.1   330.6  4960.4  332.35
  4990.3  322.61  5009.4   323.7    5021   330.8  5376.4  327.55    5522  336.72
    5787  363.38  5841.3  373.19  5925.6  396.11  5950.1  406.56  5991.6  411.74
#Mann= 11 ,-1 , 0
  3445.4     .16       0  3469.3     .05       0  3588.1     .08       0
  3626.8      .1       0  3811.5     .15       0  3825.7     .08       0
  3900.3     .12       0  4118.1     .03       0  4124.1     .12       0
  4931.1     .05       0    5522     .16       0
Bank Sta=4960.4,5021
XS Rating Curve= 0 ,0
Exp/Cntr=0.3,0.1

Type RM Length L Ch R = 1 ,8349    ,1081,1081,1081
BEGIN DESCRIPTION:
LINN CREEK 13.0
END DESCRIPTION:
XS GIS Cut Line= 3
      3602149.62     10544110.19      3601399.61     10543910.19
      3599949.59     10543510.18
#Sta/Elev= 30
  4226.5  356.22  4257.6  354.49  4281.9  349.76  4383.2  338.86  4460.9  332.39
  4514.4  328.76    4568  330.39  4596.7  320.42  4599.5  319.92  4602.7  320.42
  4623.4   328.3  4772.6  328.34  4810.2  330.19  4870.1  330.81  4888.9  327.57
  4899.2  330.84  4971.7  330.25  4992.4  321.32  5005.3  322.55  5019.9  330.79
  5295.3  328.97  5822.2   327.4    5888  330.49  5927.6  335.76  6023.5  342.35
  6309.8  375.21  6376.2  386.36  6382.4  390.19  6455.3  410.27  6506.9  413.21
#Mann= 11 ,-1 , 0
  4226.5     .05       0  4281.9     .16       0  4383.2     .12       0
  4460.9     .16       0  4596.7     .07       0  4602.7     .16       0
  4623.4     .12       0  4772.6     .07       0  4810.2     .12       0
  5295.3     .05       0  6023.5     .16       0
Bank Sta=4971.7,5019.9
XS Rating Curve= 0 ,0
Exp/Cntr=0.3,0.1

Type RM Length L Ch R = 1 ,7268    ,610,610,610
BEGIN DESCRIPTION:
LINN CREEK 12.0
END DESCRIPTION:
XS GIS Cut Line= 4
      3602608.82      10544985.4      3602261.59     10544013.14
      3601315.41     10543188.49      3599857.08     10543257.93
#Sta/Elev= 30
  2991.1  369.74  3005.9  370.18  3133.6  368.87  3956.8  359.77  4081.1  357.48
  4231.6  341.92  4234.8  341.61  4381.7  329.19  4523.1  329.43  4530.2  318.96
  4551.6  326.85  4569.5  317.73  4572.2  317.23  4575.5  317.73  4601.9  317.79
  4622.8  321.52  4629.4  329.69  4983.5   329.4  4992.7  326.83    5009  318.28
  5047.5  329.71    5775  326.93  5925.2  335.03  5947.7  337.82  6046.9  341.97
  6146.1  342.15  6245.2  351.68  6344.4  367.95    6646  406.14  6738.6  408.99
#Mann= 18 ,-1 , 0
  2991.1     .05       0  3005.9     .16       0  3133.6     .05       0
  3956.8     .08       0  4081.1     .05       0  4231.6     .12       0
  4234.8     .16       0  4569.5     .07       0  4575.5     .16       0
  4601.9     .12       0  4992.7     .16       0    5009     .05       0
  5925.2      .1       0  5947.7     .15       0  6046.9      .1       0
  6146.1     .08       0  6245.2     .05       0  6344.4     .16       0
Bank Sta=4983.5,5047.5
XS Rating Curve= 0 ,0
Exp/Cntr=0.3,0.1

Type RM Length L Ch R = 1 ,6658    ,177,177,177
BEGIN DESCRIPTION:
LINN CREEK 11.0
END DESCRIPTION:
XS GIS Cut Line= 5
      3604396.98     10543882.92      3602895.27      10543049.6
      3601402.21     10543075.64      3600343.18     10542954.12
      3599796.31     10543179.81
#Sta/Elev= 30
    2363  397.42  2826.1  365.92    2839  365.98  3047.4  352.19  3056.5  351.02
  3158.1  344.18  3274.1  341.95  3386.2  348.29  3526.1  340.22  3571.6  339.23
  3711.5  343.02  3822.2  343.75  4641.3  330.64  4956.2  329.04  4983.2  316.57
    4986  316.07  4989.2  316.57  5016.2  319.21  5026.2  328.59  5069.5  328.56
  6009.2  326.74  6210.5  331.82  6301.1  344.17  6391.6  331.62    6729  372.58
  6794.9  378.39  6946.4  391.82  7029.7  396.27  7055.2     396  7231.3  404.09
#Mann= 20 ,-1 , 0
    2363     .05       0  2826.1      .1       0    2839     .05       0
  3047.4     .07       0  3056.5     .12       0  3158.1     .05       0
  3274.1     .07       0  3526.1     .12       0  3571.6     .07       0
  3711.5      .1       0  3822.2     .05       0  4641.3     .16       0
  4983.2     .07       0  4989.2     .16       0  5069.5     .05       0
    6729     .08       0  6794.9     .16       0  6946.4     .08       0
  7029.7     .16       0  7055.2     .05       0
Bank Sta=4956.2,5026.2
XS Rating Curve= 0 ,0
Exp/Cntr=0.3,0.1

Type RM Length L Ch R = 1 ,6481    ,980,980,980
BEGIN DESCRIPTION:
LINN CREEK 10.0
END DESCRIPTION:
XS GIS Cut Line= 5
      3604379.66     10543683.29       3603016.8     10542858.63
      3601679.99     10542902.03      3600664.36     10542745.78
      3599572.61     10542719.79
#Sta/Elev= 30
  2336.7  391.31  2469.7  371.83  3119.1  343.07  3179.6  346.02    3232  344.55
  3344.9  342.12  3382.2  340.98  3457.8  339.29  3584.8  339.48  3787.4  336.95
  3795.5  335.95  4155.8  332.54  4559.2  334.39  4937.4  328.34  5004.4  316.71
  5007.2  316.21  5010.4  316.71  5054.3  328.63  5398.3  326.23  5497.8  325.88
  6293.4  342.18  6371.2  345.34  6609.6  370.13  6719.6  371.12  6769.6  357.67
  6839.6  374.73  7029.7  385.44  7069.7  380.12  7319.8  409.93  7386.8  410.34
#Mann= 18 ,-1 , 0
  2336.7     .05       0  3119.1     .12       0  3179.6     .07       0
    3232     .05       0  3344.9     .07       0  3382.2     .05       0
  3457.8     .07       0  3584.8     .05       0  3787.4      .1       0
  3795.5     .05       0  4155.8     .08       0  4559.2     .05       0
  5004.4     .04       0  5010.4     .05       0  5398.3     .08       0
  5497.8     .05       0  6293.4     .08       0  6371.2     .05       0
Bank Sta=4937.4,5054.3
XS Rating Curve= 0 ,0
Exp/Cntr=0.3,0.1