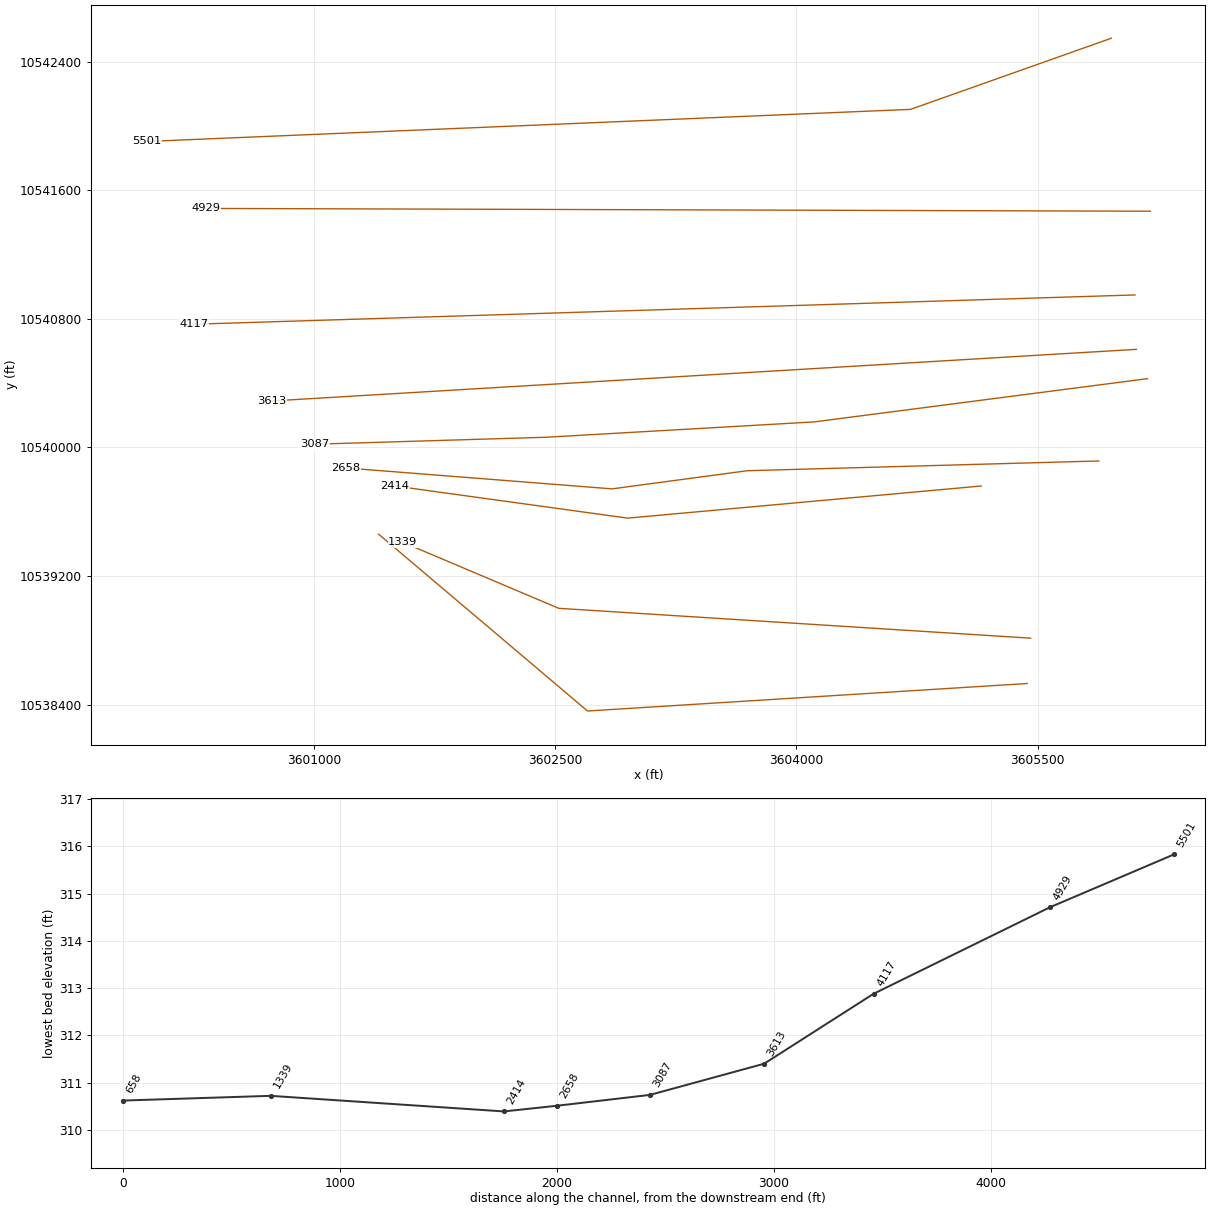
HEC-RAS study LINN CREEK.prj: LINN CREEK Base Level Engineering

--- LINN CREEK.g01 (geometry) --- (continued)

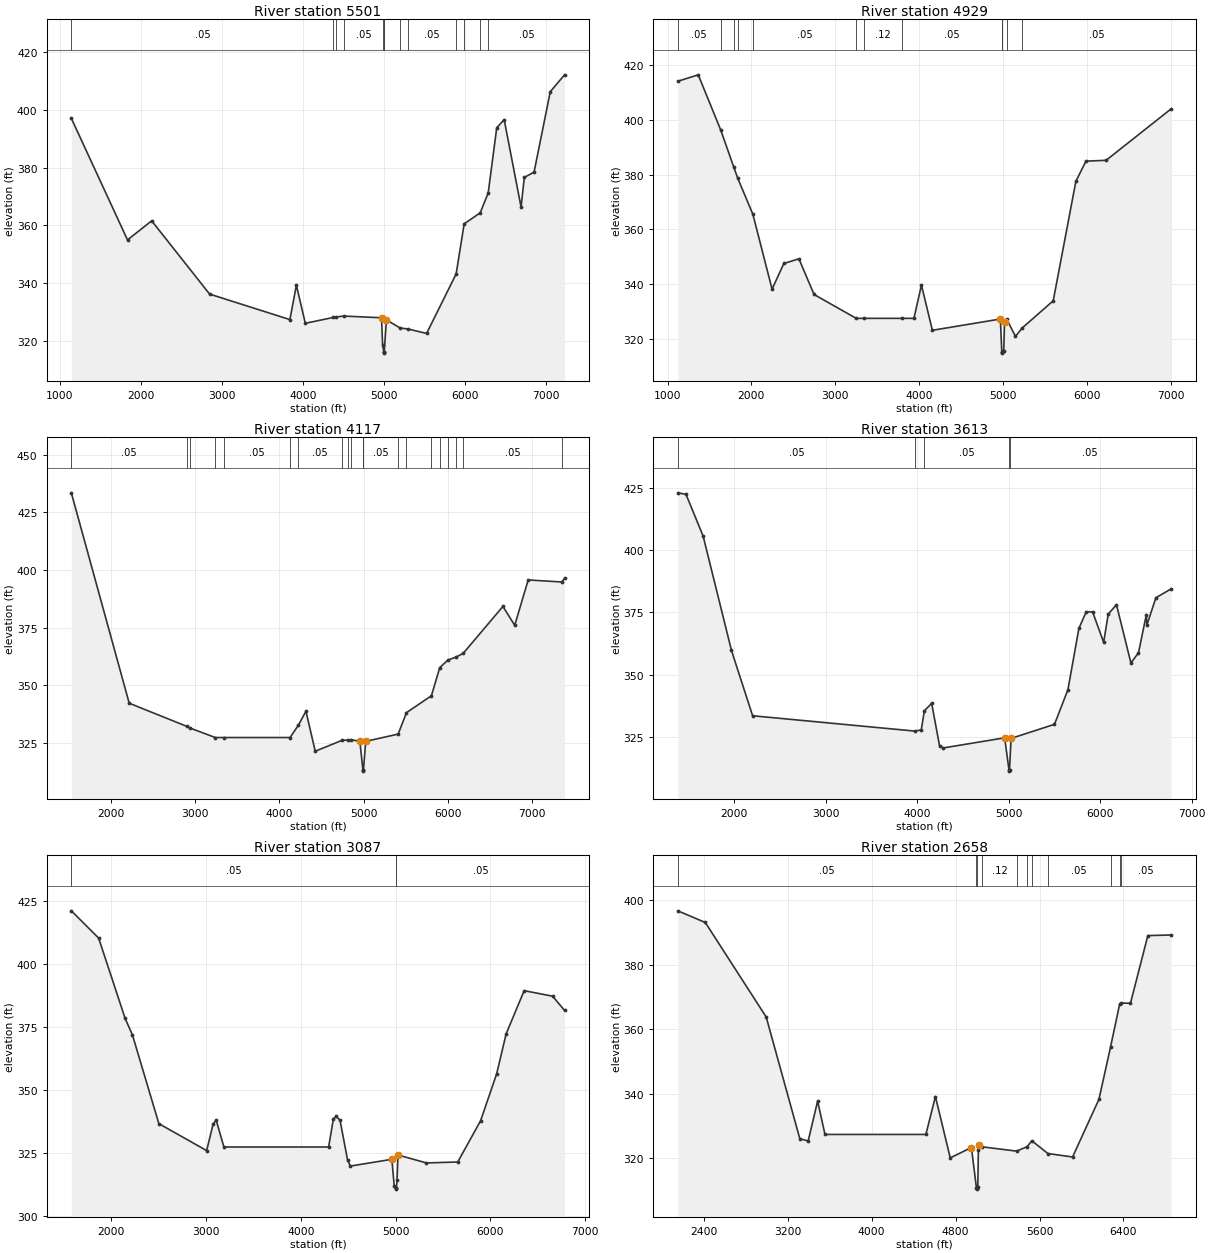
Type RM Length L Ch R = 1 ,5501    ,572,572,572
BEGIN DESCRIPTION:
LINN CREEK 9.0
END DESCRIPTION:
XS GIS Cut Line= 3
      3605959.55     10542546.14       3604709.5     10542103.42
      3599953.62     10541903.81
#Sta/Elev= 30
  1141.2  397.05  1834.5  354.99  2132.8  361.59  2847.6  336.25  3838.4  327.43
  3918.5  339.32  4028.6  326.14  4374.8  328.18  4407.8  328.34  4506.7  328.65
  4969.4  328.06  4982.1  318.74  4996.4  316.33  4999.2  315.83  5002.4  316.33
  5029.5  327.32  5198.3  324.53  5297.1  324.17  5525.1  322.64    5890  343.23
  5988.8  360.55  6186.4  364.35  6285.2  371.21  6390.7  393.78  6482.5  396.59
  6690.9  366.35    6731  376.62  6851.1  378.41  7051.3  406.25  7227.4  412.09
#Mann= 13 ,-1 , 0
  1141.2     .05       0  4374.8      .1       0  4407.8     .15       0
  4506.7     .05       0  4982.1     .12       0  4996.4     .07       0
  5002.4     .12       0  5198.3     .07       0  5297.1     .05       0
    5890     .08       0  5988.8     .15       0  6186.4     .08       0
  6285.2     .05       0
Bank Sta=4969.4,5029.5
XS Rating Curve= 0 ,0
Exp/Cntr=0.3,0.1

Type RM Length L Ch R = 1 ,4929    ,812,812,812
BEGIN DESCRIPTION:
LINN CREEK 8.0
END DESCRIPTION:
XS GIS Cut Line= 2
      3606202.58     10541469.74      3600325.81      10541487.1
#Sta/Elev= 30
  1123.1  414.13  1366.1  416.48  1633.9  396.33  1788.1  382.87  1837.5  378.62
  2017.5  365.46  2246.1   338.1  2386.1  347.49  2566.1   349.2  2746.1  336.16
  3248.1  327.43    3347  327.43  3792.7  327.43  3936.1  327.43  4026.1  339.57
  4156.1  323.06  4966.1  327.18  4983.1  315.21  4985.8  314.71  4989.1  315.21
  5006.1   315.5  5016.1  326.05  5042.9  327.02  5146.1  320.84    5226  323.89
  5596.1  333.86  5866.1  377.56  5986.1  384.92  6226.1  385.22  6999.9  404.01
#Mann= 12 ,-1 , 0
  1123.1     .05       0  1633.9     .07       0  1788.1     .05       0
  1837.5     .07       0  2017.5     .05       0  3248.1     .07       0
    3347     .12       0  3792.7     .05       0  4983.1     .03       0
  4989.1     .05       0  5042.9     .12       0    5226     .05       0
Bank Sta=4966.1,5016.1
XS Rating Curve= 0 ,0
Exp/Cntr=0.3,0.1

Type RM Length L Ch R = 1 ,4117    ,504,504,504
BEGIN DESCRIPTION:
LINN CREEK 7.0
END DESCRIPTION:
XS GIS Cut Line= 2
      3606107.05     10540948.91      3600247.68     10540766.61
#Sta/Elev= 30
  1526.5  433.41  2214.3   342.3    2901  332.23  2940.9  331.49  3237.4  327.43
  3336.2  327.43  4126.7  327.43  4225.5  332.81  4315.3  338.81  4425.3  321.49
  4743.4  326.21  4818.4  326.35  4851.2  326.47  4955.6  325.82  4992.6  313.38
  4995.4  312.88  4998.6  313.38  5025.6  325.78  5411.2  328.92  5510.1  338.21
  5806.5  345.53  5905.3  357.72  6004.1     361  6102.9  362.35  6184.1  363.88
  6656.4  384.21  6796.5  376.02  6956.6  395.68  7356.3  394.79  7388.7  396.35
#Mann= 20 ,-1 , 0
  1526.5     .05       0    2901     .07       0  2940.9     .05       0
  3237.4     .07       0  3336.2     .05       0  4126.7     .07       0
  4225.5     .05       0  4743.4      .1       0  4818.4     .15       0
  4851.2     .05       0  4992.6     .03       0  4998.6     .05       0
  5411.2     .08       0  5510.1     .15       0  5806.5     .08       0
  5905.3     .05       0  6004.1     .08       0  6102.9      .1       0
  6184.1     .05       0  7356.3     .08       0
Bank Sta=4955.6,5025.6
XS Rating Curve= 0 ,0
Exp/Cntr=0.3,0.1

Type RM Length L Ch R = 1 ,3613    ,526,526,526
BEGIN DESCRIPTION:
LINN CREEK 6.0
END DESCRIPTION:
XS GIS Cut Line= 2
      3606115.73     10540610.36       3600734.2     10540289.21
#Sta/Elev= 30
  1383.6  422.94  1472.7  422.35  1660.2   405.6  1969.9  359.76  2201.2  333.59
  3979.6  327.43  4044.4  327.96  4078.5  335.56    4158  338.58  4244.8  321.48
  4284.9  320.69  4956.1  324.75  5003.2   311.9  5005.9   311.4  5009.2   311.9
  5026.2  324.51  5500.6  330.16  5647.3     344  5767.5  368.61  5847.6  375.28
  5917.8  375.18    6038  363.02  6088.1  374.31  6178.2  378.09    6336  354.76
  6418.7   358.8  6505.1  374.15  6510.1  369.91    6609  380.88  6774.7  384.43
#Mann= 5 ,-1 , 0
  1383.6     .05       0  3979.6     .07       0  4078.5     .05       0
  5003.2     .03       0  5009.2     .05       0
Bank Sta=4956.1,5026.2
XS Rating Curve= 0 ,0
Exp/Cntr=0.3,0.1

Type RM Length L Ch R = 1 ,3087    ,429,429,429
BEGIN DESCRIPTION:
LINN CREEK 5.0
END DESCRIPTION:
XS GIS Cut Line= 4
       3606185.2     10540428.07      3604110.55     10540158.98
      3602443.88     10540063.49      3601003.76     10540020.11
#Sta/Elev= 30
  1579.6  420.93  1867.6  410.14  2145.6  378.49  2224.8  371.72  2502.9  336.66
    3007     326  3075.9  336.58  3107.9  337.99  3188.6  327.43  4293.6  327.43
  4343.7  338.53  4373.7  339.54  4413.8     338  4493.9  322.16    4524  319.88
  4960.7  322.55  4984.7  312.17  5001.7  311.24  5004.5  310.74  5007.7  311.24
  5014.8  314.19  5024.8  324.26  5325.3  321.11  5655.4  321.49  5895.6  337.76
  6065.6  356.36  6165.7  372.21  6355.8  389.32  6655.9  387.13  6781.8   381.5
#Mann= 3 ,-1 , 0
  1579.6     .05       0  5001.7     .03       0  5007.7     .05       0
Bank Sta=4960.7,5024.8
XS Rating Curve= 0 ,0
Exp/Cntr=0.3,0.1

Type RM Length L Ch R = 1 ,2658    ,244,244,244
BEGIN DESCRIPTION:
LINN CREEK 4.0
END DESCRIPTION:
XS GIS Cut Line= 4
      3605881.42     10539915.92      3603693.88     10539855.16
      3602851.86     10539742.31       3601194.2     10539872.49
#Sta/Elev= 30
  2152.8  396.62  2414.7  393.01  2994.9  363.77  3315.1  326.15  3395.1   325.4
  3485.1  337.75  3555.2  327.43    4517  327.43  4607.8  339.15  4749.1  320.18
  4950.9  323.38  4998.3  311.01  5001.1  310.51  5004.3  311.01  5011.4  311.15
  5017.5  322.66  5022.5  324.05  5054.8  323.59  5381.5  322.27    5481  323.63
    5527  325.47    5680  321.52  5915.2  320.46    6166  338.27  6276.9  354.49
    6363  367.67  6376.4  368.08  6466.9  368.04  6632.4  388.96  6853.5  389.14
#Mann= 11 ,-1 , 0
  2152.8     .05       0  4998.3     .03       0  5004.3     .05       0
  5054.8     .12       0  5381.5     .05       0    5481      .1       0
    5527     .15       0    5680     .05       0  6276.9     .08       0
    6363      .1       0  6376.4     .05       0
Bank Sta=4950.9,5022.5
XS Rating Curve= 0 ,0
Exp/Cntr=0.3,0.1

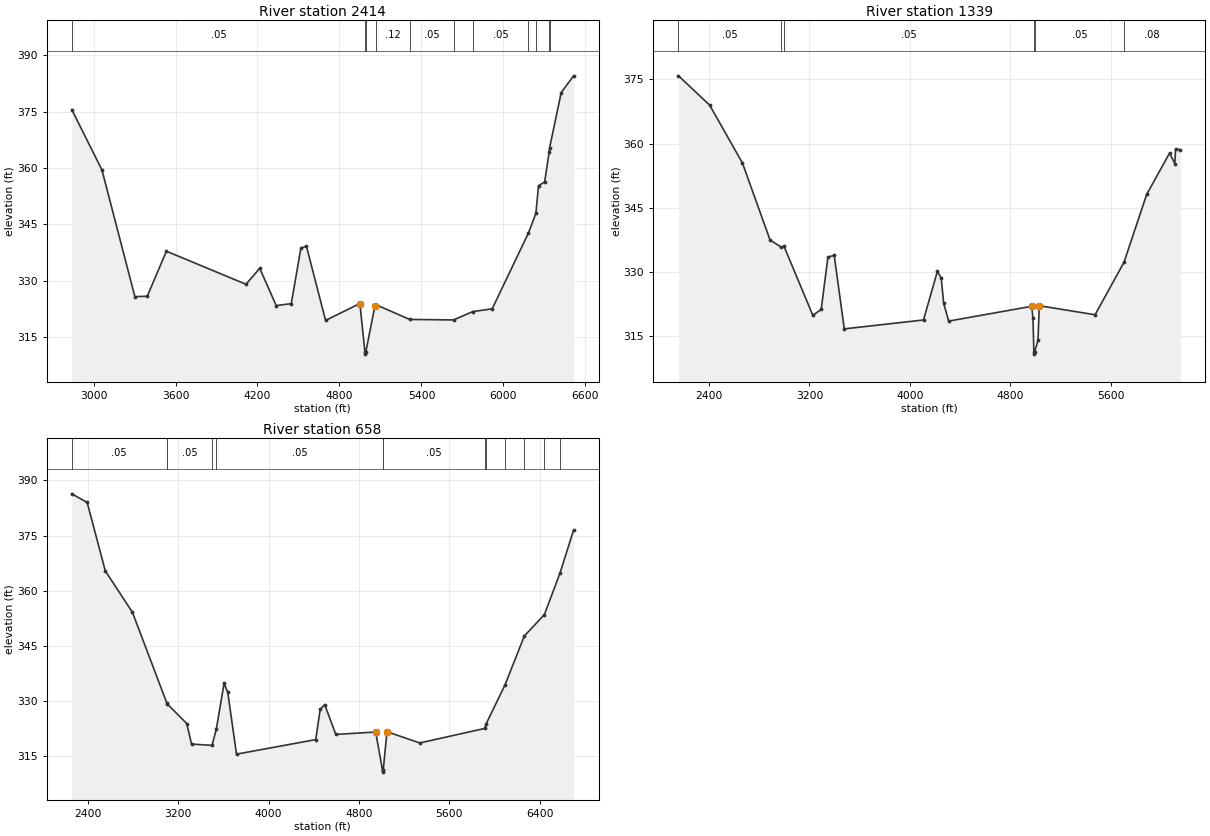
Type RM Length L Ch R = 1 ,2414    ,1075,1075,1075
BEGIN DESCRIPTION:
LINN CREEK 3.0
END DESCRIPTION:
XS GIS Cut Line= 3
      3605149.61     10539760.19      3602949.61     10539560.19
      3601499.61     10539760.19
#Sta/Elev= 30
  2840.7  375.58  3061.6  359.49  3302.6  325.71    3393  325.81  3533.5  337.82
  4115.9  329.01  4216.4  333.27  4336.9  323.33  4447.3  323.85  4517.6  338.63
  4557.8  339.19  4698.3  319.38  4949.4  323.88  4986.5  310.89  4989.3  310.39
  4992.5  310.89  5059.9  323.35  5070.3  323.51  5313.8  319.64  5635.2   319.5
  5775.4  321.73  5917.9  322.47    6183  342.68  6237.4  347.89  6256.7  355.28
  6301.5  356.29  6334.6  364.22  6337.8  365.38  6422.7  380.11  6513.5  384.58
#Mann= 11 ,-1 , 0
  2840.7     .05       0  4986.5     .03       0  4992.5     .05       0
  5070.3     .12       0  5313.8     .05       0  5635.2      .1       0
  5775.4     .05       0    6183     .08       0  6237.4     .05       0
  6334.6     .08       0  6337.8     .05       0
Bank Sta=4949.4,5059.9
XS Rating Curve= 0 ,0
Exp/Cntr=0.3,0.1

Type RM Length L Ch R = 1 ,1339    ,681,681,681
BEGIN DESCRIPTION:
LINN CREEK 2.0
END DESCRIPTION:
XS GIS Cut Line= 3
      3605457.53     10538813.34      3602520.32     10538999.13
      3601549.64     10539410.17
#Sta/Elev= 30
  2157.1  375.84  2405.5  368.98  2666.3  355.46  2886.5  337.42  2976.7  335.74
  2998.3  335.91  3227.2  319.79  3293.8  321.18  3347.4  333.42  3397.5  333.84
  3477.7  316.63  4108.9  318.71  4219.1  330.08    4250  328.55  4269.2  322.65
  4309.3  318.45  4970.6  321.91  4980.7  319.16  4987.7  311.22  4990.4  310.72
  4993.7  311.22  5020.7  313.95  5030.8  322.05  5475.2  319.93    5706  332.23
  5886.7  348.11  6068.7  357.76  6110.7   355.3  6116.1  358.69  6154.3  358.57
#Mann= 6 ,-1 , 0
  2157.1     .05       0  2976.7     .07       0  2998.3     .05       0
  4987.7     .03       0  4993.7     .05       0    5706     .08       0
Bank Sta=4970.6,5030.8
XS Rating Curve= 0 ,0
Exp/Cntr=0.3,0.1

Type RM Length L Ch R = 1 ,658     ,0,0,0
BEGIN DESCRIPTION:
LINN CREEK 1.0
END DESCRIPTION:
XS GIS Cut Line= 3
      3605435.87     10538531.22      3602699.61     10538360.19
      3601399.64     10539460.17
#Sta/Elev= 30
  2256.2  386.34  2392.7     384    2553  365.39  2793.5  354.11  3098.5  329.39
    3104   329.1  3274.4  323.85  3317.1  318.26  3498.4  317.89  3536.6  322.32
  3605.1  334.78  3637.7  332.34  3715.3  315.51  4416.7  319.47  4456.7  327.73
  4496.8  328.97  4594.5  320.88  4947.7  321.53  5008.5  311.12  5011.2  310.62
  5014.5  311.12  5047.8  321.62  5338.4  318.56  5912.8   322.5  5925.7  323.72
  6092.4  334.29  6264.4  347.66  6442.4   353.5  6579.3  364.69  6700.7  376.46
#Mann= 13 ,-1 , 0
  2256.2     .05       0  3098.5     .07       0    3104     .05       0
  3498.4      .1       0  3536.6     .05       0  5008.5     .03       0
  5014.5     .05       0  5912.8     .08       0  5925.7     .05       0
  6092.4     .08       0  6264.4     .05       0  6442.4     .08       0
  6579.3     .05       0
Bank Sta=4947.7,5047.8
XS Rating Curve= 0 ,0
Exp/Cntr=0.3,0.1

Chan Stop Cuts=-1
Use User Specified Reach Order=0
Composite Channel Slope=5