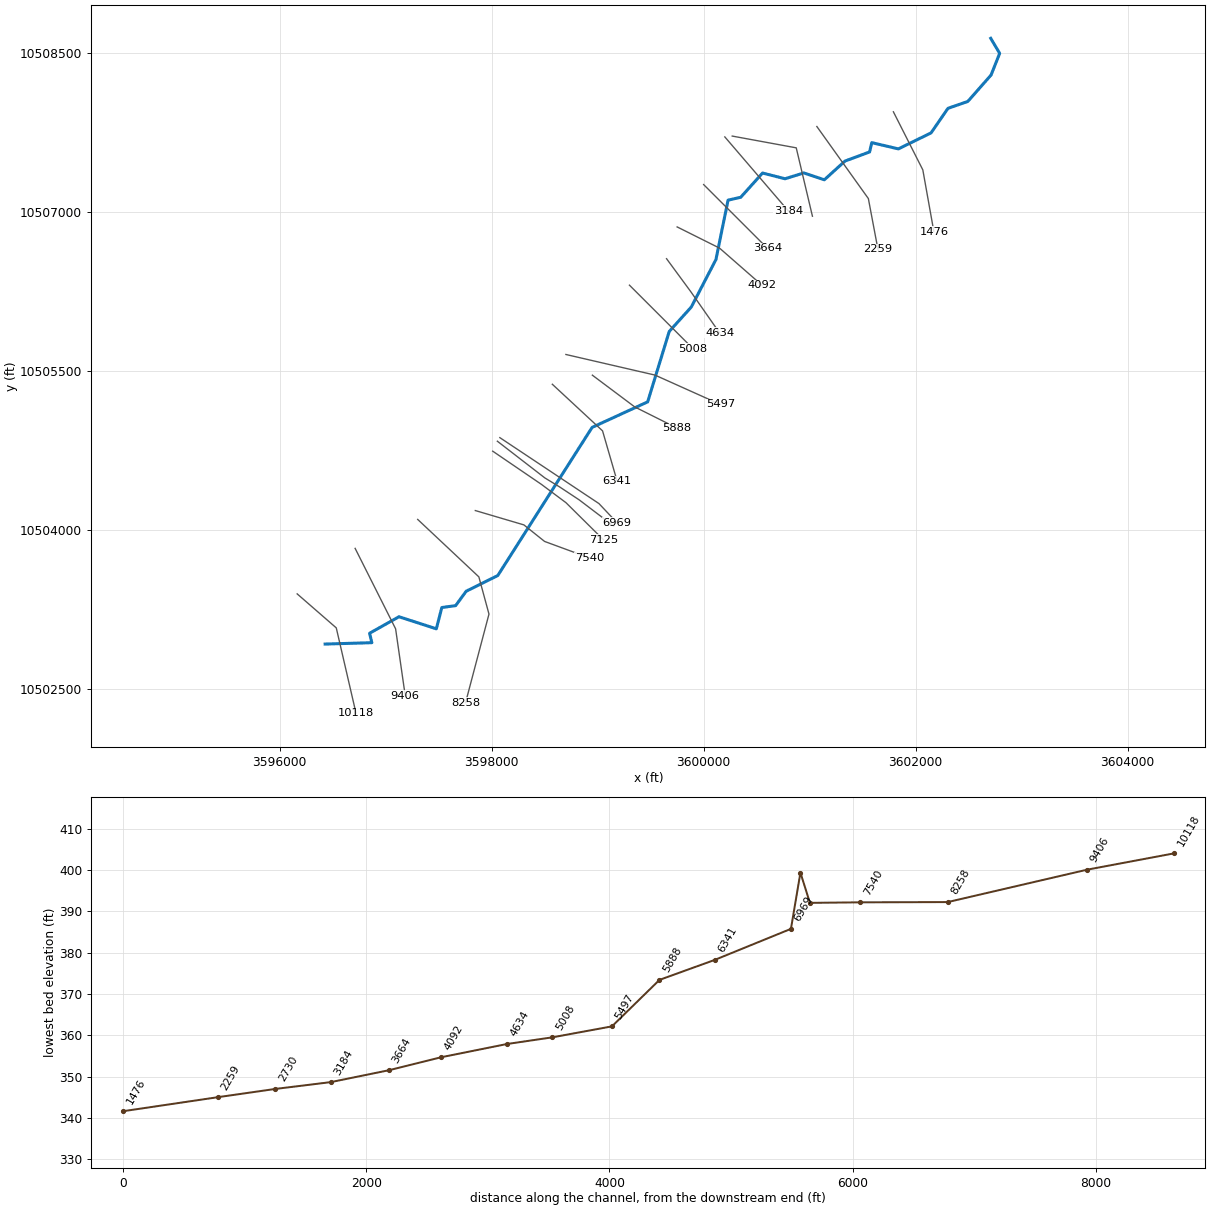
--- NANNY BRANCH.prj (project) ---

Proj Title=NANNY BRANCH Base Level Engineering
Current Plan=p01
Default Exp/Contr=0.3,0.1
English Units
Geom File=g01
Flow File=f01
Plan File=p01
Y Axis Title=Elevation
X Axis Title(PF)=Main Channel Distance
X Axis Title(XS)=Station
BEGIN DESCRIPTION:
NANNY BRANCH
END DESCRIPTION:
DSS Export Rating Curves= 0
DSS Export Rating Curve Sorted= 0
DSS Export Volume Flow Curves= 0
DXF OffsetX= 0
DXF OffsetY= 0
DXF ScaleX= 1
DXF ScaleY= 10

--- NANNY BRANCH.p01 (plan) ---

Plan Title=Multiple Run
Short Identifier=Multiple
Geom File=g01
Flow File=f01
Subcritical Flow
K Sum by GR= 0
Std Step Tol= 0.01
Critical Tol= 0.01
Num of Std Step Trials= 20
Max Error Tol= 0.3
Flow Tol Ratio= 0.001
Split Flow NTrial= 30
Split Flow Tol= 0.02
Split Flow Ratio= 0.02
Log Output Level= 0
Friction Slope Method= 1
Unsteady Friction Slope Method= 2
Unsteady Bridges Friction Slope Method= 1
Parabolic Critical Depth
Global Vel Dist=  1 , 1 , 1
Global Log Level= 0
CheckData=True
Encroach Param= -1, 0, 0, 0
BEGIN DESCRIPTION:
Multiple Run
END DESCRIPTION:

--- NANNY BRANCH.f01 (steady flow) ---

Flow Title=Multiple
Program Version=4.10
Number of Profiles= 7
Profile Names=10-year,25-year,50-year,1pct_min,100-year,1pct_plu,500-year
River Rch & RM=NANNY BRANCH,Reach-1         ,10118
    1498    2124    2658    2426    3281    4437    4986
Boundary for River Rch & Prof#=NANNY BRANCH,Reach-1         , 1
Up Type= 0
Dn Type= 3
Dn Slope=0.005
Boundary for River Rch & Prof#=NANNY BRANCH,Reach-1         , 2
Up Type= 0
Dn Type= 3
Dn Slope=0.005
Boundary for River Rch & Prof#=NANNY BRANCH,Reach-1         , 3
Up Type= 0
Dn Type= 3
Dn Slope=0.005
Boundary for River Rch & Prof#=NANNY BRANCH,Reach-1         , 4
Up Type= 0
Dn Type= 3
Dn Slope=0.005
Boundary for River Rch & Prof#=NANNY BRANCH,Reach-1         , 5
Up Type= 0
Dn Type= 3
Dn Slope=0.005
Boundary for River Rch & Prof#=NANNY BRANCH,Reach-1         , 6
Up Type= 0
Dn Type= 3
Dn Slope=0.005
Boundary for River Rch & Prof#=NANNY BRANCH,Reach-1         , 7
Up Type= 0
Dn Type= 3
Dn Slope=0.005
DSS Import GetInterval= 0
DSS Import GetPeak= 0
DSS Import FillOption= 0

--- NANNY BRANCH.g01 (geometry) ---

Geom Title=Existing Conditions
Program Version=4.10

River Reach=NANNY BRANCH    ,Reach-1
Reach XY= 30
      3596427.75       10502921.        3596869.       10502934.
       3596847.5       10503023.        3597125.       10503179.
      3597477.25       10503065.      3597529.25       10503266.
       3597659.5       10503284.        3597759.       10503420.
        3598057.       10503568.      3598947.25       10504967.
       3599471.5       10505208.        3599675.       10505873.
      3599882.75       10506103.      3600115.75       10506552.
        3600230.       10507113.       3600349.5       10507140.
       3600555.5       10507369.        3600768.       10507315.
      3600945.25       10507370.       3601138.5       10507305.
       3601333.5       10507482.      3601565.75       10507568.
      3601586.25       10507656.      3601837.25       10507597.
       3602145.5       10507748.      3602305.25       10507980.
       3602492.5       10508045.       3602711.5       10508294.
        3602793.       10508499.      3602708.75       10508641.

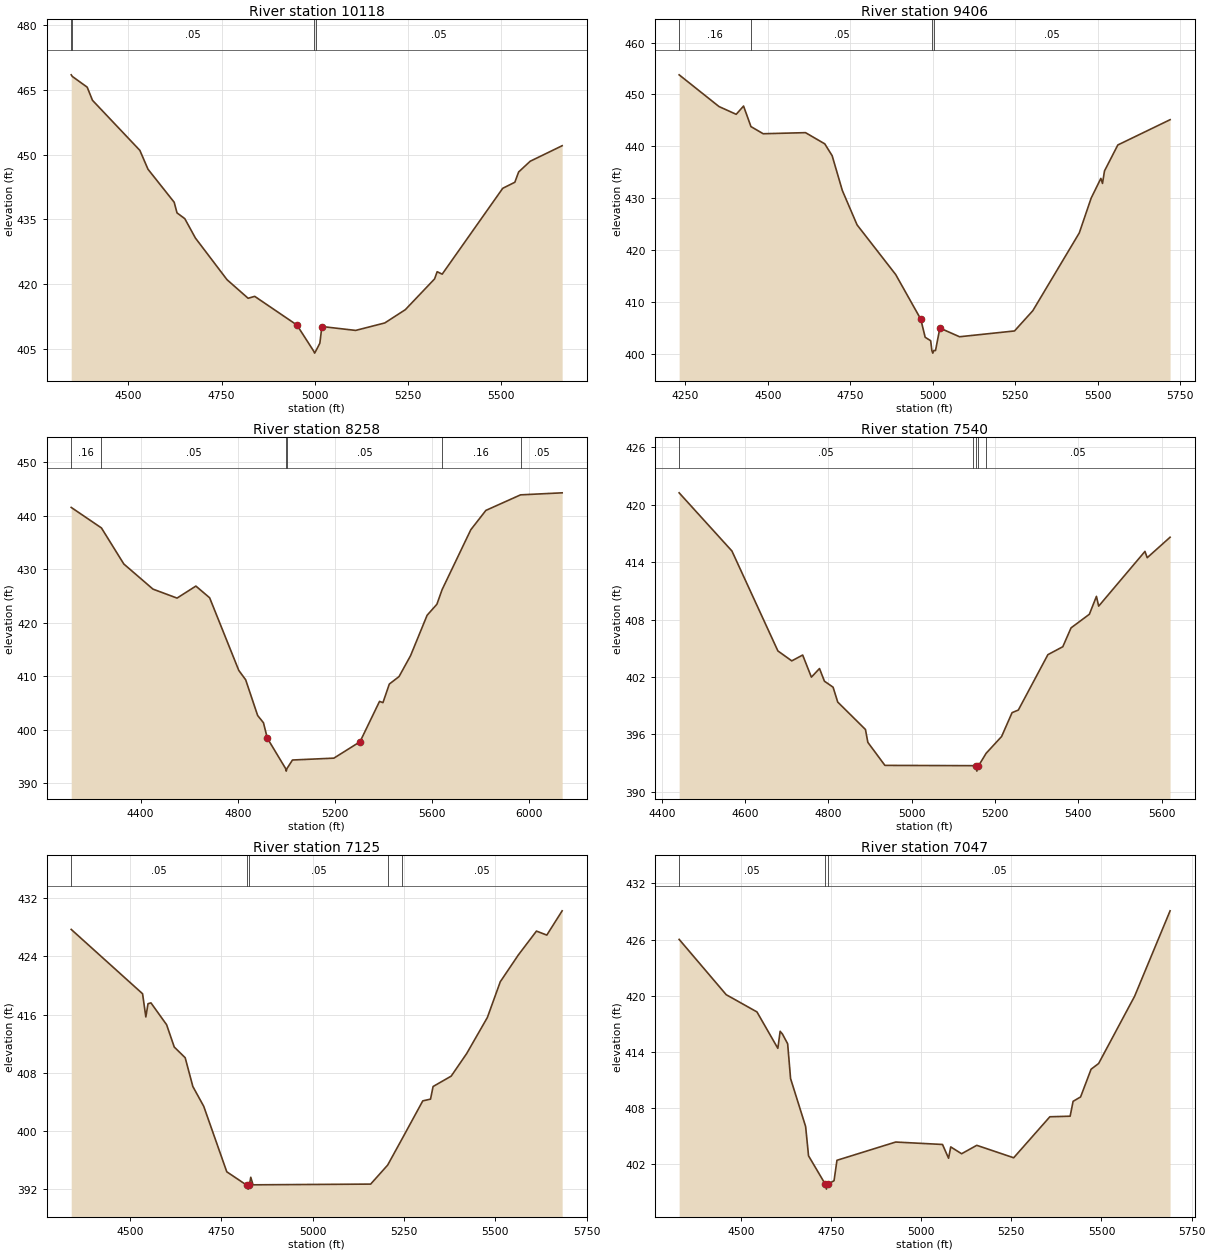
Type RM Length L Ch R = 1 ,10118   ,712,712,712
BEGIN DESCRIPTION:
NANNY BRANCH 11.0
END DESCRIPTION:
XS GIS Cut Line= 3
      3596164.18       10503395.      3596533.13      10503073.8
      3596719.77     10502266.47
#Sta/Elev= 30
  4346.4  468.46  4349.4  468.08  4389.3   465.6  4403.5  462.56  4530.7  450.96
  4552.5   446.6  4622.8  438.95  4630.4  436.49  4651.3  435.15  4679.8  430.66
  4764.6  421.02  4821.3  416.71  4838.9  417.16  4952.2  410.52    4997  404.51
  4999.8  404.01    5003  404.51  5013.8   406.3  5019.3  410.17  5109.9  409.27
  5188.2     411  5243.2  414.07  5321.7  421.19  5328.7  422.86  5342.2   422.3
  5504.7  442.18  5537.2  443.58  5547.4  445.96  5578.3  448.44  5664.2  452.04
#Mann= 4 ,-1 , 0
  4346.4     .16       0  4349.4     .05       0    4997    .035       0
    5003     .05       0
Bank Sta=4952.2,5019.3
XS Rating Curve= 0 ,0
Exp/Cntr=0.3,0.1

Type RM Length L Ch R = 1 ,9406    ,1148,1148,1148
BEGIN DESCRIPTION:
Mapping XS fd454dd7
END DESCRIPTION:
XS GIS Cut Line= 3
      3596711.08     10503824.67      3597093.02     10503065.12
       3597183.9     10502433.29
#Sta/Elev= 30
  4230.8  453.79  4351.6  447.67  4403.7  446.17  4426.1  447.76  4448.5   443.8
  4485.6  442.42  4613.9  442.63  4672.3  440.47  4694.7  438.18  4725.5  431.48
  4770.2  424.84  4887.4  415.24  4963.4  406.63  4976.7  403.14  4993.4  402.47
    4997  400.58  4999.8  400.08    5003  400.58  5008.1  400.58  5021.3  404.92
  5080.9  403.24  5247.6  404.36    5303  408.26    5444  423.28    5480     430
  5509.4   433.8  5514.4  432.83  5520.4  435.24  5560.8  440.25  5719.3  445.13
#Mann= 4 ,-1 , 0
  4230.8     .16       0  4448.5     .05       0    4997    .035       0
    5003     .05       0
Bank Sta=4963.4,5021.3
XS Rating Curve= 0 ,0
Exp/Cntr=0.3,0.1

Type RM Length L Ch R = 1 ,8258    ,718,718,718
BEGIN DESCRIPTION:
Mapping XS f779e6b6
END DESCRIPTION:
XS GIS Cut Line= 4
      3597301.39     10504098.07      3597878.61     10503555.57
       3597974.1     10503204.01      3597752.74      10502366.3
#Sta/Elev= 30
  4113.8  441.58  4238.3  437.74  4330.6  430.99  4450.7  426.29  4549.9  424.61
  4627.5  426.86  4684.2  424.67  4804.3  411.08  4832.7  409.32    4882  402.64
  4905.9  401.29  4921.9  398.39    4997  392.73  4999.8  392.23    5003  392.73
  5025.5  394.31  5196.2  394.66  5303.7  397.72  5384.2  405.28  5398.3  405.05
  5424.5  408.52  5464.7  409.93  5512.1  413.84  5580.3   421.4  5620.6  423.46
    5642  426.19  5760.3   437.4  5822.4  441.02  5965.3  443.93  6136.7  444.31
#Mann= 6 ,-1 , 0
  4113.8     .16       0  4238.3     .05       0    4997    .033       0
    5003     .05       0    5642     .16       0  5965.3     .05       0
Bank Sta=4921.9,5303.7
XS Rating Curve= 0 ,0
Exp/Cntr=0.3,0.1

Type RM Length L Ch R = 1 ,7540    ,415,415,415
BEGIN DESCRIPTION:
NANNY BRANCH 11.0
END DESCRIPTION:
XS GIS Cut Line= 4
      3597845.23     10504181.74      3598303.61     10504046.31
      3598498.92     10503890.06      3598921.51      10503734.5
#Sta/Elev= 30
  4441.7  421.25  4568.4  415.17  4678.7  404.73    4712  403.69  4738.2   404.3
  4759.1  401.99  4778.6  402.89  4790.4  401.57  4811.2  400.94  4822.3  399.39
  4888.9  396.52  4894.6  395.18  4935.6  392.77    5147  392.74  5153.5  392.67
  5156.3  392.17  5159.5  392.67  5178.5  394.03  5215.7  395.79  5240.8  398.28
  5255.8  398.55  5326.8  404.34  5362.6  405.17  5382.4  407.14  5426.3  408.56
  5443.3  410.43  5448.7  409.41  5559.8  415.13  5565.2  414.47  5620.1  416.61
#Mann= 5 ,-1 , 0
  4441.7     .05       0    5147     .08       0  5153.5    .033       0
  5159.5     .08       0  5178.5     .05       0
Bank Sta=5153.5,5159.5
XS Rating Curve= 0 ,0
Exp/Cntr=0.3,0.1

Type RM Length L Ch R = 1 ,7125    ,78,78,78
BEGIN DESCRIPTION:
Mapping XS c4f05bfb
END DESCRIPTION:
XS GIS Cut Line= 4
      3598009.31     10504742.51      3598467.67     10504429.99
      3598700.31     10504256.38       3599054.5     10503905.66
#Sta/Elev= 30
  4339.4  427.68  4534.7  418.85  4543.6  415.67  4549.6  417.48  4557.6   417.6
  4600.5   414.6  4621.4  411.54  4651.3  410.07  4672.3  406.12  4702.1   403.4
  4765.1  394.42  4820.9  392.54  4823.6  392.04  4826.9  392.54  4830.8  393.67
  4836.9  392.63  5158.9  392.73  5205.4  395.34  5245.3  398.98  5301.5  404.15
  5322.7  404.39  5329.7  406.12  5379.3  407.55  5421.7  410.65  5478.3   415.6
  5513.6   420.5  5563.1  424.18  5612.6  427.45  5640.9   426.9  5682.9  430.23
#Mann= 5 ,-1 , 0
  4339.4     .05       0  4820.9    .033       0  4826.9     .05       0
  5205.4      .1       0  5245.3     .05       0
Bank Sta=4820.9,4826.9
XS Rating Curve= 0 ,0
Exp/Cntr=0.3,0.1

Type RM Length L Ch R = 1 ,7047    ,78,78,78
BEGIN DESCRIPTION:
Mapping XS 122f2098
END DESCRIPTION:
XS GIS Cut Line= 5
      3598053.19     10504836.48      3598501.12     10504490.12
      3598641.74     10504404.18      3598826.64     10504281.78
      3599151.67     10504034.76
#Sta/Elev= 30
  4329.2  426.03  4459.7  420.12  4544.9  418.28  4602.8  414.39  4609.2  416.21
  4615.5  415.92    4630  414.88  4638.1  411.16  4679.8  406.04  4687.9  402.91
  4734.7  399.85  4737.5  399.35  4740.7  399.85  4758.6  400.25  4766.7  402.43
  4929.4  404.38  5059.3  404.12  5076.1  402.65  5082.1  403.86  5112.2  403.13
  5154.3  404.03  5256.6   402.7  5356.9  407.08  5413.1  407.14  5421.3  408.73
  5442.1   409.2  5471.2  412.16  5492.1  412.77  5591.9  419.96  5690.2  429.08
#Mann= 3 ,-1 , 0
  4329.2     .05       0  4734.7     .03       0  4740.7     .05       0
Bank Sta=4734.7,4740.7
XS Rating Curve= 0 ,0
Exp/Cntr=0.3,0.1

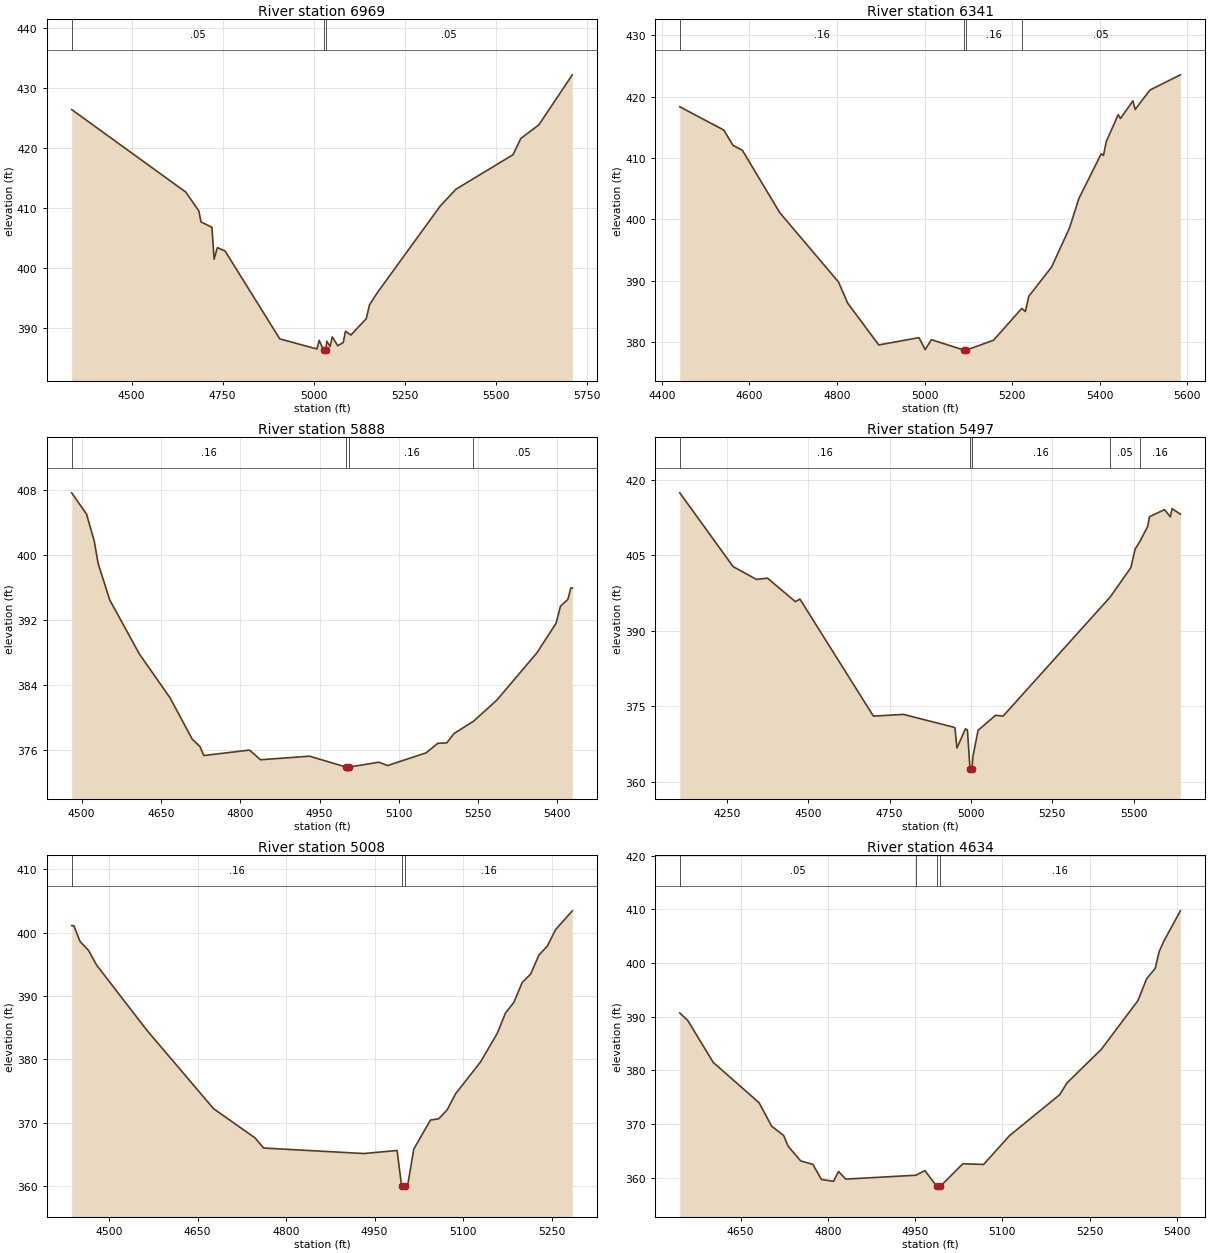
Type RM Length L Ch R = 1 ,6969    ,628,628,628
BEGIN DESCRIPTION:
NANNY BRANCH 10.0
END DESCRIPTION:
XS GIS Cut Line= 3
      3598076.62     10504870.34      3599011.54     10504247.93
      3599184.32     10504064.83
#Sta/Elev= 30
  4335.4  426.41  4648.4  412.65  4684.5  409.51  4690.5  407.65  4720.5  406.75
  4726.5  401.43  4735.4  403.37  4756.6   402.8  4906.9  388.13    5009  386.44
  5015.1  387.89  5027.1  386.25  5029.8  385.75  5033.1  386.25  5036.1  387.73
  5045.1  386.87  5051.1  388.47  5066.1  386.99  5081.2  387.52  5087.2   389.4
  5102.2  388.77  5144.3  391.49  5153.3  393.81  5174.3   395.8  5348.1  410.35
  5390.7  413.11  5547.6  418.88  5568.7  421.58  5618.4  423.86  5710.3  432.21
#Mann= 3 ,-1 , 0
  4335.4     .05       0  5027.1     .03       0  5033.1     .05       0
Bank Sta=5027.1,5033.1
XS Rating Curve= 0 ,0
Exp/Cntr=0.3,0.1

Type RM Length L Ch R = 1 ,6341    ,453,453,453
BEGIN DESCRIPTION:
NANNY BRANCH 9.0
END DESCRIPTION:
XS GIS Cut Line= 3
      3598571.85     10505374.42      3599045.79     10504934.33
      3599183.81     10504457.78
#Sta/Elev= 30
  4441.1  418.33  4541.6  414.54  4562.6  412.05  4584.1  411.24  4669.2  401.11
  4803.5   389.8  4824.5  386.36  4895.4  379.55  4987.2  380.74  5001.4  378.79
  5015.6  380.41  5089.6  378.72  5092.4  378.22  5095.6  378.72  5157.7  380.33
  5221.8   385.5  5230.1     385  5237.9  387.47    5290  392.24  5330.8  398.59
  5352.4  403.42  5403.2  410.67  5408.4   410.4  5414.9  412.68    5442  417.03
  5447.2  416.42  5475.6  419.29  5480.8   417.9  5514.4  421.04    5584  423.53
#Mann= 4 ,-1 , 0
  4441.1     .16       0  5089.6     .07       0  5095.6     .16       0
  5221.8     .05       0
Bank Sta=5089.6,5095.6
XS Rating Curve= 0 ,0
Exp/Cntr=0.3,0.1

Type RM Length L Ch R = 1 ,5888    ,391,391,391
BEGIN DESCRIPTION:
NANNY BRANCH 8.0
END DESCRIPTION:
XS GIS Cut Line= 3
      3598949.62     10505460.18      3599349.61     10505160.19
      3599749.61     10504960.19
#Sta/Elev= 30
  4481.1  407.67  4509.2  405.05  4523.8  401.72  4531.1  398.98    4553  394.49
  4609.2  387.82  4667.5  382.39  4709.2  377.33  4723.8  376.43  4731.1  375.32
  4817.5  375.99  4838.4   374.8  4931.1  375.24  5000.4   373.9  5003.2   373.4
  5006.4   373.9  5062.1   374.5  5078.9  374.09  5151.6  375.65  5173.9  376.83
  5190.7  376.88  5204.7  378.04  5241.3  379.54  5285.7  382.16  5361.2  387.96
  5397.6  391.61  5405.9  393.71  5419.9  394.55  5425.5  395.96  5428.3  395.96
#Mann= 4 ,-1 , 0
  4481.1     .16       0  5000.4     .07       0  5006.4     .16       0
  5241.3     .05       0
Bank Sta=5000.4,5006.4
XS Rating Curve= 0 ,0
Exp/Cntr=0.3,0.1

Type RM Length L Ch R = 1 ,5497    ,489,489,489
BEGIN DESCRIPTION:
NANNY BRANCH 7.0
END DESCRIPTION:
XS GIS Cut Line= 3
      3598699.93     10505655.56      3599540.18     10505461.12
      3600156.44     10505184.15
#Sta/Elev= 30
  4105.4  417.39  4269.3  402.75  4341.1   400.2  4375.1  400.45  4460.5  395.79
  4474.6   396.3  4700.4  373.07  4792.8  373.41  4945.7  370.89  4950.9  370.76
    4957  366.73    4983  370.55  4989.2  370.31  4997.1  362.65  4999.9  362.15
  5003.1  362.65  5006.2  365.09    5022  370.25  5075.6  373.23  5098.8  373.07
  5428.1  396.73  5491.3  402.54  5504.4  406.21  5519.1  407.76  5543.1  410.71
  5548.6  412.65  5594.9  414.06  5612.6  412.61  5618.1  414.25  5643.5  413.15
#Mann= 5 ,-1 , 0
  4105.4     .16       0  4997.1     .07       0  5003.1     .16       0
  5428.1     .05       0  5519.1     .16       0
Bank Sta=4997.1,5003.1
XS Rating Curve= 0 ,0
Exp/Cntr=0.3,0.1

Type RM Length L Ch R = 1 ,5008    ,374,374,374
BEGIN DESCRIPTION:
NANNY BRANCH 6.0
END DESCRIPTION:
XS GIS Cut Line= 3
      3599299.58     10506310.21      3599699.61     10505910.19
      3599899.63     10505710.16
#Sta/Elev= 30
  4436.6   401.1  4440.2   401.1  4450.8  398.59  4464.9  397.22  4479.1  394.84
  4563.9   384.6  4677.1   372.2  4747.8  367.56  4761.9  365.99  4931.6  365.12
  4988.2   365.6  4995.8     360  4998.5   359.5  5001.8     360  5005.9     360
  5016.5  365.83  5044.7   370.4  5058.9  370.62    5073  372.01  5087.2  374.54
  5129.6  379.58  5157.9  384.09    5172  387.32  5186.2     389  5200.3  392.14
  5214.5  393.44  5228.6  396.46  5242.7  397.86  5256.9  400.48  5285.2  403.44
#Mann= 3 ,-1 , 0
  4436.6     .16       0  4995.8     .07       0  5001.8     .16       0
Bank Sta=4995.8,5001.8
XS Rating Curve= 0 ,0
Exp/Cntr=0.3,0.1

Type RM Length L Ch R = 1 ,4634    ,542,542,542
BEGIN DESCRIPTION:
NANNY BRANCH 5.0
END DESCRIPTION:
XS GIS Cut Line= 3
      3599649.63     10506560.16      3599880.46     10506245.85
      3600149.63     10505860.16
#Sta/Elev= 30
  4545.5  390.71    4559  389.35  4602.9  381.51  4681.9  373.97  4703.3  369.62
  4724.1  367.86  4731.6  365.89  4753.4  363.13  4774.3  362.49  4788.9  359.68
  4809.8  359.34  4818.2  361.17  4830.8  359.75  4951.4  360.47  4966.8  361.34
  4987.1  358.38  4989.8  357.88  4993.1  358.38    5032   362.6  5067.7  362.48
  5112.2  367.85  5198.5  375.48  5210.8  377.66  5270.1  383.95  5332.9  393.02
  5347.7  397.06  5362.6  399.03  5369.2  402.12  5377.4  404.09  5405.8  409.74
#Mann= 4 ,-1 , 0
  4545.5     .05       0  4951.4     .16       0  4987.1     .07       0
  4993.1     .16       0
Bank Sta=4987.1,4993.1
XS Rating Curve= 0 ,0
Exp/Cntr=0.3,0.1

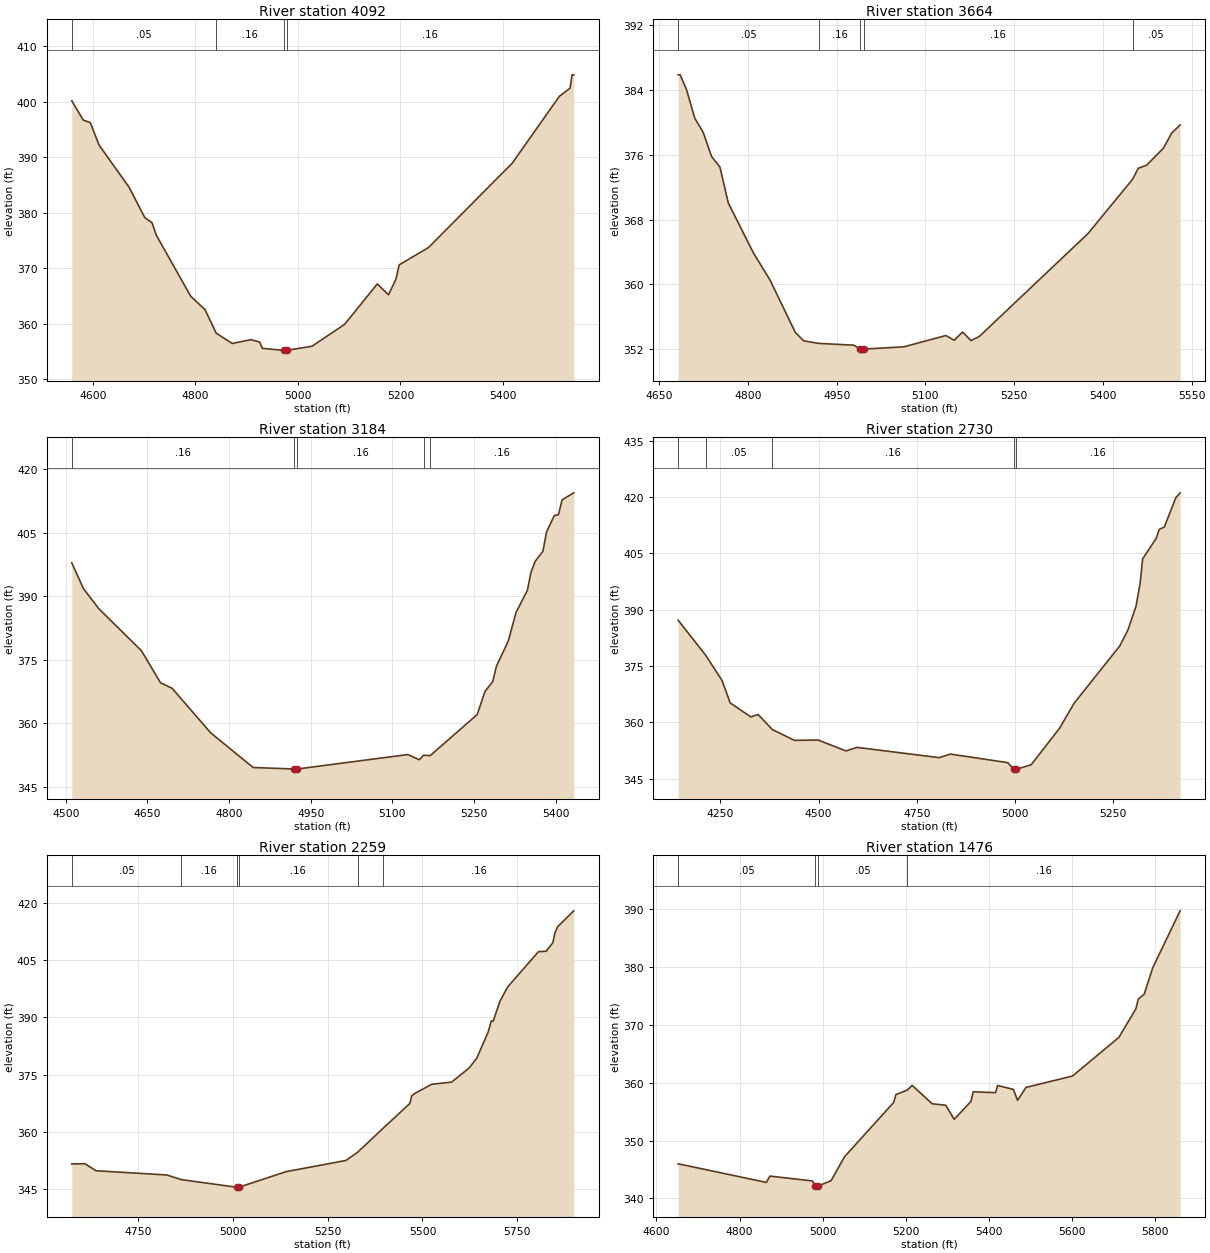
Type RM Length L Ch R = 1 ,4092    ,428,428,428
BEGIN DESCRIPTION:
NANNY BRANCH 4.0
END DESCRIPTION:
XS GIS Cut Line= 3
      3599749.65     10506860.17      3600149.61     10506660.19
      3600549.63     10506310.17
#Sta/Elev= 30
  4559.2  400.17  4581.5   396.7  4595.5   396.2  4612.3  392.19    4671  384.57
  4701.7  379.09  4715.7  378.18  4724.1  375.92  4791.1  364.93  4819.1   362.5
  4840.8  358.27  4872.2  356.41  4908.5   357.1  4925.3  356.68  4930.9  355.53
  4972.6  355.17  4975.4  354.67  4978.6  355.17  5027.7  355.92  5091.3  359.87
  5154.9  367.15  5176.7  365.19    5191  367.94  5197.6  370.58  5254.6   373.7
  5417.8  388.89  5509.9  400.97  5530.8  402.44  5534.6  404.84  5537.9  404.84
#Mann= 4 ,-1 , 0
  4559.2     .05       0  4840.8     .16       0  4972.6     .07       0
  4978.6     .16       0
Bank Sta=4972.6,4978.6
XS Rating Curve= 0 ,0
Exp/Cntr=0.3,0.1

Type RM Length L Ch R = 1 ,3664    ,480,480,480
BEGIN DESCRIPTION:
NANNY BRANCH 3.0
END DESCRIPTION:
XS GIS Cut Line= 3
      3599999.62     10507260.17      3600199.61     10507060.19
       3600599.6     10506660.19
#Sta/Elev= 30
    4682  385.84  4685.5  385.84  4696.1  384.03  4710.3  380.47  4724.4  378.75
  4738.5  375.78  4752.7  374.47  4766.8  370.05  4809.3  363.89  4837.5  360.53
    4880  354.11  4894.1  353.06  4919.6  352.74    4979  352.52  4990.1  352.04
  4992.9  351.54  4996.1  352.04  5063.8  352.32  5134.5  353.71  5148.7  353.13
  5162.8  354.14    5177  353.09  5191.1  353.59  5374.9  366.28  5450.1  372.96
  5459.8  374.32  5473.9   374.7  5502.2  376.79  5516.4  378.67  5530.5  379.66
#Mann= 5 ,-1 , 0
    4682     .05       0  4919.6     .16       0  4990.1     .07       0
  4996.1     .16       0  5450.1     .05       0
Bank Sta=4990.1,4996.1
XS Rating Curve= 0 ,0
Exp/Cntr=0.3,0.1

Type RM Length L Ch R = 1 ,3184    ,454,454,454
BEGIN DESCRIPTION:
NANNY BRANCH 2.0
END DESCRIPTION:
XS GIS Cut Line= 3
      3600199.59     10507710.21      3600499.61     10507360.19
      3600799.62     10507010.18
#Sta/Elev= 30
  4511.1  397.86  4532.5  391.78  4561.1  386.97    4639  377.11  4674.1  369.52
  4695.5  368.21  4766.3  357.69  4844.2  349.51  4919.2  349.15  4921.9  348.65
  4925.2  349.15  5128.5  352.57  5149.4  351.34  5157.3  352.42  5169.3   352.3
  5255.8  362.02  5270.1  367.46  5284.4  369.82    5291   373.4  5312.9   379.4
  5327.2  386.16    5348  391.37  5354.6  395.63  5362.3  398.21  5376.6  400.63
  5383.1  405.13  5397.4  409.02  5405.1  409.26  5411.7  412.73  5433.1  414.39
#Mann= 5 ,-1 , 0
  4511.1     .16       0  4919.2     .07       0  4925.2     .16       0
  5157.3     .05       0  5169.3     .16       0
Bank Sta=4919.2,4925.2
XS Rating Curve= 0 ,0
Exp/Cntr=0.3,0.1

Type RM Length L Ch R = 1 ,2730    ,471,471,471
BEGIN DESCRIPTION:
Mapping XS 0c3f1d75
END DESCRIPTION:
XS GIS Cut Line= 3
      3600269.32     10507718.07      3600873.51     10507606.96
       3601026.3     10506961.11
#Sta/Elev= 30
  4142.4  387.21  4212.5  377.88  4254.5  371.11  4274.9  365.19  4327.5  361.44
    4346   362.1  4382.4  358.07  4438.7   355.2  4498.6   355.3  4569.7  352.39
  4597.9  353.33  4807.4   350.6  4835.6  351.55  4981.6  349.27    4997  347.51
  4999.8  347.01    5003  347.51  5041.1  348.69  5113.6  358.43  5150.7  365.11
  5267.2  380.39  5287.8  384.64  5308.3  390.97  5318.6  396.98    5325  403.53
  5359.7  409.01  5367.2  411.39  5380.2     412  5409.5  419.79  5420.4  421.12
#Mann= 5 ,-1 , 0
  4142.4     .16       0  4212.5     .05       0  4382.4     .16       0
    4997     .07       0    5003     .16       0
Bank Sta=4997,5003
XS Rating Curve= 0 ,0
Exp/Cntr=0.3,0.1

Type RM Length L Ch R = 1 ,2259    ,783,783,783
BEGIN DESCRIPTION:
Mapping XS cbe599cb
END DESCRIPTION:
XS GIS Cut Line= 3
      3601067.95     10507808.35      3601554.07     10507127.79
      3601644.34     10506648.67
#Sta/Elev= 30
    4575  351.62  4609.7  351.67  4639.2  349.83    4826  348.72  4863.6  347.51
  5009.8  345.52  5012.5  345.02  5015.8  345.52  5140.6   349.6  5297.9  352.52
  5328.9  354.67  5397.1  361.03  5466.6  367.43  5471.7  369.44  5480.1  370.08
  5524.1  372.46  5576.6  373.02  5622.6  376.68    5643  379.27  5673.5   386.2
  5681.4     389  5686.5  388.98    5704  394.11  5724.4   397.9  5805.8  407.16
  5826.1  407.28  5843.9   409.5    5849     412  5856.6  413.72  5898.9  417.85
#Mann= 6 ,-1 , 0
    4575     .05       0  4863.6     .16       0  5009.8     .07       0
  5015.8     .16       0  5328.9     .05       0  5397.1     .16       0
Bank Sta=5009.8,5015.8
XS Rating Curve= 0 ,0
Exp/Cntr=0.3,0.1

Type RM Length L Ch R = 1 ,1476    ,0,0,0
BEGIN DESCRIPTION:
NANNY BRANCH 1.0
END DESCRIPTION:
XS GIS Cut Line= 3
       3601790.2     10507947.19      3602067.96     10507398.62
      3602172.12     10506815.33
#Sta/Elev= 30
  4652.2  345.99  4864.3  342.77    4873  343.86  4975.7  343.02  4982.1  342.11
  4984.9  341.61  4988.1  342.11  5020.2  343.07  5052.4   347.2  5170.6  356.58
  5176.2  357.95  5203.5  358.72  5215.1  359.53  5263.4  356.35    5296   356.1
  5316.3  353.67  5356.8  356.78  5361.9  358.42  5415.7  358.28  5420.8  359.51
  5458.5  358.84  5468.7  356.96    5489  359.18  5600.7  361.14  5712.4  367.82
  5753.1  372.73  5759.1  374.43  5773.4   375.3  5793.7  379.83  5859.6  389.68
#Mann= 4 ,-1 , 0
  4652.2     .05       0  4982.1     .03       0  4988.1     .05       0
  5203.5     .16       0
Bank Sta=4982.1,4988.1
XS Rating Curve= 0 ,0
Exp/Cntr=0.3,0.1

Chan Stop Cuts=-1
Use User Specified Reach Order=0
Composite Channel Slope=5