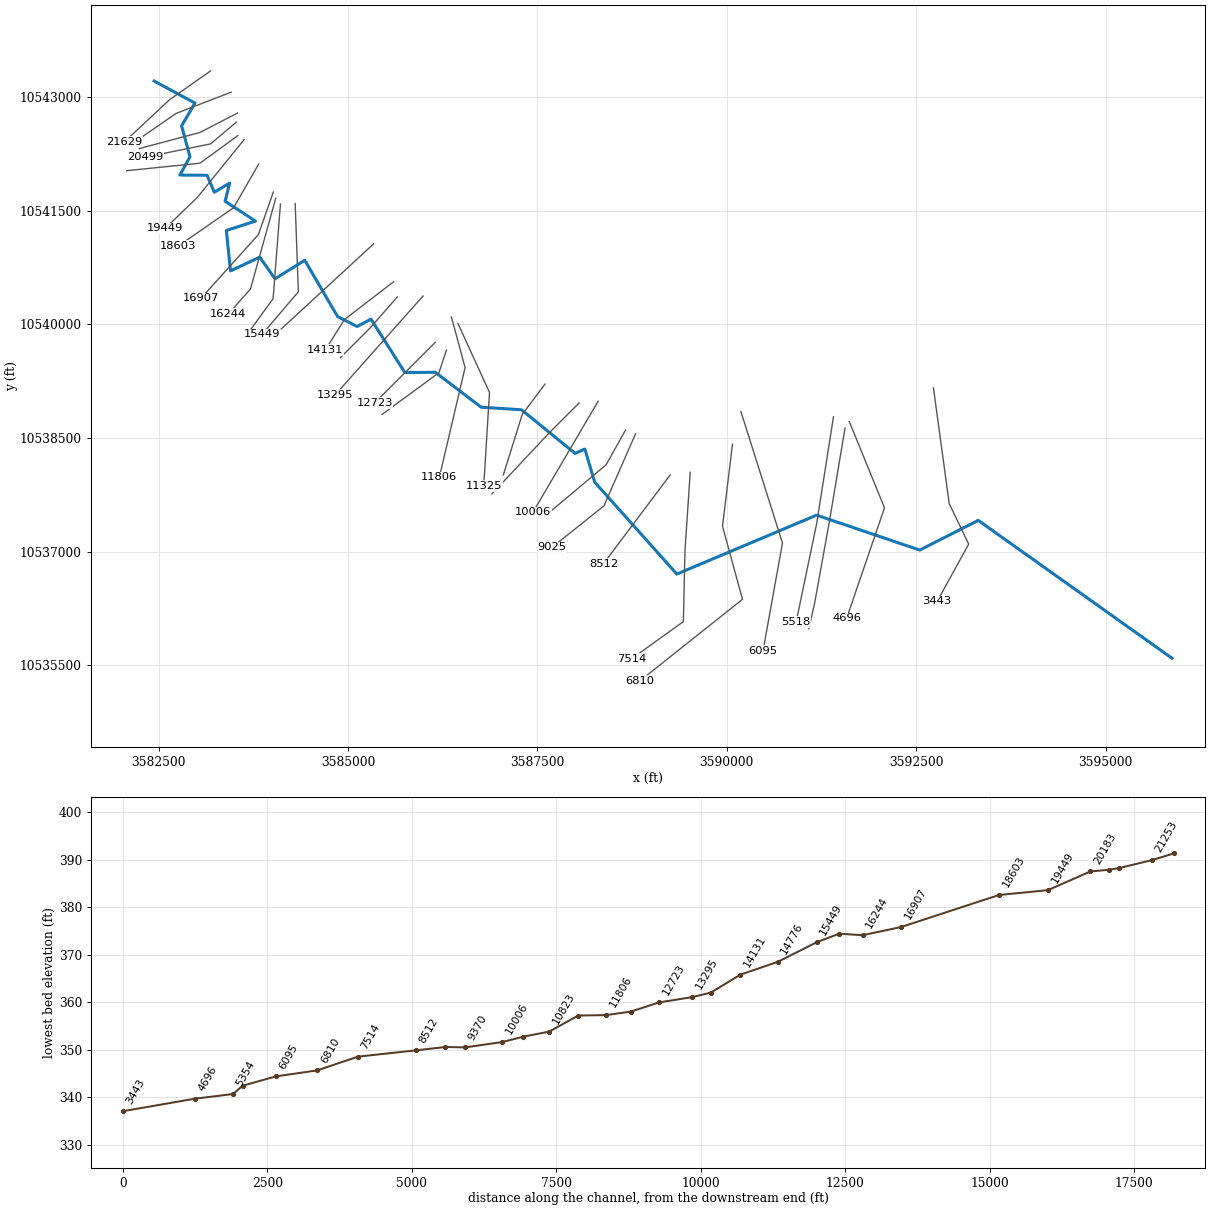
--- NORTH FORK BUFFALO CREEK.prj (project) ---

Proj Title=NORTH FORK BUFFALO CREEK Base Level Engineering
Current Plan=p01
Default Exp/Contr=0.3,0.1
English Units
Geom File=g01
Flow File=f01
Plan File=p01
Y Axis Title=Elevation
X Axis Title(PF)=Main Channel Distance
X Axis Title(XS)=Station
BEGIN DESCRIPTION:
NORTH FORK BUFFALO CREEK
END DESCRIPTION:
DSS Export Rating Curves= 0
DSS Export Rating Curve Sorted= 0
DSS Export Volume Flow Curves= 0
DXF OffsetX= 0
DXF OffsetY= 0
DXF ScaleX= 1
DXF ScaleY= 10

--- NORTH FORK BUFFALO CREEK.p01 (plan) ---

Plan Title=Multiple Run
Short Identifier=Multiple
Geom File=g01
Flow File=f01
Subcritical Flow
K Sum by GR= 0
Std Step Tol= 0.01
Critical Tol= 0.01
Num of Std Step Trials= 20
Max Error Tol= 0.3
Flow Tol Ratio= 0.001
Split Flow NTrial= 30
Split Flow Tol= 0.02
Split Flow Ratio= 0.02
Log Output Level= 0
Friction Slope Method= 1
Unsteady Friction Slope Method= 2
Unsteady Bridges Friction Slope Method= 1
Parabolic Critical Depth
Global Vel Dist=  1 , 1 , 1
Global Log Level= 0
CheckData=True
Encroach Param= -1, 0, 0, 0
BEGIN DESCRIPTION:
Multiple Run
END DESCRIPTION:

--- NORTH FORK BUFFALO CREEK.f01 (steady flow) ---

Flow Title=Multiple
Number of Profiles=7
Profile Names=10-year,25-year,50-year,1pct_min,100-year,1pct_plu,500-year
River Rch & RM= NORTH FORK BUFFA,Reach-1,21629
    1832    2597    3246    2955    3996    5405    6043
River Rch & RM= NORTH FORK BUFFA,Reach-1,13615
    2691    3880    4907    4513    6104    8255    9426
River Rch & RM= NORTH FORK BUFFA,Reach-1,9025
    3316    4802    6089    5610    7587   10261   11755
Boundary for River Rch & Prof#=NORTH FORK BUFFA,Reach-1,1
Up Type=0
Dn Type=3
Dn Slope=0.005
Boundary for River Rch & Prof#=NORTH FORK BUFFA,Reach-1,2
Up Type=0
Dn Type=3
Dn Slope=0.005
Boundary for River Rch & Prof#=NORTH FORK BUFFA,Reach-1,3
Up Type=0
Dn Type=3
Dn Slope=0.005
Boundary for River Rch & Prof#=NORTH FORK BUFFA,Reach-1,4
Up Type=0
Dn Type=3
Dn Slope=0.005
Boundary for River Rch & Prof#=NORTH FORK BUFFA,Reach-1,5
Up Type=0
Dn Type=3
Dn Slope=0.005
Boundary for River Rch & Prof#=NORTH FORK BUFFA,Reach-1,6
Up Type=0
Dn Type=3
Dn Slope=0.005
Boundary for River Rch & Prof#=NORTH FORK BUFFA,Reach-1,7
Up Type=0
Dn Type=3
Dn Slope=0.005

--- NORTH FORK BUFFALO CREEK.g01 (geometry) ---

Geom Title=Existing Conditions
Program Version=4.10

River Reach=NORTH FORK BUFFA,Reach-1
Reach XY= 30
      3582439.75       10543211.        3582979.       10542920.
      3582802.25       10542620.      3582912.75       10542210.
      3582779.75       10541970.      3583138.25       10541967.
        3583234.       10541744.      3583436.25       10541863.
        3583377.       10541624.       3583777.5       10541362.
      3583393.25       10541238.        3583448.       10540705.
      3583834.25       10540886.      3584035.25       10540600.
      3584428.25       10540845.      3584861.75       10540102.
       3585119.5       10539970.        3585302.       10540068.
        3585750.       10539362.      3586151.75       10539366.
      3586757.25       10538905.      3587290.25       10538871.
       3587997.5       10538295.        3588126.       10538353.
        3588255.       10537917.       3589340.5       10536702.
        3591185.       10537480.       3592547.5       10537019.
       3593319.5       10537411.       3595877.5       10535591.

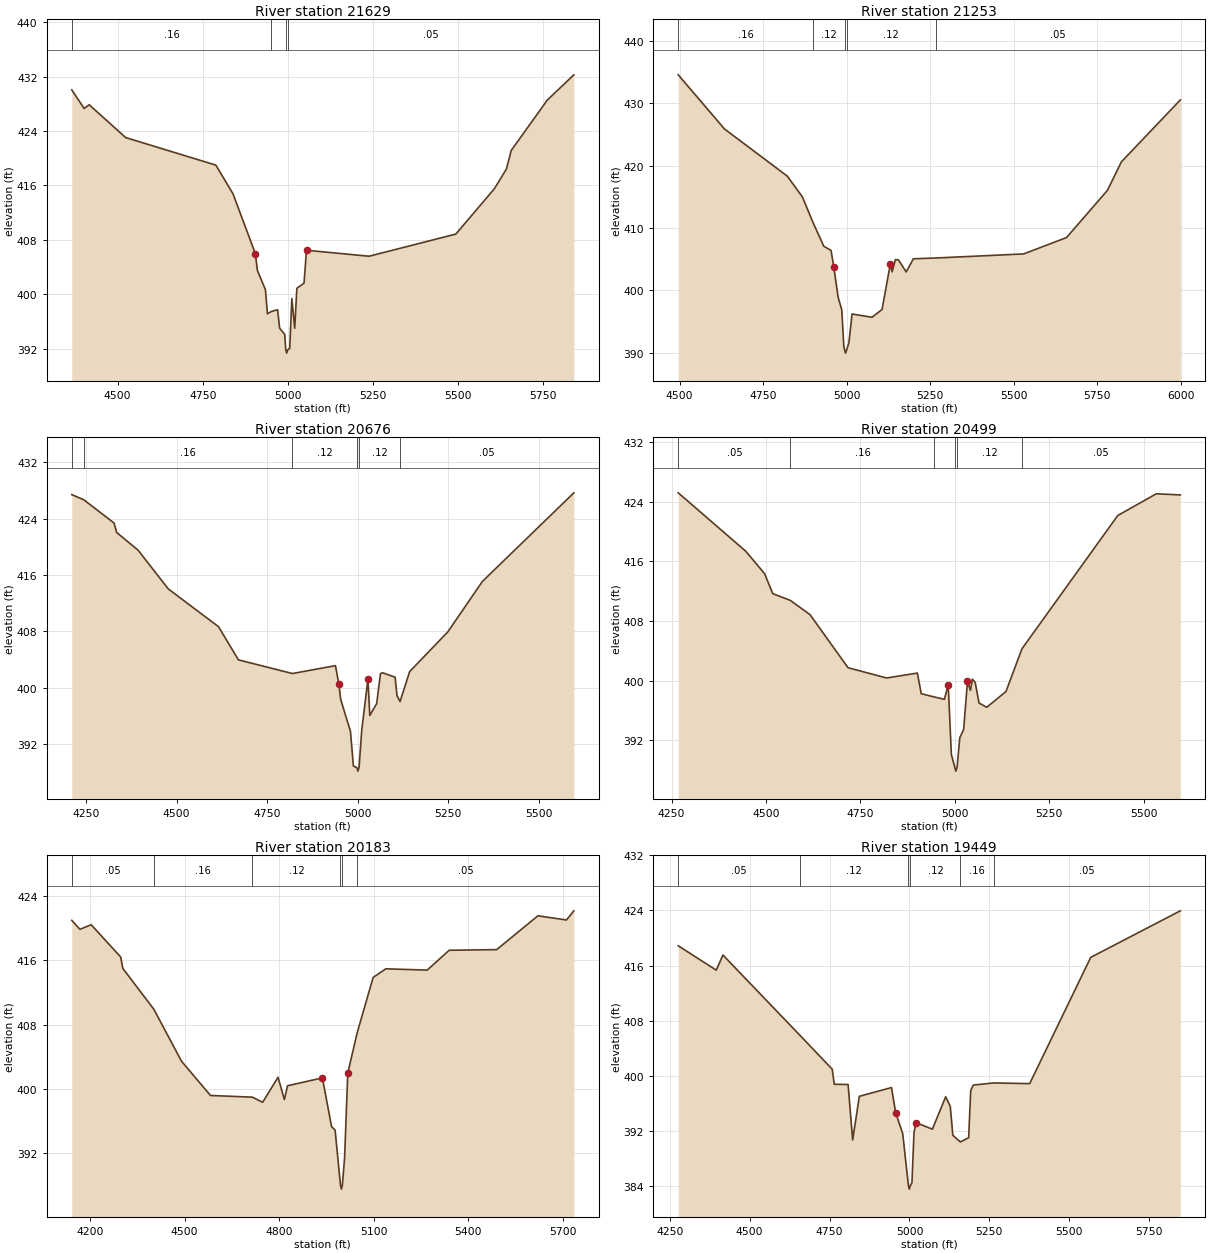
Type RM Length L Ch R = 1 ,21629   ,376,376,376
BEGIN DESCRIPTION:
NORTH FORK BUFFALO CREEK 26.0
END DESCRIPTION:
XS GIS Cut Line= 3
      3583185.62      10543345.2      3582643.93     10542964.97
      3582049.63     10542410.21
#Sta/Elev= 30
  4365.2  430.04  4401.6   427.3  4416.4  427.85  4523.6  423.02  4788.5  418.97
    4839  414.73  4904.4  405.96  4910.5  403.47    4934  400.66  4940.1   397.1
  4951.3  397.44  4969.8  397.71  4975.9  394.97  4990.7  394.09  4993.8  391.82
  4996.5  391.32  4999.8  391.82  5005.5  392.02  5011.6  399.34  5020.1  394.98
  5026.4  400.86  5047.4  401.61  5054.7  406.45  5238.4  405.57  5493.4  408.83
  5606.8  415.51  5641.9  418.39  5656.1  421.13  5762.1  428.54    5840  432.25
#Mann= 4 ,-1 , 0
  4365.2     .16       0  4951.3     .12       0  4993.8     .03       0
  4999.8     .05       0
Bank Sta=4904.4,5054.7
XS Rating Curve= 0 ,0
Exp/Cntr=0.3,0.1

Type RM Length L Ch R = 1 ,21253   ,577,577,577
BEGIN DESCRIPTION:
NORTH FORK BUFFALO CREEK 25.0
END DESCRIPTION:
XS GIS Cut Line= 3
      3583456.41     10543063.93      3582727.26     10542782.68
      3582134.08     10542371.62
#Sta/Elev= 30
  4496.2  434.59  4634.5  425.91  4822.9  418.32  4867.9     415  4900.3  410.81
  4932.1  407.07  4953.7  406.41    4962  403.71  4975.1  398.86  4985.8  396.88
    4992  390.95  4994.4  390.42  4997.1  389.92  5000.4  390.42  5007.2   391.6
  5016.6   396.2  5076.6  395.68  5106.5  396.94  5131.2  404.22  5136.5  402.97
  5146.6  404.94  5155.8  404.87  5178.7  402.95  5200.2  405.06  5267.6  405.19
  5530.4  405.84  5658.8  408.47  5781.1  416.04    5823  420.62  5999.4  430.56
#Mann= 5 ,-1 , 0
  4496.2     .16       0  4900.3     .12       0  4994.4     .07       0
  5000.4     .12       0  5267.6     .05       0
Bank Sta=4962,5131.2
XS Rating Curve= 0 ,0
Exp/Cntr=0.3,0.1

Type RM Length L Ch R = 1 ,20676   ,177,177,177
BEGIN DESCRIPTION:
NORTH FORK BUFFALO CREEK 24.0
END DESCRIPTION:
XS GIS Cut Line= 3
       3583539.8     10542787.91      3583044.97     10542532.68
      3582243.75     10542319.37
#Sta/Elev= 30
  4210.7   427.4  4244.1  426.66  4327.4  423.37  4334.7  422.03  4393.9  419.52
  4476.9  414.04    4616  408.67  4670.7  403.98  4819.7  402.04  4938.6  403.16
  4947.9  400.57  4953.1  398.36    4980  393.85  4988.1  388.93  4997.7  388.71
  5000.4  388.21  5003.7  388.71    5011  393.94  5028.2  401.24  5033.4   396.1
  5052.4  397.78  5062.8  402.01  5068.3  402.16  5103.3  401.52  5108.4  398.93
  5116.9  398.07  5143.4  402.32    5249  407.96  5344.1  415.09  5596.6  427.65
#Mann= 6 ,-1 , 0
  4210.7     .05       0  4244.1     .16       0  4819.7     .12       0
  4997.7     .07       0  5003.7     .12       0  5116.9     .05       0
Bank Sta=4947.9,5028.2
XS Rating Curve= 0 ,0
Exp/Cntr=0.3,0.1

Type RM Length L Ch R = 1 ,20499   ,316,316,316
BEGIN DESCRIPTION:
NORTH FORK BUFFALO CREEK 23.0
END DESCRIPTION:
XS GIS Cut Line= 3
      3583524.17     10542668.13      3583185.59     10542381.64
      3582317.33     10542204.87
#Sta/Elev= 30
  4267.7  425.19  4446.5  417.36  4496.4  414.35    4518  411.67  4564.8  410.76
  4616.8  408.85  4717.3  401.74  4819.4  400.36    4901  401.02  4911.2  398.25
  4946.2  397.81  4972.5   397.5  4982.7  399.41    4991  390.12  5000.1  388.37
  5002.8  387.87  5006.1  388.37  5013.3  392.34  5023.5  393.45  5033.7  399.91
  5041.5   398.7  5046.7  400.21  5054.1  399.76  5064.3     397  5084.7  396.43
  5135.7  398.55  5177.9  404.27  5431.7  422.15  5533.7  425.06  5597.3  424.91
#Mann= 6 ,-1 , 0
  4267.7     .05       0  4564.8     .16       0  4946.2     .12       0
  5000.1     .07       0  5006.1     .12       0  5177.9     .05       0
Bank Sta=4982.7,5033.7
XS Rating Curve= 0 ,0
Exp/Cntr=0.3,0.1

Type RM Length L Ch R = 1 ,20183   ,734,734,734
BEGIN DESCRIPTION:
NORTH FORK BUFFALO CREEK 22.0
END DESCRIPTION:
XS GIS Cut Line= 3
      3583544.96     10542491.01      3583044.97     10542126.43
      3582076.21     10542027.47
#Sta/Elev= 30
    4142  420.97    4168  419.86  4203.6  420.43  4297.1  416.41    4304  414.99
  4402.1  409.92  4490.2  403.43  4582.1  399.17  4715.1  398.96  4747.4  398.32
  4796.3  401.44  4816.4  398.66  4826.5  400.38  4937.1  401.36    4966   395.3
  4977.3  394.86  4994.4  388.01  4997.1  387.51  5000.4  388.01  5007.4  391.42
  5017.5  401.95  5047.2  406.96  5097.9  413.86  5138.1  414.94  5269.4  414.78
  5339.2  417.25  5489.9  417.33  5620.6  421.54  5711.1  421.02  5734.6  422.16
#Mann= 6 ,-1 , 0
    4142     .05       0  4402.1     .16       0  4715.1     .12       0
  4994.4     .07       0  5000.4     .12       0  5047.2     .05       0
Bank Sta=4937.1,5017.5
XS Rating Curve= 0 ,0
Exp/Cntr=0.3,0.1

Type RM Length L Ch R = 1 ,19449   ,846,846,846
BEGIN DESCRIPTION:
NORTH FORK BUFFALO CREEK 21.0
END DESCRIPTION:
XS GIS Cut Line= 3
      3583628.32     10542438.96      3583008.51     10541673.31
      3582586.61     10541267.03
#Sta/Elev= 30
  4276.6  418.87  4395.5  415.34  4416.5  417.53  4658.3  405.84  4758.4  400.97
  4764.8  398.79    4808  398.75  4822.3  390.71  4843.2  397.04  4943.8  398.31
  4956.9  394.66    4979  391.61  4996.8  384.08  4999.6  383.58  5002.8  384.08
  5007.8   384.5  5014.2   391.8  5021.2  393.21  5071.7  392.27  5113.3  396.97
  5127.7  395.57  5135.7  391.39  5159.4  390.42  5185.2  391.04  5191.7  397.87
  5199.6  398.67  5263.6  398.98  5376.2  398.88  5567.1  417.19  5847.4  423.94
#Mann= 6 ,-1 , 0
  4276.6     .05       0  4658.3     .12       0  4996.8     .07       0
  5002.8     .12       0  5159.4     .16       0  5263.6     .05       0
Bank Sta=4956.9,5021.2
XS Rating Curve= 0 ,0
Exp/Cntr=0.3,0.1

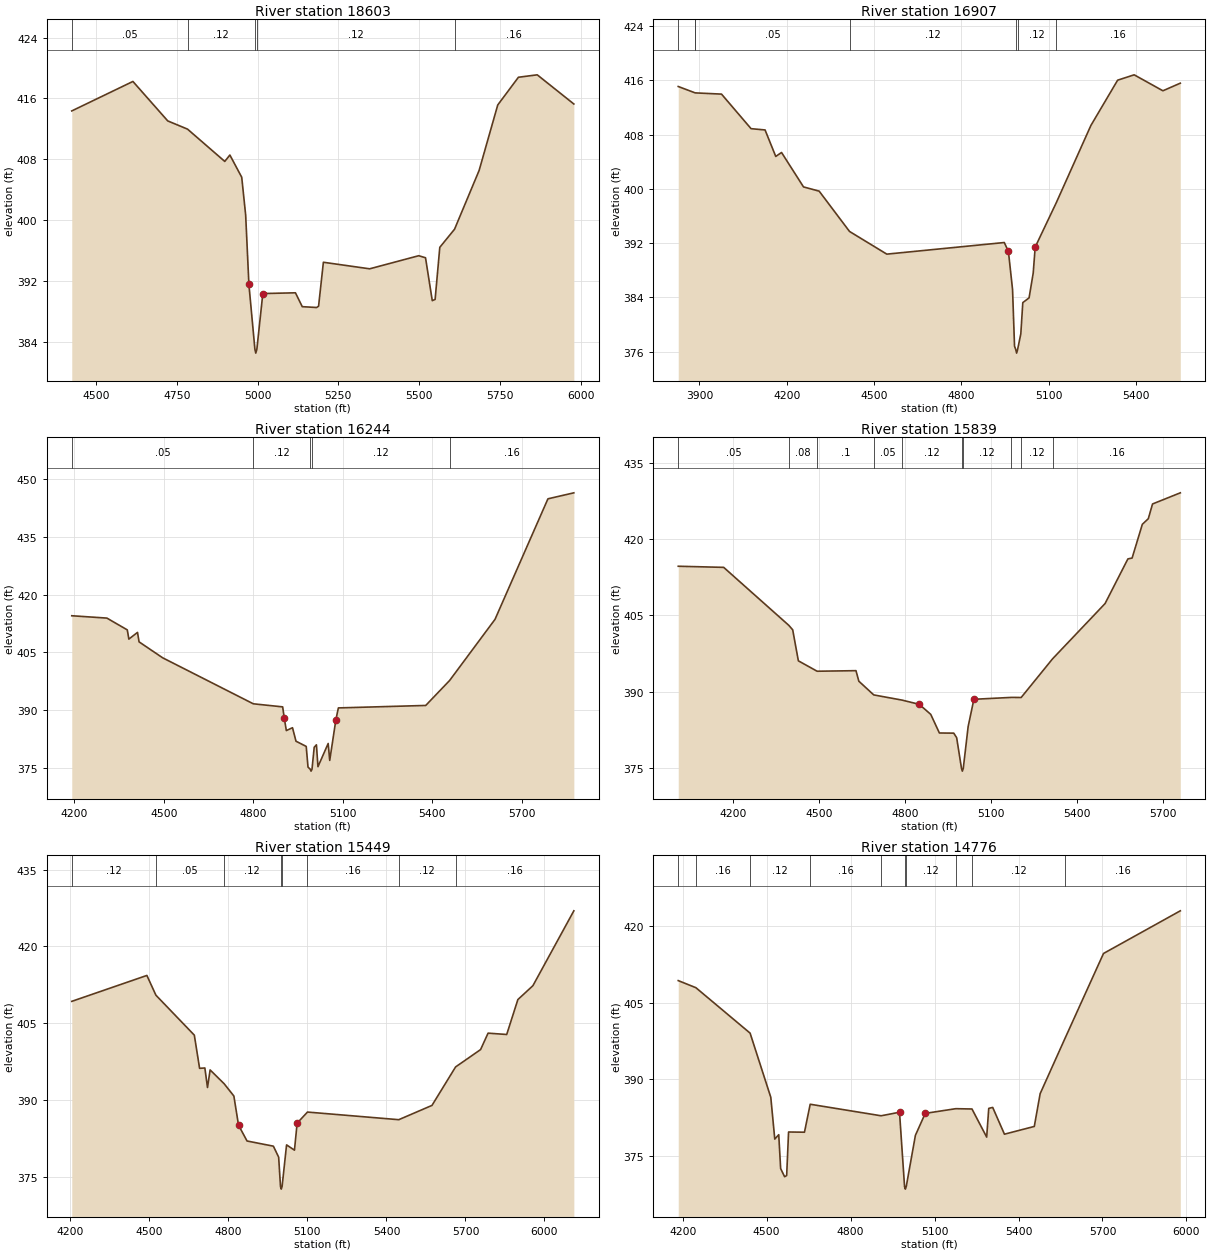
Type RM Length L Ch R = 1 ,18603   ,1696,1696,1696
BEGIN DESCRIPTION:
NORTH FORK BUFFALO CREEK 20.0
END DESCRIPTION:
XS GIS Cut Line= 3
      3583821.01       10542116.      3583487.68     10541537.89
      3582758.52     10541032.69
#Sta/Elev= 30
  4424.7  414.36    4614  418.23  4721.8  413.05  4783.1  411.97  4898.4  407.73
  4914.2  408.57  4950.9  405.65  4963.1  400.67  4973.1  391.58  4991.7  383.06
  4994.4  382.56  4997.7  383.06  5016.2  390.38  5117.2  390.48  5138.3  388.66
  5182.7  388.55  5188.8  388.72  5203.7  394.49  5346.9  393.63  5498.9  395.35
  5519.9  395.08  5540.8  389.45  5549.6  389.61  5564.1  396.45  5609.8  398.83
  5685.8  406.54  5743.5  415.14  5807.5  418.78  5865.8   419.1  5979.1  415.27
#Mann= 5 ,-1 , 0
  4424.7     .05       0  4783.1     .12       0  4991.7     .07       0
  4997.7     .12       0  5609.8     .16       0
Bank Sta=4973.1,5016.2
XS Rating Curve= 0 ,0
Exp/Cntr=0.3,0.1

Type RM Length L Ch R = 1 ,16907   ,663,663,663
BEGIN DESCRIPTION:
NORTH FORK BUFFALO CREEK 19.0
END DESCRIPTION:
XS GIS Cut Line= 3
      3584013.72     10541746.23       3583815.8     10541183.72
       3583060.6     10540345.18
#Sta/Elev= 30
  3827.3  415.07  3884.3  414.15  3885.7  414.13    3976  413.95  4077.5  408.86
  4125.6  408.67  4162.3  404.77  4182.2  405.35  4257.7  400.28  4311.4  399.66
  4415.8  393.72  4543.8  390.38  4947.4  392.09  4961.6  390.77  4975.8  385.17
  4982.6  376.82    4987   376.3  4989.8   375.8    4993   376.3  5004.2  378.64
    5011  383.24  5032.6  383.94  5046.8  387.61  5053.6  391.42  5126.2  397.97
  5244.9  409.33  5336.8     416  5393.6  416.79  5492.3  414.44  5552.1  415.56
#Mann= 7 ,-1 , 0
  3827.3     .05       0  3884.3     .08       0  3885.7     .05       0
  4415.8     .12       0    4987     .07       0    4993     .12       0
  5126.2     .16       0
Bank Sta=4961.6,5053.6
XS Rating Curve= 0 ,0
Exp/Cntr=0.3,0.1

Type RM Length L Ch R = 1 ,16244   ,405,405,405
BEGIN DESCRIPTION:
NORTH FORK BUFFALO CREEK 18.0
END DESCRIPTION:
XS GIS Cut Line= 3
      3584044.96     10541662.85      3583711.64     10540464.97
      3583419.97     10540136.85
#Sta/Elev= 30
  4191.9   414.5  4309.6  413.89    4378  410.82  4383.2  408.43  4412.2  410.17
  4417.4  407.71  4496.3  403.57  4800.2   391.6  4898.6   390.8  4903.8  387.97
  4910.9  384.64  4931.6  385.38  4943.2  381.87  4977.5  380.52  4983.5  375.14
  4990.9  374.59  4993.7  374.09  4996.9  374.59  5004.3  380.31  5011.7  380.93
  5016.9  375.24  5051.1  381.28  5056.3  376.88    5077   387.5  5085.3  390.53
    5378  391.17  5458.2  397.68  5610.2  413.57  5787.5  444.91  5874.3  446.47
#Mann= 5 ,-1 , 0
  4191.9     .05       0  4800.2     .12       0  4990.9     .07       0
  4996.9     .12       0  5458.2     .16       0
Bank Sta=4903.8,5077
XS Rating Curve= 0 ,0
Exp/Cntr=0.3,0.1

Type RM Length L Ch R = 1 ,15839   ,390,390,390
BEGIN DESCRIPTION:
NORTH FORK BUFFALO CREEK 17.0
END DESCRIPTION:
XS GIS Cut Line= 3
      3584107.47     10541588.22      3584010.25     10540338.24
      3583718.61      10539935.5
#Sta/Elev= 30
  4008.8  414.65  4167.3  414.43  4394.5  403.04    4408  402.16  4427.8  396.07
  4493.2  394.03  4628.7  394.14  4638.7  392.07  4690.6  389.38  4789.3  388.36
  4849.4  387.53  4889.5  385.55  4919.6   381.9  4969.7  381.87  4979.8  380.98
  4996.8  374.91  4999.6  374.41  5002.8  374.91  5019.9  383.17  5039.9  388.52
  5170.9  388.89  5204.8  388.87  5314.2  396.46  5497.4  407.32    5577  416.09
  5591.7  416.26  5627.3  422.88  5648.2  423.99  5662.9  426.88  5759.8  429.07
#Mann= 10 ,-1 , 0
  4008.8     .05       0  4394.5     .08       0  4493.2      .1       0
  4690.6     .05       0  4789.3     .12       0  4996.8     .07       0
  5002.8     .12       0  5170.9     .16       0  5204.8     .12       0
  5314.2     .16       0
Bank Sta=4849.4,5039.9
XS Rating Curve= 0 ,0
Exp/Cntr=0.3,0.1

Type RM Length L Ch R = 1 ,15449   ,673,673,673
BEGIN DESCRIPTION:
NORTH FORK BUFFALO CREEK 16.0
END DESCRIPTION:
XS GIS Cut Line= 3
      3584301.91     10541595.19      3584343.58     10540428.51
      3583864.51     10539866.13
#Sta/Elev= 30
  4205.3  409.27  4490.5  414.33  4524.7  410.48  4670.6  402.67  4690.6  396.19
  4710.6  396.26  4720.6  392.45  4730.6  395.88  4783.8  393.18  4820.7  390.79
  4838.4   385.1  4870.7     382  4970.8  380.99  4990.8  378.84  4997.8   373.1
  5000.6   372.6  5003.8   373.1  5020.8  381.24  5050.8  380.21  5060.9  385.48
  5100.2  387.65  5446.8  386.16  5572.9  388.95  5662.5  396.46  5757.4  399.85
  5785.9  403.06  5856.6   402.8    5899  409.62  5956.1  412.33  6111.5  426.95
#Mann= 8 ,-1 , 0
  4205.3     .12       0  4524.7     .05       0  4783.8     .12       0
  4997.8     .07       0  5003.8     .12       0  5100.2     .16       0
  5446.8     .12       0  5662.5     .16       0
Bank Sta=4838.4,5060.9
XS Rating Curve= 0 ,0
Exp/Cntr=0.3,0.1

Type RM Length L Ch R = 1 ,14776   ,645,645,645
BEGIN DESCRIPTION:
NORTH FORK BUFFALO CREEK 15.0
END DESCRIPTION:
XS GIS Cut Line= 2
      3585336.61     10541060.43      3584017.18     10539845.17
#Sta/Elev= 30
  4184.3  409.36  4247.4  407.97  4441.1  399.06    4515  386.48  4529.2  378.29
  4543.4  379.15  4550.2  372.51  4564.4  370.91  4571.7  371.14  4578.5  379.68
  4635.3  379.64  4655.8  385.12  4909.1  382.86  4974.9  383.55  4992.9  368.98
  4995.7  368.48  4998.9  368.98  5031.7  379.03  5066.8  383.33    5176  384.25
  5233.8  384.19  5286.3  378.68  5293.7  384.31  5307.8   384.5  5349.8  379.25
  5456.4  380.77  5477.4   387.2  5565.3  397.93  5703.7  414.68  5978.1  423.04
#Mann= 10 ,-1 , 0
  4184.3     .05       0  4247.4     .16       0  4441.1     .12       0
  4655.8     .16       0  4909.1     .12       0  4992.9     .07       0
  4998.9     .12       0    5176     .16       0  5233.8     .12       0
  5565.3     .16       0
Bank Sta=4974.9,5066.8
XS Rating Curve= 0 ,0
Exp/Cntr=0.3,0.1

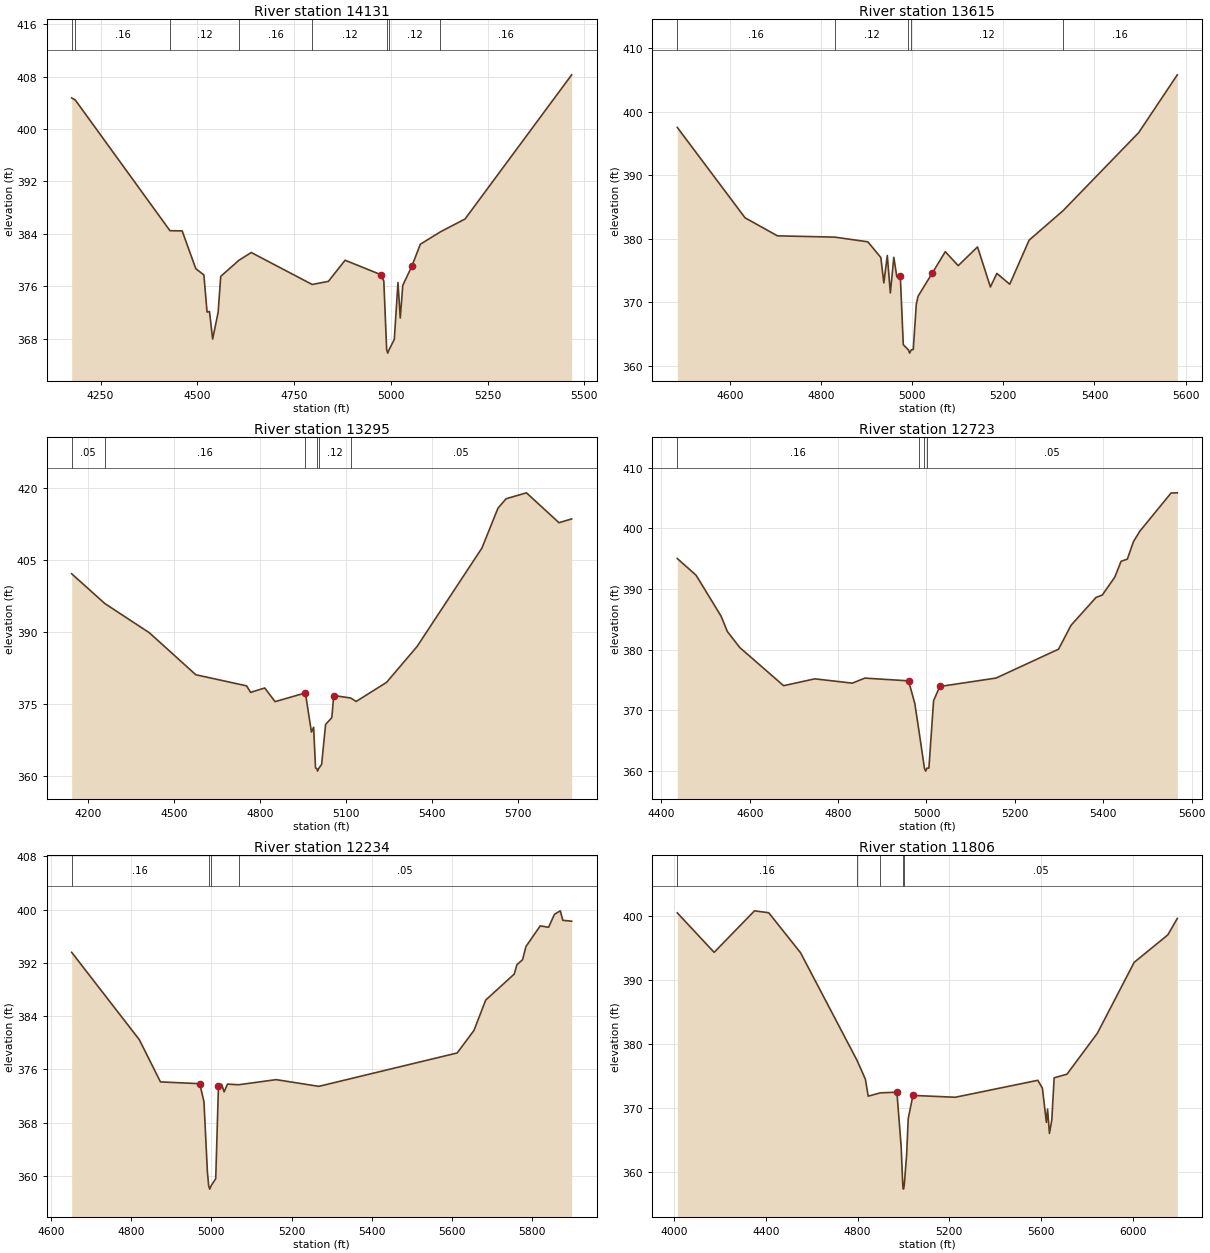
Type RM Length L Ch R = 1 ,14131   ,516,516,516
BEGIN DESCRIPTION:
NORTH FORK BUFFALO CREEK 14.0
END DESCRIPTION:
XS GIS Cut Line= 3
      3585599.62      10540560.2      3584949.61     10540060.19
       3584699.6     10539660.17
#Sta/Elev= 30
  4175.4  404.76  4184.7  404.45  4429.4  384.48  4460.9  384.45  4496.2  378.67
    4517  377.73  4525.2  372.06  4531.5  372.13  4539.7  367.93  4553.9  372.04
  4560.5   377.5  4607.5  379.96  4639.4  381.15  4796.7  376.27  4838.7  376.74
  4881.9  379.97  4973.7  377.78  4981.9   376.8  4989.3  366.28  4992.1  365.78
  4995.3  366.28    5009  367.87  5018.5  376.57  5024.4  371.15  5030.9  376.13
  5054.4  379.06  5076.3  382.42  5128.3  384.31  5191.8  386.27  5467.2  408.29
#Mann= 8 ,-1 , 0
  4175.4     .05       0  4184.7     .16       0  4429.4     .12       0
  4607.5     .16       0  4796.7     .12       0  4989.3     .07       0
  4995.3     .12       0  5128.3     .16       0
Bank Sta=4973.7,5054.4
XS Rating Curve= 0 ,0
Exp/Cntr=0.3,0.1

Type RM Length L Ch R = 1 ,13615   ,320,320,320
BEGIN DESCRIPTION:
NORTH FORK BUFFALO CREEK 13.0
END DESCRIPTION:
XS GIS Cut Line= 3
      3585649.63     10540360.21      3585299.61     10539960.19
      3584899.62      10539560.2
#Sta/Elev= 30
  4484.6  397.49  4633.2  383.28  4704.3  380.44    4830  380.24  4902.7   379.5
  4931.2  377.03  4937.8  373.04  4945.4  377.34  4952.1  371.46  4959.7  377.07
  4966.3  373.99  4973.9   374.2  4980.5  363.32  4991.8  362.49  4994.5  361.99
  4997.8  362.49  5002.4  362.56    5009  369.64  5012.8  370.93  5044.4  374.62
  5072.7  377.95    5101  375.75  5143.4   378.7  5171.7   372.4  5185.8  374.53
  5214.1  372.83  5256.6  379.76  5331.3  384.41    5497  396.67  5581.8  405.77
#Mann= 5 ,-1 , 0
  4484.6     .16       0    4830     .12       0  4991.8     .07       0
  4997.8     .12       0  5331.3     .16       0
Bank Sta=4973.9,5044.4
XS Rating Curve= 0 ,0
Exp/Cntr=0.3,0.1

Type RM Length L Ch R = 1 ,13295   ,572,572,572
BEGIN DESCRIPTION:
NORTH FORK BUFFALO CREEK 12.0
END DESCRIPTION:
XS GIS Cut Line= 2
      3585989.41     10540372.96      3584829.67     10539067.37
#Sta/Elev= 30
  4141.7   402.2  4257.5     396  4412.9  389.91  4575.3  381.15  4752.6  378.83
  4766.8  377.47  4816.2  378.39  4852.1  375.54    4956  377.32  4958.3  377.26
  4979.2   369.2  4986.8  370.19  4993.5  361.71    4998  361.55  5000.7  361.05
    5004  361.55  5014.8  362.47  5028.6  370.79  5050.3  372.19    5057  376.81
  5116.5   376.3  5135.2  375.57  5241.8  379.57    5348  387.03  5574.7  407.57
  5630.7  415.88  5659.1  417.85  5730.2  419.08  5843.9  412.85    5888  413.64
#Mann= 6 ,-1 , 0
  4141.7     .05       0  4257.5     .16       0    4956     .12       0
    4998     .07       0    5004     .12       0  5116.5     .05       0
Bank Sta=4958.3,5057
XS Rating Curve= 0 ,0
Exp/Cntr=0.3,0.1

Type RM Length L Ch R = 1 ,12723   ,489,489,489
BEGIN DESCRIPTION:
NORTH FORK BUFFALO CREEK 11.0
END DESCRIPTION:
XS GIS Cut Line= 3
      3586149.63     10539760.21      3585749.61     10539360.19
      3585349.61     10538960.19
#Sta/Elev= 30
  4436.2  395.04  4478.7  392.28  4535.2  385.53  4549.4  382.99  4577.7  380.33
  4676.7  374.04  4747.4  375.17  4832.2  374.46  4860.5  375.29  4959.5  374.84
  4973.6   371.1  4983.2  366.48  4995.4  360.43  4998.1  359.93  5001.4  360.43
  5005.5  360.43  5016.1  371.57  5030.2  373.91  5157.5   375.3  5298.9  380.07
  5327.2  384.02  5383.8  388.62  5397.9  389.01  5426.2  391.97  5440.3  394.58
  5454.5  394.94  5468.6  397.86  5482.8  399.55  5553.5  405.86  5567.6  405.89
#Mann= 4 ,-1 , 0
  4436.2     .16       0  4983.2     .05       0  4995.4     .03       0
  5001.4     .05       0
Bank Sta=4959.5,5030.2
XS Rating Curve= 0 ,0
Exp/Cntr=0.3,0.1

Type RM Length L Ch R = 1 ,12234   ,428,428,428
BEGIN DESCRIPTION:
NORTH FORK BUFFALO CREEK 10.0
END DESCRIPTION:
XS GIS Cut Line= 3
      3586299.62     10539660.23      3586199.61     10539360.19
      3585449.63     10538810.21
#Sta/Elev= 30
  4651.6  393.58  4820.3  380.45    4873  374.11    4971  373.84  4981.4  371.11
  4989.9  360.67  4993.1   358.5  4995.8     358  4999.1   358.5  5010.7  359.57
  5017.5  373.42  5025.4  373.76  5031.6  372.61    5040  373.78  5067.6  373.68
  5161.2  374.45  5267.7  373.44  5612.7  378.46  5654.4  381.84  5683.7   386.4
  5754.8  390.31  5761.5  391.72  5775.6  392.47  5784.1  394.46  5819.6  397.55
  5840.4  397.34  5855.1  399.29  5869.7  399.81  5875.9  398.39  5897.9  398.25
#Mann= 4 ,-1 , 0
  4651.6     .16       0  4993.1     .07       0  4999.1     .16       0
  5067.6     .05       0
Bank Sta=4971,5017.5
XS Rating Curve= 0 ,0
Exp/Cntr=0.3,0.1

Type RM Length L Ch R = 1 ,11806   ,481,481,481
BEGIN DESCRIPTION:
NORTH FORK BUFFALO CREEK 9.0
END DESCRIPTION:
XS GIS Cut Line= 3
       3586364.4     10540095.23      3586544.97     10539428.51
      3586204.69      10537977.1
#Sta/Elev= 30
  4013.8  400.44  4174.4  394.27  4350.5  400.76  4412.7  400.46  4551.4  394.21
  4797.9  377.39  4834.4  374.44  4846.6  371.79  4899.6  372.31    4972  372.41
  4990.4  363.92  4997.7  357.76  5000.4  357.26  5003.7  357.76  5014.4  362.68
  5021.2  368.27  5041.8  371.91  5226.6  371.62  5586.8  374.27  5606.7  373.04
  5624.1  367.69  5629.2  369.77  5637.5  365.97  5647.8  368.11    5658  374.66
  5714.1  375.23  5846.6  381.63  6007.2  392.71    6154     397  6195.3  399.57
#Mann= 5 ,-1 , 0
  4013.8     .16       0  4797.9     .12       0  4899.6     .16       0
  4997.7     .07       0  5003.7     .05       0
Bank Sta=4972,5041.8
XS Rating Curve= 0 ,0
Exp/Cntr=0.3,0.1

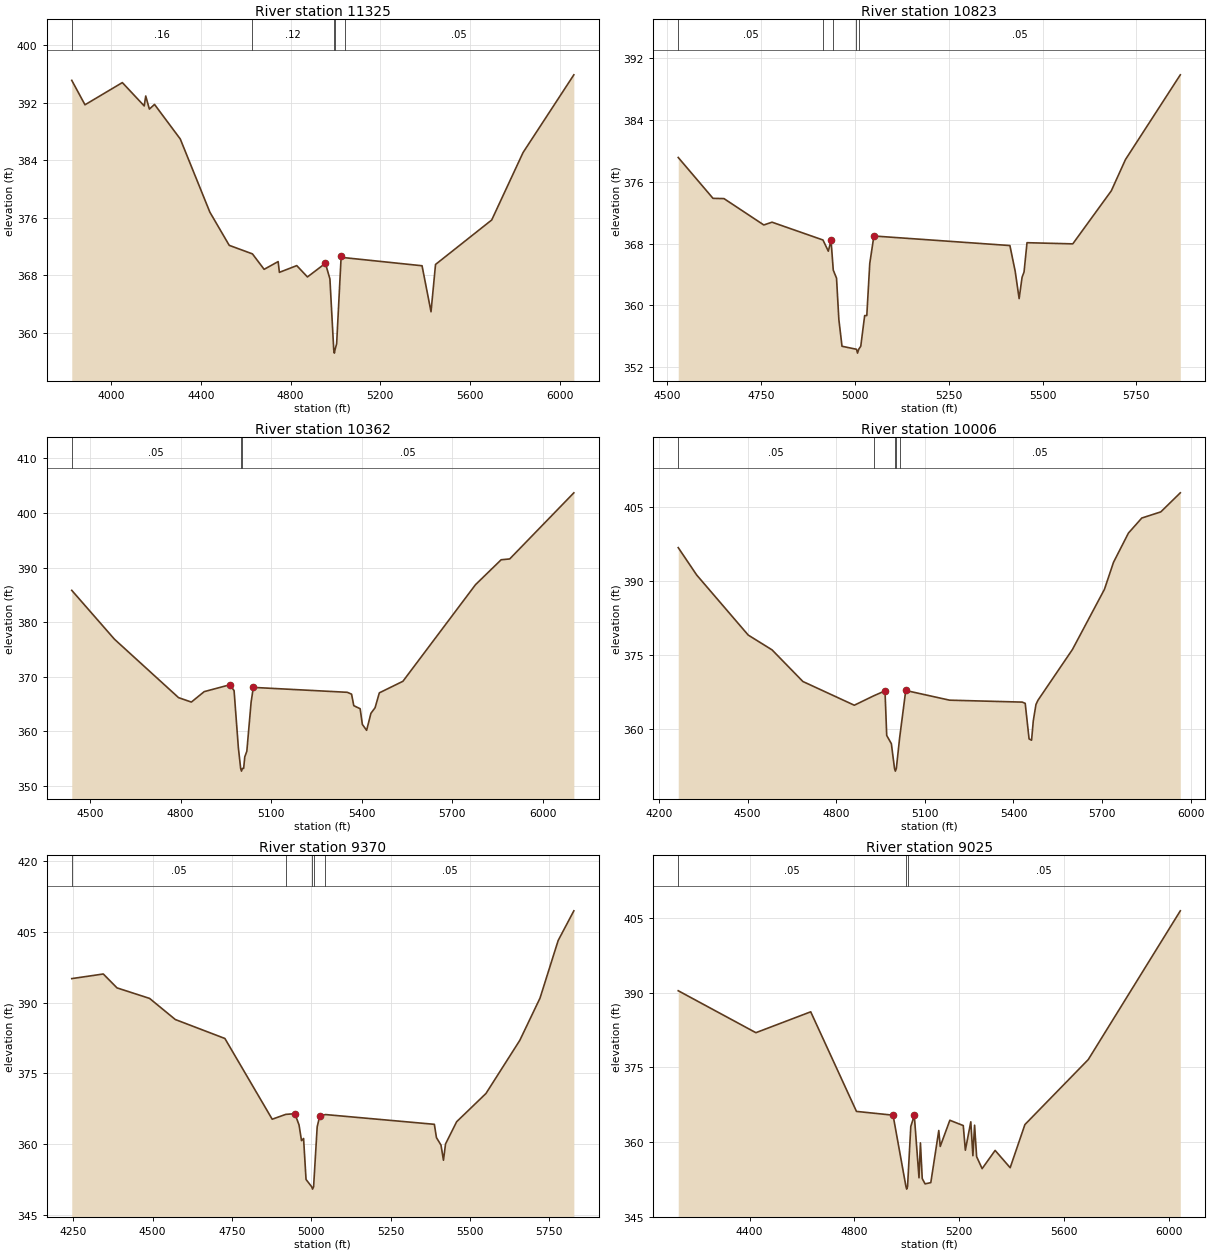
Type RM Length L Ch R = 1 ,11325   ,502,502,502
BEGIN DESCRIPTION:
NORTH FORK BUFFALO CREEK 8.0
END DESCRIPTION:
XS GIS Cut Line= 3
      3586450.62       10540010.       3586867.3     10539100.25
      3586790.94     10537864.64
#Sta/Elev= 30
  3824.7  395.13  3883.7  391.73  4050.2  394.82  4147.7  391.57  4154.5  392.95
  4170.7  391.13  4193.7  391.78  4308.5  386.97  4440.4  376.79  4526.8  372.17
  4630.3  370.98  4682.4  368.83  4744.9  369.91  4750.4  368.41  4827.9  369.35
  4875.5  367.77  4955.6  369.67  4975.7  367.49  4992.7  357.67  4995.5  357.17
  4998.7  357.67  5005.7  358.47  5025.8  370.62  5041.4  370.45  5386.5  369.33
  5426.5  362.93  5446.6  369.51  5697.1   375.7    5837  385.09  6063.3   395.9
#Mann= 5 ,-1 , 0
  3824.7     .16       0  4630.3     .12       0  4992.7     .07       0
  4998.7     .12       0  5041.4     .05       0
Bank Sta=4955.6,5025.8
XS Rating Curve= 0 ,0
Exp/Cntr=0.3,0.1

Type RM Length L Ch R = 1 ,10823   ,461,461,461
BEGIN DESCRIPTION:
NORTH FORK BUFFALO CREEK 7.0
END DESCRIPTION:
XS GIS Cut Line= 3
      3587599.61     10539210.19      3587299.61     10538810.19
       3587049.6     10538010.15
#Sta/Elev= 30
  4529.1  379.16  4621.8  373.86    4651  373.83  4757.2  370.41  4779.1  370.77
  4914.9  368.46  4929.1  367.01  4936.4   368.4  4942.3  364.56    4951  363.51
  4957.2  358.16  4965.6  354.68  5004.2  354.29    5007  353.79  5010.2  354.29
  5015.6  354.68    5026  358.66  5031.7  358.66  5039.6  365.42  5050.6  368.98
  5413.1  367.74  5427.2  364.41  5437.7  360.86  5445.6  363.64  5450.8  364.31
  5458.7  368.11  5580.7  367.96  5683.4  374.84  5721.1  378.89  5867.3  389.88
#Mann= 5 ,-1 , 0
  4529.1     .05       0  4914.9     .12       0  4942.3     .05       0
  5004.2    .035       0  5010.2     .05       0
Bank Sta=4936.4,5050.6
XS Rating Curve= 0 ,0
Exp/Cntr=0.3,0.1

Type RM Length L Ch R = 1 ,10362   ,356,356,356
BEGIN DESCRIPTION:
NORTH FORK BUFFALO CREEK 6.0
END DESCRIPTION:
XS GIS Cut Line= 3
      3588049.62      10538960.2      3587649.61     10538560.19
       3586899.6     10537760.18
#Sta/Elev= 30
  4439.9  385.82  4581.3  376.86  4793.5  366.15  4835.9  365.34  4878.3  367.25
  4963.2  368.51  4977.3  367.44  4991.5  356.95  4999.1  353.18  5001.8  352.68
  5005.1  353.18    5009  353.18  5012.7   355.3  5019.5  356.32  5033.7  365.33
    5041  368.03  5352.2  367.13  5366.3  366.79  5373.6  364.68  5394.7  364.12
    5402  361.24  5416.1  360.16  5430.3  363.27  5444.2  364.31  5458.2  367.03
  5536.3  369.15  5776.6  386.86  5861.6  391.43  5889.9  391.58  6102.2   403.7
#Mann= 3 ,-1 , 0
  4439.9     .05       0  4999.1    .035       0  5005.1     .05       0
Bank Sta=4963.2,5041
XS Rating Curve= 0 ,0
Exp/Cntr=0.3,0.1

Type RM Length L Ch R = 1 ,10006   ,636,636,636
BEGIN DESCRIPTION:
NORTH FORK BUFFALO CREEK 5.0
END DESCRIPTION:
XS GIS Cut Line= 2
      3588301.89     10538984.03      3587440.82     10537518.82
#Sta/Elev= 30
  4265.2  396.72  4327.7  391.19  4502.1  379.06  4582.8  376.07  4687.2  369.68
  4861.2  364.89  4927.2   366.8  4965.1  367.79  4970.9  358.78  4986.6  357.13
  4997.4  352.08  5000.1  351.58  5003.4  352.08  5014.6  358.28  5035.3  367.87
  5183.8  365.91  5429.8  365.52  5439.7  365.26  5452.8  358.08  5461.2  357.82
    5467  361.72    5476  365.02  5482.6  365.87  5599.8  376.17  5707.9   388.3
  5738.5  393.75  5789.1  399.66  5834.3   402.7  5898.7  403.94  5964.7  407.79
#Mann= 5 ,-1 , 0
  4265.2     .05       0  4927.2     .16       0  4997.4     .07       0
  5003.4     .16       0  5014.6     .05       0
Bank Sta=4965.1,5035.3
XS Rating Curve= 0 ,0
Exp/Cntr=0.3,0.1

Type RM Length L Ch R = 1 ,9370    ,345,345,345
BEGIN DESCRIPTION:
NORTH FORK BUFFALO CREEK 4.0
END DESCRIPTION:
XS GIS Cut Line= 3
      3588663.03     10538602.14      3588406.08     10538143.79
      3587595.28     10537464.66
#Sta/Elev= 30
    4245  395.12  4344.4   396.1  4387.7  393.15  4490.4  390.92  4571.5  386.44
  4727.8  382.42    4877  365.29  4919.8  366.32  4948.5  366.46  4961.6  364.07
  4969.4  360.75  4975.9   361.2  4983.7  352.51  5001.5  350.96  5004.3  350.46
  5007.5  350.96  5018.8  363.66  5026.6  365.91  5044.7  366.28  5388.3  364.21
  5394.9  361.38  5409.2  359.81    5417  356.59  5423.5  360.04  5458.6  364.76
    5551  370.75  5657.7  382.02  5721.4  390.98  5778.7  403.21  5828.1   409.5
#Mann= 5 ,-1 , 0
    4245     .05       0  4919.8     .16       0  5001.5     .07       0
  5007.5     .16       0  5044.7     .05       0
Bank Sta=4948.5,5026.6
XS Rating Curve= 0 ,0
Exp/Cntr=0.3,0.1

Type RM Length L Ch R = 1 ,9025    ,513,513,513
BEGIN DESCRIPTION:
NORTH FORK BUFFALO CREEK 3.0
END DESCRIPTION:
XS GIS Cut Line= 3
      3588794.98     10538553.53       3588378.3     10537602.13
      3587691.82     10537054.33
#Sta/Elev= 30
  4127.5  390.36    4424  381.94  4633.3  386.13    4808  366.14  4947.7  365.38
    4997  351.04  4999.7  350.54    5003  351.04  5015.4  363.12  5028.8  365.33
  5046.7  352.82  5052.2  359.82  5059.1  352.66    5070  351.59  5091.8  351.85
  5122.3  362.31  5127.8  359.11  5164.5  364.36  5215.7   363.3  5223.7  358.35
  5244.5  364.05  5252.5  357.24  5258.9  363.37  5266.8  357.05  5287.8  354.65
  5337.4  358.31  5394.8  354.84  5451.1   363.5  5692.9  376.54  6044.4   406.4
#Mann= 3 ,-1 , 0
  4127.5     .05       0    4997     .03       0    5003     .05       0
Bank Sta=4947.7,5028.8
XS Rating Curve= 0 ,0
Exp/Cntr=0.3,0.1

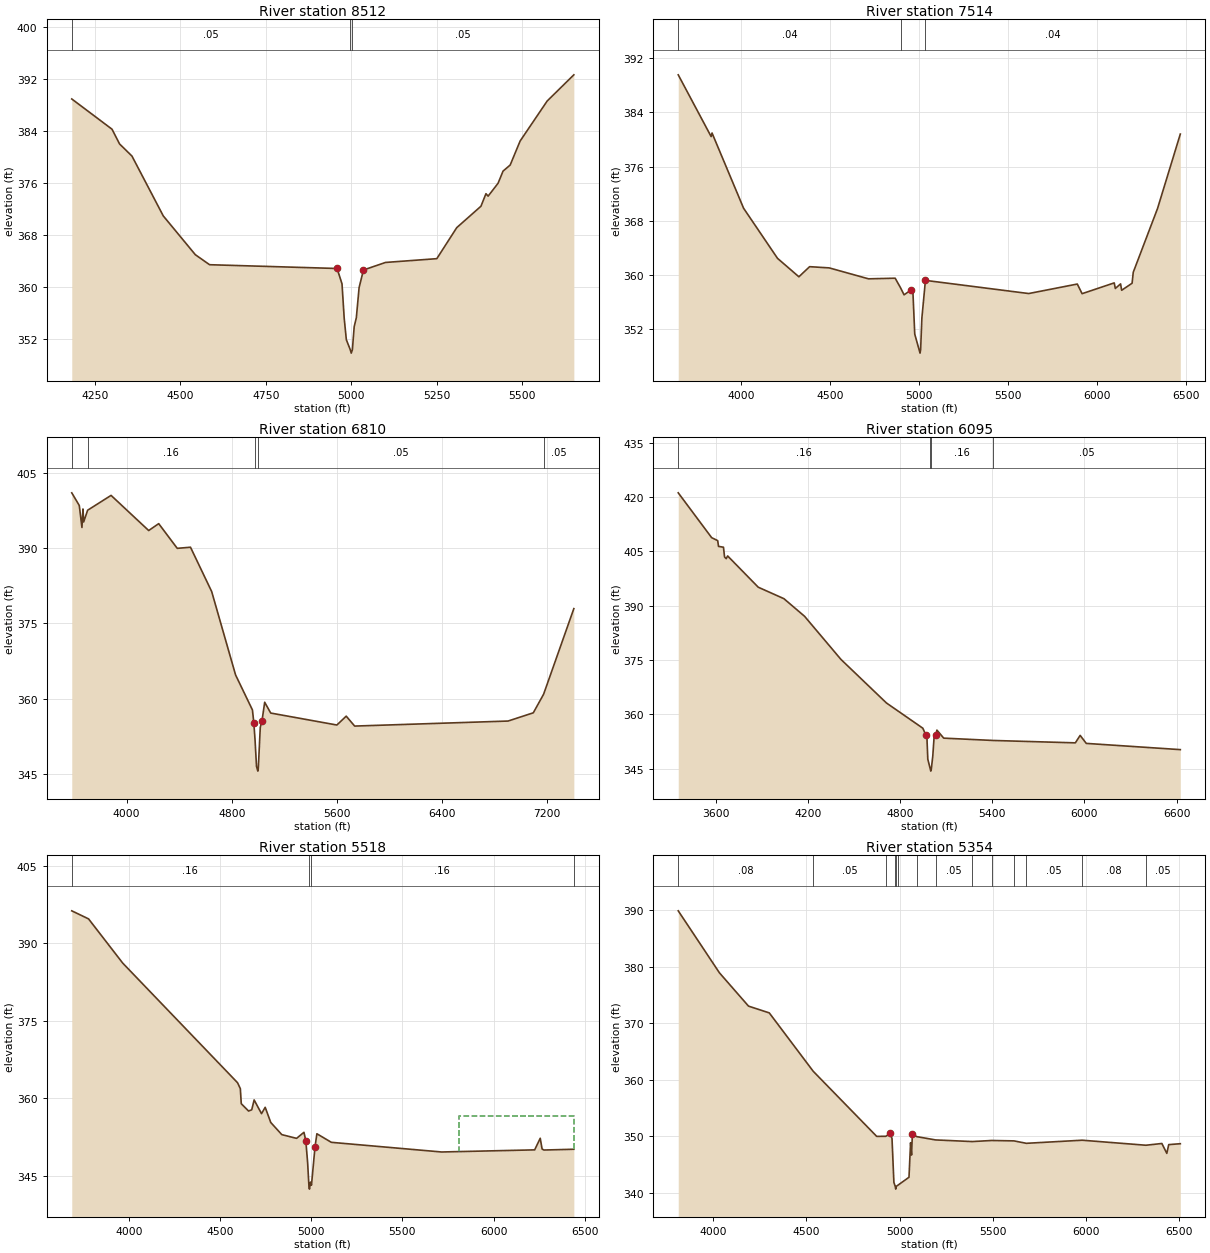
Type RM Length L Ch R = 1 ,8512    ,998,998,998
BEGIN DESCRIPTION:
NORTH FORK BUFFALO CREEK 2.0
END DESCRIPTION:
XS GIS Cut Line= 2
      3589253.33     10538011.88      3588371.36     10536838.24
#Sta/Elev= 30
  4182.8   388.9  4300.5  384.25  4322.5  381.99  4358.8  380.12  4450.4  370.92
  4544.1  364.96  4585.8  363.42  4958.6  362.84    4973  360.48  4979.4   355.2
  4985.7  351.89  4997.3  350.33    5000  349.83  5003.3  350.33  5008.6  353.89
  5014.9  355.27    5023  359.91  5035.7  362.61  5100.3  363.77  5250.2  364.35
  5308.5  369.12  5379.3  372.41  5393.9  374.34  5400.2  373.96  5429.3  375.94
  5443.9  377.81  5464.7  378.74  5493.9  382.44    5573  388.59  5650.9  392.61
#Mann= 3 ,-1 , 0
  4182.8     .05       0  4997.3     .03       0  5003.3     .05       0
Bank Sta=4958.6,5035.7
XS Rating Curve= 0 ,0
Exp/Cntr=0.3,0.1

Type RM Length L Ch R = 1 ,7514    ,704,704,704
BEGIN DESCRIPTION:
Mapping XS 187db470
END DESCRIPTION:
XS GIS Cut Line= 4
      3589517.19     10538046.61      3589447.75     10537011.85
      3589426.91     10536074.35      3588739.45     10535581.32
#Sta/Elev= 30
  3645.6  389.52  3830.5  380.42  3835.5  380.95  4012.8  369.86  4203.3  362.48
  4323.5  359.76  4383.7  361.25  4493.9  361.07  4714.4  359.46  4864.4  359.55
  4894.4  358.15  4914.4   357.1  4954.4  357.83  4964.4  357.35  4974.4  351.31
  5004.2  348.51  5007.4  349.01  5014.4  353.66  5034.4  359.23  5614.6  357.29
  5887.6  358.69  5914.6  357.27  6095.1  358.86  6101.3  358.04  6130.8  358.71
  6136.9  357.77  6195.5  358.81    6202  360.42  6338.3  369.81  6466.4  380.79
#Mann= 3 ,-1 , 0
  3645.6     .04       0  4894.4     .03       0  5034.4     .04       0
Bank Sta=4954.4,5034.4
XS Rating Curve= 0 ,0
Exp/Cntr=0.3,0.1

Type RM Length L Ch R = 1 ,6810    ,715,715,715
BEGIN DESCRIPTION:
Mapping XS 3be1e4d4
END DESCRIPTION:
XS GIS Cut Line= 4
       3590075.3     10538417.05      3589943.36     10537333.72
      3590207.25     10536368.44      3588853.85     10535292.66
#Sta/Elev= 30
  3582.4  400.97  3639.7  398.44  3659.8  394.08  3667.8  397.76  3672.9  395.18
  3703.2  397.51  3881.5  400.46  4167.8  393.47  4244.1  394.84  4385.1  389.93
  4485.9  390.15  4647.1  381.34  4828.9  364.76  4957.3  357.79  4967.7  355.28
  4977.3  351.78  4988.4  346.55  4998.5  345.62  5001.8  346.12    5017  354.33
  5029.9  355.59  5050.6  359.32  5096.4  357.17    5600  354.79  5670.9  356.55
  5735.3  354.58  6902.6  355.58  7094.8  357.22  7173.3  360.92  7403.3  377.94
#Mann= 5 ,-1 , 0
  3582.4     .04       0  3703.2     .16       0  4977.3     .03       0
  5001.8     .05       0  7173.3     .05       0
Bank Sta=4967.7,5029.9
XS Rating Curve= 0 ,0
Exp/Cntr=0.3,0.1

Type RM Length L Ch R = 1 ,6095    ,577,577,577
BEGIN DESCRIPTION:
Mapping XS dda3bb73
END DESCRIPTION:
XS GIS Cut Line= 3
      3590186.42     10538847.59      3590735.02      10537111.5
      3590478.08      10535687.9
#Sta/Elev= 30
  3356.8  421.13  3574.3  408.76  3613.7  407.94  3618.9  406.36  3651.2  406.12
  3658.2  403.44  3668.7  402.96  3678.3  403.72  3877.5  395.09  4044.4  391.93
  4178.9  387.07  4415.7  375.17  4711.8  363.15  4948.6  356.19  4969.1  354.19
  4975.7  353.06  4980.9  347.64  4997.6  344.85  5000.3  344.35  5003.6  344.85
  5013.3  348.51  5021.6  353.59  5032.1  354.34  5040.3  355.66  5084.5  353.45
  5406.3  352.81    5941  352.15  5972.3  354.21  6012.1     352  6624.1  350.28
#Mann= 4 ,-1 , 0
  3356.8     .16       0  4997.6     .05       0  5003.6     .16       0
  5406.3     .05       0
Bank Sta=4969.1,5032.1
XS Rating Curve= 0 ,0
Exp/Cntr=0.3,0.1

Type RM Length L Ch R = 1 ,5518    ,164,164,164
BEGIN DESCRIPTION:
Mapping XS 982e002d
END DESCRIPTION:
XS GIS Cut Line= 3
      3591408.63     10538778.15      3591186.41     10537368.44
      3590915.57      10536069.8
#Sta/Elev= 30
  3686.8  396.27  3778.9  394.71  3966.3  386.15  4595.8     363  4611.4  361.84
  4616.4  358.93  4656.6  357.51  4673.9  357.75    4687  359.66  4727.5     357
  4747.7  358.23  4778.1   355.3  4838.8  352.94  4919.8  352.22  4960.3  353.39
  4970.4  351.77  4980.5  347.49  4987.7  342.89  4990.4  342.39  4996.4  343.75
  5001.5  343.15    5021   350.6  5031.2  353.11  5110.5  351.45  5715.2  349.58
  6225.6  349.99  6256.2  352.24  6266.4  350.15  6276.7  349.96  6440.5  350.11
#Mann= 4 ,-1 , 0
  3686.8     .16       0  4987.7     .05       0  4996.4     .16       0
  6440.5     .05       0
#XS Ineff= 1 ,-1
 5812.78    6500 356.521
Permanent Ineff=
       F
Bank Sta=4970.4,5021
XS Rating Curve= 0 ,0
Exp/Cntr=0.3,0.1

Type RM Length L Ch R = 1 ,5354    ,658,658,658
BEGIN DESCRIPTION:
Mapping XS 118d0449
END DESCRIPTION:
XS GIS Cut Line= 4
      3591561.42     10538632.35      3591353.08     10537389.28
      3591158.64     10536312.89      3591082.25     10535979.55
#Sta/Elev= 30
  3811.3  389.91  4032.7  378.93  4188.7  373.04  4300.2  371.84  4536.3   361.5
    4877  349.98  4925.6  349.99  4949.1  350.49  4959.3   349.6  4969.4  341.83
  4976.5  341.14  4979.3  340.64  4982.5  341.14  4992.4  341.37  5050.5  342.74
    5059  348.86  5064.1  346.67  5068.7   350.4  5092.6  349.93    5193  349.35
  5390.9  349.06  5494.2  349.25  5614.6  349.18  5680.6  348.75  5980.3   349.3
  6322.7  348.41  6408.4  348.72    6435  346.97  6445.3  348.52  6507.5  348.68
#Mann= 14 ,-1 , 0
  3811.3     .08       0  4536.3     .05       0  4925.6     .08       0
  4976.5     .07       0  4982.5     .08       0  4992.4      .1       0
  5092.6     .08       0    5193     .05       0  5390.9     .08       0
  5494.2     .05       0  5614.6     .08       0  5680.6     .05       0
  5980.3     .08       0  6322.7     .05       0
Bank Sta=4949.1,5068.7
XS Rating Curve= 0 ,0
Exp/Cntr=0.3,0.1

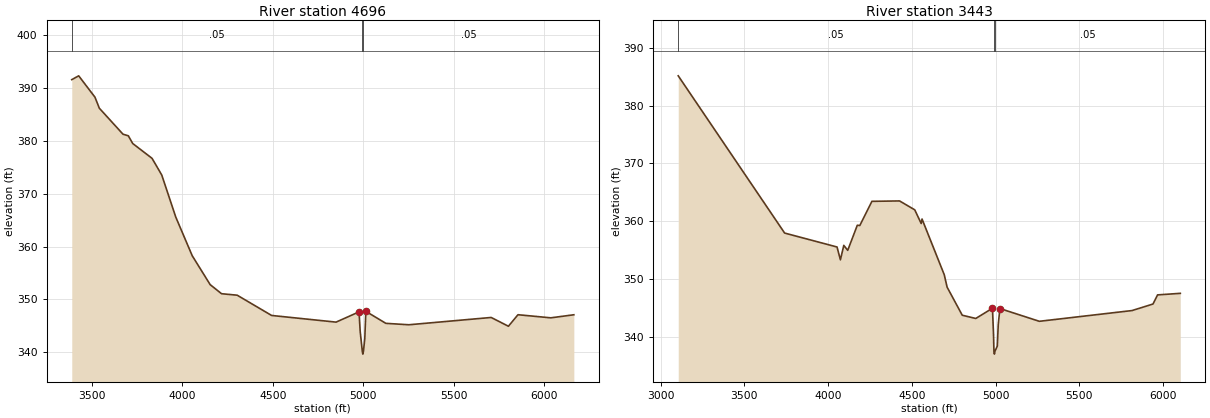
Type RM Length L Ch R = 1 ,4696    ,1253,1253,1253
BEGIN DESCRIPTION:
Mapping XS f6791d61
END DESCRIPTION:
XS GIS Cut Line= 3
      3591616.97     10538715.67      3592082.25     10537576.78
      3591582.26     10536118.48
#Sta/Elev= 30
  3390.2  391.55  3428.5  392.27  3518.3  388.23  3542.3  386.15  3673.2  381.23
  3702.6  380.93  3726.6  379.48  3833.5  376.67    3887  373.52  3964.5  365.56
  4055.1  358.27  4154.2   352.8  4217.1  351.08  4303.5   350.8  4493.5  346.97
  4849.4  345.71  4976.3  347.65  4982.4  343.99  4994.4  340.16  4997.2  339.66
  5000.4  340.16    5008  342.61  5013.7  347.75  5124.3  345.48  5251.1  345.21
  5705.7  346.59  5800.9  344.93  5853.7  347.11  6035.1  346.52  6162.1   347.1
#Mann= 3 ,-1 , 0
  3390.2     .05       0  4994.4     .03       0  5000.4     .05       0
Bank Sta=4976.3,5013.7
XS Rating Curve= 0 ,0
Exp/Cntr=0.3,0.1

Type RM Length L Ch R = 1 ,3443    ,0,0,0
BEGIN DESCRIPTION:
NORTH FORK BUFFALO CREEK 1.0
END DESCRIPTION:
XS GIS Cut Line= 4
      3592728.08     10539160.12      3592936.41     10537632.33
      3593193.36     10537097.61       3592776.7     10536340.69
#Sta/Elev= 30
  3104.7  385.17  3740.3  357.96  4053.3  355.55  4073.5  353.33  4093.7  355.83
  4117.1  354.97  4174.4  359.31  4189.4  359.27  4261.7  363.45  4426.8  363.52
  4517.6  361.98  4556.1  359.61  4561.1  360.39  4693.8  350.75  4710.9   348.6
  4801.4  343.74    4882  343.18  4981.8  344.95  4988.1  340.43  4990.6  337.51
  4993.4  337.01  4996.6  337.51  5010.7  338.39  5016.3  342.11  5026.2   344.9
  5261.7  342.69  5815.7  344.55  5940.7  345.68  5968.1  347.26  6103.9  347.53
#Mann= 3 ,-1 , 0
  3104.7     .05       0  4990.6     .03       0  4996.6     .05       0
Bank Sta=4981.8,5026.2
XS Rating Curve= 0 ,0
Exp/Cntr=0.3,0.1

Chan Stop Cuts=-1
Use User Specified Reach Order=0
Composite Channel Slope=5