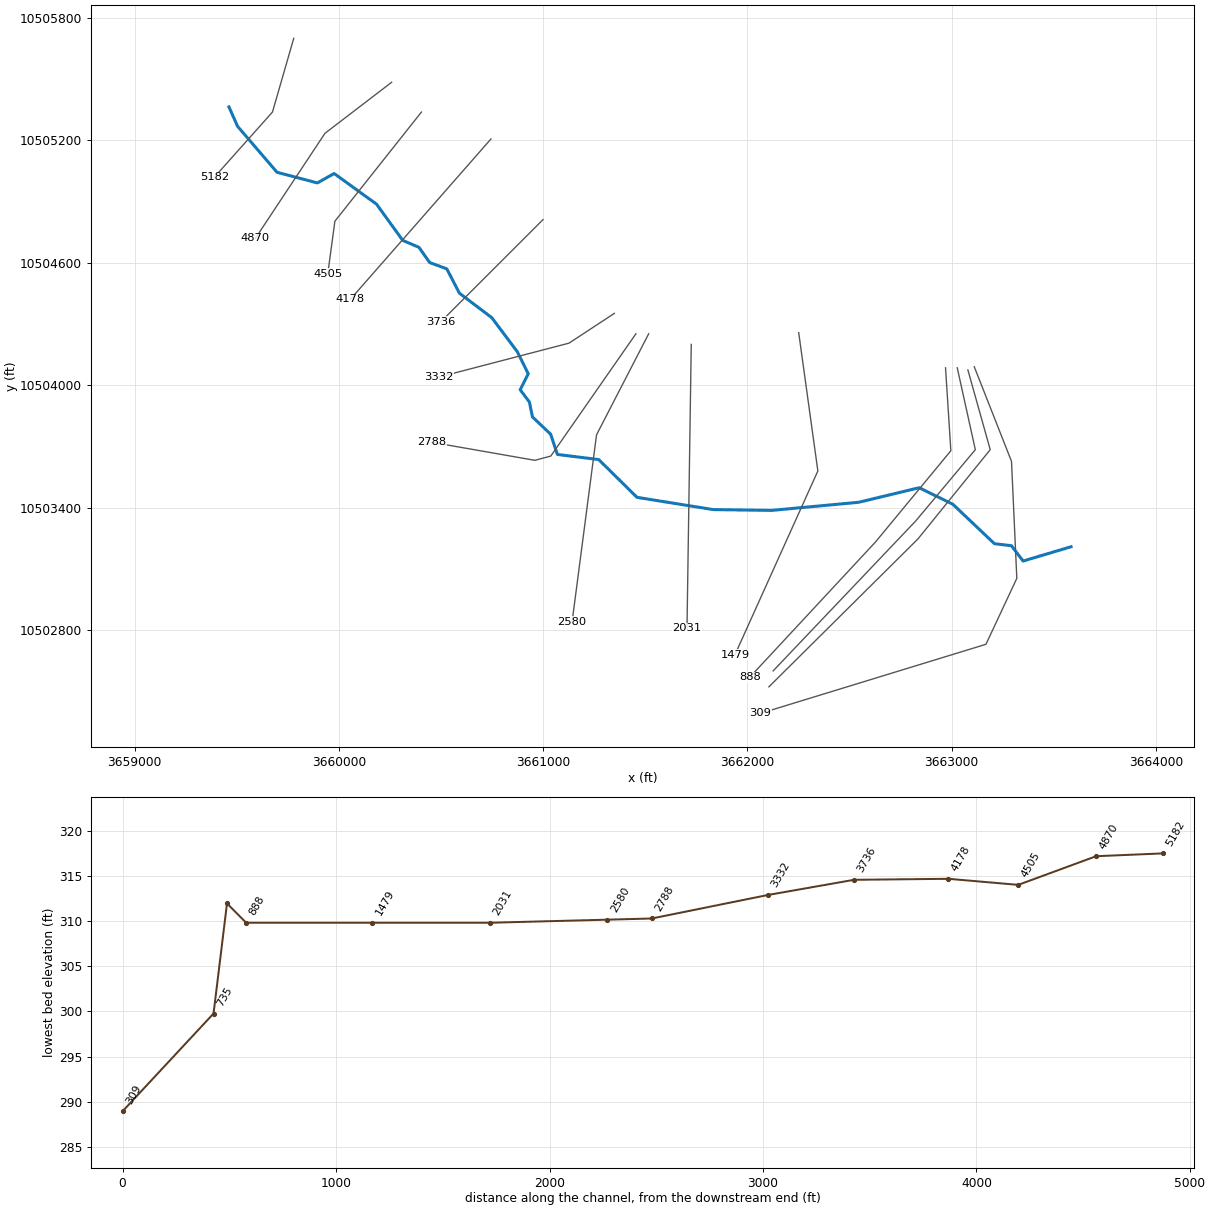
--- PATTERSON BRANCH.prj (project) ---

Proj Title=PATTERSON BRANCH Base Level Engineering
Current Plan=p01
Default Exp/Contr=0.3,0.1
English Units
Geom File=g01
Flow File=f01
Plan File=p01
Y Axis Title=Elevation
X Axis Title(PF)=Main Channel Distance
X Axis Title(XS)=Station
BEGIN DESCRIPTION:
PATTERSON BRANCH
END DESCRIPTION:
DSS Export Rating Curves= 0
DSS Export Rating Curve Sorted= 0
DSS Export Volume Flow Curves= 0
DXF OffsetX= 0
DXF OffsetY= 0
DXF ScaleX= 1
DXF ScaleY= 10

--- PATTERSON BRANCH.p01 (plan) ---

Plan Title=Multiple Run
Short Identifier=Multiple
Geom File=g01
Flow File=f01
Subcritical Flow
K Sum by GR= 0
Std Step Tol= 0.01
Critical Tol= 0.01
Num of Std Step Trials= 20
Max Error Tol= 0.3
Flow Tol Ratio= 0.001
Split Flow NTrial= 30
Split Flow Tol= 0.02
Split Flow Ratio= 0.02
Log Output Level= 0
Friction Slope Method= 1
Unsteady Friction Slope Method= 2
Unsteady Bridges Friction Slope Method= 1
Parabolic Critical Depth
Global Vel Dist=  1 , 1 , 1
Global Log Level= 0
CheckData=True
Encroach Param= -1, 0, 0, 0
BEGIN DESCRIPTION:
Multiple Run
END DESCRIPTION:

--- PATTERSON BRANCH.f01 (steady flow) ---

Flow Title=Multiple
Program Version=4.10
Number of Profiles= 7
Profile Names=10-year,25-year,50-year,1pct_min,100-year,1pct_plu,500-year
River Rch & RM=PATTERSON BRANCH,Reach-1         ,5182
     506     683     828     738     998    1350    1458
River Rch & RM=PATTERSON BRANCH,Reach-1         ,2580
    1071    1496    1856    1688    2283    3088    3472
River Rch & RM=PATTERSON BRANCH,Reach-1         ,2031
    1071    1496    1856    1688    2283    3088    3472
Boundary for River Rch & Prof#=PATTERSON BRANCH,Reach-1         , 1
Up Type= 0
Dn Type= 3
Dn Slope=0.01
Boundary for River Rch & Prof#=PATTERSON BRANCH,Reach-1         , 2
Up Type= 0
Dn Type= 3
Dn Slope=0.01
Boundary for River Rch & Prof#=PATTERSON BRANCH,Reach-1         , 3
Up Type= 0
Dn Type= 3
Dn Slope=0.01
Boundary for River Rch & Prof#=PATTERSON BRANCH,Reach-1         , 4
Up Type= 0
Dn Type= 3
Dn Slope=0.01
Boundary for River Rch & Prof#=PATTERSON BRANCH,Reach-1         , 5
Up Type= 0
Dn Type= 3
Dn Slope=0.01
Boundary for River Rch & Prof#=PATTERSON BRANCH,Reach-1         , 6
Up Type= 0
Dn Type= 3
Dn Slope=0.01
Boundary for River Rch & Prof#=PATTERSON BRANCH,Reach-1         , 7
Up Type= 0
Dn Type= 3
Dn Slope=0.01
DSS Import GetInterval= 0
DSS Import GetPeak= 0
DSS Import FillOption= 0

--- PATTERSON BRANCH.g01 (geometry) ---

Geom Title=Existing Conditions
Program Version=4.10

River Reach=PATTERSON BRANCH,Reach-1
Reach XY= 30
      3659462.34      10505362.1       3659504.5       10505267.
       3659697.5       10505042.        3659895.       10504990.
      3659977.25       10505036.       3660184.5       10504886.
       3660313.5       10504708.      3660391.75       10504675.
        3660445.       10504600.      3660528.75       10504569.
      3660590.25       10504450.      3660748.75       10504330.
        3660874.       10504163.      3660927.25       10504055.
      3660887.75       10503977.        3660933.       10503917.
      3660947.75       10503844.      3661037.25       10503759.
        3661070.       10503660.      3661272.25       10503635.
       3661459.5       10503450.       3661832.5       10503390.
      3662118.75       10503386.        3662546.       10503426.
        3662841.       10503497.        3663006.       10503416.
      3663209.25       10503223.       3663292.5       10503213.
      3663349.75       10503138.       3663584.5       10503208.

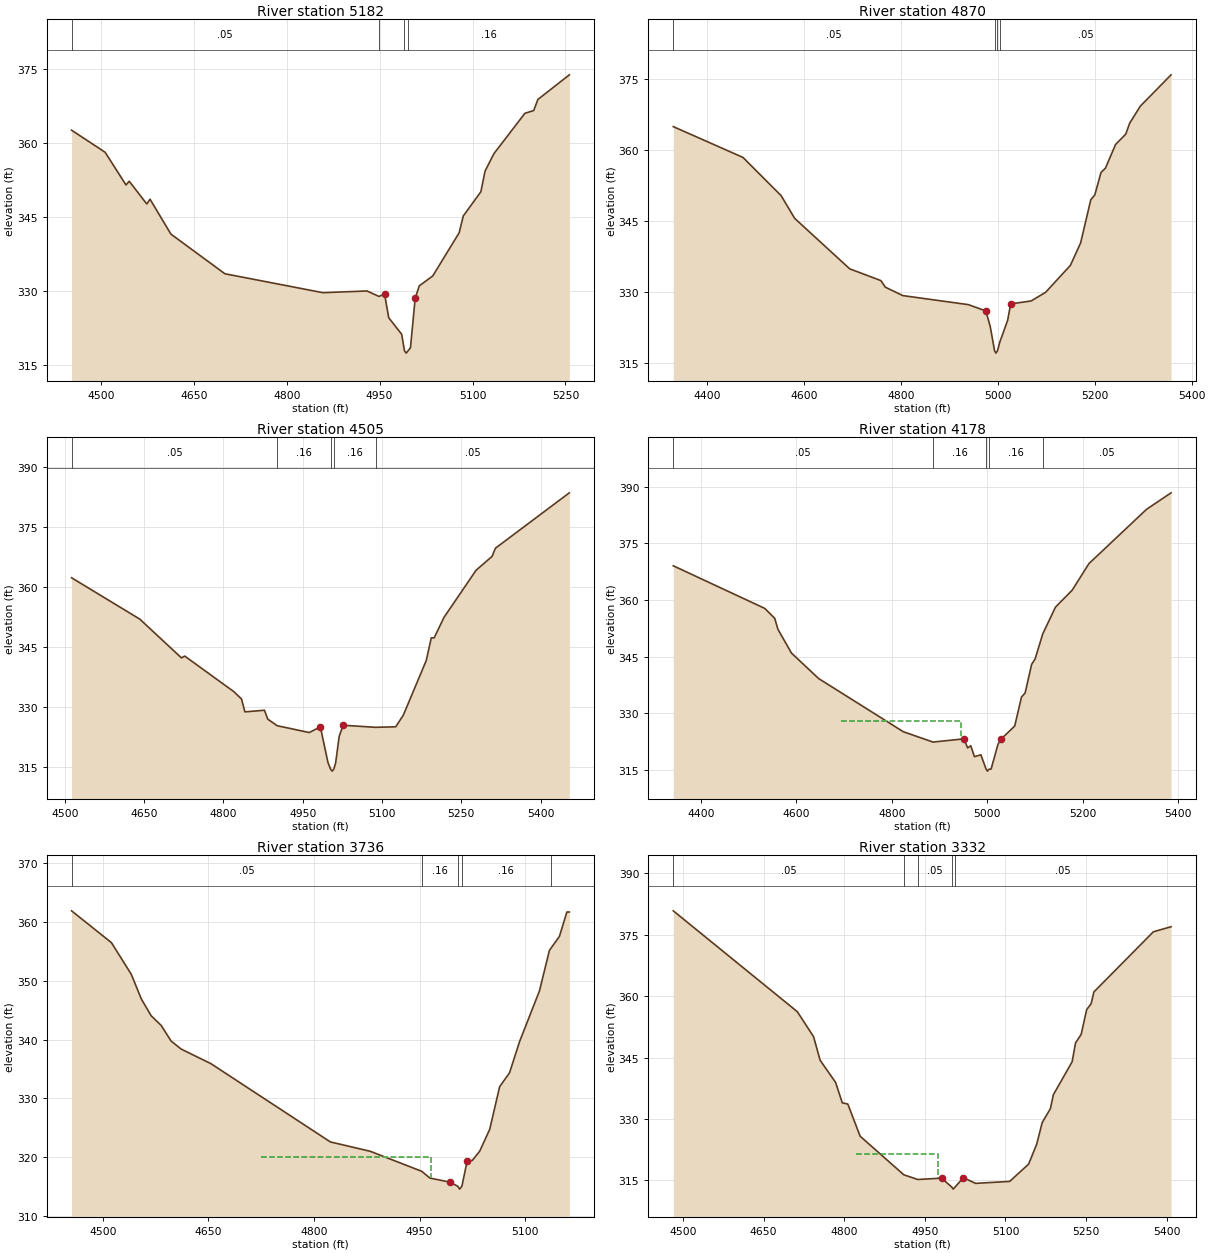
Type RM Length L Ch R = 1 ,5182    ,312,312,312
BEGIN DESCRIPTION:
PATTERSON BRANCH 11.0
END DESCRIPTION:
XS GIS Cut Line= 3
      3659779.39     10505698.13      3659675.23     10505337.05
      3659390.52     10505017.62
#Sta/Elev= 30
  4452.6  362.59  4506.8  358.12  4540.5   351.5  4545.7  352.26  4574.1  347.65
  4579.3  348.62    4613  341.56  4700.2  333.53  4858.5   329.7  4929.6  330.05
  4948.9  328.95    4958   329.4  4964.7  324.63  4985.6  321.29  4990.1  317.97
  4992.9  317.47  4996.1  317.97  4999.8  318.56  5007.4  328.58  5014.1  331.09
  5035.8  333.09  5078.4  341.82  5085.1  345.23  5113.5  350.14  5120.2  354.29
  5134.5  357.83  5184.6  366.01  5198.8  366.56  5205.5   368.8  5256.3  373.79
#Mann= 4 ,-1 , 0
  4452.6     .05       0  4948.9     .16       0  4990.1     .07       0
  4996.1     .16       0
Bank Sta=4958,5007.4
XS Rating Curve= 0 ,0
Exp/Cntr=0.3,0.1

Type RM Length L Ch R = 1 ,4870    ,365,365,365
BEGIN DESCRIPTION:
Mapping XS 98987772
END DESCRIPTION:
XS GIS Cut Line= 3
      3660258.55     10505482.87      3659932.17     10505232.88
      3659591.87     10504718.95
#Sta/Elev= 30
    4330  364.95  4473.9  358.45  4552.8  350.36  4580.6  345.59  4694.1  334.95
  4758.6  332.46  4767.6  331.08  4803.7   329.3  4939.1  327.39  4975.2  326.06
  4984.2  322.78  4993.2  317.66    4996  317.16  4999.2  317.66  5003.9  319.47
  5020.2  324.09  5026.4  327.55  5068.5  328.16  5098.6     330  5149.7  335.68
  5170.8  340.41  5191.8  349.52  5200.1  350.54  5212.9  355.29  5221.9  356.16
    5243  361.19    5264  363.37  5272.1  365.68  5294.1  369.28  5357.5  375.88
#Mann= 4 ,-1 , 0
    4330     .05       0  4993.2     .07       0  4999.2     .16       0
  5003.9     .05       0
Bank Sta=4975.2,5026.4
XS Rating Curve= 0 ,0
Exp/Cntr=0.3,0.1

Type RM Length L Ch R = 1 ,4505    ,327,327,327
BEGIN DESCRIPTION:
PATTERSON BRANCH 10.0
END DESCRIPTION:
XS GIS Cut Line= 3
      3660404.41     10505337.06      3659980.78     10504802.32
      3659946.06     10504545.36
#Sta/Elev= 30
  4512.9  362.31  4642.1  351.96  4720.7  342.29    4727  342.73    4820  333.84
  4834.4     332  4840.8   328.8  4877.7   329.2  4884.1  326.97  4901.8  325.34
  4962.6  323.63  4983.5  325.06  4997.9  316.12  5002.9  314.49  5005.7  313.99
  5008.9  314.49  5012.3  315.97  5019.2  322.75  5026.7  325.45  5087.9  324.94
  5126.1  325.07  5140.5  328.01  5183.8  341.63  5193.3  347.29  5198.7  347.29
  5217.4  352.42    5278  364.18  5308.3  367.65  5314.6  369.69  5454.4  383.53
#Mann= 5 ,-1 , 0
  4512.9     .05       0  4901.8     .16       0  5002.9     .07       0
  5008.9     .16       0  5087.9     .05       0
Bank Sta=4983.5,5026.7
XS Rating Curve= 0 ,0
Exp/Cntr=0.3,0.1

Type RM Length L Ch R = 1 ,4178    ,442,442,442
BEGIN DESCRIPTION:
PATTERSON BRANCH 9.0
END DESCRIPTION:
XS GIS Cut Line= 2
      3660744.69     10505205.12      3660057.18     10504420.39
#Sta/Elev= 30
  4341.9  369.06  4533.6  357.77  4554.5  355.14  4561.2  352.24  4589.6  345.94
  4646.6  339.18    4824   325.1  4886.2  322.36  4951.2  323.21  4958.8   320.8
  4965.4  321.39    4973   318.5  4986.6  318.98  4997.6  315.16  5000.3  314.66
  5003.6  315.16  5008.1  315.22  5022.4  321.76    5029  323.15  5057.5  326.61
  5071.7  334.29  5079.3  335.36    5093  342.95  5100.2  344.37  5116.3  351.03
  5142.9   358.1    5178  362.61  5213.1  369.65  5333.7  384.01  5385.2  388.39
#Mann= 5 ,-1 , 0
  4341.9     .05       0  4886.2     .16       0  4997.6     .07       0
  5003.6     .16       0  5116.3     .05       0
#XS Ineff= 1 ,-1
 4692.95 4945.91  327.92
Permanent Ineff=
       F
Bank Sta=4951.2,5029
XS Rating Curve= 0 ,0
Exp/Cntr=0.3,0.1

Type RM Length L Ch R = 1 ,3736    ,404,404,404
BEGIN DESCRIPTION:
PATTERSON BRANCH 8.0
END DESCRIPTION:
XS GIS Cut Line= 3
       3660999.6     10504810.18      3660599.61     10504410.19
      3660499.61     10504310.19
#Sta/Elev= 30
  4455.7  361.91  4512.3   356.5  4540.5  351.12  4554.7  346.94  4568.8  344.05
    4583  342.41  4597.1  339.75  4611.3  338.39  4653.7   335.9  4823.4  322.58
    4880  320.99  4953.2  317.58  4964.8  316.43  4993.1  315.74  5004.2  315.05
    5007  314.55  5010.2  315.05  5017.8  319.42  5024.9  319.42  5035.5  321.01
  5049.7  324.72  5063.8  331.98  5077.9  334.36  5092.1  339.65  5120.4  348.29
  5134.5  355.17  5136.4  355.49  5148.7  357.55  5159.3  361.71  5162.8  361.71
#Mann= 5 ,-1 , 0
  4455.7     .05       0  4953.2     .16       0  5004.2     .07       0
  5010.2     .16       0  5136.4     .05       0
#XS Ineff= 1 ,-1
  4725.1 4966.01320.0013
Permanent Ineff=
       F
Bank Sta=4993.1,5017.8
XS Rating Curve= 0 ,0
Exp/Cntr=0.3,0.1

Type RM Length L Ch R = 1 ,3332    ,544,544,544
BEGIN DESCRIPTION:
PATTERSON BRANCH 7.0
END DESCRIPTION:
XS GIS Cut Line= 3
      3661348.85     10504350.94      3661126.62      10504205.1
      3660487.71     10504038.43
#Sta/Elev= 30
    4482  380.81  4712.8  356.18    4743  350.08  4755.1  344.35    4784  338.91
  4796.4  333.94  4806.7  333.64  4829.6  325.79  4910.9  316.37  4936.9  315.22
  4981.2  315.55  5000.1  313.37  5002.8  312.87  5006.1  313.37  5021.7  315.65
  5044.4  314.28  5107.8  314.75  5143.1  318.98  5158.1  323.84  5168.4  329.13
  5183.6  332.52  5189.1  335.91  5224.1  343.98  5230.4  348.58  5240.8  350.63
  5251.1   356.7  5259.4  358.14  5264.5     361  5375.1  375.69  5408.1  376.93
#Mann= 5 ,-1 , 0
    4482     .05       0  4910.9     .16       0  4936.9     .05       0
  5000.1     .03       0  5006.1     .05       0
#XS Ineff= 1 ,-1
 4822.05 4974.09  321.41
Permanent Ineff=
       F
Bank Sta=4981.2,5021.7
XS Rating Curve= 0 ,0
Exp/Cntr=0.3,0.1

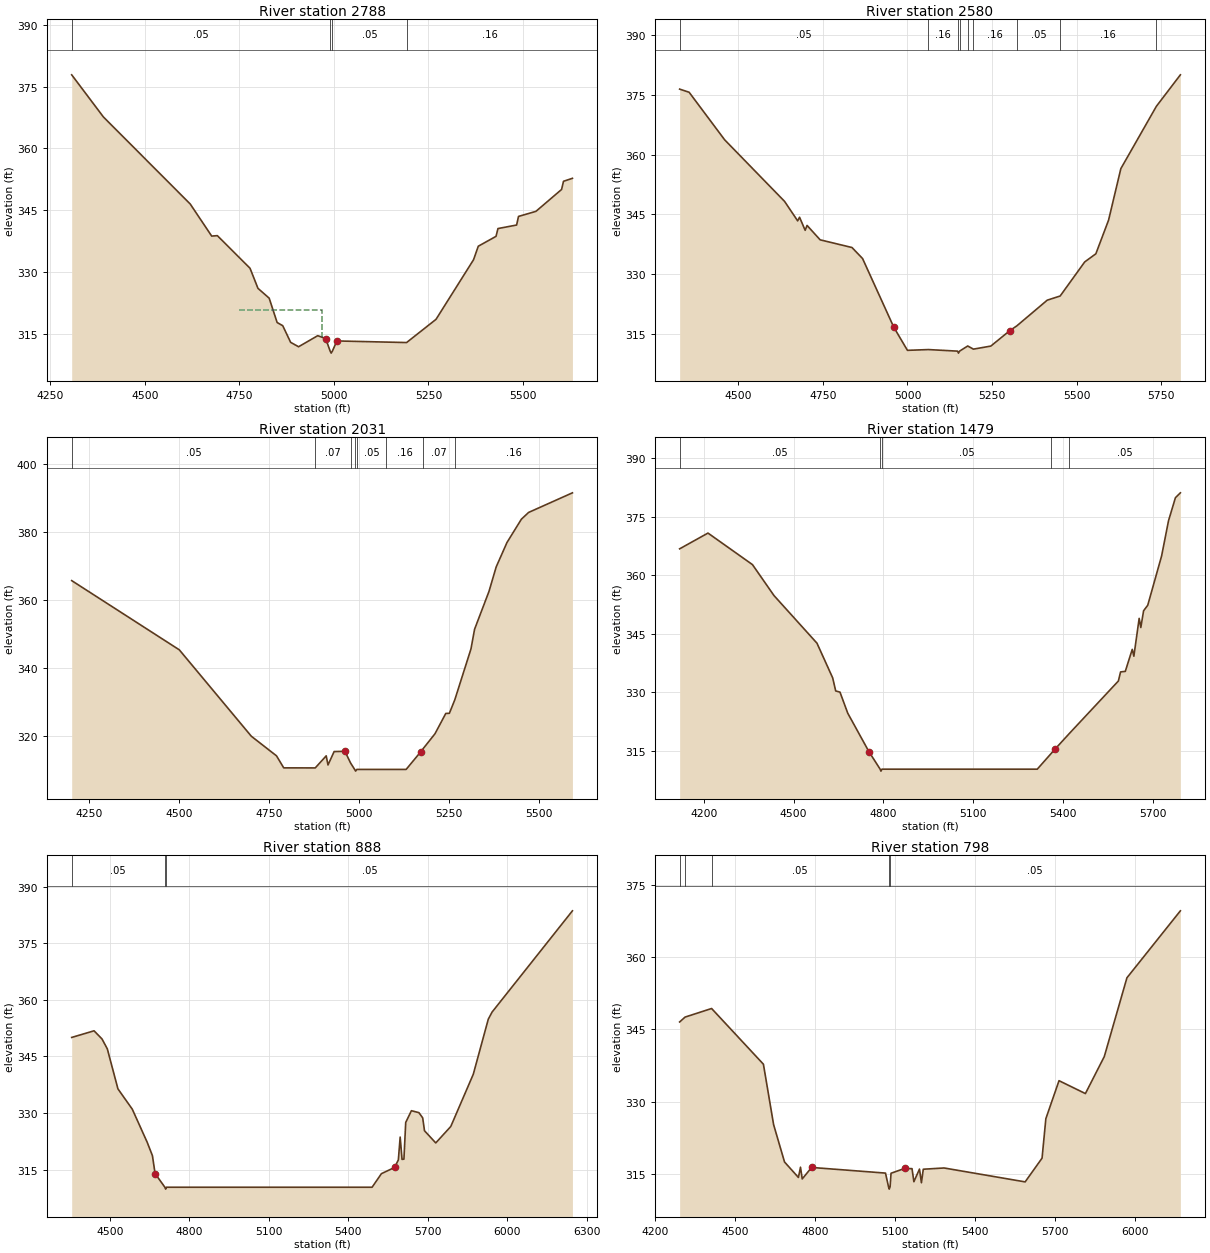
Type RM Length L Ch R = 1 ,2788    ,208,208,208
BEGIN DESCRIPTION:
PATTERSON BRANCH 6.0
END DESCRIPTION:
XS GIS Cut Line= 4
      3661454.42     10504251.11      3661037.74     10503652.13
      3660959.62      10503631.3      3660454.52     10503719.82
#Sta/Elev= 30
  4307.1   377.9  4390.9  367.66  4620.4   346.5  4677.1  338.71    4692  338.82
  4778.4  330.89  4799.3  326.02    4829  323.62    4850  317.71  4864.8  316.94
  4885.7  312.89  4906.7  311.82  4957.3  314.51  4978.2  313.82  4990.1  310.77
  4992.8  310.27  4996.1  310.77  5007.9  313.23  5192.1  312.84  5269.9  318.48
  5369.1  332.97  5381.6  336.25  5428.5  338.65  5433.6  340.54  5482.9   341.4
  5487.9  343.49  5533.9  344.72  5601.7  350.04  5606.8  352.03  5630.4  352.75
#Mann= 4 ,-1 , 0
  4307.1     .05       0  4990.1     .03       0  4996.1     .05       0
  5192.1     .16       0
#XS Ineff= 1 ,-1
 4748.18 4968.18  320.78
Permanent Ineff=
       F
Bank Sta=4978.2,5007.9
XS Rating Curve= 0 ,0
Exp/Cntr=0.3,0.1

Type RM Length L Ch R = 1 ,2580    ,549,549,549
BEGIN DESCRIPTION:
PATTERSON BRANCH 5.0
END DESCRIPTION:
XS GIS Cut Line= 3
       3661516.9     10504251.07       3661261.7      10503756.3
      3661141.91     10502839.61
#Sta/Elev= 30
    4326  376.41    4354  375.63  4459.1  363.69  4636.4  348.23  4675.1  343.34
  4680.7  344.25  4697.3  340.97  4702.9   342.2  4741.6  338.58  4835.8  336.65
  4867.1  333.88  4959.5  316.64  4999.8  310.84  5062.1  311.03  5148.1  310.64
  5150.8  310.14  5154.1  310.64  5178.2  311.93  5194.9  311.14  5246.5  311.91
  5302.4  315.77  5323.5  316.99  5413.3  323.43  5451.6  324.48  5524.2  333.03
  5557.2  335.08  5594.8  343.52  5631.1  356.45  5736.3  372.11  5807.2     380
#Mann= 9 ,-1 , 0
    4326     .05       0  5062.1     .16       0  5148.1     .03       0
  5154.1     .16       0  5178.2     .05       0  5194.9     .16       0
  5323.5     .05       0  5451.6     .16       0  5736.3     .05       0
Bank Sta=4959.5,5302.4
XS Rating Curve= 0 ,0
Exp/Cntr=0.3,0.1

Type RM Length L Ch R = 1 ,2031    ,552,552,552
BEGIN DESCRIPTION:
PATTERSON BRANCH 4.0
END DESCRIPTION:
XS GIS Cut Line= 2
      3661725.24     10504199.03      3661704.41     10502808.38
#Sta/Elev= 30
  4202.5   365.7  4501.4  345.39  4701.4  320.04  4771.4  314.28  4791.4  310.76
  4878.9  310.74  4909.4  314.28  4914.4  311.61  4931.4  315.54  4961.4  315.61
    4977  312.21  4988.4   310.3  4991.2   309.8  4994.4   310.3  5075.2   310.3
  5131.4   310.3  5171.4   315.4  5179.4  316.49  5211.5  320.76  5241.5  326.72
  5251.5  326.77  5266.5  330.71  5311.5  345.66  5321.5  351.43  5361.5  362.52
  5381.5  369.71  5411.5  376.88  5451.5  383.72  5471.5   385.7  5593.3  391.46
#Mann= 8 ,-1 , 0
  4202.5     .05       0  4878.9     .07       0    4977     .05       0
  4988.4    .035       0  4994.4     .05       0  5075.2     .16       0
  5179.4     .07       0  5266.5     .16       0
Bank Sta=4961.4,5171.4
XS Rating Curve= 0 ,0
Exp/Cntr=0.3,0.1

Type RM Length L Ch R = 1 ,1479    ,591,591,591
BEGIN DESCRIPTION:
PATTERSON BRANCH 3.0
END DESCRIPTION:
XS GIS Cut Line= 3
      3662251.28     10504256.33      3662345.03     10503579.22
      3661938.77     10502678.14
#Sta/Elev= 30
  4119.4   366.8    4214  370.84  4362.6  362.75  4434.4  354.82    4578   342.6
  4630.4  333.71  4640.5  330.36  4654.8  330.06  4680.8  324.64  4751.5  314.79
  4788.9   310.3  4791.6   309.8  4794.9   310.3  5313.5   310.3  5359.1  314.25
  5372.3  315.39  5420.4  319.43  5584.4  332.91  5591.7  335.24  5607.5  335.38
  5630.7  341.02  5636.1  339.27  5653.8  348.97  5659.3  346.62  5668.5  350.91
  5682.4  352.33  5728.7  364.97  5751.8     374  5774.9  379.91  5791.4  381.16
#Mann= 5 ,-1 , 0
  4119.4     .05       0  4788.9    .035       0  4794.9     .05       0
  5359.1     .16       0  5420.4     .05       0
Bank Sta=4751.5,5372.3
XS Rating Curve= 0 ,0
Exp/Cntr=0.3,0.1

Type RM Length L Ch R = 1 ,888     ,90,90,90
BEGIN DESCRIPTION:
PATTERSON BRANCH 2.0
END DESCRIPTION:
XS GIS Cut Line= 4
      3662970.04     10504084.41      3662996.08     10503678.17
      3662626.28     10503230.26      3662011.71     10502568.81
#Sta/Elev= 30
  4355.5  350.03  4439.9  351.79    4470  349.62    4490     347  4530.1  336.39
  4584.3     331  4640.3  322.27  4660.3  318.69  4670.4  313.92  4707.4   310.3
  4710.2   309.8  4713.4   310.3  5489.8   310.3    5525   313.9  5574.8  315.55
    5589  317.56  5595.8  323.61  5602.9  317.69    5610  317.75  5616.8  327.48
  5638.3   330.6  5666.7  330.08  5680.9  328.69  5687.7  325.28  5730.2  322.05
  5786.9  326.41  5871.9  340.26  5928.6  354.87  5942.8  356.75  6246.3  383.61
#Mann= 3 ,-1 , 0
  4355.5     .05       0  4707.4    .035       0  4713.4     .05       0
Bank Sta=4670.4,5574.8
XS Rating Curve= 0 ,0
Exp/Cntr=0.3,0.1

Type RM Length L Ch R = 1 ,798     ,63,63,63
BEGIN DESCRIPTION:
Mapping XS c7b60f29
END DESCRIPTION:
XS GIS Cut Line= 4
      3663027.33     10504084.39      3663115.87     10503683.38
       3662824.2     10503334.42      3662126.27     10502600.03
#Sta/Elev= 30
  4292.4  346.55  4312.7  347.56  4412.3  349.34  4606.7   337.8  4644.9  325.29
  4685.9  317.55    4738  314.35  4745.8  316.47  4752.3  314.04  4787.5  316.42
  5064.7  315.25    5076  312.43  5078.7  311.93    5082  312.43  5085.5  315.22
  5136.2  316.21  5164.2  316.17  5171.2  313.47  5192.2  316.08  5199.5  313.25
  5206.4  316.05  5284.4  316.31  5588.6  313.43  5652.1  318.35  5666.3  326.52
  5715.7  334.39  5814.7  331.72  5885.5  339.38  5970.5   355.7    6171  369.57
#Mann= 5 ,-1 , 0
  4292.4     .05       0  4312.7     .08       0  4412.3     .05       0
    5076     .03       0    5082     .05       0
Bank Sta=4787.5,5136.2
XS Rating Curve= 0 ,0
Exp/Cntr=0.3,0.1

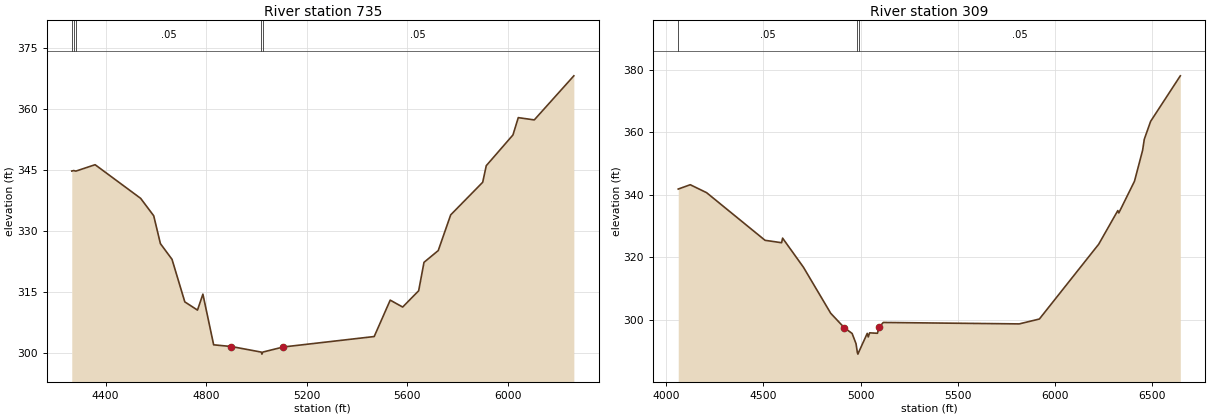
Type RM Length L Ch R = 1 ,735     ,426,426,426
BEGIN DESCRIPTION:
Mapping XS 0ae62c30
END DESCRIPTION:
XS GIS Cut Line= 4
      3663079.42     10504073.96      3663188.78     10503683.38
      3662834.62     10503245.88      3662105.46     10502521.93
#Sta/Elev= 30
  4265.6  344.83  4273.3  344.95  4281.8  344.81  4358.4  346.39  4539.4  338.11
  4591.4  333.82    4618  326.96  4664.1   323.1    4715  312.62  4765.4   310.6
  4786.9  314.52  4829.7  302.05  4900.4  301.63  5018.9  300.26  5021.6  299.76
  5024.9  300.26  5106.6  301.52  5467.9  304.09  5531.6  313.05  5581.1  311.35
  5644.7  315.36  5665.9  322.36  5722.5  325.25    5772  334.04  5899.3  342.07
  5913.4  346.15  6019.5  353.71  6040.7  357.98  6104.3  357.42  6261.6  368.27
#Mann= 5 ,-1 , 0
  4265.6     .05       0  4273.3     .08       0  4281.8     .05       0
  5018.9     .03       0  5024.9     .05       0
Bank Sta=4900.4,5106.6
XS Rating Curve= 0 ,0
Exp/Cntr=0.3,0.1

Type RM Length L Ch R = 1 ,309     ,0,0,0
BEGIN DESCRIPTION:
PATTERSON BRANCH 1.0
END DESCRIPTION:
XS GIS Cut Line= 5
      3663110.67     10504089.61      3663292.95     10503626.09
      3663318.99     10503053.17      3663167.95     10502730.26
      3662064.24     10502391.86
#Sta/Elev= 30
  4061.6  341.76  4123.5  343.14  4207.5   340.6  4508.2  325.36  4593.4  324.59
  4598.4  326.06  4705.7  316.74  4845.9  302.02  4915.9  297.39    4956  295.56
    4976  292.31    4983  289.45  4985.8  288.95    4989  289.45  5033.8  295.59
  5038.9  294.45  5046.1  295.76  5086.1  295.62  5096.1  297.62  5116.1  299.08
  5815.7  298.62  5919.2  300.18  6224.3  324.11  6322.6  334.87  6327.8  334.12
  6408.4  344.26  6450.2  354.16  6458.8  357.69  6491.5  363.43  6644.1  377.98
#Mann= 3 ,-1 , 0
  4061.6     .05       0    4983     .03       0    4989     .05       0
Bank Sta=4915.9,5096.1
XS Rating Curve= 0 ,0
Exp/Cntr=0.3,0.1

Chan Stop Cuts=-1
Use User Specified Reach Order=0
Composite Channel Slope=5