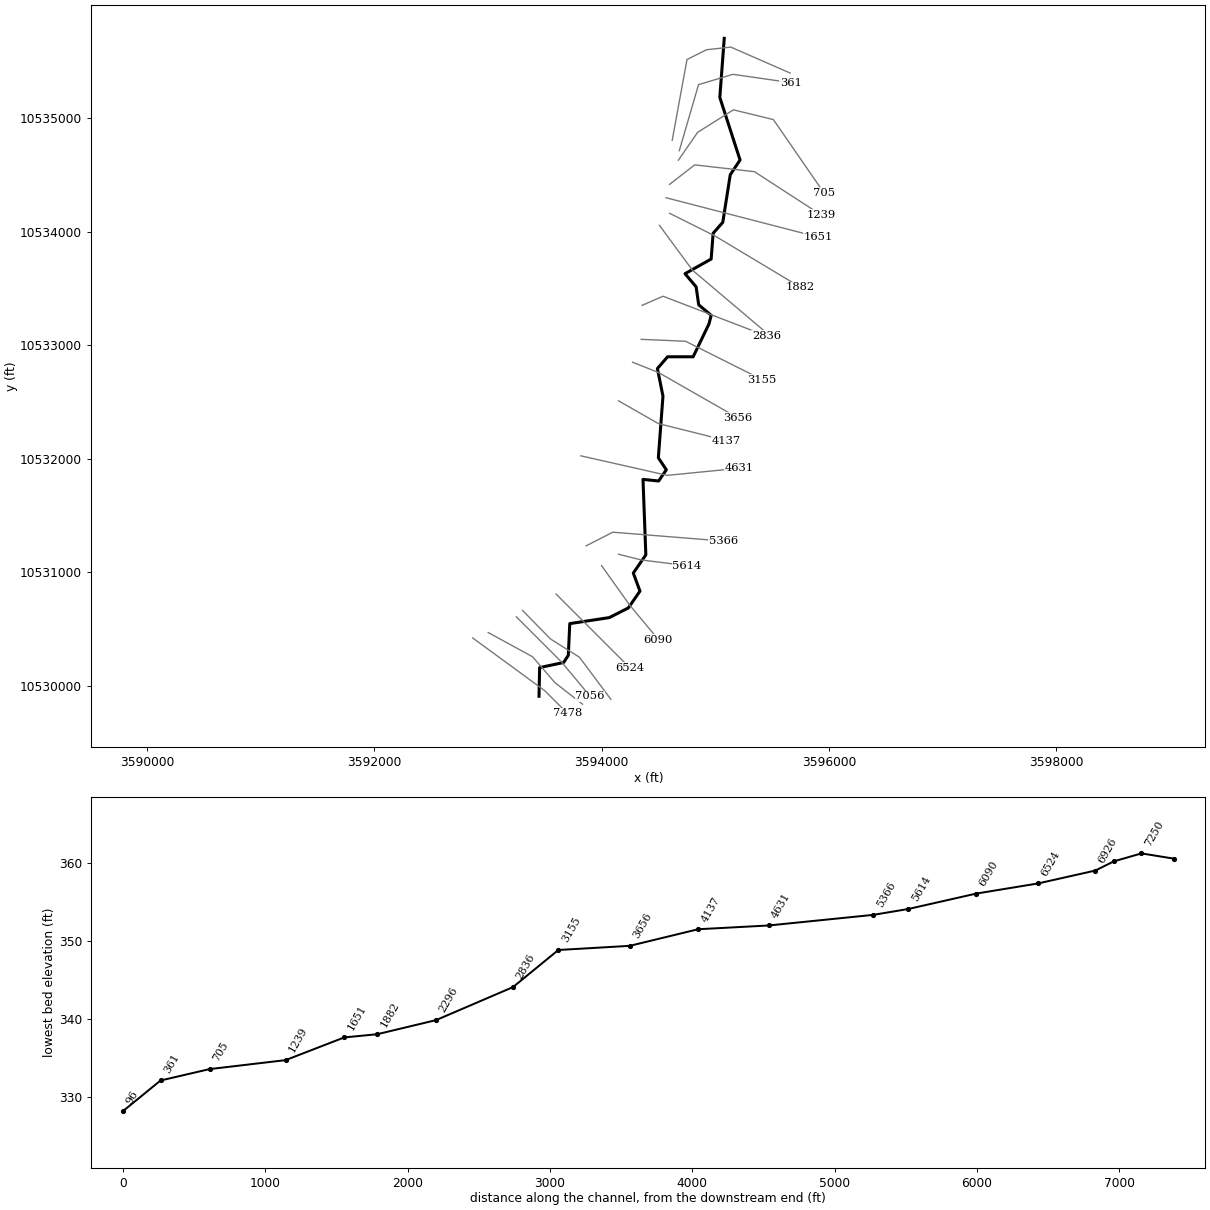
--- PINE BRANCH.prj (project) ---

Proj Title=PINE BRANCH Base Level Engineering
Current Plan=p01
Default Exp/Contr=0.3,0.1
English Units
Geom File=g01
Flow File=f01
Plan File=p01
Y Axis Title=Elevation
X Axis Title(PF)=Main Channel Distance
X Axis Title(XS)=Station
BEGIN DESCRIPTION:
PINE BRANCH
END DESCRIPTION:
DSS Export Rating Curves= 0
DSS Export Rating Curve Sorted= 0
DSS Export Volume Flow Curves= 0
DXF OffsetX= 0
DXF OffsetY= 0
DXF ScaleX= 1
DXF ScaleY= 10

--- PINE BRANCH.p01 (plan) ---

Plan Title=Multiple Run
Short Identifier=Multiple
Geom File=g01
Flow File=f01
Subcritical Flow
K Sum by GR= 0
Std Step Tol= 0.01
Critical Tol= 0.01
Num of Std Step Trials= 20
Max Error Tol= 0.3
Flow Tol Ratio= 0.001
Split Flow NTrial= 30
Split Flow Tol= 0.02
Split Flow Ratio= 0.02
Log Output Level= 0
Friction Slope Method= 1
Unsteady Friction Slope Method= 2
Unsteady Bridges Friction Slope Method= 1
Parabolic Critical Depth
Global Vel Dist=  1 , 1 , 1
Global Log Level= 0
CheckData=True
Encroach Param= -1, 0, 0, 0
BEGIN DESCRIPTION:
Multiple Run
END DESCRIPTION:

--- PINE BRANCH.f01 (steady flow) ---

Flow Title=Multiple
Number of Profiles=7
Profile Names=10-year,25-year,50-year,1pct_min,100-year,1pct_plu,500-year
River Rch & RM= PINE BRANCH,Reach-1,7478
    1612    2302    2895    2656    3592    4858    5516
River Rch & RM= PINE BRANCH,Reach-1,7250
    2017    2897    3656    3362    4547    6149    7016
Boundary for River Rch & Prof#=PINE BRANCH,Reach-1,1
Up Type=0
Dn Type=3
Dn Slope=0.005
Boundary for River Rch & Prof#=PINE BRANCH,Reach-1,2
Up Type=0
Dn Type=3
Dn Slope=0.005
Boundary for River Rch & Prof#=PINE BRANCH,Reach-1,3
Up Type=0
Dn Type=3
Dn Slope=0.005
Boundary for River Rch & Prof#=PINE BRANCH,Reach-1,4
Up Type=0
Dn Type=3
Dn Slope=0.005
Boundary for River Rch & Prof#=PINE BRANCH,Reach-1,5
Up Type=0
Dn Type=3
Dn Slope=0.005
Boundary for River Rch & Prof#=PINE BRANCH,Reach-1,6
Up Type=0
Dn Type=3
Dn Slope=0.005
Boundary for River Rch & Prof#=PINE BRANCH,Reach-1,7
Up Type=0
Dn Type=3
Dn Slope=0.005

--- PINE BRANCH.g01 (geometry) ---

Geom Title=Existing Conditions
Program Version=4.10

River Reach=PINE BRANCH     ,Reach-1
Reach XY= 30
      3593449.44     10529910.93        3593455.       10530163.
      3593666.25       10530208.      3593707.25       10530271.
      3593720.25       10530550.      3594068.25       10530603.
       3594235.5       10530688.      3594337.75       10530836.
      3594279.25       10530995.       3594389.5       10531155.
       3594364.5       10531819.      3594502.25       10531805.
      3594569.75       10531904.       3594499.5       10532009.
      3594540.25       10532552.      3594491.25       10532794.
      3594580.75       10532898.      3594805.75       10532898.
        3594945.       10533187.       3594964.5       10533263.
      3594854.75       10533355.        3594832.       10533513.
      3594734.25       10533629.      3594964.25       10533758.
      3594981.75       10533985.       3595066.5       10534081.
      3595132.25       10534499.       3595218.5       10534630.
       3595040.5       10535180.       3595079.5       10535700.

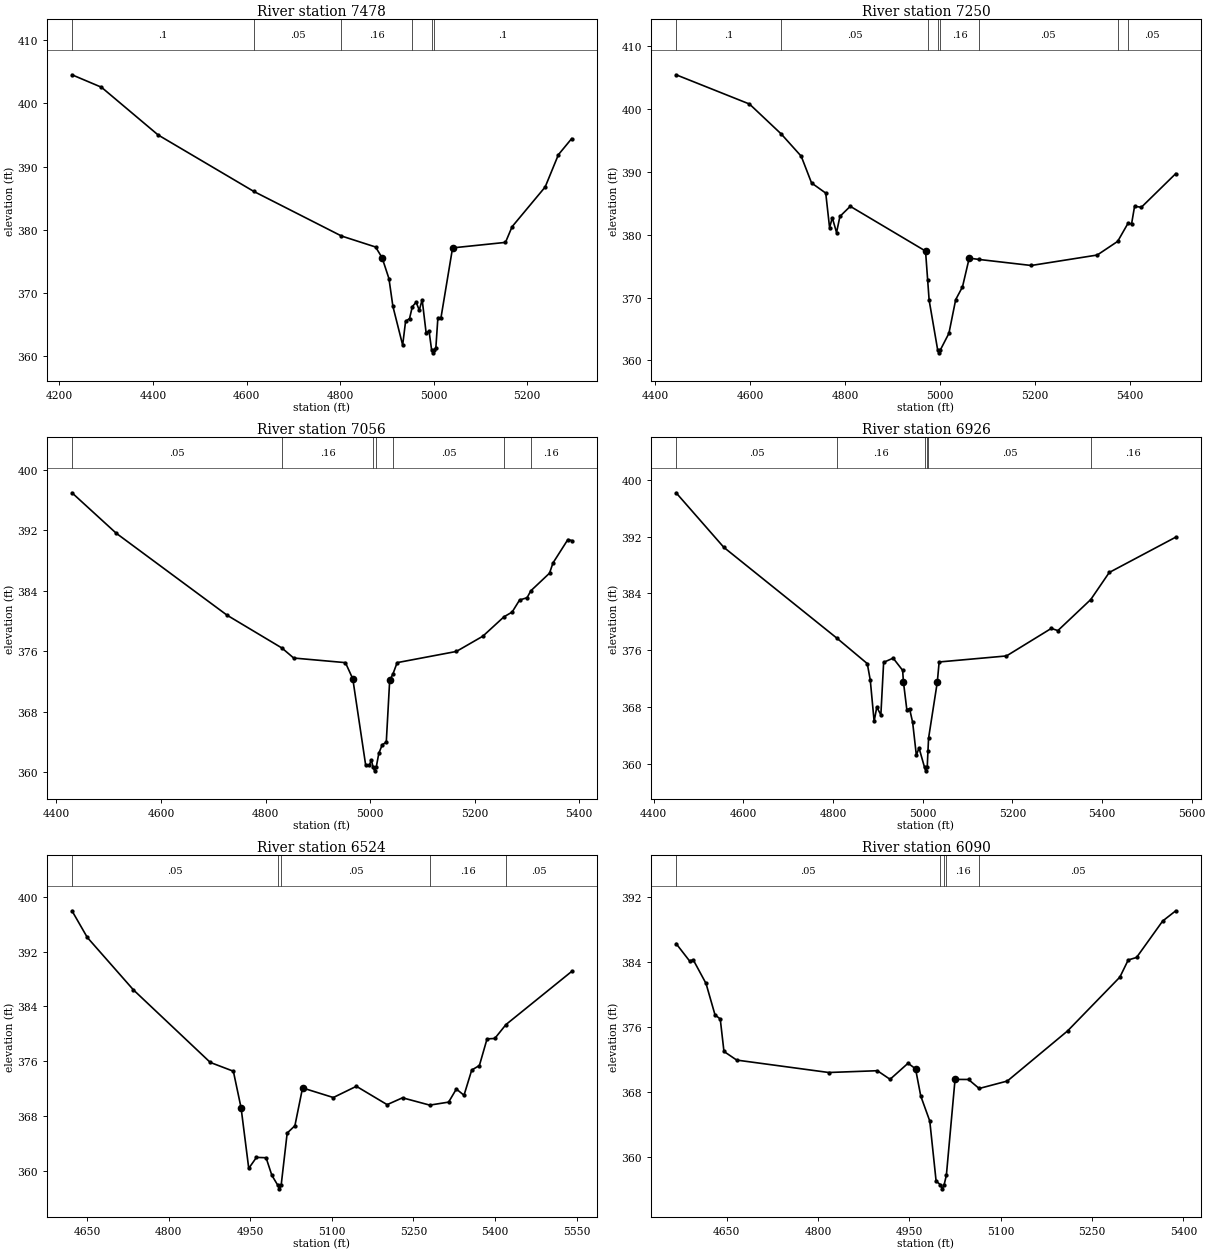
Type RM Length L Ch R = 1 ,7478    ,228,228,228
BEGIN DESCRIPTION:
PINE BRANCH 14.0
END DESCRIPTION:
XS GIS Cut Line= 3
      3592865.89     10530423.92      3593499.61     10529960.19
       3593699.6      10529760.2
#Sta/Elev= 30
  4226.8  404.52  4289.8  402.55    4411     395  4615.5  386.07  4802.9  379.02
  4875.8  377.28  4889.7  375.59  4904.4  372.28  4912.8   367.9  4933.7  361.76
  4939.9  365.51  4948.4  365.97  4954.4  367.86  4962.5  368.54  4969.2  367.29
  4975.4  368.94  4983.9  363.67  4990.1     364  4995.5  361.04  4998.3  360.54
  5001.5  361.04  5004.7  361.37    5009  366.09  5015.6  366.09  5040.4  377.14
  5153.5  378.01  5167.6  380.49  5238.3  386.77  5266.6  391.88  5294.9  394.42
#Mann= 6 ,-1 , 0
  4226.8      .1       0  4615.5     .05       0  4802.9     .16       0
  4954.4      .1       0  4995.5     .07       0  5001.5      .1       0
Bank Sta=4889.7,5040.4
XS Rating Curve= 0 ,0
Exp/Cntr=0.3,0.1

Type RM Length L Ch R = 1 ,7250    ,194,194,194
BEGIN DESCRIPTION:
Mapping XS ebe12468
END DESCRIPTION:
XS GIS Cut Line= 4
      3593002.76     10530471.53      3593393.34     10530258.01
      3593589.52     10530030.58      3593832.56     10529841.36
#Sta/Elev= 30
  4443.9  405.39  4598.6  400.74  4665.6  395.98  4707.7  392.45  4729.5   388.2
  4759.4  386.59  4767.5  381.09  4773.2  382.68  4782.2  380.32  4789.3  382.89
  4811.1  384.49  4969.8  377.38  4974.3  372.76  4977.4  369.57  4995.3  361.71
    4998  361.21  5001.3  361.71  5019.1  364.31  5033.4  369.67  5047.7  371.69
  5061.9  376.26  5082.3  376.05  5192.6  375.09  5331.8  376.75  5374.9  378.92
  5396.9  381.82  5404.2  381.69  5410.5  384.48    5425  384.35  5497.4  389.69
#Mann= 8 ,-1 , 0
  4443.9      .1       0  4665.6     .05       0  4974.3     .16       0
  4995.3     .07       0  5001.3     .16       0  5082.3     .05       0
  5374.9      .1       0  5396.9     .05       0
Bank Sta=4969.8,5061.9
XS Rating Curve= 0 ,0
Exp/Cntr=0.3,0.1

Type RM Length L Ch R = 1 ,7056    ,130,130,130
BEGIN DESCRIPTION:
PINE BRANCH 13.0
END DESCRIPTION:
XS GIS Cut Line= 3
      3593249.61     10530610.18      3593649.61     10530210.19
      3593899.61     10529910.18
#Sta/Elev= 30
  4429.6  396.99  4514.4  391.63  4726.6  380.78  4831.5  376.44  4853.9  375.12
  4952.9  374.51    4967  372.37  4991.7  360.92  4998.5  360.92  5002.4  361.61
  5005.9  360.69  5008.7  360.19  5011.9  360.69  5016.8   362.5  5023.3  363.63
  5031.1  363.99  5037.6  372.17  5043.8     373  5051.9  374.51  5165.2  375.99
  5215.9  378.01  5256.4  380.58  5271.9   381.2  5286.2   382.8  5300.5   383.1
  5307.6  384.01  5343.5  386.35    5350  387.69  5378.6   390.8  5385.8  390.67
#Mann= 7 ,-1 , 0
  4429.6     .05       0  4831.5     .16       0  5005.9     .07       0
  5011.9     .16       0  5043.8     .05       0  5256.4      .1       0
  5307.6     .16       0
Bank Sta=4967,5037.6
XS Rating Curve= 0 ,0
Exp/Cntr=0.3,0.1

Type RM Length L Ch R = 1 ,6926    ,402,402,402
BEGIN DESCRIPTION:
Mapping XS 2f97804d
END DESCRIPTION:
XS GIS Cut Line= 4
      3593304.78     10530666.01      3593551.32     10530414.26
       3593804.8     10530254.54      3594081.76      10529884.1
#Sta/Elev= 30
  4450.1  398.19  4556.6   390.5  4809.6  377.66  4876.5  374.12  4883.2  371.79
  4891.8  365.97  4897.7  367.99  4906.8  366.89    4913   374.3  4934.2  374.89
  4955.4  373.17 4957.05  371.59  4964.8  367.59  4970.7  367.79  4977.7  365.84
    4986  361.19  4991.9  362.24  5004.2  359.51  5006.9  359.01  5010.2  359.51
  5011.9  361.83  5013.2   363.6 5032.73  371.53  5036.8  374.35    5187   375.2
    5287  379.08  5301.6  378.77    5375  383.15  5416.2  386.96  5564.6  391.94
#Mann= 6 ,-1 , 0
  4450.1     .05       0  4809.6     .16       0  5004.2     .07       0
  5010.2     .16       0  5011.9     .05       0    5375     .16       0
Bank Sta=4957.05,5032.73
XS Rating Curve= 0 ,0
Exp/Cntr=0.3,0.1

Type RM Length L Ch R = 1 ,6524    ,434,434,434
BEGIN DESCRIPTION:
PINE BRANCH 12.0
END DESCRIPTION:
XS GIS Cut Line= 3
      3593599.63     10530810.16      3593849.61     10530560.19
      3594249.61     10530160.19
#Sta/Elev= 30
  4621.8  397.95    4650  394.06  4734.9   386.4  4876.3  375.81  4918.7  374.53
  4932.9  369.19    4947  360.35  4961.2  361.95  4978.9   361.9  4989.5  359.34
  5000.6  357.86  5003.4  357.36  5006.6  357.86  5017.7   365.5  5031.9  366.57
    5046  372.09  5102.6  370.69    5145  372.33  5201.6  369.65  5229.9  370.65
    5280  369.58  5314.7  370.02  5328.9  371.93    5343  371.02  5357.2   374.7
  5371.3  375.36  5385.4  379.25  5399.6  379.31  5420.2  381.34    5541  389.09
#Mann= 5 ,-1 , 0
  4621.8     .05       0  5000.6     .03       0  5006.6     .05       0
    5280     .16       0  5420.2     .05       0
Bank Sta=4932.9,5046
XS Rating Curve= 0 ,0
Exp/Cntr=0.3,0.1

Type RM Length L Ch R = 1 ,6090    ,476,476,476
BEGIN DESCRIPTION:
PINE BRANCH 11.0
END DESCRIPTION:
XS GIS Cut Line= 3
      3593999.63     10531060.16      3594249.61     10530710.19
      3594499.61     10530410.18
#Sta/Elev= 30
  4566.9  386.27    4589  384.13  4595.1  384.26    4616  381.36  4630.8  377.49
  4639.4  376.98  4645.5  372.98  4666.4  371.92  4817.6  370.39  4897.4  370.61
  4918.3  369.55  4947.8  371.53  4960.1  370.85  4968.7  367.49  4983.5  364.41
  4993.9  357.01  5001.1  356.56  5003.9  356.06  5007.1  356.56  5010.8  357.76
    5025  369.54  5047.1  369.53  5064.6  368.42  5110.9  369.34  5209.8  375.51
  5295.7  382.14  5309.4  384.25  5323.1  384.56    5366  389.05  5387.5  390.31
#Mann= 5 ,-1 , 0
  4566.9     .05       0  5001.1     .03       0  5007.1     .05       0
  5010.8     .16       0  5064.6     .05       0
Bank Sta=4960.1,5025
XS Rating Curve= 0 ,0
Exp/Cntr=0.3,0.1

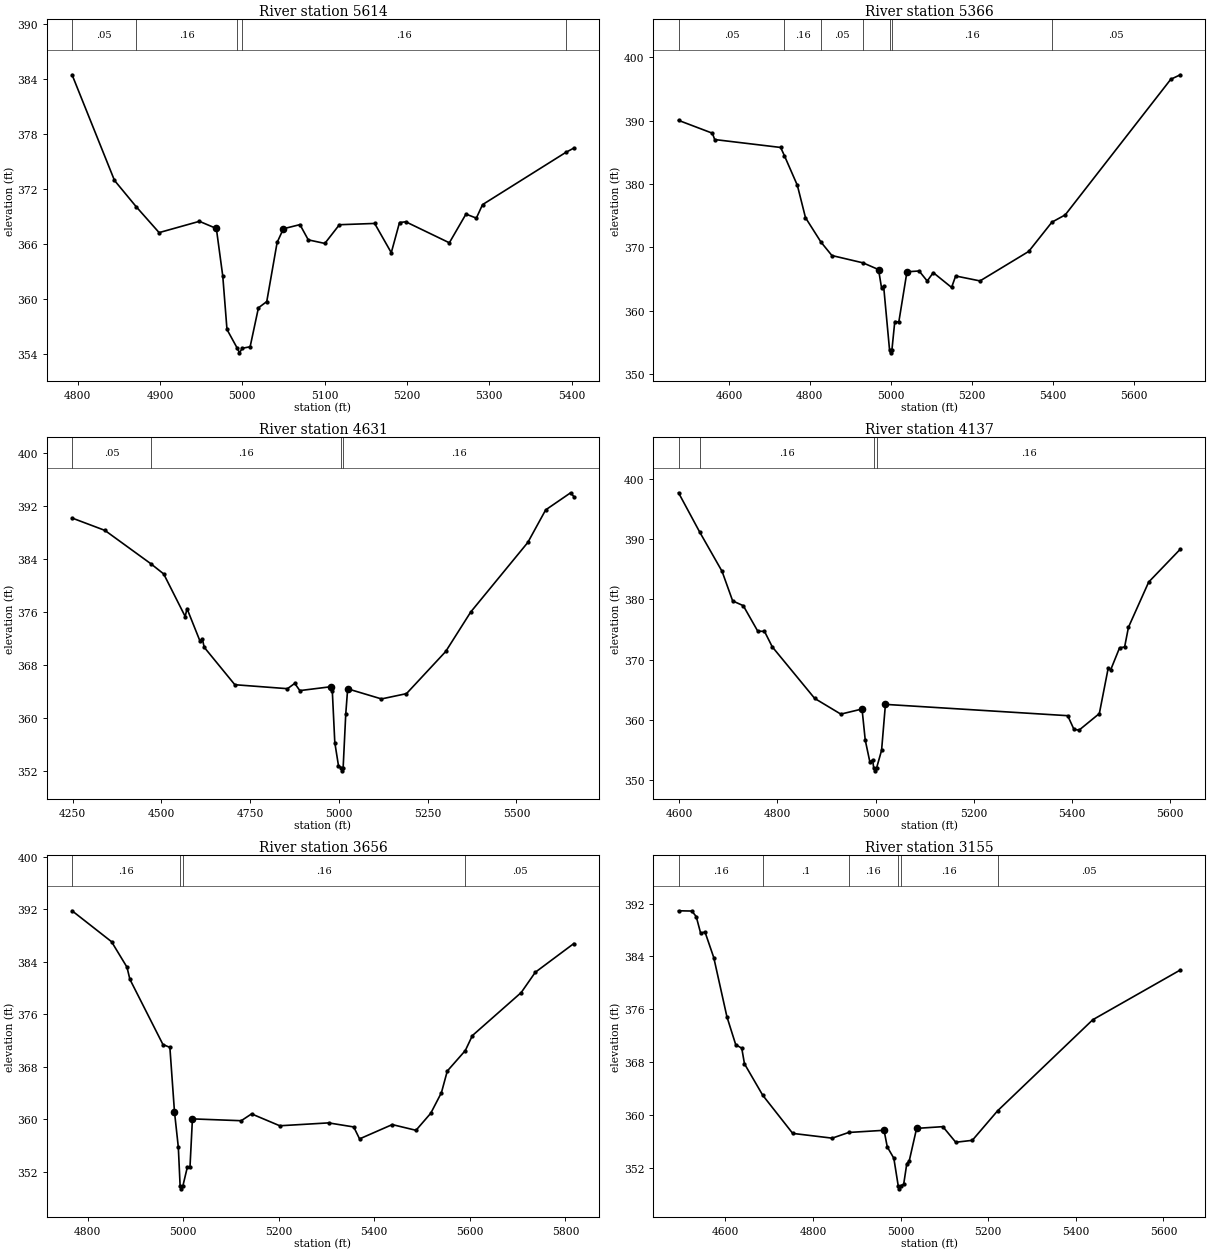
Type RM Length L Ch R = 1 ,5614    ,248,248,248
BEGIN DESCRIPTION:
PINE BRANCH 10.0
END DESCRIPTION:
XS GIS Cut Line= 3
       3594149.6     10531160.19      3594349.61     10531110.19
      3594749.63     10531060.19
#Sta/Elev= 30
  4793.3  384.41  4844.8  372.89  4871.2  370.02    4899   367.2  4947.9  368.43
  4968.5  367.65  4976.3  362.45  4981.4  356.64  4993.9  354.59  4996.6  354.09
  4999.9  354.59  5009.5  354.75  5019.6     359  5029.7  359.68  5042.3  366.13
  5049.9  367.62    5070  368.07  5080.1  366.41  5100.2  366.02  5117.9  368.06
  5160.7   368.2  5180.9  365.01  5190.9   368.3  5198.5  368.38  5251.4  366.09
  5271.6  369.22  5284.2  368.78  5291.7  370.25  5392.7  375.94  5402.6  376.42
#Mann= 5 ,-1 , 0
  4793.3     .05       0  4871.2     .16       0  4993.9     .07       0
  4999.9     .16       0  5392.7     .05       0
Bank Sta=4968.5,5049.9
XS Rating Curve= 0 ,0
Exp/Cntr=0.3,0.1

Type RM Length L Ch R = 1 ,5366    ,735,735,735
BEGIN DESCRIPTION:
PINE BRANCH 9.0
END DESCRIPTION:
XS GIS Cut Line= 3
      3593864.83     10531234.67      3594099.22     10531354.47
      3595073.16     10531276.35
#Sta/Elev= 30
  4475.4  390.05  4559.1  388.02  4564.7  387.02  4727.8  385.77  4736.9   384.5
  4769.1  379.79  4789.2  374.68  4827.5  370.82  4854.5   368.7  4931.6  367.54
  4969.8  366.48  4977.3  363.54  4982.3  363.91  4996.9  353.83  4999.6  353.33
  5002.9  353.83  5009.9  358.27  5019.9  358.21    5040  366.13  5070.1  366.26
  5090.1  364.67    5105     366  5150.3  363.66  5160.4  365.47  5220.6  364.69
    5341  369.35  5398.3  373.97  5431.2  375.12  5692.1  396.54  5715.7  397.25
#Mann= 7 ,-1 , 0
  4475.4     .05       0  4736.9     .16       0  4827.5     .05       0
  4931.6     .16       0  4996.9     .07       0  5002.9     .16       0
  5398.3     .05       0
Bank Sta=4969.8,5040
XS Rating Curve= 0 ,0
Exp/Cntr=0.3,0.1

Type RM Length L Ch R = 1 ,4631    ,494,494,494
BEGIN DESCRIPTION:
PINE BRANCH 8.0
END DESCRIPTION:
XS GIS Cut Line= 3
      3593817.99     10532026.34      3594578.39     10531854.47
      3595208.62     10531916.97
#Sta/Elev= 30
  4248.7  390.22  4341.1  388.35  4470.1  383.32  4506.7  381.76  4567.2  375.32
  4572.4  376.51  4609.2  371.56  4615.6  371.93  4620.7  370.67    4707     365
  4855.2   364.4  4875.7   365.2    4890  364.11  4976.4  364.69  4981.5  364.02
  4988.5  356.24  4998.8  352.76    5006  352.47  5008.8  351.97    5012  352.47
  5019.3  360.55  5024.7  364.38  5119.9  362.85  5190.3  363.65  5300.8  370.03
  5371.2     376    5532  386.53  5582.2  391.45  5652.5  394.04  5661.6  393.46
#Mann= 4 ,-1 , 0
  4248.7     .05       0  4470.1     .16       0    5006     .07       0
    5012     .16       0
Bank Sta=4976.4,5024.7
XS Rating Curve= 0 ,0
Exp/Cntr=0.3,0.1

Type RM Length L Ch R = 1 ,4137    ,481,481,481
BEGIN DESCRIPTION:
PINE BRANCH 7.0
END DESCRIPTION:
XS GIS Cut Line= 3
      3594149.58      10532510.2      3594499.61     10532310.19
       3595099.6     10532160.19
#Sta/Elev= 30
  4598.7  397.72  4641.7   391.2  4687.3  384.66  4708.9  379.74  4730.5  378.95
    4760  374.71  4773.7  374.68  4789.5  372.11  4875.9  363.53  4929.1  360.92
  4972.3  361.77  4978.8  356.61  4988.2  352.98  4993.9  353.31    4996  351.99
  4998.7  351.49    5002  351.99  5012.1  354.91  5019.9  362.54    5391  360.66
  5403.8  358.38  5414.2  358.26  5455.4  361.01  5473.4  368.54  5478.6   368.3
  5496.6  371.94  5506.9  372.09  5514.7  375.36  5555.9  382.88  5620.3  388.35
#Mann= 4 ,-1 , 0
  4598.7     .05       0  4641.7     .16       0    4996     .07       0
    5002     .16       0
Bank Sta=4972.3,5019.9
XS Rating Curve= 0 ,0
Exp/Cntr=0.3,0.1

Type RM Length L Ch R = 1 ,3656    ,501,501,501
BEGIN DESCRIPTION:
PINE BRANCH 6.0
END DESCRIPTION:
XS GIS Cut Line= 3
      3594272.79     10532849.97      3594499.61     10532760.19
      3595199.64     10532360.17
#Sta/Elev= 30
  4767.5  391.73  4850.1  387.02  4882.4  383.14  4888.5  381.29  4957.7  371.35
  4972.2  370.92 4981.82   361.1  4989.9  355.69  4993.6  349.86  4996.3  349.36
  4999.6  349.86  5008.8  352.68  5014.3  352.68  5019.4  360.02  5121.6  359.74
  5143.2  360.78  5202.2  358.97  5304.4  359.41    5357  358.79  5369.2  356.97
  5437.6  359.15  5487.3  358.28  5518.2  360.88  5540.5  364.01  5552.8  367.31
  5590.5  370.43  5605.3  372.71  5707.5  379.27    5737  382.36  5817.7  386.74
#Mann= 4 ,-1 , 0
  4767.5     .16       0  4993.6     .07       0  4999.6     .16       0
  5590.5     .05       0
Bank Sta=4981.82,5019.4
XS Rating Curve= 0 ,0
Exp/Cntr=0.3,0.1

Type RM Length L Ch R = 1 ,3155    ,319,319,319
BEGIN DESCRIPTION:
PINE BRANCH 5.0
END DESCRIPTION:
XS GIS Cut Line= 3
      3594349.27     10533051.34      3594739.11     10533034.58
      3595414.05     10532696.02
#Sta/Elev= 30
  4493.2  390.91  4523.6  390.87  4533.6  390.03  4543.6  387.53  4553.6   387.7
  4573.6  383.83  4603.6  374.88  4623.7  370.65  4637.5  370.11  4643.7  367.75
  4685.4  362.99  4753.8  357.22  4843.9   356.5  4881.5  357.36  4962.3  357.69
  4969.6  355.18  4984.6  353.46  4994.5  349.33  4997.2  348.83  5000.5  349.33
    5007  349.49  5014.2  352.64  5019.8  353.07  5036.6  357.98  5096.5  358.24
  5125.9  355.88  5163.7  356.17  5221.3  360.63  5438.7  374.42  5638.5  381.95
#Mann= 6 ,-1 , 0
  4493.2     .16       0  4685.4      .1       0  4881.5     .16       0
  4994.5     .07       0  5000.5     .16       0  5221.3     .05       0
Bank Sta=4962.3,5036.6
XS Rating Curve= 0 ,0
Exp/Cntr=0.3,0.1

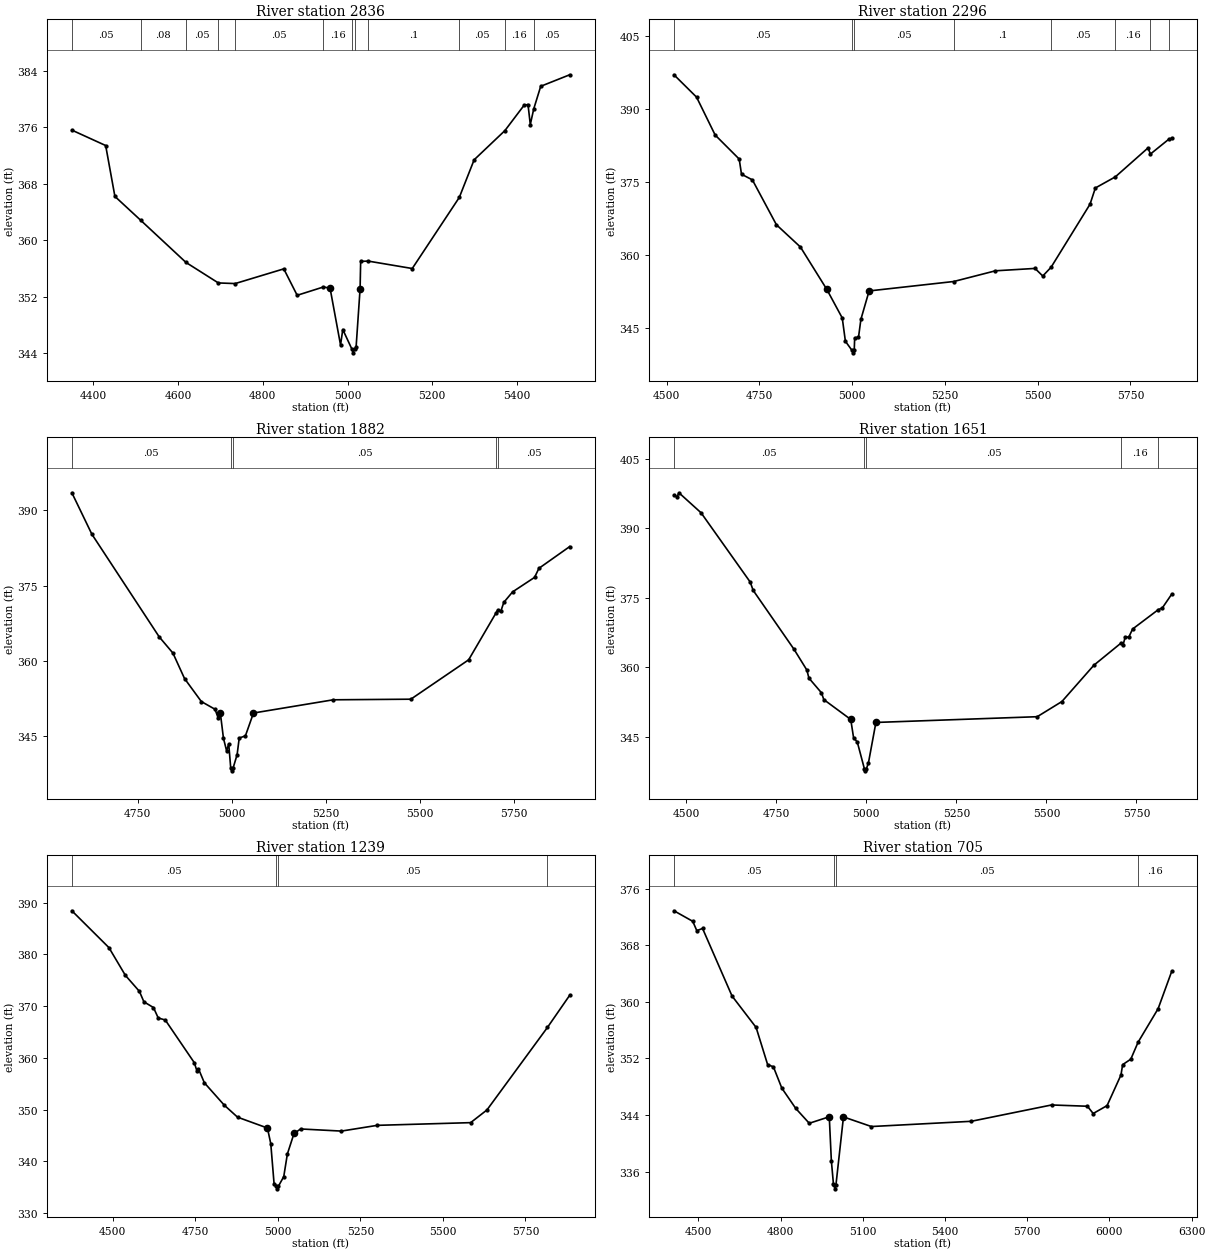
Type RM Length L Ch R = 1 ,2836    ,540,540,540
BEGIN DESCRIPTION:
PINE BRANCH 4.0
END DESCRIPTION:
XS GIS Cut Line= 3
      3594356.48     10533350.45      3594540.95     10533430.75
      3595450.24     10533081.35
#Sta/Elev= 30
  4349.2  375.58    4429   373.4  4450.8   366.2  4511.6  362.83  4618.6  356.86
    4695  353.96  4734.7  353.87  4849.5  355.95  4881.1  352.21  4943.2  353.39
  4958.8  353.21  4983.5  345.18  4988.8  347.37  5010.5  344.57  5013.2  344.07
  5016.5  344.57  5020.3  344.94 5029.66  353.14    5031  357.01  5048.8  357.05
  5152.8     356  5263.9  366.06  5298.9  371.38  5371.5  375.51  5416.7  379.09
  5426.1   379.2  5431.5  376.37  5439.6  378.58  5456.1  381.78  5524.5  383.41
#Mann= 12 ,-1 , 0
  4349.2     .05       0  4511.6     .08       0  4618.6     .05       0
    4695      .1       0  4734.7     .05       0  4943.2     .16       0
  5010.5     .07       0  5016.5     .16       0  5048.8      .1       0
  5263.9     .05       0  5371.5     .16       0  5439.6     .05       0
Bank Sta=4958.8,5029.66
XS Rating Curve= 0 ,0
Exp/Cntr=0.3,0.1

Type RM Length L Ch R = 1 ,2296    ,414,414,414
BEGIN DESCRIPTION:
PINE BRANCH 3.0
END DESCRIPTION:
XS GIS Cut Line= 3
      3594508.94     10534054.83      3594799.61     10533660.19
      3595449.61     10533110.19
#Sta/Elev= 30
  4519.8  397.02  4580.7  392.42  4630.8  384.63  4695.6  379.69  4701.8  376.57
  4731.1  375.41  4795.9  366.18  4860.6   361.6  4931.6   352.9  4973.3  347.01
  4981.8  342.22  4999.6  340.34  5002.4  339.84  5005.6  340.34  5006.8  342.93
  5017.1  343.03  5023.6  346.74  5045.7  352.57  5273.8  354.51  5386.2  356.71
  5492.8   357.2  5513.7  355.64  5536.1  357.44  5641.1  370.41  5655.4  373.74
  5709.3  376.03  5797.1  381.96    5804  380.73  5854.4  383.83  5861.4  383.95
#Mann= 8 ,-1 , 0
  4519.8     .05       0  4999.6     .03       0  5005.6     .05       0
  5273.8      .1       0  5536.1     .05       0  5709.3     .16       0
    5804     .08       0  5854.4     .05       0
Bank Sta=4931.6,5045.7
XS Rating Curve= 0 ,0
Exp/Cntr=0.3,0.1

Type RM Length L Ch R = 1 ,1882    ,231,231,231
BEGIN DESCRIPTION:
PINE BRANCH 2.0
END DESCRIPTION:
XS GIS Cut Line= 3
       3594599.6     10534160.19      3594999.61     10533960.19
      3595749.64     10533510.17
#Sta/Elev= 30
  4575.3  393.53  4628.4  385.26  4807.3  364.76  4843.6  361.54  4874.4  356.46
  4919.1  351.86  4955.4  350.32  4963.8  348.57  4969.4  349.66  4977.8  344.54
  4986.2  342.01  4991.8  343.42  4997.2  338.53  4999.9  338.03  5003.2  338.53
  5014.1  341.27  5019.7  344.58  5036.1  345.01  5057.5  349.57  5269.4  352.21
  5475.4  352.33  5628.9  360.19    5702   369.6  5705.8  370.09  5714.5  369.91
  5722.2  371.65  5745.6  373.75  5803.9  376.64  5815.5  378.45  5897.2  382.79
#Mann= 5 ,-1 , 0
  4575.3     .05       0  4997.2     .03       0  5003.2     .05       0
    5702     .16       0  5705.8     .05       0
Bank Sta=4969.4,5057.5
XS Rating Curve= 0 ,0
Exp/Cntr=0.3,0.1

Type RM Length L Ch R = 1 ,1651    ,412,412,412
BEGIN DESCRIPTION:
Mapping XS d1c5f732
END DESCRIPTION:
XS GIS Cut Line= 2
      3594566.83     10534297.48      3595904.96     10533951.23
#Sta/Elev= 30
  4465.8  397.19  4474.4  396.85  4479.6  397.72    4541   393.4  4677.5  378.42
  4685.6  376.64  4799.3  363.87  4834.8   359.4  4840.5  357.66  4875.4  354.48
  4881.8  353.02  4956.6  348.73  4964.5  344.77  4974.8  343.85  4994.3  338.12
    4997  337.62  5000.3  338.12  5005.8  339.36  5026.5  348.08  5474.4  349.32
  5542.9   352.6  5631.7  360.45    5707  365.23  5712.9  364.89  5718.5  366.47
  5728.9  366.57  5739.2  368.27  5810.2  372.44  5821.8  372.84    5848  375.83
#Mann= 5 ,-1 , 0
  4465.8     .05       0  4994.3     .03       0  5000.3     .05       0
    5707     .16       0  5810.2     .05       0
Bank Sta=4956.6,5026.5
XS Rating Curve= 0 ,0
Exp/Cntr=0.3,0.1

Type RM Length L Ch R = 1 ,1239    ,534,534,534
BEGIN DESCRIPTION:
Mapping XS 1cd0c260
END DESCRIPTION:
XS GIS Cut Line= 4
        3594598.     10534414.65      3594819.39     10534586.55
      3595345.43     10534526.66      3595931.35     10534146.46
#Sta/Elev= 30
    4376  388.44  4488.3  381.32  4538.1  375.96  4580.6  372.87  4594.2  370.85
  4623.2  369.74  4637.7  367.72  4658.9  367.34  4747.1  359.07  4754.4  357.57
  4759.5  357.92  4777.3  355.21  4837.7  350.88  4877.9  348.56  4968.5  346.46
  4978.6  343.43  4988.6   335.7  4995.7  335.21  4998.5  334.71  5001.7  335.21
  5017.9  337.07  5028.9  341.45    5049  345.41  5069.2  346.28  5192.6  345.87
  5301.3  346.98  5584.1   347.5  5633.5  349.95  5816.7  365.89  5884.2  372.11
#Mann= 4 ,-1 , 0
    4376     .05       0  4995.7     .03       0  5001.7     .05       0
  5816.7     .16       0
Bank Sta=4968.5,5049
XS Rating Curve= 0 ,0
Exp/Cntr=0.3,0.1

Type RM Length L Ch R = 1 ,705     ,344,344,344
BEGIN DESCRIPTION:
Mapping XS 5c8dfa6d
END DESCRIPTION:
XS GIS Cut Line= 5
      3594676.13     10534628.19      3594845.43     10534873.01
      3595160.53     10535070.93      3595512.09     10534984.99
      3595957.43     10534339.12
#Sta/Elev= 30
  4411.3  372.88  4479.8  371.39  4494.6  370.07  4515.6  370.38  4623.1  360.83
    4711  356.38  4752.9  351.14  4774.1  350.81  4804.8   347.8  4855.6  344.93
  4904.9  342.83  4977.9  343.75  4985.5  337.53  4993.2   334.2  4996.1  334.06
  4998.9  333.56  5002.1  334.06  5029.7  343.73  5131.6  342.37  5495.8  343.11
  5788.9  345.42  5919.8  345.24  5940.7  344.21  5991.4  345.33  6042.1  349.66
  6048.2  351.12    6078   351.9  6104.5  354.29  6177.6  359.03  6227.5  364.34
#Mann= 4 ,-1 , 0
  4411.3     .05       0  4996.1     .03       0  5002.1     .05       0
  6104.5     .16       0
Bank Sta=4977.9,5029.7
XS Rating Curve= 0 ,0
Exp/Cntr=0.3,0.1

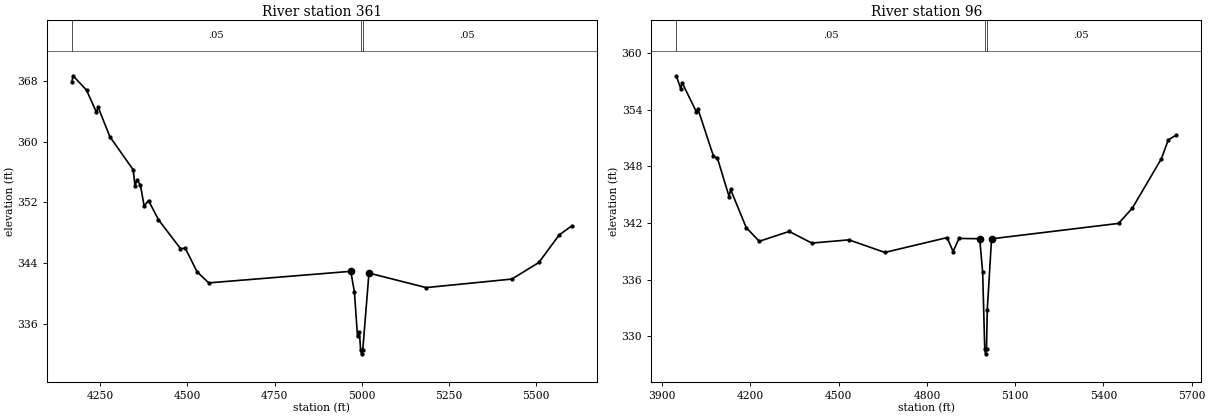
Type RM Length L Ch R = 1 ,361     ,265,265,265
BEGIN DESCRIPTION:
Mapping XS 9c42ca8b
END DESCRIPTION:
XS GIS Cut Line= 4
      3594683.98      10534711.6      3594853.24     10535292.28
      3595155.32     10535383.43      3595663.13     10535310.51
#Sta/Elev= 30
    4169  367.88    4172  368.66  4210.7  366.78    4239  363.88  4244.2  364.51
  4277.7  360.65  4344.6   356.3  4349.9  354.12  4355.1  354.98  4365.4  354.27
  4375.9  351.54  4388.6  352.26  4416.8  349.75    4480  345.95  4494.2  345.97
  4527.7  342.89  4561.2  341.43  4968.5  342.95    4979  340.22  4987.9   334.4
  4993.1  334.91  4996.9   332.6  4999.6   332.1  5002.9   332.6  5020.7  342.72
  5184.6  340.81  5430.5  341.93  5507.9  344.11  5566.5  347.75  5602.4  348.92
#Mann= 3 ,-1 , 0
    4169     .05       0  4996.9     .03       0  5002.9     .05       0
Bank Sta=4968.5,5020.7
XS Rating Curve= 0 ,0
Exp/Cntr=0.3,0.1

Type RM Length L Ch R = 1 ,96      ,0,0,0
BEGIN DESCRIPTION:
PINE BRANCH 1.0
END DESCRIPTION:
XS GIS Cut Line= 5
      3594621.47     10534802.71      3594751.68     10535513.64
      3594923.55     10535599.57      3595137.09     10535623.01
      3595659.03      10535394.5
#Sta/Elev= 30
  3947.7  357.58  3962.8  356.22  3967.8  356.84  4015.9  353.77    4021   354.1
  4074.2  349.07  4087.5  348.87  4127.3   344.8  4132.4  345.55  4185.6  341.51
  4229.8  340.07  4331.5  341.11  4408.4  339.88  4534.8  340.22  4656.8  338.89
  4868.7  340.46  4888.8  338.98  4908.9  340.37  4979.4  340.34  4989.4   336.8
  4996.5  328.66  4999.2  328.16  5002.5  328.66  5005.1  332.81  5019.6  340.33
  5451.4  341.96  5498.2  343.57  5597.2  348.81  5620.6   350.8  5647.2   351.3
#Mann= 3 ,-1 , 0
  3947.7     .05       0  4996.5     .03       0  5002.5     .05       0
Bank Sta=4979.4,5019.6
XS Rating Curve= 0 ,0
Exp/Cntr=0.3,0.1

Chan Stop Cuts=-1
Use User Specified Reach Order=0
Composite Channel Slope=5