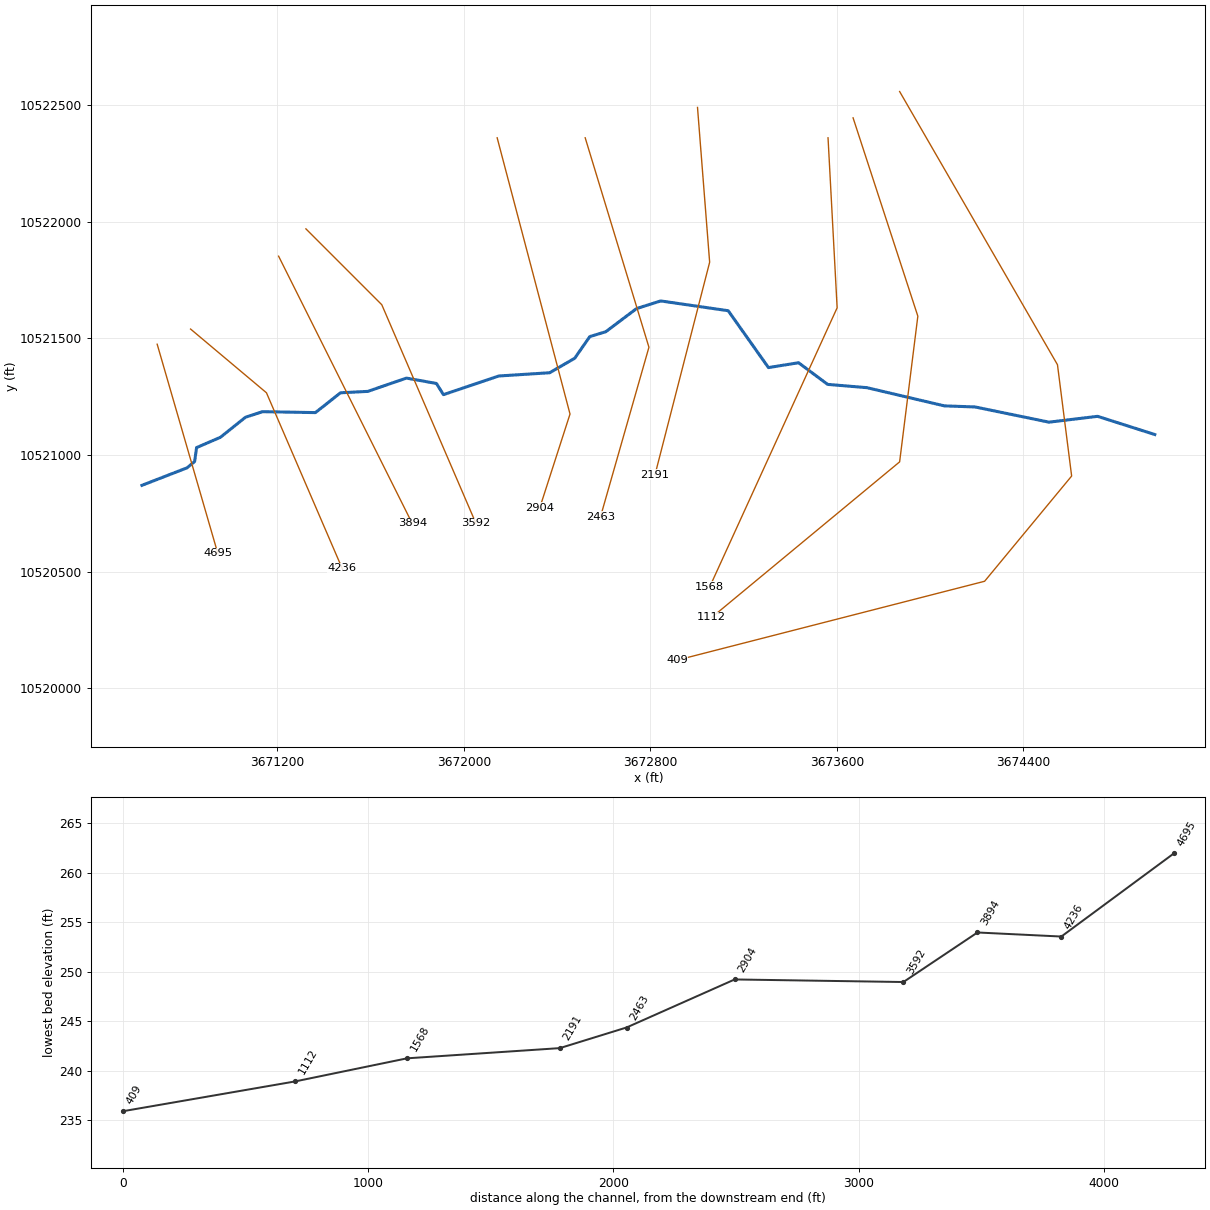
--- RED OAK BRANCH.prj (project) ---

Proj Title=RED OAK BRANCH Base Level Engineering
Current Plan=p01
Default Exp/Contr=0.3,0.1
English Units
Geom File=g01
Flow File=f01
Plan File=p01
Y Axis Title=Elevation
X Axis Title(PF)=Main Channel Distance
X Axis Title(XS)=Station
BEGIN DESCRIPTION:
RED OAK BRANCH
END DESCRIPTION:
DSS Export Rating Curves= 0
DSS Export Rating Curve Sorted= 0
DSS Export Volume Flow Curves= 0
DXF OffsetX= 0
DXF OffsetY= 0
DXF ScaleX= 1
DXF ScaleY= 10

--- RED OAK BRANCH.p01 (plan) ---

Plan Title=Multiple Run
Short Identifier=Multiple
Geom File=g01
Flow File=f01
Subcritical Flow
K Sum by GR= 0
Std Step Tol= 0.01
Critical Tol= 0.01
Num of Std Step Trials= 20
Max Error Tol= 0.3
Flow Tol Ratio= 0.001
Split Flow NTrial= 30
Split Flow Tol= 0.02
Split Flow Ratio= 0.02
Log Output Level= 0
Friction Slope Method= 1
Unsteady Friction Slope Method= 2
Unsteady Bridges Friction Slope Method= 1
Parabolic Critical Depth
Global Vel Dist=  1 , 1 , 1
Global Log Level= 0
CheckData=True
Encroach Param= -1, 0, 0, 0
BEGIN DESCRIPTION:
Multiple Run
END DESCRIPTION:

--- RED OAK BRANCH.f01 (steady flow) ---

Flow Title=Multiple
Number of Profiles=7
Profile Names=10-year,25-year,50-year,1pct_min,100-year,1pct_plu,500-year
River Rch & RM= RED OAK BRANCH,Reach-1,4695
     558     764     935     843    1140    1542    1700
River Rch & RM= RED OAK BRANCH,Reach-1,4236
     672     926    1139    1030    1392    1883    2090
Boundary for River Rch & Prof#=RED OAK BRANCH,Reach-1,1
Up Type=0
Dn Type=3
Dn Slope=0.005
Boundary for River Rch & Prof#=RED OAK BRANCH,Reach-1,2
Up Type=0
Dn Type=3
Dn Slope=0.005
Boundary for River Rch & Prof#=RED OAK BRANCH,Reach-1,3
Up Type=0
Dn Type=3
Dn Slope=0.005
Boundary for River Rch & Prof#=RED OAK BRANCH,Reach-1,4
Up Type=0
Dn Type=3
Dn Slope=0.005
Boundary for River Rch & Prof#=RED OAK BRANCH,Reach-1,5
Up Type=0
Dn Type=3
Dn Slope=0.005
Boundary for River Rch & Prof#=RED OAK BRANCH,Reach-1,6
Up Type=0
Dn Type=3
Dn Slope=0.005
Boundary for River Rch & Prof#=RED OAK BRANCH,Reach-1,7
Up Type=0
Dn Type=3
Dn Slope=0.005

--- RED OAK BRANCH.g01 (geometry) ---

Geom Title=Existing Conditions
Program Version=4.10

River Reach=RED OAK BRANCH  ,Reach-1
Reach XY= 30
       3670619.5       10520870.      3670812.75       10520945.
       3670845.5       10520972.        3670854.       10521032.
        3670956.       10521076.       3671063.5       10521162.
      3671136.75       10521186.      3671363.75       10521182.
      3671471.25       10521267.      3671588.25       10521273.
        3671754.       10521330.      3671882.75       10521307.
      3671912.75       10521259.        3672150.       10521339.
       3672368.5       10521353.      3672475.75       10521415.
       3672540.5       10521508.      3672609.25       10521529.
      3672740.75       10521628.       3672844.5       10521661.
      3673134.25       10521619.        3673307.       10521375.
        3673436.       10521396.      3673560.75       10521303.
        3673729.       10521289.      3674061.52     10521210.87
      3674193.02     10521206.26      3674510.25       10521141.
      3674718.75       10521166.        3674964.       10521088.

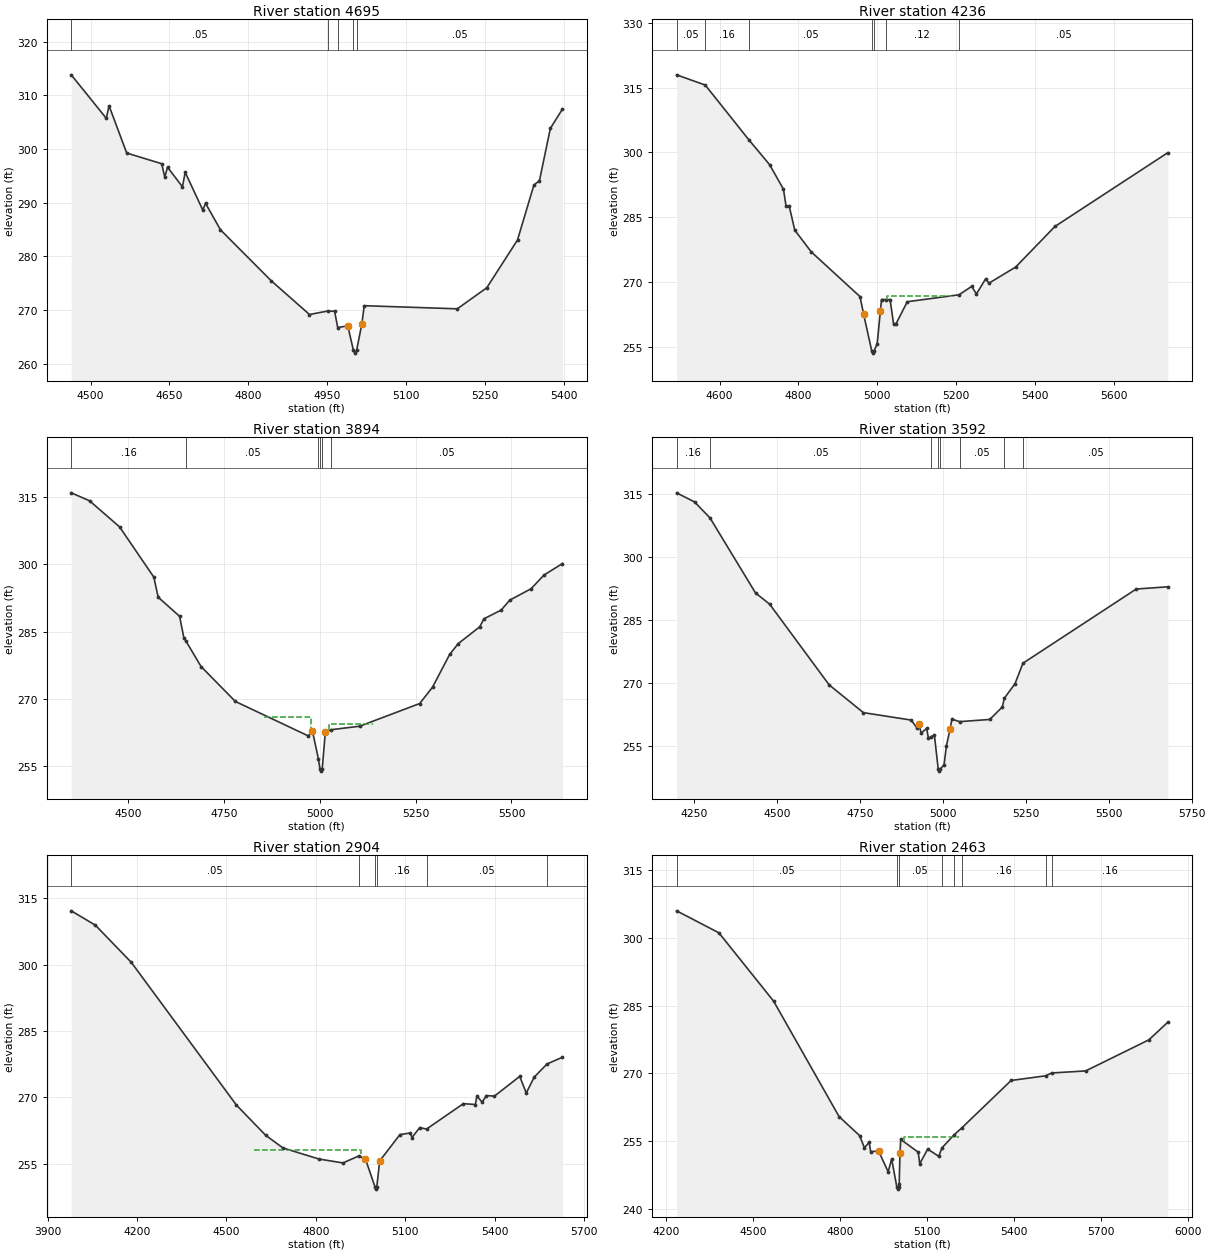
Type RM Length L Ch R = 1 ,4695    ,459,459,459
BEGIN DESCRIPTION:
RED OAK BRANCH 9.0
END DESCRIPTION:
XS GIS Cut Line= 2
      3670684.89     10521475.34      3670944.96     10520578.08
#Sta/Elev= 30
  4463.3  313.83    4530  305.72  4535.2  308.07  4568.8  299.25  4635.3  297.26
  4641.2  294.74  4646.4  296.61  4674.8  292.95    4680  295.66  4713.5  288.62
  4718.7  289.88  4747.1  284.94  4843.5  275.45  4916.4  269.15  4952.4  269.82
  4964.2  269.74  4970.1  266.72  4989.2  267.03    5000  262.45  5002.7  261.95
    5006  262.45 5015.91  267.36  5020.5  270.79  5197.5  270.21  5253.6  274.14
    5312  283.04  5343.2  293.29  5353.7  294.09  5374.5  303.86  5397.5  307.45
#Mann= 5 ,-1 , 0
  4463.3     .05       0  4952.4     .12       0  4970.1     .05       0
    5000     .03       0    5006     .05       0
Bank Sta=4989.2,5015.91
XS Rating Curve= 0 ,0
Exp/Cntr=0.3,0.1

Type RM Length L Ch R = 1 ,4236    ,342,342,342
BEGIN DESCRIPTION:
RED OAK BRANCH 8.0
END DESCRIPTION:
XS GIS Cut Line= 3
      3670828.12     10521540.47      3671153.63     10521267.05
      3671478.44     10520513.47
#Sta/Elev= 30
    4491  317.95  4563.7  315.58  4675.2  302.81    4727  297.16  4762.1  291.46
  4768.6  287.61  4776.4  287.66  4790.7  282.02  4832.5  276.99  4956.2  266.63
  4965.4  262.54  4985.9  254.06  4988.7  253.56  4991.9  254.06  4999.8  255.77
 5007.73  263.23  5010.7  265.96  5020.8  265.96  5032.5  265.94  5041.4  260.21
  5046.8  260.22    5076  265.45  5207.3  267.06  5239.4     269  5251.4  267.25
  5274.9  270.77  5282.9  269.73  5350.9  273.48  5450.4  282.86  5736.7  299.94
#Mann= 7 ,-1 , 0
    4491     .05       0  4563.7     .16       0  4675.2     .05       0
  4985.9     .03       0  4991.9     .05       0  5020.8     .12       0
  5207.3     .05       0
#XS Ineff= 1 ,-1
 5023.64 5189.89  266.73
Permanent Ineff=
       F
Bank Sta=4965.4,5007.73
XS Rating Curve= 0 ,0
Exp/Cntr=0.3,0.1

Type RM Length L Ch R = 1 ,3894    ,302,302,302
BEGIN DESCRIPTION:
RED OAK BRANCH 7.0
END DESCRIPTION:
XS GIS Cut Line= 2
      3671205.72     10521852.96      3671778.65     10520707.11
#Sta/Elev= 30
  4351.9  315.87  4399.7   314.1    4478  308.29  4567.4  297.11  4578.6  292.66
  4634.5   288.4  4645.7   283.6  4651.6  282.82  4690.4  277.24  4779.9  269.47
  4969.9  261.81  4981.1  262.83  4996.7  256.61  5000.5  254.47  5003.2  253.97
  5006.5  254.47  5014.6  262.74  5028.6  263.17  5104.1  263.96  5260.6     269
  5294.2  272.65  5338.9  279.94  5361.2  282.33  5417.1  286.06  5428.3  287.86
    5473  289.78  5495.4  291.99  5551.3  294.55  5584.8  297.58    5633  300.15
#Mann= 6 ,-1 , 0
  4351.9     .16       0  4651.6     .05       0  4996.7     .12       0
  5000.5     .07       0  5006.5     .12       0  5028.6     .05       0
#XS Ineff= 2 ,-1
 4854.55 4976.36  265.94 5023.64 5139.09  264.54
Permanent Ineff=
       F       F
Bank Sta=4981.1,5014.6
XS Rating Curve= 0 ,0
Exp/Cntr=0.3,0.1

Type RM Length L Ch R = 1 ,3592    ,688,688,688
BEGIN DESCRIPTION:
RED OAK BRANCH 6.0
END DESCRIPTION:
XS GIS Cut Line= 3
      3671322.92     10521970.15      3671648.42     10521644.65
      3672052.05     10520707.18
#Sta/Elev= 30
  4197.1  315.38  4251.3  313.21    4298  309.38  4435.1  291.49  4477.6  288.82
    4657  269.56  4760.3  262.93    4904  261.16    4922  259.29  4927.5  260.27
  4934.5  258.04    4951  259.15  4956.5  256.77  4964.1  257.21  4974.5   257.5
  4985.9  249.47  4988.7  248.97  4991.9  249.47  5003.5  250.47  5010.7  255.07
  5021.6  258.95  5027.1  261.36  5050.7  260.78  5141.3   261.3  5179.1  264.27
  5185.3  266.36  5217.5  269.85  5241.4  274.72  5582.8  292.42  5678.1  292.96
#Mann= 8 ,-1 , 0
  4197.1     .16       0    4298     .05       0  4964.1     .16       0
  4985.9     .07       0  4991.9     .16       0  5050.7     .05       0
  5185.3     .16       0  5241.4     .05       0
Bank Sta=4927.5,5021.6
XS Rating Curve= 0 ,0
Exp/Cntr=0.3,0.1

Type RM Length L Ch R = 1 ,2904    ,441,441,441
BEGIN DESCRIPTION:
RED OAK BRANCH 5.0
END DESCRIPTION:
XS GIS Cut Line= 3
      3672143.22     10522360.78      3672455.71      10521175.9
      3672325.97      10520773.7
#Sta/Elev= 30
  3979.5  312.21  4060.5  308.96  4181.4  300.52  4533.7  268.25  4631.6  261.43
  4689.7  258.55  4810.5  256.04  4891.1  255.16  4943.6  256.72  4966.5  256.06
  4998.6  249.73  5001.4  249.23  5004.6  249.73  5014.3  255.61  5082.2  261.57
  5117.3  261.94  5122.5  260.89  5148.7  263.16  5171.5  262.82    5295  268.57
  5335.2  268.38  5340.5  270.28    5358  268.93  5372.6  270.39  5399.3  270.28
  5484.1  274.74    5506  270.99  5532.8  274.59  5575.6  277.55  5627.5  279.08
#Mann= 6 ,-1 , 0
  3979.5     .05       0  4943.6     .16       0  4998.6     .07       0
  5004.6     .16       0  5171.5     .05       0  5575.6     .16       0
#XS Ineff= 1 ,-1
 4592.05    4950  258.02
Permanent Ineff=
       F
Bank Sta=4966.5,5014.3
XS Rating Curve= 0 ,0
Exp/Cntr=0.3,0.1

Type RM Length L Ch R = 1 ,2463    ,272,272,272
BEGIN DESCRIPTION:
RED OAK BRANCH 4.0
END DESCRIPTION:
XS GIS Cut Line= 3
      3672520.81     10522360.81      3672794.25     10521462.36
      3672586.19     10520734.14
#Sta/Elev= 30
  4235.4  305.95  4381.5  301.09  4570.5  285.97  4796.6  260.43  4867.6  256.21
  4884.1  253.52  4900.4  254.75  4905.6   252.7  4933.3  252.77  4966.1  248.22
  4978.2  251.05    4996  244.88  4998.7  244.38    5002  244.88  5004.2  245.49
 5006.93  252.35  5009.6  255.37  5069.9  252.55  5075.1     250  5102.7  253.24
  5140.8  251.64  5151.9  253.51  5192.9  256.33  5221.4  257.99  5390.8  268.42
  5509.8  269.45  5530.9  270.08  5648.2  270.53  5866.6  277.41  5931.9  281.31
#Mann= 8 ,-1 , 0
  4235.4     .05       0    4996     .04       0    5002     .05       0
  5151.9     .16       0  5192.9     .05       0  5221.4     .16       0
  5509.8     .05       0  5530.9     .16       0
#XS Ineff= 1 ,-1
  5019.2 5211.48  255.86
Permanent Ineff=
       F
Bank Sta=4933.3,5006.93
XS Rating Curve= 0 ,0
Exp/Cntr=0.3,0.1

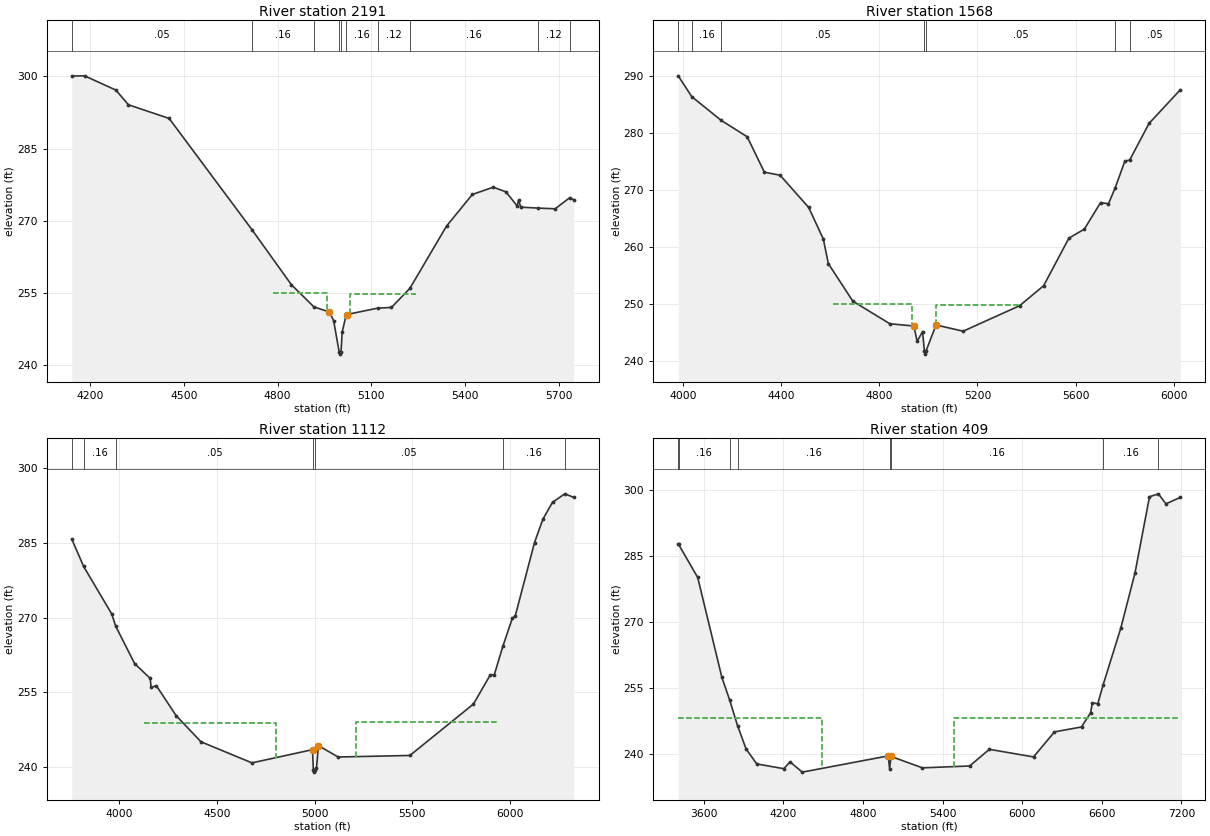
Type RM Length L Ch R = 1 ,2191    ,623,623,623
BEGIN DESCRIPTION:
RED OAK BRANCH 3.0
END DESCRIPTION:
XS GIS Cut Line= 3
      3673002.59     10522490.98      3673054.67     10521826.94
      3672820.29     10520915.47
#Sta/Elev= 30
  4140.9  300.07  4181.8  300.11  4282.1  297.15  4322.2   294.1  4452.6  291.26
  4718.6  268.07  4843.6  256.75  4916.1  252.11  4965.8  251.04  4979.2  249.25
  4996.8   242.8  4999.6   242.3  5002.8   242.8  5006.5  246.88  5018.4  250.17
  5020.5  250.52  5120.8  251.86  5164.2     252  5223.1  255.95  5340.5  268.89
  5423.1  275.46    5490  276.97  5530.8  276.01  5566.3  273.11  5571.5  274.31
    5578  272.83  5632.4  272.64  5688.5  272.49  5734.7  274.79  5748.1  274.36
#Mann= 10 ,-1 , 0
  4140.9     .05       0  4718.6     .16       0  4916.1     .12       0
  4996.8     .07       0  5002.8     .12       0  5018.4     .16       0
  5120.8     .12       0  5223.1     .16       0  5632.4     .12       0
  5734.7     .16       0
#XS Ineff= 2 ,-1
 4784.43  4958.3  255.07 5030.91 5242.61  254.89
Permanent Ineff=
       F       F
Bank Sta=4965.8,5020.5
XS Rating Curve= 0 ,0
Exp/Cntr=0.3,0.1

Type RM Length L Ch R = 1 ,1568    ,456,456,456
BEGIN DESCRIPTION:
RED OAK BRANCH 2.0
END DESCRIPTION:
XS GIS Cut Line= 3
      3673562.48     10522360.78      3673601.54     10521631.63
      3673055.02     10520434.48
#Sta/Elev= 30
  3980.5  289.95  4035.4  286.32  4155.1  282.17  4261.5  279.29  4331.6  273.09
  4395.4  272.57  4511.9  266.94  4571.9   261.4    4592  257.12  4692.1  250.53
  4843.2  246.58  4940.9  246.19  4954.1  243.49  4976.1  245.22  4983.9  241.77
  4986.7  241.27  4989.9  241.77  5031.1  246.37  5141.6  245.28  5371.8  249.74
  5469.6  253.23  5572.7  261.56  5635.7  263.14  5701.6  267.77  5733.9  267.58
  5761.3  270.35  5800.6  275.02  5820.5  275.23  5899.5  281.64  6026.7  287.51
#Mann= 7 ,-1 , 0
  3980.5     .05       0  4035.4     .16       0  4155.1     .05       0
  4983.9     .03       0  4989.9     .05       0  5761.3     .16       0
  5820.5     .05       0
#XS Ineff= 2 ,-1
 4611.36 4935.23249.9524 5032.39 5371.59249.8917
Permanent Ineff=
       F       F
Bank Sta=4940.9,5031.1
XS Rating Curve= 0 ,0
Exp/Cntr=0.3,0.1

Type RM Length L Ch R = 1 ,1112    ,703,703,703
BEGIN DESCRIPTION:
Mapping XS cf7f2d5c
END DESCRIPTION:
XS GIS Cut Line= 4
      3673669.91     10522446.38      3673947.68     10521595.71
      3673869.56     10520970.71      3673063.44     10520303.28
#Sta/Elev= 30
  3756.4   285.8    3817   280.3  3961.2  270.73  3981.7  268.25  4078.5  260.75
  4157.8   257.8    4163  255.98  4189.7  256.31  4290.6  250.31  4418.1  245.04
    4679   240.8  4989.4  243.46  4993.5  239.44  4996.2  238.94  4999.5  239.44
  5009.6   239.7  5019.6  244.28  5120.4  241.98    5488  242.29  5813.6  252.63
  5899.5  258.47  5920.4  258.53  5964.1  264.23  6012.8  269.88  6027.2  270.28
  6126.2  285.08  6169.1  289.79  6218.6  293.19  6281.5  294.89  6327.7  294.17
#Mann= 7 ,-1 , 0
  3756.4     .05       0    3817     .16       0  3981.7     .05       0
  4993.5     .03       0  4999.5     .05       0  5964.1     .16       0
  6281.5     .05       0
#XS Ineff= 2 ,-1
 4127.27 4802.27248.8737 5211.36 5946.02249.0997
Permanent Ineff=
       F       F
Bank Sta=4989.4,5019.6
XS Rating Curve= 0 ,0
Exp/Cntr=0.3,0.1

Type RM Length L Ch R = 1 ,409     ,0,0,0
BEGIN DESCRIPTION:
RED OAK BRANCH 1.0
END DESCRIPTION:
XS GIS Cut Line= 5
      3673869.56     10522559.25      3674546.64     10521387.38
       3674607.4     10520909.95      3674234.14     10520458.56
       3672914.7     10520120.02
#Sta/Elev= 30
  3408.5  287.68    3411  287.65  3555.1  280.15  3737.5  257.42  3796.9  252.23
  3855.2  246.48  3919.8  241.18  4000.2  237.79  4204.3  236.71  4250.5  238.27
  4343.1  235.93  4990.9  239.62    5001  236.66  5011.1   239.5  5248.5   236.9
  5604.1  237.33  5752.6  241.11  6085.2  239.38  6243.1  245.07    6447  246.19
    6515   249.4  6528.5  251.68  6569.2  251.45  6609.6  255.75  6742.1  268.57
  6849.5  281.13  6958.9  298.47  7026.3  299.13  7082.8  296.85  7191.1  298.32
#Mann= 8 ,-1 , 0
  3408.5     .05       0    3411     .16       0  3796.9     .05       0
  3855.2     .16       0    5001     .03       0  5011.1     .16       0
  6609.6     .16       0  7026.3     .05       0
#XS Ineff= 2 ,-1
 3130.68 4494.32248.3189 5488.64 7224.43248.3189
Permanent Ineff=
       F       F
Bank Sta=4990.9,5011.1
XS Rating Curve= 0 ,0
Exp/Cntr=0.3,0.1

Chan Stop Cuts=-1
Use User Specified Reach Order=0
Composite Channel Slope=5