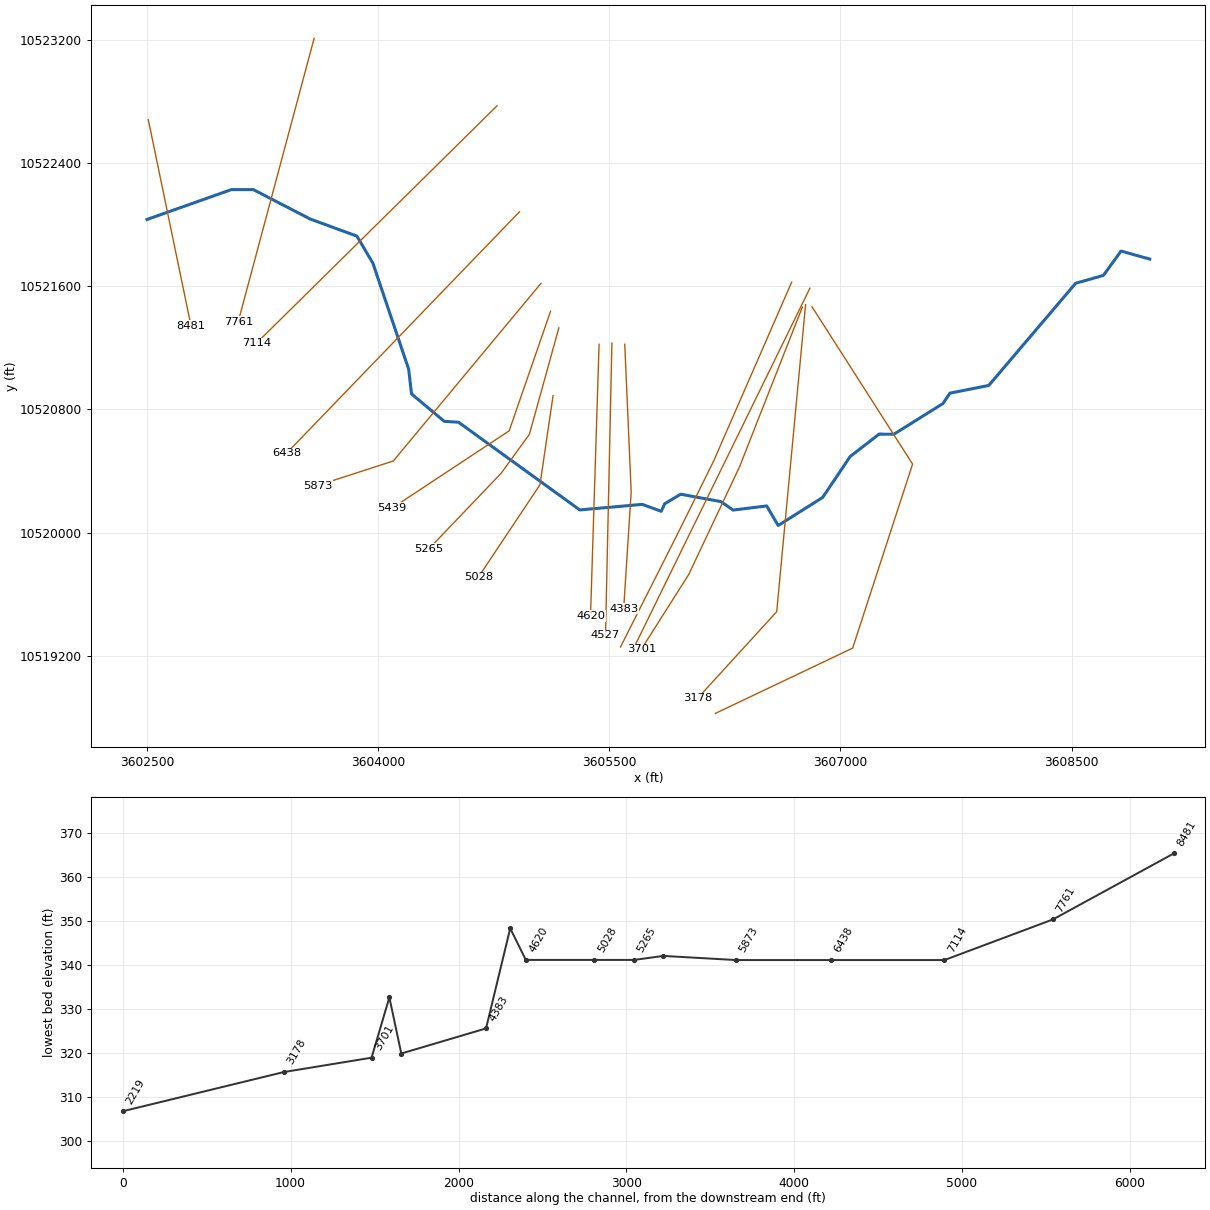
--- RENA BRANCH.prj (project) ---

Proj Title=RENA BRANCH Base Level Engineering
Current Plan=p01
Default Exp/Contr=0.3,0.1
English Units
Geom File=g01
Flow File=f01
Plan File=p01
BEGIN DESCRIPTION:
RENA BRANCH
END DESCRIPTION:

--- RENA BRANCH.p01 (plan) ---

Plan Title=Multiple Run
Short Identifier=Multiple
Geom File=g01
Flow File=f01
Subcritical Flow
K Sum by GR= 0
Std Step Tol= 0.01
Critical Tol= 0.01
Num of Std Step Trials= 20
Max Error Tol= 0.3
Flow Tol Ratio= 0.001
Split Flow NTrial= 30
Split Flow Tol= 0.02
Split Flow Ratio= 0.02
Log Output Level= 0
Friction Slope Method= 1
Unsteady Friction Slope Method= 2
Unsteady Bridges Friction Slope Method= 1
Parabolic Critical Depth
Global Vel Dist=  1 , 1 , 1
Global Log Level= 0
CheckData=True
Encroach Param= -1, 0, 0, 0
BEGIN DESCRIPTION:
Multiple Run
END DESCRIPTION:

--- RENA BRANCH.f01 (steady flow) ---

Flow Title=Multiple
Number of Profiles=7
Profile Names=10-year,25-year,50-year,1pct_min,100-year,1pct_plu,500-year
River Rch & RM= RENA BRANCH,Reach-1,8481
    1062    1469    1807    1623    2195    2968    3228
River Rch & RM= RENA BRANCH,Reach-1,3878
    1299    1814    2247    2030    2745    3712    4084
Boundary for River Rch & Prof#=RENA BRANCH,Reach-1,1
Up Type=0
Dn Type=3
Dn Slope=0.005
Boundary for River Rch & Prof#=RENA BRANCH,Reach-1,2
Up Type=0
Dn Type=3
Dn Slope=0.005
Boundary for River Rch & Prof#=RENA BRANCH,Reach-1,3
Up Type=0
Dn Type=3
Dn Slope=0.005
Boundary for River Rch & Prof#=RENA BRANCH,Reach-1,4
Up Type=0
Dn Type=3
Dn Slope=0.005
Boundary for River Rch & Prof#=RENA BRANCH,Reach-1,5
Up Type=0
Dn Type=3
Dn Slope=0.005
Boundary for River Rch & Prof#=RENA BRANCH,Reach-1,6
Up Type=0
Dn Type=3
Dn Slope=0.005
Boundary for River Rch & Prof#=RENA BRANCH,Reach-1,7
Up Type=0
Dn Type=3
Dn Slope=0.005

--- RENA BRANCH.g01 (geometry) ---

Geom Title=Existing Conditions

River Reach=RENA BRANCH,Reach-1
Reach XY= 30
      3602498.75     10522032.00      3603046.75     10522226.00
      3603189.00     10522226.00      3603558.25     10522035.00
      3603861.75     10521924.00      3603965.75     10521747.00
      3604197.50     10521060.00      3604215.75     10520900.00
      3604428.25     10520722.00      3604521.25     10520716.00
      3605307.75     10520147.00      3605714.00     10520183.00
      3605836.75     10520138.00      3605859.00     10520187.00
      3605963.25     10520249.00      3606223.75     10520201.00
      3606303.25     10520146.00      3606521.00     10520173.00
      3606595.75     10520046.00      3606884.25     10520228.00
      3607063.25     10520494.00      3607250.50     10520639.00
      3607346.00     10520638.00      3607665.75     10520838.00
      3607710.50     10520905.00      3607962.50     10520955.00
      3608526.25     10521618.00      3608706.25     10521669.00
      3608821.00     10521827.00      3609007.25     10521775.00

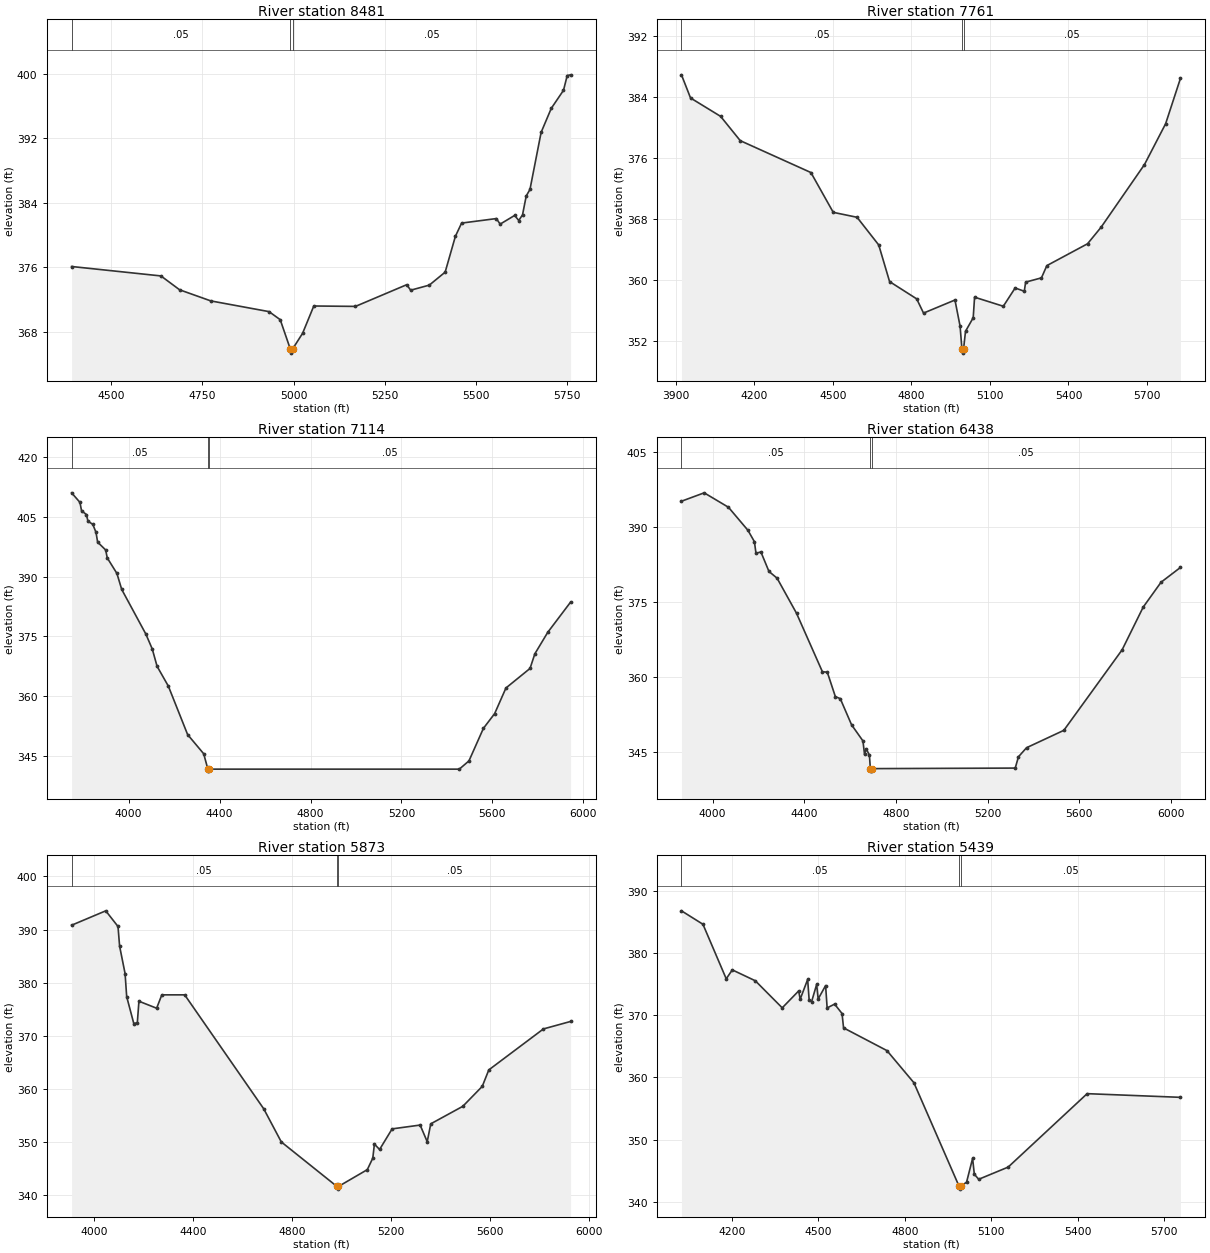
Type RM Length L Ch R = 1,8481,720,720,720
BEGIN DESCRIPTION:
RENA BRANCH 7.0
END DESCRIPTION:
XS GIS Cut Line= 2
      3602507.42     10522679.93      3602784.90     10521341.09
#Sta/Elev= 30
  4391.6  376.11  4636.4  374.94  4687.5  373.22  4773.1  371.84  4932.6  370.51
  4963.2  369.51  4990.9  365.86  4993.6  365.36  4996.9  365.86  5024.5  367.82
  5055.2  371.21  5169.4  371.16  5309.7  373.85  5320.7  373.17  5371.7  373.80
  5415.1  375.41  5443.2  379.86  5460.2  381.50  5555.4  382.06  5565.8  381.37
  5605.6  382.45  5616.8  381.82  5627.1  382.52  5637.3  384.87  5647.5  385.67
  5678.1  392.76  5705.9  395.74  5739.4  397.98  5749.6  399.81  5758.9  399.90
#Mann=3,-1,0
  4391.6    0.05       0  4990.9    0.03       0  4996.9    0.05       0
Bank Sta=4990.9,4996.9
Exp/Cntr=0.3,0.1

Type RM Length L Ch R = 1,7761,647,647,647
BEGIN DESCRIPTION:
Mapping XS e6d34ea6
END DESCRIPTION:
XS GIS Cut Line= 2
      3603583.81     10523207.74      3603090.75     10521367.45
#Sta/Elev= 30
  3922.4  386.92  3957.0  383.88  4071.9  381.46  4146.8  378.27  4416.6  374.08
  4501.9  368.85  4592.8  368.20  4675.6  364.56  4717.0  359.75  4820.5  357.48
  4846.6  355.61  4966.6  357.33  4986.2  353.89  4993.3  350.85  4996.1  350.35
  4999.3  350.85  5006.9  353.22  5036.3  355.00  5041.5  357.70  5151.2  356.51
  5196.4  358.91  5231.3  358.48  5236.5  359.68  5296.8  360.24  5317.5  361.85
  5472.8  364.72  5524.5  366.89  5690.2  375.13  5770.9  380.49  5827.6  386.46
#Mann=3,-1,0
  3922.4    0.05       0  4993.3    0.03       0  4999.3    0.05       0
Bank Sta=4993.3,4999.3
Exp/Cntr=0.3,0.1

Type RM Length L Ch R = 1,7114,676,676,676
BEGIN DESCRIPTION:
Mapping XS ea245f46
END DESCRIPTION:
XS GIS Cut Line= 2
      3604771.30     10522770.22      3603208.82     10521228.57
#Sta/Elev= 30
  3749.0  411.10  3785.6  408.70  3792.7  406.60  3813.9  405.64  3821.0  403.96
  3842.1  403.18  3856.3  401.15  3863.4  398.70  3898.7  396.73  3905.8  394.73
  3948.2  390.83  3969.4  386.80  4075.5  375.58  4103.7  371.83  4125.0  367.46
  4174.5  362.48  4259.3  350.29  4330.0  345.47  4348.3  341.60  4351.0  341.10
  4354.3  341.60  5454.4  341.60  5496.8  343.67  5560.5  351.87  5609.9  355.57
  5659.5  362.01  5765.5  366.93  5786.8  370.62  5843.3  376.00  5944.0  383.62
#Mann=3,-1,0
  3749.0    0.05       0  4348.3   0.033       0  4354.3    0.05       0
Bank Sta=4348.3,4354.3
Exp/Cntr=0.3,0.1

Type RM Length L Ch R = 1,6438,565,565,565
BEGIN DESCRIPTION:
Mapping XS d4aee4ed
END DESCRIPTION:
XS GIS Cut Line= 2
      3604917.16     10522082.74      3603404.87     10520514.96
#Sta/Elev= 30
  3863.8  395.08  3963.0  396.76  4069.0  393.87  4153.9  389.27  4182.2  386.99
  4189.1  384.67  4210.5  384.94  4245.7  381.04  4281.2  379.69  4366.1  372.67
  4479.0  360.98  4500.4  360.89  4535.6  356.00  4557.0  355.60  4606.4  350.36
  4656.0  347.14  4663.0  344.43  4670.2  345.58  4684.3  344.28  4688.3  341.60
  4691.0  341.10  4694.3  341.60  5320.8  341.71  5334.9  343.97  5370.2  345.78
  5533.0  349.26  5787.4  365.36  5879.5  373.91  5957.2  378.87  6042.1  381.84
#Mann=3,-1,0
  3863.8    0.05       0  4688.3   0.033       0  4694.3    0.05       0
Bank Sta=4688.3,4694.3
Exp/Cntr=0.3,0.1

Type RM Length L Ch R = 1,5873,434,434,434
BEGIN DESCRIPTION:
Mapping XS aa4f1908
END DESCRIPTION:
XS GIS Cut Line= 3
      3605056.05     10521617.47      3604097.69     10520464.67
      3603605.03     10520305.07
#Sta/Elev= 30
  3910.4  390.82  4048.4  393.53  4097.9  390.58  4104.4  386.87  4126.5  381.72
  4133.0  377.36  4161.7  372.30  4176.0  372.45  4182.5  376.50  4254.1  375.18
  4275.0  377.70  4367.4  377.70  4687.1  356.22  4758.0  349.99  4982.9  341.60
  4985.6  341.10  4988.9  341.60  5105.6  344.77  5127.8  346.94  5134.3  349.58
  5155.3  348.57  5205.9  352.45  5319.2  353.17  5347.8  350.03  5362.1  353.40
  5491.6  356.70  5570.3  360.46  5596.7  363.56  5817.5  371.28  5927.4  372.69
#Mann=3,-1,0
  3910.4    0.05       0  4982.9    0.03       0  4988.9    0.05       0
Bank Sta=4982.9,4988.9
Exp/Cntr=0.3,0.1

Type RM Length L Ch R = 1,5439,174,174,174
BEGIN DESCRIPTION:
RENA BRANCH 6.0
END DESCRIPTION:
XS GIS Cut Line= 3
      3605118.54     10521436.92      3604849.61     10520660.19
      3604090.78     10520159.13
#Sta/Elev= 30
  4025.5  386.76  4100.0  384.60  4180.8  375.84  4201.9  377.27  4281.7  375.52
  4375.1  371.17  4432.2  373.89  4437.4  372.56  4463.3  375.73  4468.6  372.38
  4477.1  372.18  4494.5  374.93  4499.8  372.60  4525.6  374.75  4530.9  371.16
  4556.8  371.77  4582.6  370.26  4587.9  367.95  4738.4  364.30  4831.9  359.14
  4988.3  342.54  4991.0  342.04  4994.3  342.54  5014.6  343.14  5035.6  346.98
  5041.6  344.44  5056.7  343.62  5159.0  345.58  5433.0  357.38  5756.8  356.79
#Mann=3,-1,0
  4025.5    0.05       0  4988.3    0.03       0  4994.3    0.05       0
Bank Sta=4988.3,4994.3
Exp/Cntr=0.3,0.1

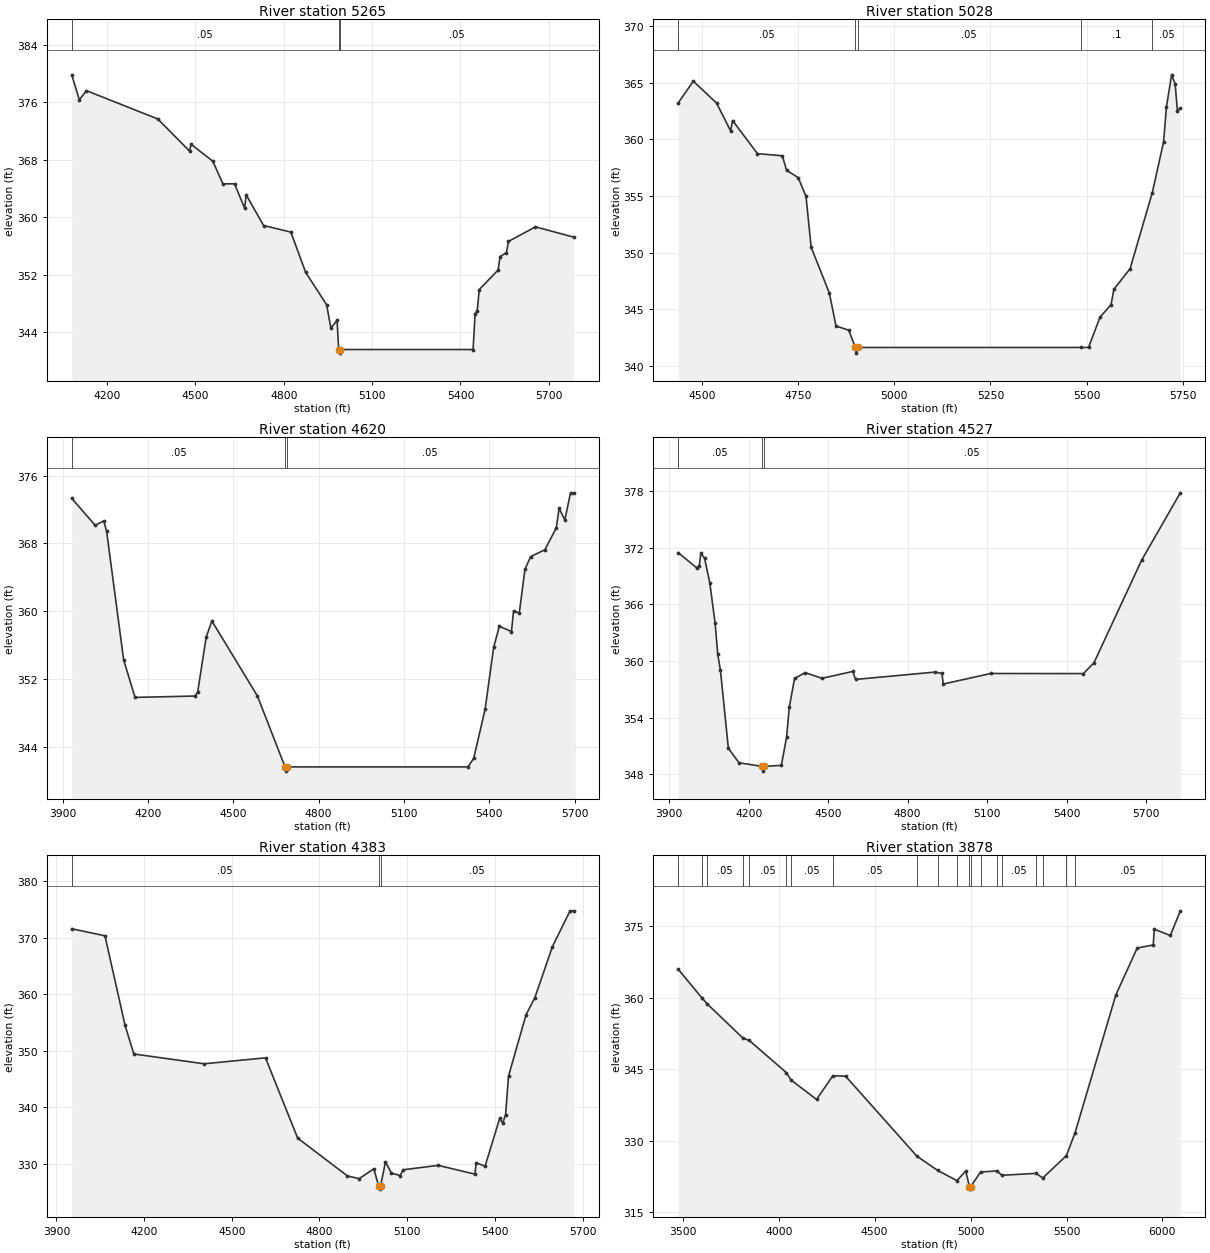
Type RM Length L Ch R = 1,5265,237,237,237
BEGIN DESCRIPTION:
Mapping XS dd230e81
END DESCRIPTION:
XS GIS Cut Line= 4
      3605171.99     10521328.15      3604981.01     10520638.04
      3604798.72     10520386.30      3604329.96     10519895.84
#Sta/Elev= 30
  4079.8  379.80  4105.5  376.32  4129.6  377.60  4371.7  373.67  4479.8  369.21
  4485.0  370.15  4558.8  367.80  4593.1  364.65  4632.6  364.66  4666.9  361.26
  4672.1  363.12  4731.4  358.86  4823.9  357.95  4874.2  352.35  4945.3  347.86
  4960.0  344.59  4980.9  345.70  4986.4  341.63  4989.2  341.13  4992.4  341.63
  5442.8  341.63  5449.8  346.58  5457.0  347.05  5463.9  349.97  5527.8  352.67
  5534.7  354.55  5556.1  355.09  5563.0  356.65  5654.8  358.68  5785.1  357.24
#Mann=3,-1,0
  4079.8    0.05       0  4986.4    0.03       0  4992.4    0.05       0
Bank Sta=4986.4,4992.4
Exp/Cntr=0.3,0.1

Type RM Length L Ch R = 1,5028,408,408,408
BEGIN DESCRIPTION:
RENA BRANCH 5.0
END DESCRIPTION:
XS GIS Cut Line= 3
      3605134.56     10520889.02      3605049.61     10520310.19
      3604649.63     10519710.22
#Sta/Elev= 30
  4437.9  363.23  4477.1  365.15  4537.8  363.21  4574.2  360.75  4579.3  361.67
  4644.0  358.75  4708.8  358.56  4719.7  357.28  4750.0  356.63  4770.3  354.97
  4783.7  350.48  4830.9  346.45  4848.4  343.52  4881.4  343.16  4898.6  341.63
  4901.4  341.13  4904.6  341.63  5485.3  341.63  5505.2  341.63  5535.2  344.31
  5563.8  345.41  5571.3  346.78  5613.3  348.58  5671.2  355.31  5700.5  359.79
  5708.0  362.91  5721.5  365.71  5730.5  364.92  5736.5  362.52  5744.0  362.74
#Mann=5,-1,0
  4437.9    0.05       0  4898.6    0.03       0  4904.6    0.05       0
  5485.3     0.1       0  5671.2    0.05       0
Bank Sta=4898.6,4904.6
Exp/Cntr=0.3,0.1

Type RM Length L Ch R = 1,4620,93,93,93
BEGIN DESCRIPTION:
Mapping XS 9efd5cbb
END DESCRIPTION:
XS GIS Cut Line= 2
      3605433.18     10521222.41      3605377.62     10519458.48
#Sta/Elev= 30
  3932.2  373.31  4014.5  370.14  4044.5  370.66  4054.5  369.47  4114.5  354.27
  4154.5  349.83  4364.6  349.99  4374.6  350.42  4404.7  356.95  4424.7  358.85
  4584.7  350.00  4681.8  341.63  4684.5  341.13  4687.8  341.63  5325.1  341.63
  5345.1  342.65  5385.1  348.43  5415.2  355.74  5435.2  358.23  5477.6  357.60
  5485.2  360.01  5505.2  359.80  5525.2  364.95  5545.2  366.45  5595.2  367.25
  5635.3  369.84  5645.3  372.14  5665.3  370.77  5685.3  373.97  5697.0  373.94
#Mann=3,-1,0
  3932.2    0.05       0  4681.8    0.03       0  4687.8    0.05       0
Bank Sta=4681.8,4687.8
Exp/Cntr=0.3,0.1

Type RM Length L Ch R = 1,4527,144,144,144
BEGIN DESCRIPTION:
RENA BRANCH 4.0
END DESCRIPTION:
XS GIS Cut Line= 2
      3605516.51     10521229.37      3605474.86     10519334.32
#Sta/Elev= 30
  3933.8  371.49  4003.0  369.89  4013.0  370.11  4019.2  371.41  4033.0  370.92
  4053.0  368.29  4073.0  364.01  4083.0  360.69  4093.0  359.04  4123.0  350.74
  4163.0  349.20  4250.1  348.81  4252.8  348.31  4256.1  348.81  4323.1  348.92
  4343.1  351.96  4353.1  355.11  4373.1  358.15  4413.1  358.76  4476.8  358.16
  4593.1  358.89  4603.1  358.04  4903.2  358.82  4929.4  358.68  4934.4  357.55
  5113.3  358.67  5463.3  358.66  5503.4  359.81  5683.4  370.70  5829.3  377.84
#Mann=3,-1,0
  3933.8    0.05       0  4250.1    0.03       0  4256.1    0.05       0
Bank Sta=4250.1,4256.1
Exp/Cntr=0.3,0.1

Type RM Length L Ch R = 1,4383,505,505,505
BEGIN DESCRIPTION:
RENA BRANCH 3.0
END DESCRIPTION:
XS GIS Cut Line= 3
      3605599.85     10521222.39      3605641.51     10520264.06
      3605592.90     10519507.15
#Sta/Elev= 30
  3952.6  371.56  4066.1  370.32  4135.0  354.47  4165.0  349.43  4405.2  347.70
  4615.4  348.75  4725.5  334.56  4895.7  327.88  4935.8  327.40  4985.9  329.13
  5002.9  326.05  5005.6  325.55  5008.9  326.05  5025.9  330.39  5046.0  328.39
  5076.0  327.95  5086.1  328.97  5206.3  329.75  5331.6  328.20  5336.6  330.21
  5366.6  329.59  5416.7  338.08  5426.8  337.21  5436.8  338.70  5446.8  345.53
  5506.9  356.38  5537.0  359.39  5597.1  368.41  5657.2  374.72  5670.3  374.73
#Mann=3,-1,0
  3952.6    0.05       0  5002.9    0.03       0  5008.9    0.05       0
Bank Sta=5002.9,5008.9
Exp/Cntr=0.3,0.1

Type RM Length L Ch R = 1,3878,71,71,71
BEGIN DESCRIPTION:
Mapping XS 0a602a78
END DESCRIPTION:
XS GIS Cut Line= 4
      3606683.18     10521625.18      3606176.45     10520463.64
      3605947.07     10520000.17      3605572.07     10519257.13
#Sta/Elev= 30
  3476.2  366.01  3601.5  359.91  3628.6  358.70  3812.7  351.58  3846.4  351.06
  4039.6  344.32  4064.2  342.75  4197.1  338.69  4282.0  343.65  4348.5  343.56
  4720.3  326.75  4828.6  323.76  4928.9  321.62  4974.6  323.64  4994.0  320.34
  4996.7  319.84  5000.0  320.34  5051.9  323.43  5135.5  323.66  5163.5  322.75
  5340.9  323.15  5376.2  322.18  5499.4  326.89  5544.5  331.69  5756.7  360.61
  5868.2  370.48  5951.8  371.12  5957.4  374.43  6041.0  373.11  6092.9  378.29
#Mann=20,-1,0
  3476.2    0.05       0  3601.5    0.16       0  3628.6    0.05       0
  3812.7    0.16       0  3846.4    0.05       0  4039.6    0.16       0
  4064.2    0.05       0  4282.0    0.05       0  4720.3    0.07       0
  4828.6    0.08       0  4928.9    0.12       0  4994.0    0.07       0
  5000.0    0.12       0  5051.9     0.1       0  5135.5    0.12       0
  5163.5    0.05       0  5340.9    0.12       0  5376.2    0.05       0
  5499.4     0.1       0  5544.5    0.05       0
Bank Sta=4994,5000
Exp/Cntr=0.3,0.1

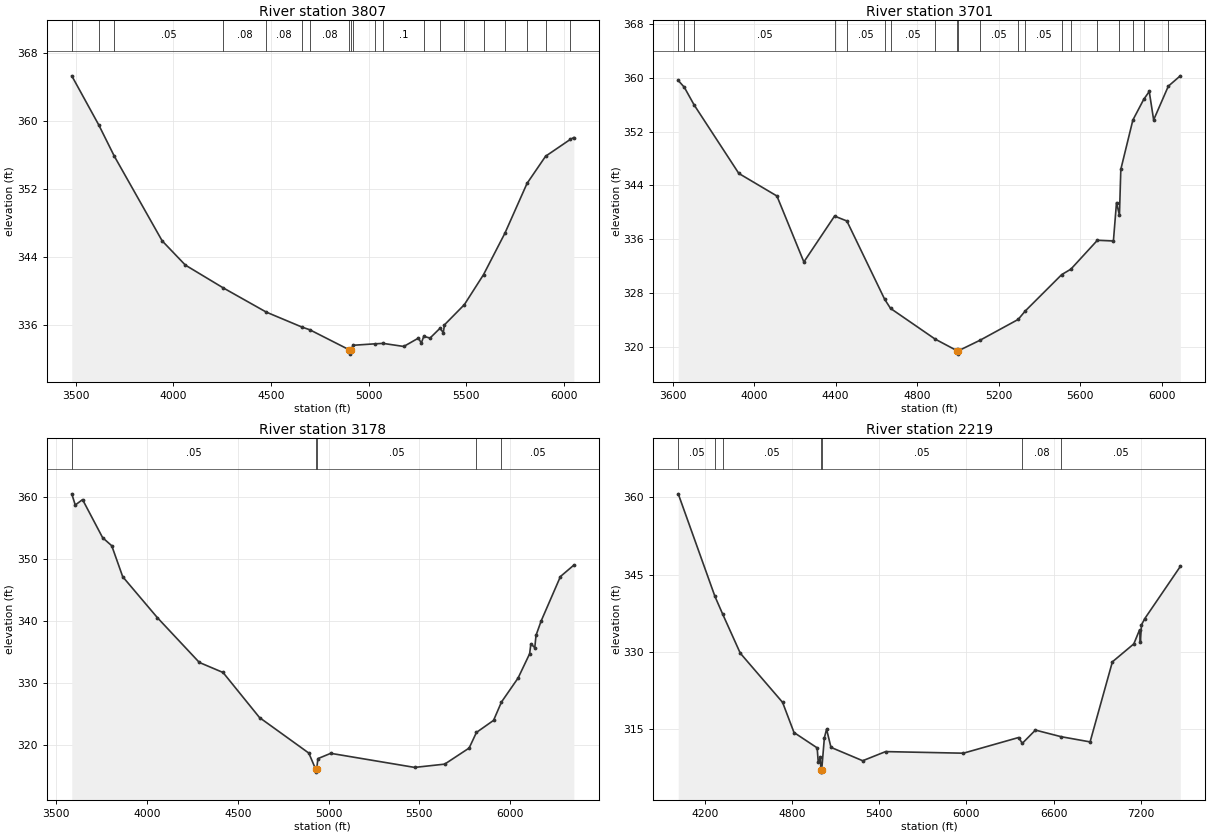
Type RM Length L Ch R = 1,3807,106,106,106
BEGIN DESCRIPTION:
RENA BRANCH 2.0
END DESCRIPTION:
XS GIS Cut Line= 2
      3606801.59     10521586.31      3605669.99     10519274.50
#Sta/Elev= 30
  3478.8  365.28  3617.3  359.51  3696.6  355.86  3942.1  345.91  4061.2  343.06
  4253.5  340.41  4476.2  337.54  4658.5  335.79  4699.0  335.47  4902.0  333.11
  4904.8  332.61  4908.0  333.11  4921.7  333.65  5033.1  333.82  5074.9  333.87
  5180.7  333.51  5255.9  334.49  5270.7  333.91  5283.2  334.69  5315.7  334.50
  5367.2  335.66  5383.2  335.12  5389.5  336.05  5491.4  338.42  5589.9  341.95
  5699.6  346.82  5812.7  352.65  5907.8  355.84  6035.4  357.83  6052.7  358.04
#Mann=20,-1,0
  3478.8    0.05       0  3617.3    0.08       0  3696.6    0.05       0
  4253.5    0.08       0  4476.2    0.08       0  4658.5    0.05       0
  4699.0    0.08       0  4902.0    0.07       0  4908.0    0.08       0
  4921.7     0.1       0  5033.1    0.08       0  5074.9     0.1       0
  5283.2    0.05       0  5367.2    0.08       0  5491.4     0.1       0
  5589.9    0.08       0  5699.6    0.05       0  5812.7    0.08       0
  5907.8    0.05       0  6035.4    0.08       0
Bank Sta=4902,4908
Exp/Cntr=0.3,0.1

Type RM Length L Ch R = 1,3701,523,523,523
BEGIN DESCRIPTION:
Mapping XS 4ccc3a17
END DESCRIPTION:
XS GIS Cut Line= 4
      3606752.61     10521463.68      3606344.64     10520426.39
      3606014.78     10519727.60      3605706.63     10519241.51
#Sta/Elev= 30
  3628.0  359.63  3657.8  358.62  3705.7  356.00  3925.2  345.79  4112.1  342.43
  4244.3  332.61  4394.8  339.44  4455.2  338.71  4640.5  327.06  4669.4  325.70
  4888.1  321.13  4996.3  319.39  4999.1  318.89  5002.3  319.39  5109.2  320.97
  5295.3  324.05  5330.2  325.31  5509.2  330.73  5554.1  331.54  5684.2  335.84
  5762.7  335.73  5777.9  341.45  5792.3  339.58  5799.1  346.40  5858.2  353.74
  5911.5  356.82  5938.5  357.99  5960.1  353.76  6032.1  358.78  6090.9  360.32
#Mann=20,-1,0
  3628.0    0.05       0  3657.8    0.08       0  3705.7    0.05       0
  4394.8    0.08       0  4455.2    0.05       0  4640.5    0.08       0
  4669.4    0.05       0  4888.1    0.05       0  4996.3    0.03       0
  5002.3    0.05       0  5109.2    0.05       0  5295.3    0.08       0
  5330.2    0.05       0  5509.2    0.08       0  5554.1    0.05       0
  5684.2    0.08       0  5792.3    0.05       0  5858.2    0.08       0
  5911.5    0.05       0  6032.1    0.08       0
Bank Sta=4996.3,5002.3
Exp/Cntr=0.3,0.1

Type RM Length L Ch R = 1,3178,959,959,959
BEGIN DESCRIPTION:
Mapping XS da56117b
END DESCRIPTION:
XS GIS Cut Line= 3
      3606773.46     10521479.35      3606585.96     10519486.28
      3606072.04     10518923.76
#Sta/Elev= 30
  3586.5  360.48  3605.7  358.68  3645.9  359.55  3756.4  353.41  3806.6  352.11
  3866.9  347.12  4057.7  340.52  4288.7  333.30  4419.3  331.68  4620.2  324.41
  4891.4  318.69  4928.6  316.12  4931.3  315.62  4934.6  316.12  4941.6  317.80
  5011.9  318.65  5474.0  316.38  5639.4  316.91  5773.9  319.50  5814.1  322.02
  5908.3  323.96  5951.9  326.92  6043.4  330.79  6106.9  334.70  6113.7  336.29
  6135.3  335.69  6142.1  337.67  6170.4  339.99  6276.5  347.15  6350.3  348.99
#Mann=5,-1,0
  3586.5    0.05       0  4928.6    0.03       0  4934.6    0.05       0
  5814.1     0.1       0  5951.9    0.05       0
Bank Sta=4928.6,4934.6
Exp/Cntr=0.3,0.1

Type RM Length L Ch R = 1,2219,0,0,0
BEGIN DESCRIPTION:
RENA BRANCH 1.0
END DESCRIPTION:
XS GIS Cut Line= 4
      3606815.10     10521465.49      3607467.90     10520444.62
      3607079.01     10519250.17      3606188.33     10518826.54
#Sta/Elev= 30
  4017.0  360.66  4269.6  340.77  4322.6  337.35  4443.8  329.77  4734.8  320.24
  4813.5  314.39  4972.9  311.41  4980.1  308.64  4995.3  309.57  4998.2  307.21
  5001.0  306.71  5004.2  307.21  5022.4  313.37  5037.6  315.03  5067.8  311.51
  5286.0  308.92  5443.7  310.69  5978.6  310.38  6358.7  313.42  6384.0  312.29
  6474.4  314.86  6651.0  313.58  6850.5  312.57  7003.9  328.09  7151.3  331.57
  7191.2  334.31  7196.7  331.98  7204.0  335.25  7226.2  336.45  7471.2  346.58
#Mann=7,-1,0
  4017.0    0.05       0  4269.6    0.16       0  4322.6    0.05       0
  4998.2    0.03       0  5004.2    0.05       0  6384.0    0.08       0
  6651.0    0.05       0
Bank Sta=4998.2,5004.2
Exp/Cntr=0.3,0.1

Chan Stop Cuts=-1