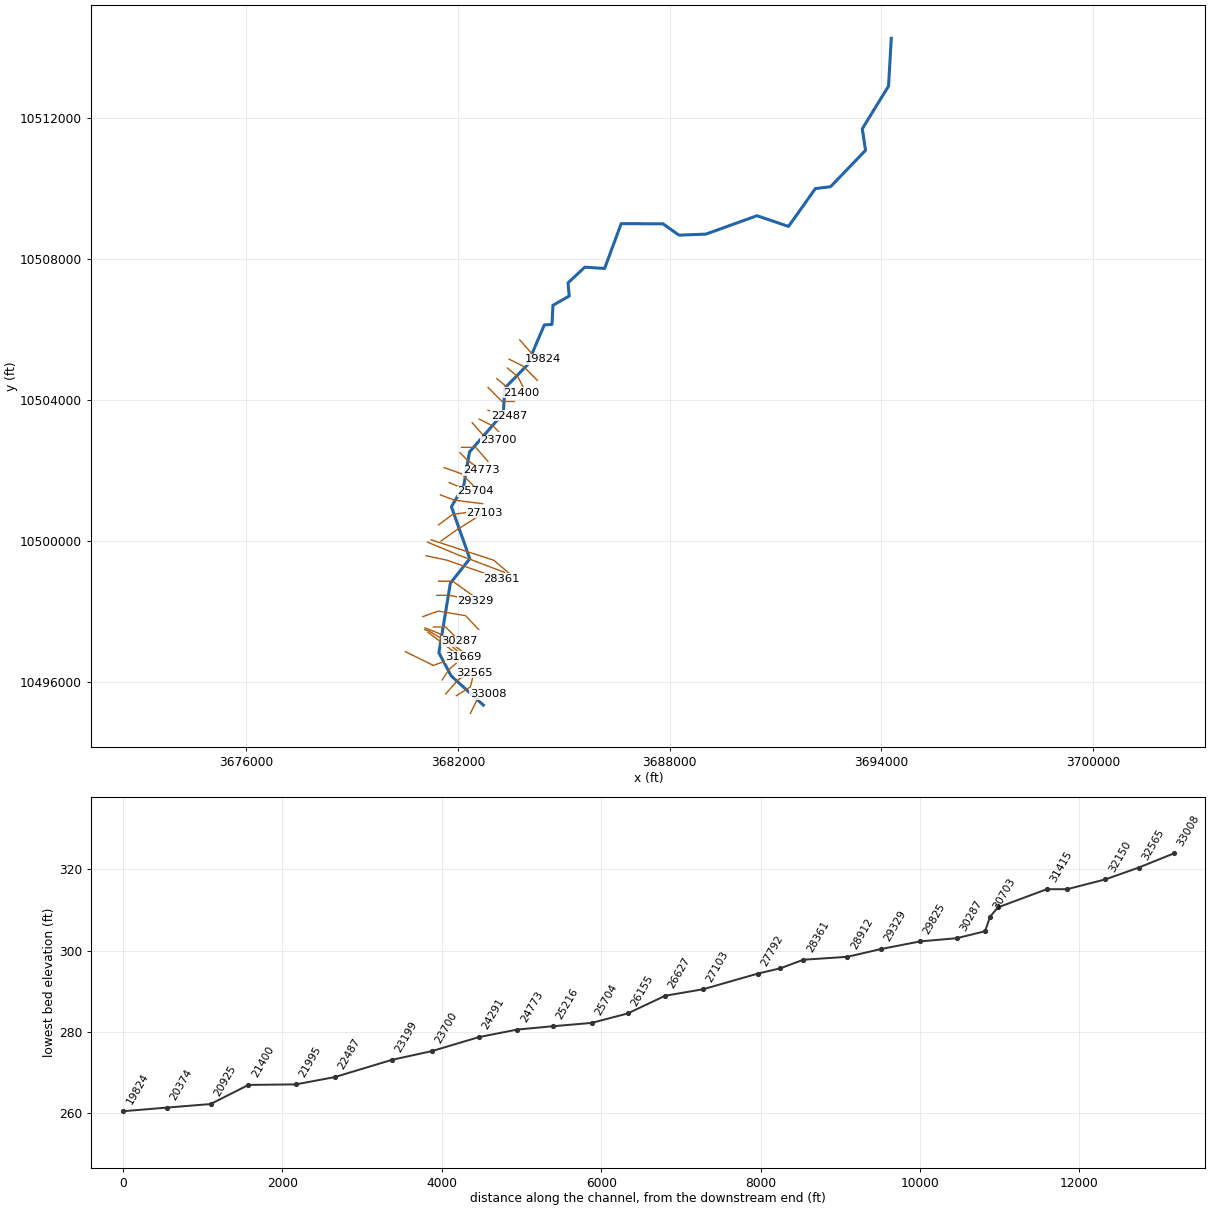
--- RESACA CREEK.prj (project) ---

Proj Title=RESACA CREEK Base Level Engineering
Current Plan=p01
Default Exp/Contr=0.3,0.1
English Units
Geom File=g01
Flow File=f01
Plan File=p01
Y Axis Title=Elevation
X Axis Title(PF)=Main Channel Distance
X Axis Title(XS)=Station
BEGIN DESCRIPTION:
RESACA CREEK
END DESCRIPTION:
DSS Export Rating Curves= 0
DSS Export Rating Curve Sorted= 0
DSS Export Volume Flow Curves= 0
DXF OffsetX= 0
DXF OffsetY= 0
DXF ScaleX= 1
DXF ScaleY= 10

--- RESACA CREEK.p01 (plan) ---

Plan Title=Multiple Run
Short Identifier=Multiple
Geom File=g01
Flow File=f01
Subcritical Flow
K Sum by GR= 0
Std Step Tol= 0.01
Critical Tol= 0.01
Num of Std Step Trials= 20
Max Error Tol= 0.3
Flow Tol Ratio= 0.001
Split Flow NTrial= 30
Split Flow Tol= 0.02
Split Flow Ratio= 0.02
Log Output Level= 0
Friction Slope Method= 1
Unsteady Friction Slope Method= 2
Unsteady Bridges Friction Slope Method= 1
Parabolic Critical Depth
Global Vel Dist=  1 , 1 , 1
Global Log Level= 0
CheckData=True
Encroach Param= -1, 0, 0, 0
BEGIN DESCRIPTION:
Multiple Run
END DESCRIPTION:

--- RESACA CREEK.f01 (steady flow) ---

Flow Title=Multiple
Program Version=4.10
Number of Profiles= 7
Profile Names=10-year,25-year,50-year,1pct_min,100-year,1pct_plu,500-year
River Rch & RM=RESACA CREEK,Reach-1         ,33008
     731    1023    1273    1165    1575    2131    2424
River Rch & RM=RESACA CREEK,Reach-1         ,32150
    1125    1605    2022    1871    2530    3422    3981
River Rch & RM=RESACA CREEK,Reach-1         ,28361
    1374    1967    2484    2301    3112    4208    4906
River Rch & RM=RESACA CREEK,Reach-1         ,20374
    1515    2172    2744    2541    3437    4648    5420
River Rch & RM=RESACA CREEK,Reach-1         ,13812
    1607    2303    2908    2690    3638    4920    5725
River Rch & RM=RESACA CREEK,Reach-1         ,7699
    2391    3483    4448    4156    5621    7602    9025
River Rch & RM=RESACA CREEK,Reach-1         ,7362
    2391    3483    4448    4156    5621    7602    9025
River Rch & RM=RESACA CREEK,Reach-1         ,4256
    2512    3660    4672    4364    5902    7981    9467
Boundary for River Rch & Prof#=RESACA CREEK,Reach-1         , 1
Up Type= 0
Dn Type= 3
Dn Slope=0.003
Boundary for River Rch & Prof#=RESACA CREEK,Reach-1         , 2
Up Type= 0
Dn Type= 3
Dn Slope=0.003
Boundary for River Rch & Prof#=RESACA CREEK,Reach-1         , 3
Up Type= 0
Dn Type= 3
Dn Slope=0.003
Boundary for River Rch & Prof#=RESACA CREEK,Reach-1         , 4
Up Type= 0
Dn Type= 3
Dn Slope=0.003
Boundary for River Rch & Prof#=RESACA CREEK,Reach-1         , 5
Up Type= 0
Dn Type= 3
Dn Slope=0.003
Boundary for River Rch & Prof#=RESACA CREEK,Reach-1         , 6
Up Type= 0
Dn Type= 3
Dn Slope=0.003
Boundary for River Rch & Prof#=RESACA CREEK,Reach-1         , 7
Up Type= 0
Dn Type= 3
Dn Slope=0.003
DSS Import GetInterval= 0
DSS Import GetPeak= 0
DSS Import FillOption= 0

--- RESACA CREEK.g01 (geometry) ---

Geom Title=Existing Conditions
Program Version=4.10

River Reach=RESACA CREEK    ,Reach-1
Reach XY= 30
      3682717.65     10495344.21      3681804.75       10496175.
      3681456.75       10496832.        3681782.       10498804.
        3682333.       10499500.       3681812.5       10500975.
        3682163.       10501573.      3682324.75       10502528.
       3683285.5       10503632.        3683325.       10504339.
      3683961.75       10504993.      3684446.75       10506134.
      3684663.75       10506147.       3684691.5       10506690.
      3685152.75       10506954.      3685118.75       10507327.
       3685593.5       10507772.      3686156.25       10507736.
      3686625.75       10509008.      3687812.75       10509002.
       3688264.5       10508681.      3689026.25       10508710.
        3690477.       10509232.      3691371.25       10508929.
      3692132.25       10510001.       3692564.5       10510057.
      3693554.75       10511088.        3693463.       10511699.
        3694207.       10512911.        3694285.       10514266.

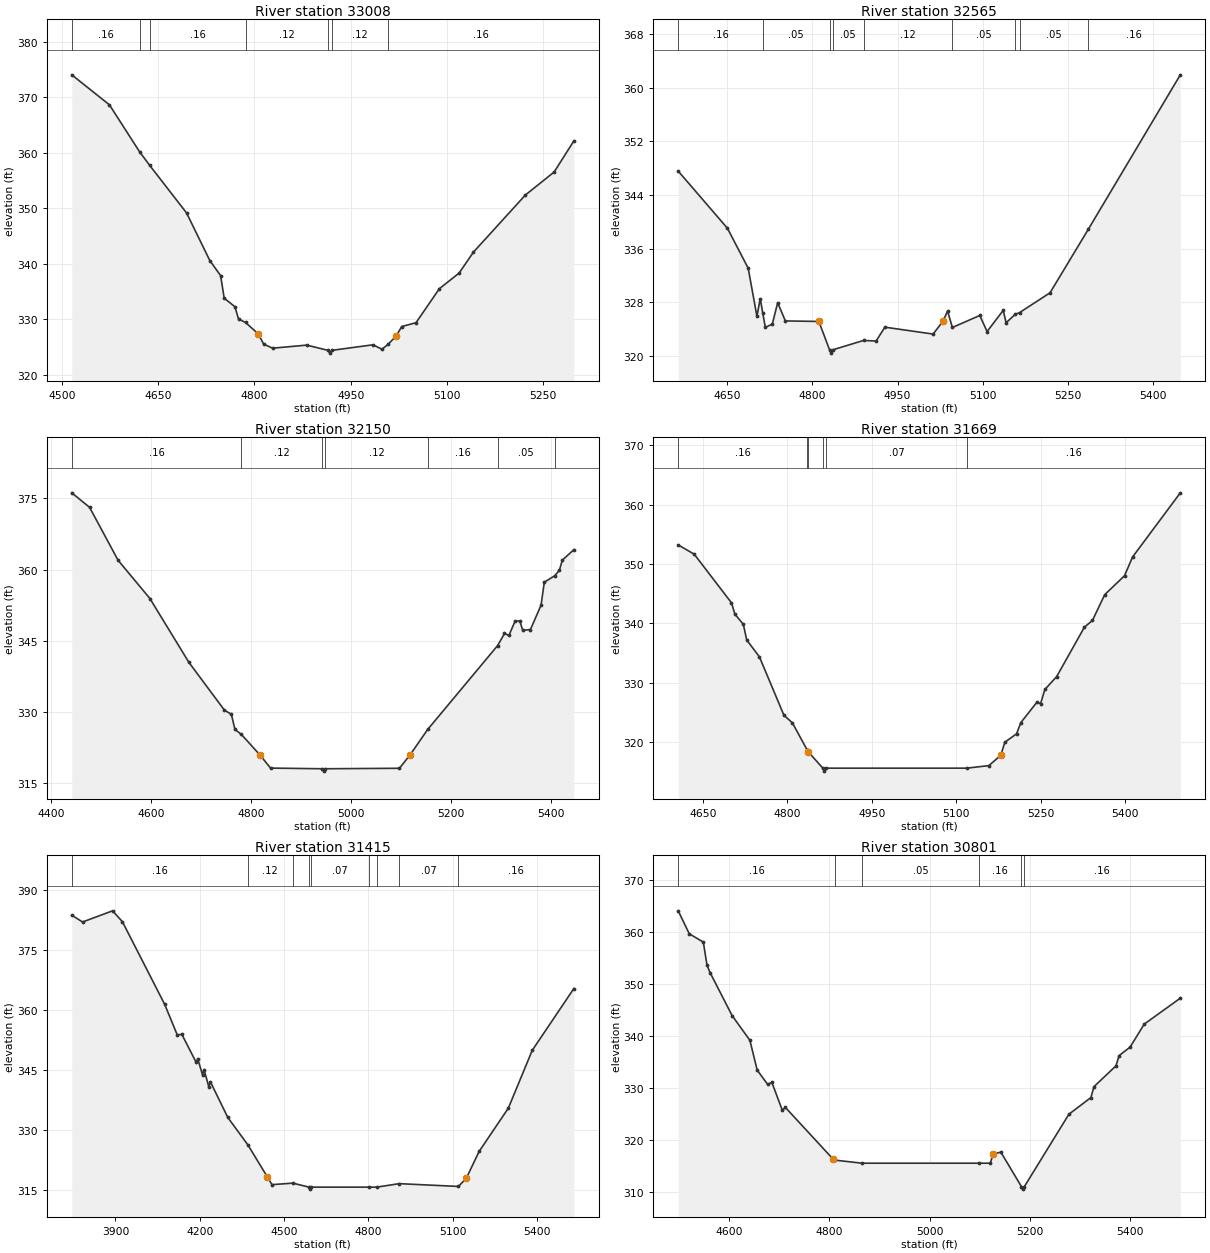
Type RM Length L Ch R = 1 ,33008   ,443,443,443
BEGIN DESCRIPTION:
RESACA CREEK 63.0
END DESCRIPTION:
XS GIS Cut Line= 3
      3682349.62     10495110.21      3682549.61     10495510.19
       3682849.6     10495660.19
#Sta/Elev= 30
  4515.2  374.02  4573.9  368.62  4620.9  360.17  4636.4  357.76  4694.1  349.17
  4730.4  340.59  4747.2  337.88  4752.8  333.82  4769.5  332.28  4775.1  330.08
    4786  329.45  4805.9  327.39  4814.3  325.56  4828.2  324.82  4881.3  325.37
  4914.7  324.43  4917.4  323.93  4920.7  324.43  4984.8  325.43  4998.7  324.63
  5008.1   325.5  5021.1  327.05  5029.5  328.71  5051.8  329.41  5088.2  335.53
  5118.9  338.33  5141.3  342.11  5222.3  352.39  5267.1  356.53  5297.8  362.12
#Mann= 7 ,-1 , 0
  4515.2     .16       0  4620.9     .12       0  4636.4     .16       0
    4786     .12       0  4914.7     .07       0  4920.7     .12       0
  5008.1     .16       0
Bank Sta=4805.9,5021.1
XS Rating Curve= 0 ,0
Exp/Cntr=0.3,0.1

Type RM Length L Ch R = 1 ,32565   ,415,415,415
BEGIN DESCRIPTION:
RESACA CREEK 62.0
END DESCRIPTION:
XS GIS Cut Line= 3
      3681949.64     10495610.21      3682349.61     10495860.19
      3682449.62     10496260.22
#Sta/Elev= 30
  4563.8  347.55  4650.4  339.04    4687  333.08  4702.3  325.93  4708.2  328.54
  4712.5  326.48  4717.1  324.27  4729.4  324.75  4738.9  327.94  4752.4  325.23
  4811.4  325.15  4830.2  320.93    4833  320.43  4836.2  320.93  4890.1  322.32
  4912.2  322.23  4927.6   324.3  5012.5  323.27    5030  325.19    5038  326.71
  5046.5  324.25  5094.7  326.04  5107.6  323.65    5136   326.8  5141.1  324.95
  5157.2  326.22  5164.8  326.47  5218.4  329.42  5285.8  338.88  5447.8   361.9
#Mann= 9 ,-1 , 0
  4563.8     .16       0  4712.5     .05       0  4830.2     .07       0
  4836.2     .05       0  4890.1     .12       0  5046.5     .05       0
  5157.2     .16       0  5164.8     .05       0  5285.8     .16       0
Bank Sta=4811.4,5030
XS Rating Curve= 0 ,0
Exp/Cntr=0.3,0.1

Type RM Length L Ch R = 1 ,32150   ,481,481,481
BEGIN DESCRIPTION:
RESACA CREEK 61.0
END DESCRIPTION:
XS GIS Cut Line= 3
      3681649.62      10495660.2      3681999.61     10496060.19
      3682399.61     10496310.19
#Sta/Elev= 30
  4441.6  376.16  4477.2   373.1  4534.1  361.96  4597.7   353.9  4675.5  340.47
  4746.7  330.37  4760.5  329.52  4767.6  326.33  4780.4  325.28    4817  321.02
  4838.8  318.18  4942.1  318.04  4944.8  317.54  4948.1  318.04  5096.3  318.14
  5117.6  320.96  5152.7  326.31  5292.6     344  5306.2  346.53  5315.1  346.12
  5327.5  349.16  5336.9  349.14  5342.8  347.17  5358.1  347.37  5379.3   352.5
  5385.8  357.34  5406.4  358.68  5415.9  359.84  5421.8  361.98  5444.8  364.19
#Mann= 7 ,-1 , 0
  4441.6     .16       0  4780.4     .12       0  4942.1     .07       0
  4948.1     .12       0  5152.7     .16       0  5292.6     .05       0
  5406.4     .16       0
Bank Sta=4817,5117.6
XS Rating Curve= 0 ,0
Exp/Cntr=0.3,0.1

Type RM Length L Ch R = 1 ,31669   ,254,254,254
BEGIN DESCRIPTION:
RESACA CREEK 60.0
END DESCRIPTION:
XS GIS Cut Line= 3
      3681549.62     10496060.21      3681749.61     10496360.19
      3682149.58     10496710.16
#Sta/Elev= 30
  4606.1  353.24  4634.6  351.67  4700.7  343.48  4706.7  341.59  4721.8  339.85
  4727.8  337.21  4750.3  334.39  4793.9  324.53  4808.9  323.26  4835.6  318.61
  4836.9   318.4    4863  315.62  4865.7  315.12    4869  315.62  5118.7  315.62
  5157.9  316.05  5179.2  317.79  5186.3  319.99  5207.2  321.41  5214.8   323.3
  5243.3  326.73  5249.9  326.51  5257.5  328.88  5278.4  331.05  5327.8  339.39
    5342  340.51  5363.8  344.86    5399  348.05  5413.2   351.2  5498.1  362.02
#Mann= 6 ,-1 , 0
  4606.1     .16       0  4835.6     .12       0  4836.9     .07       0
    4863     .07       0    4869     .07       0  5118.7     .16       0
Bank Sta=4836.9,5179.2
XS Rating Curve= 0 ,0
Exp/Cntr=0.3,0.1

Type RM Length L Ch R = 1 ,31415   ,614,614,614
BEGIN DESCRIPTION:
RESACA CREEK 59.0
END DESCRIPTION:
XS GIS Cut Line= 3
      3680507.89       10496861.      3681302.14     10496470.39
      3682148.49     10496782.89
#Sta/Elev= 30
  3744.6  383.71    3783     382  3889.8   384.8  3924.8  382.08  4075.1  361.42
  4120.1  353.74  4136.6  353.85  4187.5  346.85  4193.1  347.73    4210  343.75
  4215.5  345.06  4232.4  340.73    4238  342.01  4299.9  333.08  4371.5   326.2
  4440.3  318.24  4457.2  316.24  4531.5  316.62    4589  315.62  4591.8  315.12
    4595  315.62  4801.7  315.62  4830.3  315.62  4910.3  316.49  5121.2  315.79
  5149.3  317.88  5194.7  324.56  5298.6  335.38  5383.9  349.88  5531.9  365.34
#Mann= 9 ,-1 , 0
  3744.6     .16       0  4371.5     .12       0  4531.5     .07       0
    4589     .07       0    4595     .07       0  4801.7     .16       0
  4830.3     .05       0  4910.3     .07       0  5121.2     .16       0
Bank Sta=4440.3,5149.3
XS Rating Curve= 0 ,0
Exp/Cntr=0.3,0.1

Type RM Length L Ch R = 1 ,30801   ,98,98,98
BEGIN DESCRIPTION:
RESACA CREEK 58.0
END DESCRIPTION:
XS GIS Cut Line= 3
      3681149.61     10497410.19      3681549.61     10497110.19
      3681949.61     10496810.19
#Sta/Elev= 30
  4499.4  364.08  4521.3  359.68  4549.4  358.07  4556.7  353.63  4562.9   352.2
  4606.7  343.96  4642.1  339.22  4656.7  333.48  4677.5  330.76  4685.9  331.12
  4706.7  325.78  4712.9  326.32  4806.7  316.52  4811.1  316.21  4865.4  315.62
  5098.2  315.62  5121.3  315.62 5126.14  317.43  5142.1  317.72  5182.9  311.14
  5185.6  310.64  5188.9  311.14  5277.5  325.02  5321.3  328.22  5327.5  330.32
  5371.3  334.32  5377.5  336.28  5399.4  337.91  5427.5  342.32  5499.4  347.31
#Mann= 6 ,-1 , 0
  4499.4     .16       0  4811.1     .12       0  4865.4     .05       0
  5098.2     .16       0  5182.9    .033       0  5188.9     .16       0
Bank Sta=4806.7,5126.14
XS Rating Curve= 0 ,0
Exp/Cntr=0.3,0.1

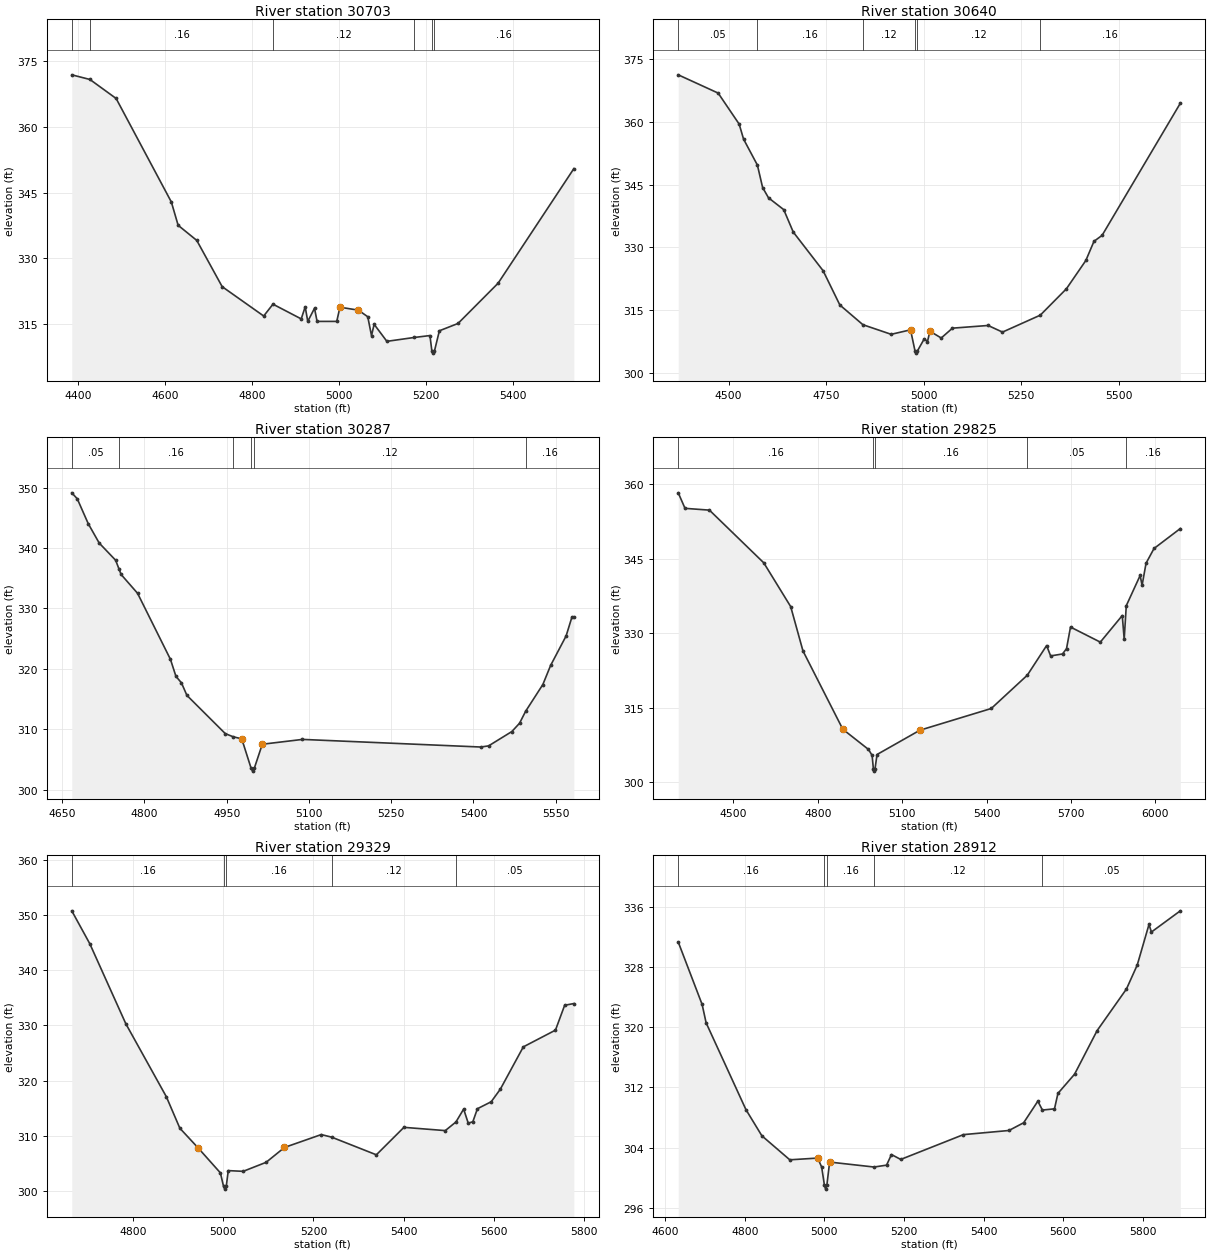
Type RM Length L Ch R = 1 ,30703   ,63,63,63
BEGIN DESCRIPTION:
Mapping XS 6f3b69fe
END DESCRIPTION:
XS GIS Cut Line= 5
      3681055.75     10497487.16      3681177.25     10497445.94
      3681613.44     10497185.52      3681672.04     10497146.46
      3682009.56     10496854.37
#Sta/Elev= 30
  4385.8  371.89  4427.5  370.83  4487.7  366.49  4614.5  342.87  4630.1  337.55
  4672.9   334.1  4731.2  323.55  4826.6  316.85  4847.9  319.55  4912.8  316.19
  4921.9  318.95  4927.8  315.62  4943.3  318.62  4949.2  315.62  4994.4  315.62
  5001.7  318.86  5044.2  318.18  5065.6  316.68  5074.2  312.36  5080.2  314.96
  5109.5  311.07  5172.9  311.96  5208.4  312.39  5212.8  308.88  5215.6  308.38
  5218.8  308.88  5230.1  313.48  5272.9  315.15    5365  324.34  5538.9  350.48
#Mann= 6 ,-1 , 0
  4385.8     .05       0  4427.5     .16       0  4847.9     .12       0
  5172.9     .16       0  5212.8     .07       0  5218.8     .16       0
Bank Sta=5001.7,5044.2
XS Rating Curve= 0 ,0
Exp/Cntr=0.3,0.1

Type RM Length L Ch R = 1 ,30640   ,353,353,353
BEGIN DESCRIPTION:
Mapping XS 535422a1
END DESCRIPTION:
XS GIS Cut Line= 4
      3681064.44      10497534.9      3681465.87     10497376.49
      3681852.16      10497070.5      3682138.64     10496849.13
#Sta/Elev= 30
  4371.1  371.21  4473.4  366.85  4527.2  359.45  4538.5  355.86  4573.9  349.67
  4587.3  344.31  4602.4  341.85  4641.4  339.03  4665.8  333.68  4742.2  324.46
  4785.2  316.27  4844.3  311.56  4916.7  309.27  4966.3  310.34  4977.8  305.28
  4980.5  304.78  4983.8  305.28  5001.6  308.22  5009.6  307.51    5016  310.01
  5044.9  308.39  5073.7  310.74    5165  311.38  5201.9   309.8  5298.7  313.84
  5365.6  320.13  5415.5   326.9  5436.3  331.47  5457.1  332.89  5657.5  364.42
#Mann= 6 ,-1 , 0
  4371.1     .05       0  4573.9     .16       0  4844.3     .12       0
  4977.8     .07       0  4983.8     .12       0  5298.7     .16       0
Bank Sta=4966.3,5016
XS Rating Curve= 0 ,0
Exp/Cntr=0.3,0.1

Type RM Length L Ch R = 1 ,30287   ,462,462,462
BEGIN DESCRIPTION:
RESACA CREEK 57.0
END DESCRIPTION:
XS GIS Cut Line= 3
      3681299.56     10497560.19      3681649.61     10497560.19
      3682049.59     10497160.21
#Sta/Elev= 30
  4667.4  349.13  4677.4  348.15  4697.4  344.03  4717.4  340.82  4747.4  337.97
  4753.3  336.58  4757.4  335.61  4787.4   332.5  4847.4  321.56  4857.4  318.75
  4867.4  317.68  4877.4   315.6  4947.4  309.27    4962  308.74  4977.4  308.41
  4994.4  303.56  4997.2  303.06  5000.4  303.56  5014.9  307.51  5088.2  308.31
  5413.4  307.05  5427.6  307.24    5470  309.61  5484.1  310.99  5495.1  312.96
  5526.6   317.4  5540.7  320.55    5569  325.44  5579.6  328.56  5583.1  328.56
#Mann= 6 ,-1 , 0
  4667.4     .05       0  4753.3     .16       0    4962     .12       0
  4994.4     .07       0  5000.4     .12       0  5495.1     .16       0
Bank Sta=4977.4,5014.9
XS Rating Curve= 0 ,0
Exp/Cntr=0.3,0.1

Type RM Length L Ch R = 1 ,29825   ,496,496,496
BEGIN DESCRIPTION:
RESACA CREEK 56.0
END DESCRIPTION:
XS GIS Cut Line= 4
      3681003.46     10497856.46      3681437.48      10498012.7
      3682210.05      10497882.5      3682583.28     10497491.91
#Sta/Elev= 30
    4304  358.21  4328.1  355.09  4414.9  354.73  4608.1  344.14  4703.8  335.34
  4747.4  326.44  4889.1  310.69  4980.4  306.63  4993.3  305.43  4997.7  302.77
  5000.4  302.27  5003.7  302.77  5010.8  305.61    5163  310.49  5416.9  314.86
    5545  321.55  5613.7  327.51  5627.9  325.43  5670.3  325.82  5684.5   326.9
  5698.6  331.23  5804.6   328.2  5882.6  333.54  5889.5   328.8  5896.9  335.52
  5946.2   341.6  5953.1  339.62  5967.2  344.06  5995.5  347.02    6089  351.03
#Mann= 5 ,-1 , 0
    4304     .16       0  4997.7     .07       0  5003.7     .16       0
    5545     .05       0  5896.9     .16       0
Bank Sta=4889.1,5163
XS Rating Curve= 0 ,0
Exp/Cntr=0.3,0.1

Type RM Length L Ch R = 1 ,29329   ,417,417,417
BEGIN DESCRIPTION:
RESACA CREEK 55.0
END DESCRIPTION:
XS GIS Cut Line= 3
      3681399.65     10498460.19      3681749.61     10498460.19
      3682499.59     10498310.19
#Sta/Elev= 30
  4663.4  350.73  4703.4  344.78  4783.4   330.3  4873.4  317.09  4903.4  311.39
  4943.4  307.88  4993.4  303.31  5000.4  300.87  5003.1  300.37  5006.4  300.87
  5010.9  303.72    5044  303.59  5094.9  305.22  5135.7  307.91  5217.3  310.24
  5240.3  309.78  5339.7  306.58  5400.9  311.55  5492.7  310.96  5516.4  312.52
  5533.5  314.85  5543.7  312.31  5553.9  312.56  5564.1  314.92  5594.7  316.18
    5615  318.46    5666  326.11  5737.4  329.14  5757.8  333.64  5778.2  333.95
#Mann= 5 ,-1 , 0
  4663.4     .16       0  5000.4     .07       0  5006.4     .16       0
  5240.3     .12       0  5516.4     .05       0
Bank Sta=4943.4,5135.7
XS Rating Curve= 0 ,0
Exp/Cntr=0.3,0.1

Type RM Length L Ch R = 1 ,28912   ,551,551,551
BEGIN DESCRIPTION:
RESACA CREEK 54.0
END DESCRIPTION:
XS GIS Cut Line= 3
       3681449.6     10498860.19      3681849.61     10498860.19
      3682549.57     10498360.22
#Sta/Elev= 30
  4633.2  331.34  4693.2  323.03  4703.2  320.59  4803.2  309.04  4843.2  305.56
  4913.2  302.37  4983.2   302.6  4993.2  301.41  5000.2  298.97    5003  298.47
  5006.2  298.97  5013.2  302.07  5124.7  301.41  5156.1  301.66  5168.4  303.07
  5191.7  302.42    5349  305.72  5463.3  306.27  5500.2   307.3  5535.8  310.17
  5547.3  308.99  5577.6  309.15  5586.2   311.2    5628  313.76  5684.5  319.55
  5758.3   325.1  5785.3  328.28  5814.8  333.68  5820.9  332.67  5893.4  335.49
#Mann= 5 ,-1 , 0
  4633.2     .16       0  5000.2     .07       0  5006.2     .16       0
  5124.7     .12       0  5547.3     .05       0
Bank Sta=4983.2,5013.2
XS Rating Curve= 0 ,0
Exp/Cntr=0.3,0.1

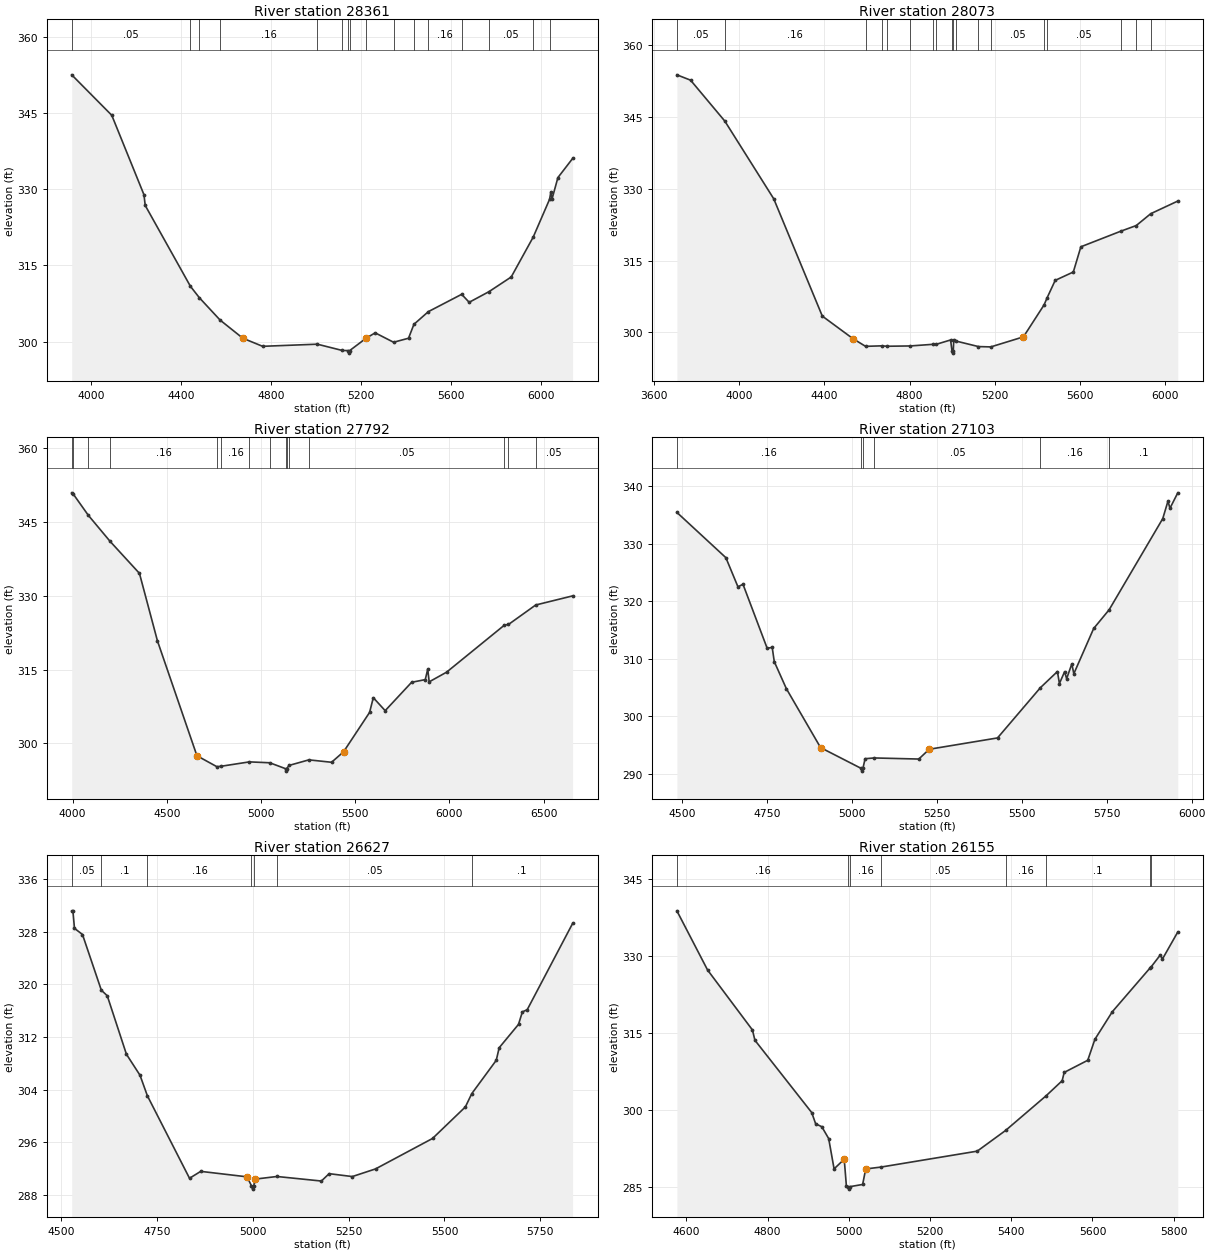
Type RM Length L Ch R = 1 ,28361   ,288,288,288
BEGIN DESCRIPTION:
RESACA CREEK 53.0
END DESCRIPTION:
XS GIS Cut Line= 4
      3681095.51     10499583.77      3681678.87     10499458.76
       3682338.6     10499229.59      3683218.86     10498924.62
#Sta/Elev= 30
  3914.4  352.51  4092.5  344.55  4235.6  328.92  4241.2  326.81  4442.2   310.9
  4482.2  308.64  4574.1  304.26  4675.1  300.69  4763.1   299.1  5006.1  299.52
  5117.5  298.28    5144  298.26  5146.7  297.76    5150  298.26  5223.6  300.71
  5263.4  301.75  5345.2   299.9  5411.6  300.69  5435.7  303.43  5499.7  305.92
  5647.8  309.33  5681.2  307.76  5769.2  309.85  5868.1  312.74    5966   320.6
  6038.7  328.03  6044.4  329.48  6049.7  328.11  6075.6  332.29    6141  336.05
#Mann= 16 ,-1 , 0
  3914.4     .05       0  4442.2     .16       0  4482.2     .08       0
  4574.1     .16       0  5006.1     .12       0  5117.5     .05       0
    5144     .07       0    5150     .05       0  5223.6     .08       0
  5345.2     .16       0  5435.7     .08       0  5499.7     .16       0
  5647.8     .08       0  5769.2     .05       0    5966     .08       0
  6038.7     .05       0
Bank Sta=4675.1,5223.6
XS Rating Curve= 0 ,0
Exp/Cntr=0.3,0.1

Type RM Length L Ch R = 1 ,28073   ,281,281,281
BEGIN DESCRIPTION:
RESACA CREEK 52.0
END DESCRIPTION:
XS GIS Cut Line= 4
      3681130.28     10499972.64       3682026.1     10499597.65
      3682442.76     10499444.87       3683316.2     10499112.13
#Sta/Elev= 30
  3708.6  353.83  3772.9  352.71  3933.6  344.15    4163  327.91  4390.8  303.39
    4534  298.69  4593.6  297.07  4668.5  297.17  4695.8  297.09  4802.7  297.15
  4909.5  297.49    4925  297.49  4992.4   298.4  4999.1  296.15  5001.8  295.65
  5005.1  296.15  5007.4  298.46  5016.3  298.19  5123.1  297.02    5181  296.95
  5334.2  299.05  5431.1  305.74  5445.2  307.21  5483.2  310.86  5568.2  312.61
  5603.6  317.88  5790.9  321.14  5863.4  322.32  5931.4   324.8  6058.2  327.44
#Mann= 18 ,-1 , 0
  3708.6     .05       0  3933.6     .16       0  4593.6     .05       0
  4668.5     .16       0  4695.8     .07       0  4802.7     .12       0
  4909.5     .05       0    4925     .12       0  4999.1     .07       0
  5005.1     .12       0  5016.3     .05       0  5123.1     .12       0
    5181     .05       0  5431.1      .1       0  5445.2     .05       0
  5790.9     .08       0  5863.4     .05       0  5931.4     .08       0
Bank Sta=4534,5334.2
XS Rating Curve= 0 ,0
Exp/Cntr=0.3,0.1

Type RM Length L Ch R = 1 ,27792   ,689,689,689
BEGIN DESCRIPTION:
RESACA CREEK 51.0
END DESCRIPTION:
XS GIS Cut Line= 3
      3681237.82     10500035.28      3683017.34     10499453.68
      3683615.45     10498942.25
#Sta/Elev= 30
    3995  350.93  4003.8  350.65  4083.2  346.36  4199.3  341.04  4354.6  334.56
  4450.2  320.83  4659.7  297.49  4765.7  295.26    4790  295.36  4938.1  296.24
  5046.2  296.06  5130.1  294.86  5132.8  294.36  5136.1  294.86  5148.8  295.52
  5254.1  296.65  5374.6  296.16  5438.2  298.29  5576.4   306.3    5596  309.29
  5659.1  306.65  5799.5  312.42  5871.9  312.96    5885  315.09  5892.7  312.51
  5984.9  314.47  6292.1  324.04  6313.7  324.17  6458.2  328.13  6654.1  329.98
#Mann= 15 ,-1 , 0
    3995     .05       0  4003.8     .16       0  4083.2     .05       0
  4199.3     .16       0  4765.7     .05       0    4790     .16       0
  4938.1     .12       0  5046.2     .05       0  5130.1     .07       0
  5136.1     .05       0  5148.8     .12       0  5254.1     .05       0
  6292.1     .12       0  6313.7     .08       0  6458.2     .05       0
Bank Sta=4659.7,5438.2
XS Rating Curve= 0 ,0
Exp/Cntr=0.3,0.1

Type RM Length L Ch R = 1 ,27103   ,476,476,476
BEGIN DESCRIPTION:
RESACA CREEK 50.0
END DESCRIPTION:
XS GIS Cut Line= 3
      3681517.85     10500000.86      3681949.61     10500310.19
      3682749.58     10500810.17
#Sta/Elev= 30
  4484.7  335.46  4628.9  327.59  4664.5  322.52  4679.3  322.97  4750.5  311.84
  4765.3     312  4771.4  309.52    4807  304.82  4907.7  294.58  5026.4  290.99
  5029.1  290.49  5032.4  290.99  5038.8  292.65  5065.9  292.78  5196.8  292.59
  5227.5  294.29  5428.6  296.26  5554.9     305  5604.9   307.8  5610.8  305.72
  5626.1  307.78    5632  306.56  5647.3  309.13  5653.2  307.42  5711.6  315.28
  5757.3  318.55    5915  334.38  5930.3  337.41  5936.2  336.18  5959.2  338.86
#Mann= 6 ,-1 , 0
  4484.7     .16       0  5026.4     .07       0  5032.4     .16       0
  5065.9     .05       0  5554.9     .16       0  5757.3      .1       0
Bank Sta=4907.7,5227.5
XS Rating Curve= 0 ,0
Exp/Cntr=0.3,0.1

Type RM Length L Ch R = 1 ,26627   ,472,472,472
BEGIN DESCRIPTION:
RESACA CREEK 49.0
END DESCRIPTION:
XS GIS Cut Line= 3
      3681449.64     10500460.21      3681849.61     10500760.19
      3682649.63     10500860.19
#Sta/Elev= 30
  4527.9  331.19    4531  331.19  4535.1  328.53    4556  327.59  4605.1  319.13
  4620.6  318.28  4670.6  309.39    4706   306.2  4725.2  303.08  4835.1  290.54
  4864.3  291.59  4985.1  290.76  4996.7  289.39  4999.5  288.89  5002.7  289.39
    5006  290.41  5063.1  290.81    5179  290.12  5199.2  291.24  5259.6   290.8
  5320.1  291.96  5468.8  296.59  5554.4  301.38  5571.2  303.41    5635  308.47
  5642.6  310.38    5693  313.93  5703.1  315.83  5715.7  316.16  5834.1  329.27
#Mann= 7 ,-1 , 0
  4527.9     .05       0  4605.1      .1       0  4725.2     .16       0
  4996.7     .07       0  5002.7     .16       0  5063.1     .05       0
  5571.2      .1       0
Bank Sta=4985.1,5006
XS Rating Curve= 0 ,0
Exp/Cntr=0.3,0.1

Type RM Length L Ch R = 1 ,26155   ,451,451,451
BEGIN DESCRIPTION:
RESACA CREEK 48.0
END DESCRIPTION:
XS GIS Cut Line= 3
      3681499.63     10501310.18      3681899.61     10501160.19
       3682699.6     10501060.19
#Sta/Elev= 30
  4576.6  338.82  4652.2  327.27  4762.6  315.58  4768.8  313.56  4908.6  299.46
  4918.3  297.27  4933.5  296.69  4950.4  294.38  4963.7  288.47  4988.7  290.36
    4994  285.11  4998.1  285.02  5000.9  284.52  5004.1  285.02    5034  285.43
  5041.6  288.46  5078.9  288.82  5316.2  291.93  5385.9  295.96    5486  302.75
  5525.3  305.67  5530.3  307.29  5588.3  309.66  5605.9  313.75  5648.8  319.13
  5741.3  327.63  5743.5  327.79  5767.2  330.23  5772.2  329.41    5810  334.69
#Mann= 8 ,-1 , 0
  4576.6     .16       0  4998.1     .07       0  5004.1     .16       0
  5078.9     .05       0  5385.9     .16       0    5486      .1       0
  5741.3     .16       0  5743.5      .1       0
Bank Sta=4988.7,5041.6
XS Rating Curve= 0 ,0
Exp/Cntr=0.3,0.1

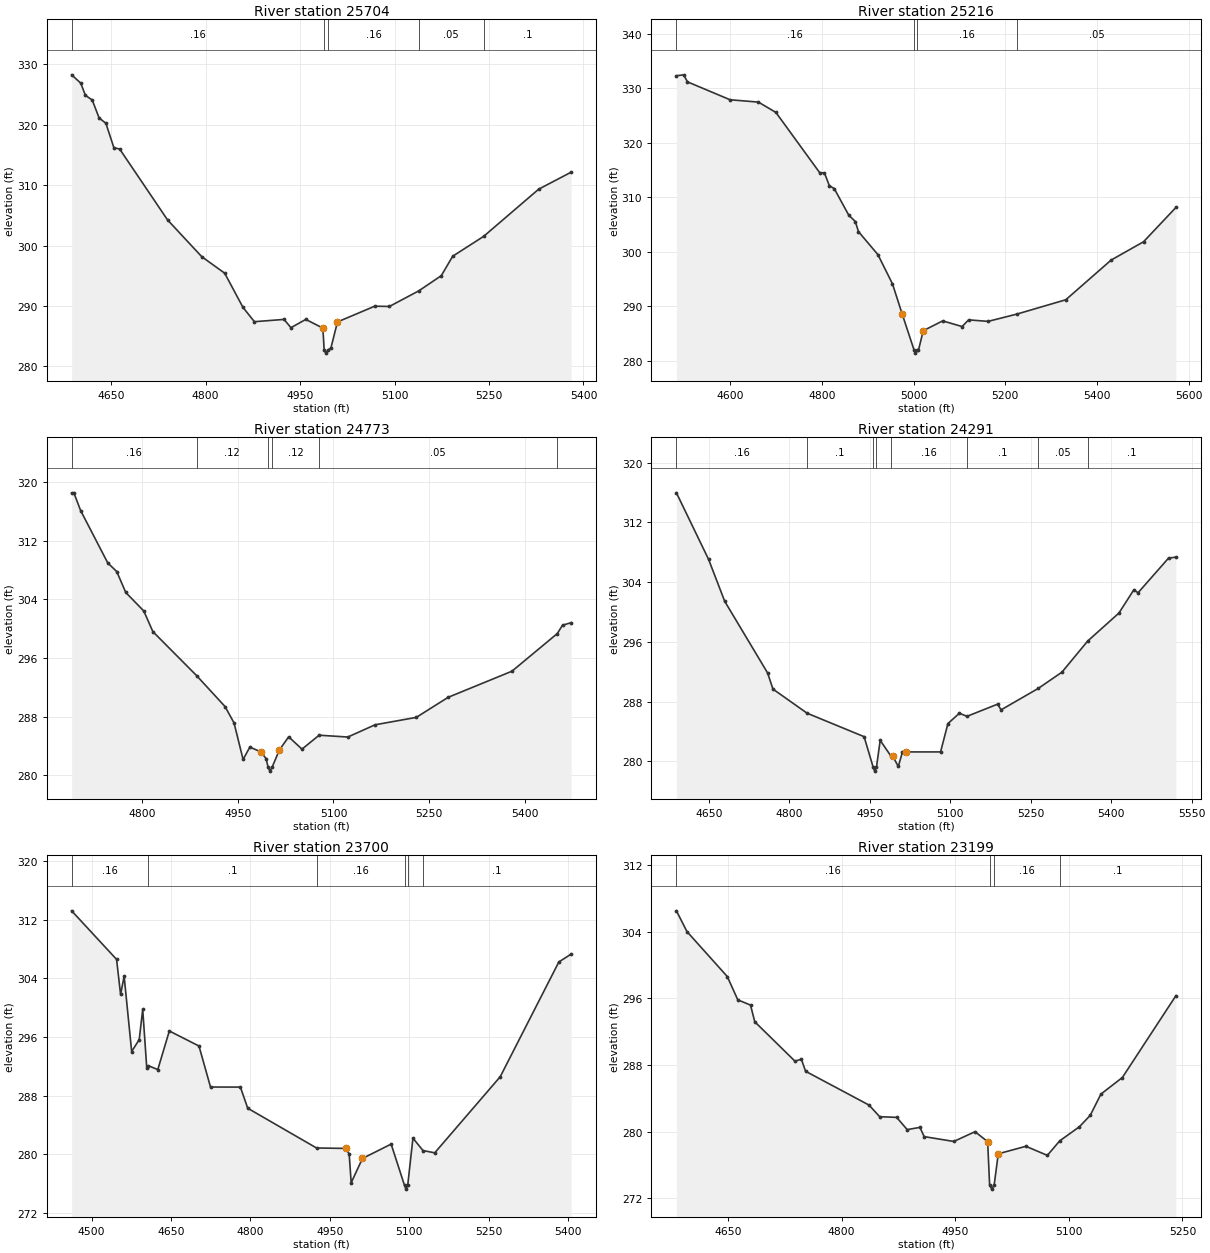
Type RM Length L Ch R = 1 ,25704   ,488,488,488
BEGIN DESCRIPTION:
RESACA CREEK 47.0
END DESCRIPTION:
XS GIS Cut Line= 3
      3681749.58      10501660.2      3682099.61     10501510.19
      3682499.58      10501410.2
#Sta/Elev= 30
  4587.3  328.25  4601.8  326.87  4609.1  324.86    4620  324.08  4630.9  321.12
  4641.7  320.23  4654.4  316.18  4663.5  315.98  4739.6  304.24    4794  298.15
  4830.3  295.43  4859.3  289.78  4877.5   287.4  4924.6  287.78  4935.5  286.41
  4959.1  287.78  4986.2  286.34  4988.3   282.7  4991.1   282.2  4994.3   282.7
    4999  283.06  5009.4  287.36  5068.6  289.97  5091.8  289.92  5138.6  292.51
  5174.3  295.02  5192.3  298.23  5241.5  301.52  5328.9  309.33  5380.4  312.14
#Mann= 5 ,-1 , 0
  4587.3     .16       0  4988.3     .07       0  4994.3     .16       0
  5138.6     .05       0  5241.5      .1       0
Bank Sta=4986.2,5009.4
XS Rating Curve= 0 ,0
Exp/Cntr=0.3,0.1

Type RM Length L Ch R = 1 ,25216   ,443,443,443
BEGIN DESCRIPTION:
RESACA CREEK 46.0
END DESCRIPTION:
XS GIS Cut Line= 3
      3681604.67     10502084.19      3682099.61     10501910.19
      3682499.59      10501510.2
#Sta/Elev= 30
    4482  332.32  4497.8  332.49  4506.1   331.2  4599.1  327.91    4661  327.48
  4699.2  325.58  4794.6  314.53  4805.2  314.46  4815.9  312.11  4826.4  311.61
  4858.2  306.71  4872.5  305.55  4879.4  303.69  4921.8  299.47  4953.6   294.1
  4974.8  288.56    5001  281.88  5003.7  281.38    5007  281.88  5010.2  281.88
  5020.8   285.5  5063.2   287.3  5105.6  286.26  5119.8  287.49  5162.2  287.21
  5224.8  288.54  5331.9  291.18  5430.9  298.47  5501.6  301.83  5572.3  308.13
#Mann= 4 ,-1 , 0
    4482     .16       0    5001     .07       0    5007     .16       0
  5224.8     .05       0
Bank Sta=4974.8,5020.8
XS Rating Curve= 0 ,0
Exp/Cntr=0.3,0.1

Type RM Length L Ch R = 1 ,24773   ,482,482,482
BEGIN DESCRIPTION:
RESACA CREEK 45.0
END DESCRIPTION:
XS GIS Cut Line= 3
      3682049.62     10502510.18      3682249.61     10502310.19
      3682649.59     10502010.21
#Sta/Elev= 30
  4689.7  318.53  4693.2  318.53  4703.8  316.11  4746.3  308.97  4760.4  307.79
  4774.5  304.94  4802.8  302.41    4817   299.6  4885.4  293.61  4930.1  289.38
  4944.2  287.15  4958.4  282.16    4969  283.85  4986.1   283.2  4994.4  282.29
  4997.7  281.07  5000.4  280.57  5003.7  281.07  5015.2  283.44  5029.8  285.25
  5050.7  283.57  5077.6  285.47  5122.5  285.22  5165.2  286.89  5229.8   287.9
  5279.8  290.64  5379.8   294.2  5450.9  299.34    5459  300.47  5472.5  300.82
#Mann= 6 ,-1 , 0
  4689.7     .16       0  4885.4     .12       0  4997.7     .07       0
  5003.7     .12       0  5077.6     .05       0  5450.9      .1       0
Bank Sta=4986.1,5015.2
XS Rating Curve= 0 ,0
Exp/Cntr=0.3,0.1

Type RM Length L Ch R = 1 ,24291   ,591,591,591
BEGIN DESCRIPTION:
RESACA CREEK 44.0
END DESCRIPTION:
XS GIS Cut Line= 3
      3682099.59     10502660.19      3682499.61     10502660.19
      3682849.59     10502260.21
#Sta/Elev= 30
  4589.2  315.95  4649.2  307.04  4679.2  301.44  4759.2  291.85  4769.2  289.69
  4832.9  286.46  4939.2  283.32  4956.2  279.21    4959  278.71  4962.2  279.21
  4969.2  282.83  4989.3  280.72  4992.5  280.72    5003  279.33  5010.6  281.24
  5017.2  281.28  5081.8  281.28  5095.5  285.07  5116.9  286.46    5131  286.04
  5188.1  287.67  5194.7  286.91  5263.8  289.77  5308.1  291.95  5356.2  296.12
  5414.4  299.86  5442.4  302.99    5450  302.57    5507  307.22  5520.7  307.34
#Mann= 8 ,-1 , 0
  4589.2     .16       0  4832.9      .1       0  4956.2     .07       0
  4962.2      .1       0  4989.3     .16       0    5131      .1       0
  5263.8     .05       0  5356.2      .1       0
Bank Sta=4992.5,5017.2
XS Rating Curve= 0 ,0
Exp/Cntr=0.3,0.1

Type RM Length L Ch R = 1 ,23700   ,501,501,501
BEGIN DESCRIPTION:
RESACA CREEK 43.0
END DESCRIPTION:
XS GIS Cut Line= 3
      3682399.61     10503360.19      3682749.61     10502960.19
      3683149.59     10502860.19
#Sta/Elev= 30
  4462.2   313.2  4547.1  306.58  4554.7   301.8  4561.4  304.28  4575.6  294.02
  4589.9  295.65  4596.5  299.77  4604.1  291.83  4607.3  292.08    4625  291.56
  4646.8  296.82  4702.8  294.77  4724.6  289.18  4781.1  289.17  4794.9  286.29
  4924.9  280.87  4979.9  280.81  4986.6  280.06  4990.4  276.13  5011.7  279.44
  5065.9   281.4  5091.2  275.76    5094  275.26  5097.2  275.76  5107.1  282.21
  5126.1  280.52  5148.3  280.21    5272  290.58  5382.8  306.23    5406   307.3
#Mann= 6 ,-1 , 0
  4462.2     .16       0  4607.3      .1       0  4924.9     .16       0
  5091.2     .07       0  5097.2     .16       0  5126.1      .1       0
Bank Sta=4979.9,5011.7
XS Rating Curve= 0 ,0
Exp/Cntr=0.3,0.1

Type RM Length L Ch R = 1 ,23199   ,712,712,712
BEGIN DESCRIPTION:
RESACA CREEK 42.0
END DESCRIPTION:
XS GIS Cut Line= 3
      3682599.63     10503460.18      3682999.61     10503260.19
       3683149.6      10503110.2
#Sta/Elev= 30
  4582.1   306.5    4596  304.01  4649.2  298.62  4663.1  295.82  4679.9  295.19
  4685.5  293.19  4738.6  288.46    4747   288.7  4752.6  287.25  4836.4  283.19
  4850.4   281.8  4872.8  281.72  4886.7  280.25  4903.5  280.52  4909.1  279.41
  4948.2  278.83  4976.2     280  4992.9  278.81  4995.5  273.61  4998.3  273.11
  5001.5  273.61  5006.9  277.35  5043.4  278.25  5071.7  277.16    5088   278.9
  5114.1   280.6  5128.3  281.96  5142.4  284.51  5170.7   286.5  5241.4  296.32
#Mann= 4 ,-1 , 0
  4582.1     .16       0  4995.5     .07       0  5001.5     .16       0
    5088      .1       0
Bank Sta=4992.9,5006.9
XS Rating Curve= 0 ,0
Exp/Cntr=0.3,0.1

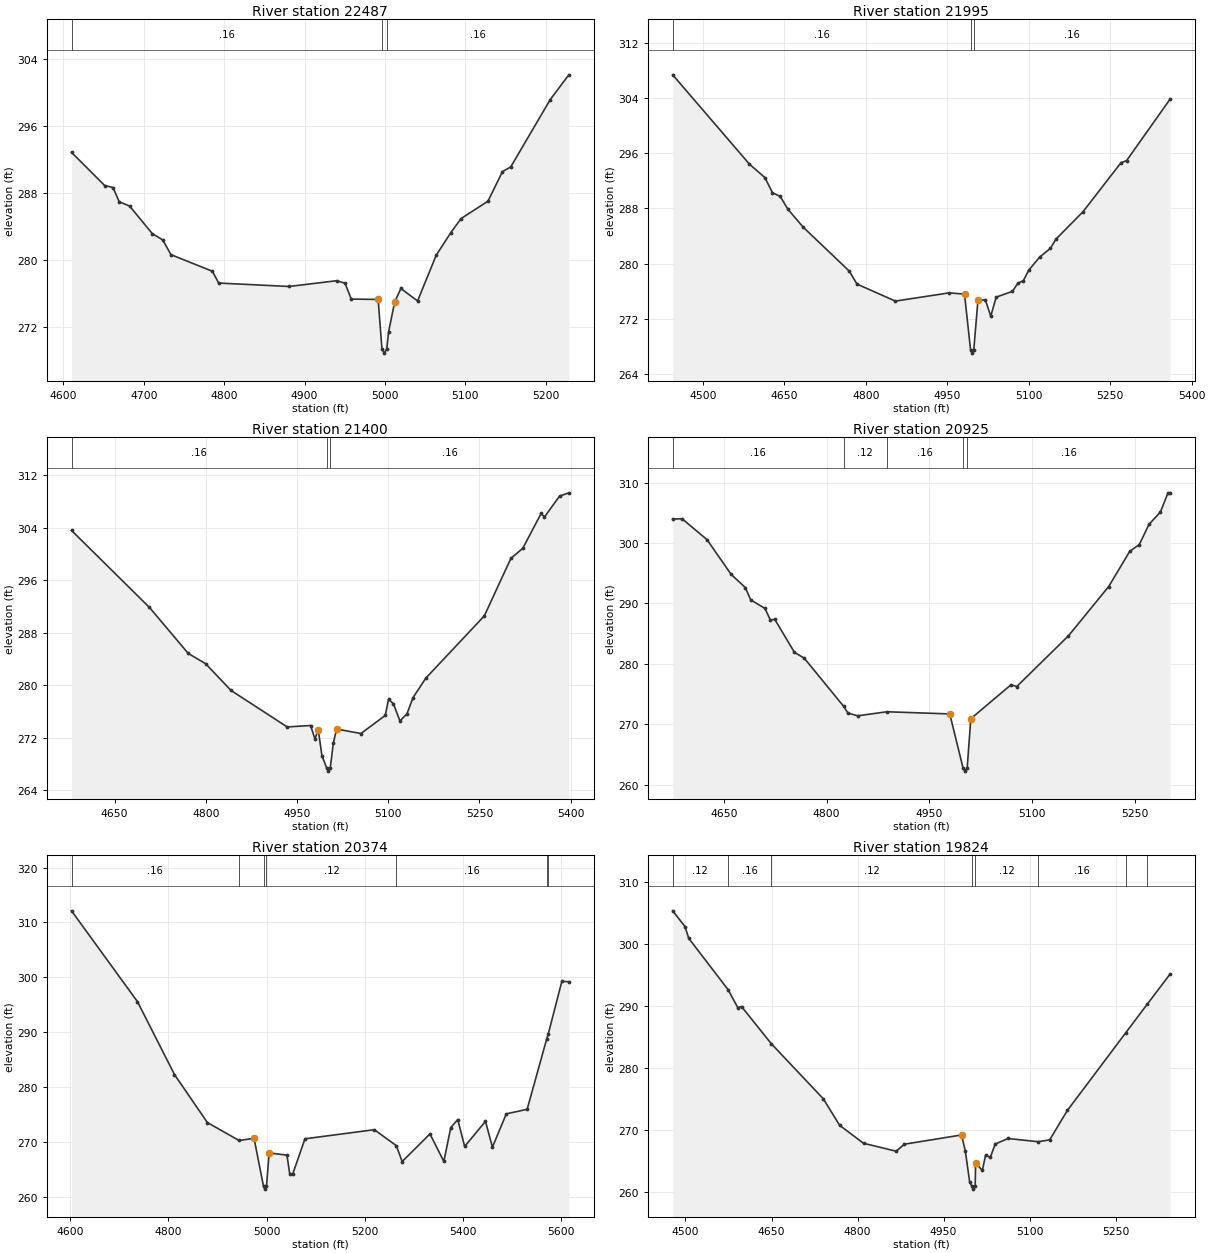
Type RM Length L Ch R = 1 ,22487   ,492,492,492
BEGIN DESCRIPTION:
RESACA CREEK 41.0
END DESCRIPTION:
XS GIS Cut Line= 3
       3682849.6     10503710.19      3683249.61     10503610.19
      3683449.63     10503560.18
#Sta/Elev= 30
  4610.1  292.87  4651.3  288.91  4661.7  288.67  4669.4  286.97  4682.3  286.46
  4710.6  283.16  4723.5  282.42  4733.8  280.65  4785.3  278.67  4793.1  277.26
  4880.7  276.85    4940  277.54  4950.3  277.24    4958  275.35  4991.5   275.3
  4996.2  269.39    4999  268.89  5002.2  269.39  5004.4  271.41  5012.1  275.02
  5019.8  276.61  5040.5  275.12  5063.7  280.58  5081.7  283.26  5094.6  284.96
  5128.1  287.04  5146.1  290.57  5156.4  291.13  5205.4  299.15  5228.6  302.13
#Mann= 3 ,-1 , 0
  4610.1     .16       0  4996.2     .07       0  5002.2     .16       0
Bank Sta=4991.5,5012.1
XS Rating Curve= 0 ,0
Exp/Cntr=0.3,0.1

Type RM Length L Ch R = 1 ,21995   ,595,595,595
BEGIN DESCRIPTION:
RESACA CREEK 40.0
END DESCRIPTION:
XS GIS Cut Line= 3
      3682849.61     10504360.19      3683249.61     10503960.19
      3683599.63     10503960.19
#Sta/Elev= 30
  4444.3  307.34  4585.7  294.41    4614  292.48  4628.1  290.28  4642.3  289.75
  4656.4   287.9  4684.7  285.29  4769.6  278.93  4783.7  277.06  4854.4   274.6
  4953.4  275.79  4981.7  275.61  4992.8  267.57  4995.6  267.07  4998.8  267.57
  5006.4  274.69    5020   274.8    5030  272.41    5040  275.17    5070  276.01
    5080  277.18    5090  277.56    5100  279.07    5120  280.96    5140  282.24
    5150  283.56    5200  287.54    5270  294.64    5280  294.91    5360  303.79
#Mann= 3 ,-1 , 0
  4444.3     .16       0  4992.8     .07       0  4998.8     .16       0
Bank Sta=4981.7,5006.4
XS Rating Curve= 0 ,0
Exp/Cntr=0.3,0.1

Type RM Length L Ch R = 1 ,21400   ,475,475,475
BEGIN DESCRIPTION:
RESACA CREEK 39.0
END DESCRIPTION:
XS GIS Cut Line= 3
      3683099.64     10504610.17      3683399.61     10504360.19
      3683799.63     10504210.18
#Sta/Elev= 30
  4579.2  303.61  4707.4  291.87  4771.2  284.87  4799.8   283.3  4841.5  279.23
  4933.9  273.67  4972.3  273.89  4979.5  271.84  4984.8  273.28    4991  269.29
  4998.7  267.44  5001.5  266.94  5004.7  267.44  5009.7   271.2  5015.1  273.35
  5055.1  272.67  5095.2  275.43  5100.5  277.88  5108.5  277.22  5119.2  274.59
  5130.8  275.66  5140.6  278.12  5161.9  281.12    5258  290.59  5301.6  299.34
  5321.2  300.88  5351.5  306.21  5356.8  305.65  5381.7  308.83  5396.9  309.34
#Mann= 3 ,-1 , 0
  4579.2     .16       0  4998.7     .07       0  5004.7     .16       0
Bank Sta=4984.8,5015.1
XS Rating Curve= 0 ,0
Exp/Cntr=0.3,0.1

Type RM Length L Ch R = 1 ,20925   ,551,551,551
BEGIN DESCRIPTION:
RESACA CREEK 38.0
END DESCRIPTION:
XS GIS Cut Line= 3
      3683399.61     10504910.19      3683699.61     10504660.19
       3683849.6     10504360.21
#Sta/Elev= 30
  4575.4  303.96  4589.1  304.02  4625.5  300.56  4660.7  294.81  4681.5  292.62
  4689.3  290.58  4710.1  289.18  4717.9  287.26  4724.4  287.36  4753.1   281.9
  4767.4  280.94  4825.1  272.94  4831.2  271.85  4845.5  271.39  4888.2  272.06
  4979.9   271.7  4999.3  262.73    5002  262.23  5005.3  262.73  5010.6  270.91
  5069.3  276.53  5077.7  276.24  5153.2  284.64  5211.9   292.8  5242.6  298.62
  5256.6  299.75  5270.6  303.07  5287.3  305.12  5298.5  308.31  5301.3  308.31
#Mann= 5 ,-1 , 0
  4575.4     .16       0  4825.1     .12       0  4888.2     .16       0
  4999.3     .07       0  5005.3     .16       0
Bank Sta=4979.9,5010.6
XS Rating Curve= 0 ,0
Exp/Cntr=0.3,0.1

Type RM Length L Ch R = 1 ,20374   ,550,550,550
BEGIN DESCRIPTION:
RESACA CREEK 37.0
END DESCRIPTION:
XS GIS Cut Line= 3
      3683449.58      10505160.2      3683849.61     10504960.19
      3684249.59     10504560.21
#Sta/Elev= 30
  4602.6  312.11  4736.8  295.56  4812.3  282.25  4879.3   273.5  4943.9  270.22
  4974.4  270.62  4993.7  261.85  4996.5  261.35  4999.7  261.85  5005.1  267.96
  5041.5  267.54    5047  264.16  5053.4  264.16  5078.1  270.53  5219.5  272.19
  5264.3  269.27  5276.1  266.38  5332.7  271.42    5361   266.4  5375.1  272.57
  5389.3  274.04  5403.4  269.13  5445.8  273.72    5460  269.01  5488.2  275.08
  5530.7  275.91  5570.7   288.8  5573.7  289.65  5601.4  299.25  5615.5  299.18
#Mann= 7 ,-1 , 0
  4602.6     .16       0  4943.9     .12       0  4993.7     .07       0
  4999.7     .12       0  5264.3     .16       0  5570.7     .05       0
  5573.7     .08       0
Bank Sta=4974.4,5005.1
XS Rating Curve= 0 ,0
Exp/Cntr=0.3,0.1

Type RM Length L Ch R = 1 ,19824   ,519,519,519
BEGIN DESCRIPTION:
RESACA CREEK 36.0
END DESCRIPTION:
XS GIS Cut Line= 3
      3683749.58     10505710.22      3684099.61     10505310.19
      3684399.64     10505160.17
#Sta/Elev= 30
  4477.7  305.37  4499.1  302.84  4505.7  300.93  4574.2  292.66  4591.2  289.75
  4597.8  289.92  4649.8  283.91  4740.2  275.05  4768.7  270.77  4810.4  267.86
  4867.4  266.58  4881.6  267.71  4981.3   269.2  4987.9  266.64  4995.5  261.62
  4999.1  260.96  5001.9  260.46  5005.1  260.96  5005.9  264.69  5017.6  263.47
  5023.2  265.93  5031.6   265.6    5040  267.73  5062.4  268.63    5115  268.11
    5135  268.41  5165.8  273.15  5267.3  285.65  5305.3  290.32  5344.7  295.14
#Mann= 8 ,-1 , 0
  4477.7     .12       0  4574.2     .16       0  4649.8     .12       0
  4999.1     .07       0  5005.1     .12       0    5115     .16       0
  5267.3     .12       0  5305.3     .16       0
Bank Sta=4981.3,5005.9
XS Rating Curve= 0 ,0
Exp/Cntr=0.3,0.1