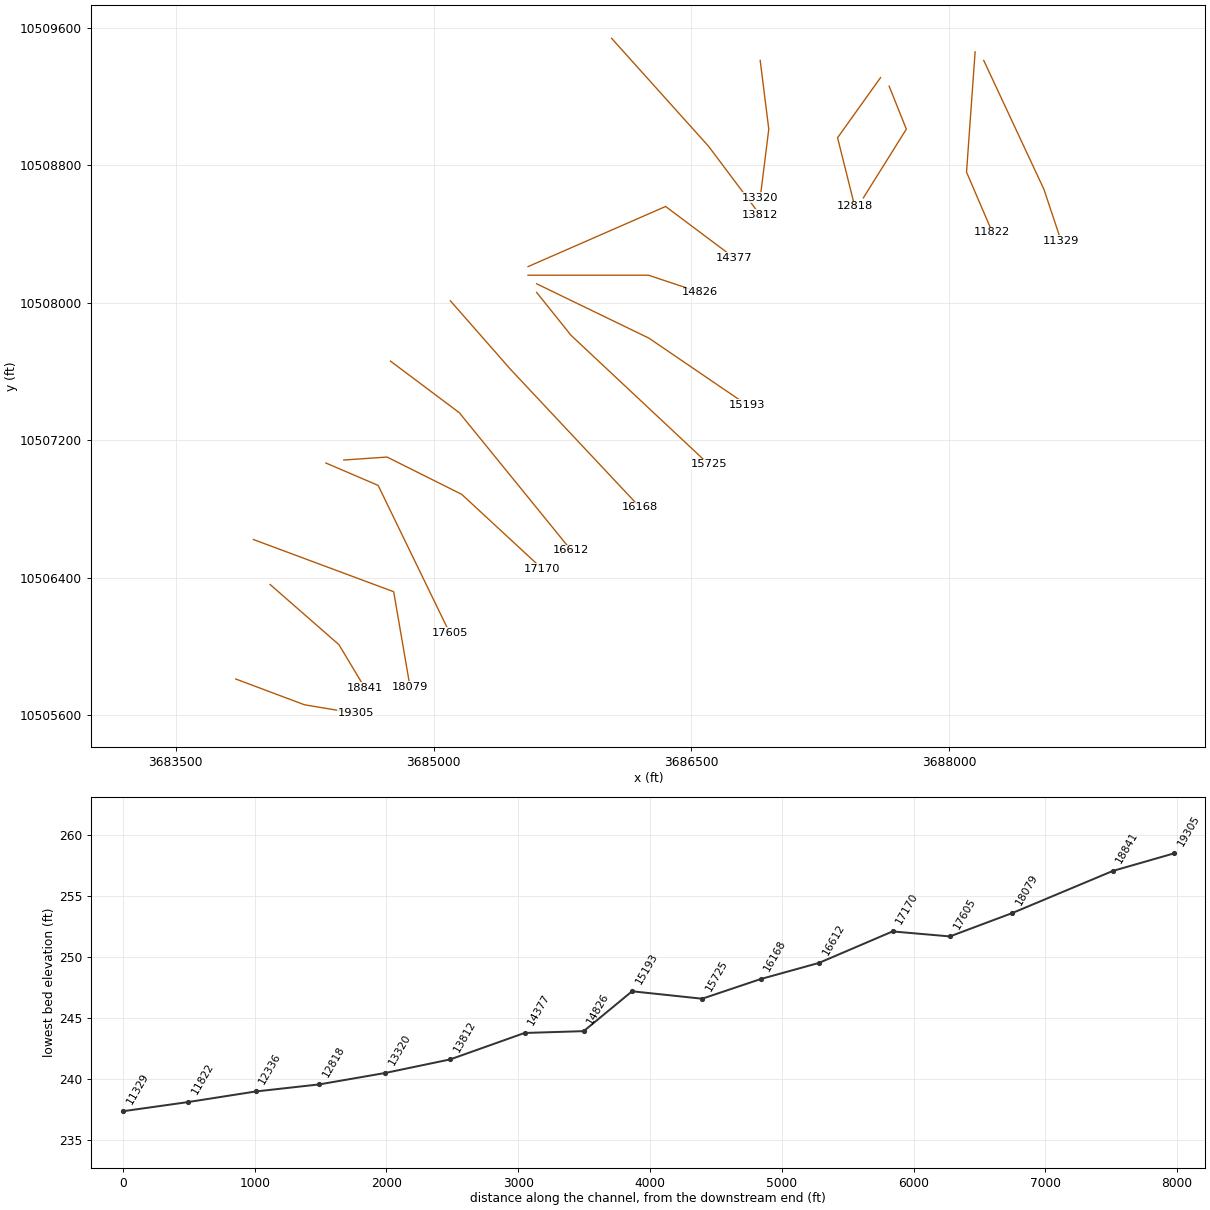
HEC-RAS study RESACA CREEK.prj: RESACA CREEK Base Level Engineering

--- RESACA CREEK.g01 (geometry) --- (continued)

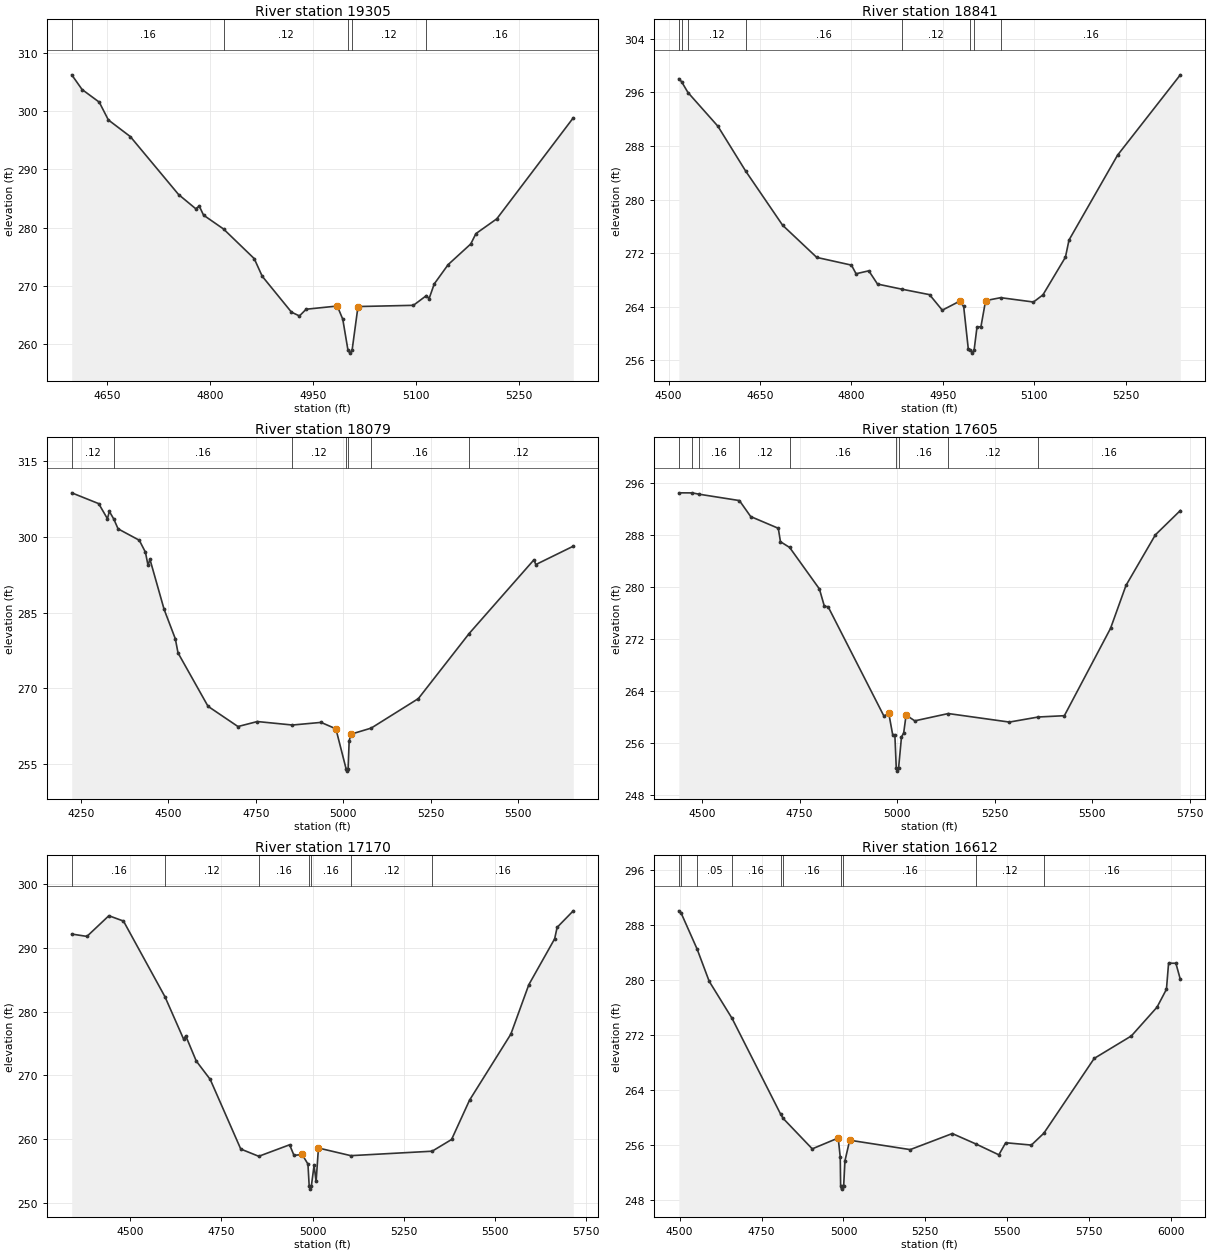
Type RM Length L Ch R = 1 ,19305   ,464,464,464
BEGIN DESCRIPTION:
RESACA CREEK 35.0
END DESCRIPTION:
XS GIS Cut Line= 3
       3683849.6     10505810.19      3684249.61     10505660.19
      3684549.56      10505610.2
#Sta/Elev= 30
  4598.3   306.2  4613.4  303.68  4638.4  301.52  4651.7  298.47  4683.7  295.62
  4754.1  285.69    4779  283.27  4784.3  283.69  4790.5  282.16  4819.6  279.79
  4864.4  274.71    4876   271.7  4918.7  265.54  4930.3  264.89  4940.1  266.04
  4985.5  266.59  4993.5  264.33  5001.1  259.02  5003.9  258.52  5007.1  259.02
  5015.7   266.5  5096.5  266.71  5115.5  268.38  5119.3  267.83  5126.9  270.38
  5147.2  273.69  5180.1  277.22  5187.7     279  5218.1  281.53  5329.6  298.83
#Mann= 5 ,-1 , 0
  4598.3     .16       0  4819.6     .12       0  5001.1     .07       0
  5007.1     .12       0  5115.5     .16       0
Bank Sta=4985.5,5015.7
XS Rating Curve= 0 ,0
Exp/Cntr=0.3,0.1

Type RM Length L Ch R = 1 ,18841   ,762,762,762
BEGIN DESCRIPTION:
RESACA CREEK 34.0
END DESCRIPTION:
XS GIS Cut Line= 3
      3684049.59     10506360.21      3684449.61     10506010.19
      3684599.62     10505760.17
#Sta/Elev= 30
  4516.9  298.04  4521.4  297.61  4531.9  295.99    4581  290.96  4626.7  284.25
  4687.3  276.17  4743.3  271.37  4800.2  270.22  4807.8  268.93  4828.7  269.37
    4843  267.39  4882.8  266.63  4928.4  265.81  4949.3  263.49  4977.7  264.83
  4984.4  264.05    4992   257.7  4995.6  257.58  4998.4  257.08  5001.6  257.58
  5006.2  260.92  5012.8  261.05  5020.4  264.92  5045.2  265.36    5099  264.71
  5114.5  265.78  5151.4   271.4  5157.3  273.97    5237  286.64    5340  298.63
#Mann= 8 ,-1 , 0
  4516.9     .12       0  4521.4     .16       0  4531.9     .12       0
  4626.7     .16       0  4882.8     .12       0  4995.6     .07       0
  5001.6     .12       0  5045.2     .16       0
Bank Sta=4977.7,5020.4
XS Rating Curve= 0 ,0
Exp/Cntr=0.3,0.1

Type RM Length L Ch R = 1 ,18079   ,474,474,474
BEGIN DESCRIPTION:
RESACA CREEK 33.0
END DESCRIPTION:
XS GIS Cut Line= 3
      3683952.22     10506621.99      3684768.22     10506318.16
      3684863.48     10505763.91
#Sta/Elev= 30
  4224.2  308.74  4301.2   306.6  4326.2  303.61  4331.6  305.07  4344.4  303.54
  4356.6  301.61  4417.2  299.35  4434.8  296.98  4442.2  294.36  4447.6  295.59
  4488.2  285.65  4520.2  279.83  4527.9  277.04  4613.6  266.47  4699.2  262.46
  4754.6  263.45  4854.8  262.76  4936.6  263.28    4979  262.01    5008  254.13
  5010.8  253.63    5014  254.13  5016.9  259.64  5022.3  260.95  5079.9  262.15
  5214.6  267.99  5359.8  280.88  5545.1  295.49  5550.2  294.53  5657.3  298.17
#Mann= 7 ,-1 , 0
  4224.2     .12       0  4344.4     .16       0  4854.8     .12       0
    5008     .07       0    5014     .12       0  5079.9     .16       0
  5359.8     .12       0
Bank Sta=4979,5022.3
XS Rating Curve= 0 ,0
Exp/Cntr=0.3,0.1

Type RM Length L Ch R = 1 ,17605   ,435,435,435
BEGIN DESCRIPTION:
RESACA CREEK 32.0
END DESCRIPTION:
XS GIS Cut Line= 3
      3684373.84     10507067.21      3684677.68       10506937.
      3685094.33     10506077.65
#Sta/Elev= 30
  4440.5  294.49    4475  294.48  4492.2  294.28  4595.8   293.3  4624.8  290.84
  4695.5  289.04    4701  286.98  4724.6  286.09  4800.9  279.71  4813.7  277.03
  4823.1  276.99  4966.2  260.18  4978.7   260.6  4988.7  257.31  4994.3  257.29
  4997.9  252.21  5000.7  251.71  5003.9  252.21  5011.3  256.97  5016.9  257.57
  5023.1  260.32  5045.4  259.44  5131.3  260.56  5287.8  259.25  5361.9  260.03
  5428.8  260.23  5547.2  273.66  5586.8  280.26  5662.1  288.03  5726.1  291.77
#Mann= 9 ,-1 , 0
  4440.5     .16       0    4475     .12       0  4492.2     .16       0
  4595.8     .12       0  4724.6     .16       0  4997.9     .07       0
  5003.9     .16       0  5131.3     .12       0  5361.9     .16       0
Bank Sta=4978.7,5023.1
XS Rating Curve= 0 ,0
Exp/Cntr=0.3,0.1

Type RM Length L Ch R = 1 ,17170   ,558,558,558
BEGIN DESCRIPTION:
RESACA CREEK 31.0
END DESCRIPTION:
XS GIS Cut Line= 4
      3684477.98     10507084.56      3684729.76     10507101.93
      3685163.79     10506884.91      3685632.56     10506450.87
#Sta/Elev= 30
  4339.2  292.21  4380.9  291.84  4441.1  295.09  4481.2  294.25  4595.2  282.34
  4646.5  275.66  4652.1  276.21  4680.9  272.26  4719.2  269.37  4803.1  258.42
  4852.5  257.28  4937.2  259.09  4949.2  257.42  4971.5  257.57  4987.5  256.06
  4990.9  252.62  4993.7  252.12  4996.9  252.62  5004.3  255.85  5009.9  253.34
  5016.3  258.58  5105.2  257.38  5328.4  258.08  5381.7  259.92    5431   266.1
  5544.4  276.48  5593.7  284.25  5664.6  291.46  5671.4  293.26  5715.7  295.86
#Mann= 7 ,-1 , 0
  4339.2     .16       0  4595.2     .12       0  4852.5     .16       0
  4990.9     .07       0  4996.9     .16       0  5105.2     .12       0
  5328.4     .16       0
Bank Sta=4971.5,5016.3
XS Rating Curve= 0 ,0
Exp/Cntr=0.3,0.1

Type RM Length L Ch R = 1 ,16612   ,444,444,444
BEGIN DESCRIPTION:
RESACA CREEK 30.0
END DESCRIPTION:
XS GIS Cut Line= 3
      3684749.59      10507660.2      3685149.61     10507360.19
      3685799.61     10506560.19
#Sta/Elev= 30
  4497.5   290.1  4504.7  289.76  4553.4  284.52  4590.2  279.83  4660.2  274.41
    4808  260.49  4815.7  259.86  4904.8  255.41    4984  256.99  4990.2  254.21
  4991.4  250.04  4994.1  249.54  4997.4  250.04  5000.7  250.04  5004.7  253.69
  5019.1  256.67  5203.7   255.3  5332.3  257.64  5405.3   256.1  5474.3  254.54
  5495.3   256.3  5573.6  255.96  5611.7  257.69  5765.4  268.59  5878.9  271.87
  5957.2  276.06  5985.9  278.67  5992.4  282.47  6014.7  282.46  6028.3   280.1
#Mann= 10 ,-1 , 0
  4497.5     .07       0  4504.7     .16       0  4553.4     .05       0
  4660.2     .16       0    4808     .05       0  4815.7     .16       0
  4991.4     .07       0  4997.4     .16       0  5405.3     .12       0
  5611.7     .16       0
Bank Sta=4984,5019.1
XS Rating Curve= 0 ,0
Exp/Cntr=0.3,0.1

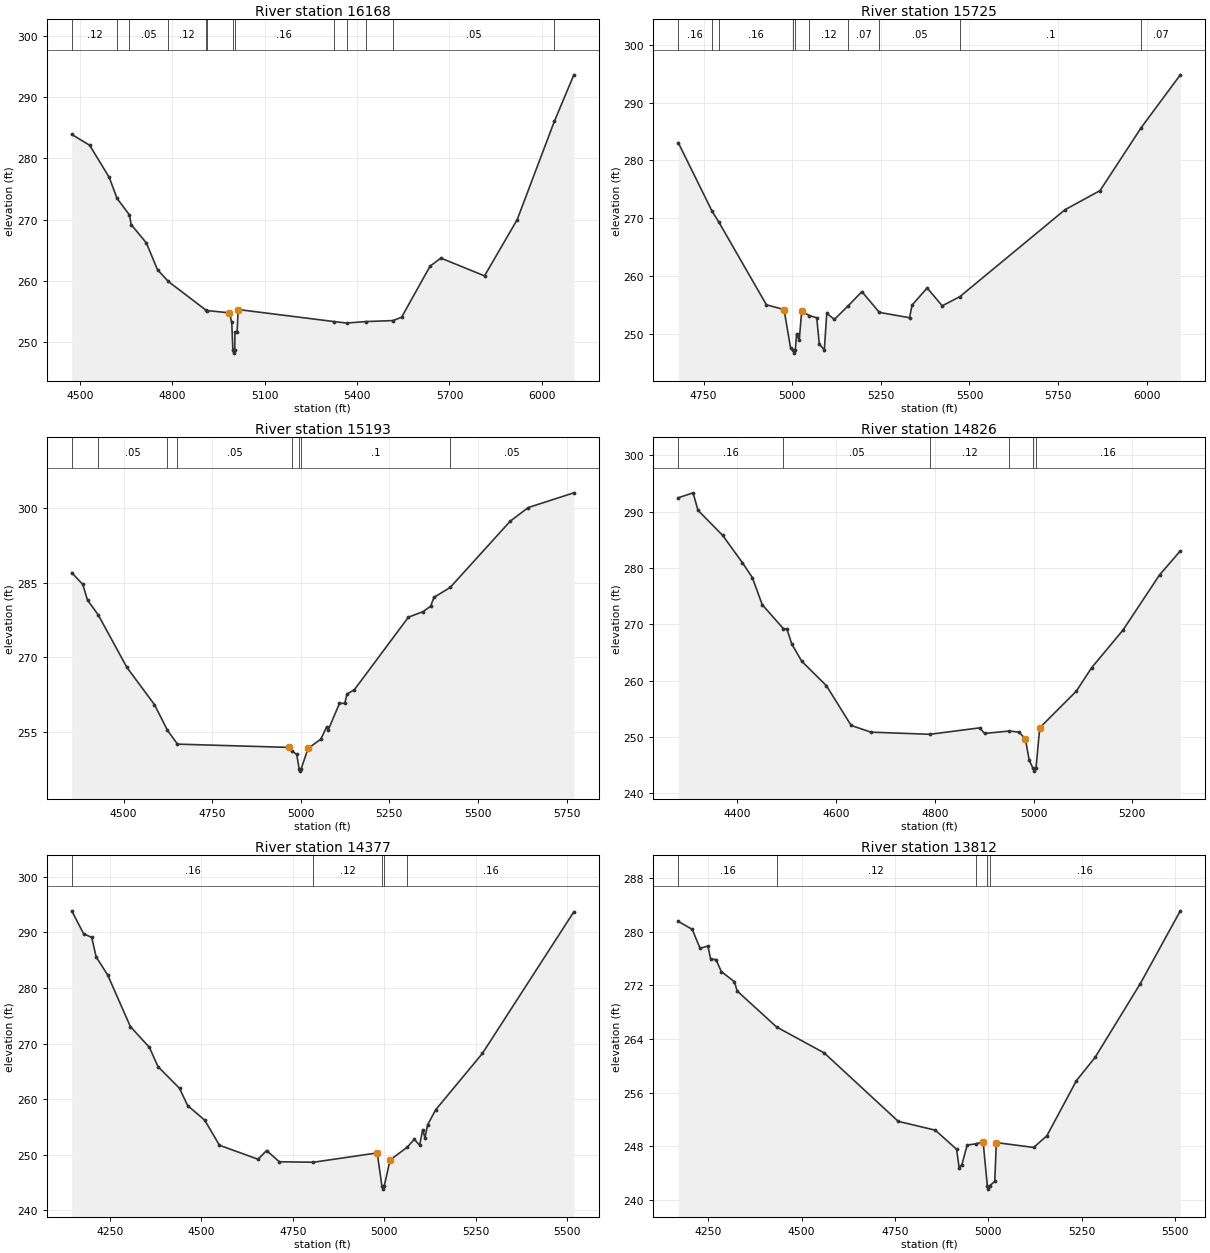
Type RM Length L Ch R = 1 ,16168   ,443,443,443
BEGIN DESCRIPTION:
RESACA CREEK 29.0
END DESCRIPTION:
XS GIS Cut Line= 3
      3685098.06     10508010.88      3685449.61     10507610.19
      3686199.58     10506810.21
#Sta/Elev= 30
    4474  283.88  4532.1  282.11  4595.7  276.86  4620.9  273.45  4661.2  270.75
  4666.9  269.17  4716.2  266.18  4752.3  261.81  4787.4   259.9  4909.5  255.22
  4913.6  255.15  4985.7  254.78  4993.3  253.21  4996.9  248.71  4999.7  248.21
  5002.9  248.71  5003.7  251.58  5010.5  251.58  5014.1  255.32  5324.7  253.36
  5365.7  253.12  5430.1  253.36  5516.4  253.52  5544.6  254.07  5636.9  262.39
  5672.1  263.71  5813.7  260.81  5919.7  269.98  6040.3  286.01  6103.6   293.6
#Mann= 13 ,-1 , 0
    4474     .12       0  4620.9     .16       0  4661.2     .05       0
  4787.4     .12       0  4909.5     .05       0  4913.6     .16       0
  4996.9     .07       0  5002.9     .16       0  5324.7     .12       0
  5365.7     .05       0  5430.1     .07       0  5516.4     .05       0
  6040.3      .1       0
Bank Sta=4985.7,5014.1
XS Rating Curve= 0 ,0
Exp/Cntr=0.3,0.1

Type RM Length L Ch R = 1 ,15725   ,532,532,532
BEGIN DESCRIPTION:
RESACA CREEK 28.0
END DESCRIPTION:
XS GIS Cut Line= 3
      3685599.61     10508060.19      3685799.61     10507810.19
      3686599.57     10507060.22
#Sta/Elev= 30
  4678.2  283.09  4774.1  271.15    4792   269.4  4927.1  254.97  4976.8  254.16
  4995.2  247.49  5002.4   247.1  5005.2   246.6  5008.4   247.1  5012.3  249.94
  5019.6  248.83  5026.5  253.82  5048.5  253.11    5069  252.72  5076.3  248.14
  5090.4  247.17  5097.3  253.49  5118.8  252.45  5158.1  254.82  5196.4  257.26
  5245.8  253.66  5330.8  252.74  5338.1  254.94  5380.6   257.9  5423.1   254.8
  5472.8  256.39  5769.4  271.45  5868.5  274.78  5984.7   285.7  6094.9  294.84
#Mann= 10 ,-1 , 0
  4678.2     .16       0  4774.1     .05       0    4792     .16       0
  5002.4     .07       0  5008.4     .16       0  5048.5     .12       0
  5158.1     .07       0  5245.8     .05       0  5472.8      .1       0
  5984.7     .07       0
Bank Sta=4976.8,5026.5
XS Rating Curve= 0 ,0
Exp/Cntr=0.3,0.1

Type RM Length L Ch R = 1 ,15193   ,367,367,367
BEGIN DESCRIPTION:
RESACA CREEK 27.0
END DESCRIPTION:
XS GIS Cut Line= 3
      3685599.63     10508110.18      3686252.59     10507793.85
      3686823.64      10507404.5
#Sta/Elev= 30
    4354     287  4385.1  284.63  4398.4  281.49  4428.4  278.57  4509.5  268.01
  4587.3  260.55  4624.1  255.39  4652.3  252.62  4966.2  251.97  4974.5   251.3
  4988.8  250.55  4995.5  247.71  4998.2  247.21  5001.5  247.71  5020.7  251.76
  5056.6  253.61  5073.6  256.13    5078  255.52  5109.4   260.8  5124.4  260.81
  5130.4  262.65  5151.4  263.53  5303.9  278.07  5345.9  279.21  5366.8  280.29
  5375.7  282.03  5421.7  284.03  5591.2  297.32    5642  300.05  5770.7     303
#Mann= 8 ,-1 , 0
    4354     .16       0  4428.4     .05       0  4624.1     .16       0
  4652.3     .05       0  4974.5      .1       0  4995.5     .07       0
  5001.5      .1       0  5421.7     .05       0
Bank Sta=4966.2,5020.7
XS Rating Curve= 0 ,0
Exp/Cntr=0.3,0.1

Type RM Length L Ch R = 1 ,14826   ,449,449,449
BEGIN DESCRIPTION:
RESACA CREEK 26.0
END DESCRIPTION:
XS GIS Cut Line= 3
      3685549.61     10508160.19      3686249.61     10508160.19
      3686549.58      10508060.2
#Sta/Elev= 30
  4280.9  292.47  4310.9  293.35  4320.9  290.25  4370.9  285.79  4410.9  280.93
  4430.9  278.31  4450.9  273.49  4493.6  269.25  4500.9  269.16  4510.9  266.47
  4530.9  263.45  4580.9   259.1  4630.9  252.05  4670.9  250.86  4790.2  250.48
  4890.9  251.62  4900.9  250.63  4951.1  251.06  4970.9  250.86  4983.5  249.65
  4991.4  245.84    4999  244.44  5001.7  243.94    5005  244.44  5012.5  251.63
  5086.3  258.11  5117.9  262.33  5181.2     269    5255  278.77  5297.1  283.04
#Mann= 6 ,-1 , 0
  4280.9     .16       0  4493.6     .05       0  4790.2     .12       0
  4951.1     .16       0    4999     .07       0    5005     .16       0
Bank Sta=4983.5,5012.5
XS Rating Curve= 0 ,0
Exp/Cntr=0.3,0.1

Type RM Length L Ch R = 1 ,14377   ,565,565,565
BEGIN DESCRIPTION:
RESACA CREEK 25.0
END DESCRIPTION:
XS GIS Cut Line= 3
      3685549.58     10508210.17      3686349.61     10508560.19
      3686749.57     10508260.22
#Sta/Elev= 30
  4145.7  293.89  4178.1  289.76  4200.3   289.1  4212.4   285.6    4244  282.33
    4306  273.05  4358.2   269.3  4381.6  265.83  4440.4  261.94  4462.7  258.83
  4509.4   256.2  4549.6  251.69  4655.2  249.17  4678.6  250.74  4713.3  248.72
  4806.5  248.63  4981.1  250.31  4994.1  244.29  4996.9  243.79  5000.1  244.29
  5016.2  249.03  5063.6  251.36  5082.5  252.77  5097.1  251.68  5105.4  254.49
  5111.7  253.04  5118.9  255.36  5140.8  258.06  5268.9  268.23  5518.9  293.72
#Mann= 5 ,-1 , 0
  4145.7     .16       0  4806.5     .12       0  4994.1     .07       0
  5000.1     .12       0  5063.6     .16       0
Bank Sta=4981.1,5016.2
XS Rating Curve= 0 ,0
Exp/Cntr=0.3,0.1

Type RM Length L Ch R = 1 ,13812   ,492,492,492
BEGIN DESCRIPTION:
RESACA CREEK 24.0
END DESCRIPTION:
XS GIS Cut Line= 3
      3686035.55     10509538.67      3686599.61     10508910.19
      3686899.62     10508510.18
#Sta/Elev= 30
  4169.9  281.57  4207.4  280.36  4228.4  277.54  4249.3  277.88  4256.8  275.92
    4271  275.87  4285.2  274.08  4320.3  272.55  4327.8  271.17  4433.2  265.81
    4561  261.93  4759.1  251.73  4858.5  250.41  4915.3  247.56  4922.1  244.84
  4929.5  245.29  4943.7   248.2  4966.4  248.37  4986.4  248.67  4997.6  242.12
  5000.3  241.62  5003.6  242.12  5017.5  242.77  5021.7  248.56  5121.7  247.84
  5157.1  249.58  5236.3  257.81  5286.3  261.28  5407.1  272.26  5514.4  283.13
#Mann= 5 ,-1 , 0
  4169.9     .16       0  4433.2     .12       0  4966.4     .16       0
  4997.6     .07       0  5003.6     .16       0
Bank Sta=4986.4,5021.7
XS Rating Curve= 0 ,0
Exp/Cntr=0.3,0.1

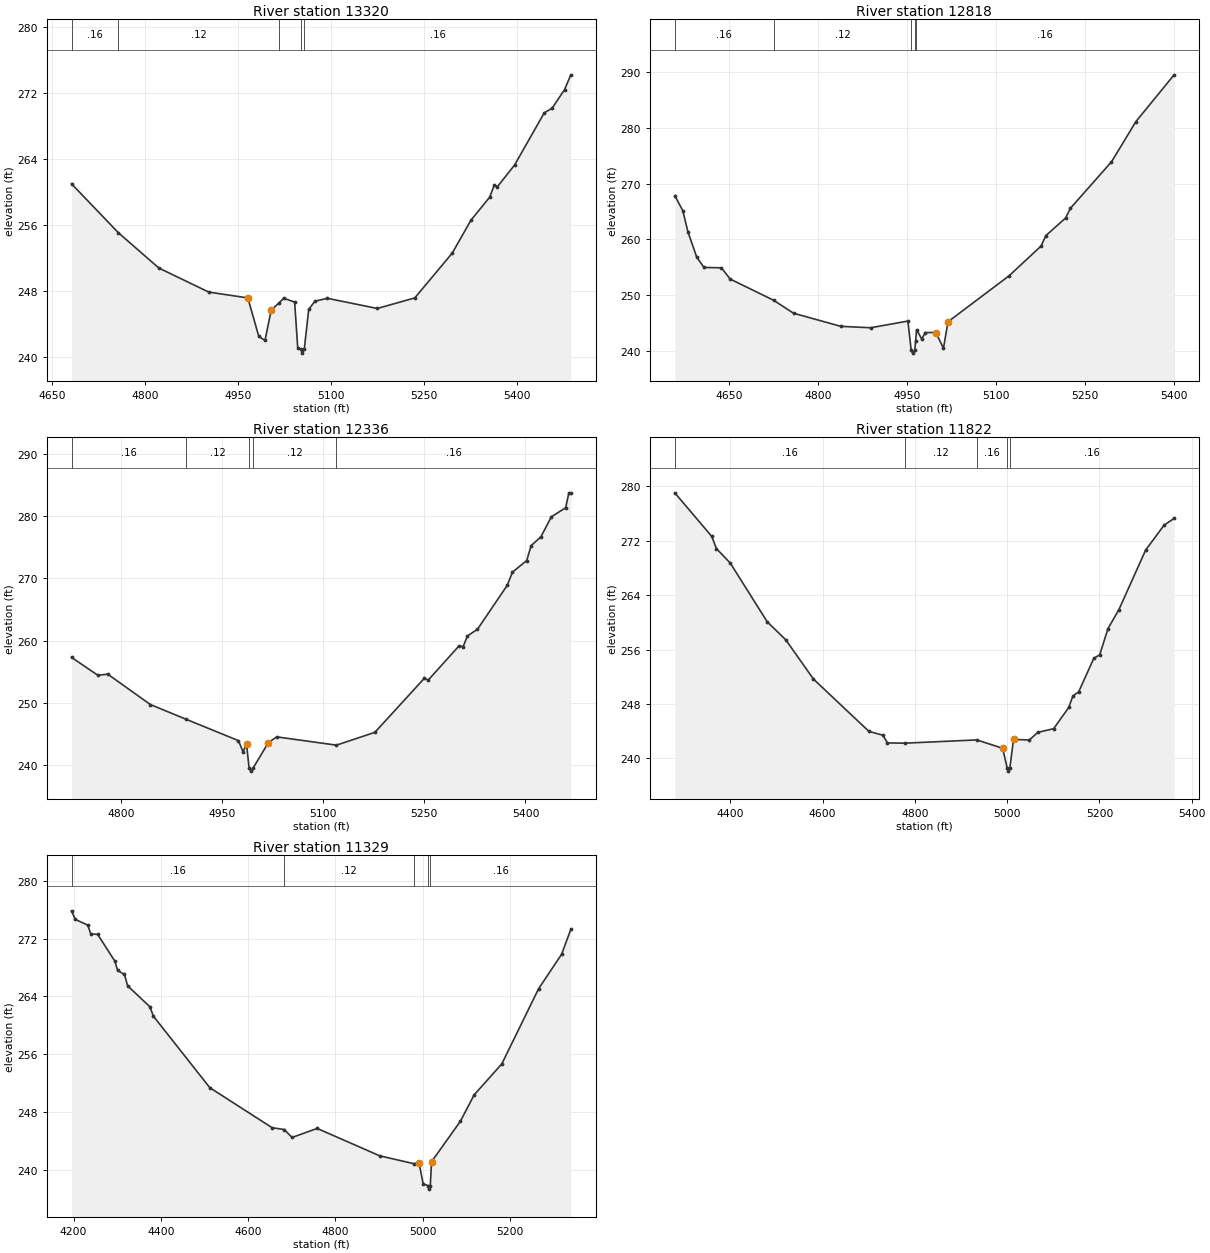
Type RM Length L Ch R = 1 ,13320   ,502,502,502
BEGIN DESCRIPTION:
RESACA CREEK 23.0
END DESCRIPTION:
XS GIS Cut Line= 3
      3686899.61     10509410.21      3686949.61     10509010.19
      3686899.62     10508610.24
#Sta/Elev= 30
  4680.9  260.99  4756.7  255.06    4822   250.8  4902.6  247.89  4965.6  247.19
  4983.3  242.54  4993.3  242.04  5003.4  245.73  5016.2  246.59  5023.6  247.15
  5041.2  246.68  5046.2  241.14  5050.8  241.01  5053.6  240.51  5056.8  241.01
  5063.9   245.8    5074  246.79  5094.1  247.14  5174.7  245.91  5235.2  247.19
  5295.7  252.61  5325.9  256.59  5356.1  259.37  5363.7  260.85  5368.7  260.65
  5396.4  263.27  5444.3  269.58  5456.9  270.13  5477.1  272.39  5487.1  274.17
#Mann= 5 ,-1 , 0
  4680.9     .16       0  4756.7     .12       0  5016.2     .16       0
  5050.8     .07       0  5056.8     .16       0
Bank Sta=4965.6,5003.4
XS Rating Curve= 0 ,0
Exp/Cntr=0.3,0.1

Type RM Length L Ch R = 1 ,12818   ,482,482,482
BEGIN DESCRIPTION:
RESACA CREEK 22.0
END DESCRIPTION:
XS GIS Cut Line= 3
      3687599.61     10509310.19      3687349.61     10508960.19
       3687449.6     10508560.22
#Sta/Elev= 30
    4558  267.87  4571.5  265.18  4580.1  261.39  4594.9  256.85  4607.2  254.96
  4636.7   254.9  4651.4  252.88  4724.7  249.07  4758.3  246.74  4838.2  244.38
  4888.6  244.13  4951.3  245.33  4956.9  240.07  4959.6  239.57  4962.9  240.07
  4964.3  241.75    4966  243.79  4974.6  242.11  4980.7  243.27  4998.4  243.27
  5011.3  240.45    5019  245.21  5122.1  253.47  5176.2  258.83    5184  260.68
  5217.5  263.86  5225.2  265.56  5294.8  273.94    5336  281.17  5400.4  289.57
#Mann= 5 ,-1 , 0
    4558     .16       0  4724.7     .12       0  4956.9     .07       0
  4962.9     .12       0  4964.3     .16       0
Bank Sta=4998.4,5019
XS Rating Curve= 0 ,0
Exp/Cntr=0.3,0.1

Type RM Length L Ch R = 1 ,12336   ,514,514,514
BEGIN DESCRIPTION:
RESACA CREEK 21.0
END DESCRIPTION:
XS GIS Cut Line= 3
      3687649.62     10509260.16      3687749.61     10509010.19
      3687499.62     10508610.21
#Sta/Elev= 30
  4726.4   257.3  4765.4  254.42  4780.2  254.59  4843.5   249.7    4897  247.31
  4974.1   243.9  4980.8  242.14  4986.2  243.28  4989.9  239.49  4992.7  238.99
  4995.9  239.49  5018.6  243.59    5031   244.5  5119.5  243.17  5176.6  245.23
  5249.8  253.91  5255.7  253.64  5301.6  259.16  5307.5  259.01    5314  260.75
  5328.8  261.81    5373  268.89  5380.7     271  5401.9  272.88  5408.4  275.26
  5423.1  276.72  5438.4  279.91  5459.7  281.37  5464.4  283.77  5467.3  283.77
#Mann= 5 ,-1 , 0
  4726.4     .16       0    4897     .12       0  4989.9     .07       0
  4995.9     .12       0  5119.5     .16       0
Bank Sta=4986.2,5018.6
XS Rating Curve= 0 ,0
Exp/Cntr=0.3,0.1

Type RM Length L Ch R = 1 ,11822   ,493,493,493
BEGIN DESCRIPTION:
RESACA CREEK 20.0
END DESCRIPTION:
XS GIS Cut Line= 3
      3688149.61     10509460.15      3688099.61     10508760.19
       3688249.6     10508410.22
#Sta/Elev= 30
  4279.4  279.04  4359.6  272.63  4369.6  270.85  4399.7  268.71  4479.9  260.07
    4520  257.43  4580.1  251.65  4700.4  243.96  4730.5   243.4  4740.5  242.27
  4777.9  242.23  4934.1  242.71  4990.2  241.48  4999.9  238.62  5002.7  238.12
  5005.9  238.62  5013.8  242.78  5048.2   242.7  5066.4  243.82  5100.8  244.36
  5133.5  247.48  5142.5  249.16  5155.2   249.8  5187.9  254.71  5200.6  255.22
  5218.7  259.09  5242.3  261.87  5300.3  270.63  5340.2  274.28  5361.9  275.28
#Mann= 5 ,-1 , 0
  4279.4     .16       0  4777.9     .12       0  4934.1     .16       0
  4999.9     .07       0  5005.9     .16       0
Bank Sta=4990.2,5013.8
XS Rating Curve= 0 ,0
Exp/Cntr=0.3,0.1

Type RM Length L Ch R = 1 ,11329   ,464,464,464
BEGIN DESCRIPTION:
RESACA CREEK 19.0
END DESCRIPTION:
XS GIS Cut Line= 3
       3688199.6     10509410.21      3688549.61     10508660.19
      3688649.61     10508360.18
#Sta/Elev= 30
  4195.3  275.84    4204  274.65  4232.4  273.87  4239.5  272.65  4255.2  272.59
  4294.6  268.88  4300.9  267.61  4316.7  267.04  4323.8  265.48    4375  262.57
  4382.9  261.28  4512.2  251.39  4654.9  245.86  4682.7  245.61  4700.6  244.51
  4758.1  245.76  4901.6  241.97  4980.2  240.88  4991.4  241.05  5000.9  238.11
  5011.3  237.87    5014  237.37  5017.3  237.87  5020.2  241.16  5086.2  246.75
  5117.8   250.4  5181.1  254.68  5265.4  265.07  5318.1  269.83  5339.2  273.26
#Mann= 5 ,-1 , 0
  4195.3     .16       0  4682.7     .12       0  4980.2     .16       0
  5011.3     .07       0  5017.3     .16       0
Bank Sta=4991.4,5020.2
XS Rating Curve= 0 ,0
Exp/Cntr=0.3,0.1