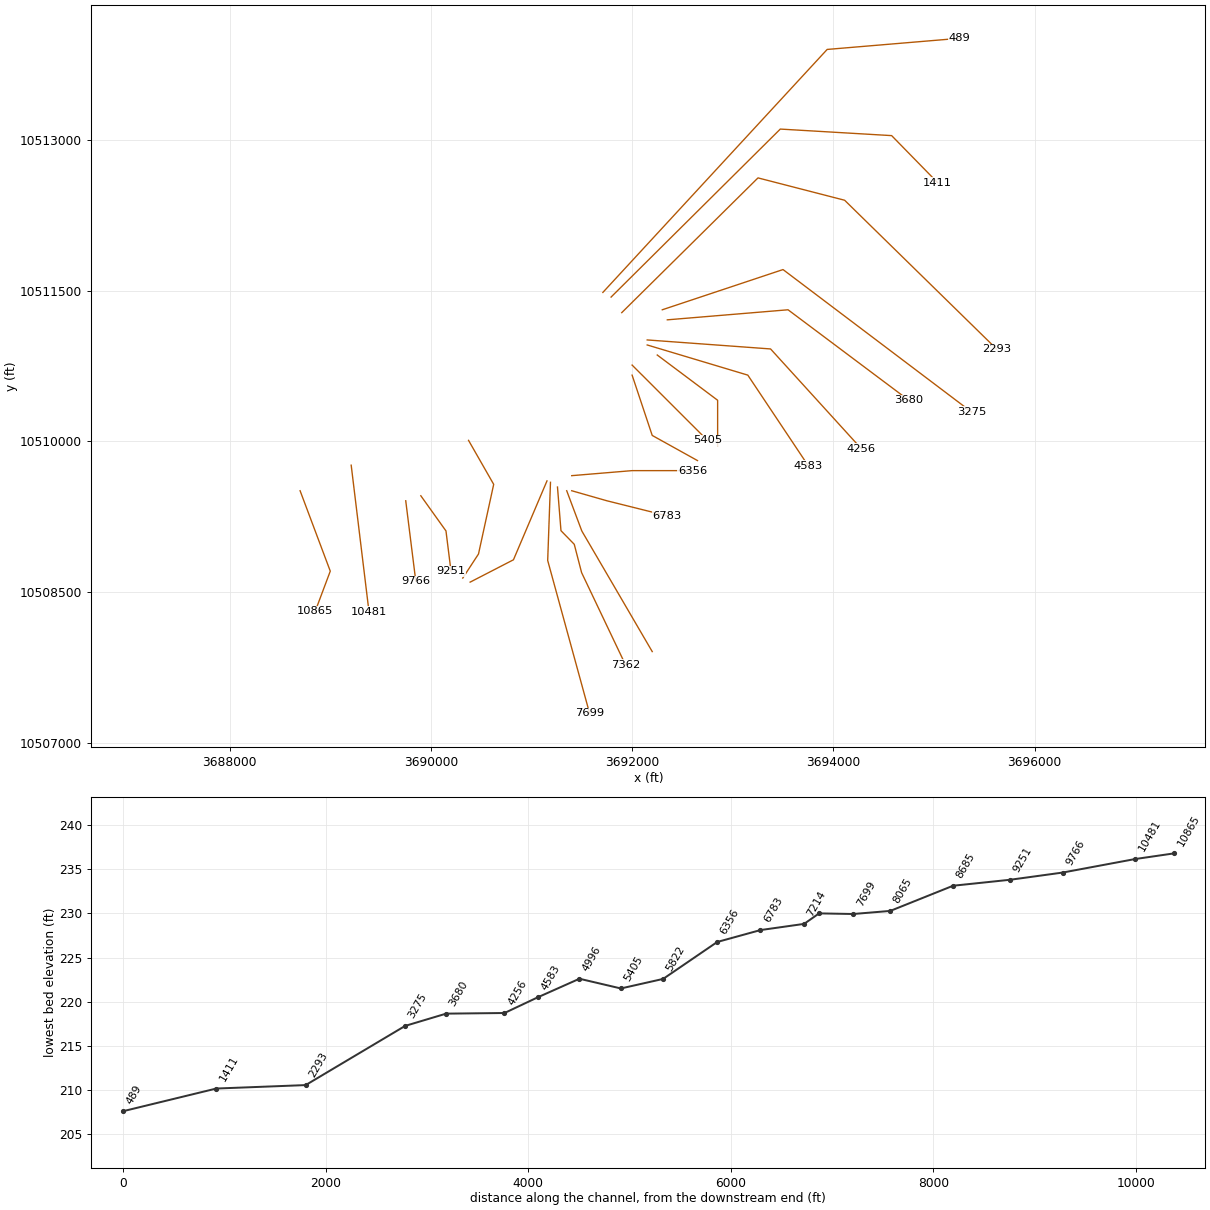
HEC-RAS study RESACA CREEK.prj: RESACA CREEK Base Level Engineering

--- RESACA CREEK.g01 (geometry) --- (continued)

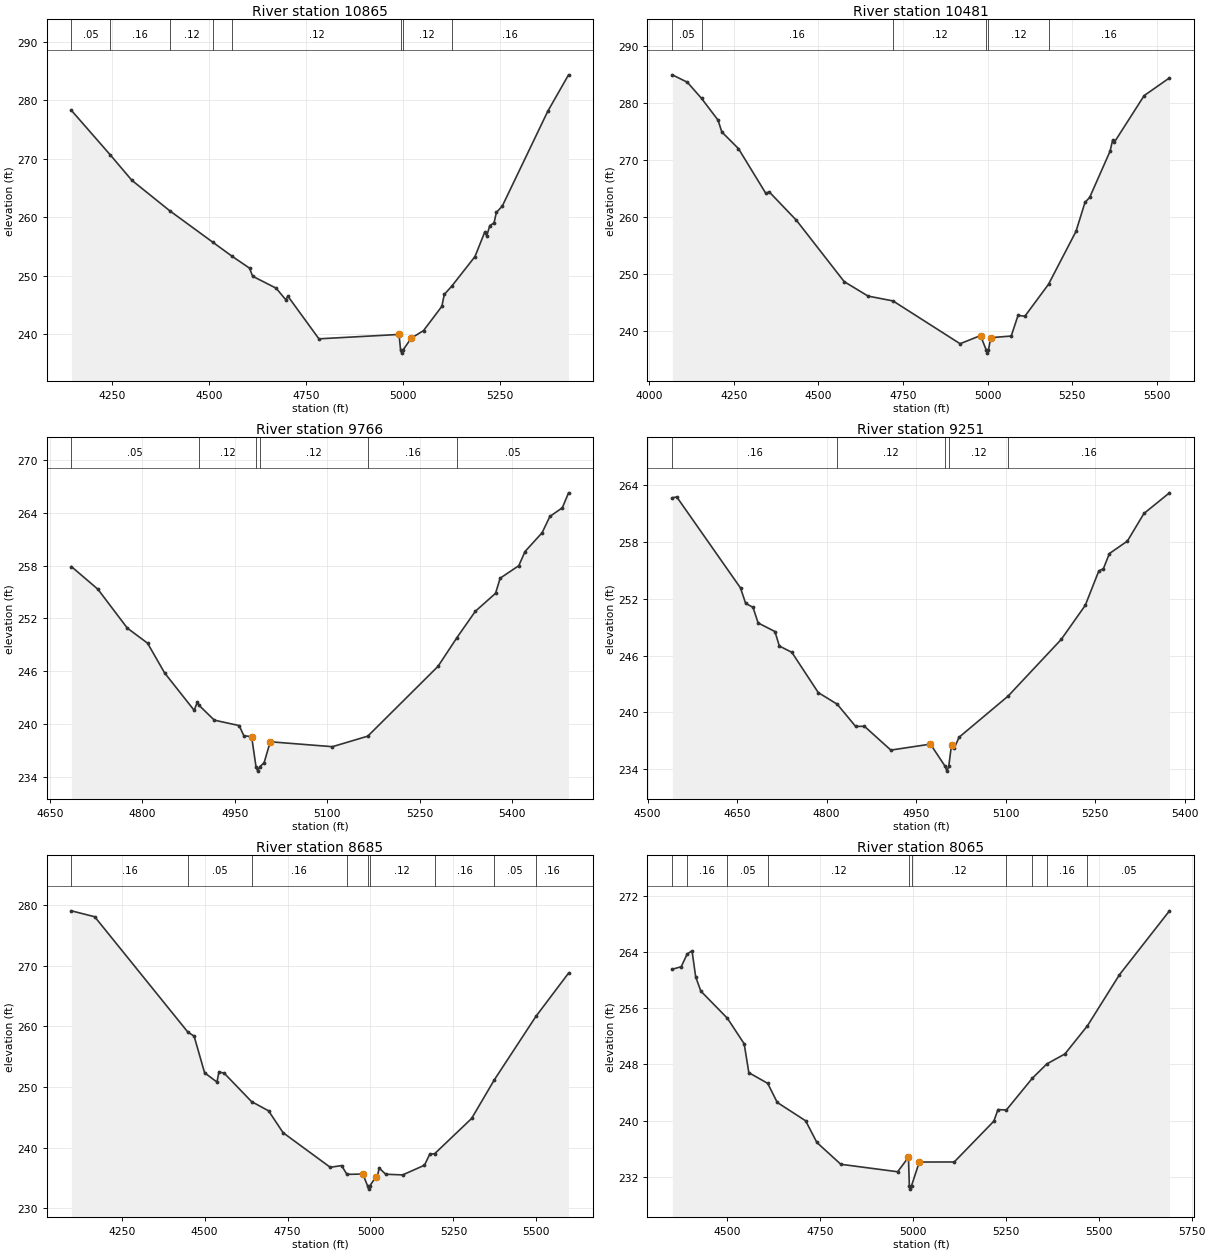
Type RM Length L Ch R = 1 ,10865   ,384,384,384
BEGIN DESCRIPTION:
RESACA CREEK 18.0
END DESCRIPTION:
XS GIS Cut Line= 3
      3688699.61     10509510.19      3688999.61     10508710.19
      3688849.61     10508310.19
#Sta/Elev= 30
  4145.4  278.24  4245.6  270.64  4301.1  266.31  4399.1  261.09  4510.9  255.68
  4560.1  253.31  4604.6   251.3  4612.6  249.92  4673.2  247.88  4698.1   245.9
  4703.4  246.52  4783.5  239.23    4990  239.98  4994.1  237.29  4996.9  236.79
  5000.1  237.29  5021.2  239.33  5053.2  240.64  5100.4  244.78  5106.6  246.81
  5125.9  248.22  5185.8  253.28  5210.7  257.42  5216.1  256.82  5224.1  258.58
  5234.8  259.01    5241  260.82  5256.1  261.89  5373.6  278.11    5427  284.31
#Mann= 8 ,-1 , 0
  4145.4     .05       0  4245.6     .16       0  4399.1     .12       0
  4510.9     .16       0  4560.1     .12       0  4994.1     .07       0
  5000.1     .12       0  5125.9     .16       0
Bank Sta=4990,5021.2
XS Rating Curve= 0 ,0
Exp/Cntr=0.3,0.1

Type RM Length L Ch R = 1 ,10481   ,715,715,715
BEGIN DESCRIPTION:
RESACA CREEK 17.0
END DESCRIPTION:
XS GIS Cut Line= 2
      3689207.46     10509764.29      3689384.54     10508306.01
#Sta/Elev= 30
  4068.1  284.98  4112.5  283.68  4154.4  280.85  4203.2  277.03  4214.3  274.96
  4263.6  272.03  4344.2   264.2  4354.3  264.45  4434.9  259.45  4575.9   248.7
  4646.4  246.16  4720.2  245.31  4918.4   237.8  4978.8  239.23    4996  236.65
  4998.7  236.15    5002  236.65  5009.1  238.86  5069.5  239.15  5089.7  242.78
  5109.8  242.62  5179.7  248.23  5260.9  257.51  5287.5   262.6  5301.2  263.46
  5361.6  271.58  5369.2  273.52  5374.3  273.16  5462.4  281.34  5537.1  284.44
#Mann= 6 ,-1 , 0
  4068.1     .05       0  4154.4     .16       0  4720.2     .12       0
    4996     .07       0    5002     .12       0  5179.7     .16       0
Bank Sta=4978.8,5009.1
XS Rating Curve= 0 ,0
Exp/Cntr=0.3,0.1

Type RM Length L Ch R = 1 ,9766    ,515,515,515
BEGIN DESCRIPTION:
RESACA CREEK 16.0
END DESCRIPTION:
XS GIS Cut Line= 3
       3689749.6     10509410.23      3689799.61     10509010.19
      3689849.61     10508610.16
#Sta/Elev= 30
  4685.1  257.89    4728  255.32  4775.8  250.89  4808.6  249.18  4836.3  245.79
  4884.2  241.54  4889.2  242.44  4891.9  242.12  4916.9  240.42  4957.2   239.8
  4964.8  238.64  4977.4  238.55  4984.5  235.12  4987.2  234.62  4990.5  235.12
  4997.6  235.56  5007.6  237.96  5108.4   237.4  5165.8   238.6  5279.7  246.54
  5310.5  249.82  5340.2   252.8    5373  254.85  5380.5  256.57  5410.7  257.99
  5420.8   259.6  5448.5  261.74  5461.1  263.59  5481.3  264.58  5491.4  266.28
#Mann= 6 ,-1 , 0
  4685.1     .05       0  4891.9     .12       0  4984.5     .07       0
  4990.5     .12       0  5165.8     .16       0  5310.5     .05       0
Bank Sta=4977.4,5007.6
XS Rating Curve= 0 ,0
Exp/Cntr=0.3,0.1

Type RM Length L Ch R = 1 ,9251    ,566,566,566
BEGIN DESCRIPTION:
RESACA CREEK 15.0
END DESCRIPTION:
XS GIS Cut Line= 3
      3689899.61     10509460.19      3690149.61     10509110.19
      3690199.61     10508710.22
#Sta/Elev= 30
  4541.4  262.66  4548.8  262.75  4655.7  253.14  4664.3  251.51  4676.6   251.1
  4685.2  249.45  4713.4  248.54  4720.8  247.01  4741.7  246.35    4786   242.1
  4817.8  240.87  4848.6  238.53  4863.4  238.54  4907.6  236.03    4974  236.66
  4998.7  234.31  5001.5  233.81  5004.7  234.31  5009.3  236.59  5014.3  236.29
  5021.9  237.38    5104  241.72  5193.2  247.71  5233.5  251.31  5256.2  254.94
  5263.8  255.16  5273.9  256.77  5304.1  258.09  5331.8     261  5374.6  263.18
#Mann= 5 ,-1 , 0
  4541.4     .16       0  4817.8     .12       0  4998.7     .07       0
  5004.7     .12       0    5104     .16       0
Bank Sta=4974,5009.3
XS Rating Curve= 0 ,0
Exp/Cntr=0.3,0.1

Type RM Length L Ch R = 1 ,8685    ,620,620,620
BEGIN DESCRIPTION:
RESACA CREEK 14.0
END DESCRIPTION:
XS GIS Cut Line= 4
      3690373.85     10510011.23      3690623.86     10509573.71
      3690472.82     10508881.01      3690316.58     10508641.45
#Sta/Elev= 30
  4098.3  279.11  4168.6  278.13  4449.8  259.05  4468.2  258.42  4499.9  252.35
  4537.2  250.82  4543.1  252.49  4558.9  252.29  4641.5  247.59  4692.7  246.07
  4736.6  242.45  4878.7  236.74  4912.9  237.02    4929  235.57  4976.8  235.62
  4991.7  233.63  4994.5  233.13  4997.7  233.63  5015.2  235.06  5020.7  235.06
  5025.9  236.63  5045.9  235.59  5097.1  235.48  5162.8  237.08    5179  238.93
  5193.3  238.97  5304.9   244.8    5373  251.15  5498.7  261.66  5597.2  268.82
#Mann= 9 ,-1 , 0
  4098.3     .16       0  4449.8     .05       0  4641.5     .16       0
    4929     .12       0  4991.7     .07       0  4997.7     .12       0
  5193.3     .16       0    5373     .05       0  5498.7     .16       0
Bank Sta=4976.8,5015.2
XS Rating Curve= 0 ,0
Exp/Cntr=0.3,0.1

Type RM Length L Ch R = 1 ,8065    ,366,366,366
BEGIN DESCRIPTION:
RESACA CREEK 13.0
END DESCRIPTION:
XS GIS Cut Line= 3
      3691153.63     10509608.07       3690820.3     10508823.36
      3690389.73     10508601.13
#Sta/Elev= 30
  4353.2  261.53  4377.2  261.89    4393  263.69  4406.2  264.15  4416.1  260.43
  4429.9  258.42  4501.4  254.56  4546.5  250.93    4559  246.83  4609.8  245.31
  4635.4   242.6  4711.8  239.99    4742  236.91  4806.4  233.81  4959.2  232.75
  4988.3   234.8  4990.7  230.78  4993.5  230.28  4996.7  230.78  5017.4  234.13
  5111.4  234.14  5217.8  239.93  5229.1  241.58  5251.7  241.53  5321.8  246.06
  5360.7  248.08  5409.1  249.49  5469.8   253.5  5555.8  260.75  5690.3  269.83
#Mann= 10 ,-1 , 0
  4353.2     .05       0    4393     .16       0  4501.4     .05       0
  4609.8     .12       0  4990.7     .07       0  4996.7     .12       0
  5251.7     .16       0  5321.8     .05       0  5360.7     .16       0
  5469.8     .05       0
Bank Sta=4988.3,5017.4
XS Rating Curve= 0 ,0
Exp/Cntr=0.3,0.1

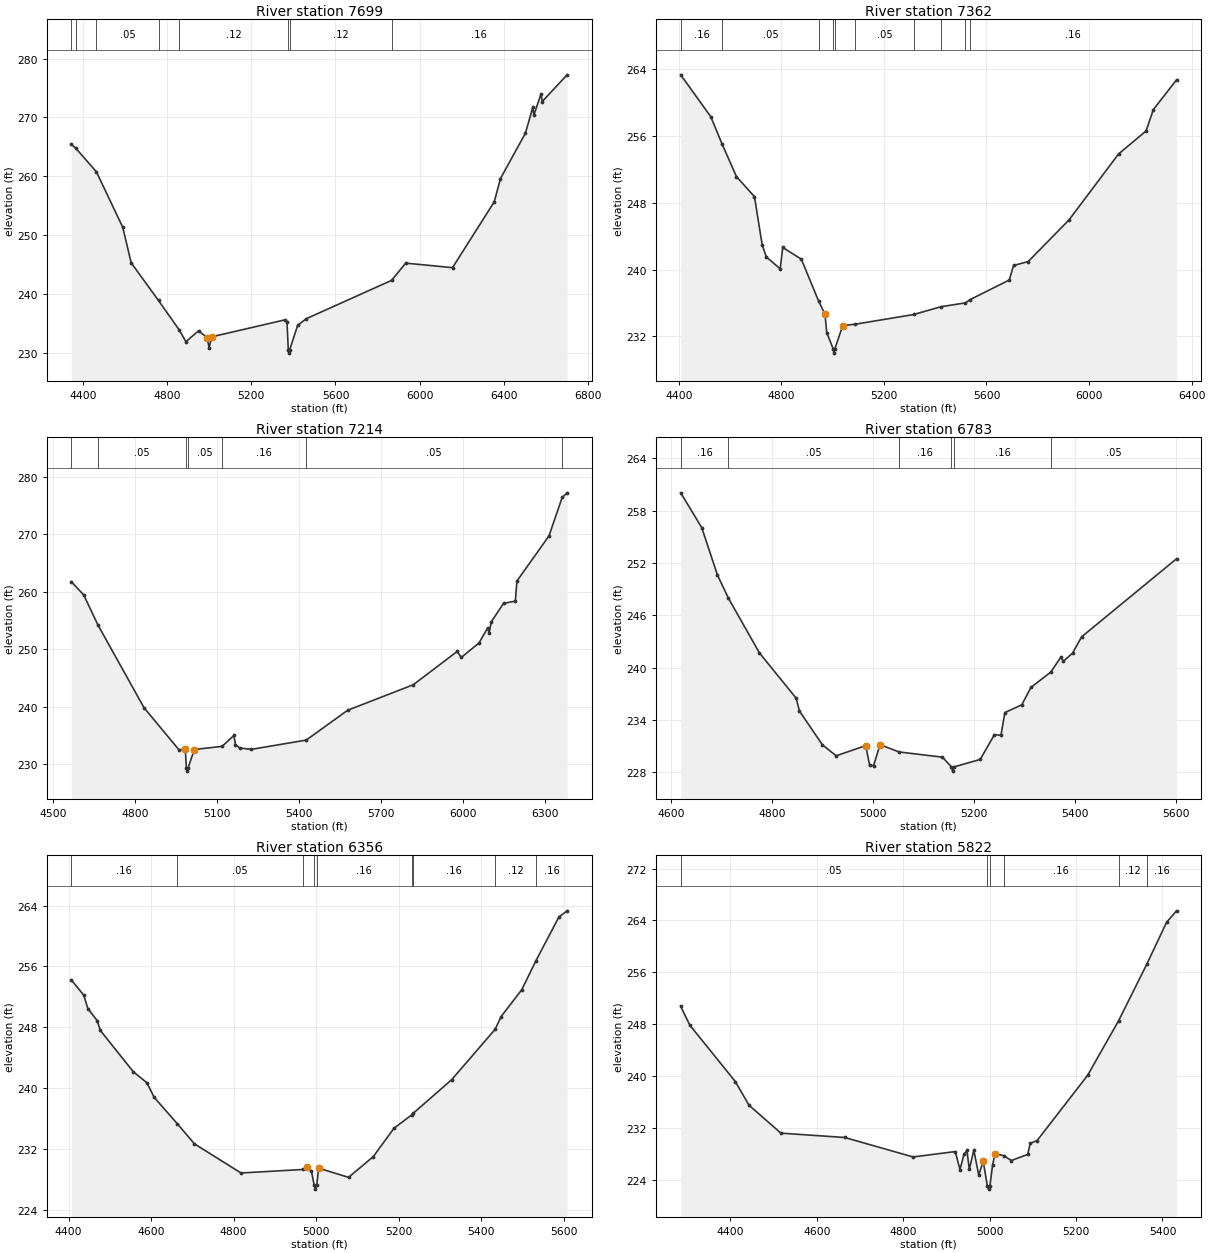
Type RM Length L Ch R = 1 ,7699    ,337,337,337
BEGIN DESCRIPTION:
RESACA CREEK 12.0
END DESCRIPTION:
XS GIS Cut Line= 3
      3691188.36     10509594.19      3691160.58     10508816.42
      3691577.24     10507295.63
#Sta/Elev= 30
  4345.3  265.42  4366.2  264.77  4464.5  260.75  4589.5  251.33  4629.5  245.29
  4759.4  238.88  4857.7  233.88  4889.6  231.88  4949.7  233.73  4989.7  232.58
  4999.7  230.88  5012.7  232.71  5358.1  235.57  5369.8  235.23  5375.9  230.43
  5378.6  229.93  5381.9  230.43  5420.3  234.66  5461.8  235.79  5866.2  242.29
  5933.6  245.23    6156  244.46  6354.3  255.66  6383.6   259.6  6502.5  267.33
    6537   271.7  6542.2  270.38  6576.7  274.01  6581.9   272.7  6700.4  277.24
#Mann= 8 ,-1 , 0
  4345.3     .05       0  4366.2      .1       0  4464.5     .05       0
  4759.4     .16       0  4857.7     .12       0  5375.9     .07       0
  5381.9     .12       0  5866.2     .16       0
Bank Sta=4989.7,5012.7
XS Rating Curve= 0 ,0
Exp/Cntr=0.3,0.1

Type RM Length L Ch R = 1 ,7362    ,148,148,148
BEGIN DESCRIPTION:
Mapping XS 45790873
END DESCRIPTION:
XS GIS Cut Line= 5
       3691257.9     10509546.87      3691292.62     10509112.86
      3691424.57     10508977.44      3691497.48     10508696.19
      3691934.78     10507776.47
#Sta/Elev= 30
  4407.6  263.28  4524.7  258.28  4569.7  254.95    4625  251.11  4695.2  248.71
  4725.3  242.95  4741.4  241.51  4795.5  240.08  4805.5  242.64  4878.1  241.23
    4945  236.25  4970.1  234.67  4977.1  232.45  5002.4   230.5  5005.1     230
  5008.4   230.5  5039.6   233.3    5087  233.45  5316.4  234.62  5422.6  235.55
    5518  236.01  5535.5  236.39  5688.8  238.74  5705.7  240.48  5762.5  240.95
  5921.5  245.92  6115.4  253.83  6222.4  256.57  6250.6  259.12    6341  262.68
#Mann= 10 ,-1 , 0
  4407.6     .16       0  4569.7     .05       0    4945     .12       0
  5002.4     .07       0  5008.4     .12       0    5087     .05       0
  5316.4     .16       0  5422.6     .12       0    5518     .05       0
  5535.5     .16       0
Bank Sta=4970.1,5039.6
XS Rating Curve= 0 ,0
Exp/Cntr=0.3,0.1

Type RM Length L Ch R = 1 ,7214    ,431,431,431
BEGIN DESCRIPTION:
RESACA CREEK 11.0
END DESCRIPTION:
XS GIS Cut Line= 3
      3691349.59     10509510.23      3691499.61     10509110.19
      3692199.61     10507910.18
#Sta/Elev= 30
  4566.1  261.76  4611.5  259.46  4663.7  254.22  4832.3  239.85  4961.3  232.47
  4983.6  232.72  4987.7  229.31  4990.4  228.81  4993.7  229.31  5016.5  232.57
  5118.6  233.12  5161.6  235.01  5167.4  233.44  5183.1  232.83  5226.1   232.6
  5426.8  234.21  5578.4   239.4    5819  243.84  5979.5  249.62  5995.2   248.6
  6059.7   251.1  6091.1  253.69  6096.9  252.86  6104.7  254.79  6149.8     258
  6192.8  258.38  6198.6  261.88    6316  269.72  6364.4  276.41  6382.6  277.22
#Mann= 7 ,-1 , 0
  4566.1     .16       0  4663.7     .05       0  4987.7     .04       0
  4993.7     .05       0  5118.6     .16       0  5426.8     .05       0
  6364.4     .16       0
Bank Sta=4983.6,5016.5
XS Rating Curve= 0 ,0
Exp/Cntr=0.3,0.1

Type RM Length L Ch R = 1 ,6783    ,427,427,427
BEGIN DESCRIPTION:
RESACA CREEK 10.0
END DESCRIPTION:
XS GIS Cut Line= 3
      3691399.58      10509510.2      3691749.61     10509410.19
       3692349.6     10509260.19
#Sta/Elev= 30
  4618.9  260.05  4660.5  256.07  4691.7  250.62  4713.4  247.96  4774.9  241.68
  4847.7  236.48  4854.2  235.01  4899.7  231.13    4927  229.87  4985.5  231.04
  4993.2   228.8    5001  228.73  5013.9  231.15  5051.6  230.31  5137.6  229.71
  5155.2  228.61  5157.9  228.11  5161.2  228.61  5212.3  229.45  5240.6   232.3
  5253.5  232.22  5261.3  234.83  5294.8  235.72  5312.8  237.71  5352.3  239.48
  5372.1  241.19  5377.2  240.72  5395.3  241.65  5413.3  243.52  5601.4  252.48
#Mann= 6 ,-1 , 0
  4618.9     .16       0  4713.4     .05       0  5051.6     .16       0
  5155.2     .03       0  5161.2     .16       0  5352.3     .05       0
Bank Sta=4985.5,5013.9
XS Rating Curve= 0 ,0
Exp/Cntr=0.3,0.1

Type RM Length L Ch R = 1 ,6356    ,534,534,534
BEGIN DESCRIPTION:
RESACA CREEK 9.0
END DESCRIPTION:
XS GIS Cut Line= 3
      3691399.62     10509660.19      3691999.61     10509710.19
      3692599.64     10509710.19
#Sta/Elev= 30
  4406.6  254.24  4436.7  252.23  4446.7  250.47  4469.3  248.89  4476.8  247.61
  4557.1  242.16  4589.7  240.74  4607.3  238.83  4663.8  235.33  4705.1  232.71
    4818  228.88  4968.1  229.34  4978.6  229.69  4988.6  229.16  4995.6  227.26
  4998.4  226.76  5001.6  227.26  5006.2  229.51  5078.7  228.31  5138.7  231.03
  5188.7  234.74  5231.5   236.5  5235.9  236.74  5328.7  241.13  5434.1  247.75
  5448.7  249.43  5498.7  252.95    5533  256.75  5588.7   262.5  5608.7  263.31
#Mann= 9 ,-1 , 0
  4406.6     .16       0  4663.8     .05       0  4968.1     .16       0
  4995.6     .07       0  5001.6     .16       0  5231.5     .12       0
  5235.9     .16       0  5434.1     .12       0    5533     .16       0
Bank Sta=4978.6,5006.2
XS Rating Curve= 0 ,0
Exp/Cntr=0.3,0.1

Type RM Length L Ch R = 1 ,5822    ,417,417,417
BEGIN DESCRIPTION:
RESACA CREEK 8.0
END DESCRIPTION:
XS GIS Cut Line= 3
      3691999.61     10510660.18      3692199.61     10510060.19
      3692649.58      10509810.2
#Sta/Elev= 30
  4285.3  250.75  4306.4  247.86  4411.8  239.15  4443.4  235.51  4517.2  231.21
  4664.8  230.54  4822.9  227.54  4920.6  228.37  4931.5  225.59  4940.6  227.92
  4947.5  228.55  4953.2  225.64  4963.5  228.61  4974.9  224.75  4985.2   226.9
  4994.8  223.08  4997.6  222.58  5000.8  223.08    5007  226.33  5012.7  228.06
  5032.9  227.73  5050.4  226.99  5088.2  227.93  5093.9  229.62  5109.9  230.07
  5226.6   240.1  5298.7  248.56  5363.7  257.25  5409.6  263.72  5432.5  265.48
#Mann= 6 ,-1 , 0
  4285.3     .05       0  4994.8     .03       0  5000.8     .05       0
  5032.9     .16       0  5298.7     .12       0  5363.7     .16       0
Bank Sta=4985.2,5012.7
XS Rating Curve= 0 ,0
Exp/Cntr=0.3,0.1

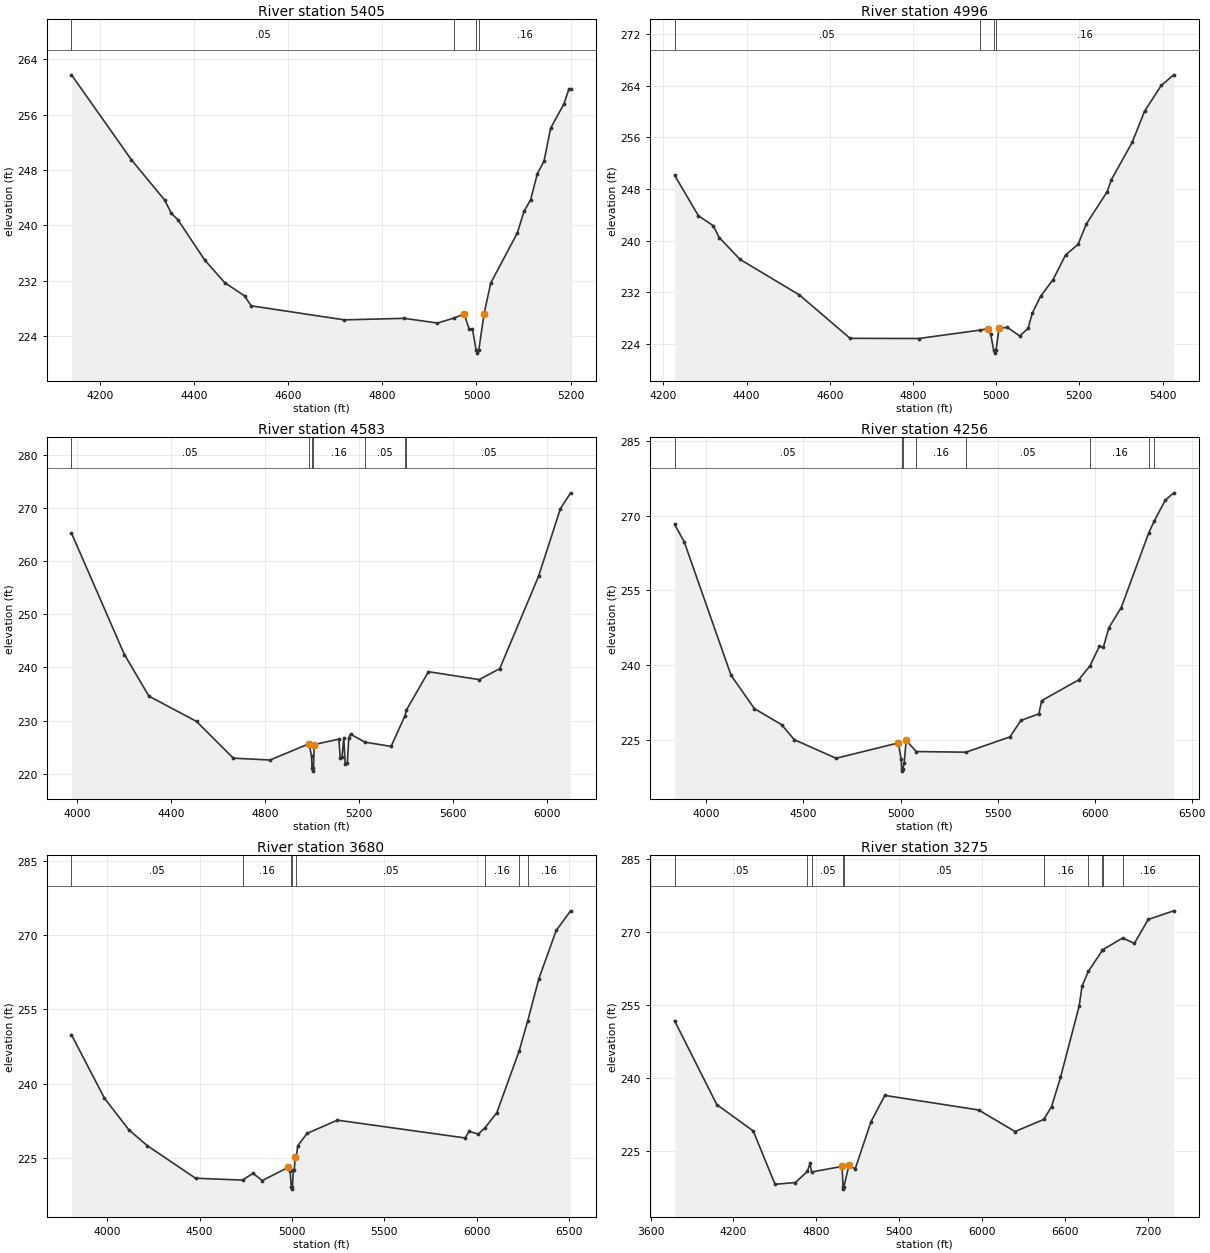
Type RM Length L Ch R = 1 ,5405    ,409,409,409
BEGIN DESCRIPTION:
RESACA CREEK 7.0
END DESCRIPTION:
XS GIS Cut Line= 3
      3691999.59     10510760.21      3692599.61     10510160.19
      3692749.62     10510010.18
#Sta/Elev= 30
  4139.4  261.74  4266.7  249.46  4337.4  243.63  4351.6  241.72  4365.7  240.77
  4422.3  234.98  4464.7  231.71  4507.1  229.78  4521.3  228.34  4719.3  226.31
  4846.5  226.53  4917.2  225.85  4952.7  226.58  4973.8  227.17  4984.4     225
  4991.5     225  4999.1     222  5001.8   221.5  5005.1     222  5016.2  227.22
  5030.4  231.64    5087  238.89  5101.1     242  5115.2  243.69  5129.4  247.45
  5143.5  249.25  5157.7  254.03  5185.9  257.54  5196.6   259.7  5200.1   259.7
#Mann= 4 ,-1 , 0
  4139.4     .05       0  4952.7     .16       0  4999.1     .07       0
  5005.1     .16       0
Bank Sta=4973.8,5016.2
XS Rating Curve= 0 ,0
Exp/Cntr=0.3,0.1

Type RM Length L Ch R = 1 ,4996    ,413,413,413
BEGIN DESCRIPTION:
RESACA CREEK 6.0
END DESCRIPTION:
XS GIS Cut Line= 3
      3692249.61     10510860.19      3692849.61     10510410.19
      3692849.61     10509960.19
#Sta/Elev= 30
  4226.9  250.13  4284.2  243.86  4319.6  242.33  4334.2  240.49  4384.2  237.11
  4526.9  231.61  4648.8  224.89  4813.4  224.86  4961.2  226.16  4979.4  226.38
  4986.9  225.56  4993.9   223.1  4996.6   222.6  4999.9   223.1  5006.9  226.44
  5026.9  226.58  5056.9  225.26  5076.9  226.45  5086.9  228.78  5106.9   231.4
  5136.9  233.98  5166.9  237.79  5196.9  239.43  5216.9  242.59  5266.9  247.58
  5276.9  249.42  5326.9   255.2  5356.9  260.04  5396.9  264.02  5426.9  265.67
#Mann= 4 ,-1 , 0
  4226.9     .05       0  4961.2     .16       0  4993.9     .07       0
  4999.9     .16       0
Bank Sta=4979.4,5006.9
XS Rating Curve= 0 ,0
Exp/Cntr=0.3,0.1

Type RM Length L Ch R = 1 ,4583    ,327,327,327
BEGIN DESCRIPTION:
RESACA CREEK 5.0
END DESCRIPTION:
XS GIS Cut Line= 3
      3692149.58      10510960.2      3693149.61     10510660.19
      3693749.59     10509760.21
#Sta/Elev= 30
  3976.4  265.27  4201.8  242.42  4306.2   234.6  4508.9  229.84  4665.5  222.93
  4822.1  222.58  4988.3  225.65  4998.7  223.33  5000.9  220.99  5003.7  220.49
  5006.9  220.99    5010  225.49  5115.1  226.51  5121.1  222.89  5128.6  223.17
  5136.1  226.77  5142.2  221.77  5151.2  222.07  5157.2  226.73  5164.7  227.45
  5226.4  225.94  5337.5  225.14  5396.5   230.9  5403.1  232.01  5496.7   239.2
    5713  237.71  5800.2  239.77  5965.4  257.13  6058.6  269.87  6102.1  272.85
#Mann= 7 ,-1 , 0
  3976.4     .05       0  4988.3     .16       0  5000.9     .07       0
  5006.9     .16       0  5226.4     .05       0  5396.5     .16       0
  5403.1     .05       0
Bank Sta=4988.3,5010
XS Rating Curve= 0 ,0
Exp/Cntr=0.3,0.1

Type RM Length L Ch R = 1 ,4256    ,576,576,576
BEGIN DESCRIPTION:
RESACA CREEK 4.0
END DESCRIPTION:
XS GIS Cut Line= 3
      3692149.63     10511010.19      3693375.86     10510920.59
      3694278.65     10509927.51
#Sta/Elev= 30
  3835.9  268.23    3886  264.68  4126.7  237.96    4247  231.26  4387.3  228.04
  4452.9  225.02  4668.1   221.3  4988.9  224.38  5003.1  221.11    5006  219.22
  5008.8  218.72    5012  219.22    5019  220.44  5029.1  224.88    5081  222.65
  5337.3  222.52  5564.1  225.59  5620.2   228.9  5712.8   230.2    5727  232.85
  5917.5  237.02  5976.8  239.88  6024.3  243.75  6045.2   243.6  6073.6  247.49
  6137.1  251.53  6279.5  266.57  6307.5  268.92  6363.5  273.03  6407.5  274.55
#Mann= 8 ,-1 , 0
  3835.9     .05       0    5006     .03       0    5012     .05       0
    5081     .16       0  5337.3     .05       0  5976.8     .16       0
  6279.5     .12       0  6307.5     .16       0
Bank Sta=4988.9,5029.1
XS Rating Curve= 0 ,0
Exp/Cntr=0.3,0.1

Type RM Length L Ch R = 1 ,3680    ,405,405,405
BEGIN DESCRIPTION:
RESACA CREEK 3.0
END DESCRIPTION:
XS GIS Cut Line= 3
      3692349.63     10511210.19      3693549.61     10511310.19
      3694749.58     10510410.21
#Sta/Elev= 30
  3805.5  249.86  3983.6  237.06  4116.6  230.63  4216.9  227.42  4477.8  220.85
  4732.2  220.48  4788.9  221.85  4839.1  220.38  4979.5  223.05  4989.6  222.35
  4996.6  219.15  4999.4  218.65  5002.6  219.15  5007.1  222.57  5012.8  222.57
  5016.9  225.11  5022.7  225.08  5031.5  227.43  5081.5  229.91  5246.1   232.6
  5937.8     229  5959.6  230.32  6009.6  229.79  6044.9  231.02  6109.6  234.09
  6230.4  246.55  6276.2  252.55  6337.8  261.22  6431.5  270.96  6509.6  274.93
#Mann= 8 ,-1 , 0
  3805.5     .05       0  4732.2     .16       0  4996.6     .07       0
  5002.6     .16       0  5022.7     .05       0  6044.9     .16       0
  6230.4     .12       0  6276.2     .16       0
Bank Sta=4979.5,5016.9
XS Rating Curve= 0 ,0
Exp/Cntr=0.3,0.1

Type RM Length L Ch R = 1 ,3275    ,982,982,982
BEGIN DESCRIPTION:
RESACA CREEK 2.0
END DESCRIPTION:
XS GIS Cut Line= 3
      3692299.64      10511310.2      3693499.61     10511710.19
      3695372.61     10510294.19
#Sta/Elev= 30
    3774  251.84  4079.7  234.62  4343.2  229.21  4501.3  218.25  4648.9  218.62
    4735  220.89  4754.3  222.57    4766  220.78  4986.2  221.93  4993.7  217.76
  4996.5  217.26  4999.7  217.76  5036.2  222.17  5081.5  221.43    5196  231.13
  5295.9  236.51  5974.3  233.52  6238.6  229.09  6446.8  231.58  6502.9  234.22
  6567.4   240.2  6702.6  254.87  6723.5  258.97  6768.7  261.97  6870.8  266.32
  6873.8  266.43  7017.6  268.84  7102.2  267.73  7202.1  272.64  7386.9  274.42
#Mann= 10 ,-1 , 0
    3774     .05       0    4735     .16       0    4766     .05       0
  4993.7     .03       0  4999.7     .05       0  6446.8     .16       0
  6768.7     .12       0  6870.8     .16       0  6873.8     .12       0
  7017.6     .16       0
Bank Sta=4986.2,5036.2
XS Rating Curve= 0 ,0
Exp/Cntr=0.3,0.1

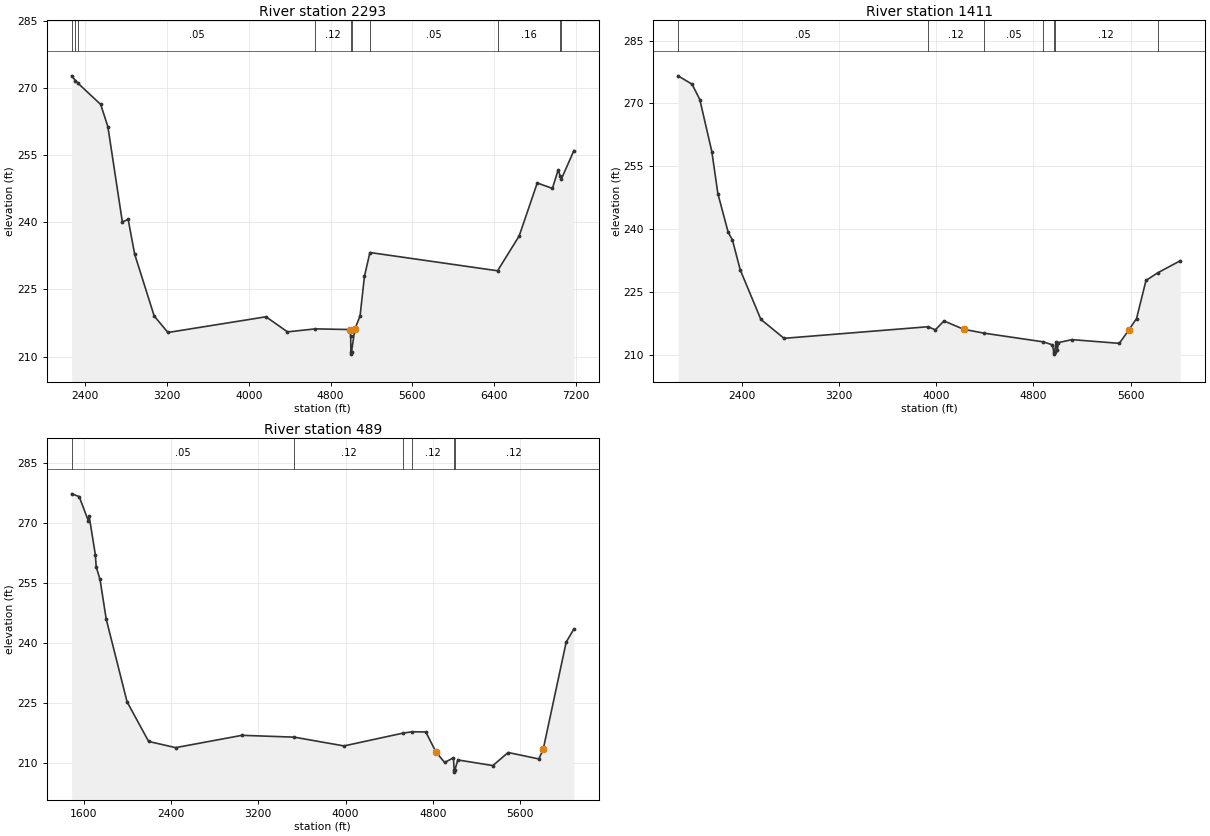
Type RM Length L Ch R = 1 ,2293    ,882,882,882
BEGIN DESCRIPTION:
Mapping XS e7a32ecf
END DESCRIPTION:
XS GIS Cut Line= 4
      3691896.68     10511281.68      3693250.86     10512621.98
      3694111.97     10512399.75      3695623.86     10510918.24
#Sta/Elev= 30
  2267.2   272.7  2304.8  271.64  2327.5  271.08  2551.1  266.31  2621.8  261.32
  2763.2  240.05  2819.8  240.67  2883.4  232.89  3074.3  219.08  3208.7  215.39
  4168.1   218.9  4377.8  215.53  4650.8   216.2  4987.1  216.05  4996.2  214.57
  4998.3  211.06  5001.1  210.56  5004.3  211.06  5036.8  216.14  5088.1  219.11
  5130.5  227.91  5184.3  233.25  6432.8  229.17  6643.8  236.94  6820.7  248.77
  6969.1  247.57  7025.7  251.73  7043.9  250.38    7056  249.62  7178.6  255.98
#Mann= 10 ,-1 , 0
  2267.2     .05       0  2304.8     .16       0  2327.5     .05       0
  4650.8     .12       0  4998.3     .07       0  5004.3     .12       0
  5184.3     .05       0  6432.8     .16       0  7043.9     .12       0
    7056     .16       0
Bank Sta=4987.1,5036.8
XS Rating Curve= 0 ,0
Exp/Cntr=0.3,0.1

Type RM Length L Ch R = 1 ,1411    ,922,922,922
BEGIN DESCRIPTION:
Mapping XS 1ba98e0c
END DESCRIPTION:
XS GIS Cut Line= 4
      3691790.65     10511436.67      3693472.48     10513107.65
      3694579.25     10513042.55      3695034.77     10512576.19
#Sta/Elev= 30
  1877.1  276.59    1992  274.58  2055.6  270.92  2154.6  258.49  2204.1  248.49
    2289  239.23  2324.3  237.39    2388  230.28  2557.7  218.47  2748.6  213.94
  3933.6  216.71  3993.1  215.96  4063.8  218.09  4226.5   216.1  4392.4  215.18
  4881.2   213.1  4956.3  212.38  4968.1  210.67  4970.9  210.17  4974.1  210.67
  4986.3  213.03  4996.3  211.07  5006.3  212.92  5116.5  213.63    5507  212.74
  5584.7  215.93  5648.5  218.67  5726.2  227.75  5821.8  229.56  6008.5  232.46
#Mann= 7 ,-1 , 0
  1877.1     .05       0  3933.6     .12       0  4392.4     .05       0
  4881.2     .12       0  4968.1     .07       0  4974.1     .12       0
  5821.8     .16       0
Bank Sta=4226.5,5584.7
XS Rating Curve= 0 ,0
Exp/Cntr=0.3,0.1

Type RM Length L Ch R = 1 ,489     ,0,0,0
BEGIN DESCRIPTION:
RESACA CREEK 1.0
END DESCRIPTION:
XS GIS Cut Line= 3
      3691709.17     10511483.06      3693938.36     10513899.75
       3695249.6     10514010.19
#Sta/Elev= 30
  1489.2  277.37  1558.2  276.68  1643.2  270.54    1650  271.71  1706.7  262.07
  1714.1  259.08  1749.3   255.9    1806  245.97  1997.1  225.23    2195  215.29
  2442.8  213.74  3051.2  216.83  3528.9  216.37  3985.8  214.17  4530.5   217.4
  4612.2  217.72    4736  217.67  4828.4  212.67  4908.7  210.02    4989  211.19
    4996   208.1  4998.8   207.6    5002   208.1  5029.2  210.66  5350.3  209.24
  5490.8  212.52  5771.8  210.91  5811.9  213.31  6022.7  240.18  6092.9  243.48
#Mann= 6 ,-1 , 0
  1489.2     .05       0  3528.9     .12       0  4530.5     .16       0
  4612.2     .12       0    4996     .07       0    5002     .12       0
Bank Sta=4828.4,5811.9
XS Rating Curve= 0 ,0
Exp/Cntr=0.3,0.1

Chan Stop Cuts=-1
Use User Specified Reach Order=0
Composite Channel Slope=5