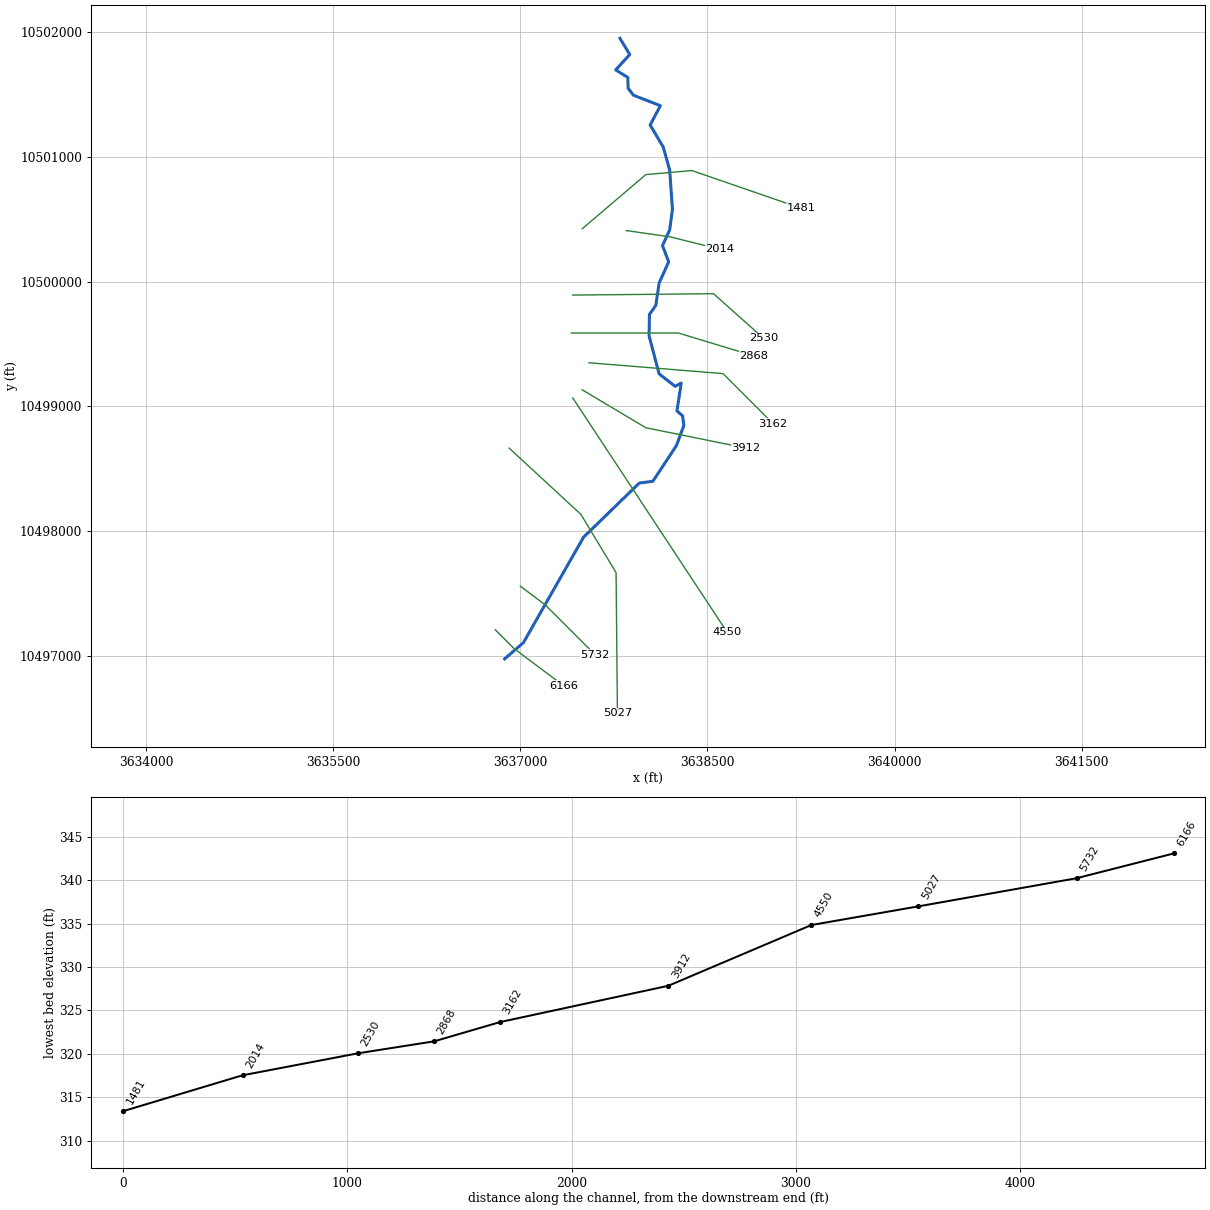
--- RIGHT BRANCH.prj (project) ---

Proj Title=RIGHT BRANCH Base Level Engineering
Current Plan=p01
Default Exp/Contr=0.3,0.1
English Units
Geom File=g01
Flow File=f01
Plan File=p01
BEGIN DESCRIPTION:
RIGHT BRANCH
END DESCRIPTION:

--- RIGHT BRANCH.p01 (plan) ---

Plan Title=Multiple Run
Short Identifier=Multiple
Geom File=g01
Flow File=f01
Subcritical Flow
K Sum by GR= 0
Std Step Tol= 0.01
Critical Tol= 0.01
Num of Std Step Trials= 20
Max Error Tol= 0.3
Flow Tol Ratio= 0.001
Split Flow NTrial= 30
Split Flow Tol= 0.02
Split Flow Ratio= 0.02
Log Output Level= 0
Friction Slope Method= 1
Unsteady Friction Slope Method= 2
Unsteady Bridges Friction Slope Method= 1
Parabolic Critical Depth
Global Vel Dist=  1 , 1 , 1
Global Log Level= 0
CheckData=True
Encroach Param= -1, 0, 0, 0
BEGIN DESCRIPTION:
Multiple Run
END DESCRIPTION:

--- RIGHT BRANCH.f01 (steady flow) ---

Flow Title=Multiple
Number of Profiles=7
Profile Names=10-year,25-year,50-year,1pct_min,100-year,1pct_plu,500-year
River Rch & RM= RIGHT BRANCH,Reach-1,6166
    2150    3096    3915    3608    4879    6599    7558
Boundary for River Rch & Prof#=RIGHT BRANCH,Reach-1,1
Up Type=0
Dn Type=3
Dn Slope=0.005
Boundary for River Rch & Prof#=RIGHT BRANCH,Reach-1,2
Up Type=0
Dn Type=3
Dn Slope=0.005
Boundary for River Rch & Prof#=RIGHT BRANCH,Reach-1,3
Up Type=0
Dn Type=3
Dn Slope=0.005
Boundary for River Rch & Prof#=RIGHT BRANCH,Reach-1,4
Up Type=0
Dn Type=3
Dn Slope=0.005
Boundary for River Rch & Prof#=RIGHT BRANCH,Reach-1,5
Up Type=0
Dn Type=3
Dn Slope=0.005
Boundary for River Rch & Prof#=RIGHT BRANCH,Reach-1,6
Up Type=0
Dn Type=3
Dn Slope=0.005
Boundary for River Rch & Prof#=RIGHT BRANCH,Reach-1,7
Up Type=0
Dn Type=3
Dn Slope=0.005

--- RIGHT BRANCH.g01 (geometry) ---

Geom Title=Existing Conditions

River Reach=RIGHT BRANCH,Reach-1
Reach XY= 30
      3636874.25     10496977.00      3637025.00     10497107.00
      3637506.75     10497952.00      3637953.50     10498386.00
      3638063.00     10498401.00      3638251.00     10498686.00
      3638310.75     10498847.00      3638301.00     10498925.00
      3638255.50     10498964.00      3638289.75     10499188.00
      3638241.50     10499161.00      3638112.25     10499262.00
      3638032.25     10499566.00      3638035.25     10499738.00
      3638086.25     10499810.00      3638112.50     10499989.00
      3638189.00     10500159.00      3638139.75     10500290.00
      3638197.25     10500415.00      3638219.50     10500580.00
      3638197.25     10500895.00      3638146.00     10501079.00
      3638041.00     10501256.00      3638122.50     10501411.00
      3637907.00     10501495.00      3637863.75     10501551.00
      3637862.50     10501637.00      3637764.75     10501698.00
      3637877.25     10501821.00      3637799.00     10501951.00

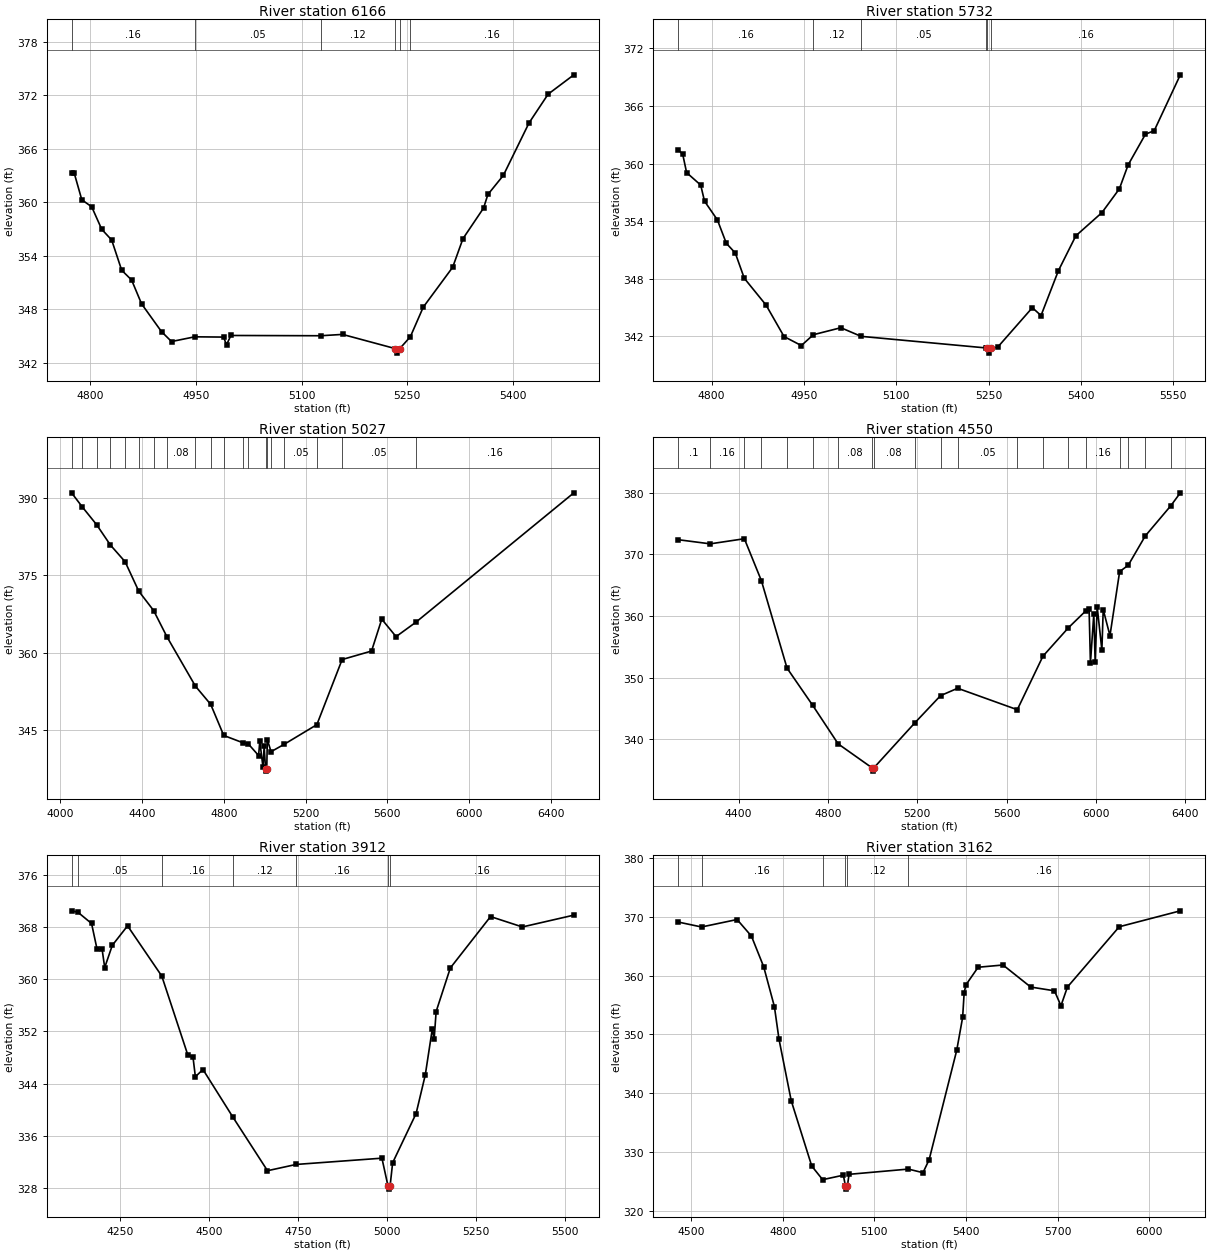
Type RM Length L Ch R = 1,6166,434,434,434
BEGIN DESCRIPTION:
RIGHT BRANCH 11.0
END DESCRIPTION:
XS GIS Cut Line= 3
      3636799.58     10497210.22      3636949.61     10497060.19
      3637349.63     10496760.17
#Sta/Elev= 30
  4774.0  363.24  4777.6  363.24  4788.2  360.29  4802.3  359.49  4816.5  356.97
  4830.6  355.77  4844.8  352.38  4858.9  351.28  4873.0  348.61  4901.3  345.49
  4915.5  344.38  4948.4  344.91  4989.3  344.88  4993.5  344.01  4999.7  345.06
  5127.0  345.03  5158.1  345.18  5233.2  343.58  5235.9  343.08  5239.2  343.58
  5254.3  344.92  5272.6  348.24  5314.3  352.71  5328.9  355.92  5358.1  359.35
  5364.3  360.88  5386.2  363.02  5422.6  368.90  5449.7  372.13  5486.2  374.30
#Mann=6,-1,0
  4774.0    0.16       0  4948.4    0.05       0  5127.0    0.12       0
  5233.2    0.03       0  5239.2    0.12       0  5254.3    0.16       0
Bank Sta=5233.2,5239.2
Exp/Cntr=0.3,0.1

Type RM Length L Ch R = 1,5732,705,705,705
BEGIN DESCRIPTION:
RIGHT BRANCH 10.0
END DESCRIPTION:
XS GIS Cut Line= 3
      3636999.59     10497560.20      3637199.61     10497410.19
      3637599.60     10497010.19
#Sta/Elev= 30
  4745.7  361.44  4753.0  360.96  4759.3  359.05  4782.2  357.75  4788.4  356.07
  4809.3  354.12  4823.8  351.68  4838.4  350.66  4853.0  348.03  4888.4  345.23
  4917.6  341.95  4945.7  341.01  4965.2  342.14  5009.9  342.87  5042.8  341.97
  5246.0  340.76  5247.3  340.72  5250.0  340.22  5253.3  340.72  5264.4  340.82
  5321.0  344.96  5335.1  344.14  5363.4  348.83  5391.7  352.46  5434.1  354.88
  5462.4  357.36  5476.6  359.85  5504.8  363.06  5519.0  363.42  5561.4  369.25
#Mann=6,-1,0
  4745.7    0.16       0  4965.2    0.12       0  5042.8    0.05       0
  5246.0    0.16       0  5247.3    0.07       0  5253.3    0.16       0
Bank Sta=5247.3,5253.3
Exp/Cntr=0.3,0.1

Type RM Length L Ch R = 1,5027,477,477,477
BEGIN DESCRIPTION:
RIGHT BRANCH 9.0
END DESCRIPTION:
XS GIS Cut Line= 4
      3636910.43     10498666.98      3637485.54     10498135.28
      3637767.66     10497668.70      3637778.51     10496540.23
#Sta/Elev= 30
  4055.6  391.00  4105.9  388.37  4176.8  384.88  4244.6  380.91  4316.5  377.67
  4383.3  371.95  4456.2  368.18  4522.0  363.03  4660.7  353.49  4735.5  349.95
  4799.3  343.91  4892.0  342.51  4918.9  342.29  4969.9  340.01  4975.7  342.78
  4991.3  337.77  4997.1  341.81  5003.8  337.48  5006.5  336.98  5009.8  337.48
  5012.6  343.07  5031.0  340.76  5096.3  342.22  5255.0  346.01  5378.7  358.66
  5522.6  360.31  5572.6  366.50  5642.6  363.11  5740.3  365.93  6512.6  391.05
#Mann=20,-1,0
  4055.6    0.05       0  4105.9    0.16       0  4176.8    0.05       0
  4244.6    0.16       0  4316.5    0.08       0  4383.3    0.16       0
  4456.2     0.1       0  4522.0    0.08       0  4660.7    0.05       0
  4735.5    0.08       0  4799.3    0.05       0  4892.0    0.08       0
  4918.9    0.05       0  5003.8    0.04       0  5009.8    0.05       0
  5031.0    0.08       0  5096.3    0.05       0  5255.0    0.08       0
  5378.7    0.05       0  5740.3    0.16       0
Bank Sta=5003.8,5009.8
Exp/Cntr=0.3,0.1

Type RM Length L Ch R = 1,4550,638,638,638
BEGIN DESCRIPTION:
RIGHT BRANCH 8.0
END DESCRIPTION:
XS GIS Cut Line= 2
      3637420.46     10499068.40      3638657.39     10497191.31
#Sta/Elev= 30
  4130.0  372.39  4273.3  371.72  4426.1  372.55  4502.4  365.73  4617.1  351.55
  4731.6  345.53  4846.1  339.25  4999.1  335.33  5001.9  334.83  5005.1  335.33
  5189.7  342.68  5304.4  347.08  5381.0  348.28  5648.1  344.80  5763.0  353.49
  5877.2  358.11  5953.9  360.81  5969.6  361.10  5975.6  352.36  5990.7  360.35
  5996.7  352.60  6005.8  361.51  6026.8  354.47  6032.8  361.05  6063.0  356.82
  6106.3  367.21  6144.9  368.25  6220.9  372.99  6335.4  377.90  6378.0  380.00
#Mann=20,-1,0
  4130.0     0.1       0  4273.3    0.16       0  4426.1    0.16       0
  4502.4    0.05       0  4617.1    0.05       0  4731.6    0.08       0
  4846.1    0.08       0  4999.1    0.07       0  5005.1    0.08       0
  5189.7    0.05       0  5304.4    0.08       0  5381.0    0.05       0
  5648.1    0.08       0  5763.0    0.16       0  5877.2    0.05       0
  5953.9    0.16       0  6106.3    0.05       0  6144.9    0.16       0
  6220.9    0.05       0  6335.4    0.08       0
Bank Sta=4999.1,5005.1
Exp/Cntr=0.3,0.1

Type RM Length L Ch R = 1,3912,750,750,750
BEGIN DESCRIPTION:
RIGHT BRANCH 7.0
END DESCRIPTION:
XS GIS Cut Line= 3
      3637496.42     10499133.53      3638006.38     10498829.72
      3638809.35     10498666.96
#Sta/Elev= 30
  4112.9  370.45  4130.3  370.23  4168.6  368.51  4184.2  364.54  4198.1  364.62
  4205.6  361.77  4227.0  365.17  4269.9  368.15  4366.2  360.46  4439.3  348.40
  4454.2  347.99  4460.7  345.04  4482.1  346.15  4565.7  338.91  4663.7  330.65
  4744.3  331.61  4985.7  332.57  5002.7  328.33  5005.4  327.83  5008.7  328.33
  5015.9  331.87  5081.9  339.41  5107.7  345.31  5127.5  352.37  5132.6  350.76
  5138.3  355.03  5178.2  361.70  5291.4  369.57  5380.9  367.98  5525.8  369.79
#Mann=7,-1,0
  4112.9     0.1       0  4130.3    0.05       0  4366.2    0.16       0
  4565.7    0.12       0  4744.3    0.16       0  5002.7    0.07       0
  5008.7    0.16       0
Bank Sta=5002.7,5008.7
Exp/Cntr=0.3,0.1

Type RM Length L Ch R = 1,3162,294,294,294
BEGIN DESCRIPTION:
RIGHT BRANCH 5.0
END DESCRIPTION:
XS GIS Cut Line= 3
      3637550.68     10499350.55      3638624.87     10499263.75
      3639025.45     10498863.17
#Sta/Elev= 30
  4457.7  369.10  4534.0  368.26  4650.4  369.53  4697.4  366.71  4737.5  361.50
  4772.6  354.72  4787.7  349.15  4827.8  338.68  4894.9  327.58  4930.6  325.26
  4998.4  326.02  5005.4  324.15  5008.2  323.65  5011.4  324.15  5017.2  326.17
  5211.2  327.06  5259.2  326.45  5279.3  328.65  5369.6  347.25  5389.0  352.86
  5394.0  357.03  5399.7  358.40  5439.8  361.41  5521.3  361.79  5612.0  358.04
  5689.8  357.40  5711.0  354.85  5732.2  358.04  5901.9  368.30  6101.9  371.01
#Mann=6,-1,0
  4457.7    0.05       0  4534.0    0.16       0  4930.6    0.12       0
  5005.4    0.07       0  5011.4    0.12       0  5211.2    0.16       0
Bank Sta=5005.4,5011.4
Exp/Cntr=0.3,0.1

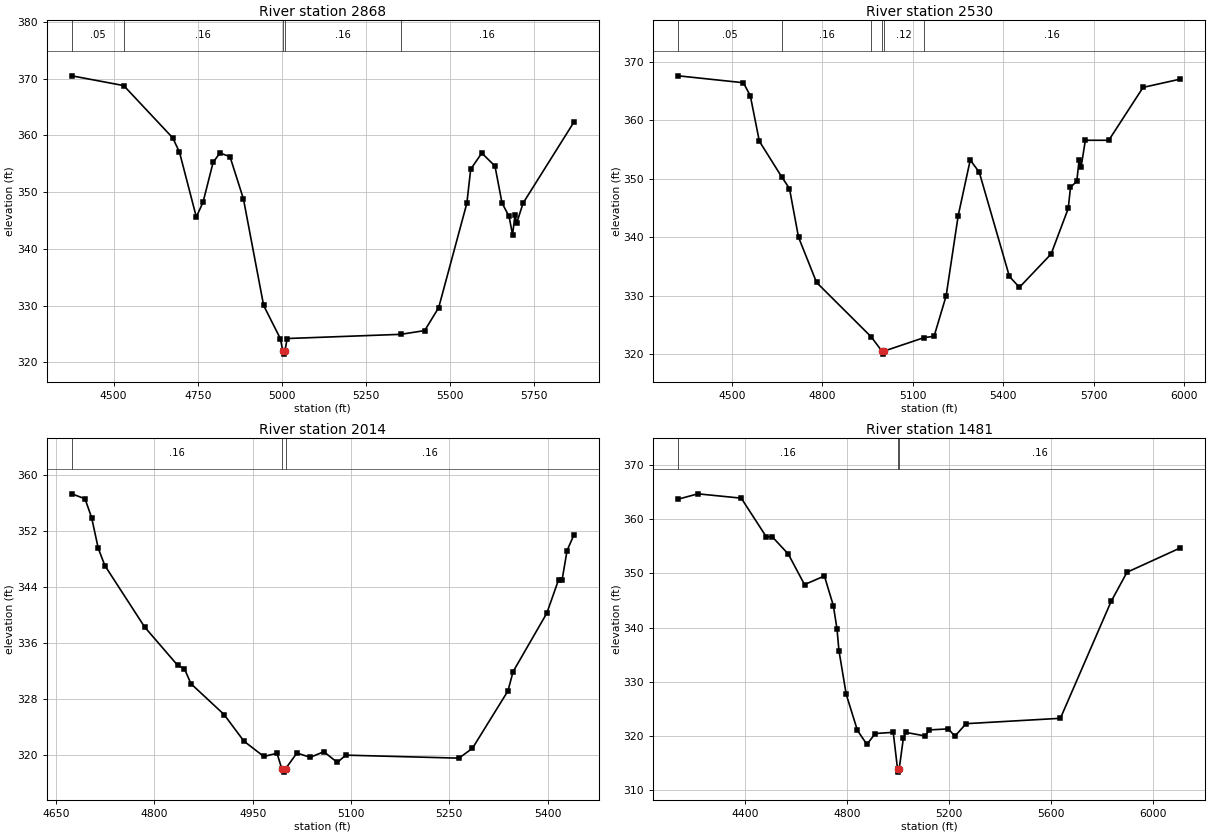
Type RM Length L Ch R = 1,2868,338,338,338
BEGIN DESCRIPTION:
RIGHT BRANCH 4.0
END DESCRIPTION:
XS GIS Cut Line= 3
      3637409.60     10499589.27      3638266.79     10499589.27
      3638873.85     10499404.99
#Sta/Elev= 30
  4375.8  370.49  4530.1  368.77  4675.8  359.55  4695.8  357.03  4745.8  345.61
  4765.8  348.21  4795.8  355.25  4815.8  356.88  4845.8  356.25  4885.8  348.79
  4945.8  330.01  4995.8  324.12  5002.8  321.93  5005.6  321.43  5008.8  321.93
  5015.8  324.18  5353.4  324.92  5424.2  325.58  5465.8  329.62  5549.5  348.02
  5561.0  354.03  5593.9  356.88  5633.1  354.58  5654.0  348.07  5674.9  345.72
  5685.3  342.48  5692.6  345.96  5697.8  344.57  5716.7  348.06  5867.4  362.31
#Mann=5,-1,0
  4375.8    0.05       0  4530.1    0.16       0  5002.8    0.07       0
  5008.8    0.16       0  5353.4    0.16       0
Bank Sta=5002.8,5008.8
Exp/Cntr=0.3,0.1

Type RM Length L Ch R = 1,2530,516,516,516
BEGIN DESCRIPTION:
RIGHT BRANCH 3.0
END DESCRIPTION:
XS GIS Cut Line= 3
      3637420.42     10499893.09      3638548.91     10499903.94
      3638950.38     10499545.87
#Sta/Elev= 30
  4321.6  367.60  4537.8  366.42  4560.8  364.20  4590.8  356.43  4665.0  350.34
  4690.8  348.35  4720.8  340.04  4780.8  332.30  4962.5  322.99  4997.8  320.56
  5000.6  320.06  5003.8  320.56  5137.5  322.88  5170.8  323.11  5210.8  330.00
  5250.8  343.70  5290.8  353.22  5320.8  351.13  5420.8  333.33  5454.0  331.47
  5559.2  337.16  5616.1  344.94  5623.6  348.56  5644.5  349.58  5652.0  353.18
  5658.7  351.99  5672.9  356.59  5750.7  356.59  5864.4  365.62  5988.1  367.04
#Mann=6,-1,0
  4321.6    0.05       0  4665.0    0.16       0  4962.5    0.12       0
  4997.8    0.07       0  5003.8    0.12       0  5137.5    0.16       0
Bank Sta=4997.8,5003.8
Exp/Cntr=0.3,0.1

Type RM Length L Ch R = 1,2014,533,533,533
BEGIN DESCRIPTION:
RIGHT BRANCH 2.0
END DESCRIPTION:
XS GIS Cut Line= 3
      3637849.64     10500410.18      3638199.61     10500360.19
      3638599.58     10500260.20
#Sta/Elev= 30
  4674.1  357.34  4694.3  356.63  4704.4  353.93  4714.5  349.54  4724.6  347.07
  4785.2  338.29  4835.7  332.79  4845.8  332.34  4855.9  330.17  4906.4  325.76
  4936.7  321.95  4967.0  319.76  4987.2  320.22  4994.3  318.02  4997.1  317.52
  5000.3  318.02  5017.5  320.25  5037.9  319.64  5058.5  320.44  5079.2  318.91
  5092.0  319.95  5264.7  319.52  5285.3  320.94  5339.4  329.14  5347.2  331.89
  5398.7  340.27  5416.7  345.07  5421.9  345.00  5429.6  349.23  5439.9  351.44
#Mann=3,-1,0
  4674.1    0.16       0  4994.3    0.07       0  5000.3    0.16       0
Bank Sta=4994.3,5000.3
Exp/Cntr=0.3,0.1

Type RM Length L Ch R = 1,1481,0,0,0
BEGIN DESCRIPTION:
RIGHT BRANCH 1.0
END DESCRIPTION:
XS GIS Cut Line= 4
      3637496.40     10500424.78      3638006.38     10500858.80
      3638375.30     10500891.35      3639254.24     10500587.52
#Sta/Elev= 30
  4137.1  363.64  4214.2  364.62  4384.4  363.82  4483.2  356.66  4505.2  356.75
  4568.9  353.53  4632.6  347.91  4710.6  349.49  4745.7  344.04  4760.0  339.76
  4767.7  335.75  4796.3  327.69  4840.1  321.07  4877.3  318.49  4910.4  320.49
  4980.7  320.71  4997.8  313.88  5000.5  313.38  5003.8  313.88  5020.8  319.74
  5030.9  320.69  5106.6  320.03  5121.2  321.15  5196.8  321.34  5222.7  319.99
  5266.3  322.30  5636.6  323.29  5835.6  344.81  5897.9  350.18  6107.1  354.66
#Mann=3,-1,0
  4137.1    0.16       0  4997.8    0.07       0  5003.8    0.16       0
Bank Sta=4997.8,5003.8
Exp/Cntr=0.3,0.1

Chan Stop Cuts=-1