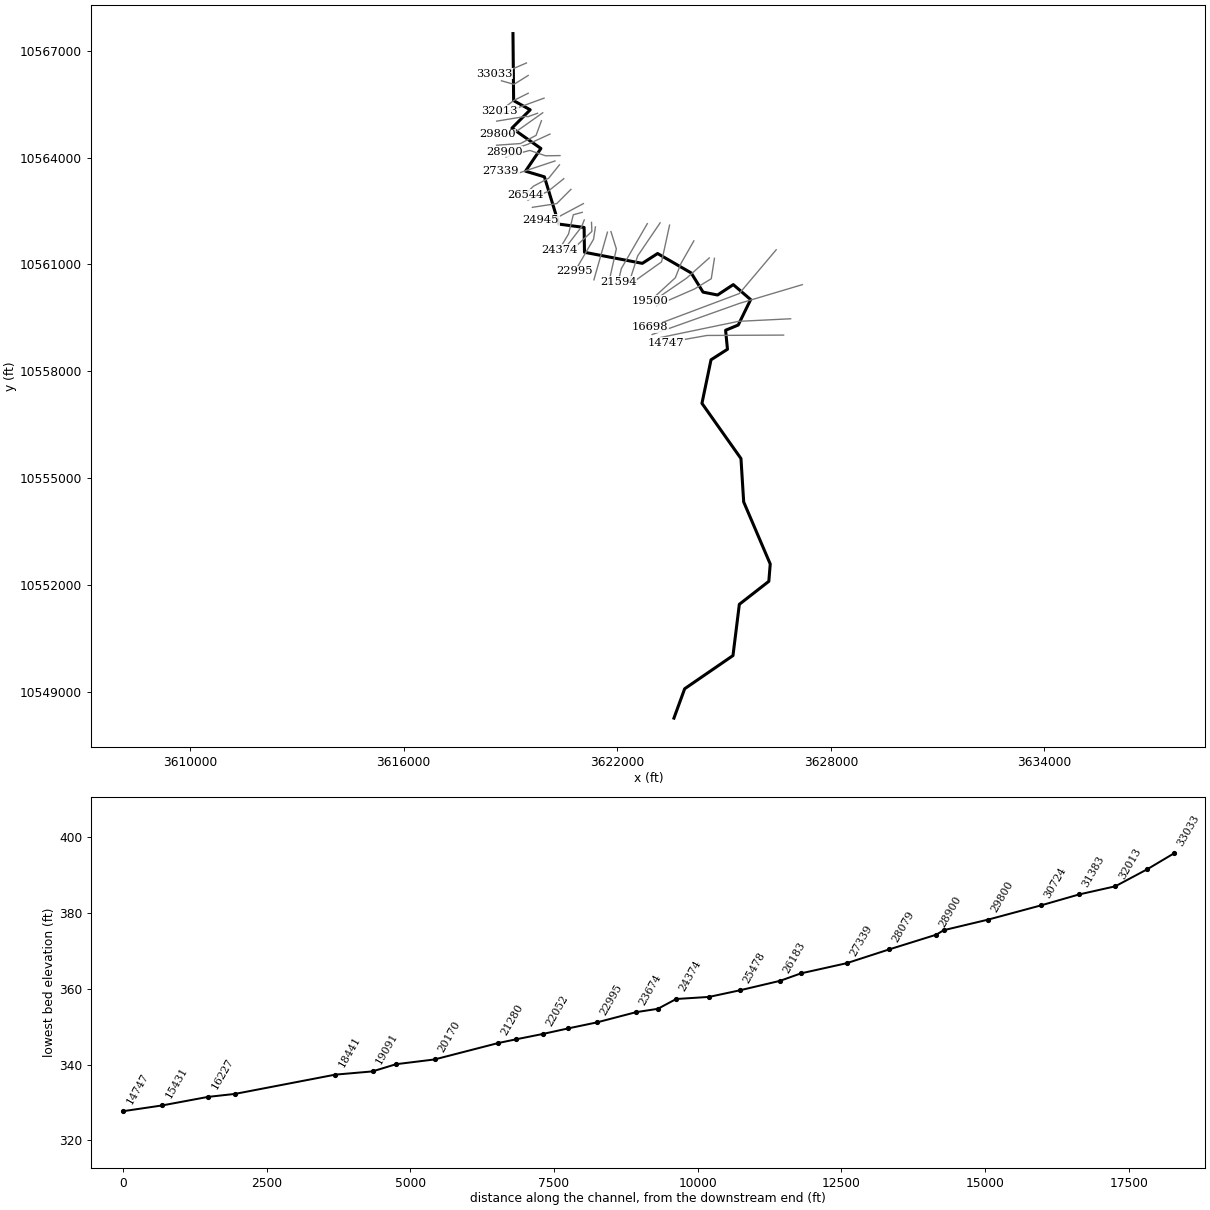
--- SELF CREEK.prj (project) ---

Proj Title=SELF CREEK Base Level Engineering
Current Plan=p01
Default Exp/Contr=0.3,0.1
English Units
Geom File=g01
Flow File=f01
Plan File=p01
Y Axis Title=Elevation
X Axis Title(PF)=Main Channel Distance
X Axis Title(XS)=Station
BEGIN DESCRIPTION:
SELF CREEK
END DESCRIPTION:
DSS Export Rating Curves= 0
DSS Export Rating Curve Sorted= 0
DSS Export Volume Flow Curves= 0
DXF OffsetX= 0
DXF OffsetY= 0
DXF ScaleX= 1
DXF ScaleY= 10

--- SELF CREEK.p01 (plan) ---

Plan Title=Multiple Run
Short Identifier=Multiple
Geom File=g01
Flow File=f01
Subcritical Flow
K Sum by GR= 0
Std Step Tol= 0.01
Critical Tol= 0.01
Num of Std Step Trials= 20
Max Error Tol= 0.3
Flow Tol Ratio= 0.001
Split Flow NTrial= 30
Split Flow Tol= 0.02
Split Flow Ratio= 0.02
Log Output Level= 0
Friction Slope Method= 1
Unsteady Friction Slope Method= 2
Unsteady Bridges Friction Slope Method= 1
Parabolic Critical Depth
Global Vel Dist=  1 , 1 , 1
Global Log Level= 0
CheckData=True
Encroach Param= -1, 0, 0, 0
BEGIN DESCRIPTION:
Multiple Run
END DESCRIPTION:

--- SELF CREEK.f01 (steady flow) ---

Flow Title=Multiple
Program Version=4.10
Number of Profiles= 7
Profile Names=10-year,25-year,50-year,1pct_min,100-year,1pct_plu,500-year
River Rch & RM=SELF CREEK,Reach-1         ,33033
    2199    3164    3998    3681    4978    6732    7694
River Rch & RM=SELF CREEK,Reach-1         ,21594
    2980    4346    5541    5142    6953    9404   10922
River Rch & RM=SELF CREEK,Reach-1         ,20170
    2980    4346    5541    5142    6953    9404   10922
River Rch & RM=SELF CREEK,Reach-1         ,16698
    4010    5917    7604    7105    9608   12994   15305
River Rch & RM=SELF CREEK,Reach-1         ,13968
    4197    6195    7961    7437   10057   13602   16015
River Rch & RM=SELF CREEK,Reach-1         ,11217
    4405    6495    8341    7784   10527   14237   16728
River Rch & RM=SELF CREEK,Reach-1         ,7092
    4624    6811    8739    8145   11015   14896   17458
Boundary for River Rch & Prof#=SELF CREEK,Reach-1         , 1
Up Type= 0
Dn Type= 3
Dn Slope=0.006
Boundary for River Rch & Prof#=SELF CREEK,Reach-1         , 2
Up Type= 0
Dn Type= 3
Dn Slope=0.006
Boundary for River Rch & Prof#=SELF CREEK,Reach-1         , 3
Up Type= 0
Dn Type= 3
Dn Slope=0.006
Boundary for River Rch & Prof#=SELF CREEK,Reach-1         , 4
Up Type= 0
Dn Type= 3
Dn Slope=0.006
Boundary for River Rch & Prof#=SELF CREEK,Reach-1         , 5
Up Type= 0
Dn Type= 3
Dn Slope=0.006
Boundary for River Rch & Prof#=SELF CREEK,Reach-1         , 6
Up Type= 0
Dn Type= 3
Dn Slope=0.006
Boundary for River Rch & Prof#=SELF CREEK,Reach-1         , 7
Up Type= 0
Dn Type= 3
Dn Slope=0.006
DSS Import GetInterval= 0
DSS Import GetPeak= 0
DSS Import FillOption= 0

--- SELF CREEK.g01 (geometry) ---

Geom Title=Existing Conditions
Program Version=4.10

River Reach=SELF CREEK      ,Reach-1
Reach XY= 30
      3619071.75       10567486.      3619090.25       10565603.
       3619555.5       10565345.        3619043.       10564831.
       3619856.5       10564259.       3619423.5       10563621.
      3619954.25       10563463.      3620359.25       10562135.
        3621070.       10562041.       3621080.5       10561343.
      3622704.75       10561032.        3623134.       10561308.
      3624077.25       10560763.        3624411.       10560224.
      3624818.25       10560143.      3625260.25       10560435.
        3625748.       10560014.      3625399.25       10559300.
       3625044.5       10559153.       3625096.5       10558619.
      3624634.75       10558323.        3624380.       10557100.
        3625476.       10555549.      3625552.25       10554331.
      3626298.25       10552586.      3626258.25       10552100.
       3625430.5       10551455.       3625251.5       10550015.
       3623894.5       10549083.      3623593.25       10548258.

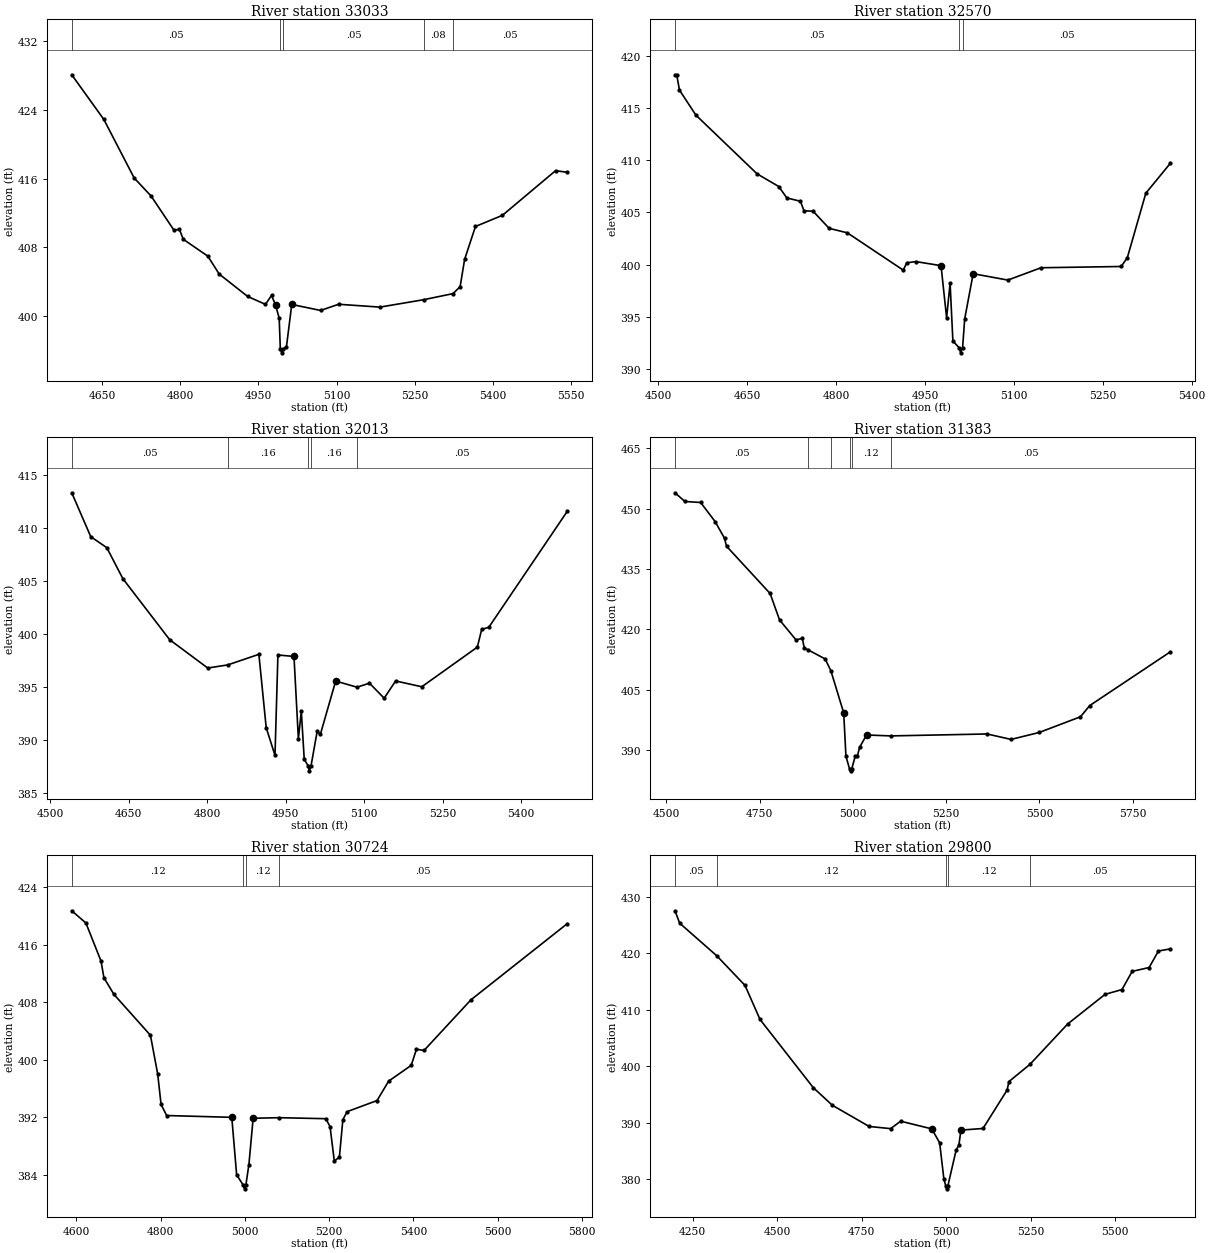
Type RM Length L Ch R = 1 ,33033   ,463,463,463
BEGIN DESCRIPTION:
SELF CREEK 59.0
END DESCRIPTION:
XS GIS Cut Line= 3
       3619449.6     10566660.18      3619099.61     10566510.19
      3618549.58     10566360.18
#Sta/Elev= 30
  4591.9  428.09  4653.5  422.89  4711.6  416.09  4744.2  413.98  4787.7  410.04
  4798.6  410.09  4805.9  408.95    4853  406.99  4874.8  404.91  4929.2  402.31
  4963.6  401.38  4975.3  402.42    4983  401.29    4990  399.77  4992.1  396.24
  4994.9  395.74  4998.1  396.24  5003.8   396.4  5014.1  401.37  5069.4  400.67
    5104  401.39  5183.4  401.06  5267.1  401.92  5323.6  402.63  5337.2  403.44
  5345.8  406.61  5366.6  410.44  5418.4  411.74  5520.3  416.93  5542.8  416.75
#Mann= 5 ,-1 , 0
  4591.9     .05       0  4992.1     .03       0  4998.1     .05       0
  5267.1     .08       0  5323.6     .05       0
Bank Sta=4983,5014.1
XS Rating Curve= 0 ,0
Exp/Cntr=0.3,0.1

Type RM Length L Ch R = 1 ,32570   ,557,557,557
BEGIN DESCRIPTION:
SELF CREEK 58.0
END DESCRIPTION:
XS GIS Cut Line= 3
      3619499.58     10566310.17      3619099.61     10566060.19
      3618749.58      10566160.2
#Sta/Elev= 30
  4528.5  418.16  4531.4  418.16  4536.1  416.69  4563.8   414.3    4667  408.68
  4703.6  407.47  4717.1  406.38  4740.1  406.06    4746  405.15  4761.4  405.11
  4788.5  403.47  4819.2  403.04  4913.5  399.47  4919.4  400.17  4934.7  400.29
  4977.2   399.9  4986.6  394.92  4992.5  398.21  4997.2  392.69  5007.6  392.06
  5010.3  391.56  5013.6  392.06  5017.1   394.8  5031.4  399.13  5089.9  398.52
  5145.8   399.7    5281  399.82  5291.4  400.66  5322.6  406.83  5364.2  409.71
#Mann= 3 ,-1 , 0
  4528.5     .05       0  5007.6     .03       0  5013.6     .05       0
Bank Sta=4977.2,5031.4
XS Rating Curve= 0 ,0
Exp/Cntr=0.3,0.1

Type RM Length L Ch R = 1 ,32013   ,630,630,630
BEGIN DESCRIPTION:
SELF CREEK 57.0
END DESCRIPTION:
XS GIS Cut Line= 3
      3619499.58     10565810.17      3619099.61     10565610.19
      3618699.59     10565310.17
#Sta/Elev= 30
  4541.1  413.29  4577.4  409.15  4608.1  408.11  4638.9  405.18  4728.3  399.43
    4801  396.76  4839.1  397.05  4898.8  398.05  4912.8  391.13  4929.6  388.52
  4935.2  397.99  4965.9  397.85  4974.3  390.09  4979.9  392.68  4985.5  388.15
  4992.6  387.56  4995.3  387.06  4998.6  387.56  5010.2  390.78  5016.4  390.51
  5045.6  395.53  5086.4  394.95  5110.2  395.33  5138.3  393.91  5160.2  395.54
  5210.2  394.99  5316.4  398.73  5324.7   400.4  5338.3   400.6  5488.3  411.54
#Mann= 5 ,-1 , 0
  4541.1     .05       0  4839.1     .16       0  4992.6     .07       0
  4998.6     .16       0  5086.4     .05       0
Bank Sta=4965.9,5045.6
XS Rating Curve= 0 ,0
Exp/Cntr=0.3,0.1

Type RM Length L Ch R = 1 ,31383   ,659,659,659
BEGIN DESCRIPTION:
SELF CREEK 56.0
END DESCRIPTION:
XS GIS Cut Line= 3
      3619944.26     10565672.58      3619499.61     10565510.19
      3618699.59     10565210.18
#Sta/Elev= 30
  4523.3  453.93  4549.9  451.77  4592.1  451.52  4630.8  446.79    4656  442.64
  4661.4  440.67  4778.2  428.93  4803.5  422.37  4847.6  417.42  4864.5  417.79
  4869.9  415.38  4879.3  414.97  4925.6  412.69    4941  409.77  4975.4   399.3
  4981.4  388.55    4991  385.41  4993.8  384.91    4997  385.41  5006.5  388.58
  5011.8  388.51    5018  390.75  5036.7  393.81  5101.6  393.58  5359.8  394.06
  5423.9  392.71  5499.5  394.44  5609.9  398.33  5634.8  401.12  5851.1  414.47
#Mann= 6 ,-1 , 0
  4523.3     .05       0  4879.3     .16       0    4941     .12       0
    4991     .07       0    4997     .12       0  5101.6     .05       0
Bank Sta=4975.4,5036.7
XS Rating Curve= 0 ,0
Exp/Cntr=0.3,0.1

Type RM Length L Ch R = 1 ,30724   ,924,924,924
BEGIN DESCRIPTION:
SELF CREEK 55.0
END DESCRIPTION:
XS GIS Cut Line= 4
      3619761.34     10565248.39      3619493.07     10565151.16
      3619425.36     10565160.71      3618614.16     10565026.23
#Sta/Elev= 30
  4589.2  420.69  4622.8  418.99  4658.7  413.69  4665.5  411.39  4689.4  409.06
  4775.9  403.39  4793.1  398.02  4801.2  393.77  4814.4  392.23    4969  391.98
  4980.5  383.99  4996.4  382.54  4999.2  382.04  5002.4  382.54  5009.6  385.41
  5019.7  391.85  5081.4  391.93    5192  391.79  5202.2   390.7  5212.3   385.9
  5224.4  386.45  5232.6  391.64  5242.7  392.77  5313.7  394.31  5341.3  397.01
  5394.8   399.2  5407.3  401.45  5425.2  401.27  5536.7  408.32  5765.2   418.9
#Mann= 4 ,-1 , 0
  4589.2     .12       0  4996.4     .07       0  5002.4     .12       0
  5081.4     .05       0
Bank Sta=4969,5019.7
XS Rating Curve= 0 ,0
Exp/Cntr=0.3,0.1

Type RM Length L Ch R = 1 ,29800   ,772,772,772
BEGIN DESCRIPTION:
SELF CREEK 54.0
END DESCRIPTION:
XS GIS Cut Line= 3
       3619907.8     10565261.98      3619100.54     10564689.08
      3618626.62     10564652.63
#Sta/Elev= 30
  4197.9  427.56  4211.8  425.36  4321.7  419.57    4405  414.33  4449.3   408.3
  4606.8  396.21  4663.3  393.08    4772  389.33  4835.6  388.94  4865.1  390.26
  4957.3   388.9  4980.5  386.42    4993  380.03  4998.7  378.77  5001.4  378.27
  5004.7  378.77  5029.5   385.2  5037.3  385.98  5043.5  388.68  5108.7  388.97
    5180  395.78  5185.3  397.28  5247.4  400.33  5359.2   407.5  5469.5  412.74
  5519.7   413.6  5549.8  416.82  5599.9   417.5  5627.4  420.43  5663.1  420.81
#Mann= 5 ,-1 , 0
  4197.9     .05       0  4321.7     .12       0  4998.7     .07       0
  5004.7     .12       0  5247.4     .05       0
Bank Sta=4957.3,5043.5
XS Rating Curve= 0 ,0
Exp/Cntr=0.3,0.1

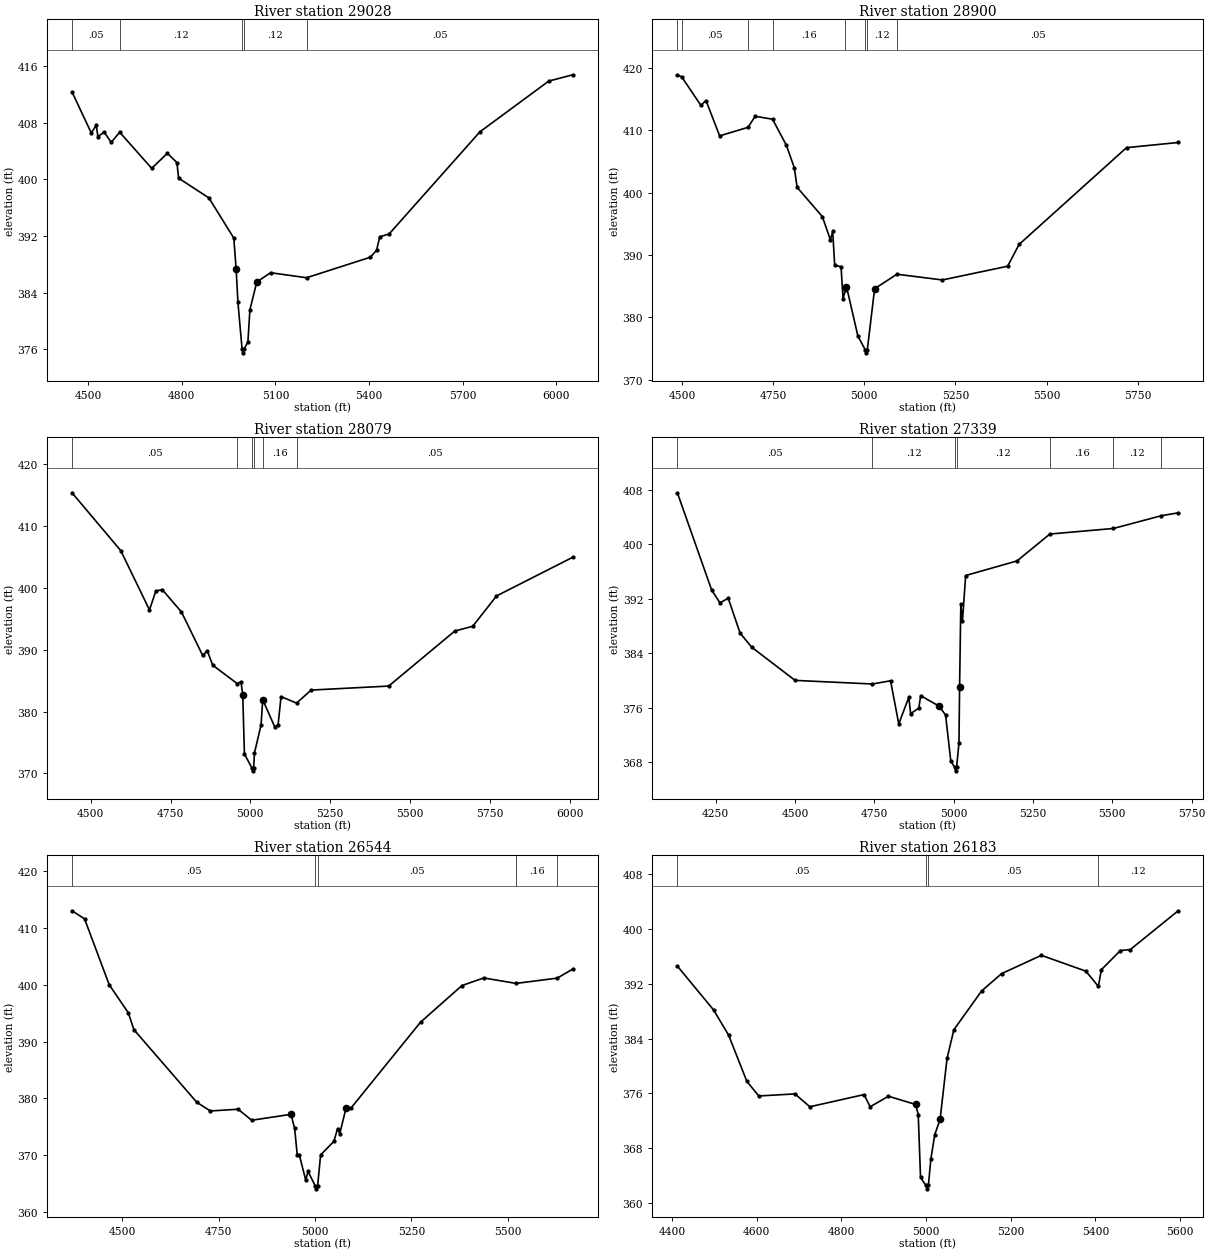
Type RM Length L Ch R = 1 ,29028   ,128,128,128
BEGIN DESCRIPTION:
SELF CREEK 53.0
END DESCRIPTION:
XS GIS Cut Line= 4
      3619871.36     10565038.01      3619720.33     10564626.58
      3619282.83     10564397.42      3618612.81     10564350.67
#Sta/Elev= 30
  4448.6  412.37  4510.2  406.58  4526.2  407.66  4531.5  406.05  4551.4   406.7
  4574.1  405.25  4601.2  406.68  4703.8  401.57  4754.1   403.7  4784.6  402.38
  4789.9  400.18  4886.9  397.39  4966.7  391.71  4974.2  387.34  4979.9  382.64
  4993.3  375.98    4996  375.48  4999.3  375.98  5011.9  377.03  5018.3  381.57
  5040.4  385.51  5084.5  386.81  5199.8   386.1    5404     389  5424.1     390
  5434.1  391.89  5464.2  392.29  5754.9  406.73  5975.4  413.91  6052.4   414.8
#Mann= 5 ,-1 , 0
  4448.6     .05       0  4601.2     .12       0  4993.3     .07       0
  4999.3     .12       0  5199.8     .05       0
Bank Sta=4974.2,5040.4
XS Rating Curve= 0 ,0
Exp/Cntr=0.3,0.1

Type RM Length L Ch R = 1 ,28900   ,821,821,821
BEGIN DESCRIPTION:
SELF CREEK 52.0
END DESCRIPTION:
XS GIS Cut Line= 3
      3620110.98     10564663.06      3619475.54     10564371.37
      3618834.95     10564163.06
#Sta/Elev= 30
  4487.6   418.9  4499.6  418.55    4552     414  4566.1  414.76  4603.5   409.1
  4681.3  410.47    4701  412.25  4748.6  411.77  4786.2  407.62  4808.2  403.98
  4815.9  400.84  4884.9  396.16  4907.2  392.43  4913.4  393.78  4918.9  388.33
  4936.3  388.12  4941.8  382.99  4948.4  384.35  4951.2  384.93  4982.3  377.03
  5002.3   374.8  5005.1   374.3  5008.3   374.8  5028.3  384.58  5089.4  386.91
  5214.1  385.99  5392.8  388.19  5424.4  391.69  5718.8  407.21  5860.4  408.04
#Mann= 8 ,-1 , 0
  4487.6     .12       0  4499.6     .05       0  4681.3     .12       0
  4748.6     .16       0  4948.4     .12       0  5002.3     .07       0
  5008.3     .12       0  5089.4     .05       0
Bank Sta=4951.2,5028.3
XS Rating Curve= 0 ,0
Exp/Cntr=0.3,0.1

Type RM Length L Ch R = 1 ,28079   ,740,740,740
BEGIN DESCRIPTION:
SELF CREEK 51.0
END DESCRIPTION:
XS GIS Cut Line= 4
      3620392.19     10564058.87      3619985.95     10564053.67
      3619543.24     10564204.71      3618873.01     10564022.86
#Sta/Elev= 30
  4441.5  415.41  4594.1  406.05  4684.1  396.46  4704.1  399.51  4724.1  399.74
  4784.1  396.13  4850.8  389.08    4865  389.85  4882.2  387.51  4959.2  384.52
  4970.7  384.83  4976.2  382.73  4981.5  373.15  5004.5  370.91  5007.3  370.41
  5010.5  370.91    5013   373.3  5033.6  377.84  5038.8  381.95    5039  381.91
  5076.4  377.52  5086.9  377.86  5096.2  382.42  5144.9  381.37  5190.2  383.48
  5433.4  384.13  5640.5  393.04  5696.5   393.8    5771  398.71    6010  404.98
#Mann= 6 ,-1 , 0
  4441.5     .05       0  4959.2     .12       0  5004.5     .07       0
  5010.5     .12       0    5039     .16       0  5144.9     .05       0
Bank Sta=4976.2,5038.8
XS Rating Curve= 0 ,0
Exp/Cntr=0.3,0.1

Type RM Length L Ch R = 1 ,27339   ,795,795,795
BEGIN DESCRIPTION:
SELF CREEK 50.0
END DESCRIPTION:
XS GIS Cut Line= 3
      3620251.56     10563907.83      3619235.95     10563569.29
       3618732.7     10563636.74
#Sta/Elev= 30
  4129.2  407.53  4237.2  393.28  4263.5  391.39  4289.4  392.08  4326.8  386.97
  4363.7  384.88  4500.2  380.03  4743.6   379.5  4801.1  379.97    4827  373.64
  4858.6  377.56  4864.4  375.15  4890.2  375.98    4896  377.79  4953.5  376.27
  4974.5  374.96  4990.9  368.22  5003.2  367.27  5005.9  366.77  5009.2  367.27
  5016.7  370.89 5018.64  379.02  5022.5  391.17  5027.7  388.73  5037.8   395.4
  5199.7  397.54  5303.1  401.48  5503.7   402.3  5653.8  404.16  5707.5  404.59
#Mann= 7 ,-1 , 0
  4129.2     .05       0  4743.6     .12       0  5003.2     .07       0
  5009.2     .12       0  5303.1     .16       0  5503.7     .12       0
  5653.8     .16       0
Bank Sta=4953.5,5018.64
XS Rating Curve= 0 ,0
Exp/Cntr=0.3,0.1

Type RM Length L Ch R = 1 ,26544   ,361,361,361
BEGIN DESCRIPTION:
SELF CREEK 49.0
END DESCRIPTION:
XS GIS Cut Line= 4
      3620376.59     10563798.48      3620074.49     10563423.46
      3619647.41      10563199.5      3619407.87     10562965.17
#Sta/Elev= 30
  4369.8  413.02  4402.3   411.6  4466.3     400  4515.8  395.07  4530.2  392.11
  4693.4  379.32  4728.6  377.79  4800.6   378.1  4835.8  376.16  4937.7   377.2
  4947.2  374.73  4954.1  369.99  4959.7  369.99  4976.1  365.57  4981.8  367.18
  5000.8  364.59  5003.6  364.09  5006.8  364.59  5014.6  370.06  5048.8  372.43
  5058.7  374.68  5064.4  373.82  5080.8  378.39    5094  378.36  5273.7  393.41
  5381.1  399.86  5437.7   401.2  5521.6  400.24  5628.5  401.17  5668.7  402.77
#Mann= 5 ,-1 , 0
  4369.8     .05       0  5000.8     .03       0  5006.8     .05       0
  5521.6     .16       0  5628.5     .12       0
Bank Sta=4937.7,5080.8
XS Rating Curve= 0 ,0
Exp/Cntr=0.3,0.1

Type RM Length L Ch R = 1 ,26183   ,705,705,705
BEGIN DESCRIPTION:
SELF CREEK 48.0
END DESCRIPTION:
XS GIS Cut Line= 3
      3620499.65     10563410.22      3620048.45     10563048.46
      3619492.93     10562809.63
#Sta/Elev= 30
  4412.4  394.53  4498.1  388.14  4533.3  384.51  4576.5  377.77  4604.7  375.64
  4690.1  375.94  4725.3  374.07  4853.4  375.84  4867.8  374.07    4911   375.6
    4975  374.41  4981.4  372.94  4986.8  363.81  4999.4  362.63  5002.1  362.13
  5005.4  362.63  5011.2  366.48  5020.5  370.03    5033  372.22  5049.5  381.12
  5065.6  385.28    5131  390.91  5178.1  393.43  5272.3   396.1  5377.3   393.8
  5406.9  391.58    5414  394.01  5458.8  396.79  5482.4  396.94  5595.4  402.58
#Mann= 4 ,-1 , 0
  4412.4     .05       0  4999.4     .03       0  5005.4     .05       0
  5406.9     .12       0
Bank Sta=4975,5033
XS Rating Curve= 0 ,0
Exp/Cntr=0.3,0.1

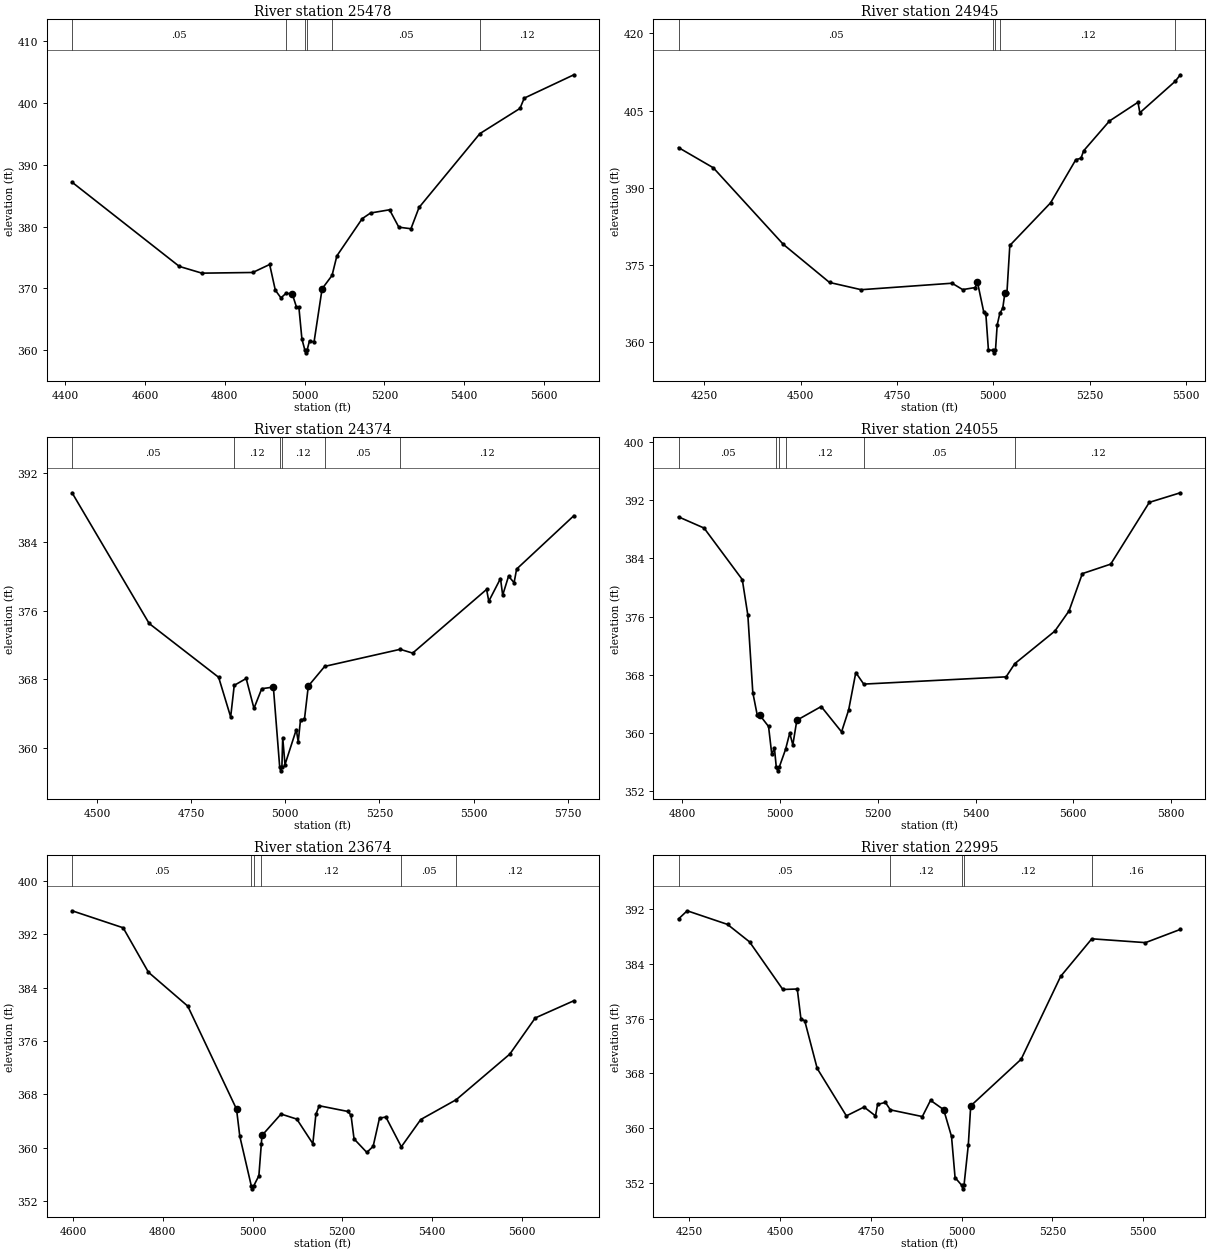
Type RM Length L Ch R = 1 ,25478   ,533,533,533
BEGIN DESCRIPTION:
SELF CREEK 47.0
END DESCRIPTION:
XS GIS Cut Line= 3
      3620699.63     10563110.21      3620299.61     10562710.19
      3619616.16     10562605.75
#Sta/Elev= 30
  4417.6  387.15  4686.3  373.56  4742.9  372.47  4870.2  372.58  4912.6  373.87
  4926.8  369.72  4940.9  368.48  4953.4  369.21  4969.2  369.13  4979.8  366.99
  4985.8  366.99  4993.4  361.85  5000.6  360.11  5003.3  359.61  5006.6  360.11
  5012.5  361.56  5023.8  361.35    5044  369.95  5068.9   372.1    5081  375.26
  5144.5  381.27  5165.4  382.18    5213   382.7  5236.2  379.89  5266.6  379.64
  5286.8  383.07  5439.2  394.99  5539.7  399.06  5550.4  400.72  5674.7  404.49
#Mann= 6 ,-1 , 0
  4417.6     .05       0  4953.4     .12       0  5000.6     .07       0
  5006.6     .12       0  5068.9     .05       0  5439.2     .12       0
Bank Sta=4969.2,5044
XS Rating Curve= 0 ,0
Exp/Cntr=0.3,0.1

Type RM Length L Ch R = 1 ,24945   ,571,571,571
BEGIN DESCRIPTION:
SELF CREEK 46.0
END DESCRIPTION:
XS GIS Cut Line= 3
      3621049.58     10562710.17      3620299.61     10562310.19
      3619850.58     10562251.59
#Sta/Elev= 30
  4182.8   397.8  4273.1  393.87  4454.8  378.98  4574.8  371.57    4657  370.16
  4892.9  371.42  4920.5  370.18  4953.1  370.58  4958.7   371.7    4975   365.9
  4980.7   365.4  4987.4   358.4  4999.7  358.38  5002.4  357.88  5005.7  358.38
  5010.1  363.29  5016.9  365.54  5024.6  366.57  5029.9  369.43  5035.3  369.43
  5042.9  378.76  5148.7  387.05  5214.3  395.45  5227.7  395.73  5234.5  397.17
  5301.6  402.97  5375.6  406.61  5380.6  404.58  5472.6  410.71  5485.6  411.96
#Mann= 5 ,-1 , 0
  4182.8     .05       0  4999.7     .03       0  5005.7     .05       0
  5016.9     .12       0  5472.6     .16       0
Bank Sta=4958.7,5029.9
XS Rating Curve= 0 ,0
Exp/Cntr=0.3,0.1

Type RM Length L Ch R = 1 ,24374   ,319,319,319
BEGIN DESCRIPTION:
SELF CREEK 45.0
END DESCRIPTION:
XS GIS Cut Line= 4
      3621017.23     10562465.13       3620767.2     10562397.42
      3620631.79     10561855.75      3620366.81     10561414.12
#Sta/Elev= 30
  4433.9  389.73  4638.6   374.5  4823.1  368.23    4855  363.61  4864.5  367.29
  4896.2  368.09  4916.9  364.61  4937.5   366.9  4968.4  367.09  4985.1  357.83
  4987.8  357.33  4991.1  357.83  4993.2   361.2  4999.3  358.06  5029.3  362.14
  5034.4   360.7  5040.5   363.3  5050.9  363.32  5061.2  367.21  5104.7   369.5
  5305.1  371.49  5338.3  371.05  5534.6  378.47  5540.4  377.09  5571.5  379.74
  5577.3   377.8  5592.9  380.01  5607.6  379.25  5614.3  380.84  5766.3  387.06
#Mann= 6 ,-1 , 0
  4433.9     .05       0  4864.5     .12       0  4985.1     .07       0
  4991.1     .12       0  5104.7     .05       0  5305.1     .12       0
Bank Sta=4968.4,5061.2
XS Rating Curve= 0 ,0
Exp/Cntr=0.3,0.1

Type RM Length L Ch R = 1 ,24055   ,381,381,381
BEGIN DESCRIPTION:
SELF CREEK 44.0
END DESCRIPTION:
XS GIS Cut Line= 3
      3621074.49     10562251.56      3620999.61     10562060.19
      3620499.59     10561410.16
#Sta/Elev= 30
    4793  389.73  4845.2  388.19  4923.3  381.09  4934.7  376.17  4944.8  365.53
  4953.8  362.44  4959.1  362.41    4977  360.85  4983.6     357    4989  357.87
  4992.8  355.24  4995.6  354.74  4998.8  355.24  5011.7  357.69  5020.3  359.95
  5026.6  358.31  5034.8  361.71  5084.6   363.6  5126.2  360.11  5140.7  363.13
  5155.3  368.28  5171.5  366.69  5462.5  367.69  5480.3  369.51  5562.1  373.99
  5591.2  376.78  5618.3  381.91  5676.3  383.22  5755.2  391.73  5818.6  393.05
#Mann= 6 ,-1 , 0
    4793     .05       0  4992.8     .03       0  4998.8     .05       0
  5011.7     .12       0  5171.5     .05       0  5480.3     .12       0
Bank Sta=4959.1,5034.8
XS Rating Curve= 0 ,0
Exp/Cntr=0.3,0.1

Type RM Length L Ch R = 1 ,23674   ,679,679,679
BEGIN DESCRIPTION:
SELF CREEK 43.0
END DESCRIPTION:
XS GIS Cut Line= 3
      3621277.62     10562183.85      3621288.04     10561928.67
      3620657.82     10561340.12
#Sta/Elev= 30
  4598.1  395.52  4711.9  392.97  4768.2  386.31  4855.8  381.23  4964.4   365.8
  4971.7  361.73  4997.1  354.35  4999.8  353.85  5003.1  354.35  5014.2  355.81
  5019.6  360.54  5021.1  361.85  5063.6  365.06  5098.7   364.3  5134.4  360.62
  5141.2  365.01  5148.6   366.3  5212.1  365.45  5219.4  364.89  5226.2  361.33
  5254.6  359.31  5268.7  360.21  5282.9  364.45  5297.1  364.61  5331.5  360.15
  5374.8  364.24  5453.8  367.21  5573.1  374.04  5629.8  379.46  5715.8  382.04
#Mann= 6 ,-1 , 0
  4598.1     .05       0  4997.1     .03       0  5003.1     .05       0
  5019.6     .12       0  5331.5     .05       0  5453.8     .12       0
Bank Sta=4964.4,5021.1
XS Rating Curve= 0 ,0
Exp/Cntr=0.3,0.1

Type RM Length L Ch R = 1 ,22995   ,501,501,501
BEGIN DESCRIPTION:
SELF CREEK 42.0
END DESCRIPTION:
XS GIS Cut Line= 3
        3621387.     10562053.67      3621334.91     10561709.92
      3620814.69     10560815.13
#Sta/Elev= 30
  4219.8  390.56  4243.6  391.75  4354.8  389.76  4415.5  387.21  4507.2  380.26
    4547  380.33  4557.1  375.95  4567.5   375.7  4601.9  368.73  4682.3  361.81
  4731.1   363.1  4762.5  361.81  4768.3  363.48  4789.8  363.78  4803.4  362.69
  4891.6  361.71  4914.2  364.08  4950.4  362.72    4972  358.81  4981.8   352.8
  5000.4  351.66  5003.1  351.16  5006.4  351.66  5018.3  357.57  5024.9  363.27
  5163.9  370.08  5272.8  382.18  5358.6  387.66  5506.5   387.1  5602.5  389.03
#Mann= 5 ,-1 , 0
  4219.8     .05       0  4803.4     .12       0  5000.4     .07       0
  5006.4     .12       0  5358.6     .16       0
Bank Sta=4950.4,5024.9
XS Rating Curve= 0 ,0
Exp/Cntr=0.3,0.1

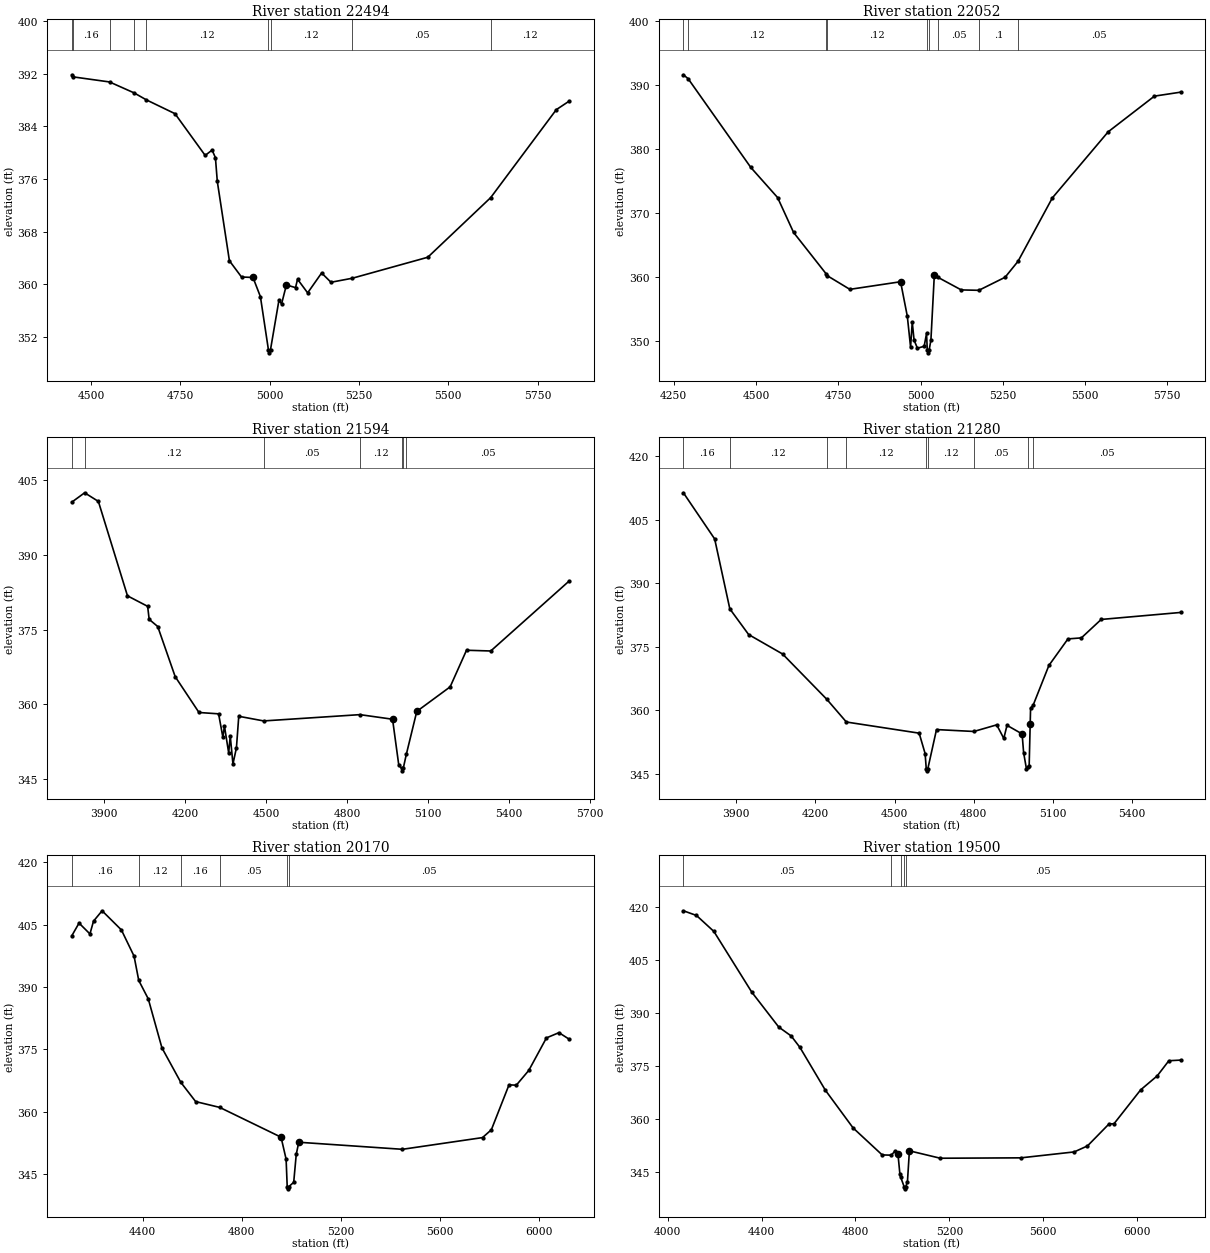
Type RM Length L Ch R = 1 ,22494   ,442,442,442
BEGIN DESCRIPTION:
SELF CREEK 41.0
END DESCRIPTION:
XS GIS Cut Line= 2
      3621725.55     10561907.88      3621345.34     10560569.33
#Sta/Elev= 30
  4446.5  391.81  4448.9   391.5    4552  390.72  4620.7  389.06  4655.1     388
  4735.2   385.9  4819.7  379.56  4839.1  380.37  4848.4  379.21  4853.6  375.62
  4887.5  363.56  4921.4  361.09  4953.5  361.02  4974.3   358.1  4996.6  350.07
  4999.3  349.57  5002.6  350.07  5026.2  357.58  5033.5     357    5047  359.88
  5072.6  359.48  5078.2  360.75  5106.5  358.68  5145.6   361.7  5171.8  360.29
  5231.2   360.9  5442.7  364.09  5618.8  373.15  5802.4  386.51    5838  387.79
#Mann= 9 ,-1 , 0
  4446.5     .05       0  4448.9     .16       0    4552     .12       0
  4620.7     .16       0  4655.1     .12       0  4996.6     .07       0
  5002.6     .12       0  5231.2     .05       0  5618.8     .12       0
Bank Sta=4953.5,5047
XS Rating Curve= 0 ,0
Exp/Cntr=0.3,0.1

Type RM Length L Ch R = 1 ,22052   ,458,458,458
BEGIN DESCRIPTION:
SELF CREEK 40.0
END DESCRIPTION:
XS GIS Cut Line= 3
      3621824.51     10561923.42      3621975.54     10561439.08
       3621756.8     10560459.96
#Sta/Elev= 30
  4279.5  391.59  4293.9  390.98  4484.3   377.1  4565.7  372.39  4614.3  366.93
  4712.6   360.5  4716.2  360.18  4785.3  358.03  4939.4  359.22  4959.9  353.82
  4969.8     349  4974.9  352.89  4980.4   350.1  4990.6  348.82  5011.1  349.13
  5018.3  351.14  5020.5   348.6  5023.2   348.1  5026.5   348.6  5031.6  350.11
  5041.9  360.23  5053.3   359.9  5123.8  357.94  5177.2  357.88    5257  359.92
  5296.2  362.41  5400.5  372.33  5570.2  382.67  5710.7  388.25  5790.1  388.87
#Mann= 9 ,-1 , 0
  4279.5     .16       0  4293.9     .12       0  4712.6     .05       0
  4716.2     .12       0  5020.5     .07       0  5026.5     .12       0
  5053.3     .05       0  5177.2      .1       0  5296.2     .05       0
Bank Sta=4939.4,5041.9
XS Rating Curve= 0 ,0
Exp/Cntr=0.3,0.1

Type RM Length L Ch R = 1 ,21594   ,314,314,314
BEGIN DESCRIPTION:
SELF CREEK 39.0
END DESCRIPTION:
XS GIS Cut Line= 3
      3622845.34     10562147.44      3622116.16       10560887.
        3622028.     10560513.63
#Sta/Elev= 30
  3781.5   400.5  3828.9  402.37  3879.7  400.64  3987.4  381.74    4062  379.64
  4067.7  377.03  4099.3   375.6  4163.9  365.57    4252  358.39  4324.6  358.12
  4340.4  353.44  4346.2  355.67  4361.9   350.3  4367.7  353.68  4377.7  348.09
  4390.6  351.32  4399.2  357.63  4491.4   356.7  4847.5  357.96  4968.3  357.04
  4991.4  347.84  5001.9  347.21  5004.7  346.71  5007.9  347.21  5019.2  349.99
    5058  358.61  5181.4  363.52    5242  370.85  5331.7   370.7  5621.3  384.68
#Mann= 7 ,-1 , 0
  3781.5     .16       0  3828.9     .12       0  4491.4     .05       0
  4847.5     .12       0  5001.9     .07       0  5007.9     .12       0
  5019.2     .05       0
Bank Sta=4968.3,5058
XS Rating Curve= 0 ,0
Exp/Cntr=0.3,0.1

Type RM Length L Ch R = 1 ,21280   ,1110,1110,1110
BEGIN DESCRIPTION:
SELF CREEK 38.0
END DESCRIPTION:
XS GIS Cut Line= 3
       3623204.7     10562168.25      3622574.49     10561241.17
      3622340.64     10560513.63
#Sta/Elev= 30
  3699.2  411.33  3817.8  400.44  3875.3  383.94  3946.6  377.88  4075.3  373.29
  4242.9  362.61  4317.2  357.24  4593.2  354.61  4615.8   349.8  4620.1  346.22
  4622.9  345.72  4626.1  346.22    4659  355.46  4800.7  355.01  4887.3  356.57
  4914.2  353.36  4926.3  356.46  4983.6  354.43  4989.3  350.02  4999.8  346.26
  5007.8  346.68  5010.3  346.81  5014.2  356.72  5015.7  360.51  5025.2  361.17
  5085.2  370.59  5157.4  376.85  5208.3  377.09  5283.4  381.44  5584.4  383.09
#Mann= 9 ,-1 , 0
  3699.2     .16       0  3875.3     .12       0  4242.9     .05       0
  4317.2     .12       0  4620.1     .03       0  4626.1     .12       0
  4800.7     .05       0  5007.8     .12       0  5025.2     .05       0
Bank Sta=4983.6,5014.2
XS Rating Curve= 0 ,0
Exp/Cntr=0.3,0.1

Type RM Length L Ch R = 1 ,20170   ,670,670,670
BEGIN DESCRIPTION:
SELF CREEK 37.0
END DESCRIPTION:
XS GIS Cut Line= 3
      3623470.32     10562105.72      3623246.37      10561074.5
      3622470.36     10560522.44
#Sta/Elev= 30
  4114.1  402.33  4143.2  405.38  4187.2  402.76  4201.6  405.84  4236.3  408.34
  4314.2  403.73  4365.4  397.41  4384.3  391.56  4422.7  387.13  4477.9  375.33
  4553.9  367.05  4614.1  362.39  4711.3  360.99  4958.9  353.82  4979.3  348.54
  4983.8  341.88  4986.6  341.38  4989.8  341.88    5010  342.95  5020.3   349.7
  5030.5   352.6    5449   350.9  5772.4  353.72  5808.1   355.6  5879.4  366.42
  5908.9  366.34  5959.3   369.9  6030.6  377.73  6081.1  378.99  6121.7  377.44
#Mann= 6 ,-1 , 0
  4114.1     .16       0  4384.3     .12       0  4553.9     .16       0
  4711.3     .05       0  4983.8     .03       0  4989.8     .05       0
Bank Sta=4958.9,5030.5
XS Rating Curve= 0 ,0
Exp/Cntr=0.3,0.1

Type RM Length L Ch R = 1 ,19500   ,409,409,409
BEGIN DESCRIPTION:
SELF CREEK 36.0
END DESCRIPTION:
XS GIS Cut Line= 4
      3624152.63     10561663.06      3623793.24     10561032.83
      3623631.79     10560626.58      3622928.64     10559980.73
#Sta/Elev= 30
    4067  418.99  4122.8  417.66  4196.9  413.13  4358.1  395.93  4473.2  386.01
  4526.2  383.48  4563.6  380.22  4671.6  368.11  4789.8   357.4  4913.7  349.75
  4952.2  349.68  4967.5  350.77    4981  349.89    4989  344.38  4991.9  343.55
  5007.7  340.63  5010.4  340.13  5013.7  340.63  5021.3   342.2  5029.6  350.91
  5161.2  348.81  5504.4  348.92  5731.3   350.6    5788   352.3  5879.9  358.55
  5900.8  358.58  6014.3  368.19  6085.2  372.18  6134.5  376.46  6184.4  376.64
#Mann= 5 ,-1 , 0
    4067     .05       0  4952.2     .16       0  4991.9     .05       0
  5007.7     .03       0  5013.7     .05       0
Bank Sta=4981,5029.6
XS Rating Curve= 0 ,0
Exp/Cntr=0.3,0.1

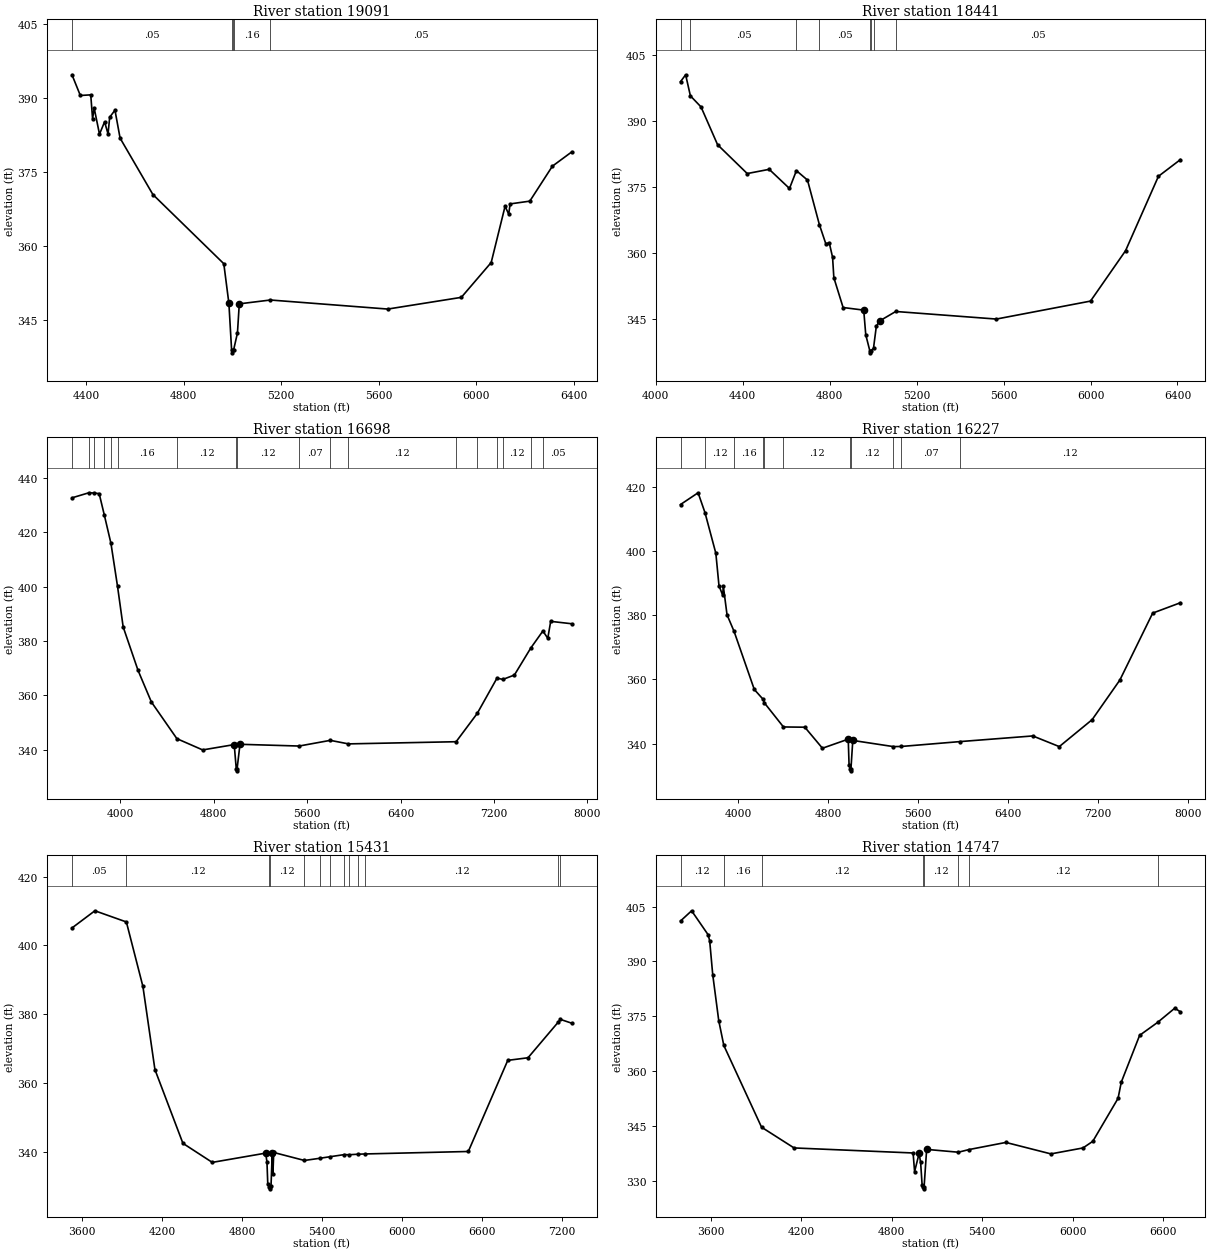
Type RM Length L Ch R = 1 ,19091   ,650,650,650
BEGIN DESCRIPTION:
SELF CREEK 35.0
END DESCRIPTION:
XS GIS Cut Line= 3
       3624584.9     10561183.87       3623954.7     10560621.37
      3622959.92     10559939.09
#Sta/Elev= 30
  4342.4  394.76  4376.7  390.55  4419.4  390.68  4426.9  385.84  4433.6  387.95
  4455.3  382.69  4476.2  385.19  4490.4  382.73  4497.1  386.13  4518.8  387.56
  4539.8  381.88  4674.3  370.42  4965.3  356.35  4986.2  348.28  4997.4  338.73
  5000.1  338.23  5003.4  338.73  5005.2  338.75  5021.3  342.27  5028.8  348.19
  5156.5  348.97    5638  347.13  5939.8  349.51  6062.3  356.59  6119.2  368.02
  6134.1  366.44  6140.1  368.51  6220.7  369.07  6313.4  376.18  6393.4   379.1
#Mann= 5 ,-1 , 0
  4342.4     .05       0  4997.4     .03       0  5003.4     .05       0
  5005.2     .16       0  5156.5     .05       0
Bank Sta=4986.2,5028.8
XS Rating Curve= 0 ,0
Exp/Cntr=0.3,0.1

Type RM Length L Ch R = 1 ,18441   ,1743,1743,1743
BEGIN DESCRIPTION:
SELF CREEK 34.0
END DESCRIPTION:
XS GIS Cut Line= 4
      3624730.75     10561173.49       3624642.2     10560600.54
      3624173.45     10560314.08      3623100.58     10559845.35
#Sta/Elev= 30
  4113.6  398.94  4137.2  400.51  4159.1  395.73    4208  393.21  4284.3  384.62
  4420.6  378.08  4521.7  379.04    4615  374.69  4646.8  378.74  4697.8   376.6
  4752.6  366.47  4782.3  362.11  4797.8  362.39  4813.2  359.07  4819.1  354.43
  4861.7  347.66  4956.5  347.07  4965.9  341.47  4984.4  337.87  4987.1  337.37
  4990.4  337.87  5001.5  338.41  5014.6  343.43    5030  344.62  5103.8  346.76
  5566.7  345.04  5999.9  349.12  6161.1  360.56  6312.4  377.46  6413.5  381.25
#Mann= 8 ,-1 , 0
  4113.6     .16       0  4159.1     .05       0  4646.8     .16       0
  4752.6     .05       0  4984.4     .03       0  4990.4     .05       0
  5001.5     .12       0  5103.8     .05       0
Bank Sta=4956.5,5030
XS Rating Curve= 0 ,0
Exp/Cntr=0.3,0.1

Type RM Length L Ch R = 1 ,16698   ,471,471,471
BEGIN DESCRIPTION:
SELF CREEK 33.0
END DESCRIPTION:
XS GIS Cut Line= 3
      3626465.13     10561413.06      3625428.66     10560183.87
      3622924.06      10559241.4
#Sta/Elev= 30
  3584.6  432.68  3729.3  434.54  3771.9  434.46  3817.7  434.23    3862  426.31
  3918.5  415.96  3974.8  400.17  4023.2  385.22  4150.8  369.22    4265  357.61
  4483.6  344.12  4704.5  339.98  4974.9  341.94  4992.8  332.79  4995.5  332.29
  4998.8  332.79  5024.4  342.05  5531.1  341.41  5798.2   343.5  5953.8   342.2
  6876.5     343  7057.3   353.4  7226.6  366.38  7277.5  365.91  7375.7  367.52
  7515.7  377.42  7619.9  383.71  7661.9  381.04  7686.8  387.26  7868.5  386.37
#Mann= 18 ,-1 , 0
  3584.6     .05       0  3729.3     .16       0  3771.9     .05       0
    3862     .16       0  3918.5     .12       0  3974.8     .16       0
  4483.6     .12       0  4992.8     .07       0  4998.8     .12       0
  5531.1     .07       0  5798.2     .05       0  5953.8     .12       0
  6876.5     .16       0  7057.3     .12       0  7226.6     .16       0
  7277.5     .12       0  7515.7     .16       0  7619.9     .05       0
Bank Sta=4974.9,5024.4
XS Rating Curve= 0 ,0
Exp/Cntr=0.3,0.1

Type RM Length L Ch R = 1 ,16227   ,796,796,796
BEGIN DESCRIPTION:
SELF CREEK 32.0
END DESCRIPTION:
XS GIS Cut Line= 3
      3627199.51     10560433.88      3625433.87     10559907.83
      3622980.78     10559032.85
#Sta/Elev= 30
    3486  414.45  3642.4  418.11  3703.5  411.96  3800.4  399.26  3828.3  389.16
  3861.5  386.18  3866.7  389.09  3899.9   380.1  3962.6  374.93  4142.4  356.84
    4221  353.77  4232.3  352.66  4401.6  345.17  4591.9  345.09  4748.5  338.54
    4978  341.37  4985.3  333.44  4995.9     332  4998.6   331.5  5001.9     332
  5018.5  340.97  5379.6  339.05  5449.6  339.09    5976  340.62  6619.5  342.37
  6855.3  339.05  7147.5  347.44    7394  359.77  7686.1  380.63  7932.8  383.86
#Mann= 11 ,-1 , 0
    3486     .05       0  3703.5     .12       0  3962.6     .16       0
    4221     .12       0  4232.3     .16       0  4401.6     .12       0
  4995.9     .07       0  5001.9     .12       0  5379.6     .05       0
  5449.6     .07       0    5976     .12       0
Bank Sta=4978,5018.5
XS Rating Curve= 0 ,0
Exp/Cntr=0.3,0.1

Type RM Length L Ch R = 1 ,15431   ,684,684,684
BEGIN DESCRIPTION:
SELF CREEK 31.0
END DESCRIPTION:
XS GIS Cut Line= 3
      3626871.41     10559475.54      3625402.62     10559402.62
      3623168.29     10558939.09
#Sta/Elev= 30
  3523.4  405.09  3695.4  410.09  3931.7  406.84  4055.9  388.08    4146  363.93
  4356.2  342.48  4576.5  336.94    4977  339.63    4987   337.1    4993  330.78
  5004.3  329.75    5007  329.25  5010.3  329.75  5017.5  330.16  5026.6   339.6
  5031.7  333.66  5037.9  339.82  5268.4   337.5  5382.9  338.13  5459.5  338.58
    5569  339.21    5600  339.16  5669.2  339.31  5721.6  339.39  6498.4  340.11
  6794.5   366.6  6946.6  367.36    7174  377.75    7190  378.51  7275.9  377.39
#Mann= 13 ,-1 , 0
  3523.4     .05       0  3931.7     .12       0  5004.3     .07       0
  5010.3     .12       0  5268.4     .07       0  5382.9     .05       0
  5459.5     .07       0    5569     .16       0    5600     .07       0
  5669.2     .16       0  5721.6     .12       0    7174     .16       0
    7190     .12       0
Bank Sta=4977,5026.6
XS Rating Curve= 0 ,0
Exp/Cntr=0.3,0.1

Type RM Length L Ch R = 1 ,14747   ,779,779,779
BEGIN DESCRIPTION:
SELF CREEK 30.0
END DESCRIPTION:
XS GIS Cut Line= 3
       3626673.4     10559017.21      3624522.41     10559006.79
      3623372.99     10558803.95
#Sta/Elev= 30
  3397.8  401.07  3471.6  403.87  3581.6  397.28  3591.6  395.59  3611.6  386.41
  3651.6  373.79  3685.4  366.98  3935.8   344.6  4151.6  338.92  4941.6  337.54
  4951.6  332.43  4981.6  337.43  4991.6  334.94  5001.6  328.74  5008.6  328.22
  5011.4  327.72  5014.6  328.22  5031.6  338.52  5242.1  337.75  5313.2  338.48
  5557.4  340.43  5856.3  337.29  6069.5  338.92  6134.5  340.74  6302.1   352.5
  6323.4  356.93  6445.3  369.76  6563.9  373.28  6678.8   377.2    6716  376.18
#Mann= 8 ,-1 , 0
  3397.8     .12       0  3685.4     .16       0  3935.8     .12       0
  5008.6     .07       0  5014.6     .12       0  5242.1     .07       0
  5313.2     .12       0  6563.9     .16       0
Bank Sta=4981.6,5031.6
XS Rating Curve= 0 ,0
Exp/Cntr=0.3,0.1