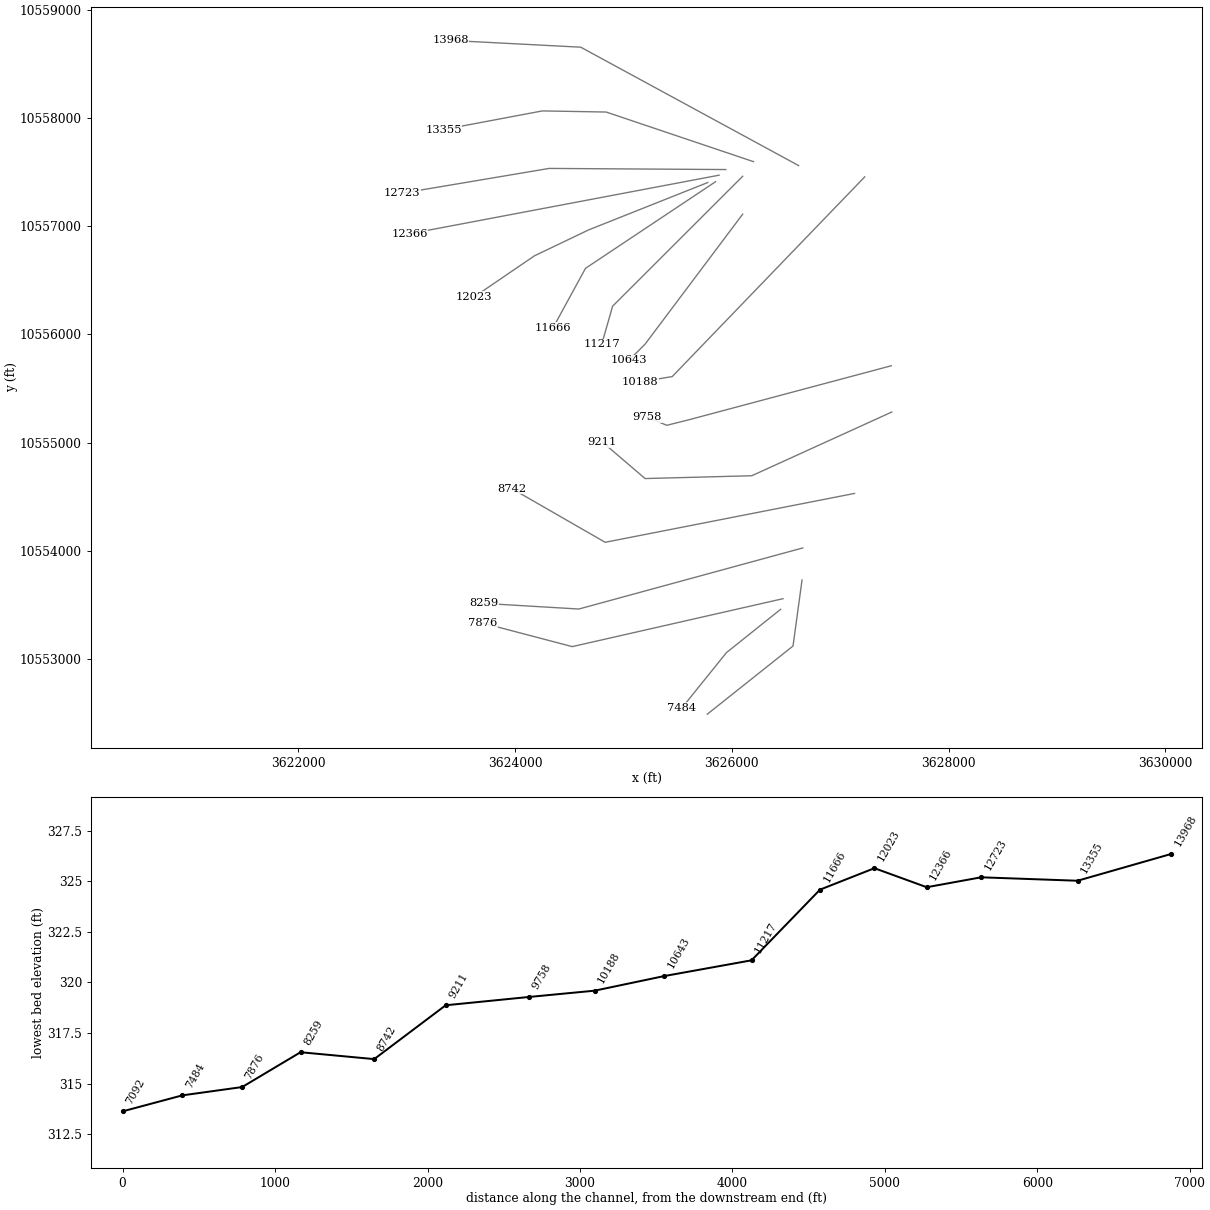
HEC-RAS study SELF CREEK.prj: SELF CREEK Base Level Engineering

--- SELF CREEK.g01 (geometry) --- (continued)

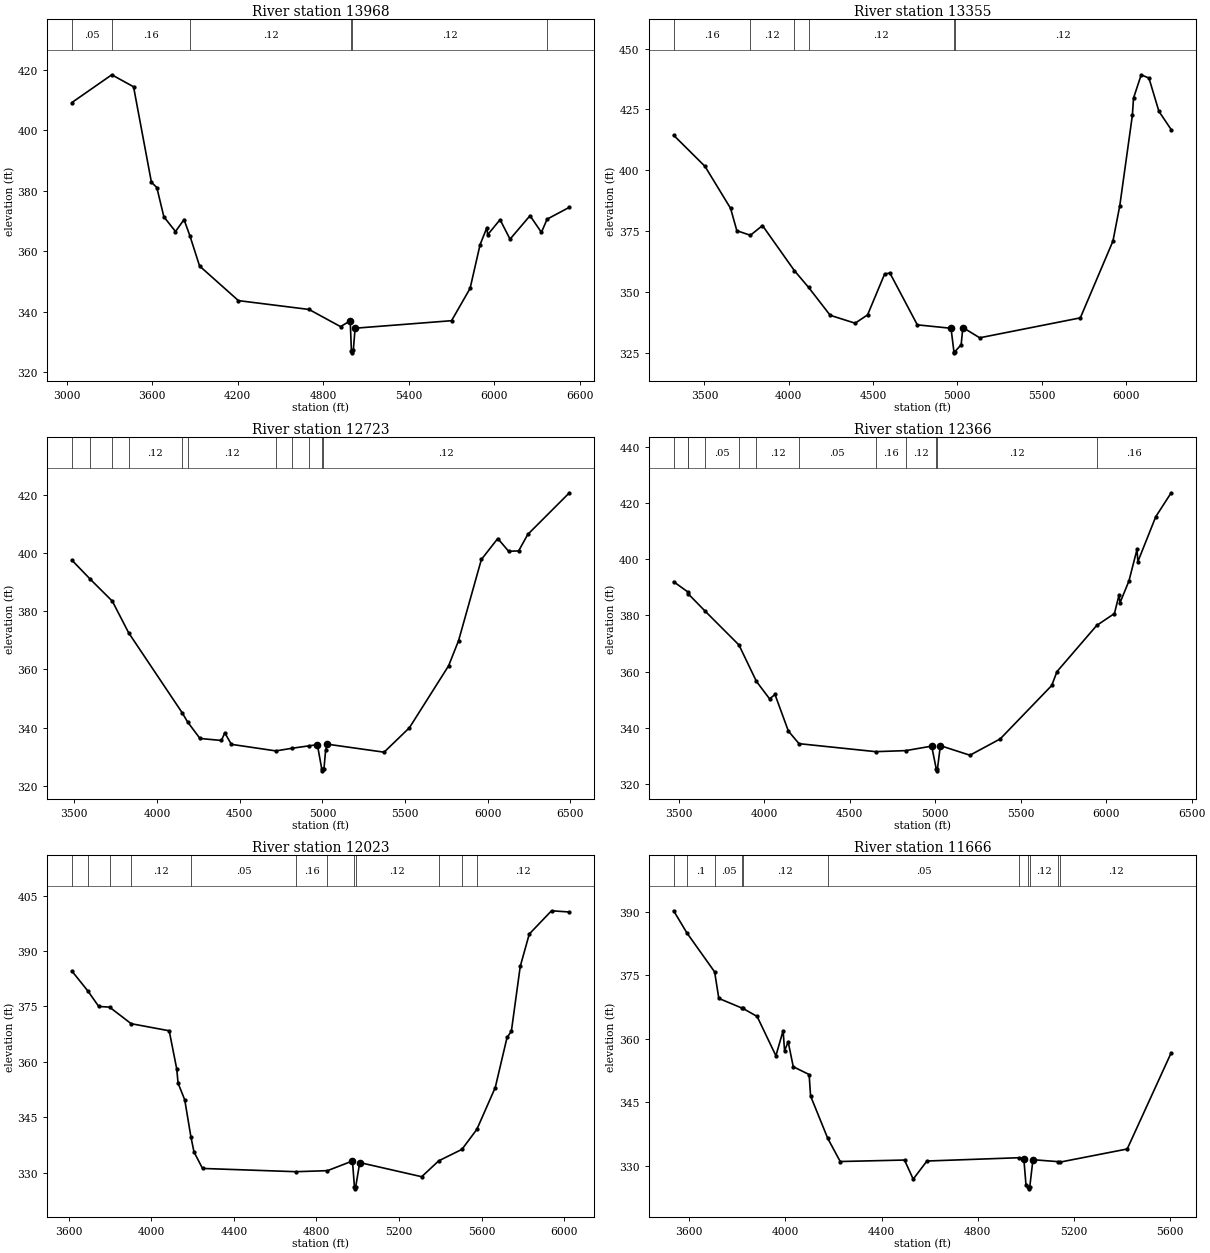
Type RM Length L Ch R = 1 ,13968   ,613,613,613
BEGIN DESCRIPTION:
SELF CREEK 29.0
END DESCRIPTION:
XS GIS Cut Line= 3
      3626616.19     10557558.86      3624605.74     10558652.62
      3623403.58     10558715.07
#Sta/Elev= 30
  3036.3  409.25  3316.6  418.46  3469.4  414.49  3594.8  382.86  3632.8   381.1
  3682.1  371.42  3763.8  366.53  3823.7  370.49  3865.2  365.07  3932.9   355.1
  4205.5  343.64  4701.4  340.71  4922.2  335.03  4990.2  336.92  4998.9  326.84
  5001.6  326.34  5004.9  326.84    5012  327.16  5024.6   334.5  5701.7  336.99
  5831.8   347.7  5901.9  362.19  5949.8  367.84  5954.9  365.45  6042.1  370.46
  6112.2     364  6252.4  371.78  6332.5  366.25  6372.3  370.63  6528.8  374.56
#Mann= 6 ,-1 , 0
  3036.3     .05       0  3316.6     .16       0  3865.2     .12       0
  4998.9     .07       0  5004.9     .12       0  6372.3     .16       0
Bank Sta=4990.2,5024.6
XS Rating Curve= 0 ,0
Exp/Cntr=0.3,0.1

Type RM Length L Ch R = 1 ,13355   ,632,632,632
BEGIN DESCRIPTION:
SELF CREEK 27.0
END DESCRIPTION:
XS GIS Cut Line= 4
      3626199.48     10557595.34      3624840.12     10558053.67
      3624251.58     10558064.08      3623340.13     10557892.21
#Sta/Elev= 30
  3317.5  414.42  3503.4  401.64  3655.1   384.4  3692.3   375.2  3772.7  373.32
  3844.4  377.32  4033.8  358.77  4118.1  351.89    4246  340.44  4393.8   337.2
  4467.7  340.62  4568.5  357.37  4599.9  357.83  4762.6  336.52  4962.6  335.11
  4979.6  325.52  4982.3  325.02  4985.6  325.52  5022.6  328.34  5032.6  335.43
  5132.6   331.2  5729.4  339.39  5922.7  370.91  5963.4  385.48    6038  422.57
  6044.8  429.66  6090.4  439.26  6136.4  437.89  6195.3  424.27  6268.2  416.74
#Mann= 6 ,-1 , 0
  3317.5     .16       0  3772.7     .12       0  4033.8     .16       0
  4118.1     .12       0  4979.6     .07       0  4985.6     .12       0
Bank Sta=4962.6,5032.6
XS Rating Curve= 0 ,0
Exp/Cntr=0.3,0.1

Type RM Length L Ch R = 1 ,12723   ,357,357,357
BEGIN DESCRIPTION:
SELF CREEK 26.0
END DESCRIPTION:
XS GIS Cut Line= 3
       3625944.3     10557522.42      3624314.08     10557532.83
      3622954.71     10557303.67
#Sta/Elev= 30
  3484.8  397.51  3596.2  390.95  3729.5  383.43  3828.4  372.55  4151.4  345.17
  4184.7  341.97  4259.5   336.3  4389.5  335.61  4409.5  338.24  4449.5  334.28
  4718.7  332.03  4817.6  332.95  4916.5  333.75  4969.5  334.17  4996.5  325.69
  4999.3  325.19  5002.5  325.69  5009.5  325.99  5019.5  332.26  5029.5  334.34
  5373.1  331.59  5526.1  339.98  5763.1  361.24  5823.6   369.9  5961.3  397.73
  6060.5  404.92  6126.1  400.55  6186.6  400.66    6242  406.34  6493.6  420.62
#Mann= 11 ,-1 , 0
  3484.8     .12       0  3596.2     .16       0  3729.5      .1       0
  3828.4     .12       0  4151.4      .1       0  4184.7     .12       0
  4718.7     .16       0  4817.6     .05       0  4916.5     .12       0
  4996.5     .07       0  5002.5     .12       0
Bank Sta=4969.5,5029.5
XS Rating Curve= 0 ,0
Exp/Cntr=0.3,0.1

Type RM Length L Ch R = 1 ,12366   ,343,343,343
BEGIN DESCRIPTION:
SELF CREEK 25.0
END DESCRIPTION:
XS GIS Cut Line= 2
      3625881.83     10557470.34      3623023.56     10556928.88
#Sta/Elev= 30
  3471.2  391.93  3552.9  388.36  3557.2  387.57  3653.1  381.61    3853  369.45
  3955.4  356.48  4032.2  350.29  4063.8  351.84  4141.9  338.85  4204.2  334.36
  4652.3  331.52  4829.2  331.89  4979.8  333.49  5007.3   325.2  5010.1   324.7
  5013.3   325.2  5030.7  333.65  5203.7  330.25  5380.6  336.05    5682  355.05
  5712.6  359.98  5944.9  376.39  6048.5  380.62  6075.8  387.29  6080.9  384.41
  6133.2  392.18  6180.5  403.42  6185.5  399.06  6290.2  415.05  6380.3  423.55
#Mann= 12 ,-1 , 0
  3471.2     .12       0  3552.9     .16       0  3557.2      .1       0
  3653.1     .05       0    3853      .1       0  3955.4     .12       0
  4204.2     .05       0  4652.3     .16       0  4829.2     .12       0
  5007.3     .07       0  5013.3     .12       0  5944.9     .16       0
Bank Sta=4979.8,5030.7
XS Rating Curve= 0 ,0
Exp/Cntr=0.3,0.1

Type RM Length L Ch R = 1 ,12023   ,357,357,357
BEGIN DESCRIPTION:
SELF CREEK 24.0
END DESCRIPTION:
XS GIS Cut Line= 4
      3625777.63     10557402.63      3624678.66     10556965.12
      3624178.66     10556725.54      3623622.96     10556346.42
#Sta/Elev= 30
  3615.3   384.6  3692.9  379.19  3745.6     375  3797.7  374.83  3902.6  370.34
  4086.8  368.42  4123.3   358.1  4129.8  354.25  4162.1  349.72    4192  339.71
  4206.9  335.62  4248.2  331.16  4700.3  330.28  4853.5  330.56  4974.5  333.18
  4984.1  326.14  4986.9  325.64  4990.1  326.14  5009.8  332.75  5309.9  328.92
  5392.3  333.22  5504.7  336.32    5577  341.73  5666.2  353.06  5723.3  366.62
  5744.2  368.28  5787.2  385.84    5831  394.61  5938.7   400.9  6025.3  400.57
#Mann= 12 ,-1 , 0
  3615.3      .1       0  3692.9     .05       0  3797.7      .1       0
  3902.6     .12       0    4192     .05       0  4700.3     .16       0
  4853.5     .12       0  4984.1     .07       0  4990.1     .12       0
  5392.3     .05       0  5504.7     .07       0    5577     .12       0
Bank Sta=4974.5,5009.8
XS Rating Curve= 0 ,0
Exp/Cntr=0.3,0.1

Type RM Length L Ch R = 1 ,11666   ,449,449,449
BEGIN DESCRIPTION:
SELF CREEK 23.0
END DESCRIPTION:
XS GIS Cut Line= 3
      3625849.64     10557410.21      3624649.61     10556610.19
      3624349.59     10556060.15
#Sta/Elev= 30
  3535.1  390.24  3589.8  385.05  3705.6   375.8  3722.9  369.55  3821.4  367.21
  3822.4  367.21  3882.2  365.29  3960.3     356  3990.3  361.93  3996.3   357.2
  4011.4  359.28  4032.4  353.42  4098.5  351.57  4104.5   346.5  4175.8  336.51
  4227.7  331.03  4495.1  331.38  4531.2  326.87  4588.3  331.15  4972.6  331.93
  4991.1  331.74  5000.1  325.57    5010  325.08  5012.7  324.58    5016  325.08
  5029.1  331.46  5133.7     331  5141.7  330.89  5421.1  333.99  5603.9   356.7
#Mann= 11 ,-1 , 0
  3535.1     .16       0  3589.8      .1       0  3705.6     .05       0
  3821.4      .1       0  3822.4     .12       0  4175.8     .05       0
  4972.6     .12       0    5010     .07       0    5016     .12       0
  5133.7     .07       0  5141.7     .12       0
Bank Sta=4991.1,5029.1
XS Rating Curve= 0 ,0
Exp/Cntr=0.3,0.1

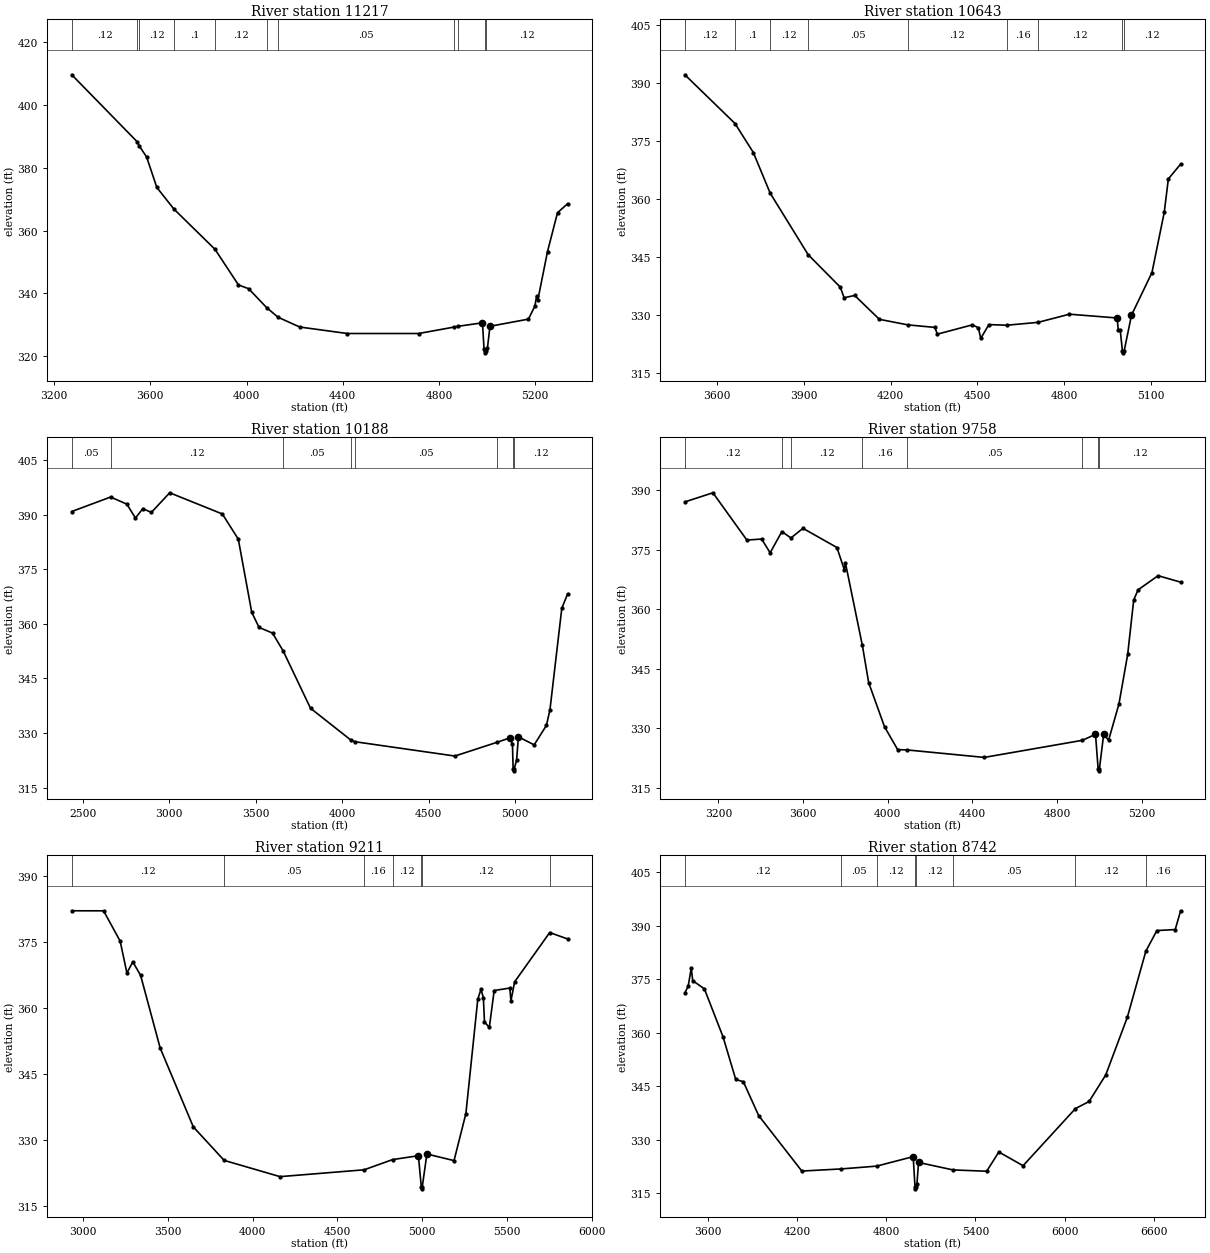
Type RM Length L Ch R = 1 ,11217   ,574,574,574
BEGIN DESCRIPTION:
SELF CREEK 22.0
END DESCRIPTION:
XS GIS Cut Line= 3
      3626099.62      10557460.2      3624899.61     10556260.19
       3624799.6     10555910.17
#Sta/Elev= 30
  3273.4  409.69  3545.2  388.36  3553.4  387.08  3584.5  383.51    3627   373.8
  3697.8  366.93  3869.1  354.06  3966.4  342.73  4008.8  341.52  4083.6   335.5
  4130.9  332.44  4220.9  329.32  4418.9  327.25  4715.9  327.25  4860.7  329.27
  4878.8  329.54  4980.9  330.66  4987.4  322.29  4989.6  321.59  4992.3  321.09
  4995.6  321.59  5001.7  322.69  5012.1  329.55    5172  331.83  5199.3  336.07
  5205.8  339.21    5211  337.92  5251.3  353.36  5292.9  365.75  5334.5  368.57
#Mann= 11 ,-1 , 0
  3273.4     .12       0  3545.2      .1       0  3553.4     .12       0
  3697.8      .1       0  3869.1     .12       0  4083.6      .1       0
  4130.9     .05       0  4860.7     .16       0  4878.8     .12       0
  4989.6     .07       0  4995.6     .12       0
Bank Sta=4980.9,5012.1
XS Rating Curve= 0 ,0
Exp/Cntr=0.3,0.1

Type RM Length L Ch R = 1 ,10643   ,455,455,455
BEGIN DESCRIPTION:
SELF CREEK 21.0
END DESCRIPTION:
XS GIS Cut Line= 3
      3626099.58     10557110.15      3625199.61     10555910.19
       3625049.6     10555760.18
#Sta/Elev= 30
  3489.8  392.18    3663  379.58  3726.2  372.09  3784.4  361.58  3915.6  345.67
  4026.2  337.32  4039.8  334.55  4076.2  335.14  4161.6  328.97  4259.7  327.54
  4353.3  326.88  4361.6  325.14  4482.5  327.54  4503.3   326.8  4511.6  324.04
  4539.8  327.61  4602.2  327.45  4709.5  328.19  4817.9   330.3  4982.5  329.32
  4986.6  326.17  4993.3  326.17  5000.9  320.81  5003.6  320.31  5006.9  320.81
  5032.2  330.05  5102.9  341.05  5145.3  356.62  5159.5  365.26  5201.9  369.09
#Mann= 9 ,-1 , 0
  3489.8     .12       0    3663      .1       0  3784.4     .12       0
  3915.6     .05       0  4259.7     .12       0  4602.2     .16       0
  4709.5     .12       0  5000.9     .07       0  5006.9     .12       0
Bank Sta=4982.5,5032.2
XS Rating Curve= 0 ,0
Exp/Cntr=0.3,0.1

Type RM Length L Ch R = 1 ,10188   ,430,430,430
BEGIN DESCRIPTION:
SELF CREEK 20.0
END DESCRIPTION:
XS GIS Cut Line= 3
       3627225.5     10557454.67      3625449.61     10555610.19
       3625149.6     10555560.19
#Sta/Elev= 30
  2437.3  390.89  2661.7  394.87  2755.8  392.91  2805.2  389.09  2847.7  391.67
  2897.3  390.65  3003.3  396.04  3307.4  390.21  3399.5   383.3  3477.2  363.18
  3519.6  359.02  3597.3  357.47  3658.9  352.55  3816.8   336.8  4052.1  327.97
  4075.7  327.58  4651.1  323.66    4892   327.4  4969.6  328.66  4983.7  326.93
  4987.7  320.09  4990.4  319.59  4993.7  320.09  5007.9   322.6    5018  328.94
  5109.3  326.73  5180.2   332.1  5200.5  336.43  5268.9   364.3  5301.9  368.16
#Mann= 8 ,-1 , 0
  2437.3     .05       0  2661.7     .12       0  3658.9     .05       0
  4052.1     .16       0  4075.7     .05       0    4892     .12       0
  4987.7     .07       0  4993.7     .12       0
Bank Sta=4969.6,5018
XS Rating Curve= 0 ,0
Exp/Cntr=0.3,0.1

Type RM Length L Ch R = 1 ,9758    ,547,547,547
BEGIN DESCRIPTION:
SELF CREEK 19.0
END DESCRIPTION:
XS GIS Cut Line= 4
      3627470.36     10555709.93      3625599.61     10555210.19
      3625399.61     10555160.19      3625216.09     10555235.56
#Sta/Elev= 30
    3042  386.98  3174.4  389.28  3334.7  377.38  3404.5  377.63  3444.6  374.17
  3500.1  379.51  3542.8  377.91  3599.7  380.33    3760   375.5  3794.9  369.91
  3800.1  371.63  3880.1  350.85  3909.9  341.47  3984.7  330.38  4046.8  324.62
  4090.2  324.55  4455.5  322.66  4919.5  326.97  4980.9  328.48  4993.4  319.78
  4996.1  319.28  4999.4  319.78  5019.6  328.49  5042.8  326.99  5091.7  336.13
    5133  348.63  5161.3  362.28  5181.9  364.84  5276.5  368.41  5382.9  366.78
#Mann= 8 ,-1 , 0
    3042     .12       0  3500.1     .16       0  3542.8     .12       0
  3880.1     .16       0  4090.2     .05       0  4919.5     .12       0
  4993.4     .07       0  4999.4     .12       0
Bank Sta=4980.9,5019.6
XS Rating Curve= 0 ,0
Exp/Cntr=0.3,0.1

Type RM Length L Ch R = 1 ,9211    ,469,469,469
BEGIN DESCRIPTION:
SELF CREEK 18.0
END DESCRIPTION:
XS GIS Cut Line= 4
      3627475.56     10555282.85      3626183.87     10554694.29
      3625199.49     10554668.25      3624805.06      10555005.6
#Sta/Elev= 30
  2933.4     382    3121  381.99  3218.7  375.11  3258.6  367.87  3293.3   370.4
  3339.4  367.32  3454.6  350.85    3650  332.94  3831.8  325.33  4161.5  321.64
  4657.2  323.19  4825.1  325.51  4977.3  326.39  4994.3  319.37  4997.1  318.87
  5000.3  319.37  5027.4  326.78  5187.4  325.28  5257.4  335.97  5327.5  361.92
  5346.1  364.16  5360.4  362.29    5367  356.77  5395.5  355.51  5424.1   363.9
  5516.3  364.45  5522.9  361.55  5544.8  365.87  5751.6  377.06  5856.6  375.61
#Mann= 7 ,-1 , 0
  2933.4     .12       0  3831.8     .05       0  4657.2     .16       0
  4825.1     .12       0  4994.3     .07       0  5000.3     .12       0
  5751.6     .16       0
Bank Sta=4977.3,5027.4
XS Rating Curve= 0 ,0
Exp/Cntr=0.3,0.1

Type RM Length L Ch R = 1 ,8742    ,483,483,483
BEGIN DESCRIPTION:
SELF CREEK 17.0
END DESCRIPTION:
XS GIS Cut Line= 3
      3627131.52     10554530.82      3624831.16     10554079.43
      3623973.23      10554573.4
#Sta/Elev= 30
  3446.6  371.17  3468.9   373.1  3489.3  378.09  3499.5  374.63  3577.8  372.33
  3703.3  358.86  3788.7  346.91  3840.1  346.26    3943  336.76  4233.2   321.2
  4494.9  321.79    4736  322.58  4982.1  325.25  4994.5  316.71  4997.3  316.21
  5000.5  316.71  5007.7  317.64  5017.9  323.61    5250  321.52  5476.5  321.15
  5558.2  326.55  5721.1   322.7  6073.1  338.72  6165.4  340.73  6277.3  348.19
  6422.6  364.38  6546.9  382.91  6620.9  388.69  6744.4  388.97  6780.8  394.24
#Mann= 8 ,-1 , 0
  3446.6     .12       0  4494.9     .05       0    4736     .12       0
  4994.5     .07       0  5000.5     .12       0    5250     .05       0
  6073.1     .12       0  6546.9     .16       0
Bank Sta=4982.1,5017.9
XS Rating Curve= 0 ,0
Exp/Cntr=0.3,0.1

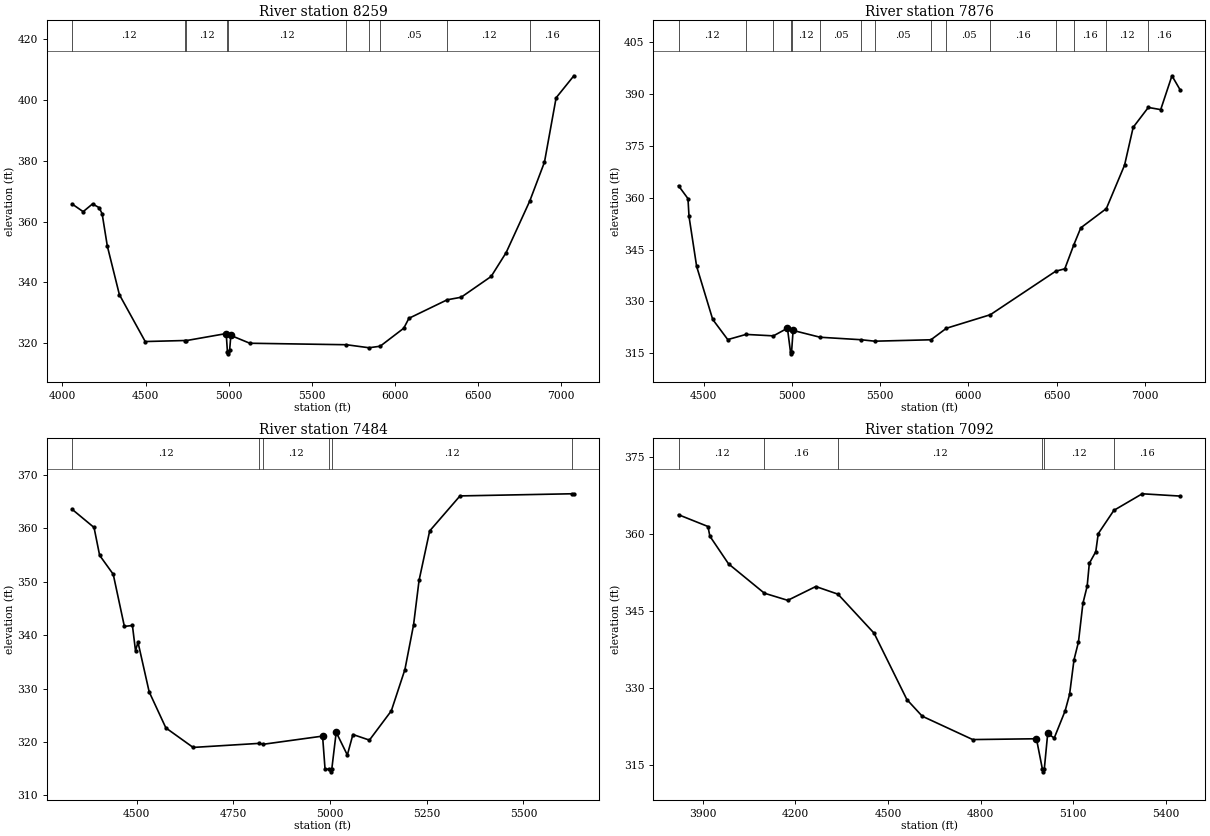
Type RM Length L Ch R = 1 ,8259    ,383,383,383
BEGIN DESCRIPTION:
SELF CREEK 16.0
END DESCRIPTION:
XS GIS Cut Line= 3
      3626654.08     10554027.35      3624588.11     10553463.11
      3623713.09     10553515.09
#Sta/Elev= 30
  4057.9  365.77  4124.7  363.25  4180.9  365.79  4220.6  364.57  4238.8  362.55
  4269.9  351.96  4342.4     336  4497.9  320.59  4737.7  320.93  4745.7  320.91
  4985.1  323.21  4992.5  317.05  4995.2  316.55  4998.5  317.05  5005.9  317.96
    5013  322.59    5127  320.03  5708.1  319.54    5844  318.55  5911.1  319.05
  6052.9  324.96    6084  328.22  6314.2   334.3  6398.3  335.14  6578.7  341.97
  6668.9  349.81  6810.7  366.72  6899.3  379.51  6969.4  400.65  7076.1  407.88
#Mann= 10 ,-1 , 0
  4057.9     .12       0  4737.7     .16       0  4745.7     .12       0
  4992.5     .07       0  4998.5     .12       0  5708.1     .05       0
    5844     .12       0  5911.1     .05       0  6314.2     .12       0
  6810.7     .16       0
Bank Sta=4985.1,5013
XS Rating Curve= 0 ,0
Exp/Cntr=0.3,0.1

Type RM Length L Ch R = 1 ,7876    ,392,392,392
BEGIN DESCRIPTION:
SELF CREEK 15.0
END DESCRIPTION:
XS GIS Cut Line= 3
      3626471.79      10553558.6      3624527.34     10553115.89
      3623703.69     10553332.64
#Sta/Elev= 30
  4356.3  363.46  4409.8  359.74  4415.8  354.57  4458.9  340.15  4550.1  324.79
  4635.4  318.95  4739.1  320.45  4894.5  320.03  4973.9  322.25  4991.4  315.33
  4994.2  314.83  4997.4  315.33    5006   321.6  5159.3  319.63  5389.4  318.92
  5469.2  318.49  5787.9   318.9  5875.5  322.23  6124.8  326.15  6495.5  338.74
    6547  339.43  6598.8  346.46  6637.7  351.29  6782.6  356.85  6885.9  369.42
  6934.8  380.37  7020.6  386.12  7090.9  385.49  7154.7  395.28  7202.2  391.11
#Mann= 15 ,-1 , 0
  4356.3     .12       0  4739.1     .16       0  4894.5     .12       0
  4991.4     .07       0  4997.4     .12       0  5159.3     .05       0
  5389.4     .12       0  5469.2     .05       0  5787.9     .12       0
  5875.5     .05       0  6124.8     .16       0  6495.5     .05       0
  6598.8     .16       0  6782.6     .12       0  7020.6     .16       0
Bank Sta=4973.9,5006
XS Rating Curve= 0 ,0
Exp/Cntr=0.3,0.1

Type RM Length L Ch R = 1 ,7484    ,392,392,392
BEGIN DESCRIPTION:
SELF CREEK 14.0
END DESCRIPTION:
XS GIS Cut Line= 3
      3626449.58     10553460.17      3625949.61     10553060.19
      3625538.02     10552548.44
#Sta/Elev= 30
  4333.4  363.58  4390.2  360.17  4404.6  354.96  4439.8  351.41  4468.6  341.65
  4489.4  341.82  4497.4  337.08  4503.8  338.69  4532.7  329.39  4575.9  322.64
  4646.3  318.99    4817  319.75  4827.4  319.58  4980.9  321.11  4987.3  314.93
  4998.7  314.92  5001.4  314.42  5004.7  314.92  5016.1  321.83  5044.9  317.57
  5059.3  321.41    5102  320.36  5158.5  325.83  5193.7  333.57    5216   341.9
  5230.3  350.27  5257.7  359.52  5336.1  366.08  5624.7  366.48  5630.4  366.45
#Mann= 6 ,-1 , 0
  4333.4     .12       0    4817     .16       0  4827.4     .12       0
  4998.7     .07       0  5004.7     .12       0  5624.7      .1       0
Bank Sta=4980.9,5016.1
XS Rating Curve= 0 ,0
Exp/Cntr=0.3,0.1

Type RM Length L Ch R = 1 ,7092    ,485,485,485
BEGIN DESCRIPTION:
SELF CREEK 13.0
END DESCRIPTION:
XS GIS Cut Line= 3
       3626647.4      10553730.7      3626564.08     10553121.37
      3625773.49     10552492.02
#Sta/Elev= 30
  3821.6  363.67    3917  361.38    3923  359.51  3983.6  354.11  4099.6   348.4
  4175.4  347.01  4266.2   349.7  4338.1  348.21  4455.1  340.61  4561.3   327.7
    4611  324.46  4774.6  319.91    4981  320.07  5000.4  314.13  5003.2  313.63
  5006.4  314.13  5017.5   321.1  5038.6  320.21  5073.9  325.49  5088.3  328.69
  5102.7  335.44  5117.1   338.9  5131.5  346.41  5145.3  349.77  5152.3  354.21
  5173.2  356.48  5181.2  359.99  5231.8  364.52  5323.7  367.75  5447.1   367.3
#Mann= 6 ,-1 , 0
  3821.6     .12       0  4099.6     .16       0  4338.1     .12       0
  5000.4     .07       0  5006.4     .12       0  5231.8     .16       0
Bank Sta=4981,5017.5
XS Rating Curve= 0 ,0
Exp/Cntr=0.3,0.1