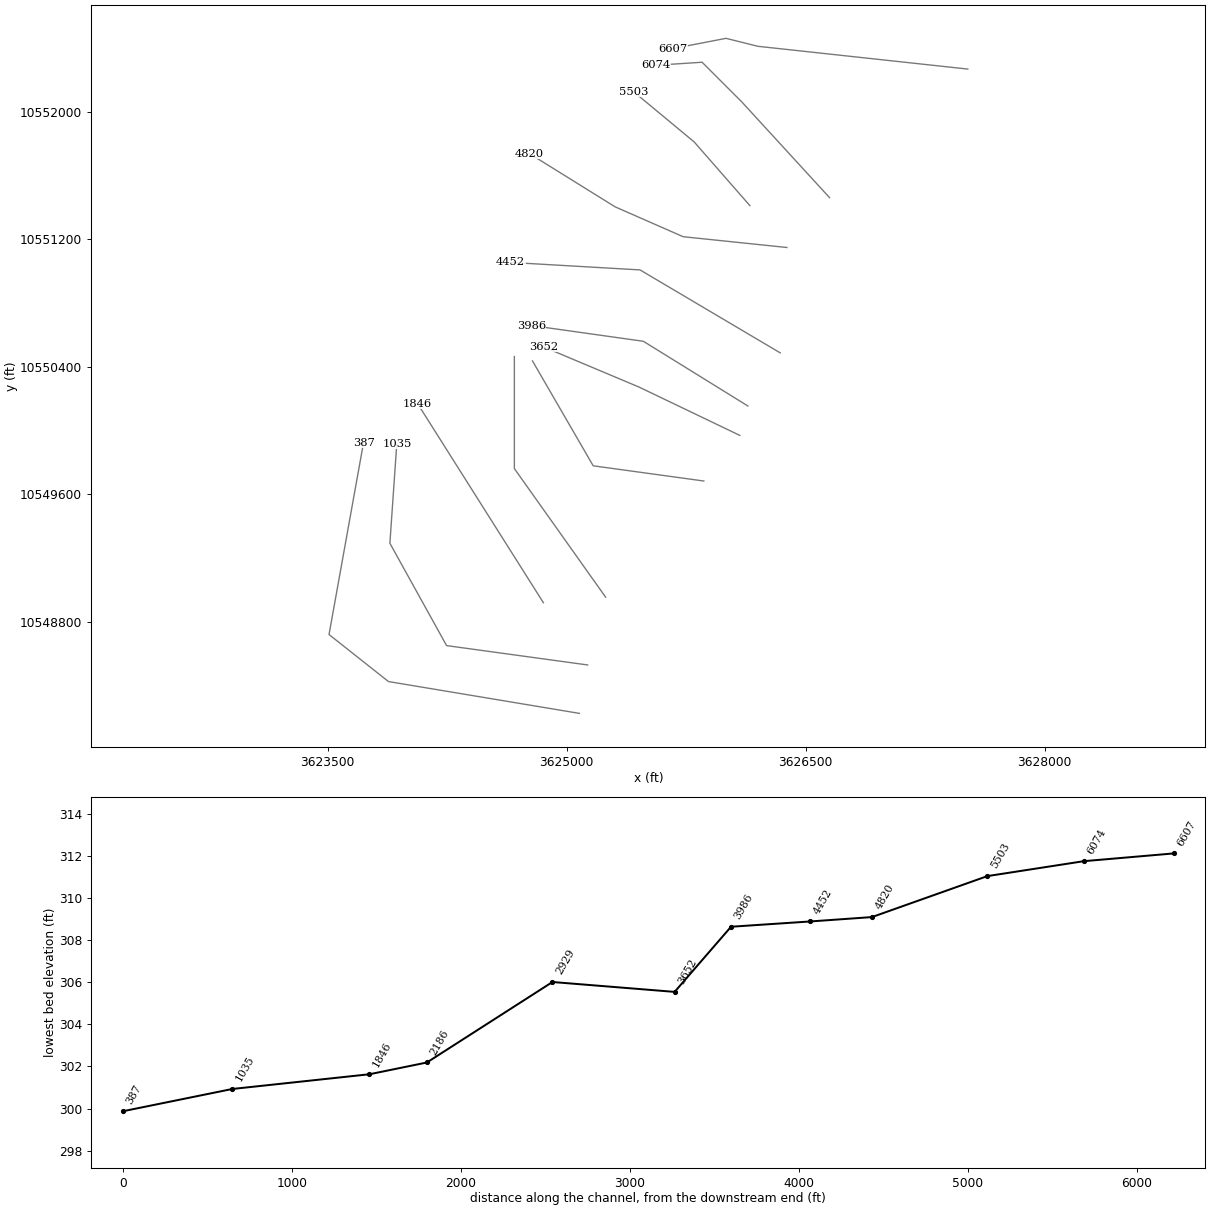
HEC-RAS study SELF CREEK.prj: SELF CREEK Base Level Engineering

--- SELF CREEK.g01 (geometry) --- (continued)

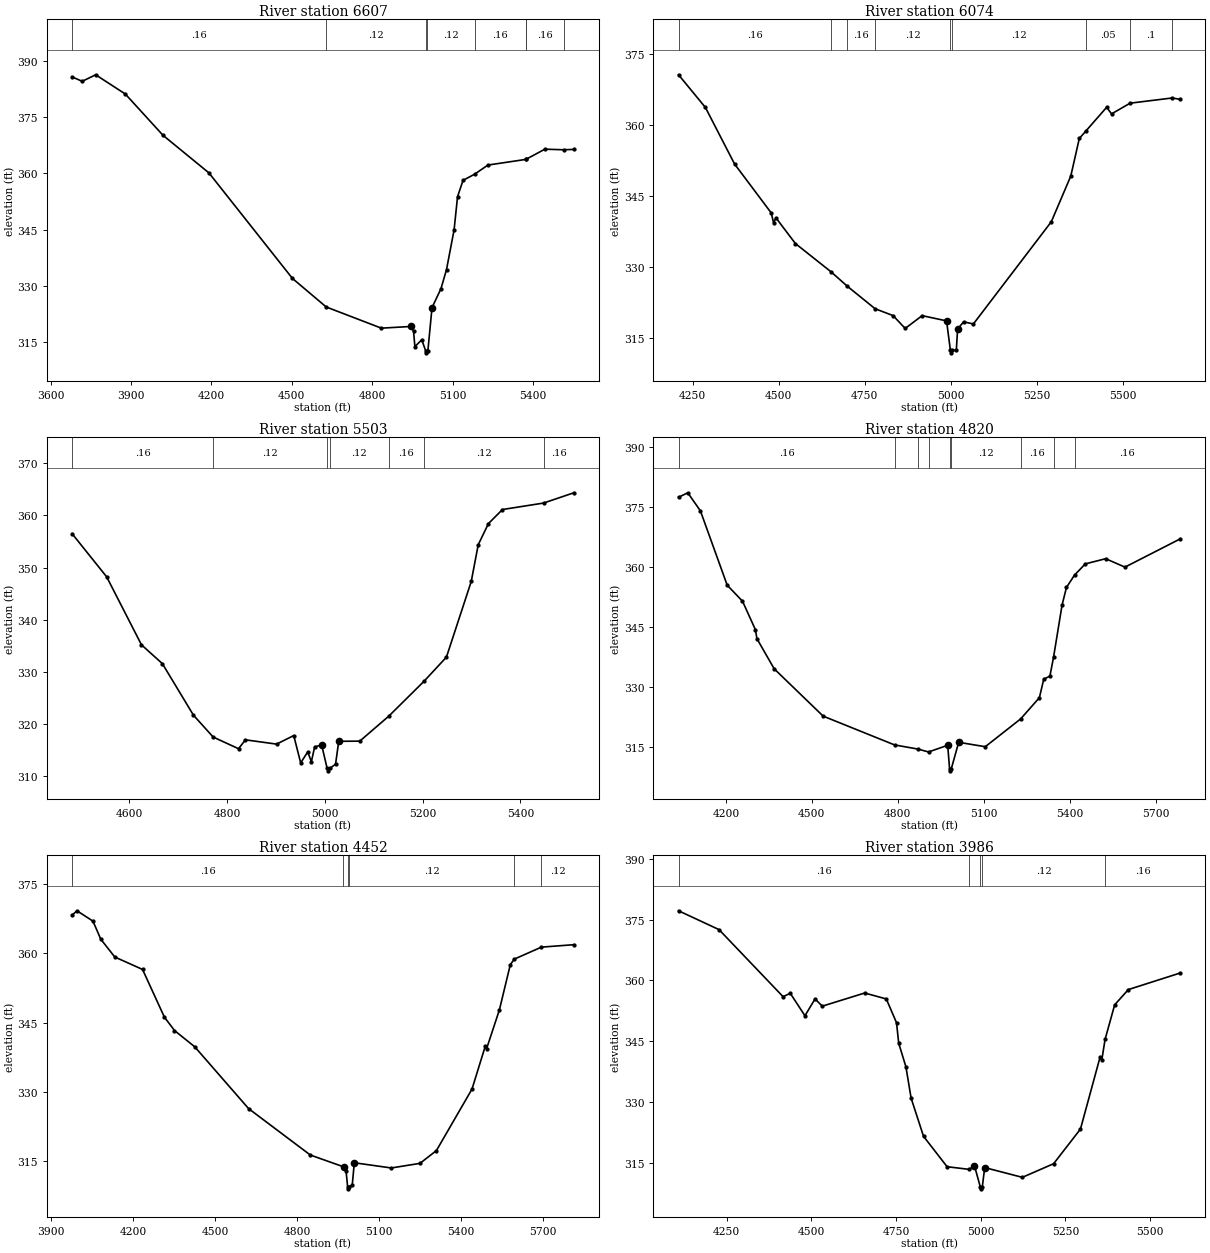
Type RM Length L Ch R = 1 ,6607    ,533,533,533
BEGIN DESCRIPTION:
SELF CREEK 12.0
END DESCRIPTION:
XS GIS Cut Line= 4
      3627517.22     10552267.21      3626199.61     10552410.19
      3625999.61     10552460.19      3625664.52     10552395.41
#Sta/Elev= 30
  3679.8   385.7  3717.6  384.52  3767.9  386.26  3878.6  381.13  4019.4  370.11
  4190.4  360.12  4502.2  331.98  4628.4  324.36  4834.1  318.72  4944.8  319.17
  4954.3  317.88  4959.3   313.8    4985  315.63  4999.6  312.64  5002.4  312.14
  5005.6  312.64  5007.7  312.64  5023.2  324.19  5056.7  329.25  5077.3  334.34
  5105.6  344.92  5118.5  353.78  5139.1  358.13  5182.3  359.76  5231.7  362.19
  5372.3  363.69  5374.6  363.75  5444.4  366.43  5514.4  366.27  5552.6  366.37
#Mann= 8 ,-1 , 0
  3679.8     .16       0  4628.4     .12       0  4999.6     .07       0
  5005.6     .12       0  5182.3     .16       0  5372.3     .12       0
  5374.6     .16       0  5514.4      .1       0
Bank Sta=4944.8,5023.2
XS Rating Curve= 0 ,0
Exp/Cntr=0.3,0.1

Type RM Length L Ch R = 1 ,6074    ,571,571,571
BEGIN DESCRIPTION:
SELF CREEK 11.0
END DESCRIPTION:
XS GIS Cut Line= 4
      3626649.58     10551460.22      3626099.61     10552060.19
      3625849.61     10552310.19      3625560.38     10552291.24
#Sta/Elev= 30
  4208.9  370.61  4286.9   363.7  4371.6  351.73    4478  341.39  4484.8  339.35
  4492.2   340.3  4548.3   334.9  4651.4  328.94  4699.5  325.84  4779.8   321.1
    4832  319.65  4867.1  316.93  4916.4  319.64  4987.3  318.53  4998.5  312.27
  5001.3  311.77  5004.5  312.27  5015.7  312.37  5019.4  316.81  5036.9  318.33
  5065.2  317.88  5291.5  339.51  5348.1  349.18  5372.8  357.13  5391.1  358.64
  5452.2  363.73  5466.5  362.33  5520.3   364.6  5642.5   365.7  5666.2  365.41
#Mann= 9 ,-1 , 0
  4208.9     .16       0  4651.4     .12       0  4699.5     .16       0
  4779.8     .12       0  4998.5     .07       0  5004.5     .12       0
  5391.1     .05       0  5520.3      .1       0  5642.5     .12       0
Bank Sta=4987.3,5019.4
XS Rating Curve= 0 ,0
Exp/Cntr=0.3,0.1

Type RM Length L Ch R = 1 ,5503    ,683,683,683
BEGIN DESCRIPTION:
SELF CREEK 10.0
END DESCRIPTION:
XS GIS Cut Line= 3
      3626149.61     10551410.18      3625799.61     10551810.19
      3625419.12     10552125.86
#Sta/Elev= 30
  4483.5   356.5  4554.2  348.23  4625.4   335.2  4668.1   331.6  4731.7  321.72
    4772  317.53  4823.8   315.3    4838     317  4901.6  316.18  4936.7  317.82
  4950.9  312.58  4965.2  314.68  4972.8  312.83  4979.4  315.63  4993.7  316.04
  5004.9  311.56  5007.6  311.06  5010.9  311.56  5022.2  312.34  5028.7  316.72
  5071.7  316.75  5130.8  321.52    5203  328.21  5248.9  332.85  5299.6  347.34
  5313.9  354.38  5334.7  358.42  5363.4  361.12  5447.4  362.36  5509.4  364.33
#Mann= 7 ,-1 , 0
  4483.5     .16       0    4772     .12       0  5004.9     .07       0
  5010.9     .12       0  5130.8     .16       0    5203     .12       0
  5447.4     .16       0
Bank Sta=4993.7,5028.7
XS Rating Curve= 0 ,0
Exp/Cntr=0.3,0.1

Type RM Length L Ch R = 1 ,4820    ,368,368,368
BEGIN DESCRIPTION:
SELF CREEK 9.0
END DESCRIPTION:
XS GIS Cut Line= 4
      3626381.75     10551147.42      3625730.74     10551215.12
      3625303.66     10551402.62      3624767.83     10551735.57
#Sta/Elev= 30
  4034.6  377.37  4066.9  378.49  4110.9  373.99  4204.5  355.43  4257.9  351.44
  4303.1  344.31  4308.2  342.09  4368.5  334.57  4539.5  322.76  4788.6  315.58
  4870.4  314.54  4907.3  313.82  4974.3  315.49  4980.8  309.61  4983.5  309.11
  4986.8  309.61  5012.6  316.23  5105.4  315.13    5229  322.07  5294.4  327.37
  5309.7     332    5331  332.72  5343.7  337.41  5373.5  350.46  5388.8  354.86
    5417  357.95  5454.7  360.75  5525.8  362.04  5593.1  359.94  5786.4     367
#Mann= 9 ,-1 , 0
  4034.6     .16       0  4788.6     .12       0  4870.4     .16       0
  4907.3     .12       0  4980.8     .07       0  4986.8     .12       0
    5229     .16       0  5343.7     .12       0    5417     .16       0
Bank Sta=4974.3,5012.6
XS Rating Curve= 0 ,0
Exp/Cntr=0.3,0.1

Type RM Length L Ch R = 1 ,4452    ,466,466,466
BEGIN DESCRIPTION:
SELF CREEK 8.0
END DESCRIPTION:
XS GIS Cut Line= 3
      3626340.09     10550485.97      3625459.91     10551006.79
      3624647.39     10551053.67
#Sta/Elev= 30
  3976.9   368.3  3994.9  369.25  4053.4     367    4082  363.08  4133.4  359.21
  4234.8  356.52  4314.7  346.18  4351.8  343.26  4425.9  339.73  4622.9  326.32
  4848.9  316.24  4969.1  313.71  4973.9  313.74  4979.7  312.79  4985.4   309.4
  4988.1   308.9  4991.4   309.4  5002.3  309.65  5009.9  314.56  5145.3  313.43
  5250.3  314.43  5310.4   317.2  5440.7  330.55  5489.2  339.85  5494.2  339.34
  5540.8  347.71  5580.9  357.55  5595.3  358.75  5694.6  361.36  5813.5  361.89
#Mann= 6 ,-1 , 0
  3976.9     .16       0  4969.1     .12       0  4985.4     .07       0
  4991.4     .12       0  5595.3     .16       0  5694.6     .12       0
Bank Sta=4973.9,5009.9
XS Rating Curve= 0 ,0
Exp/Cntr=0.3,0.1

Type RM Length L Ch R = 1 ,3986    ,334,334,334
BEGIN DESCRIPTION:
SELF CREEK 7.0
END DESCRIPTION:
XS GIS Cut Line= 3
      3626136.98     10550152.64      3625480.74     10550558.87
      3624777.57     10550657.84
#Sta/Elev= 30
  4107.5  377.15  4227.1  372.51  4416.2  355.99  4437.5  356.82  4480.8  351.29
  4510.7  355.44    4532  353.65  4657.2  356.89  4721.1  355.43  4751.3  349.56
  4757.7  344.53    4779  338.71  4794.4  330.98    4831  321.59  4900.6   314.1
  4966.3  313.44  4981.4  314.34  4998.6  309.15  5001.4  308.65  5004.6  309.15
  5011.7  313.89  5122.8  311.48  5215.2  314.84  5294.5  323.38  5352.6  341.16
  5357.6  340.41  5367.1  345.45  5395.5  353.98  5435.9  357.74  5589.4  361.83
#Mann= 5 ,-1 , 0
  4107.5     .16       0  4966.3     .12       0  4998.6     .07       0
  5004.6     .12       0  5367.1     .16       0
Bank Sta=4981.4,5011.7
XS Rating Curve= 0 ,0
Exp/Cntr=0.3,0.1

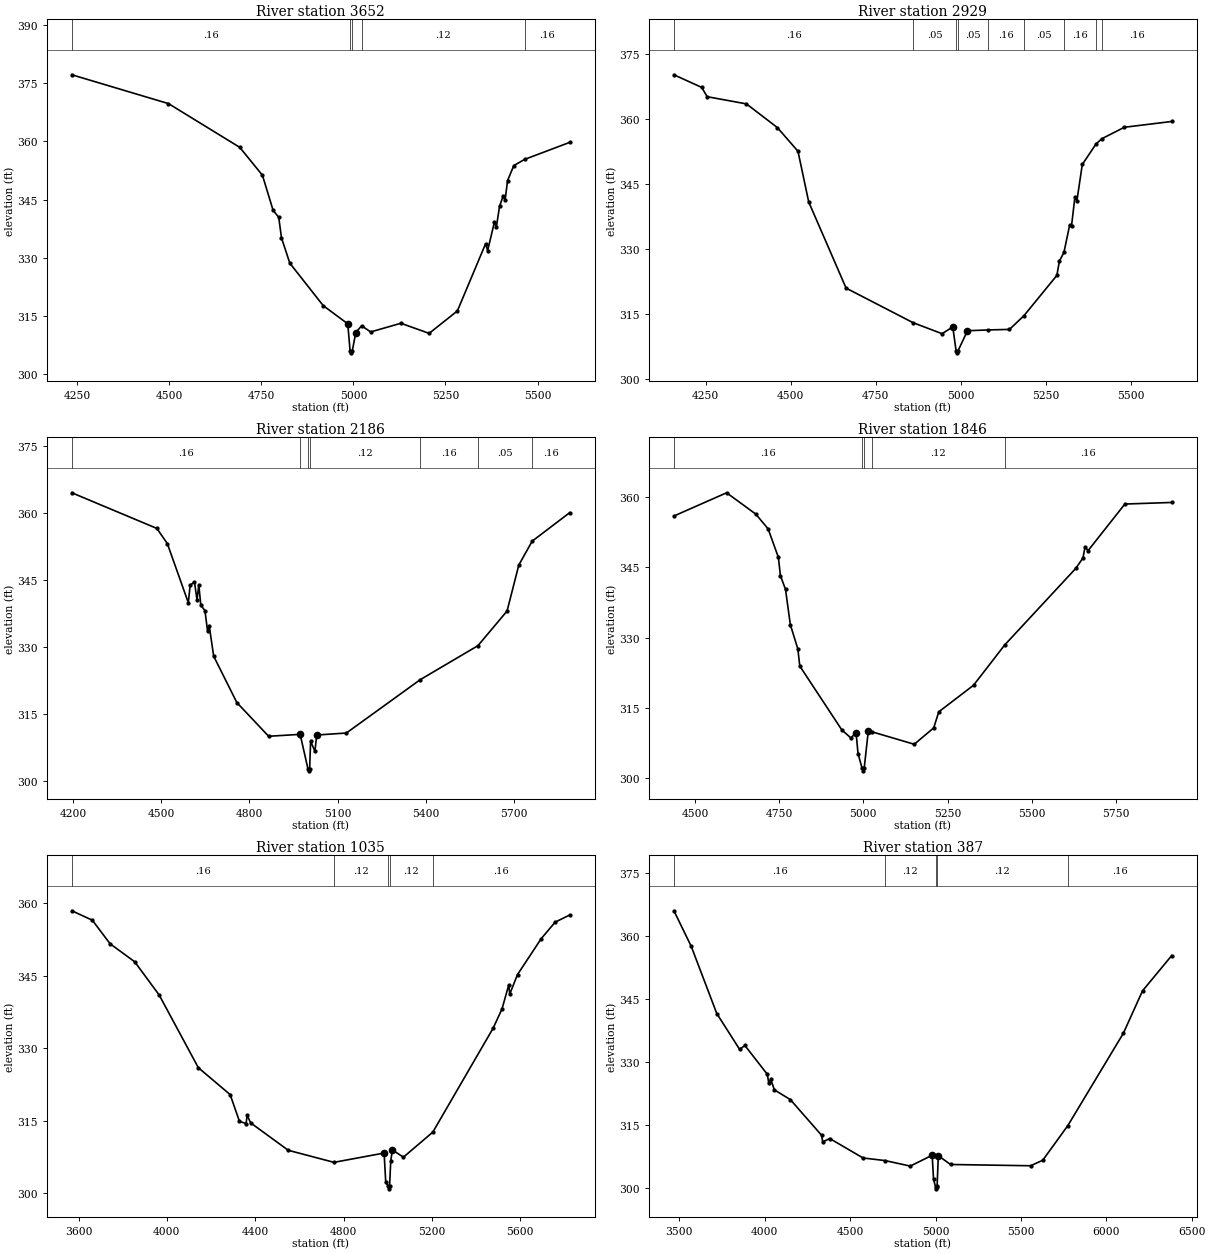
Type RM Length L Ch R = 1 ,3652    ,723,723,723
BEGIN DESCRIPTION:
SELF CREEK 6.0
END DESCRIPTION:
XS GIS Cut Line= 3
      3626086.23     10549968.24      3625452.53     10550272.07
       3624854.1     10550523.58
#Sta/Elev= 30
  4235.4  377.11  4497.8  369.69  4691.4  358.43  4752.9  351.26    4782  342.21
  4797.2  340.43  4804.7  335.14  4827.3  328.63    4918   317.7  4984.7  313.02
    4991  306.05  4993.7  305.55    4997  306.05  5006.4  310.76  5022.3  312.51
  5046.9  310.93    5129  313.16  5205.7  310.56  5282.4  316.34  5359.1  333.65
  5364.5  331.85  5382.8  339.13  5388.2  337.91  5396.9  343.24  5406.6   345.9
    5412  344.82  5418.6  349.87  5435.7  353.75  5465.2  355.34  5587.3  359.71
#Mann= 5 ,-1 , 0
  4235.4     .16       0    4991     .07       0    4997     .16       0
  5022.3     .12       0  5465.2     .16       0
Bank Sta=4984.7,5006.4
XS Rating Curve= 0 ,0
Exp/Cntr=0.3,0.1

Type RM Length L Ch R = 1 ,2929    ,743,743,743
BEGIN DESCRIPTION:
SELF CREEK 5.0
END DESCRIPTION:
XS GIS Cut Line= 3
      3625860.53     10549681.79      3625166.07     10549777.28
      3624784.88      10550435.7
#Sta/Elev= 30
  4157.2  370.21  4238.9  367.29  4254.8  365.15  4370.1  363.49    4461  358.02
  4521.5  352.55    4553  340.85  4662.8  320.96  4859.2  312.99  4944.6  310.44
  4976.1     312  4985.7  306.52  4988.4  306.02  4991.7  306.52  5019.2  311.12
  5080.9  311.31  5142.6  311.43  5184.8  314.57  5281.8   323.9  5289.1  327.18
  5302.6  329.23  5319.1  335.44  5324.9  335.41  5334.8  342.04  5340.6  341.14
  5356.4   349.5  5396.4   354.2  5413.4  355.43  5479.8  358.09    5619  359.43
#Mann= 9 ,-1 , 0
  4157.2     .16       0  4859.2     .05       0  4985.7     .03       0
  4991.7     .05       0  5080.9     .16       0  5184.8     .05       0
  5302.6     .16       0  5396.4      .1       0  5413.4     .16       0
Bank Sta=4976.1,5019.2
XS Rating Curve= 0 ,0
Exp/Cntr=0.3,0.1

Type RM Length L Ch R = 1 ,2186    ,340,340,340
BEGIN DESCRIPTION:
SELF CREEK 4.0
END DESCRIPTION:
XS GIS Cut Line= 3
      3625244.22      10548952.6      3624671.28     10549759.92
      3624671.28     10550463.06
#Sta/Elev= 30
  4196.5  364.61  4485.6  356.61  4521.3  353.19  4592.6  339.93  4598.8  343.86
  4613.5  344.58  4622.2  340.56  4628.3   343.9    4635  339.42  4649.2  338.12
  4657.9  333.64    4664  334.61  4678.8  327.93  4757.6  317.52  4865.8  309.95
  4972.8  310.38    4974  310.06  4999.3  302.69  5002.1  302.19  5005.3  302.69
  5008.5   308.8  5023.2   306.6  5029.4  310.23  5130.2  310.68  5381.5  322.66
  5577.7  330.29  5676.7  338.06  5716.7   348.4  5762.2  353.75  5889.6  360.14
#Mann= 7 ,-1 , 0
  4196.5     .16       0    4974     .12       0  4999.3     .07       0
  5005.3     .12       0  5381.5     .16       0  5577.7     .05       0
  5762.2     .16       0
Bank Sta=4972.8,5029.4
XS Rating Curve= 0 ,0
Exp/Cntr=0.3,0.1

Type RM Length L Ch R = 1 ,1846    ,811,811,811
BEGIN DESCRIPTION:
SELF CREEK 3.0
END DESCRIPTION:
XS GIS Cut Line= 2
      3624853.59     10548917.88      3624063.65      10550167.9
#Sta/Elev= 30
  4437.3   355.9  4593.8  360.85  4680.6   356.3  4717.1  353.17  4747.6  347.09
  4753.6  343.22  4768.8  340.26  4783.1  332.76  4805.3  327.61  4811.2  323.94
  4935.9  310.36    4963  308.63  4978.3  309.78  4984.2   305.3  4996.4  302.13
  4999.2  301.63  5002.4  302.13  5014.7  310.12  5024.7  309.96  5151.2  307.29
  5208.9  310.77  5224.1   314.2  5327.2  319.85  5419.9  328.44  5631.1  344.75
  5652.3  346.96  5658.5  349.28  5667.6  348.53  5776.8  358.45    5916  358.79
#Mann= 5 ,-1 , 0
  4437.3     .16       0  4996.4     .07       0  5002.4     .16       0
  5024.7     .12       0  5419.9     .16       0
Bank Sta=4978.3,5014.7
XS Rating Curve= 0 ,0
Exp/Cntr=0.3,0.1

Type RM Length L Ch R = 1 ,1035    ,648,648,648
BEGIN DESCRIPTION:
SELF CREEK 2.0
END DESCRIPTION:
XS GIS Cut Line= 4
      3625131.33     10548527.28      3624245.94     10548648.81
      3623890.03     10549291.17       3623933.4      10549915.7
#Sta/Elev= 30
  3569.8  358.43  3662.4  356.48  3743.1   351.6  3854.2  347.89  3965.2  341.01
  4142.3  325.99  4286.5  320.42  4328.6   314.9  4358.6  314.42  4363.6  316.17
    4379  314.58  4549.8   308.9  4756.7  306.41  4983.7  308.33    4991  302.39
  5002.4  301.43  5005.2  300.93  5008.4  301.43  5013.8  306.72  5021.4  308.98
    5071  307.47  5204.3  312.66  5477.6  334.17  5517.7  338.14  5547.7  343.04
  5552.7  341.21  5587.8  345.24    5695  352.66  5758.2  356.08  5823.9  357.55
#Mann= 5 ,-1 , 0
  3569.8     .16       0  4756.7     .12       0  5002.4     .07       0
  5008.4     .12       0  5204.3     .16       0
Bank Sta=4983.7,5021.4
XS Rating Curve= 0 ,0
Exp/Cntr=0.3,0.1

Type RM Length L Ch R = 1 ,387     ,0,0,0
BEGIN DESCRIPTION:
SELF CREEK 1.0
END DESCRIPTION:
XS GIS Cut Line= 4
      3625079.31     10548223.45      3623881.35     10548423.11
      3623508.09     10548718.25      3623724.86     10549923.48
#Sta/Elev= 30
  3468.3     366  3569.4  357.56  3719.3  341.56  3853.2  333.02  3883.6  333.97
  4015.4   327.1  4023.4  325.02  4035.7  325.93    4056  323.42  4150.1  321.09
  4332.6  312.62  4339.9  311.01  4380.4  311.84  4575.9  307.21    4705  306.59
  4852.2  305.28  4980.5  307.86  4988.5  302.16    5000  300.37  5002.7  299.87
    5006  300.37  5009.3  300.46  5016.5  307.75  5087.9  305.66  5556.9  305.36
    5628  306.67  5774.6  314.89  6099.9  336.86  6212.3  346.96  6383.2  355.35
#Mann= 5 ,-1 , 0
  3468.3     .16       0    4705     .12       0    5000     .07       0
    5006     .12       0  5774.6     .16       0
Bank Sta=4980.5,5016.5
XS Rating Curve= 0 ,0
Exp/Cntr=0.3,0.1

Chan Stop Cuts=-1
Use User Specified Reach Order=0
Composite Channel Slope=5