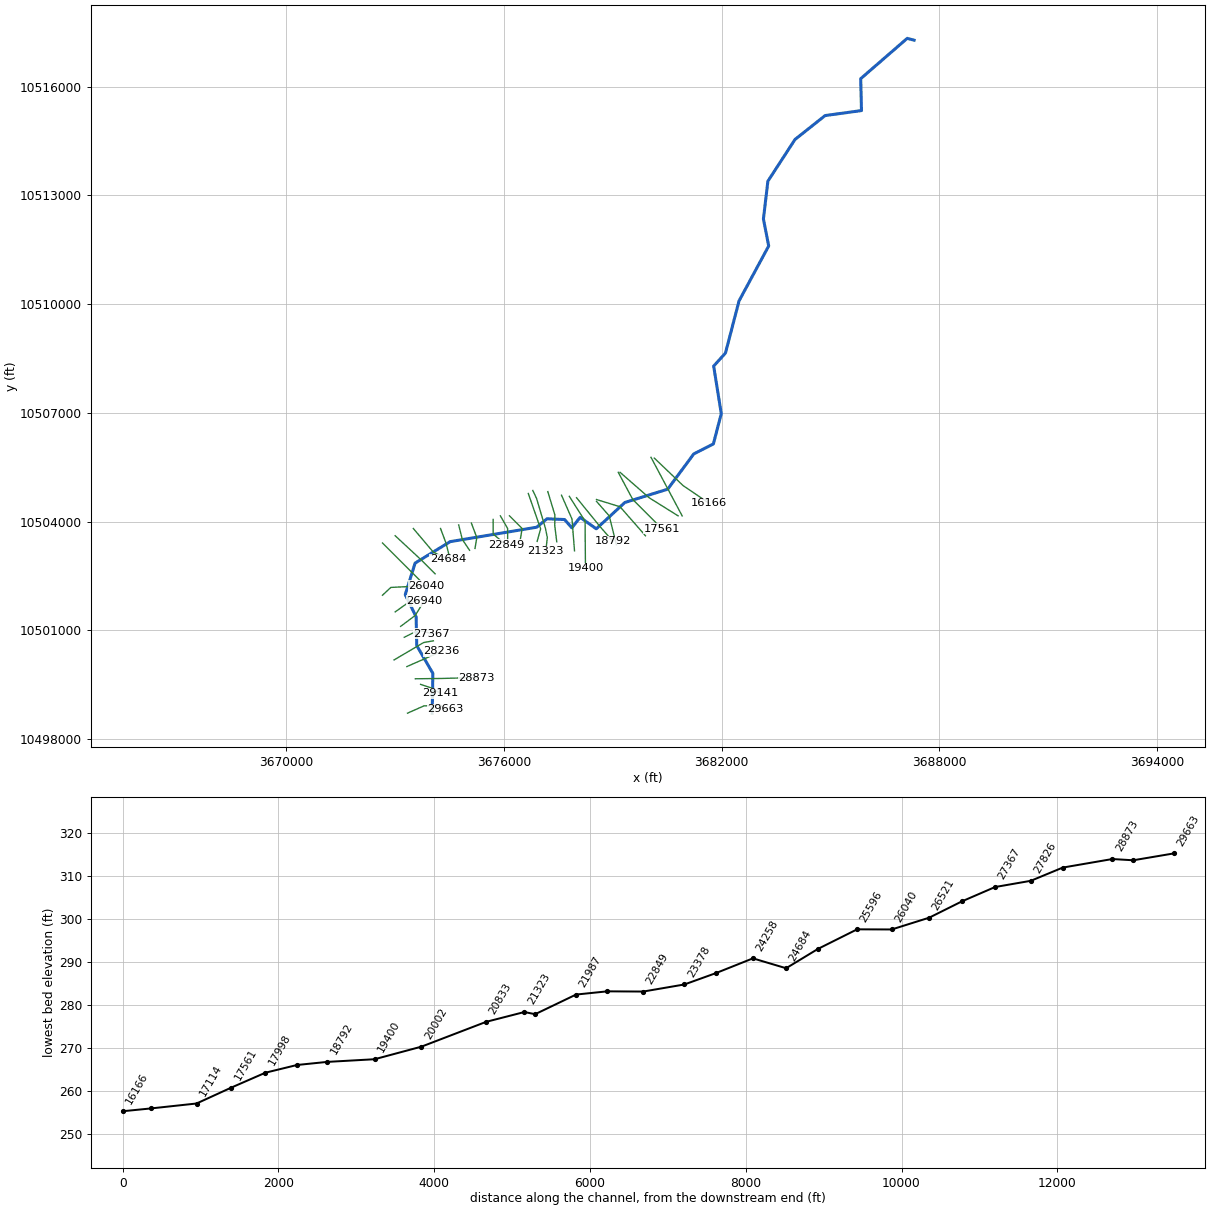
--- SERASCA CREEK.prj (project) ---

Proj Title=SERASCA CREEK Base Level Engineering
Current Plan=p01
Default Exp/Contr=0.3,0.1
English Units
Geom File=g01
Flow File=f01
Plan File=p01
BEGIN DESCRIPTION:
SERASCA CREEK
END DESCRIPTION:

--- SERASCA CREEK.p01 (plan) ---

Plan Title=Multiple Run
Short Identifier=Multiple
Geom File=g01
Flow File=f01
Subcritical Flow
K Sum by GR= 0
Std Step Tol= 0.01
Critical Tol= 0.01
Num of Std Step Trials= 20
Max Error Tol= 0.3
Flow Tol Ratio= 0.001
Split Flow NTrial= 30
Split Flow Tol= 0.02
Split Flow Ratio= 0.02
Log Output Level= 0
Friction Slope Method= 1
Unsteady Friction Slope Method= 2
Unsteady Bridges Friction Slope Method= 1
Parabolic Critical Depth
Global Vel Dist=  1 , 1 , 1
Global Log Level= 0
CheckData=True
Encroach Param= -1, 0, 0, 0
BEGIN DESCRIPTION:
Multiple Run
END DESCRIPTION:

--- SERASCA CREEK.f01 (steady flow) ---

Flow Title=Multiple
Number of Profiles=7
Profile Names=10-year,25-year,50-year,1pct_min,100-year,1pct_plu,500-year
River Rch & RM= SERASCA CREEK,Reach-1,29663
    1006    1424    1784    1641    2219    3002    3452
River Rch & RM= SERASCA CREEK,Reach-1,25095
    1275    1814    2278    2099    2839    3839    4429
River Rch & RM= SERASCA CREEK,Reach-1,17114
    1580    2269    2870    2659    3596    4864    5679
River Rch & RM= SERASCA CREEK,Reach-1,16532
    1749    2512    3177    2942    3979    5381    6275
River Rch & RM= SERASCA CREEK,Reach-1,8959
    1798    2574    3246    2997    4053    5482    6353
Boundary for River Rch & Prof#=SERASCA CREEK,Reach-1,1
Up Type=0
Dn Type=3
Dn Slope=0.005
Boundary for River Rch & Prof#=SERASCA CREEK,Reach-1,2
Up Type=0
Dn Type=3
Dn Slope=0.005
Boundary for River Rch & Prof#=SERASCA CREEK,Reach-1,3
Up Type=0
Dn Type=3
Dn Slope=0.005
Boundary for River Rch & Prof#=SERASCA CREEK,Reach-1,4
Up Type=0
Dn Type=3
Dn Slope=0.005
Boundary for River Rch & Prof#=SERASCA CREEK,Reach-1,5
Up Type=0
Dn Type=3
Dn Slope=0.005
Boundary for River Rch & Prof#=SERASCA CREEK,Reach-1,6
Up Type=0
Dn Type=3
Dn Slope=0.005
Boundary for River Rch & Prof#=SERASCA CREEK,Reach-1,7
Up Type=0
Dn Type=3
Dn Slope=0.005

--- SERASCA CREEK.g01 (geometry) ---

Geom Title=Existing Conditions

River Reach=SERASCA CREEK,Reach-1
Reach XY= 30
      3674019.50     10498710.00      3674037.75     10499814.00
      3673593.00     10500582.00      3673576.50     10501375.00
      3673276.00     10501986.00      3673547.75     10502856.00
      3674515.50     10503448.00      3676899.75     10503846.00
      3677185.00     10504079.00      3677668.00     10504058.00
      3677870.50     10503829.00      3678097.25     10504118.00
      3678544.25     10503802.00      3679330.75     10504528.00
      3680512.25     10504895.00      3681231.25     10505868.00
      3681772.25     10506144.00      3681989.75     10506978.00
      3681780.25     10508291.00      3682106.00     10508652.00
      3682479.75     10510090.00      3683297.50     10511606.00
      3683152.00     10512350.00      3683275.00     10513393.00
      3684023.00     10514544.00      3684853.00     10515203.00
      3685855.75     10515341.00      3685834.25     10516221.00
      3687117.75     10517334.00      3687306.00     10517283.00

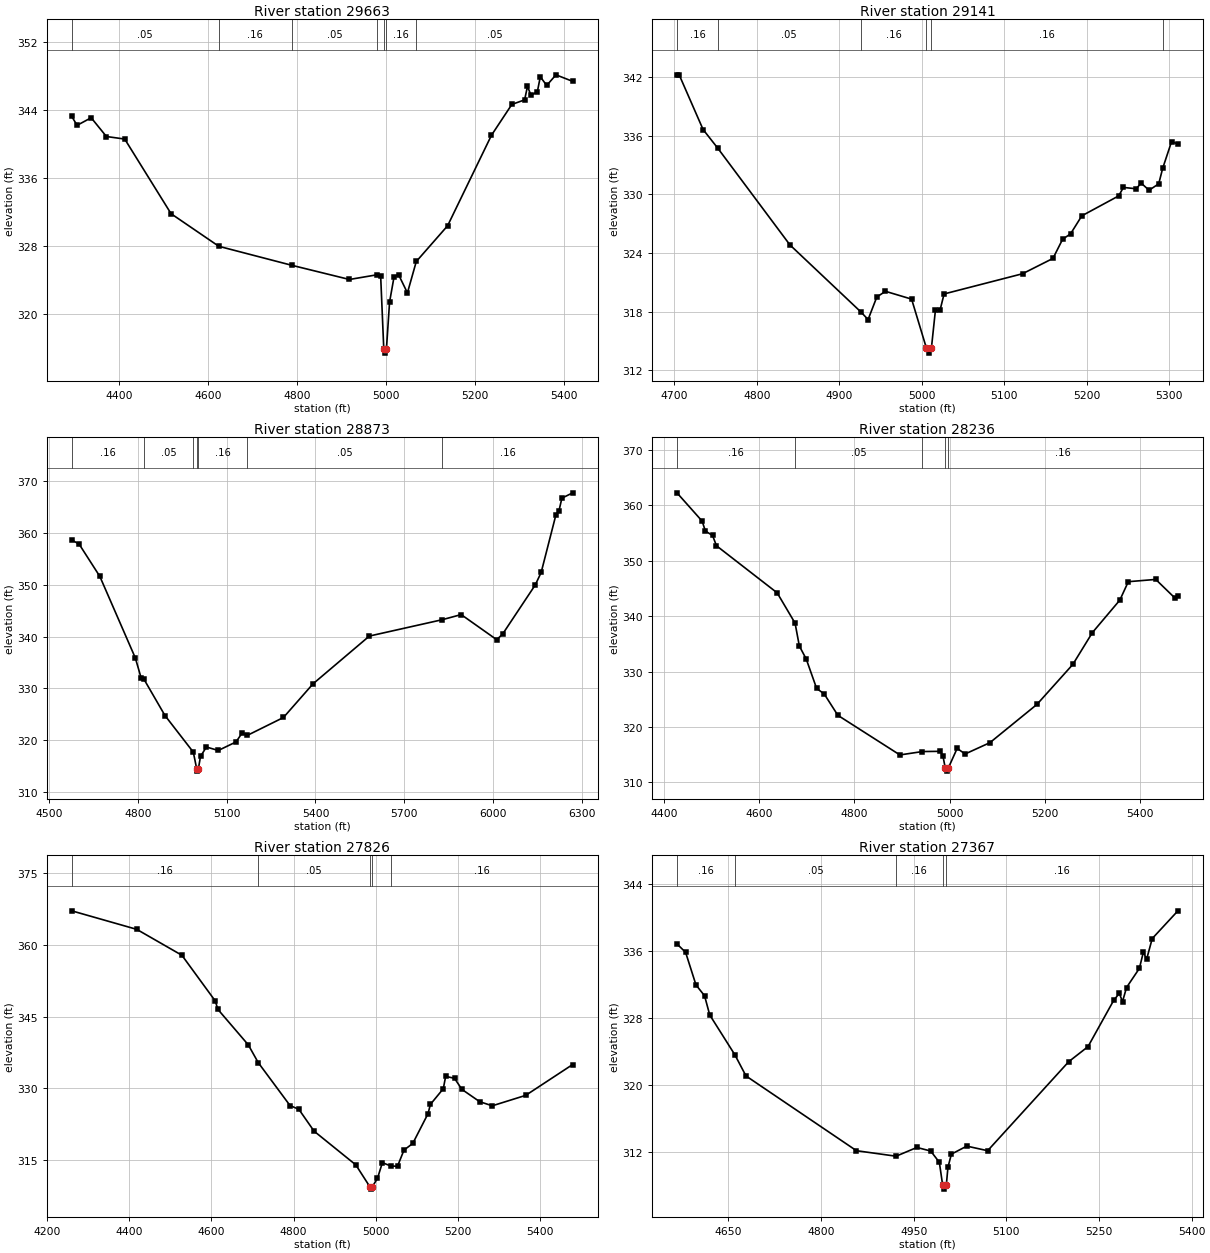
Type RM Length L Ch R = 1,29663,522,522,522
BEGIN DESCRIPTION:
SERASCA CREEK 58.0
END DESCRIPTION:
XS GIS Cut Line= 4
      3673338.52     10498715.83      3673789.91     10498915.48
      3674241.30     10498941.52      3674380.21     10498828.66
#Sta/Elev= 30
  4293.8  343.24  4305.9  342.19  4337.5  343.08  4371.7  340.87  4412.8  340.57
  4516.9  331.77  4624.1  327.93  4788.0  325.69  4917.3  324.02  4980.0  324.58
  4987.4  324.46  4994.4  315.84  4997.2  315.34  5000.4  315.84  5007.4  321.36
  5017.5  324.34  5027.5  324.60  5047.5  322.44  5067.4  326.14  5137.7  330.35
  5236.2  341.02  5281.9  344.65  5310.6  345.19  5317.0  346.78  5325.0  345.72
  5339.3  346.17  5345.8  347.91  5360.2  346.89  5381.0  348.14  5418.5  347.37
#Mann=7,-1,0
  4293.8    0.05       0  4624.1    0.16       0  4788.0    0.05       0
  4980.0    0.16       0  4994.4    0.07       0  5000.4    0.16       0
  5067.4    0.05       0
Bank Sta=4994.4,5000.4
Exp/Cntr=0.3,0.1

Type RM Length L Ch R = 1,29141,268,268,268
BEGIN DESCRIPTION:
SERASCA CREEK 57.0
END DESCRIPTION:
XS GIS Cut Line= 3
      3673699.56     10499510.20      3673999.61     10499410.19
      3674249.59     10499260.20
#Sta/Elev= 30
  4703.0  342.24  4705.7  342.24  4734.7  336.64  4752.6  334.72  4840.1  324.82
  4926.0  317.97  4934.9  317.18  4945.5  319.49  4956.0  320.07  4987.7  319.27
  5005.7  314.24  5008.5  313.74  5011.7  314.24  5016.6  318.14  5022.2  318.14
  5027.1  319.80  5122.3  321.87  5159.2  323.44  5170.9  325.40  5180.6  325.96
  5194.2  327.80  5238.9  329.84  5244.7  330.71  5260.3  330.57  5266.1  331.16
  5275.8  330.42  5287.5  331.08  5292.3  332.66  5303.1  335.40  5310.8  335.16
#Mann=6,-1,0
  4703.0    0.16       0  4752.6    0.05       0  4926.0    0.16       0
  5005.7    0.07       0  5011.7    0.16       0  5292.3    0.05       0
Bank Sta=5005.7,5011.7
Exp/Cntr=0.3,0.1

Type RM Length L Ch R = 1,28873,637,637,637
BEGIN DESCRIPTION:
SERASCA CREEK 56.0
END DESCRIPTION:
XS GIS Cut Line= 3
      3673554.70     10499664.84      3674301.27     10499673.52
      3675246.00     10499699.52
#Sta/Elev= 30
  4576.8  358.68  4601.7  357.89  4671.7  351.65  4791.7  335.88  4811.7  331.94
  4821.1  331.75  4891.7  324.77  4987.4  317.70  4998.7  314.53  5001.5  314.03
  5004.7  314.53  5011.7  316.87  5031.7  318.69  5071.7  318.02  5131.7  319.67
  5151.7  321.36  5170.0  320.94  5291.8  324.39  5391.8  330.90  5581.9  340.12
  5828.0  343.28  5892.0  344.27  6012.0  339.42  6032.0  340.51  6142.1  349.99
  6162.1  352.41  6212.1  363.58  6222.1  364.30  6232.1  366.76  6268.5  367.79
#Mann=7,-1,0
  4576.8    0.16       0  4821.1    0.05       0  4987.4    0.16       0
  4998.7    0.07       0  5004.7    0.16       0  5170.0    0.05       0
  5828.0    0.16       0
Bank Sta=4998.7,5004.7
Exp/Cntr=0.3,0.1

Type RM Length L Ch R = 1,28236,410,410,410
BEGIN DESCRIPTION:
SERASCA CREEK 55.0
END DESCRIPTION:
XS GIS Cut Line= 2
      3673321.18     10500000.56      3674283.86     10500425.53
#Sta/Elev= 30
  4427.2  362.21  4480.1  357.11  4486.9  355.32  4502.0  354.52  4510.2  352.67
  4637.7  344.18  4675.3  338.72  4684.3  334.59  4698.8  332.24  4720.6  326.94
  4736.4  325.97  4765.2  322.10  4895.5  314.96  4942.9  315.57  4980.5  315.61
  4985.9  314.79  4990.9  312.54  4993.6  312.04  4996.9  312.54  5015.8  316.14
  5032.5  315.13  5084.6  317.17  5183.4  324.07  5258.8  331.28  5299.9  337.02
  5357.5  342.87  5375.3  346.19  5432.9  346.60  5474.0  343.18  5479.5  343.69
#Mann=5,-1,0
  4427.2    0.16       0  4675.3    0.05       0  4942.9    0.16       0
  4990.9    0.07       0  4996.9    0.16       0
Bank Sta=4990.9,4996.9
Exp/Cntr=0.3,0.1

Type RM Length L Ch R = 1,27826,459,459,459
BEGIN DESCRIPTION:
SERASCA CREEK 54.0
END DESCRIPTION:
XS GIS Cut Line= 3
      3672968.73     10500184.58      3673781.23     10500663.75
      3674052.03     10500712.35
#Sta/Elev= 30
  4260.2  367.07  4418.4  363.20  4528.2  357.79  4609.5  348.23  4615.5  346.51
  4689.7  339.08  4713.8  335.38  4791.2  326.41  4812.6  325.63  4849.7  321.06
  4951.2  314.02  4985.3  309.46  4988.0  308.96  4991.3  309.46  5003.9  311.22
  5015.8  314.49  5036.4  313.78  5052.6  313.74  5068.3  317.11  5089.7  318.50
  5126.8  324.72  5132.6  326.66  5163.9  329.92  5169.7  332.51  5191.2  332.10
  5209.3  329.78  5252.6  327.21  5283.1  326.36  5364.4  328.54  5478.6  334.98
#Mann=5,-1,0
  4260.2    0.16       0  4713.8    0.05       0  4985.3    0.03       0
  4991.3    0.05       0  5036.4    0.16       0
Bank Sta=4985.3,4991.3
Exp/Cntr=0.3,0.1

Type RM Length L Ch R = 1,27367,427,427,427
BEGIN DESCRIPTION:
SERASCA CREEK 53.0
END DESCRIPTION:
XS GIS Cut Line= 3
      3673249.60     10500810.19      3673649.61     10501010.19
      3673999.58     10500910.20
#Sta/Elev= 30
  4566.6  336.87  4580.6  335.86  4597.4  331.96  4611.3  330.66  4619.7  328.36
  4660.4  323.59  4678.4  321.06  4857.3  312.11  4921.4  311.45  4955.1  312.50
  4977.5  312.07  4991.5  310.72  4996.8  308.01  4999.6  307.51  5002.8  308.01
  5005.4  310.12  5011.0  311.70  5035.9  312.66  5069.7  312.11  5201.0  322.77
  5232.2  324.57  5273.8  330.11  5282.9  330.95  5288.1  329.96  5294.6  331.65
  5315.4  333.94  5321.9  335.90  5327.1  335.02  5336.2  337.51  5377.8  340.83
#Mann=5,-1,0
  4566.6    0.16       0  4660.4    0.05       0  4921.4    0.16       0
  4996.8    0.07       0  5002.8    0.16       0
Bank Sta=4996.8,5002.8
Exp/Cntr=0.3,0.1

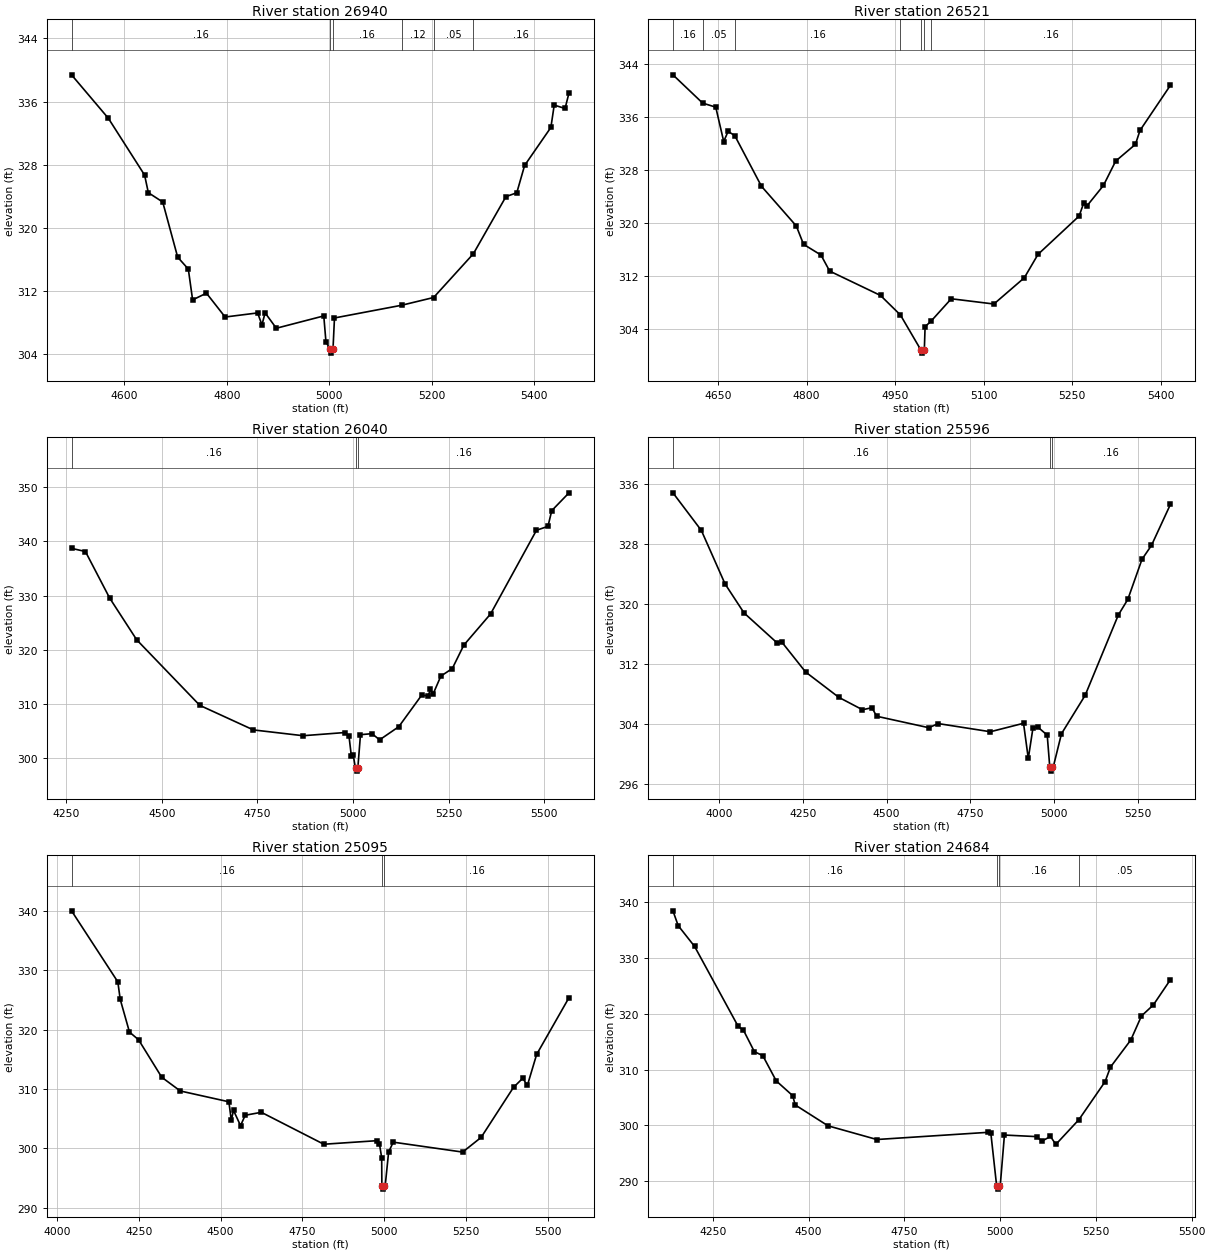
Type RM Length L Ch R = 1,26940,419,419,419
BEGIN DESCRIPTION:
SERASCA CREEK 52.0
END DESCRIPTION:
XS GIS Cut Line= 3
      3673149.61     10501110.19      3673549.61     10501410.19
      3673799.61     10501810.19
#Sta/Elev= 30
  4496.8  339.39  4568.7  333.89  4639.5  326.70  4646.8  324.47  4674.9  323.29
  4704.1  316.31  4724.9  314.80  4733.3  310.90  4760.3  311.75  4796.8  308.73
  4860.3  309.25  4868.7  307.74  4874.9  309.26  4896.8  307.31  4989.5  308.87
  4993.7  305.62  5001.5  304.66  5004.2  304.16  5007.5  304.66  5010.4  308.61
  5141.5  310.22  5204.0  311.20  5281.7  316.74  5345.3  323.97  5366.5  324.46
  5381.8  327.92  5433.1  332.73  5439.6  335.56  5460.8  335.13  5468.5  337.11
#Mann=6,-1,0
  4496.8    0.16       0  5001.5    0.07       0  5007.5    0.16       0
  5141.5    0.12       0  5204.0    0.05       0  5281.7    0.16       0
Bank Sta=5001.5,5007.5
Exp/Cntr=0.3,0.1

Type RM Length L Ch R = 1,26521,481,481,481
BEGIN DESCRIPTION:
SERASCA CREEK 51.0
END DESCRIPTION:
XS GIS Cut Line= 3
      3672999.61     10501510.19      3673349.61     10501760.19
      3673749.59     10501860.18
#Sta/Elev= 30
  4573.7  342.30  4624.0  338.04  4646.2  337.43  4659.7  332.25  4667.1  333.78
  4678.4  333.14  4723.6  325.51  4782.6  319.53  4794.9  316.76  4824.4  315.15
  4839.1  312.73  4925.2  309.06  4958.9  306.12  4993.4  300.87  4996.2  300.37
  4999.4  300.87  5000.7  304.36  5010.4  305.15  5045.0  308.56  5117.2  307.77
  5168.7  311.72  5191.9  315.25  5261.5  321.02  5269.2  322.96  5274.4  322.51
  5302.7  325.63  5323.4  329.30  5356.9  331.83  5364.6  333.92  5416.1  340.72
#Mann=7,-1,0
  4573.7    0.16       0  4624.0    0.05       0  4678.4    0.16       0
  4958.9    0.12       0  4993.4    0.07       0  4999.4    0.12       0
  5010.4    0.16       0
Bank Sta=4993.4,4999.4
Exp/Cntr=0.3,0.1

Type RM Length L Ch R = 1,26040,444,444,444
BEGIN DESCRIPTION:
SERASCA CREEK 50.0
END DESCRIPTION:
XS GIS Cut Line= 3
      3672649.27     10501969.29      3672878.45     10502184.58
      3673864.61     10502233.19
#Sta/Elev= 30
  4263.5  338.71  4299.8  338.13  4363.3  329.54  4434.1  321.84  4599.1  309.76
  4739.3  305.23  4869.5  304.16  4979.6  304.75  4989.6  304.06  4995.6  300.49
  5000.6  300.60  5006.6  298.13  5009.4  297.63  5012.6  298.13  5019.6  304.35
  5049.7  304.54  5069.7  303.40  5119.8  305.82  5179.8  311.64  5197.2  311.50
  5202.2  312.72  5209.9  311.89  5229.9  315.15  5259.9  316.55  5290.0  320.86
  5360.0  326.61  5480.2  342.05  5510.2  342.77  5520.2  345.67  5565.3  348.95
#Mann=3,-1,0
  4263.5    0.16       0  5006.6    0.07       0  5012.6    0.16       0
Bank Sta=5006.6,5012.6
Exp/Cntr=0.3,0.1

Type RM Length L Ch R = 1,25596,501,501,501
BEGIN DESCRIPTION:
SERASCA CREEK 49.0
END DESCRIPTION:
XS GIS Cut Line= 3
      3672649.59     10503410.20      3673449.61     10502610.19
      3673699.58     10502360.22
#Sta/Elev= 30
  3862.4  334.83  3947.3  329.80  4018.0  322.66  4074.6  318.79  4173.5  314.78
  4187.7  314.88  4258.4  310.90  4357.4  307.52  4428.1  305.86  4456.4  306.13
  4470.5  304.99  4626.1  303.46  4654.4  304.01  4809.9  302.92  4908.9  304.05
  4923.1  299.35  4937.2  303.47  4951.4  303.55  4979.6  302.47  4987.3  298.16
  4990.0  297.66  4993.3  298.16  4997.3  298.16  5022.1  302.65  5092.8  307.78
  5191.8  318.51  5220.1  320.59  5262.5  325.95  5290.8  327.81  5347.3  333.28
#Mann=3,-1,0
  3862.4    0.16       0  4987.3    0.07       0  4993.3    0.16       0
Bank Sta=4987.3,4993.3
Exp/Cntr=0.3,0.1

Type RM Length L Ch R = 1,25095,411,411,411
BEGIN DESCRIPTION:
SERASCA CREEK 48.0
END DESCRIPTION:
XS GIS Cut Line= 3
      3672999.60     10503610.19      3673699.61     10502960.19
      3674099.58     10502560.22
#Sta/Elev= 30
  4044.1  339.99  4185.6  328.03  4192.9  325.09  4221.2  319.57  4249.1  318.27
  4319.9  311.96  4376.6  309.65  4525.1  307.83  4532.5  304.72  4539.3  306.38
  4560.8  303.81  4575.0  305.56  4624.3  306.06  4815.4  300.68  4978.1  301.28
  4985.4  300.76  4992.3  298.41  4992.9  293.62  4995.7  293.12  4998.9  293.62
  5002.9  293.62  5013.5  299.36  5027.6  301.03  5239.8  299.36  5296.3  301.83
  5395.3  310.26  5423.6  311.79  5437.8  310.59  5466.0  315.80  5565.0  325.37
#Mann=3,-1,0
  4044.1    0.16       0  4992.9    0.07       0  4998.9    0.16       0
Bank Sta=4992.9,4998.9
Exp/Cntr=0.3,0.1

Type RM Length L Ch R = 1,24684,426,426,426
BEGIN DESCRIPTION:
SERASCA CREEK 47.0
END DESCRIPTION:
XS GIS Cut Line= 3
      3673499.61     10503810.19      3674049.61     10503160.19
      3674449.62     10502960.18
#Sta/Elev= 30
  4145.8  338.41  4159.5  335.76  4202.4  332.03  4316.1  317.73  4329.8  317.06
  4358.4  313.20  4380.4  312.49  4415.5  307.97  4458.4  305.33  4465.0  303.67
  4550.7  299.93  4678.1  297.48  4969.3  298.77  4975.8  298.58  4991.0  289.10
  4993.7  288.60  4997.0  289.10  5000.1  289.10  5011.2  298.28  5095.1  298.00
  5109.1  297.19  5131.4  298.03  5145.4  296.60  5205.7  301.04  5274.0  307.84
  5288.0  310.44  5341.1  315.29  5369.0  319.60  5399.8  321.55  5444.5  326.08
#Mann=4,-1,0
  4145.8    0.16       0  4991.0    0.07       0  4997.0    0.16       0
  5205.7    0.05       0
Bank Sta=4991,4997
Exp/Cntr=0.3,0.1

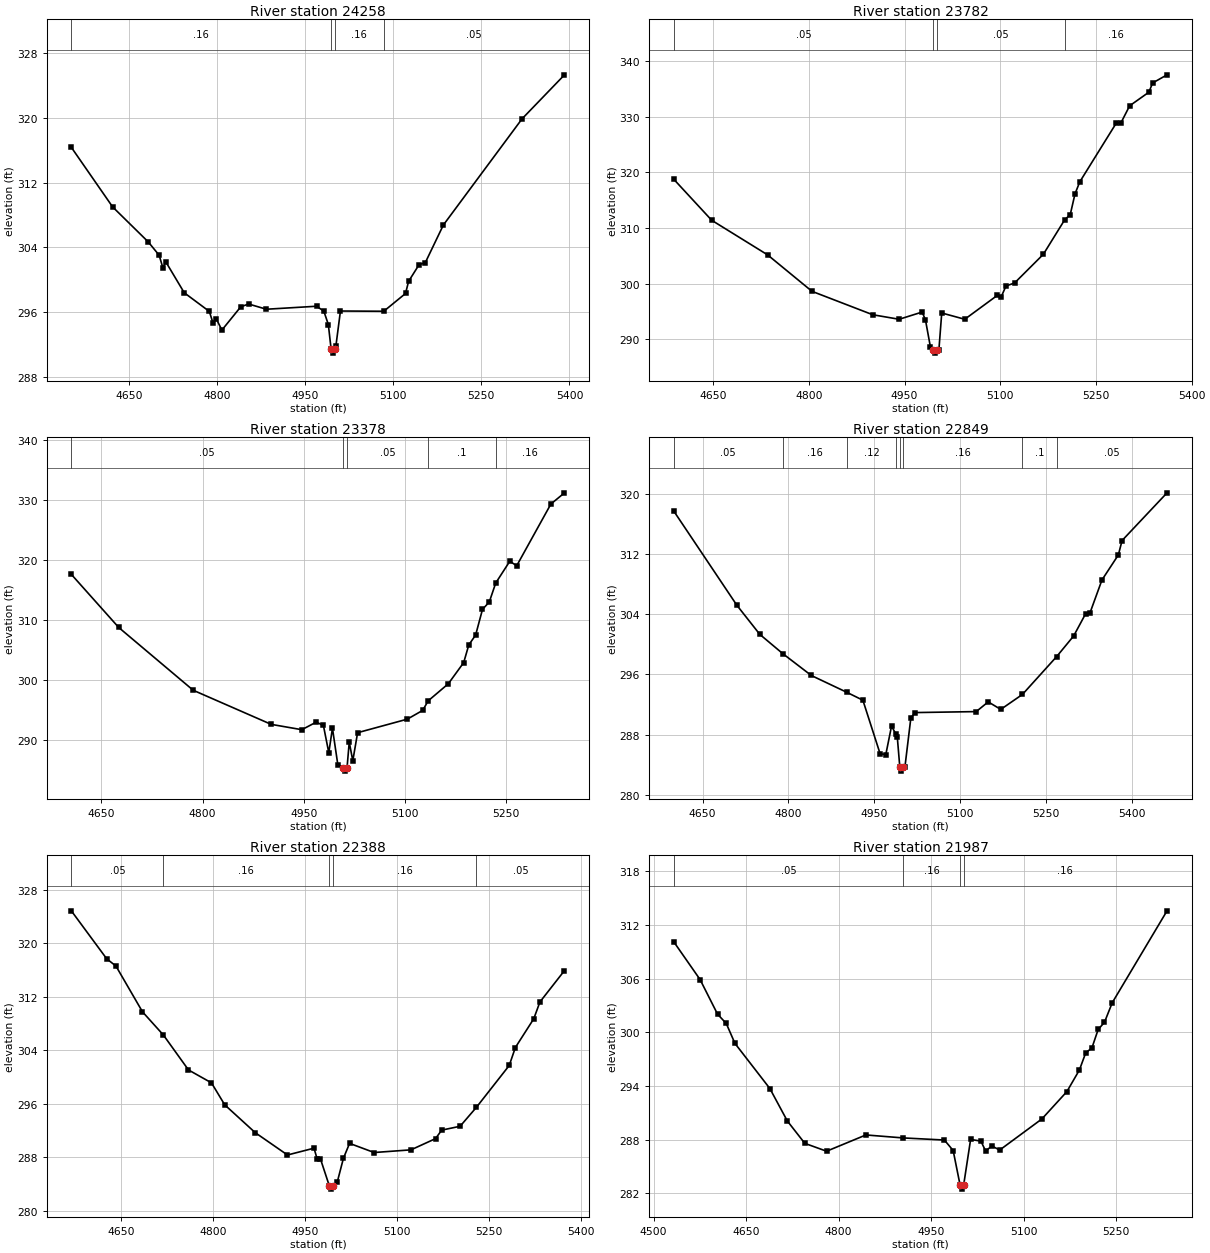
Type RM Length L Ch R = 1,24258,476,476,476
BEGIN DESCRIPTION:
SERASCA CREEK 46.0
END DESCRIPTION:
XS GIS Cut Line= 3
      3674249.61     10503810.18      3674399.61     10503410.19
      3674499.61     10503010.19
#Sta/Elev= 30
  4552.0  316.36  4622.3  308.99  4682.8  304.67  4701.5  303.01  4707.7  301.49
  4713.1  302.16  4744.2  298.37  4786.9  296.06  4793.2  294.62  4798.5  295.18
  4808.3  293.75  4840.3  296.62  4853.7  296.98  4884.0  296.33  4969.4  296.70
  4981.8  296.10  4989.5  294.44  4994.2  291.40  4997.0  290.90  5000.2  291.40
  5002.4  291.80  5010.1  296.11  5083.9  296.08  5120.9  298.28  5126.1  299.78
  5144.1  301.86  5154.4  302.07  5185.3  306.75  5319.3  319.89  5391.5  325.33
#Mann=4,-1,0
  4552.0    0.16       0  4994.2    0.07       0  5000.2    0.16       0
  5083.9    0.05       0
Bank Sta=4994.2,5000.2
Exp/Cntr=0.3,0.1

Type RM Length L Ch R = 1,23782,404,404,404
BEGIN DESCRIPTION:
SERASCA CREEK 45.0
END DESCRIPTION:
XS GIS Cut Line= 3
      3674749.60     10503910.21      3674849.61     10503510.19
      3675049.62     10503210.18
#Sta/Elev= 30
  4588.5  318.76  4647.8  311.39  4735.4  305.16  4805.0  298.59  4900.3  294.37
  4941.6  293.56  4977.6  294.86  4982.8  293.45  4990.5  288.61  4995.3  287.96
  4998.0  287.46  5001.3  287.96  5003.8  287.96  5008.3  294.69  5044.4  293.56
  5095.5  297.87  5101.5  297.60  5109.0  299.55  5122.5  300.10  5167.6  305.27
  5200.9  311.46  5209.7  312.41  5217.2  316.16  5224.7  318.32  5281.8  328.89
  5289.3  328.97  5302.8  332.01  5332.8  334.45  5338.9  336.13  5361.4  337.59
#Mann=4,-1,0
  4588.5    0.05       0  4995.3    0.03       0  5001.3    0.05       0
  5200.9    0.16       0
Bank Sta=4995.3,5001.3
Exp/Cntr=0.3,0.1

Type RM Length L Ch R = 1,23378,529,529,529
BEGIN DESCRIPTION:
SERASCA CREEK 44.0
END DESCRIPTION:
XS GIS Cut Line= 3
      3675099.61     10503960.19      3675249.61     10503560.19
      3675199.62     10503260.23
#Sta/Elev= 30
  4605.4  317.64  4675.7  308.78  4786.1  298.31  4901.8  292.62  4947.2  291.73
  4968.5  292.99  4979.2  292.44  4987.2  287.89  4992.6  291.98  5000.6  285.88
  5008.2  285.32  5011.0  284.82  5014.2  285.32  5017.5  289.65  5022.8  286.55
  5029.9  291.23  5103.6  293.49  5126.4  294.95  5134.6  296.55  5164.4  299.39
  5187.2  302.92  5194.8  305.88  5204.9  307.51  5215.1  311.80  5225.2  313.04
  5234.7  316.19  5255.6  319.83  5265.8  319.07  5316.5  329.37  5336.7  331.24
#Mann=5,-1,0
  4605.4    0.05       0  5008.2    0.03       0  5014.2    0.05       0
  5134.6     0.1       0  5234.7    0.16       0
Bank Sta=5008.2,5014.2
Exp/Cntr=0.3,0.1

Type RM Length L Ch R = 1,22849,461,461,461
BEGIN DESCRIPTION:
SERASCA CREEK 43.0
END DESCRIPTION:
XS GIS Cut Line= 3
      3675699.61     10504060.24      3675699.61     10503660.19
      3676049.59     10503360.20
#Sta/Elev= 30
  4599.9  317.66  4709.9  305.18  4749.9  301.32  4789.9  298.77  4839.9  295.86
  4902.1  293.62  4929.9  292.58  4959.9  285.49  4969.9  285.36  4979.9  289.14
  4987.9  288.04  4989.9  287.76  4994.4  283.67  4997.2  283.17  5000.4  283.67
  5003.2  283.67  5013.7  290.26  5021.3  290.94  5127.8  291.07  5148.7  292.36
  5170.6  291.36  5208.5  293.35  5268.2  298.37  5297.9  301.11  5318.8  304.06
  5326.5  304.19  5347.3  308.54  5375.9  311.86  5382.4  313.77  5460.9  320.10
#Mann=8,-1,0
  4599.9    0.05       0  4789.9    0.16       0  4902.1    0.12       0
  4987.9    0.16       0  4994.4    0.07       0  5000.4    0.16       0
  5208.5     0.1       0  5268.2    0.05       0
Bank Sta=4994.4,5000.4
Exp/Cntr=0.3,0.1

Type RM Length L Ch R = 1,22388,401,401,401
BEGIN DESCRIPTION:
SERASCA CREEK 42.0
END DESCRIPTION:
XS GIS Cut Line= 3
      3675899.61     10504160.18      3676099.61     10503810.19
      3676099.61     10503410.19
#Sta/Elev= 30
  4569.6  324.88  4627.2  317.70  4642.3  316.61  4685.5  309.76  4719.6  306.28
  4760.4  301.06  4797.8  299.13  4819.4  295.84  4869.0  291.68  4921.6  288.33
  4964.8  289.35  4969.8  287.77  4975.2  287.77  4989.7  283.72  4992.5  283.22
  4995.7  283.72  5002.7  284.29  5012.7  287.84  5022.7  290.07  5062.7  288.70
  5122.7  289.10  5162.7  290.78  5172.7  292.05  5202.7  292.63  5229.2  295.46
  5282.7  301.73  5292.7  304.42  5322.7  308.73  5332.7  311.24  5372.7  315.94
#Mann=5,-1,0
  4569.6    0.05       0  4719.6    0.16       0  4989.7    0.07       0
  4995.7    0.16       0  5229.2    0.05       0
Bank Sta=4989.7,4995.7
Exp/Cntr=0.3,0.1

Type RM Length L Ch R = 1,21987,525,525,525
BEGIN DESCRIPTION:
SERASCA CREEK 41.0
END DESCRIPTION:
XS GIS Cut Line= 3
      3676149.58     10504160.22      3676499.61     10503810.19
      3676449.60     10503510.15
#Sta/Elev= 30
  4533.0  310.12  4575.5  305.91  4603.8  302.04  4617.9  301.00  4632.0  298.77
  4688.6  293.72  4716.9  290.09  4745.2  287.59  4780.5  286.71  4844.2  288.53
  4904.0  288.20  4971.4  287.96  4985.6  286.79  4996.7  282.97  4999.5  282.47
  5002.7  282.97  5013.9  288.03  5030.6  287.84  5038.2  286.73  5048.3  287.30
  5061.0  286.84  5129.4  290.32  5169.9  293.38  5190.2  295.80  5200.4  297.71
  5210.5  298.27  5220.6  300.33  5230.8  301.13  5243.4  303.32  5332.2  313.60
#Mann=4,-1,0
  4533.0    0.05       0  4904.0    0.16       0  4996.7    0.07       0
  5002.7    0.16       0
Bank Sta=4996.7,5002.7
Exp/Cntr=0.3,0.1

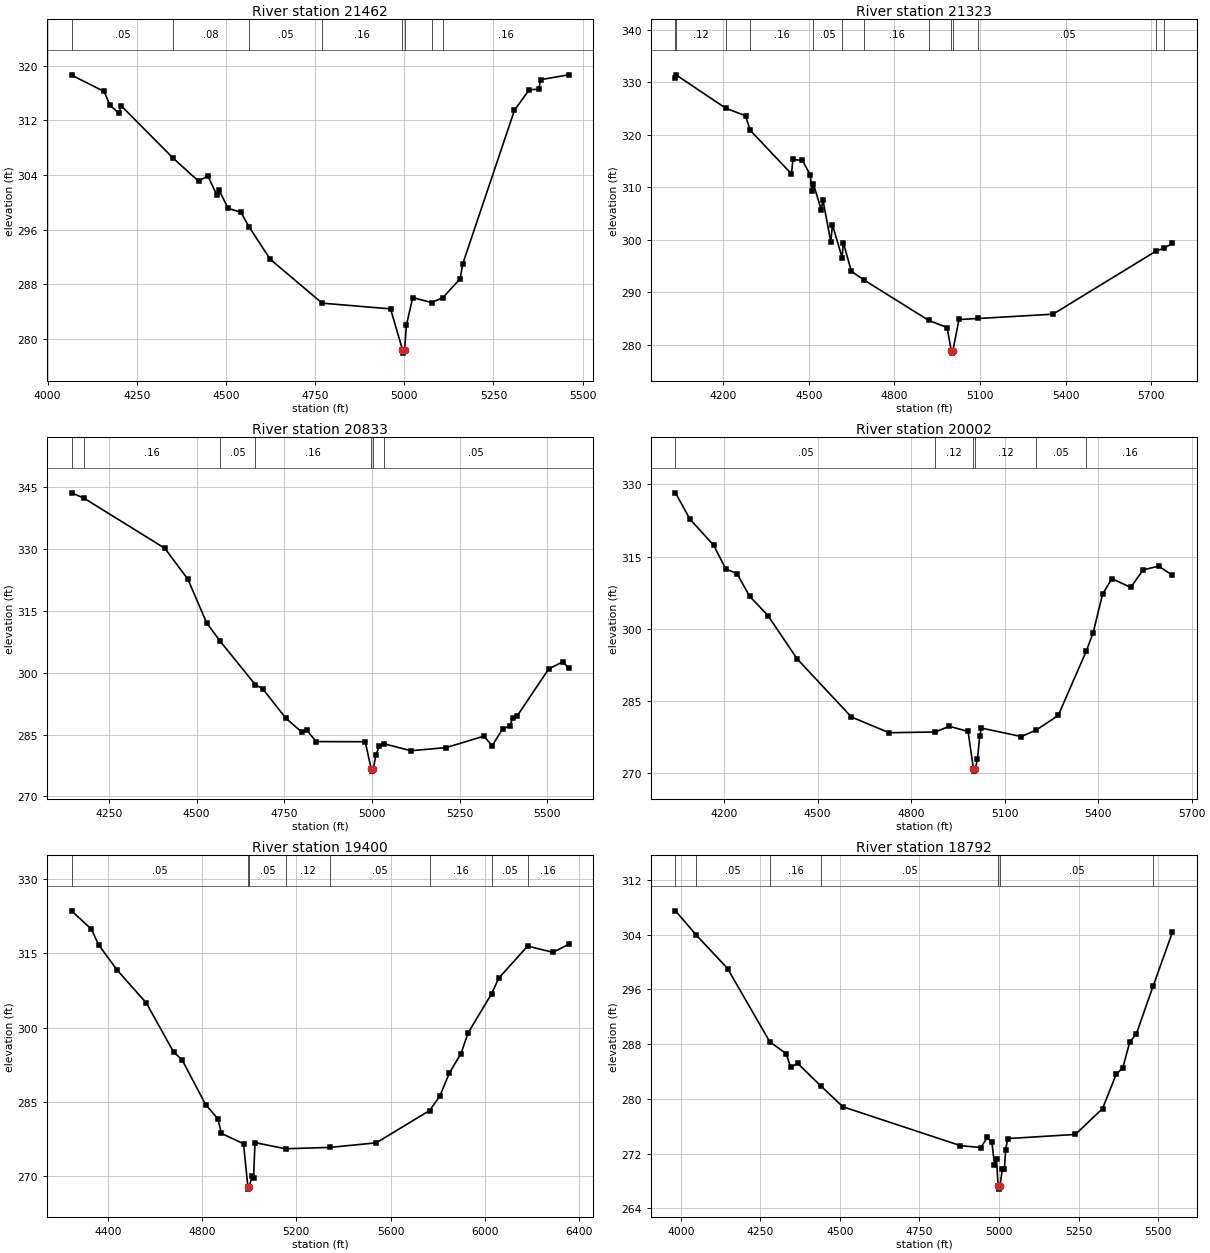
Type RM Length L Ch R = 1,21462,139,139,139
BEGIN DESCRIPTION:
SERASCA CREEK 40.0
END DESCRIPTION:
XS GIS Cut Line= 3
      3676669.04     10504776.52      3677009.31     10503800.83
      3676912.31     10503454.38
#Sta/Elev= 30
  4067.3  318.63  4158.7  316.23  4175.0  314.22  4200.7  313.02  4206.0  314.16
  4352.3  306.46  4423.5  303.08  4449.3  303.87  4475.1  301.02  4480.4  301.83
  4506.1  299.12  4542.5  298.52  4564.9  296.39  4624.7  291.63  4769.9  285.22
  4961.6  284.38  4995.0  278.40  4997.7  277.90  5001.0  278.40  5006.0  281.99
  5023.7  286.03  5076.8  285.31  5107.9  286.02  5156.8  288.79  5163.6  290.92
  5309.0  313.49  5350.5  316.50  5377.1  316.55  5382.3  317.96  5460.4  318.67
#Mann=8,-1,0
  4067.3    0.05       0  4352.3    0.08       0  4564.9    0.05       0
  4769.9    0.16       0  4995.0    0.07       0  5001.0    0.16       0
  5076.8    0.08       0  5107.9    0.16       0
Bank Sta=4995,5001
Exp/Cntr=0.3,0.1

Type RM Length L Ch R = 1,21323,490,490,490
BEGIN DESCRIPTION:
SERASCA CREEK 39.0
END DESCRIPTION:
XS GIS Cut Line= 5
      3676794.02     10504859.89      3676898.20     10504637.64
      3677141.26     10503818.19      3677193.34     10503561.25
      3677151.81     10503183.99
#Sta/Elev= 30
  4032.7  330.88  4034.6  331.43  4208.7  325.08  4278.2  323.63  4294.6  320.87
  4439.3  312.55  4444.5  315.30  4477.7  315.12  4505.0  312.38  4510.9  309.27
  4515.6  310.72  4544.2  305.63  4549.4  307.64  4577.4  299.53  4582.6  302.89
  4616.8  296.61  4621.1  299.45  4649.1  294.00  4694.6  292.30  4920.3  284.64
  4984.8  283.28  4999.2  278.90  5002.0  278.40  5005.2  278.90  5026.5  284.81
  5094.6  285.00  5355.8  285.82  5718.2  297.88  5743.4  298.37  5774.6  299.31
#Mann=13,-1,0
  4032.7    0.08       0  4034.6    0.12       0  4208.7    0.05       0
  4294.6    0.16       0  4515.6    0.05       0  4616.8    0.08       0
  4694.6    0.16       0  4920.3    0.08       0  4999.2    0.07       0
  5005.2    0.08       0  5094.6    0.05       0  5718.2    0.16       0
  5743.4    0.05       0
Bank Sta=4999.2,5005.2
Exp/Cntr=0.3,0.1

Type RM Length L Ch R = 1,20833,831,831,831
BEGIN DESCRIPTION:
SERASCA CREEK 38.0
END DESCRIPTION:
XS GIS Cut Line= 4
      3677207.23     10504828.60      3677401.68     10504186.25
      3677398.20     10503898.05      3677453.64     10503444.18
#Sta/Elev= 30
  4143.5  343.65  4178.2  342.39  4409.4  330.20  4475.3  322.66  4528.4  312.13
  4566.1  307.76  4667.4  297.10  4688.5  296.10  4754.4  288.95  4800.1  285.58
  4814.6  286.01  4840.7  283.29  4980.7  283.25  4997.7  276.62  5000.5  276.12
  5003.7  276.62  5010.7  279.97  5020.7  282.11  5033.1  282.79  5110.8  281.07
  5211.5  281.83  5319.0  284.61  5342.5  282.27  5372.7  286.44  5392.9  286.99
  5400.5  288.92  5413.0  289.42  5503.7  300.92  5544.0  302.65  5560.1  301.15
#Mann=7,-1,0
  4143.5    0.05       0  4178.2    0.16       0  4566.1    0.05       0
  4667.4    0.16       0  4997.7    0.07       0  5003.7    0.16       0
  5033.1    0.05       0
Bank Sta=4997.7,5003.7
Exp/Cntr=0.3,0.1

Type RM Length L Ch R = 1,20002,602,602,602
BEGIN DESCRIPTION:
SERASCA CREEK 37.0
END DESCRIPTION:
XS GIS Cut Line= 3
      3677585.72     10504727.88      3677873.90     10504071.66
      3677943.35     10503196.62
#Sta/Elev= 30
  4043.9  328.26  4090.7  322.75  4166.2  317.37  4205.2  312.43  4241.8  311.42
  4281.7  306.74  4340.7  302.72  4434.1  293.71  4608.5  281.60  4729.5  278.33
  4877.6  278.49  4922.6  279.67  4982.8  278.60  4999.8  270.84  5002.6  270.34
  5005.8  270.84  5012.9  272.85  5020.1  277.61  5025.2  279.30  5153.6  277.54
  5201.3  278.88  5271.9  281.93  5362.1  295.34  5384.0  299.15  5414.1  307.16
  5444.2  310.40  5504.4  308.58  5544.5  312.24  5594.7  312.99  5638.4  311.10
#Mann=6,-1,0
  4043.9    0.05       0  4877.6    0.12       0  4999.8    0.07       0
  5005.8    0.12       0  5201.3    0.05       0  5362.1    0.16       0
Bank Sta=4999.8,5005.8
Exp/Cntr=0.3,0.1

Type RM Length L Ch R = 1,19400,608,608,608
BEGIN DESCRIPTION:
SERASCA CREEK 36.0
END DESCRIPTION:
XS GIS Cut Line= 3
      3677800.54     10504697.98      3678234.57     10504014.37
      3678245.41     10502713.78
#Sta/Elev= 30
  4245.3  323.55  4329.5  319.85  4360.0  316.73  4438.8  311.61  4562.5  304.99
  4678.5  295.09  4714.9  293.48  4814.9  284.45  4866.6  281.63  4881.8  278.65
  4975.8  276.56  4994.0  267.91  4996.8  267.41  5000.0  267.91  5012.3  270.12
  5018.2  269.67  5024.5  276.79  5154.3  275.55  5343.4  275.83  5539.3  276.75
  5765.6  283.26  5809.3  286.17  5849.3  290.79  5899.3  294.76  5929.3  298.94
  6029.0  306.81  6059.3  309.94  6181.8  316.44  6289.3  315.18  6355.7  316.76
#Mann=8,-1,0
  4245.3    0.05       0  4994.0    0.03       0  5000.0    0.05       0
  5154.3    0.12       0  5343.4    0.05       0  5765.6    0.16       0
  6029.0    0.05       0  6181.8    0.16       0
Bank Sta=4994,5000
Exp/Cntr=0.3,0.1

Type RM Length L Ch R = 1,18792,388,388,388
BEGIN DESCRIPTION:
SERASCA CREEK 35.0
END DESCRIPTION:
XS GIS Cut Line= 3
      3677999.58     10504660.22      3678649.61     10503860.19
      3678999.59     10503460.21
#Sta/Elev= 30
  3983.0  307.49  4047.8  303.98  4146.8  299.05  4279.5  288.34  4330.9  286.60
  4345.1  284.63  4367.4  285.18  4441.5  281.81  4509.6  278.83  4878.8  273.15
  4942.7  272.87  4963.5  274.35  4977.9  273.61  4985.8  270.37  4992.3  271.19
  4997.2  267.29  4999.9  266.79  5003.2  267.29  5010.6  269.72  5017.1  269.72
  5020.9  272.57  5027.6  274.18  5240.2  274.79  5325.6  278.57  5368.3  283.57
  5389.2  284.54  5411.0  288.28  5431.9  289.51  5484.2  296.44  5545.3  304.37
#Mann=7,-1,0
  3983.0    0.16       0  4047.8    0.05       0  4279.5    0.16       0
  4441.5    0.05       0  4997.2    0.03       0  5003.2    0.05       0
  5484.2    0.16       0
Bank Sta=4997.2,5003.2
Exp/Cntr=0.3,0.1

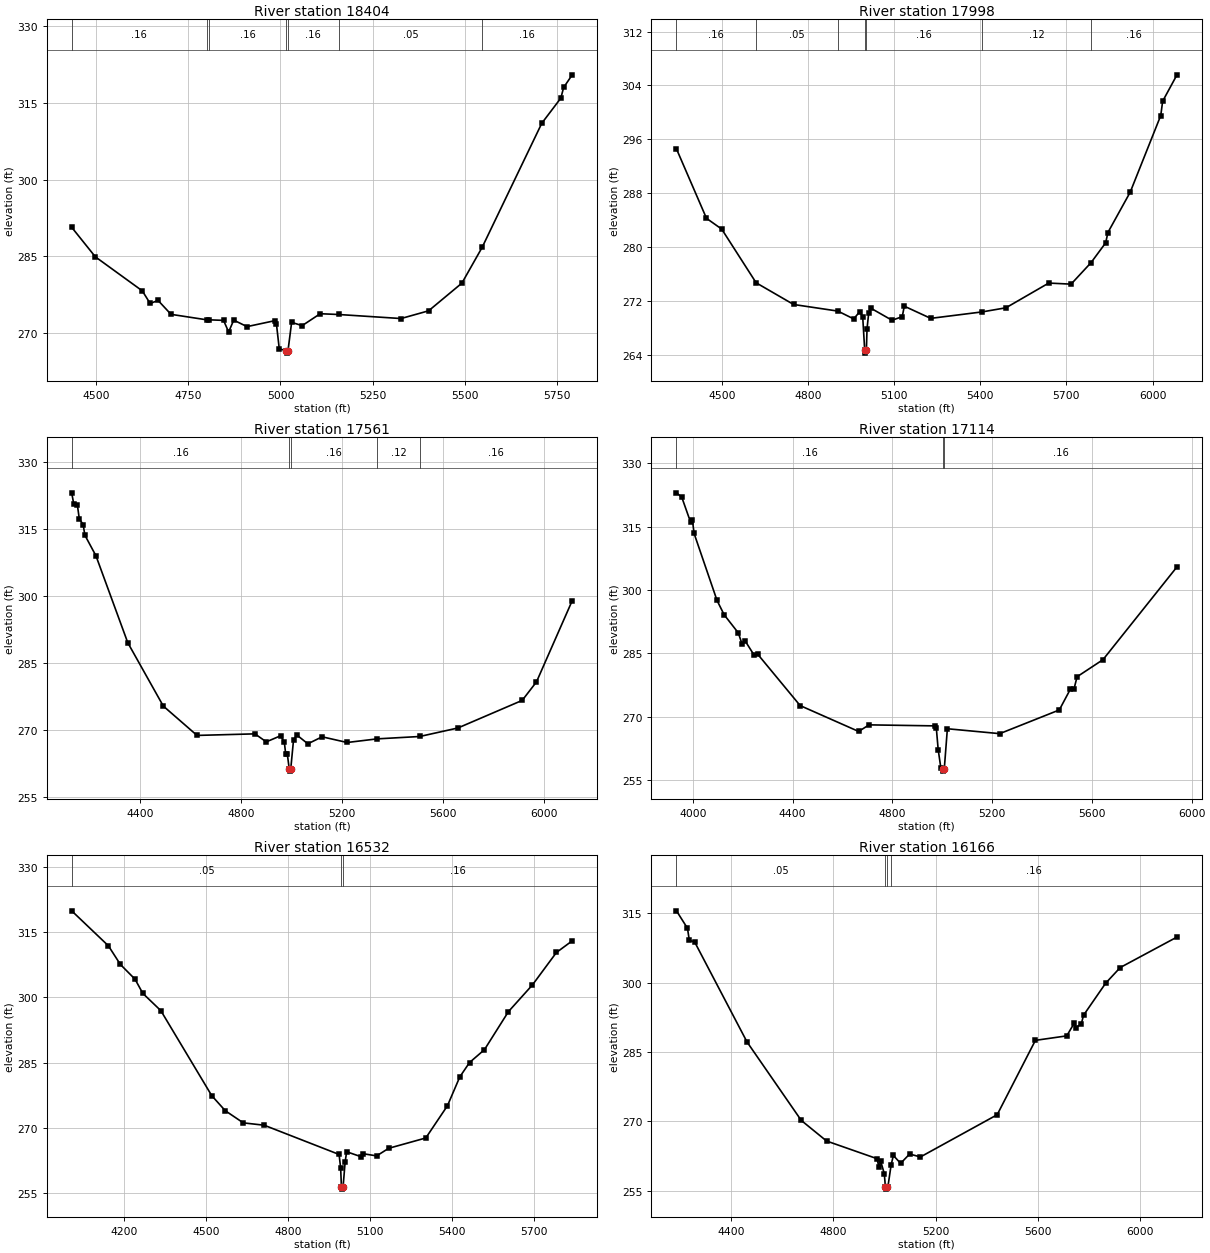
Type RM Length L Ch R = 1,18404,406,406,406
BEGIN DESCRIPTION:
SERASCA CREEK 34.0
END DESCRIPTION:
XS GIS Cut Line= 3
      3678549.60     10504560.20      3678899.61     10504160.19
      3679099.60     10503360.23
#Sta/Elev= 30
  4434.4  290.66  4498.5  284.89  4625.7  278.24  4647.0  275.77  4668.4  276.37
  4703.5  273.65  4800.2  272.58  4806.4  272.58  4845.9  272.47  4859.6  270.20
  4873.4  272.52  4909.4  271.25  4984.0  272.40  4989.1  271.79  4996.8  266.91
  5014.5  266.57  5017.2  266.07  5020.5  266.57  5030.3  272.09  5058.7  271.44
  5107.7  273.77  5157.4  273.62  5326.7  272.83  5401.4  274.34  5491.6  279.75
  5546.6  286.76  5708.1  311.00  5759.6  315.90  5767.3  317.99  5790.5  320.46
#Mann=7,-1,0
  4434.4    0.16       0  4800.2    0.05       0  4806.4    0.16       0
  5014.5    0.07       0  5020.5    0.16       0  5157.4    0.05       0
  5546.6    0.16       0
Bank Sta=5014.5,5020.5
Exp/Cntr=0.3,0.1

Type RM Length L Ch R = 1,17998,437,437,437
BEGIN DESCRIPTION:
SERASCA CREEK 33.0
END DESCRIPTION:
XS GIS Cut Line= 3
      3678549.64     10504610.18      3679199.61     10504410.19
      3679899.64     10503610.15
#Sta/Elev= 30
  4342.1  294.59  4446.7  284.28  4499.7  282.68  4619.6  274.71  4750.1  271.49
  4904.2  270.51  4959.4  269.35  4980.3  270.42  4990.8  269.63  4997.6  264.77
  5000.3  264.27  5003.6  264.77  5005.8  267.90  5011.7  270.24  5019.5  270.93
  5092.8  269.15  5128.4  269.68  5135.6  271.24  5227.6  269.43  5406.9  270.39
  5489.6  271.00  5638.6  274.67  5716.4  274.51  5785.9  277.70  5837.0  280.65
  5844.6  282.17  5922.4  288.17  6028.7  299.54  6035.3  301.66  6085.2  305.58
#Mann=7,-1,0
  4342.1    0.16       0  4619.6    0.05       0  4904.2    0.16       0
  4997.6    0.07       0  5003.6    0.16       0  5406.9    0.12       0
  5785.9    0.16       0
Bank Sta=4997.6,5003.6
Exp/Cntr=0.3,0.1

Type RM Length L Ch R = 1,17561,447,447,447
BEGIN DESCRIPTION:
SERASCA CREEK 32.0
END DESCRIPTION:
XS GIS Cut Line= 3
      3679149.60     10505360.21      3679549.61     10504610.19
      3680349.61     10503810.18
#Sta/Elev= 30
  4128.6  323.01  4136.8  320.51  4151.3  320.20  4158.7  317.20  4174.0  315.92
  4180.7  313.55  4224.6  308.94  4350.7  289.50  4491.3  275.35  4624.8  268.79
  4854.0  269.14  4898.9  267.35  4956.0  268.72  4970.5  267.24  4975.8  264.59
  4982.2  264.59  4989.8  261.31  4992.5  260.81  4995.8  261.31  5006.9  267.87
  5021.0  268.83  5063.5  266.92  5120.0  268.48  5219.0  267.21  5337.8  268.02
  5506.2  268.55  5657.4  270.45  5912.0  276.62  5968.6  280.76  6110.0  298.91
#Mann=5,-1,0
  4128.6    0.16       0  4989.8    0.07       0  4995.8    0.16       0
  5337.8    0.12       0  5506.2    0.16       0
Bank Sta=4989.8,4995.8
Exp/Cntr=0.3,0.1

Type RM Length L Ch R = 1,17114,582,582,582
BEGIN DESCRIPTION:
SERASCA CREEK 31.0
END DESCRIPTION:
XS GIS Cut Line= 3
      3679199.64     10505360.16      3679999.61     10504660.19
      3680799.63     10504160.18
#Sta/Elev= 30
  3934.8  322.97  3956.1  321.94  3991.2  316.06  3998.8  316.50  4005.5  313.36
  4097.5  297.49  4126.0  294.11  4183.0  289.80  4197.2  287.27  4211.4  287.81
  4246.5  284.51  4260.8  284.75  4430.7  272.61  4665.1  266.49  4706.9  268.05
  4969.8  267.81  4976.4  267.37  4984.0  262.18  4994.5  257.93  5002.4  257.60
  5005.2  257.10  5008.4  257.60  5020.8  267.13  5230.7  265.97  5469.5  271.58
  5513.7  276.48  5528.4  276.54  5540.8  279.44  5644.6  283.48  5941.2  305.44
#Mann=3,-1,0
  3934.8    0.16       0  5002.4    0.07       0  5008.4    0.16       0
Bank Sta=5002.4,5008.4
Exp/Cntr=0.3,0.1

Type RM Length L Ch R = 1,16532,366,366,366
BEGIN DESCRIPTION:
SERASCA CREEK 30.0
END DESCRIPTION:
XS GIS Cut Line= 2
      3680052.06     10505774.87      3680913.16     10504156.84
#Sta/Elev= 30
  4008.5  319.84  4142.9  311.81  4186.8  307.53  4240.4  304.15  4269.0  300.89
  4334.9  296.93  4521.3  277.42  4570.9  273.96  4636.9  271.17  4713.4  270.63
  4987.7  263.92  4993.4  260.81  4996.3  256.46  4999.1  255.96  5002.3  256.46
  5009.7  262.10  5015.3  264.54  5067.3  263.42  5075.6  264.09  5125.2  263.59
  5169.3  265.33  5305.2  267.70  5384.5  275.10  5429.8  281.73  5465.4  285.02
  5520.0  287.97  5607.9  296.71  5695.7  302.83  5783.6  310.28  5841.4  312.95
#Mann=3,-1,0
  4008.5    0.05       0  4996.3    0.07       0  5002.3    0.16       0
Bank Sta=4996.3,5002.3
Exp/Cntr=0.3,0.1

Type RM Length L Ch R = 1,16166,352,352,352
BEGIN DESCRIPTION:
SERASCA CREEK 29.0
END DESCRIPTION:
XS GIS Cut Line= 3
      3680142.37     10505753.99      3680934.01     10504997.08
      3681649.29     10504510.96
#Sta/Elev= 30
  4185.3  315.57  4228.4  311.80  4235.7  309.19  4256.7  308.81  4461.8  287.16
  4674.1  270.18  4773.2  265.72  4971.0  261.89  4978.2  260.03  4985.1  261.34
  4999.3  258.64  5003.5  255.80  5006.3  255.30  5009.5  255.80  5013.4  255.82
  5026.0  260.55  5034.8  262.59  5063.1  260.88  5098.4  262.90  5140.8  262.27
  5441.3  271.41  5591.0  287.52  5713.7  288.49  5743.6  291.30  5749.7  290.22
  5771.0  291.15  5779.5  292.96  5866.3  299.91  5923.2  303.29  6145.4  309.89
#Mann=4,-1,0
  4185.3    0.05       0  5003.5    0.03       0  5009.5    0.05       0
  5026.0    0.16       0
Bank Sta=5003.5,5009.5
Exp/Cntr=0.3,0.1