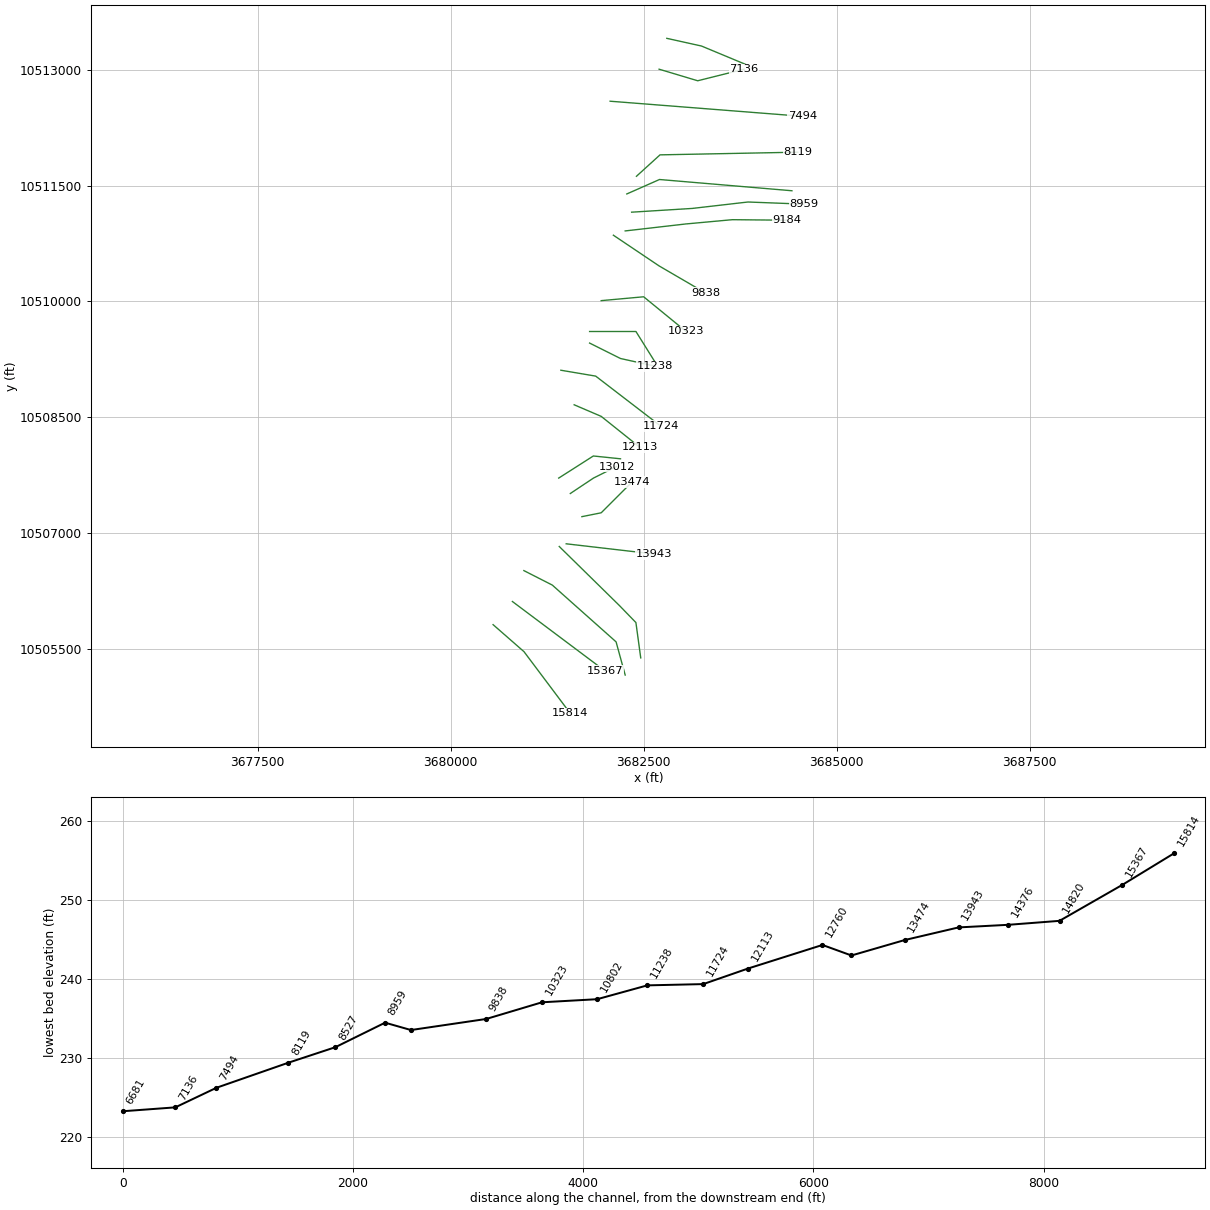
HEC-RAS study SERASCA CREEK.prj: SERASCA CREEK Base Level Engineering

--- SERASCA CREEK.g01 (geometry) --- (continued)

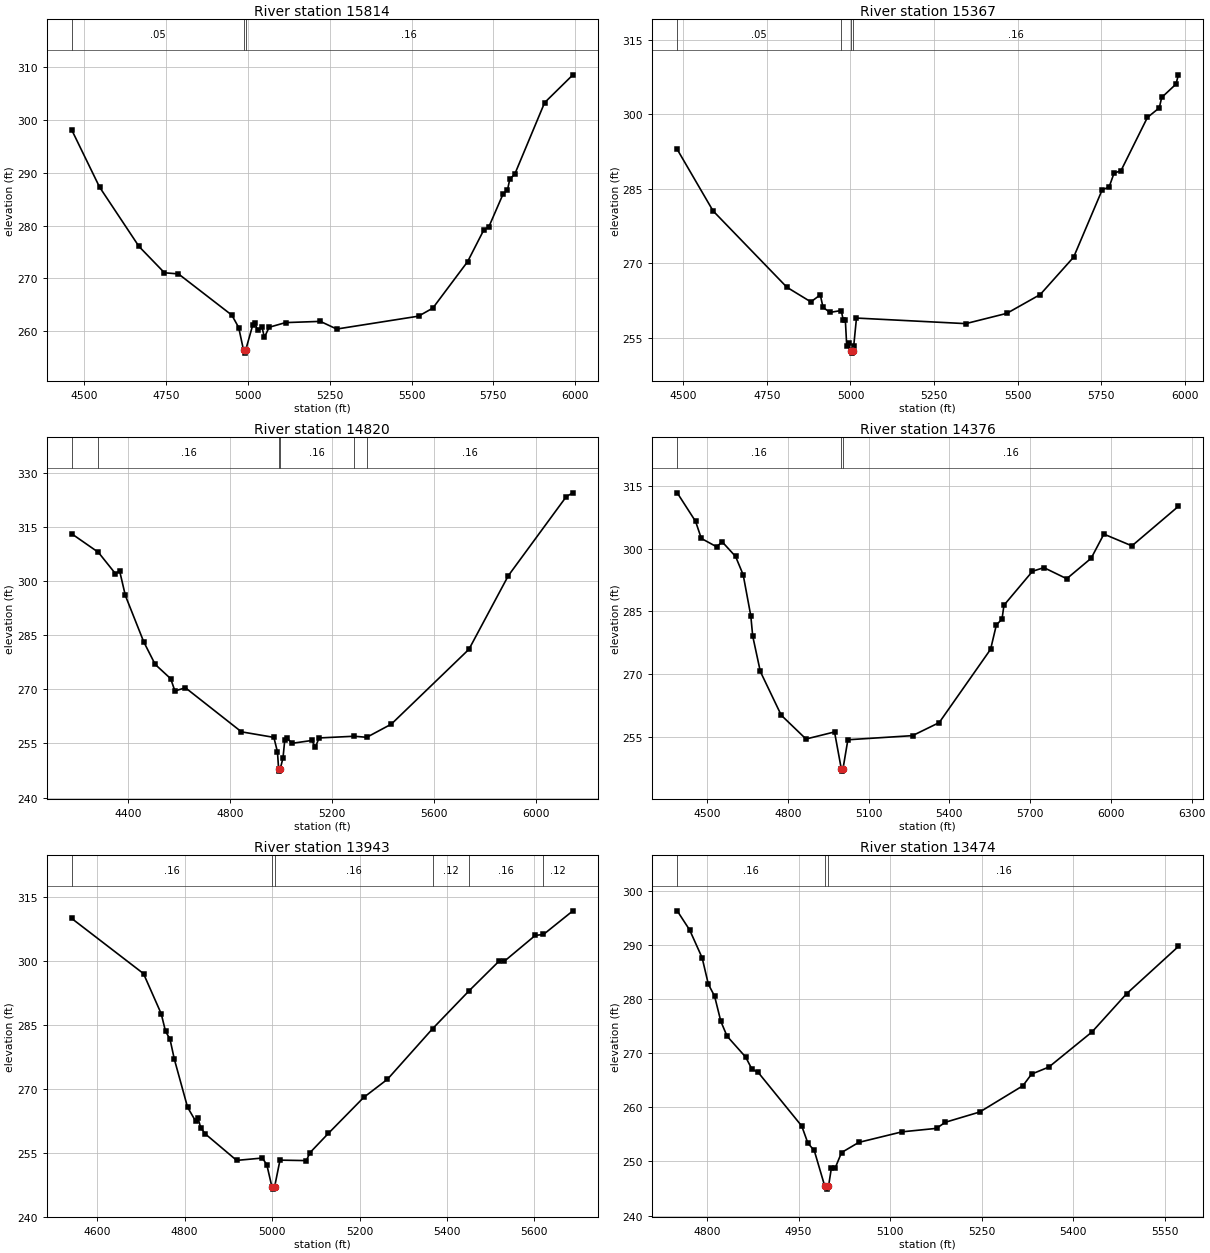
Type RM Length L Ch R = 1,15814,447,447,447
BEGIN DESCRIPTION:
SERASCA CREEK 28.0
END DESCRIPTION:
XS GIS Cut Line= 3
      3680549.58     10505810.21      3680949.61     10505460.19
      3681549.58     10504660.23
#Sta/Elev= 30
  4461.4  298.11  4546.4  287.29  4666.9  276.05  4744.8  271.06  4787.5  270.85
  4950.7  263.04  4971.6  260.70  4986.6  256.35  4989.4  255.85  4992.6  256.35
  5014.8  261.23  5021.1  261.55  5029.4  260.21  5042.9  260.71  5050.2  258.86
  5064.8  260.75  5114.8  261.63  5221.1  261.86  5271.1  260.41  5521.1  262.85
  5564.8  264.37  5671.1  273.17  5721.1  279.23  5735.7  279.71  5779.4  285.96
  5792.9  286.71  5800.2  288.85  5814.8  289.67  5906.5  303.28  5992.9  308.54
#Mann=3,-1,0
  4461.4    0.05       0  4986.6    0.07       0  4992.6    0.16       0
Bank Sta=4986.6,4992.6
Exp/Cntr=0.3,0.1

Type RM Length L Ch R = 1,15367,547,547,547
BEGIN DESCRIPTION:
SERASCA CREEK 27.0
END DESCRIPTION:
XS GIS Cut Line= 3
      3680799.58     10506110.21      3681199.61     10505810.19
      3681999.58     10505210.21
#Sta/Elev= 30
  4481.4  292.91  4588.7  280.52  4809.6  265.15  4881.4  262.20  4909.6  263.61
  4917.9  261.09  4938.7  260.08  4972.3  260.46  4978.3  258.55  4984.6  258.55
  4988.7  253.39  4995.0  253.89  5000.3  252.38  5003.1  251.88  5006.3  252.38
  5009.6  253.25  5017.9  258.94  5345.0  257.82  5467.9  259.89  5567.9  263.68
  5667.9  271.21  5753.3  284.76  5774.1  285.33  5788.7  288.11  5809.6  288.62
  5888.7  299.34  5924.1  301.26  5931.4  303.36  5974.1  306.04  5981.4  307.92
#Mann=4,-1,0
  4481.4    0.05       0  4972.3    0.16       0  5000.3    0.07       0
  5006.3    0.16       0
Bank Sta=5000.3,5006.3
Exp/Cntr=0.3,0.1

Type RM Length L Ch R = 1,14820,444,444,444
BEGIN DESCRIPTION:
SERASCA CREEK 26.0
END DESCRIPTION:
XS GIS Cut Line= 4
      3680947.91     10506510.96      3681315.95     10506323.47
      3682142.34     10505587.36      3682260.40     10505156.80
#Sta/Elev= 30
  4178.3  313.05  4282.7  307.93  4349.7  302.02  4366.3  302.74  4388.6  295.98
  4460.9  283.11  4505.7  276.88  4566.5  272.92  4583.1  269.52  4624.3  270.41
  4844.2  258.20  4971.3  256.67  4985.5  252.62  4990.0  247.82  4992.7  247.32
  4996.0  247.82  5007.2  251.01  5013.9  255.83  5021.4  256.56  5042.3  255.02
  5120.1  255.81  5134.3  253.95  5148.5  256.51  5286.2  256.98  5335.7  256.69
  5432.0  260.33  5736.6  281.06  5891.3  301.47  6118.8  323.37  6144.5  324.40
#Mann=6,-1,0
  4178.3    0.05       0  4282.7    0.16       0  4990.0    0.07       0
  4996.0    0.16       0  5286.2    0.05       0  5335.7    0.16       0
Bank Sta=4990,4996
Exp/Cntr=0.3,0.1

Type RM Length L Ch R = 1,14376,433,433,433
BEGIN DESCRIPTION:
SERASCA CREEK 25.0
END DESCRIPTION:
XS GIS Cut Line= 4
      3681406.24     10506823.46      3682184.01     10506059.58
      3682399.29     10505837.36      3682461.78     10505379.05
#Sta/Elev= 30
  4388.7  313.30  4457.0  306.47  4478.2  302.41  4534.8  300.42  4556.0  301.58
  4605.5  298.10  4633.8  293.72  4662.1  283.92  4669.2  279.08  4697.5  270.62
  4775.2  260.18  4867.2  254.49  4973.2  256.18  4998.5  247.32  5001.3  246.82
  5004.5  247.32  5022.8  254.31  5263.1  255.30  5362.1  258.41  5553.1  275.93
  5574.4  281.73  5595.5  283.15  5602.7  286.45  5708.7  294.56  5751.1  295.43
  5835.9  292.78  5926.7  297.67  5973.9  303.44  6078.1  300.63  6250.8  310.07
#Mann=3,-1,0
  4388.7    0.16       0  4998.5    0.07       0  5004.5    0.16       0
Bank Sta=4998.5,5004.5
Exp/Cntr=0.3,0.1

Type RM Length L Ch R = 1,13943,469,469,469
BEGIN DESCRIPTION:
SERASCA CREEK 24.0
END DESCRIPTION:
XS GIS Cut Line= 2
      3681496.46     10506858.20      3682635.05     10506726.29
#Sta/Elev= 30
  4541.8  309.87  4706.0  296.95  4746.5  287.55  4756.4  283.41  4766.4  281.67
  4776.5  276.90  4806.7  265.67  4825.2  262.40  4830.2  263.23  4836.9  260.87
  4847.0  259.44  4919.0  253.22  4977.8  253.77  4987.9  252.22  4999.7  246.99
  5002.5  246.49  5005.7  246.99  5018.1  253.28  5078.5  253.17  5086.4  255.00
  5128.8  259.55  5209.4  267.95  5263.9  272.22  5366.9  284.04  5450.6  292.94
  5520.1  299.98  5531.5  299.88  5602.0  305.91  5620.6  306.12  5688.0  311.66
#Mann=6,-1,0
  4541.8    0.16       0  4999.7    0.07       0  5005.7    0.16       0
  5366.9    0.12       0  5450.6    0.16       0  5620.6    0.12       0
Bank Sta=4999.7,5005.7
Exp/Cntr=0.3,0.1

Type RM Length L Ch R = 1,13474,462,462,462
BEGIN DESCRIPTION:
SERASCA CREEK 23.0
END DESCRIPTION:
XS GIS Cut Line= 3
      3681699.64     10507210.20      3681949.61     10507260.19
      3682349.61     10507660.19
#Sta/Elev= 30
  4751.3  296.28  4771.7  292.74  4792.1  287.61  4802.3  282.72  4812.5  280.52
  4822.7  275.88  4832.9  273.14  4863.4  269.27  4873.6  267.05  4883.8  266.45
  4955.2  256.54  4965.4  253.34  4975.6  252.05  4993.0  245.39  4995.8  244.89
  4999.0  245.39  5003.7  248.75  5009.8  248.75  5020.4  251.65  5048.6  253.52
  5119.4  255.47  5175.9  256.11  5190.1  257.23  5246.6  259.13  5317.3  263.98
  5331.5  266.13  5359.8  267.43  5430.5  273.92  5487.1  280.97  5571.9  289.70
#Mann=3,-1,0
  4751.3    0.16       0  4993.0    0.07       0  4999.0    0.16       0
Bank Sta=4993,4999
Exp/Cntr=0.3,0.1

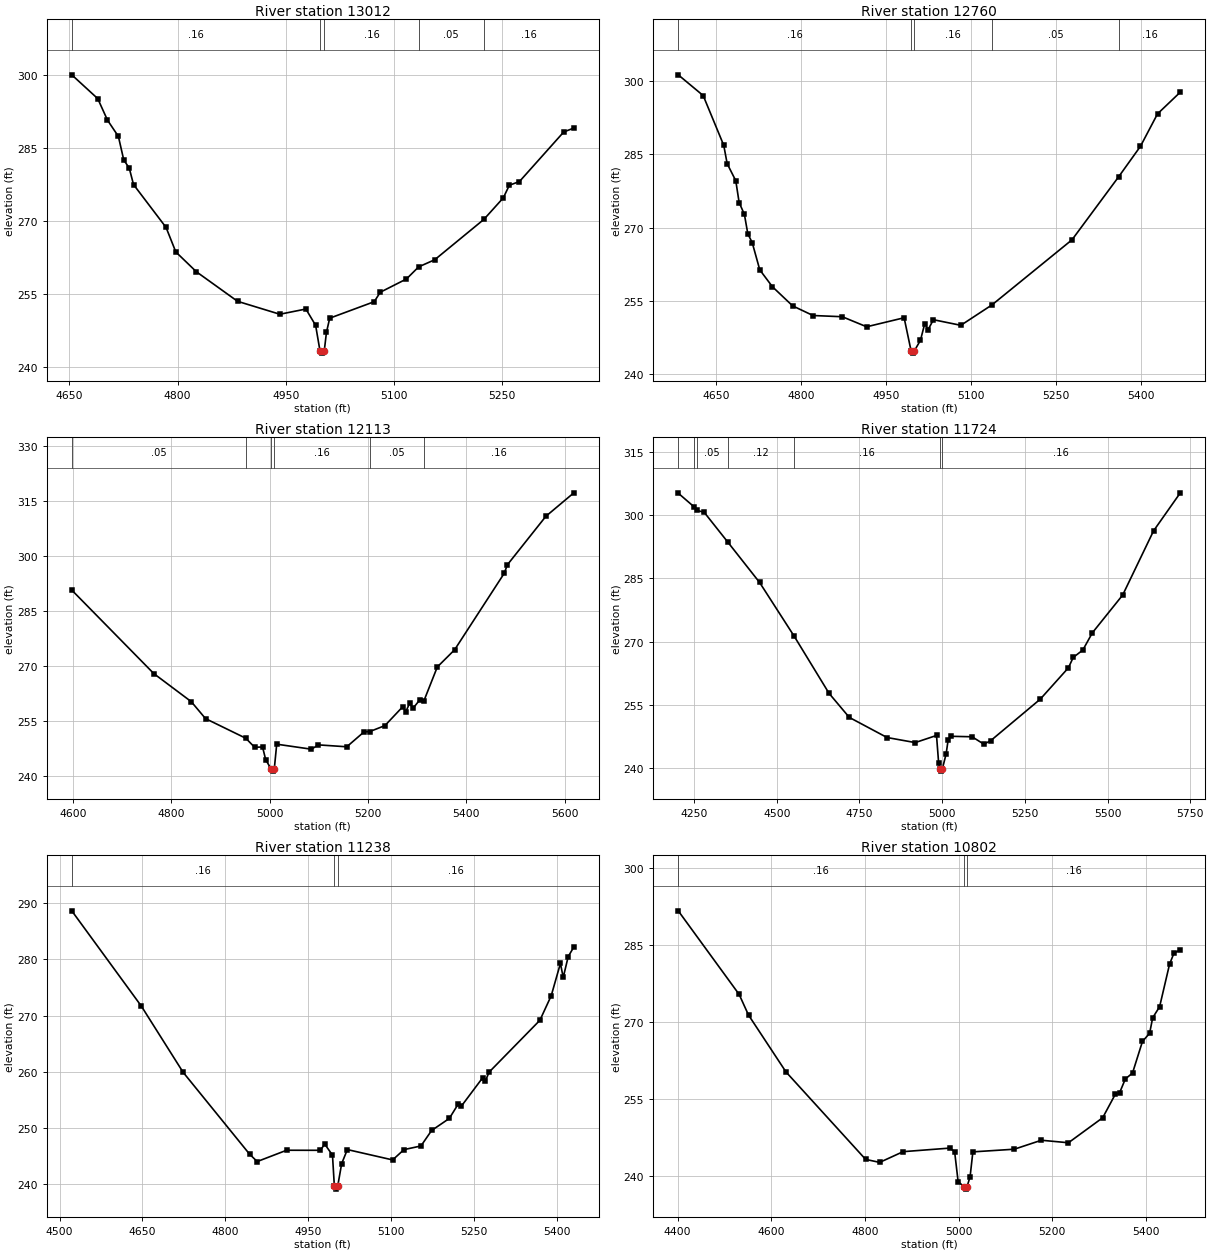
Type RM Length L Ch R = 1,13012,252,252,252
BEGIN DESCRIPTION:
SERASCA CREEK 22.0
END DESCRIPTION:
XS GIS Cut Line= 3
      3681549.65     10507510.21      3681849.61     10507710.19
      3682149.59     10507860.18
#Sta/Elev= 30
  4653.3  299.98  4689.3  295.10  4702.8  290.69  4717.9  287.36  4725.4  282.50
  4732.9  280.90  4738.9  277.49  4784.0  268.70  4797.5  263.68  4826.0  259.62
  4883.1  253.56  4941.7  250.91  4977.8  251.98  4991.3  248.63  4997.3  243.44
  5000.0  242.94  5003.3  243.44  5006.3  247.19  5010.8  250.10  5072.5  253.48
  5080.9  255.42  5117.2  258.14  5134.1  260.62  5156.4  262.08  5224.5  270.35
  5251.4  274.76  5259.8  277.35  5273.8  278.11  5335.2  288.27  5349.2  289.07
#Mann=5,-1,0
  4653.3    0.16       0  4997.3    0.07       0  5003.3    0.16       0
  5134.1    0.05       0  5224.5    0.16       0
Bank Sta=4997.3,5003.3
Exp/Cntr=0.3,0.1

Type RM Length L Ch R = 1,12760,647,647,647
BEGIN DESCRIPTION:
SERASCA CREEK 21.0
END DESCRIPTION:
XS GIS Cut Line= 3
      3681399.62     10507710.19      3681847.86     10507996.58
      3682199.56     10507960.19
#Sta/Elev= 30
  4583.2  301.31  4627.2  297.06  4663.5  286.85  4669.5  283.10  4684.7  279.60
  4690.6  275.14  4699.9  272.70  4705.9  268.74  4713.7  266.91  4727.0  261.34
  4749.3  257.88  4784.9  253.96  4820.9  251.98  4872.5  251.73  4915.5  249.67
  4981.6  251.52  4993.8  244.77  4996.6  244.27  4999.8  244.77  5010.4  246.90
  5018.0  250.33  5023.9  249.07  5033.2  251.12  5081.6  249.97  5136.7  254.17
  5277.7  267.50  5360.1  280.44  5398.4  286.66  5428.5  293.31  5468.7  297.76
#Mann=5,-1,0
  4583.2    0.16       0  4993.8    0.07       0  4999.8    0.16       0
  5136.7    0.05       0  5360.1    0.16       0
Bank Sta=4993.8,4999.8
Exp/Cntr=0.3,0.1

Type RM Length L Ch R = 1,12113,389,389,389
BEGIN DESCRIPTION:
SERASCA CREEK 20.0
END DESCRIPTION:
XS GIS Cut Line= 3
      3681599.58     10508660.20      3681949.61     10508510.19
      3682449.58     10508110.21
#Sta/Elev= 30
  4597.8  290.75  4764.7  267.93  4840.8  260.27  4869.8  255.64  4951.8  250.27
  4969.6  247.81  4985.8  247.88  4992.2  244.41  5003.6  241.79  5006.4  241.29
  5009.6  241.79  5014.6  248.65  5085.1  247.28  5099.5  248.46  5157.1  247.94
  5192.3  252.02  5204.1  252.11  5234.7  253.73  5270.8  258.87  5277.2  257.54
  5285.2  259.93  5291.6  258.42  5306.0  260.82  5314.0  260.50  5341.2  269.74
  5376.4  274.44  5477.3  295.33  5483.7  297.66  5562.1  310.92  5618.9  317.32
#Mann=6,-1,0
  4597.8    0.05       0  4951.8    0.16       0  5003.6    0.07       0
  5009.6    0.16       0  5204.1    0.05       0  5314.0    0.16       0
Bank Sta=5003.6,5009.6
Exp/Cntr=0.3,0.1

Type RM Length L Ch R = 1,11724,486,486,486
BEGIN DESCRIPTION:
SERASCA CREEK 19.0
END DESCRIPTION:
XS GIS Cut Line= 3
      3681427.04     10509108.20      3681878.45     10509031.80
      3682718.71     10508385.99
#Sta/Elev= 30
  4202.3  305.16  4250.5  301.90  4259.0  301.07  4280.6  300.64  4351.5  293.63
  4448.3  284.00  4553.3  271.21  4658.2  257.74  4719.3  252.05  4833.5  247.28
  4918.6  246.08  4983.0  247.77  4989.5  241.14  4994.5  239.82  4997.3  239.32
  5000.5  239.82  5012.0  243.37  5018.3  246.80  5026.5  247.57  5090.4  247.46
  5126.2  245.70  5147.0  246.55  5296.5  256.36  5381.7  263.80  5396.2  266.25
  5425.2  268.00  5454.3  272.11  5545.7  281.03  5639.1  296.24  5719.9  305.24
#Mann=7,-1,0
  4202.3    0.05       0  4250.5    0.12       0  4259.0    0.05       0
  4351.5    0.12       0  4553.3    0.16       0  4994.5    0.07       0
  5000.5    0.16       0
Bank Sta=4994.5,5000.5
Exp/Cntr=0.3,0.1

Type RM Length L Ch R = 1,11238,436,436,436
BEGIN DESCRIPTION:
SERASCA CREEK 18.0
END DESCRIPTION:
XS GIS Cut Line= 3
      3681799.57     10509460.21      3682199.61     10509260.19
      3682649.58     10509160.20
#Sta/Elev= 30
  4522.1  288.62  4647.9  271.69  4723.4  259.94  4843.6  245.39  4857.5  244.06
  4910.7  246.07  4971.9  246.06  4979.6  247.17  4993.7  245.20  4997.1  239.66
  4999.8  239.16  5003.1  239.66  5010.3  243.69  5020.6  246.19  5102.5  244.35
  5123.0  246.18  5153.7  246.83  5173.0  249.58  5205.0  251.72  5221.6  254.35
  5226.7  253.89  5265.1  258.92  5270.3  258.35  5276.7  259.92  5368.9  269.17
  5389.4  273.54  5406.0  279.27  5411.1  276.78  5420.1  280.49  5430.3  282.19
#Mann=3,-1,0
  4522.1    0.16       0  4997.1    0.07       0  5003.1    0.16       0
Bank Sta=4997.1,5003.1
Exp/Cntr=0.3,0.1

Type RM Length L Ch R = 1,10802,479,479,479
BEGIN DESCRIPTION:
SERASCA CREEK 17.0
END DESCRIPTION:
XS GIS Cut Line= 3
      3681799.63     10509610.19      3682399.61     10509610.19
      3682649.62     10509210.17
#Sta/Elev= 30
  4401.5  291.72  4531.5  275.41  4551.5  271.38  4631.5  260.28  4801.5  243.21
  4831.5  242.63  4881.5  244.72  4981.5  245.42  4991.5  244.69  4999.0  238.82
  5012.0  237.91  5014.8  237.41  5018.0  237.91  5024.5  239.84  5030.4  244.68
  5118.8  245.20  5176.6  246.95  5234.4  246.46  5307.5  251.34  5334.6  255.95
  5343.5  256.19  5355.8  258.90  5371.2  260.07  5392.4  266.23  5407.7  267.83
  5414.2  270.85  5429.0  273.00  5450.2  281.29  5459.6  283.46  5473.2  284.10
#Mann=3,-1,0
  4401.5    0.16       0  5012.0    0.07       0  5018.0    0.16       0
Bank Sta=5012,5018
Exp/Cntr=0.3,0.1

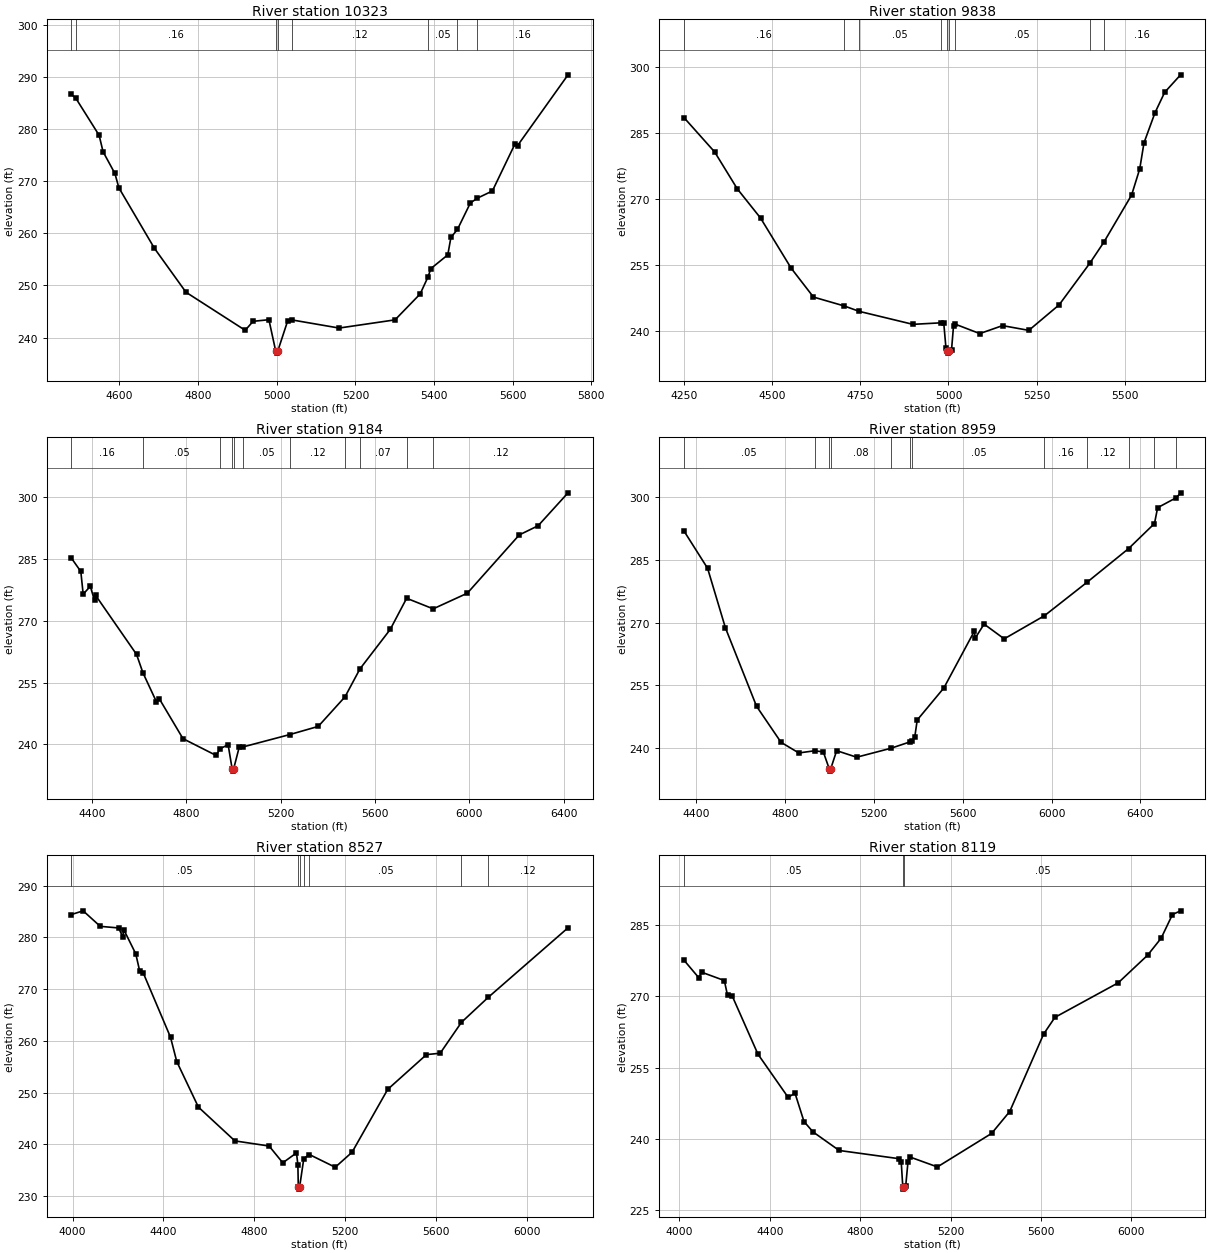
Type RM Length L Ch R = 1,10323,485,485,485
BEGIN DESCRIPTION:
SERASCA CREEK 16.0
END DESCRIPTION:
XS GIS Cut Line= 3
      3681949.62     10510010.19      3682499.61     10510060.19
      3683049.62     10509610.18
#Sta/Elev= 30
  4477.9  286.64  4489.0  285.90  4548.2  278.80  4558.2  275.65  4588.3  271.48
  4598.4  268.73  4688.8  257.13  4769.1  248.70  4919.7  241.40  4939.8  243.12
  4980.0  243.43  4997.0  237.52  4999.8  237.02  5003.0  237.52  5027.6  243.17
  5037.7  243.40  5158.6  241.83  5300.8  243.40  5364.7  248.37  5384.7  251.64
  5391.9  253.23  5435.0  255.87  5442.9  259.20  5459.6  260.75  5492.4  265.82
  5510.4  266.75  5548.4  268.12  5605.8  277.13  5612.3  276.81  5740.8  290.40
#Mann=8,-1,0
  4477.9    0.05       0  4489.0    0.16       0  4997.0    0.07       0
  5003.0    0.16       0  5037.7    0.12       0  5384.7    0.05       0
  5459.6    0.12       0  5510.4    0.16       0
Bank Sta=4997,5003
Exp/Cntr=0.3,0.1

Type RM Length L Ch R = 1,9838,654,654,654
BEGIN DESCRIPTION:
SERASCA CREEK 15.0
END DESCRIPTION:
XS GIS Cut Line= 3
      3682107.60     10510858.20      3682699.61     10510460.19
      3683299.62     10510110.18
#Sta/Elev= 30
  4250.2  288.40  4337.0  280.61  4401.1  272.24  4467.1  265.60  4553.9  254.21
  4617.1  247.65  4704.7  245.62  4746.8  244.40  4899.1  241.45  4979.7  241.80
  4986.7  241.67  4992.9  236.03  4995.7  235.41  4998.5  234.91  5001.7  235.41
  5008.6  235.59  5014.4  241.16  5017.6  241.54  5088.8  239.35  5153.3  241.16
  5227.8  240.08  5313.8  245.88  5400.8  255.34  5440.8  260.14  5519.3  270.83
  5542.4  276.79  5554.4  282.68  5585.8  289.56  5613.1  294.17  5658.2  298.14
#Mann=9,-1,0
  4250.2    0.16       0  4704.7    0.12       0  4746.8    0.05       0
  4979.7    0.16       0  4995.7    0.07       0  5001.7    0.16       0
  5017.6    0.05       0  5400.8    0.12       0  5440.8    0.16       0
Bank Sta=4995.7,5001.7
Exp/Cntr=0.3,0.1

Type RM Length L Ch R = 1,9184,225,225,225
BEGIN DESCRIPTION:
SERASCA CREEK 14.0
END DESCRIPTION:
XS GIS Cut Line= 4
      3682260.41     10510913.75      3683045.12     10511004.02
      3683649.29     10511059.58      3684356.15     10511052.65
#Sta/Elev= 30
  4314.3  285.23  4353.8  282.02  4363.8  276.51  4394.0  278.41  4411.8  274.99
  4416.8  276.19  4589.8  261.88  4616.9  257.41  4673.9  250.39  4685.9  251.13
  4786.6  241.40  4927.5  237.31  4942.4  238.89  4977.8  239.95  4995.0  234.01
  4997.7  233.51  5001.0  234.01  5025.0  239.37  5041.5  239.40  5239.5  242.40
  5359.7  244.38  5473.1  251.57  5536.3  258.35  5664.5  267.93  5734.1  275.51
  5846.6  272.94  5991.2  276.74  6211.2  290.90  6291.3  293.14  6417.8  301.13
#Mann=11,-1,0
  4314.3    0.16       0  4616.9    0.05       0  4942.4    0.16       0
  4995.0    0.07       0  5001.0    0.16       0  5041.5    0.05       0
  5239.5    0.12       0  5473.1    0.08       0  5536.3    0.07       0
  5734.1    0.05       0  5846.6    0.12       0
Bank Sta=4995,5001
Exp/Cntr=0.3,0.1

Type RM Length L Ch R = 1,8959,432,432,432
BEGIN DESCRIPTION:
SERASCA CREEK 13.0
END DESCRIPTION:
XS GIS Cut Line= 4
      3682343.77     10511156.80      3683128.45     10511205.41
      3683850.68     10511288.75      3684572.94     10511260.97
#Sta/Elev= 30
  4345.2  291.90  4451.2  283.00  4531.4  268.75  4671.7  249.96  4781.9  241.34
  4862.0  238.79  4932.8  239.31  4972.2  239.05  4999.3  234.94  5002.0  234.44
  5005.3  234.94  5032.4  239.34  5122.5  237.77  5277.2  239.92  5362.7  241.44
  5373.5  241.71  5384.2  242.64  5395.2  246.68  5515.1  254.35  5651.9  267.89
  5657.0  266.34  5696.3  269.64  5786.9  266.11  5968.2  271.65  6159.1  279.62
  6346.8  287.71  6463.6  293.72  6477.8  297.51  6562.7  299.93  6581.2  301.07
#Mann=12,-1,0
  4345.2    0.05       0  4932.8    0.08       0  4999.3    0.07       0
  5005.3    0.08       0  5277.2    0.05       0  5362.7    0.16       0
  5373.5    0.05       0  5968.2    0.16       0  6159.1    0.12       0
  6346.8    0.05       0  6463.6    0.08       0  6562.7    0.16       0
Bank Sta=4999.3,5005.3
Exp/Cntr=0.3,0.1

Type RM Length L Ch R = 1,8527,408,408,408
BEGIN DESCRIPTION:
SERASCA CREEK 12.0
END DESCRIPTION:
XS GIS Cut Line= 3
      3682281.23     10511392.91      3682704.84     10511580.41
      3684420.10     10511434.58
#Sta/Elev= 30
  3995.3  284.41  4046.5  285.12  4121.9  282.12  4202.7  281.81  4220.5  280.12
  4226.0  281.43  4278.0  276.82  4295.8  273.40  4310.7  273.15  4431.0  260.69
  4458.4  256.00  4553.7  247.19  4714.2  240.66  4864.8  239.67  4925.0  236.43
  4985.2  238.34  4991.3  236.09  4993.3  231.84  4996.1  231.34  4999.3  231.84
  5017.4  237.24  5041.7  238.03  5155.8  235.57  5229.8  238.47  5386.7  250.62
  5557.3  257.34  5617.5  257.60  5711.2  263.58  5829.1  268.41  6180.0  281.84
#Mann=7,-1,0
  3995.3    0.05       0  4993.3    0.03       0  4999.3    0.05       0
  5017.4    0.16       0  5041.7    0.05       0  5711.2    0.16       0
  5829.1    0.12       0
Bank Sta=4993.3,4999.3
Exp/Cntr=0.3,0.1

Type RM Length L Ch R = 1,8119,625,625,625
BEGIN DESCRIPTION:
SERASCA CREEK 11.0
END DESCRIPTION:
XS GIS Cut Line= 3
      3682406.27     10511622.11      3682711.79     10511899.86
      3684495.55     10511934.56
#Sta/Elev= 30
  4021.0  277.63  4085.7  273.98  4099.9  275.10  4199.2  273.36  4213.4  270.22
  4234.3  270.08  4347.9  257.84  4481.7  248.72  4511.7  249.64  4551.7  243.63
  4591.7  241.44  4707.4  237.53  4971.8  235.80  4981.8  235.18  4988.8  229.88
  4991.6  229.38  4994.8  229.88  5001.8  230.06  5011.8  235.15  5021.8  236.13
  5141.9  234.06  5381.9  241.13  5461.9  245.74  5611.9  262.07  5662.0  265.60
  5942.0  272.88  6072.0  278.70  6132.0  282.29  6182.0  287.28  6218.0  288.06
#Mann=3,-1,0
  4021.0    0.05       0  4988.8    0.03       0  4994.8    0.05       0
Bank Sta=4988.8,4994.8
Exp/Cntr=0.3,0.1

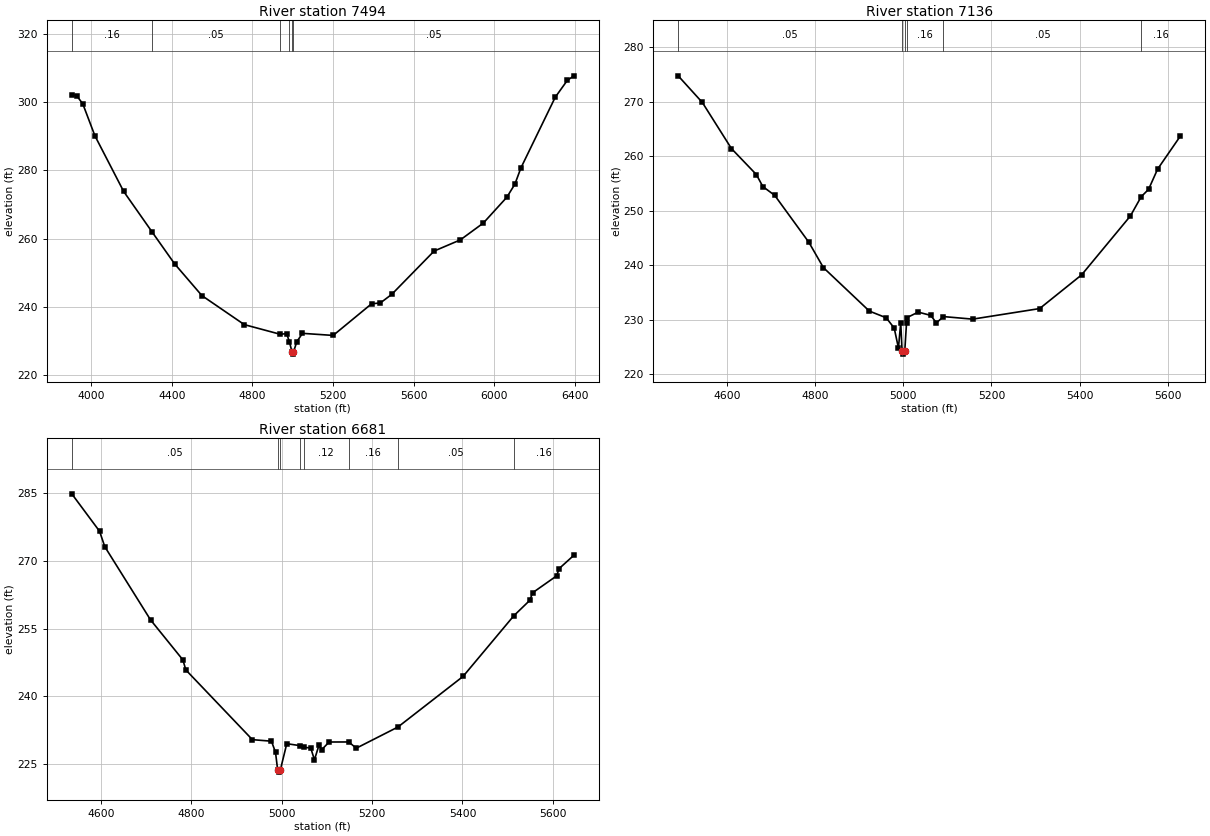
Type RM Length L Ch R = 1,7494,358,358,358
BEGIN DESCRIPTION:
SERASCA CREEK 10.0
END DESCRIPTION:
XS GIS Cut Line= 2
      3682065.08     10512595.17      3684552.02     10512399.86
#Sta/Elev= 30
  3902.2  302.06  3926.8  301.78  3956.9  299.43  4017.1  290.08  4160.0  273.80
  4302.5  261.84  4413.1  252.62  4548.7  243.33  4759.4  234.84  4936.5  232.04
  4970.0  232.19  4983.6  229.75  4997.1  226.71  4999.9  226.21  5003.1  226.71
  5020.2  229.85  5048.4  232.29  5200.7  231.68  5391.3  240.92  5435.6  241.20
  5491.6  243.68  5702.3  256.36  5832.7  259.63  5946.8  264.55  6063.4  272.09
  6103.5  275.92  6133.6  280.69  6304.1  301.36  6364.3  306.31  6396.8  307.62
#Mann=6,-1,0
  3902.2    0.16       0  4302.5    0.05       0  4936.5    0.16       0
  4983.6    0.05       0  4997.1    0.03       0  5003.1    0.05       0
Bank Sta=4997.1,5003.1
Exp/Cntr=0.3,0.1

Type RM Length L Ch R = 1,7136,455,455,455
BEGIN DESCRIPTION:
SERASCA CREEK 9.0
END DESCRIPTION:
XS GIS Cut Line= 3
      3682699.57     10513010.20      3683199.61     10512860.19
      3683799.59     10513010.18
#Sta/Elev= 30
  4488.4  274.80  4543.3  269.91  4609.4  261.45  4665.9  256.69  4680.7  254.48
  4707.7  252.86  4785.1  244.27  4818.2  239.61  4922.6  231.63  4960.9  230.40
  4979.1  228.51  4988.7  224.85  4993.9  229.50  4997.0  224.23  4999.8  223.73
  5003.0  224.23  5007.0  229.39  5007.8  230.42  5033.6  231.44  5062.0  230.84
  5074.9  229.47  5091.0  230.62  5157.3  230.15  5309.4  232.09  5404.7  238.27
  5515.5  249.08  5540.0  252.61  5556.8  253.97  5577.4  257.69  5628.9  263.73
#Mann=6,-1,0
  4488.4    0.05       0  4997.0    0.03       0  5003.0    0.05       0
  5007.0    0.16       0  5091.0    0.05       0  5540.0    0.16       0
Bank Sta=4997,5003
Exp/Cntr=0.3,0.1

Type RM Length L Ch R = 1,6681,457,457,457
BEGIN DESCRIPTION:
SERASCA CREEK 8.0
END DESCRIPTION:
XS GIS Cut Line= 3
      3682799.56     10513410.20      3683249.61     10513310.19
      3683849.58     10513060.20
#Sta/Elev= 30
  4535.6  284.87  4597.1  276.58  4608.6  273.17  4709.8  256.97  4781.5  248.09
  4787.9  245.88  4935.2  230.43  4977.4  230.09  4986.4  227.63  4991.1  223.74
  4993.8  223.24  4997.1  223.74  5011.3  229.54  5039.6  229.12  5049.1  228.73
  5064.3  228.59  5072.5  225.97  5082.8  229.28  5088.2  228.17  5105.0  229.91
  5148.4  229.92  5165.1  228.54  5257.3  233.23  5401.3  244.43  5513.5  257.85
  5549.1  261.29  5555.1  262.95  5608.2  266.69  5614.1  268.33  5646.6  271.27
#Mann=8,-1,0
  4535.6    0.05       0  4991.1    0.03       0  4997.1    0.05       0
  5039.6    0.16       0  5049.1    0.12       0  5148.4    0.16       0
  5257.3    0.05       0  5513.5    0.16       0
Bank Sta=4991.1,4997.1
Exp/Cntr=0.3,0.1