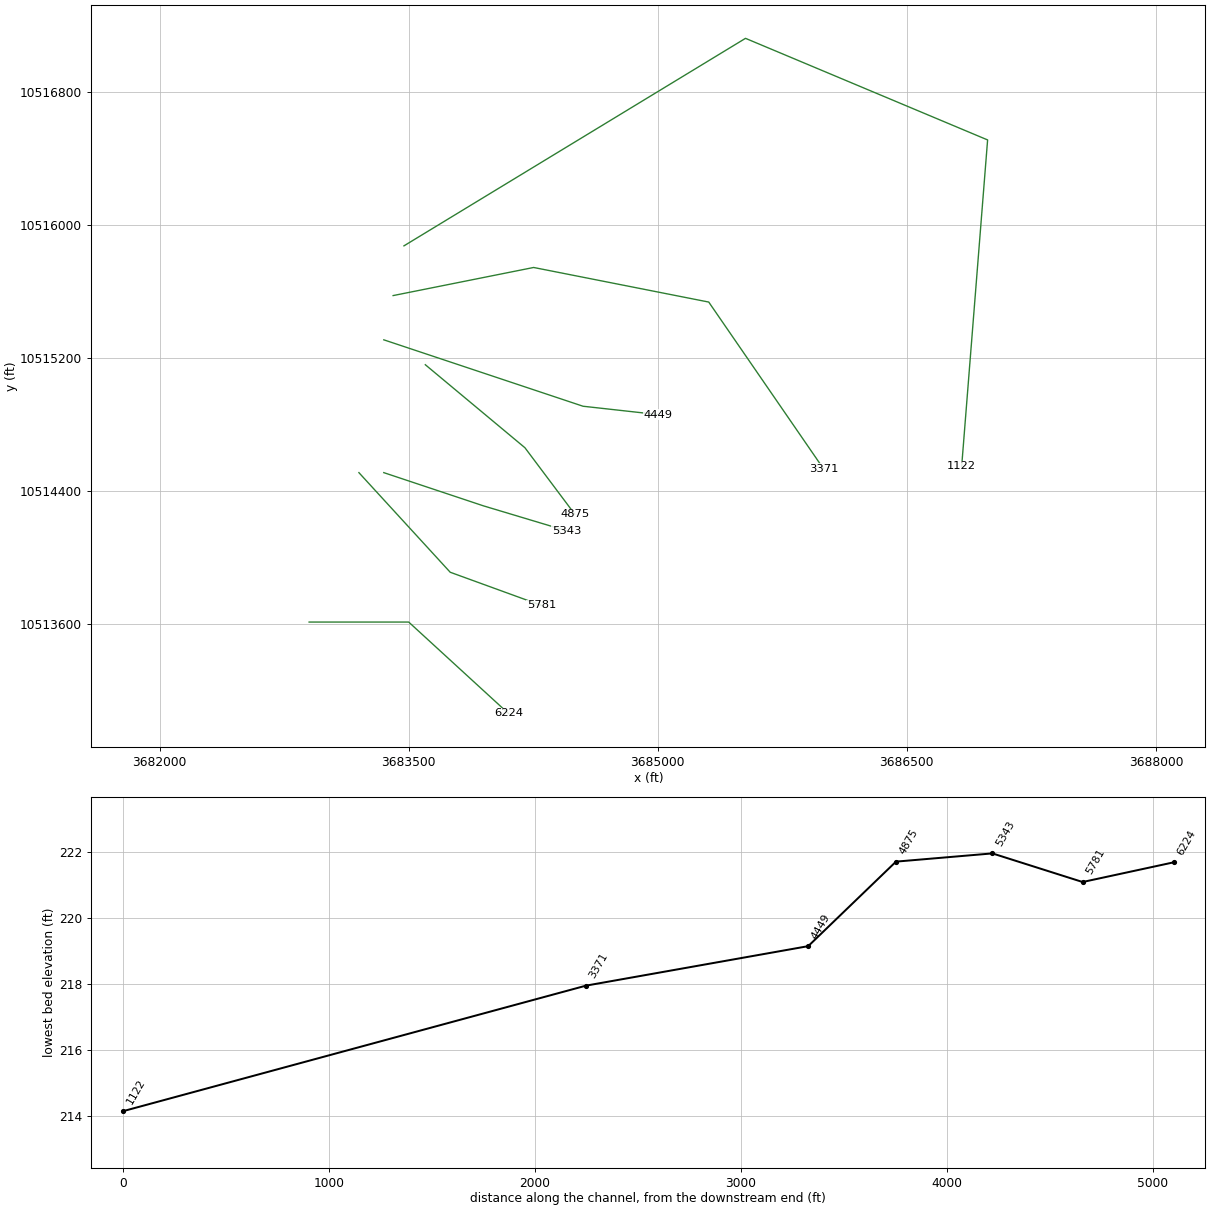
HEC-RAS study SERASCA CREEK.prj: SERASCA CREEK Base Level Engineering

--- SERASCA CREEK.g01 (geometry) --- (continued)

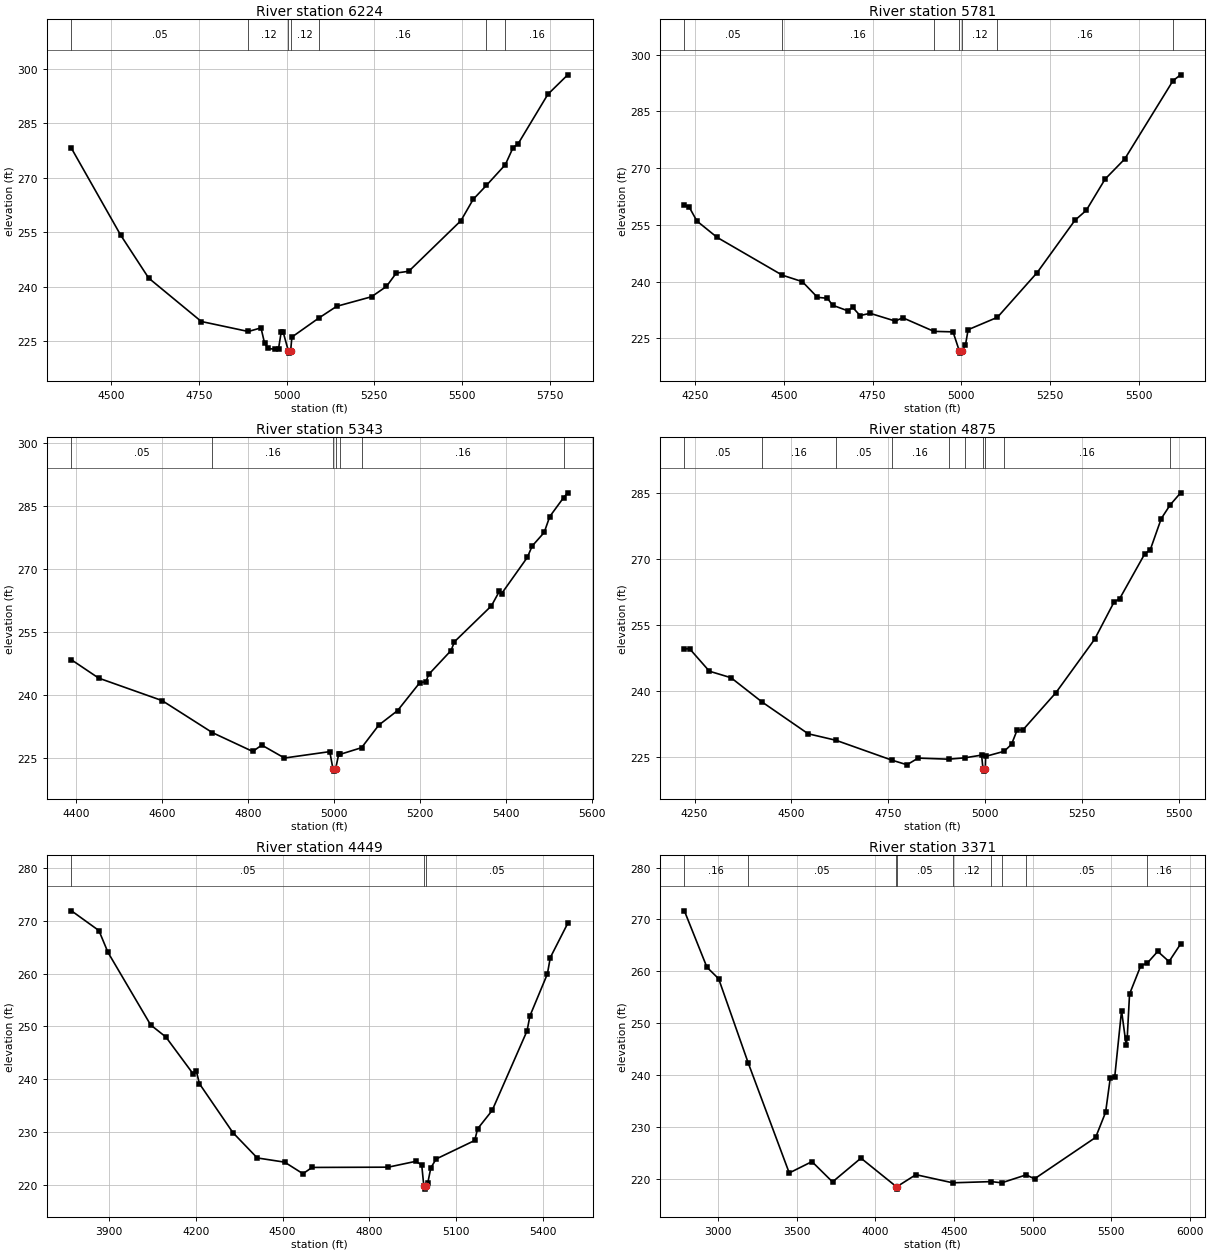
Type RM Length L Ch R = 1,6224,443,443,443
BEGIN DESCRIPTION:
SERASCA CREEK 7.0
END DESCRIPTION:
XS GIS Cut Line= 3
      3682899.59     10513610.19      3683499.61     10513610.19
      3684099.64     10513060.16
#Sta/Elev= 30
  4387.2  278.03  4527.2  254.19  4607.2  242.34  4757.2  230.40  4891.1  227.65
  4927.2  228.65  4937.2  224.51  4947.2  222.98  4967.2  222.76  4977.2  222.95
  4984.7  227.42  4990.6  227.42  5005.5  222.20  5008.2  221.70  5011.5  222.20
  5015.3  226.12  5091.2  231.30  5142.9  234.58  5242.2  237.21  5284.7  240.05
  5312.8  243.74  5348.3  244.22  5496.9  258.14  5532.0  264.03  5569.7  267.86
  5623.4  273.54  5645.5  278.24  5659.7  279.26  5744.7  292.91  5801.2  298.26
#Mann=7,-1,0
  4387.2    0.05       0  4891.1    0.12       0  5005.5    0.07       0
  5011.5    0.12       0  5091.2    0.16       0  5569.7    0.05       0
  5623.4    0.16       0
Bank Sta=5005.5,5011.5
Exp/Cntr=0.3,0.1

Type RM Length L Ch R = 1,5781,438,438,438
BEGIN DESCRIPTION:
SERASCA CREEK 6.0
END DESCRIPTION:
XS GIS Cut Line= 3
      3683199.63     10514510.17      3683749.61     10513910.19
      3684299.57     10513710.20
#Sta/Elev= 30
  4219.3  260.28  4233.1  259.66  4254.7  256.01  4311.5  251.70  4495.2  241.71
  4551.9  239.99  4594.5  235.85  4622.8  235.59  4637.0  233.77  4679.6  232.30
  4693.8  233.19  4714.7  231.03  4743.1  231.62  4814.0  229.57  4835.0  230.45
  4922.9  226.85  4976.8  226.72  4994.8  221.60  4997.5  221.10  5000.8  221.60
  5011.9  223.26  5019.3  227.29  5102.0  230.57  5214.1  242.40  5320.5  256.21
  5352.4  258.83  5405.6  267.10  5460.8  272.40  5597.0  293.10  5618.4  294.65
#Mann=7,-1,0
  4219.3    0.05       0  4495.2    0.16       0  4922.9    0.12       0
  4994.8    0.07       0  5000.8    0.12       0  5102.0    0.16       0
  5597.0    0.05       0
Bank Sta=4994.8,5000.8
Exp/Cntr=0.3,0.1

Type RM Length L Ch R = 1,5343,468,468,468
BEGIN DESCRIPTION:
SERASCA CREEK 5.0
END DESCRIPTION:
XS GIS Cut Line= 3
      3683349.58     10514510.20      3683949.61     10514310.19
      3684449.61     10514160.19
#Sta/Elev= 30
  4389.9  248.46  4453.2  244.11  4600.7  238.76  4717.8  231.13  4811.6  226.65
  4832.6  228.17  4885.4  225.09  4990.8  226.61  4998.3  222.47  5001.1  221.97
  5004.3  222.47  5011.8  226.08  5014.1  225.94  5064.8  227.55  5105.0  232.94
  5148.5  236.37  5199.9  242.98  5214.7  243.28  5220.8  244.97  5273.0  250.68
  5280.8  252.76  5366.9  261.31  5385.2  264.74  5390.4  264.19  5450.4  272.84
  5461.7  275.55  5489.6  278.77  5502.6  282.56  5534.8  287.07  5544.4  288.21
#Mann=7,-1,0
  4389.9    0.05       0  4717.8    0.16       0  4998.3    0.07       0
  5004.3    0.16       0  5014.1    0.12       0  5064.8    0.16       0
  5534.8    0.05       0
Bank Sta=4998.3,5004.3
Exp/Cntr=0.3,0.1

Type RM Length L Ch R = 1,4875,426,426,426
BEGIN DESCRIPTION:
SERASCA CREEK 4.0
END DESCRIPTION:
XS GIS Cut Line= 3
      3683599.57     10515160.22      3684199.61     10514660.19
      3684499.63     10514260.17
#Sta/Elev= 30
  4223.8  249.59  4237.5  249.59  4288.3  244.49  4344.3  243.00  4424.4  237.47
  4543.4  230.23  4615.1  228.75  4759.9  224.21  4798.6  223.17  4827.2  224.69
  4905.9  224.44  4947.6  224.75  4991.2  225.37  4994.7  222.22  4997.5  221.72
  5000.7  222.22  5001.6  225.08  5049.4  226.24  5068.4  227.82  5083.0  231.11
  5097.6  231.09  5183.0  239.59  5283.0  251.77  5333.0  260.23  5347.6  261.01
  5412.2  271.20  5426.7  272.18  5454.9  279.25  5477.9  282.37  5504.9  285.13
#Mann=10,-1,0
  4223.8    0.05       0  4424.4    0.16       0  4615.1    0.05       0
  4759.9    0.16       0  4905.9    0.07       0  4947.6    0.05       0
  4994.7    0.03       0  5000.7    0.05       0  5049.4    0.16       0
  5477.9    0.05       0
Bank Sta=4994.7,5000.7
Exp/Cntr=0.3,0.1

Type RM Length L Ch R = 1,4449,1078,1078,1078
BEGIN DESCRIPTION:
SERASCA CREEK 3.0
END DESCRIPTION:
XS GIS Cut Line= 3
      3683349.57     10515310.20      3684549.61     10514910.19
      3684999.58     10514860.19
#Sta/Elev= 30
  3769.5  271.88  3864.4  268.14  3896.0  263.99  4043.6  250.26  4096.3  247.97
  4191.2  240.94  4201.7  241.53  4212.3  239.13  4328.2  229.86  4412.5  225.06
  4507.4  224.26  4570.7  222.07  4602.3  223.26  4865.8  223.31  4960.7  224.41
  4981.8  223.74  4989.3  219.65  4992.0  219.15  4995.3  219.65  5002.8  220.32
  5013.4  223.19  5031.8  224.86  5165.3  228.37  5175.3  230.58  5225.6  234.05
  5346.4  249.13  5356.4  251.97  5416.8  259.92  5426.9  263.02  5487.2  269.50
#Mann=3,-1,0
  3769.5    0.05       0  4989.3    0.03       0  4995.3    0.05       0
Bank Sta=4989.3,4995.3
Exp/Cntr=0.3,0.1

Type RM Length L Ch R = 1,3371,2249,2249,2249
BEGIN DESCRIPTION:
SERASCA CREEK 2.0
END DESCRIPTION:
XS GIS Cut Line= 4
      3683405.80     10515576.72      3684252.12     10515745.98
      3685306.80     10515537.65      3685996.86     10514535.12
#Sta/Elev= 30
  2785.5  271.66  2928.9  260.78  3003.5  258.55  3191.4  242.31  3452.3  221.07
  3596.8  223.26  3727.6  219.34  3908.3  223.93  4132.3  218.45  4135.0  217.95
  4138.3  218.45  4257.6  220.74  4491.4  219.17  4736.9  219.40  4803.1  219.17
  4958.6  220.70  5011.9  219.94  5400.4  227.93  5463.8  232.78  5493.6  239.43
  5521.8  239.59  5565.3  252.41  5594.6  245.72  5601.2  247.08  5616.1  255.60
  5687.7  261.08  5728.3  261.55  5795.3  263.83  5867.0  261.87  5940.7  265.26
#Mann=9,-1,0
  2785.5    0.16       0  3191.4    0.05       0  4132.3    0.03       0
  4138.3    0.05       0  4491.4    0.12       0  4736.9    0.05       0
  4803.1    0.07       0  4958.6    0.05       0  5728.3    0.16       0
Bank Sta=4132.3,4138.3
Exp/Cntr=0.3,0.1

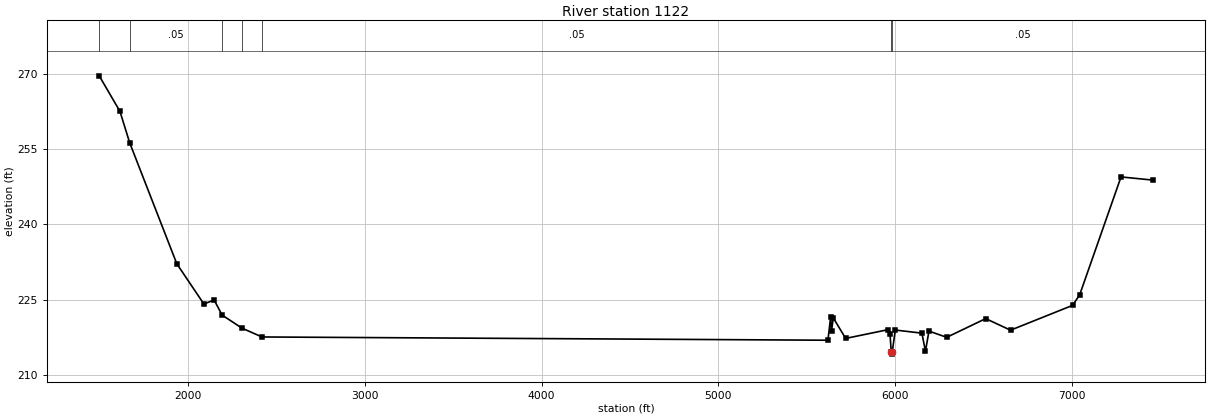
Type RM Length L Ch R = 1,1122,0,0,0
BEGIN DESCRIPTION:
SERASCA CREEK 1.0
END DESCRIPTION:
XS GIS Cut Line= 4
      3683470.89     10515876.20      3685528.16     10517126.19
      3686986.49     10516514.21      3686830.24     10514548.09
#Sta/Elev= 30
  1497.1  269.60  1614.6  262.50  1669.7  256.23  1936.2  232.13  2089.3  224.12
  2147.5  224.92  2192.1  221.92  2305.2  219.30  2418.2  217.55  5620.3  216.90
  5635.6  221.47  5640.6  218.69  5650.4  221.37  5720.6  217.26  5961.4  219.01
  5971.4  218.19  5978.5  214.63  5981.2  214.13  5984.5  214.63  6001.5  218.93
  6152.0  218.31  6172.1  214.71  6192.1  218.72  6292.4  217.48  6513.1  221.21
  6653.6  218.90  7004.7  223.85  7044.8  225.95  7278.7  249.45  7458.2  248.82
#Mann=7,-1,0
  1497.1    0.16       0  1669.7    0.05       0  2192.1    0.12       0
  2305.2    0.07       0  2418.2    0.05       0  5978.5   0.033       0
  5984.5    0.05       0
Bank Sta=5978.5,5984.5
Exp/Cntr=0.3,0.1

Chan Stop Cuts=-1