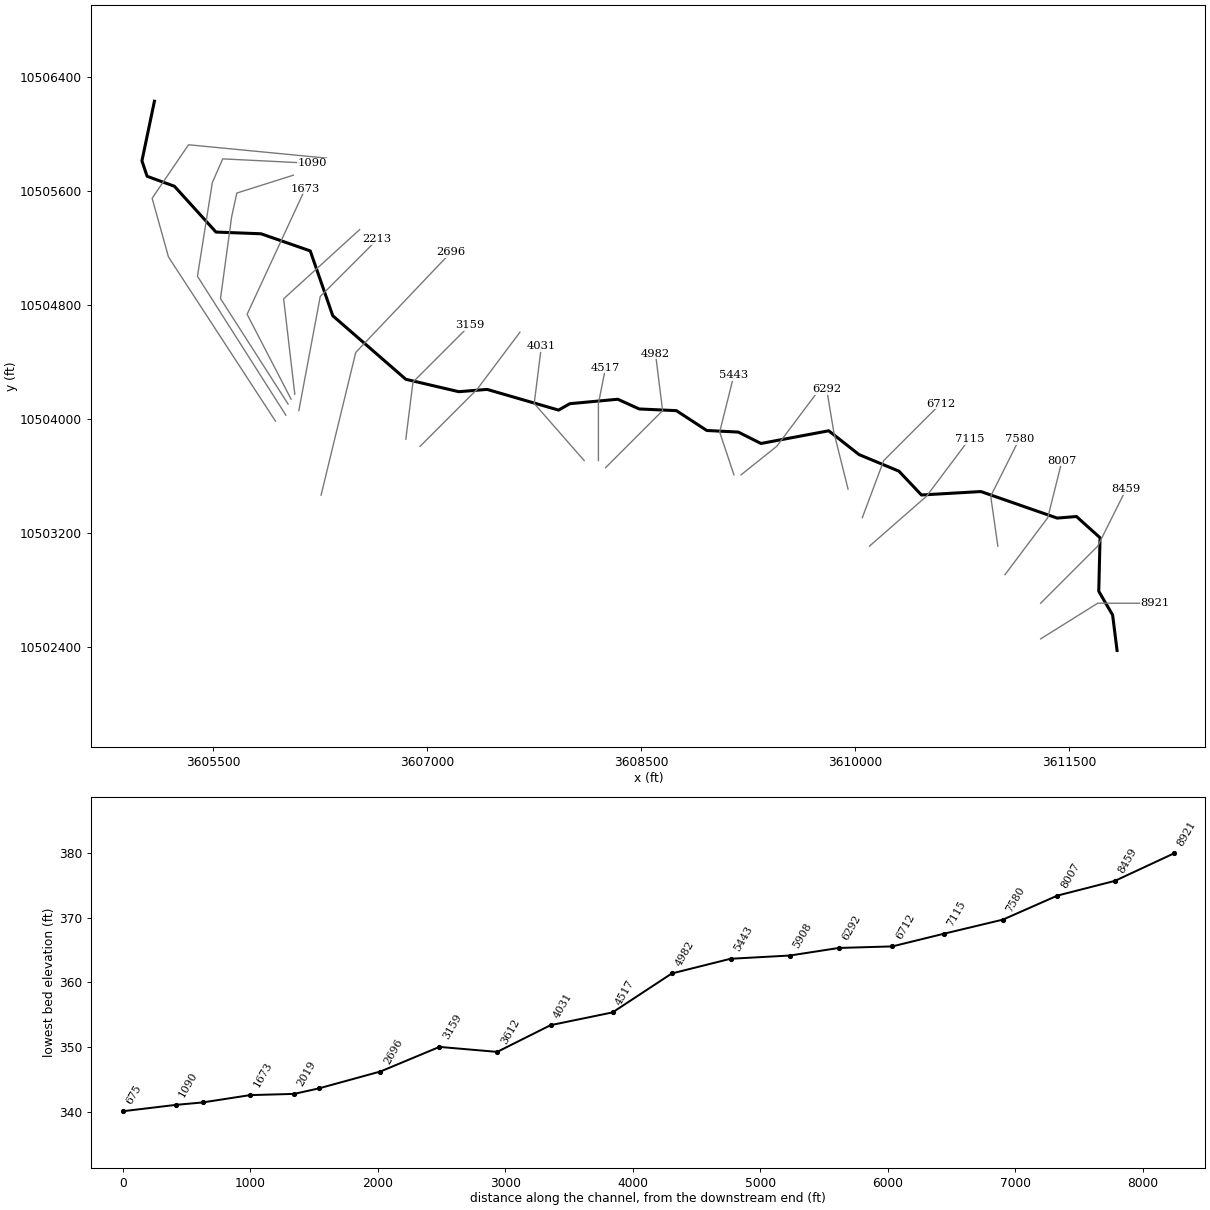
--- TAPE CREEK.prj (project) ---

Proj Title=TAPE CREEK Base Level Engineering
Current Plan=p01
Default Exp/Contr=0.3,0.1
English Units
Geom File=g01
Flow File=f01
Plan File=p01
BEGIN DESCRIPTION:
TAPE CREEK
END DESCRIPTION:

--- TAPE CREEK.p01 (plan) ---

Plan Title=Multiple Run
Short Identifier=Multiple
Geom File=g01
Flow File=f01
Subcritical Flow
K Sum by GR= 0
Std Step Tol= 0.01
Critical Tol= 0.01
Num of Std Step Trials= 20
Max Error Tol= 0.3
Flow Tol Ratio= 0.001
Split Flow NTrial= 30
Split Flow Tol= 0.02
Split Flow Ratio= 0.02
Log Output Level= 0
Friction Slope Method= 1
Unsteady Friction Slope Method= 2
Unsteady Bridges Friction Slope Method= 1
Parabolic Critical Depth
Global Vel Dist=  1 , 1 , 1
Global Log Level= 0
CheckData=True
Encroach Param= -1, 0, 0, 0
BEGIN DESCRIPTION:
Multiple Run
END DESCRIPTION:

--- TAPE CREEK.f01 (steady flow) ---

Flow Title=Multiple
Number of Profiles=7
Profile Names=10-year,25-year,50-year,1pct_min,100-year,1pct_plu,500-year
River Rch & RM= TAPE CREEK,Reach-1,8921
    1898    2717    3421    3139    4246    5742    6522
River Rch & RM= TAPE CREEK,Reach-1,5443
    2341    3381    4280    3946    5336    7217    8276
Boundary for River Rch & Prof#=TAPE CREEK,Reach-1,1
Up Type=0
Dn Type=3
Dn Slope=0.005
Boundary for River Rch & Prof#=TAPE CREEK,Reach-1,2
Up Type=0
Dn Type=3
Dn Slope=0.005
Boundary for River Rch & Prof#=TAPE CREEK,Reach-1,3
Up Type=0
Dn Type=3
Dn Slope=0.005
Boundary for River Rch & Prof#=TAPE CREEK,Reach-1,4
Up Type=0
Dn Type=3
Dn Slope=0.005
Boundary for River Rch & Prof#=TAPE CREEK,Reach-1,5
Up Type=0
Dn Type=3
Dn Slope=0.005
Boundary for River Rch & Prof#=TAPE CREEK,Reach-1,6
Up Type=0
Dn Type=3
Dn Slope=0.005
Boundary for River Rch & Prof#=TAPE CREEK,Reach-1,7
Up Type=0
Dn Type=3
Dn Slope=0.005

--- TAPE CREEK.g01 (geometry) ---

Geom Title=Existing Conditions

River Reach=TAPE CREEK,Reach-1
Reach XY= 30
      3611835.25     10502379.00      3611804.00     10502628.00
      3611707.00     10502794.00      3611716.00     10503169.00
      3611550.75     10503318.00      3611415.25     10503307.00
      3610880.50     10503493.00      3610464.00     10503469.00
      3610306.00     10503636.00      3610026.75     10503752.00
      3609814.00     10503919.00      3609339.25     10503830.00
      3609179.75     10503910.00      3608959.25     10503921.00
      3608746.25     10504060.00      3608485.50     10504072.00
      3608335.50     10504140.00      3607999.75     10504109.00
      3607920.25     10504064.00      3607419.50     10504209.00
      3607220.50     10504193.00      3606849.50     10504280.00
      3606337.75     10504725.00      3606179.50     10505180.00
      3605834.25     10505300.00      3605518.75     10505312.00
      3605227.50     10505633.00      3605036.00     10505703.00
      3604999.75     10505811.00      3605087.25     10506229.00

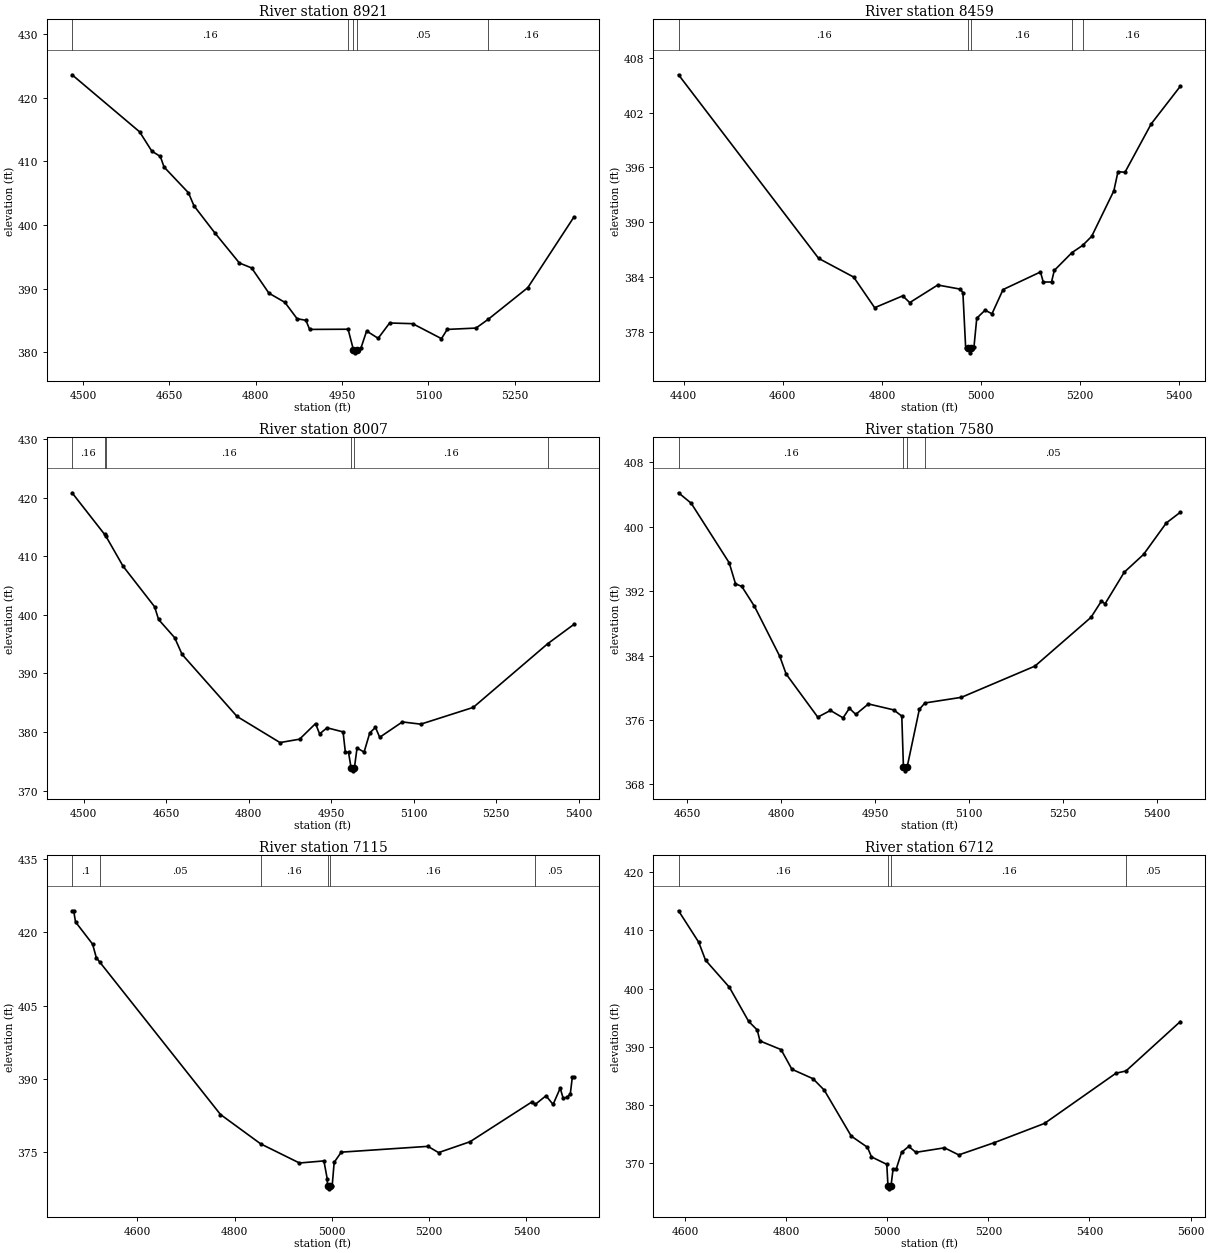
Type RM Length L Ch R = 1,8921,462,462,462
BEGIN DESCRIPTION:
TAPE CREEK 17.0
END DESCRIPTION:
XS GIS Cut Line= 3
      3611299.62     10502460.19      3611699.61     10502710.19
      3612099.62     10502710.19
#Sta/Elev= 30
  4480.9  423.59  4598.2  414.63  4619.4  411.60  4634.2  410.76  4640.7  409.10
  4683.1  405.05  4692.6  403.02  4728.5  398.80  4771.6  394.02  4792.8  393.25
  4822.9  389.28  4850.6  387.84  4871.8  385.27  4887.1  385.02  4893.6  383.59
  4960.4  383.62  4969.6  380.41  4972.3  379.91  4975.6  380.41  4982.6  380.63
  4992.6  383.34  5012.6  382.19  5032.6  384.60  5072.6  384.49  5122.6  382.14
  5132.6  383.59  5182.6  383.80  5203.7  385.17  5272.6  390.15  5352.6  401.23
#Mann=5,-1,0
  4480.9    0.16       0  4960.4    0.05       0  4969.6    0.04       0
  4975.6    0.05       0  5203.7    0.16       0
Bank Sta=4969.6,4975.6
Exp/Cntr=0.3,0.1

Type RM Length L Ch R = 1,8459,452,452,452
BEGIN DESCRIPTION:
TAPE CREEK 16.0
END DESCRIPTION:
XS GIS Cut Line= 3
      3611299.63     10502710.21      3611699.61     10503110.19
      3611899.62     10503510.22
#Sta/Elev= 30
  4389.4  406.17  4672.2  386.03  4742.9  383.98  4785.3  380.62  4841.9  381.92
  4856.1  381.18  4912.6  383.11  4957.8  382.66  4963.4  382.28  4969.0  376.20
  4974.4  376.17  4977.2  375.67  4980.4  376.17  4985.8  376.34  4991.4  379.47
  5008.2  380.35  5022.1  379.95  5044.5  382.61  5120.0  384.54  5125.6  383.44
  5142.3  383.44  5147.9  384.71  5183.7  386.67  5205.0  387.45  5223.4  388.45
  5268.1  393.44  5276.5  395.55  5290.5  395.47  5343.6  400.79  5402.3  404.91
#Mann=5,-1,0
  4389.4    0.16       0  4974.4    0.07       0  4980.4    0.16       0
  5183.7    0.05       0  5205.0    0.16       0
Bank Sta=4974.4,4980.4
Exp/Cntr=0.3,0.1

Type RM Length L Ch R = 1,8007,427,427,427
BEGIN DESCRIPTION:
TAPE CREEK 15.0
END DESCRIPTION:
XS GIS Cut Line= 3
      3611049.59     10502910.17      3611349.61     10503310.19
      3611449.60     10503710.16
#Sta/Elev= 30
  4478.9  420.81  4538.0  413.72  4540.2  413.44  4571.6  408.29  4628.9  401.38
  4636.2  399.20  4665.4  396.10  4678.9  393.25  4778.9  382.66  4857.0  378.21
  4892.5  378.79  4921.6  381.45  4928.9  379.69  4942.5  380.73  4971.6  380.03
  4975.8  376.55  4981.5  376.55  4986.2  373.89  4989.0  373.39  4992.2  373.89
  4997.0  377.28  5009.8  376.59  5020.2  379.87  5030.5  380.80  5038.2  379.11
  5079.4  381.73  5112.9  381.35  5208.3  384.21  5343.9  395.09  5391.2  398.36
#Mann=6,-1,0
  4478.9    0.16       0  4538.0    0.05       0  4540.2    0.16       0
  4986.2    0.07       0  4992.2    0.16       0  5343.9    0.05       0
Bank Sta=4986.2,4992.2
Exp/Cntr=0.3,0.1

Type RM Length L Ch R = 1,7580,465,465,465
BEGIN DESCRIPTION:
TAPE CREEK 14.0
END DESCRIPTION:
XS GIS Cut Line= 3
      3610999.61     10503110.20      3610949.61     10503460.19
      3611149.63     10503860.23
#Sta/Elev= 30
  4636.4  404.22  4656.6  402.92  4717.2  395.53  4727.3  392.92  4737.4  392.58
  4757.6  390.11  4798.0  383.90  4808.1  381.71  4858.6  376.35  4878.8  377.18
  4899.0  376.26  4909.1  377.45  4919.2  376.69  4939.4  377.99  4979.8  377.25
  4992.7  376.48  4995.3  370.18  4998.1  369.68  5001.3  370.18  5020.7  377.32
  5029.6  378.11  5087.8  378.81  5205.2  382.69  5294.6  388.74  5311.4  390.78
  5317.0  390.42  5347.7  394.35  5378.5  396.56  5414.8  400.47  5437.2  401.80
#Mann=4,-1,0
  4636.4    0.16       0  4995.3    0.07       0  5001.3    0.16       0
  5029.6    0.05       0
Bank Sta=4995.3,5001.3
Exp/Cntr=0.3,0.1

Type RM Length L Ch R = 1,7115,403,403,403
BEGIN DESCRIPTION:
TAPE CREEK 13.0
END DESCRIPTION:
XS GIS Cut Line= 3
      3610099.62     10503110.20      3610499.61     10503460.19
      3610799.61     10503860.19
#Sta/Elev= 30
  4466.1  424.42  4469.4  424.42  4473.2  422.14  4508.3  417.59  4515.9  414.83
  4523.3  413.88  4771.2  382.71  4853.8  376.70  4933.5  372.78  4983.8  373.21
  4990.5  369.59  4991.3  367.99  4994.0  367.49  4997.3  367.99  5000.7  367.99
  5004.9  372.92  5019.5  375.00  5197.6  376.19  5219.5  374.91  5284.1  377.13
  5411.1  385.27  5418.4  384.79  5440.3  386.54  5454.9  384.77  5469.5  388.10
  5475.7  386.03  5484.1  386.25  5490.3  386.94  5494.5  390.41  5497.6  390.41
#Mann=6,-1,0
  4466.1     0.1       0  4523.3    0.05       0  4853.8    0.16       0
  4991.3    0.07       0  4997.3    0.16       0  5418.4    0.05       0
Bank Sta=4991.3,4997.3
Exp/Cntr=0.3,0.1

Type RM Length L Ch R = 1,6712,420,420,420
BEGIN DESCRIPTION:
TAPE CREEK 12.0
END DESCRIPTION:
XS GIS Cut Line= 3
      3610049.62     10503310.20      3610199.61     10503710.19
      3610599.63     10504110.21
#Sta/Elev= 30
  4586.9  413.39  4626.9  407.97  4640.3  404.89  4687.5  400.23  4725.7  394.35
  4742.6  392.88  4748.0  390.99  4789.8  389.50  4811.2  386.12  4853.0  384.49
  4875.2  382.53  4928.6  374.62  4960.7  372.69  4968.7  371.04  4999.0  369.75
  5001.3  366.04  5004.0  365.54  5007.3  366.04  5011.4  368.94  5017.6  368.94
  5028.2  371.82  5042.4  372.84  5056.5  371.82  5113.1  372.60  5141.4  371.38
  5212.1  373.50  5311.1  376.80  5452.5  385.44  5472.2  385.82  5579.8  394.33
#Mann=4,-1,0
  4586.9    0.16       0  5001.3    0.07       0  5007.3    0.16       0
  5472.2    0.05       0
Bank Sta=5001.3,5007.3
Exp/Cntr=0.3,0.1

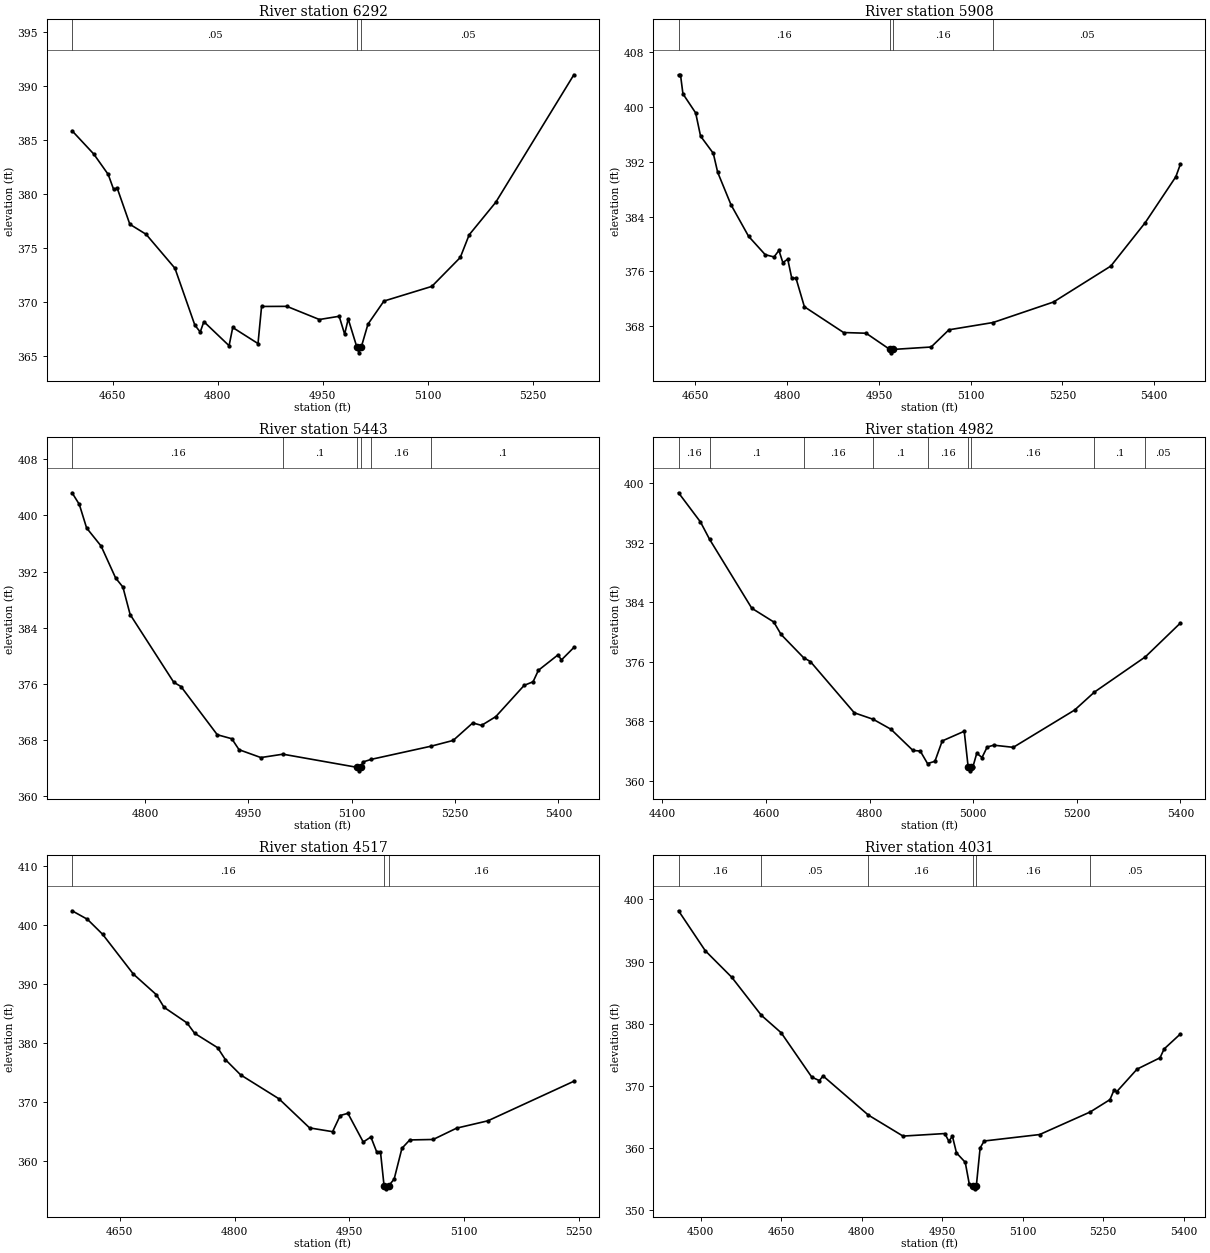
Type RM Length L Ch R = 1,6292,384,384,384
BEGIN DESCRIPTION:
TAPE CREEK 11.0
END DESCRIPTION:
XS GIS Cut Line= 3
      3609949.62     10503510.14      3609849.61     10503910.19
      3609799.61     10504210.19
#Sta/Elev= 30
  4592.2  385.89  4623.2  383.73  4643.8  381.84  4651.5  380.46  4656.7  380.56
  4674.7  377.22  4697.9  376.29  4739.1  373.14  4767.5  367.87  4775.2  367.23
  4780.4  368.19  4816.4  365.96  4821.6  367.65  4857.7  366.16  4862.8  369.60
  4898.9  369.61  4945.3  368.39  4973.6  368.69  4981.4  367.03  4986.5  368.44
  4999.0  365.80  5001.7  365.30  5005.0  365.80  5014.7  367.96  5037.5  370.10
  5105.9  371.46  5146.5  374.14  5159.2  376.24  5197.2  379.26  5308.7  391.08
#Mann=3,-1,0
  4592.2    0.05       0  4999.0    0.03       0  5005.0    0.05       0
Bank Sta=4999,5005
Exp/Cntr=0.3,0.1

Type RM Length L Ch R = 1,5908,465,465,465
BEGIN DESCRIPTION:
TAPE CREEK 10.0
END DESCRIPTION:
XS GIS Cut Line= 3
      3609199.59     10503610.18      3609449.61     10503810.19
      3609749.62     10504210.21
#Sta/Elev= 30
  4622.4  404.67  4625.6  404.67  4629.6  401.89  4650.4  399.11  4658.4  395.73
  4679.2  393.22  4686.4  390.45  4708.1  385.73  4736.9  381.12  4764.1  378.44
  4778.5  378.11  4786.5  379.06  4792.9  377.29  4800.9  377.78  4807.3  375.08
  4814.5  374.98  4828.1  370.85  4892.2  367.09  4929.0  366.99  4967.7  364.63
  4970.4  364.13  4973.7  364.63  5035.3  364.98  5064.4  367.49  5136.5  368.55
  5235.3  371.54  5329.0  376.78  5385.3  383.12  5435.3  389.81  5442.6  391.61
#Mann=4,-1,0
  4622.4    0.16       0  4967.7    0.07       0  4973.7    0.16       0
  5136.5    0.05       0
Bank Sta=4967.7,4973.7
Exp/Cntr=0.3,0.1

Type RM Length L Ch R = 1,5443,461,461,461
BEGIN DESCRIPTION:
TAPE CREEK 9.0
END DESCRIPTION:
XS GIS Cut Line= 3
      3609149.61     10503610.18      3609049.61     10503910.19
      3609149.60     10504310.15
#Sta/Elev= 30
  4693.9  403.21  4704.4  401.56  4715.0  398.20  4736.1  395.62  4757.2  391.07
  4767.7  389.79  4778.2  385.88  4841.5  376.24  4852.0  375.63  4904.7  368.77
  4925.8  368.20  4936.3  366.64  4968.0  365.52  5000.0  366.00  5107.6  364.13
  5110.4  363.63  5113.6  364.13  5115.8  364.88  5128.5  365.27  5215.6  367.15
  5247.2  367.96  5275.6  370.45  5288.4  370.10  5309.1  371.35  5350.3  375.80
  5363.2  376.31  5370.9  377.94  5399.3  380.13  5404.4  379.42  5422.4  381.19
#Mann=6,-1,0
  4693.9    0.16       0  5000.0     0.1       0  5107.6    0.07       0
  5113.6     0.1       0  5128.5    0.16       0  5215.6     0.1       0
Bank Sta=5107.6,5113.6
Exp/Cntr=0.3,0.1

Type RM Length L Ch R = 1,4982,465,465,465
BEGIN DESCRIPTION:
TAPE CREEK 8.0
END DESCRIPTION:
XS GIS Cut Line= 3
      3608249.60     10503660.18      3608649.61     10504060.19
      3608599.61     10504460.17
#Sta/Elev= 30
  4431.1  398.74  4473.5  394.81  4491.0  392.49  4572.5  383.22  4615.0  381.37
  4629.1  379.69  4672.4  376.58  4685.7  376.05  4770.5  369.16  4806.9  368.29
  4841.2  366.95  4883.7  364.10  4897.8  364.02  4911.8  362.34  4926.1  362.64
  4940.2  365.38  4982.7  366.68  4990.3  361.86  4993.0  361.36  4996.3  361.86
  4999.3  361.86  5006.9  363.73  5017.0  363.15  5027.0  364.56  5039.6  364.81
  5077.4  364.52  5195.8  369.53  5234.1  371.95  5332.5  376.69  5399.9  381.22
#Mann=9,-1,0
  4431.1    0.16       0  4491.0     0.1       0  4672.4    0.16       0
  4806.9     0.1       0  4911.8    0.16       0  4990.3    0.07       0
  4996.3    0.16       0  5234.1     0.1       0  5332.5    0.05       0
Bank Sta=4990.3,4996.3
Exp/Cntr=0.3,0.1

Type RM Length L Ch R = 1,4517,486,486,486
BEGIN DESCRIPTION:
TAPE CREEK 7.0
END DESCRIPTION:
XS GIS Cut Line= 3
      3608199.61     10503710.23      3608199.61     10504110.19
      3608249.61     10504360.18
#Sta/Elev= 30
  4588.0  402.43  4608.0  400.99  4628.0  398.43  4668.0  391.71  4698.0  388.22
  4708.0  386.09  4738.0  383.44  4748.0  381.68  4778.0  379.24  4788.0  377.24
  4808.0  374.64  4858.0  370.59  4898.0  365.66  4928.0  365.02  4938.0  367.76
  4948.0  368.13  4968.0  363.27  4978.0  364.12  4985.5  361.62  4990.5  361.62
  4995.2  355.84  4997.9  355.34  5001.2  355.84  5008.4  357.01  5018.5  362.20
  5028.7  363.62  5059.3  363.70  5089.9  365.62  5130.7  366.86  5242.9  373.56
#Mann=3,-1,0
  4588.0    0.16       0  4995.2    0.07       0  5001.2    0.16       0
Bank Sta=4995.2,5001.2
Exp/Cntr=0.3,0.1

Type RM Length L Ch R = 1,4031,419,419,419
BEGIN DESCRIPTION:
TAPE CREEK 6.0
END DESCRIPTION:
XS GIS Cut Line= 3
      3608099.61     10503710.19      3607749.61     10504110.19
      3607799.61     10504510.17
#Sta/Elev= 30
  4458.9  398.18  4508.7  391.74  4558.1  387.46  4613.2  381.33  4650.1  378.52
  4707.1  371.37  4721.3  370.81  4728.0  371.57  4812.4  365.26  4877.0  361.87
  4954.8  362.28  4962.4  361.04  4969.0  361.85  4976.6  359.16  4992.9  357.65
  5000.5  354.10  5007.6  353.87  5010.3  353.37  5013.6  353.87  5020.6  359.96
  5028.2  361.08  5131.5  362.12  5225.7  365.76  5262.5  367.75  5270.1  369.31
  5275.1  369.03  5312.9  372.66  5355.7  374.49  5363.3  375.91  5393.5  378.32
#Mann=6,-1,0
  4458.9    0.16       0  4613.2    0.05       0  4812.4    0.16       0
  5007.6    0.07       0  5013.6    0.16       0  5225.7    0.05       0
Bank Sta=5007.6,5013.6
Exp/Cntr=0.3,0.1

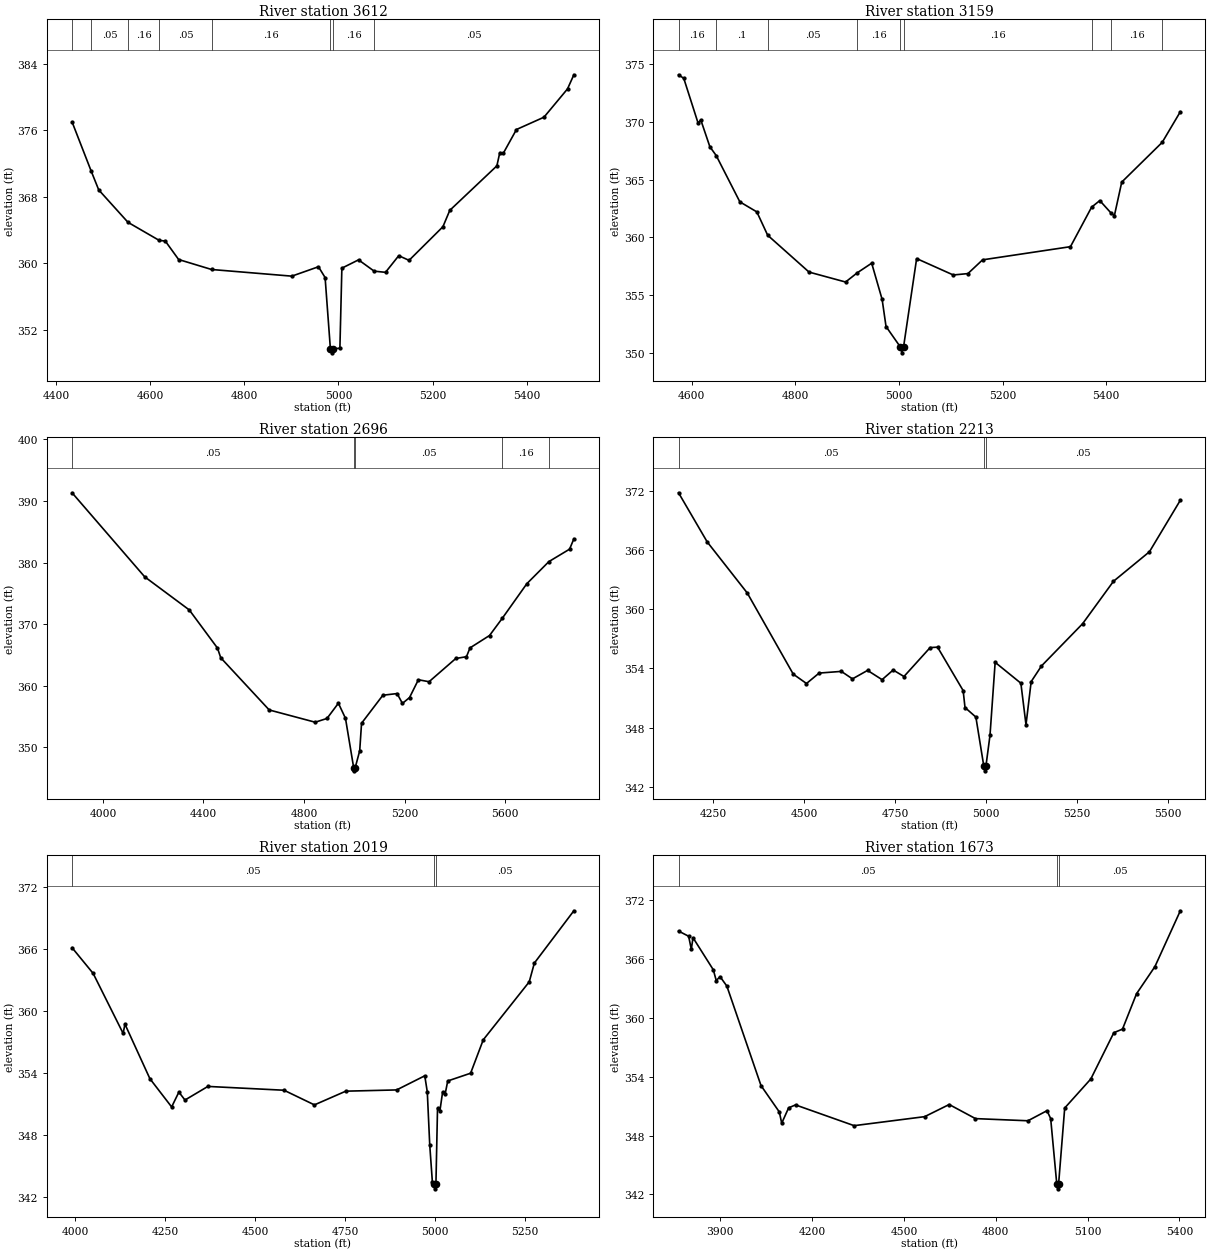
Type RM Length L Ch R = 1,3612,453,453,453
BEGIN DESCRIPTION:
TAPE CREEK 5.0
END DESCRIPTION:
XS GIS Cut Line= 3
      3606949.60     10503810.18      3607349.61     10504210.19
      3607649.61     10504610.19
#Sta/Elev= 30
  4434.2  377.00  4474.8  371.09  4490.8  368.83  4553.0  364.93  4619.2  362.76
  4632.2  362.68  4660.5  360.46  4730.5  359.26  4900.9  358.46  4957.5  359.59
  4971.6  358.29  4982.8  349.74  4985.5  349.24  4988.8  349.74  5003.0  349.79
  5007.2  359.42  5042.6  360.42  5075.8  359.06  5099.9  358.92  5128.0  360.92
  5149.9  360.36  5221.8  364.40  5236.4  366.37  5336.4  371.72  5342.6  373.31
  5349.9  373.22  5378.0  376.09  5436.4  377.57  5486.4  380.97  5499.9  382.67
#Mann=8,-1,0
  4434.2    0.16       0  4474.8    0.05       0  4553.0    0.16       0
  4619.2    0.05       0  4730.5    0.16       0  4982.8    0.07       0
  4988.8    0.16       0  5075.8    0.05       0
Bank Sta=4982.8,4988.8
Exp/Cntr=0.3,0.1

Type RM Length L Ch R = 1,3159,463,463,463
BEGIN DESCRIPTION:
TAPE CREEK 4.0
END DESCRIPTION:
XS GIS Cut Line= 3
      3606849.61     10503860.16      3606899.61     10504260.19
      3607299.59     10504660.17
#Sta/Elev= 30
  4574.5  374.08  4584.6  373.77  4612.3  369.89  4617.4  370.18  4635.0  367.85
  4647.2  367.09  4692.9  363.08  4725.7  362.21  4746.6  360.19  4826.5  357.00
  4897.0  356.14  4919.6  356.94  4947.4  357.77  4967.6  354.63  4975.1  352.29
  5002.9  350.51  5005.7  350.01  5008.9  350.51  5034.2  358.17  5104.9  356.75
  5133.2  356.87  5161.5  358.06  5331.2  359.20  5372.0  362.62  5387.8  363.19
  5409.6  362.11  5416.0  361.89  5430.2  364.79  5508.3  368.23  5543.3  370.88
#Mann=9,-1,0
  4574.5    0.16       0  4647.2     0.1       0  4746.6    0.05       0
  4919.6    0.16       0  5002.9    0.07       0  5008.9    0.16       0
  5372.0    0.05       0  5409.6    0.16       0  5508.3    0.05       0
Bank Sta=5002.9,5008.9
Exp/Cntr=0.3,0.1

Type RM Length L Ch R = 1,2696,483,483,483
BEGIN DESCRIPTION:
TAPE CREEK 3.0
END DESCRIPTION:
XS GIS Cut Line= 3
      3606255.46     10503468.09      3606498.51     10504468.07
      3607164.93     10505169.19
#Sta/Elev= 30
  3877.4  391.33  4166.4  377.69  4343.7  372.32  4455.9  366.13  4468.9  364.56
  4661.7  356.09  4844.7  354.10  4891.6  354.71  4937.0  357.18  4965.2  354.73
  4997.8  346.71  5000.5  346.21  5003.8  346.71  5021.8  349.47  5029.1  353.93
  5114.0  358.48  5170.6  358.75  5191.7  357.15  5220.0  358.10  5255.2  360.99
  5297.7  360.67  5404.0  364.44  5446.5  364.73  5460.6  366.16  5538.3  368.17
  5589.5  370.99  5686.8  376.58  5774.4  380.16  5856.7  382.18  5873.8  383.85
#Mann=5,-1,0
  3877.4    0.05       0  4997.8   0.035       0  5003.8    0.05       0
  5589.5    0.16       0  5774.4    0.05       0
Bank Sta=4997.8,5003.8
Exp/Cntr=0.3,0.1

Type RM Length L Ch R = 1,2213,194,194,194
BEGIN DESCRIPTION:
TAPE CREEK 2.0
END DESCRIPTION:
XS GIS Cut Line= 3
      3606099.61     10504060.21      3606249.61     10504860.19
      3606649.61     10505260.19
#Sta/Elev= 30
  4154.3  371.84  4233.1  366.85  4343.3  361.66  4469.7  353.42  4506.1  352.47
  4540.9  353.53  4601.9  353.70  4632.5  352.94  4674.0  353.80  4713.9  352.86
  4744.4  353.84  4774.1  353.18  4846.1  356.12  4866.5  356.16  4936.8  351.75
  4941.9  350.03  4971.8  349.06  4993.5  344.10  4996.2  343.60  4999.5  344.10
  5010.6  347.20  5024.8  354.62  5095.5  352.50  5109.6  348.28  5123.8  352.66
  5152.1  354.25  5265.2  358.54  5350.1  362.85  5449.0  365.85  5533.9  371.08
#Mann=3,-1,0
  4154.3    0.05       0  4993.5    0.03       0  4999.5    0.05       0
Bank Sta=4993.5,4999.5
Exp/Cntr=0.3,0.1

Type RM Length L Ch R = 1,2019,346,346,346
BEGIN DESCRIPTION:
Mapping XS 0acb18cd
END DESCRIPTION:
XS GIS Cut Line= 3
      3606071.21     10504175.54      3605993.08     10504843.99
      3606525.74     10505329.02
#Sta/Elev= 30
  3991.7  366.13  4050.2  363.64  4133.5  357.82  4138.5  358.72  4207.8  353.43
  4268.2  350.69  4288.3  352.13  4305.2  351.36  4368.9  352.68  4580.3  352.31
  4664.7  350.89  4751.8  352.22  4893.0  352.34  4971.1  353.71  4978.1  352.15
  4984.9  347.00  4992.3  343.37  4996.1  343.25  4998.8  342.75  5002.1  343.25
  5006.5  350.55  5013.2  350.33  5020.7  352.15  5027.4  351.90  5034.9  353.21
  5098.4  353.96  5133.5  357.20  5261.2  362.82  5275.4  364.64  5385.1  369.71
#Mann=3,-1,0
  3991.7    0.05       0  4996.1    0.03       0  5002.1    0.05       0
Bank Sta=4996.1,5002.1
Exp/Cntr=0.3,0.1

Type RM Length L Ch R = 1,1673,372,372,372
BEGIN DESCRIPTION:
Mapping XS 28e6118a
END DESCRIPTION:
XS GIS Cut Line= 3
      3606045.16     10504140.87      3605737.00     10504735.48
      3606144.50     10505615.50
#Sta/Elev= 30
  3763.6  368.88  3796.6  368.35  3805.3  367.02  3810.9  368.20  3877.3  364.92
  3886.7  363.83  3899.4  364.22  3921.5  363.26  4033.1  353.10  4092.9  350.41
  4100.7  349.26  4123.3  350.83  4145.8  351.13  4337.3  349.01  4567.8  349.93
  4647.9  351.17  4733.8  349.73  4905.2  349.51  4967.5  350.54  4979.5  349.73
  4999.4  343.06  5002.2  342.56  5005.4  343.06  5025.3  350.81  5110.7  353.78
  5185.8  358.50  5214.2  358.87  5260.0  362.48  5320.1  365.25  5403.1  370.95
#Mann=3,-1,0
  3763.6    0.05       0  4999.4   0.035       0  5005.4    0.05       0
Bank Sta=4999.4,5005.4
Exp/Cntr=0.3,0.1

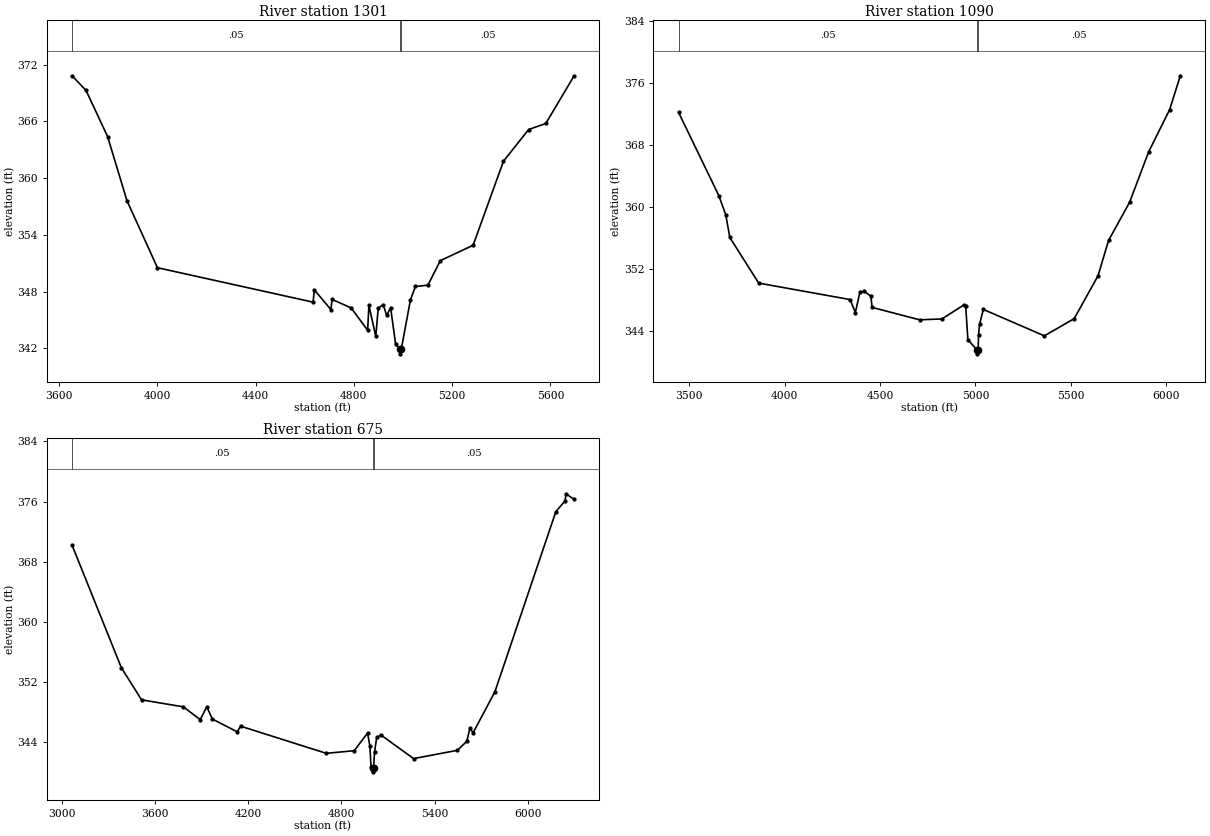
Type RM Length L Ch R = 1,1301,211,211,211
BEGIN DESCRIPTION:
Mapping XS 82cd47b9
END DESCRIPTION:
XS GIS Cut Line= 5
      3606024.39     10504106.24      3605550.42     10504845.84
      3605628.54     10505418.76      3605665.00     10505585.42
      3606060.86     10505710.43
#Sta/Elev= 30
  3653.1  370.81  3709.8  369.27  3797.7  364.39  3876.3  357.63  4000.6  350.53
  4634.2  346.89  4639.2  348.19  4706.5  346.11  4711.6  347.18  4789.0  346.28
  4856.2  343.92  4861.3  346.55  4889.2  343.28  4899.3  346.28  4919.5  346.62
  4933.6  345.49  4949.7  346.31  4969.9  342.47  4987.1  341.93  4989.8  341.43
  4993.1  341.93  5030.5  347.15  5050.7  348.55  5101.1  348.68  5152.2  351.28
  5285.4  352.90  5409.1  361.79  5511.4  365.13  5581.3  365.77  5695.5  370.76
#Mann=3,-1,0
  3653.1    0.05       0  4987.1    0.03       0  4993.1    0.05       0
Bank Sta=4987.1,4993.1
Exp/Cntr=0.3,0.1

Type RM Length L Ch R = 1,1090,415,415,415
BEGIN DESCRIPTION:
Mapping XS e0d0aca3
END DESCRIPTION:
XS GIS Cut Line= 5
      3606008.77     10504028.10      3605388.96     10505002.09
      3605493.12     10505658.34      3605566.04     10505825.01
      3606195.41     10505793.80
#Sta/Elev= 30
  3443.2  372.20  3654.5  361.45  3690.9  358.98  3712.0  356.06  3863.6  350.17
  4342.8  348.05  4370.2  346.37  4393.9  348.98  4415.6  349.13  4452.0  348.49
  4457.9  347.04  4707.1  345.44  4824.3  345.55  4940.0  347.37  4948.9  347.18
  4960.3  342.88  5007.9  341.55  5010.6  341.05  5013.9  341.55  5016.2  343.46
  5021.3  344.85  5041.3  346.78  5361.3  343.37  5517.7  345.59  5642.6  351.11
  5697.9  355.67  5808.1  360.59  5908.2  367.10  6018.3  372.55  6074.2  376.91
#Mann=3,-1,0
  3443.2    0.05       0  5007.9    0.03       0  5013.9    0.05       0
Bank Sta=5007.9,5013.9
Exp/Cntr=0.3,0.1

Type RM Length L Ch R = 1,675,0,0,0
BEGIN DESCRIPTION:
TAPE CREEK 1.0
END DESCRIPTION:
XS GIS Cut Line= 5
      3605935.86     10503986.42      3605185.83     10505137.51
      3605071.25     10505548.96      3605326.46     10505923.96
      3606294.94     10505830.24
#Sta/Elev= 30
  3067.5  370.20  3384.7  353.90  3514.5  349.64  3783.2  348.71  3891.8  347.01
  3934.0  348.72  3970.2  347.08  4130.2  345.39  4151.3  346.14  4702.7  342.53
  4882.1  342.88  4968.1  345.22  4983.0  343.53  4990.9  340.65  5001.0  340.57
  5003.7  340.07  5007.0  340.57  5012.9  342.71  5027.2  344.65  5054.8  344.96
  5264.3  341.83  5546.3  342.93  5606.6  344.13  5626.7  345.88  5646.8  345.25
  5787.4  350.72  6179.2  374.66  6239.1  376.09  6244.1  377.03  6295.1  376.31
#Mann=3,-1,0
  3067.5    0.05       0  5001.0    0.03       0  5007.0    0.05       0
Bank Sta=5001,5007
Exp/Cntr=0.3,0.1

Chan Stop Cuts=-1